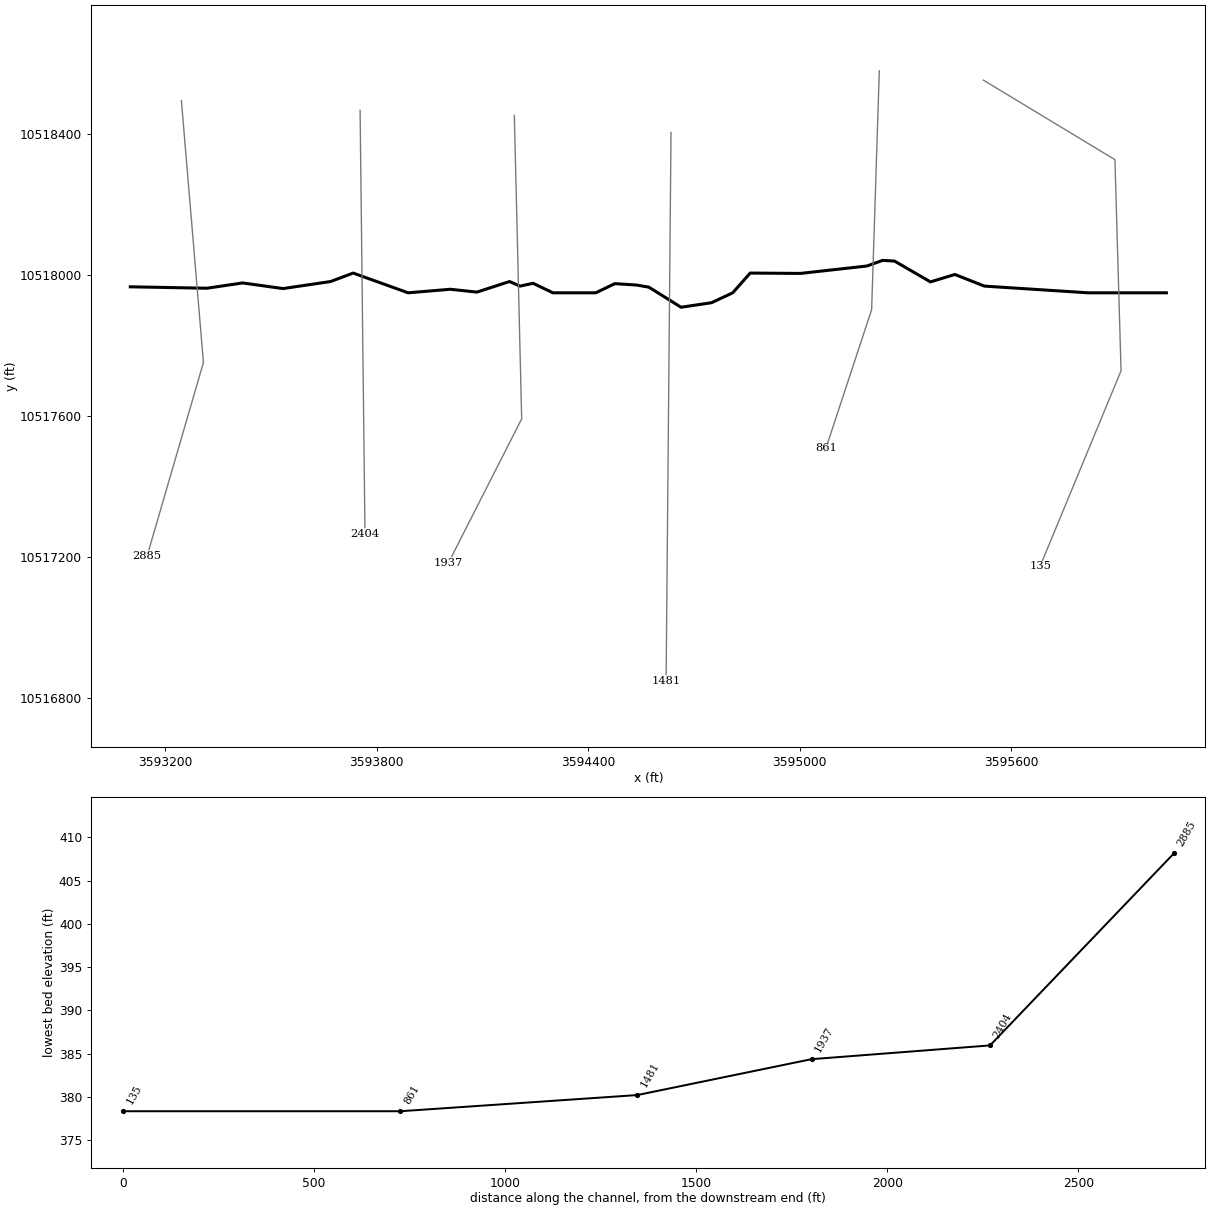
--- TAYLOR SPRINGS BRANCH.prj (project) ---

Proj Title=TAYLOR SPRINGS BRANCH Base Level Engineering
Current Plan=p01
Default Exp/Contr=0.3,0.1
English Units
Geom File=g01
Flow File=f01
Plan File=p01
BEGIN DESCRIPTION:
TAYLOR SPRINGS BRANCH
END DESCRIPTION:

--- TAYLOR SPRINGS BRANCH.p01 (plan) ---

Plan Title=Multiple Run
Short Identifier=Multiple
Geom File=g01
Flow File=f01
Subcritical Flow
K Sum by GR= 0
Std Step Tol= 0.01
Critical Tol= 0.01
Num of Std Step Trials= 20
Max Error Tol= 0.3
Flow Tol Ratio= 0.001
Split Flow NTrial= 30
Split Flow Tol= 0.02
Split Flow Ratio= 0.02
Log Output Level= 0
Friction Slope Method= 1
Unsteady Friction Slope Method= 2
Unsteady Bridges Friction Slope Method= 1
Parabolic Critical Depth
Global Vel Dist=  1 , 1 , 1
Global Log Level= 0
CheckData=True
Encroach Param= -1, 0, 0, 0
BEGIN DESCRIPTION:
Multiple Run
END DESCRIPTION:

--- TAYLOR SPRINGS BRANCH.f01 (steady flow) ---

Flow Title=Multiple
Number of Profiles=7
Profile Names=10-year,25-year,50-year,1pct_min,100-year,1pct_plu,500-year
River Rch & RM= TAYLOR SPRINGS B,Reach-1,2885
    1528    2182    2745    2522    3410    4612    5247
Boundary for River Rch & Prof#=TAYLOR SPRINGS B,Reach-1,1
Up Type=0
Dn Type=3
Dn Slope=0.005
Boundary for River Rch & Prof#=TAYLOR SPRINGS B,Reach-1,2
Up Type=0
Dn Type=3
Dn Slope=0.005
Boundary for River Rch & Prof#=TAYLOR SPRINGS B,Reach-1,3
Up Type=0
Dn Type=3
Dn Slope=0.005
Boundary for River Rch & Prof#=TAYLOR SPRINGS B,Reach-1,4
Up Type=0
Dn Type=3
Dn Slope=0.005
Boundary for River Rch & Prof#=TAYLOR SPRINGS B,Reach-1,5
Up Type=0
Dn Type=3
Dn Slope=0.005
Boundary for River Rch & Prof#=TAYLOR SPRINGS B,Reach-1,6
Up Type=0
Dn Type=3
Dn Slope=0.005
Boundary for River Rch & Prof#=TAYLOR SPRINGS B,Reach-1,7
Up Type=0
Dn Type=3
Dn Slope=0.005

--- TAYLOR SPRINGS BRANCH.g01 (geometry) ---

Geom Title=Existing Conditions

River Reach=TAYLOR SPRINGS B,Reach-1
Reach XY= 30
      3593100.75     10517967.00      3593318.00     10517963.00
      3593419.50     10517978.00      3593533.75     10517962.00
      3593669.00     10517982.00      3593733.00     10518006.00
      3593888.75     10517950.00      3594008.25     10517960.00
      3594084.00     10517952.00      3594176.50     10517982.00
      3594206.25     10517969.00      3594243.25     10517977.00
      3594299.50     10517950.00      3594421.00     10517950.00
      3594475.25     10517976.00      3594537.00     10517972.00
      3594571.75     10517966.00      3594663.00     10517909.00
      3594749.75     10517922.00      3594809.50     10517950.00
      3594859.25     10518006.00      3595001.50     10518005.00
      3595190.25     10518026.00      3595234.75     10518042.00
      3595268.50     10518040.00      3595370.50     10517981.00
      3595439.75     10518002.00      3595523.50     10517969.00
      3595817.50     10517950.00      3596039.75     10517950.00

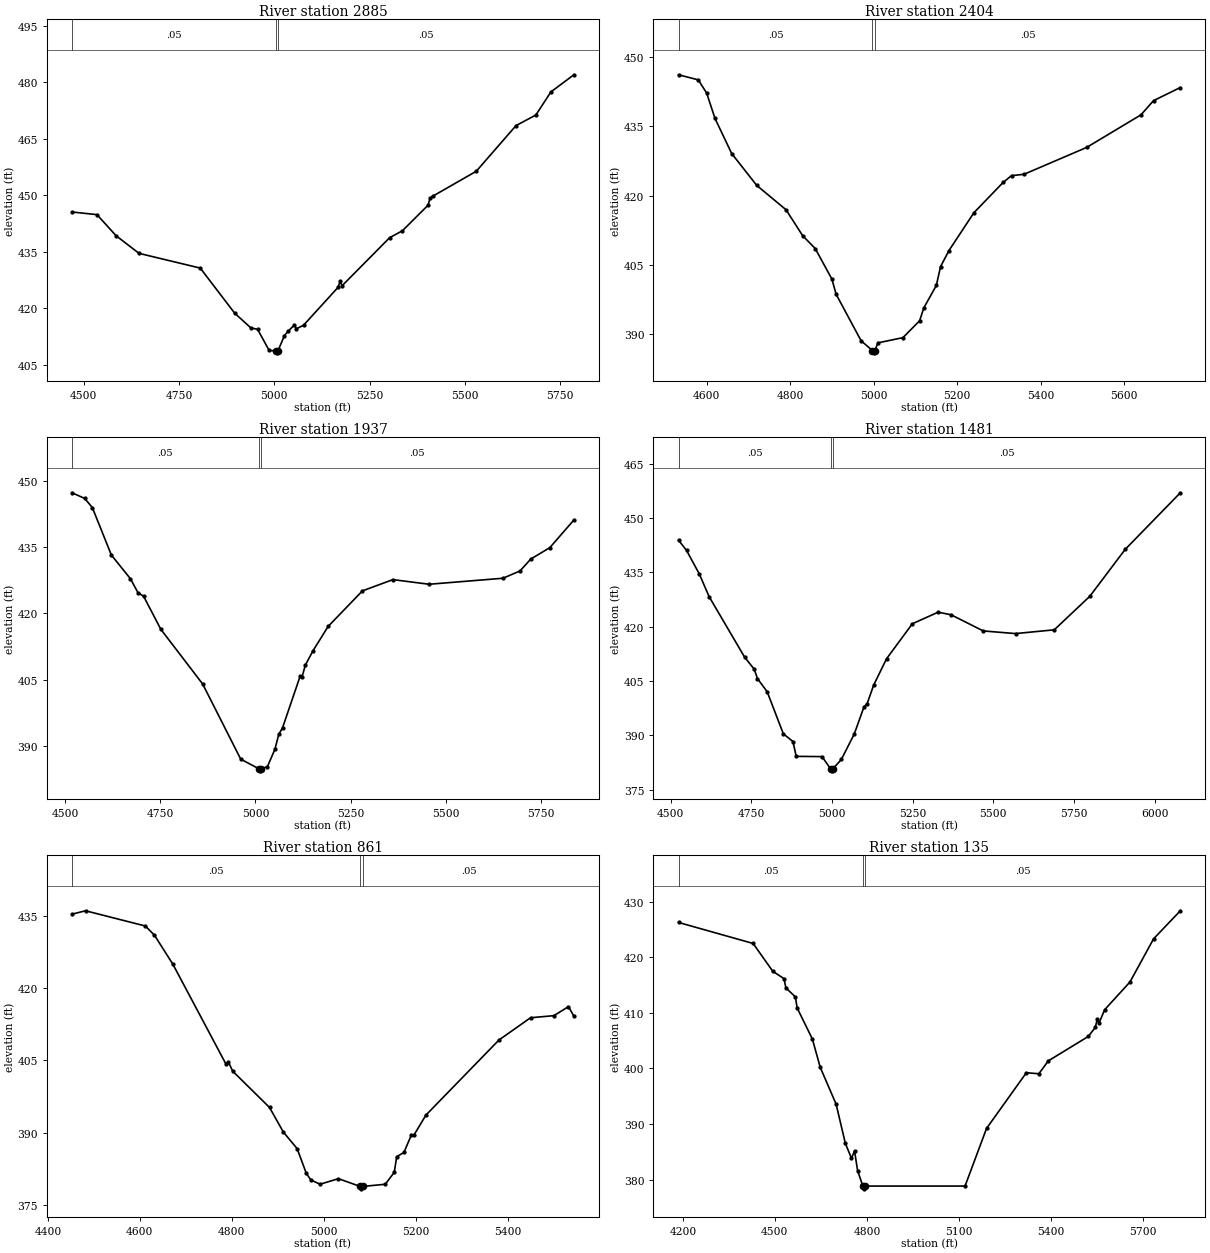
Type RM Length L Ch R = 1,2885,481,481,481
BEGIN DESCRIPTION:
TAYLOR SPRINGS BRANCH 6.0
END DESCRIPTION:
XS GIS Cut Line= 3
      3593245.62     10518495.25      3593308.12     10517752.17
      3593148.65     10517204.42
#Sta/Elev= 30
  4469.5  445.57  4534.8  444.87  4585.0  439.26  4645.2  434.58  4805.7  430.67
  4896.1  418.68  4938.0  414.82  4956.3  414.37  4986.4  408.79  5003.5  408.65
  5006.2  408.15  5009.5  408.65  5026.5  412.73  5036.6  413.95  5052.8  415.55
  5057.8  414.53  5076.7  415.49  5167.0  425.53  5172.7  427.16  5177.7  425.97
  5302.6  438.76  5336.1  440.59  5403.1  447.36  5408.3  449.16  5415.2  449.75
  5529.7  456.39  5633.9  468.52  5686.0  471.34  5725.5  477.48  5785.7  482.03
#Mann=3,-1,0
  4469.5    0.05       0  5003.5    0.03       0  5009.5    0.05       0
Bank Sta=5003.5,5009.5
Exp/Cntr=0.3,0.1

Type RM Length L Ch R = 1,2404,467,467,467
BEGIN DESCRIPTION:
TAYLOR SPRINGS BRANCH 5.0
END DESCRIPTION:
XS GIS Cut Line= 2
      3593752.56     10518467.46      3593766.45     10517266.04
#Sta/Elev= 30
  4532.7  446.14  4580.0  445.04  4600.0  442.18  4620.0  436.69  4660.0  429.09
  4720.0  422.19  4790.0  416.93  4830.0  411.30  4860.0  408.53  4900.0  401.90
  4910.0  398.63  4970.0  388.54  4997.0  386.45  4999.7  385.95  5003.0  386.45
  5010.0  388.11  5070.0  389.24  5110.0  392.90  5120.0  395.68  5150.0  400.54
  5160.0  404.59  5180.0  408.06  5240.0  416.29  5310.0  422.84  5330.0  424.31
  5360.0  424.60  5510.0  430.42  5640.0  437.47  5670.0  440.54  5734.2  443.38
#Mann=3,-1,0
  4532.7    0.05       0  4997.0    0.03       0  5003.0    0.05       0
Bank Sta=4997,5003
Exp/Cntr=0.3,0.1

Type RM Length L Ch R = 1,1937,456,456,456
BEGIN DESCRIPTION:
TAYLOR SPRINGS BRANCH 4.0
END DESCRIPTION:
XS GIS Cut Line= 3
      3594190.07     10518453.55      3594210.90     10517592.45
      3594003.20     10517183.97
#Sta/Elev= 30
  4517.7  447.28  4551.1  445.99  4571.1  443.91  4621.1  433.18  4671.1  427.84
  4691.1  424.66  4705.8  423.87  4751.1  416.39  4861.2  404.00  4961.2  387.01
  5008.2  384.86  5011.0  384.36  5014.2  384.86  5031.2  385.27  5051.2  389.25
  5061.2  392.60  5071.2  394.10  5117.6  405.81  5122.6  405.67  5131.2  408.28
  5151.2  411.52  5191.3  417.06  5281.3  425.08  5361.3  427.63  5456.8  426.58
  5650.8  427.94  5695.7  429.59  5723.8  432.27  5774.2  434.87  5837.3  441.12
#Mann=3,-1,0
  4517.7    0.05       0  5008.2    0.03       0  5014.2    0.05       0
Bank Sta=5008.2,5014.2
Exp/Cntr=0.3,0.1

Type RM Length L Ch R = 1,1481,620,620,620
BEGIN DESCRIPTION:
TAYLOR SPRINGS BRANCH 3.0
END DESCRIPTION:
XS GIS Cut Line= 2
      3594634.51     10518404.93      3594620.62     10516849.39
#Sta/Elev= 30
  4524.2  443.92  4548.9  441.11  4588.9  434.53  4618.9  428.34  4728.9  411.63
  4758.9  408.27  4768.9  405.69  4799.0  402.06  4849.0  390.45  4879.0  388.29
  4889.0  384.21  4969.0  384.14  4996.0  380.71  4998.7  380.21  5002.0  380.71
  5029.0  383.35  5069.0  390.39  5099.0  397.85  5109.0  398.79  5129.0  403.86
  5169.0  411.16  5249.0  420.83  5329.0  424.03  5369.0  423.32  5469.0  418.85
  5569.0  418.12  5689.0  419.16  5799.0  428.40  5909.0  441.39  6079.8  457.01
#Mann=3,-1,0
  4524.2    0.05       0  4996.0    0.03       0  5002.0    0.05       0
Bank Sta=4996,5002
Exp/Cntr=0.3,0.1

Type RM Length L Ch R = 1,861,726,726,726
BEGIN DESCRIPTION:
TAYLOR SPRINGS BRANCH 2.0
END DESCRIPTION:
XS GIS Cut Line= 3
      3595225.37     10518579.44      3595203.66     10517902.34
      3595074.03     10517509.11
#Sta/Elev= 30
  4452.6  435.38  4481.9  436.08  4611.9  432.92  4631.9  431.00  4672.0  424.96
  4787.7  404.18  4792.7  404.67  4802.0  402.77  4882.1  395.24  4912.1  390.14
  4942.1  386.70  4962.1  381.56  4972.1  380.17  4992.1  379.30  5032.1  380.45
  5079.2  378.84  5081.9  378.34  5085.2  378.84  5133.8  379.29  5153.4  381.76
  5158.8  385.02  5174.4  385.89  5190.6  389.50  5195.8  389.43  5222.3  393.65
  5381.1  409.24  5449.9  413.87  5500.8  414.30  5532.4  416.18  5544.1  414.20
#Mann=3,-1,0
  4452.6    0.05       0  5079.2    0.03       0  5085.2    0.05       0
Bank Sta=5079.2,5085.2
Exp/Cntr=0.3,0.1

Type RM Length L Ch R = 1,135,0,0,0
BEGIN DESCRIPTION:
TAYLOR SPRINGS BRANCH 1.0
END DESCRIPTION:
XS GIS Cut Line= 4
      3595520.54     10518553.36      3595893.77     10518327.69
      3595911.13     10517728.73      3595681.50     10517174.15
#Sta/Elev= 30
  4186.0  426.25  4429.1  422.47  4493.1  417.48  4530.0  416.13  4535.8  414.49
  4566.9  412.86  4572.7  410.86  4622.2  405.29  4647.9  400.19  4699.7  393.56
  4729.7  386.52  4749.7  383.84  4759.7  385.16  4769.7  381.61  4786.7  378.84
  4789.5  378.34  4792.7  378.84  5119.9  378.84  5189.9  389.20  5319.7  399.22
  5360.5  399.04  5391.4  401.36  5521.7  405.75  5544.5  407.38  5551.0  408.89
  5556.4  408.13  5574.9  410.55  5657.4  415.54  5734.5  423.31  5821.6  428.35
#Mann=3,-1,0
  4186.0    0.05       0  4786.7   0.033       0  4792.7    0.05       0
Bank Sta=4786.7,4792.7
Exp/Cntr=0.3,0.1

Chan Stop Cuts=-1