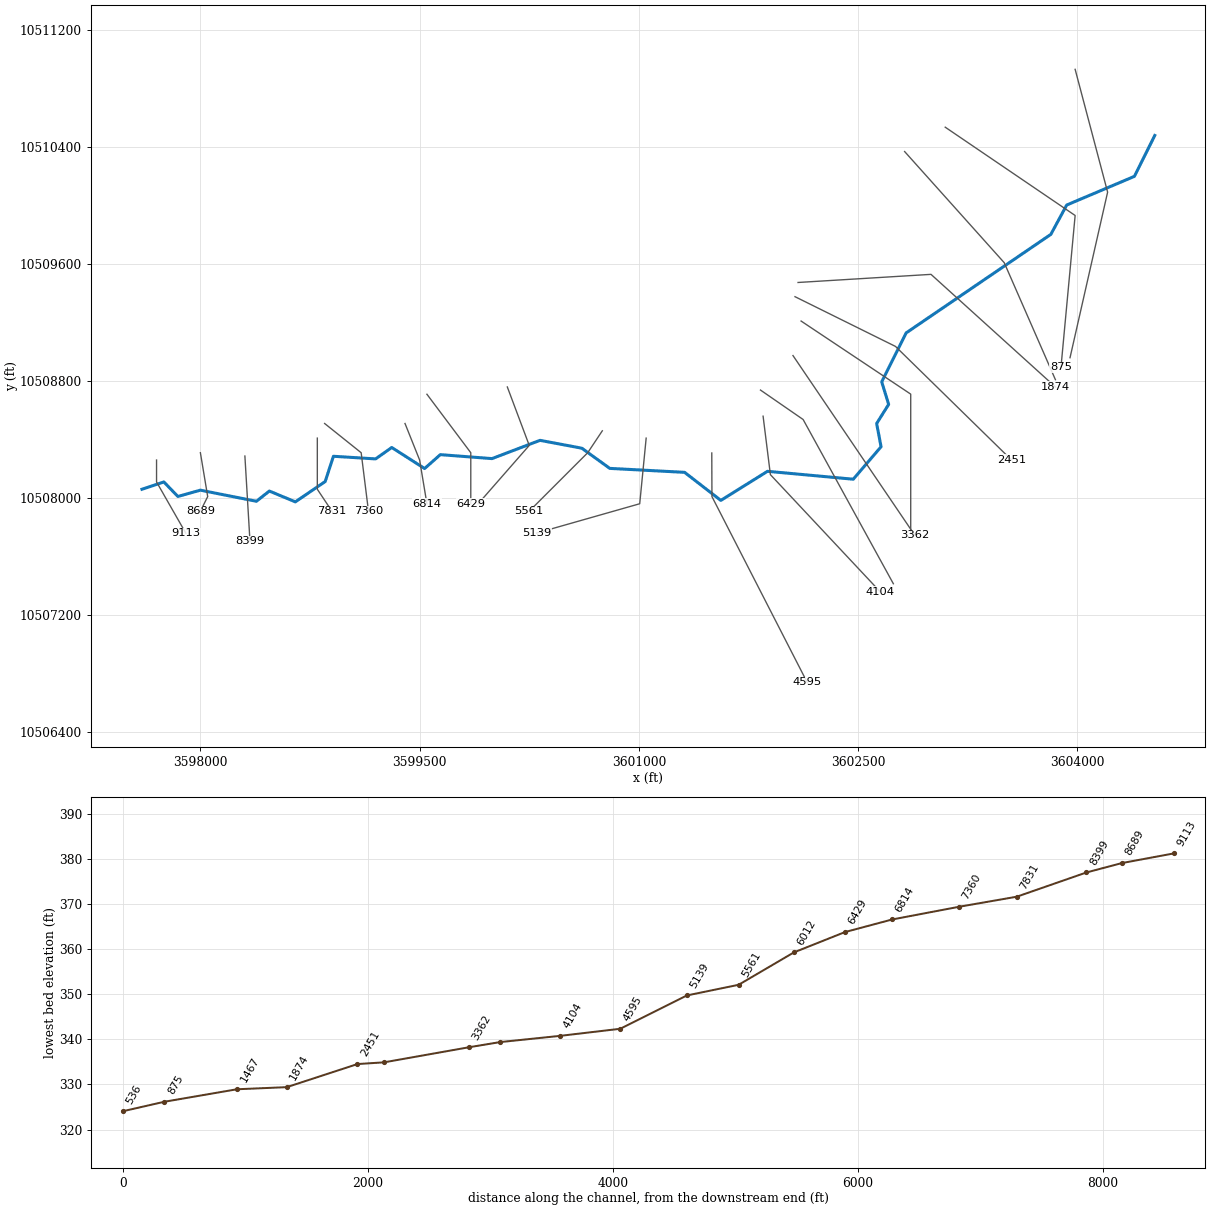
--- THUNDERING SPRINGS BRANCH.prj (project) ---

Proj Title=THUNDERING SPRINGS BRANCH Base Level Engineering
Current Plan=p01
Default Exp/Contr=0.3,0.1
English Units
Geom File=g01
Flow File=f01
Plan File=p01
Y Axis Title=Elevation
X Axis Title(PF)=Main Channel Distance
X Axis Title(XS)=Station
BEGIN DESCRIPTION:
THUNDERING SPRINGS BRANCH
END DESCRIPTION:
DSS Export Rating Curves= 0
DSS Export Rating Curve Sorted= 0
DSS Export Volume Flow Curves= 0
DXF OffsetX= 0
DXF OffsetY= 0
DXF ScaleX= 1
DXF ScaleY= 10

--- THUNDERING SPRINGS BRANCH.p01 (plan) ---

Plan Title=Multiple Run
Short Identifier=Multiple
Geom File=g01
Flow File=f01
Subcritical Flow
K Sum by GR= 0
Std Step Tol= 0.01
Critical Tol= 0.01
Num of Std Step Trials= 20
Max Error Tol= 0.3
Flow Tol Ratio= 0.001
Split Flow NTrial= 30
Split Flow Tol= 0.02
Split Flow Ratio= 0.02
Log Output Level= 0
Friction Slope Method= 1
Unsteady Friction Slope Method= 2
Unsteady Bridges Friction Slope Method= 1
Parabolic Critical Depth
Global Vel Dist=  1 , 1 , 1
Global Log Level= 0
CheckData=True
Encroach Param= -1, 0, 0, 0
BEGIN DESCRIPTION:
Multiple Run
END DESCRIPTION:

--- THUNDERING SPRINGS BRANCH.f01 (steady flow) ---

Flow Title=Multiple
Program Version=4.10
Number of Profiles= 7
Profile Names=10-year,25-year,50-year,1pct_min,100-year,1pct_plu,500-year
River Rch & RM=THUNDERING SPRIN,Reach-1         ,9113
    1763    2531    3193    2938    3973    5373    6137
River Rch & RM=THUNDERING SPRIN,Reach-1         ,4595
    3570    5304    6847    6433    8699   11765   14016
River Rch & RM=THUNDERING SPRIN,Reach-1         ,2668
    3570    5304    6847    6433    8699   11765   14016
Boundary for River Rch & Prof#=THUNDERING SPRIN,Reach-1         , 1
Up Type= 0
Dn Type= 3
Dn Slope=0.004
Boundary for River Rch & Prof#=THUNDERING SPRIN,Reach-1         , 2
Up Type= 0
Dn Type= 3
Dn Slope=0.004
Boundary for River Rch & Prof#=THUNDERING SPRIN,Reach-1         , 3
Up Type= 0
Dn Type= 3
Dn Slope=0.004
Boundary for River Rch & Prof#=THUNDERING SPRIN,Reach-1         , 4
Up Type= 0
Dn Type= 3
Dn Slope=0.004
Boundary for River Rch & Prof#=THUNDERING SPRIN,Reach-1         , 5
Up Type= 0
Dn Type= 3
Dn Slope=0.004
Boundary for River Rch & Prof#=THUNDERING SPRIN,Reach-1         , 6
Up Type= 0
Dn Type= 3
Dn Slope=0.004
Boundary for River Rch & Prof#=THUNDERING SPRIN,Reach-1         , 7
Up Type= 0
Dn Type= 3
Dn Slope=0.004
DSS Import GetInterval= 0
DSS Import GetPeak= 0
DSS Import FillOption= 0

--- THUNDERING SPRINGS BRANCH.g01 (geometry) ---

Geom Title=Existing Conditions
Program Version=4.10

River Reach=THUNDERING SPRIN,Reach-1
Reach XY= 30
      3597599.61     10508060.19      3597749.61     10508110.19
       3597845.5       10508011.       3597999.5       10508054.
        3598383.       10507978.       3598471.5       10508048.
      3598649.25       10507974.       3598853.5       10508113.
      3598909.75       10508286.       3599198.5       10508268.
      3599308.75       10508346.      3599533.75       10508202.
        3599641.       10508297.      3599994.75       10508270.
      3600323.25       10508395.       3600609.5       10508341.
      3600800.75       10508203.       3601312.5       10508176.
       3601560.5       10507984.      3601879.75       10508183.
       3602466.5       10508129.      3602656.75       10508351.
       3602626.5       10508510.      3602708.75       10508641.
      3602661.25       10508795.       3602828.5       10509130.
      3603818.25       10509804.        3603927.       10510005.
        3604390.       10510201.       3604529.5       10510481.

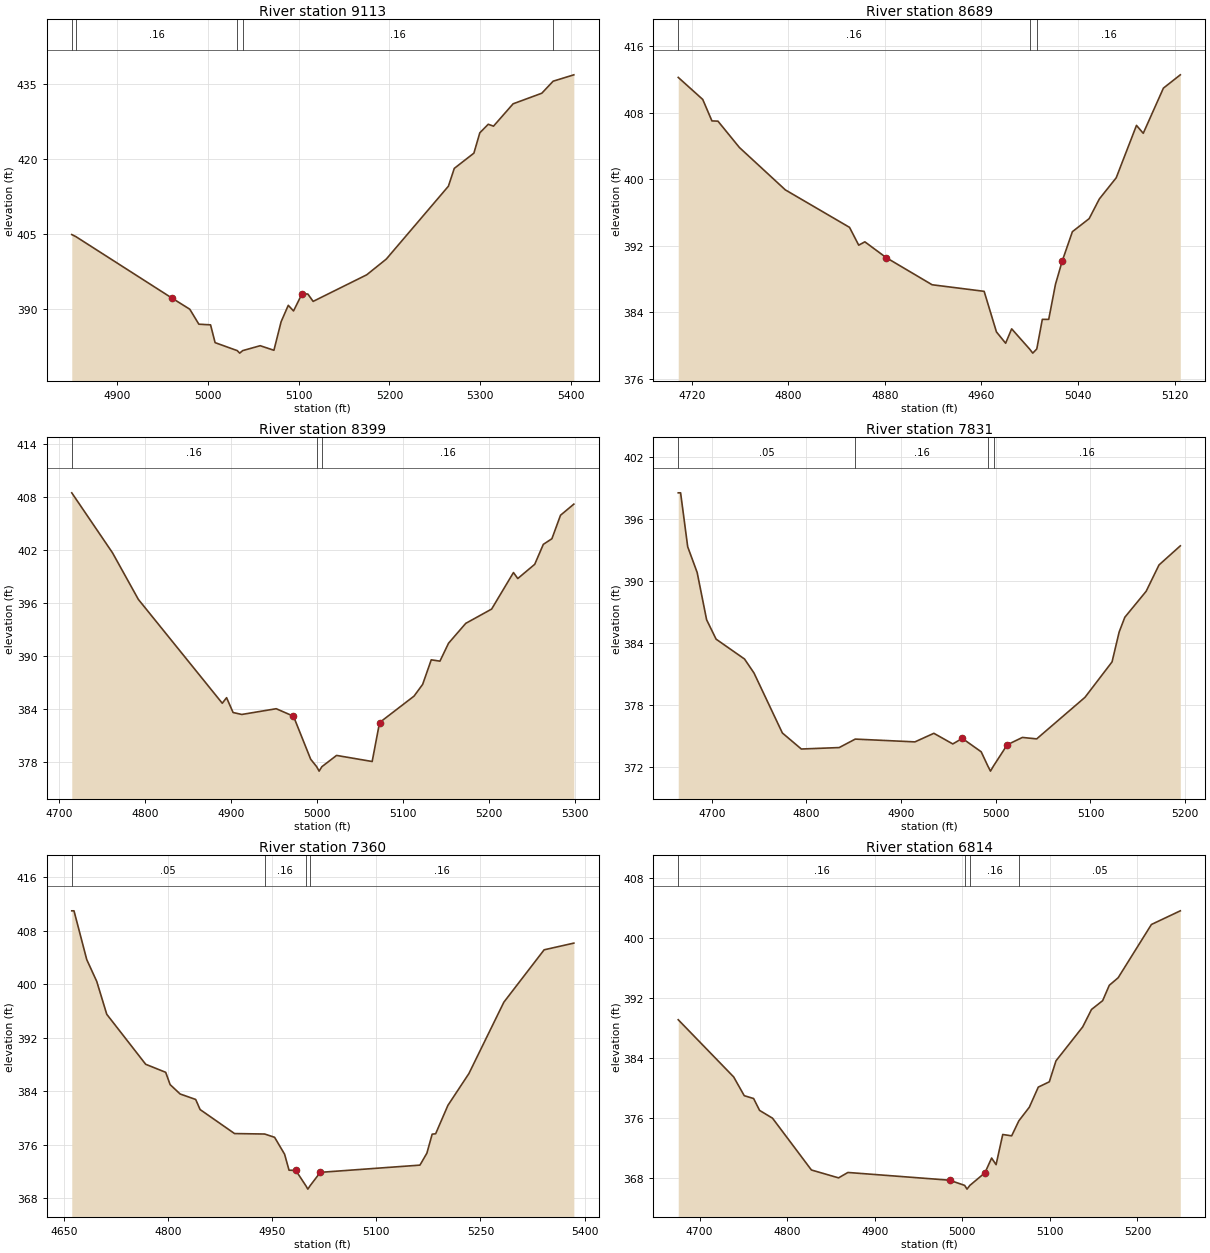
Type RM Length L Ch R = 1 ,9113    ,424,424,424
BEGIN DESCRIPTION:
THUNDERING SPRINGS BRANCH 20.0
END DESCRIPTION:
XS GIS Cut Line= 3
      3597699.61     10508260.19      3597699.61     10508110.19
       3597899.6      10507760.2
#Sta/Elev= 30
    4850  404.87  4854.6  404.45    4960  392.24    4980  389.98    4990  386.99
  5002.9  386.86  5007.9  383.31  5032.3  381.72    5035  381.22  5038.3  381.72
  5057.6   382.7  5072.7  381.79  5080.6  387.47  5088.5  390.76  5094.3  389.63
  5103.7  393.07  5110.1     393  5115.9  391.54  5174.9  396.84  5196.5  399.98
  5264.9  414.51  5271.4  418.07    5293  421.11  5299.5  425.16  5308.8  426.87
  5314.6  426.49  5336.2  430.95  5367.8  433.06  5380.3  435.46  5403.1  436.73
#Mann= 5 ,-1 , 0
    4850     .05       0  4854.6     .16       0  5032.3     .07       0
  5038.3     .16       0  5380.3     .05       0
Bank Sta=4960,5103.7
XS Rating Curve= 0 ,0
Exp/Cntr=0.3,0.1

Type RM Length L Ch R = 1 ,8689    ,290,290,290
BEGIN DESCRIPTION:
THUNDERING SPRINGS BRANCH 19.0
END DESCRIPTION:
XS GIS Cut Line= 3
      3597999.61     10508310.16      3598049.61     10508010.19
      3597999.62      10507910.2
#Sta/Elev= 30
  4708.9  412.23  4729.2  409.58  4736.8     407  4741.8  406.97  4759.6   403.8
  4797.6  398.71  4850.8   394.2  4858.4  392.06  4863.5  392.46  4881.2  390.56
  4919.2   387.3  4962.3  386.51  4972.5  381.63  4980.1  380.27  4985.1     382
  4999.9  379.58  5002.6  379.08  5005.9  379.58  5010.5  383.14  5015.8  383.14
  5021.4  387.36    5027  390.16  5035.4  393.68  5049.3  395.25  5057.7  397.61
  5071.7  400.16  5088.5  406.46  5094.1  405.51  5110.8  410.94  5124.8  412.54
#Mann= 3 ,-1 , 0
  4708.9     .16       0  4999.9     .07       0  5005.9     .16       0
Bank Sta=4881.2,5027
XS Rating Curve= 0 ,0
Exp/Cntr=0.3,0.1

Type RM Length L Ch R = 1 ,8399    ,568,568,568
BEGIN DESCRIPTION:
THUNDERING SPRINGS BRANCH 18.0
END DESCRIPTION:
XS GIS Cut Line= 2
      3598304.07      10508287.5      3598338.76     10507704.73
#Sta/Elev= 30
    4715  408.52  4762.4  401.72  4792.4  396.45    4890  384.68    4895  385.31
  4902.6  383.63  4912.7  383.41  4952.7  384.06  4972.8  383.21  4992.8  378.34
  4999.8  377.49  5002.6  376.99  5005.8  377.49  5022.9  378.77  5064.3  378.08
  5072.9  382.49    5113  385.49    5123  386.82    5133   389.6  5143.1  389.45
  5153.1  391.48  5173.1  393.73  5203.2  395.35  5228.6  399.49  5233.6  398.81
  5253.3  400.42  5263.3  402.68  5273.3  403.32  5283.3  405.98  5298.8  407.24
#Mann= 3 ,-1 , 0
    4715     .16       0  4999.8     .07       0  5005.8     .16       0
Bank Sta=4972.8,5072.9
XS Rating Curve= 0 ,0
Exp/Cntr=0.3,0.1

Type RM Length L Ch R = 1 ,7831    ,471,471,471
BEGIN DESCRIPTION:
THUNDERING SPRINGS BRANCH 17.0
END DESCRIPTION:
XS GIS Cut Line= 3
      3598799.61      10508410.2      3598799.61     10508060.19
      3598899.61     10507910.18
#Sta/Elev= 30
  4664.6  398.55  4667.1  398.55  4674.6  393.33  4684.6  390.84  4694.6  386.26
  4704.6  384.39  4734.6  382.47  4744.6  381.12  4774.6  375.31  4794.6  373.76
  4834.6   373.9  4851.6  374.72  4914.6  374.45  4934.6  375.28  4954.6  374.25
  4964.6  374.79  4984.6  373.49  4991.6  372.12  4994.4  371.62  4997.6  372.12
  5012.1  374.17  5028.1  374.88  5043.2  374.74  5094.2  378.76  5122.8  382.19
  5130.3  385.08  5136.3  386.51  5158.8  389.02  5172.4  391.57  5194.9  393.42
#Mann= 4 ,-1 , 0
  4664.6     .05       0  4851.6     .16       0  4991.6     .07       0
  4997.6     .16       0
Bank Sta=4964.6,5012.1
XS Rating Curve= 0 ,0
Exp/Cntr=0.3,0.1

Type RM Length L Ch R = 1 ,7360    ,546,546,546
BEGIN DESCRIPTION:
THUNDERING SPRINGS BRANCH 16.0
END DESCRIPTION:
XS GIS Cut Line= 3
       3598849.6      10508510.2      3599099.61     10508310.19
      3599149.61     10507910.17
#Sta/Elev= 30
  4661.2  411.01  4664.4  411.01  4682.8  403.71  4697.2  400.45  4711.6  395.54
  4767.7  388.06  4796.5  386.86  4802.9  385.02  4817.3  383.62  4839.7   382.8
  4846.1  381.29  4895.7   377.7  4939.1  377.63  4953.4  377.14  4967.8  374.61
  4974.2  372.22  4983.9  372.19  4998.5  369.89  5001.3  369.39  5004.5  369.89
  5019.2   371.9  5162.8  372.98  5172.8  374.77  5180.4  377.61  5185.4  377.67
  5203.1  381.92  5233.3  386.67  5283.7  397.35  5341.7  405.18  5384.5  406.18
#Mann= 4 ,-1 , 0
  4661.2     .05       0  4939.1     .16       0  4998.5     .07       0
  5004.5     .16       0
Bank Sta=4983.9,5019.2
XS Rating Curve= 0 ,0
Exp/Cntr=0.3,0.1

Type RM Length L Ch R = 1 ,6814    ,385,385,385
BEGIN DESCRIPTION:
THUNDERING SPRINGS BRANCH 15.0
END DESCRIPTION:
XS GIS Cut Line= 3
      3599399.62     10508510.17      3599499.61     10508260.19
      3599549.61     10507960.16
#Sta/Elev= 30
  4675.6  389.14  4738.9  381.52    4751  379.02  4761.7  378.64  4768.5  377.06
  4783.3  376.02  4827.7  369.12  4858.7  368.07  4869.4  368.79  4985.4  367.76
  5002.7  367.07  5005.4  366.57  5008.7  367.07  5025.9  368.75  5033.5  370.71
  5038.6  369.83  5046.2  373.85  5056.4  373.67  5064.6  375.67  5076.6  377.49
  5086.8  380.16  5099.4  380.87    5107  383.66  5137.5  388.18  5147.6  390.51
  5160.3  391.68  5167.9  393.73    5178  394.73    5216  401.83    5249  403.65
#Mann= 4 ,-1 , 0
  4675.6     .16       0  5002.7     .07       0  5008.7     .16       0
  5064.6     .05       0
Bank Sta=4985.4,5025.9
XS Rating Curve= 0 ,0
Exp/Cntr=0.3,0.1

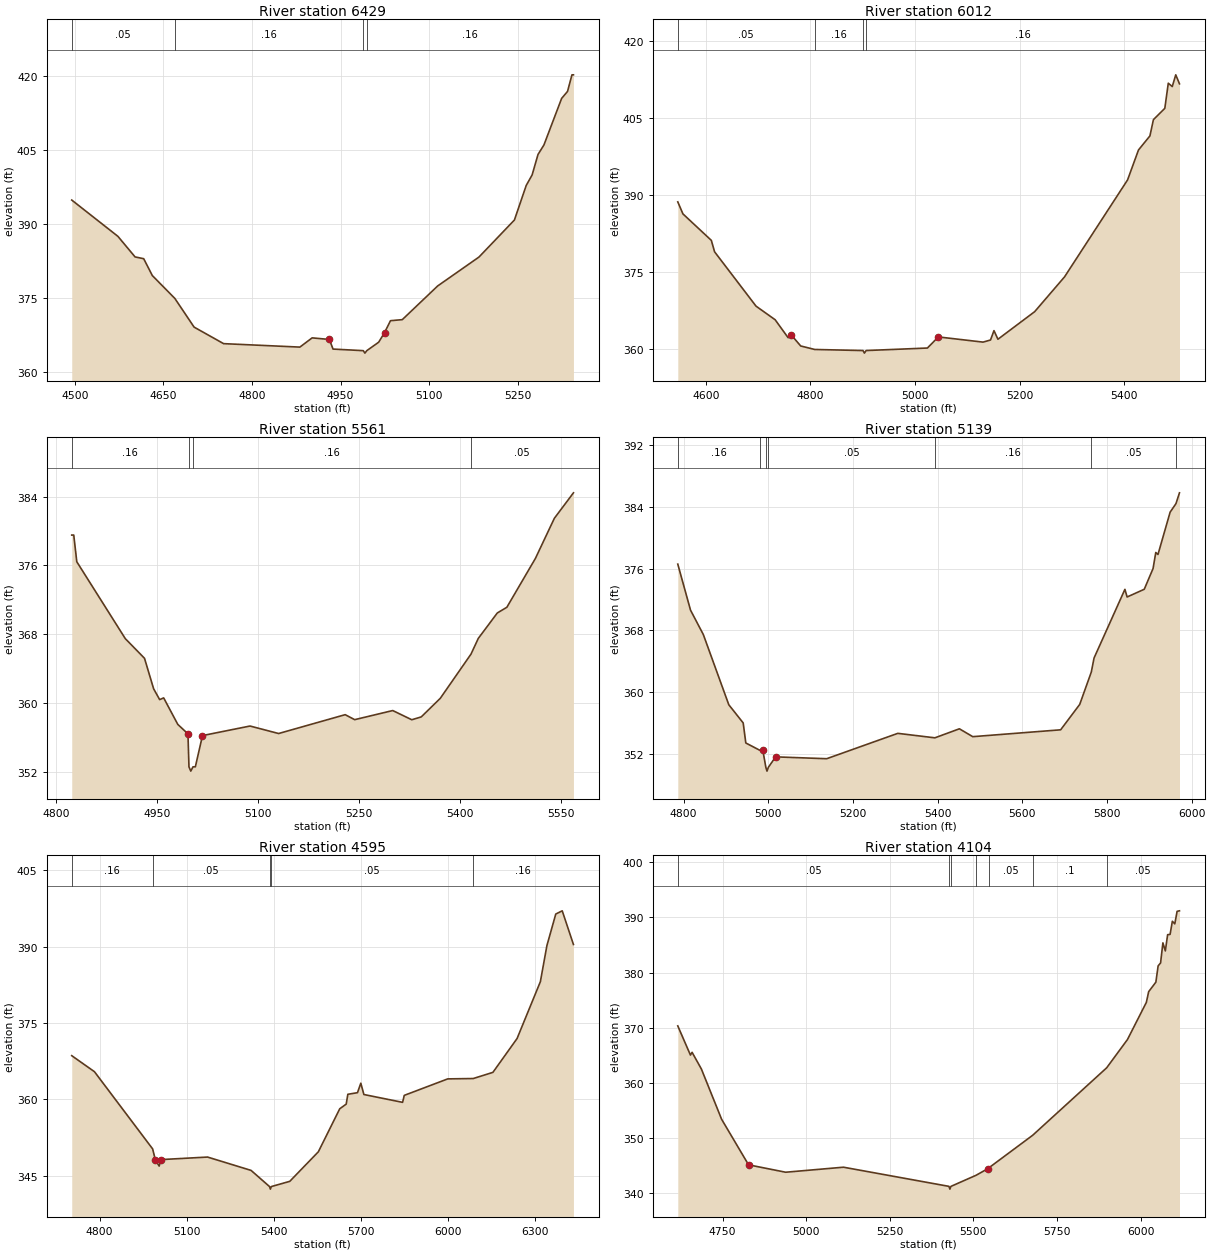
Type RM Length L Ch R = 1 ,6429    ,417,417,417
BEGIN DESCRIPTION:
THUNDERING SPRINGS BRANCH 14.0
END DESCRIPTION:
XS GIS Cut Line= 3
      3599549.58     10508710.22      3599849.61     10508310.19
      3599849.61     10507960.23
#Sta/Elev= 30
  4494.6  394.79  4572.8  387.44  4601.9  383.27  4616.5  382.91  4631.1   379.5
  4669.3  374.86  4701.9  369.05  4751.9   365.7  4881.1     365  4901.9  366.87
  4931.1  366.55  4937.3   364.6  4988.5  364.28  4991.3  363.78  4994.5  364.28
  5014.6  365.99  5024.6  367.93  5034.6  370.35  5054.6  370.56  5114.6  377.39
  5184.6  383.25  5244.6  390.75  5264.6  397.75  5274.6  399.88  5284.6  404.03
  5294.6  405.95  5324.6  415.38  5334.6   416.8  5342.1  420.16  5344.6  420.16
#Mann= 4 ,-1 , 0
  4494.6     .05       0  4669.3     .16       0  4988.5     .07       0
  4994.5     .16       0
Bank Sta=4931.1,5024.6
XS Rating Curve= 0 ,0
Exp/Cntr=0.3,0.1

Type RM Length L Ch R = 1 ,6012    ,451,451,451
BEGIN DESCRIPTION:
THUNDERING SPRINGS BRANCH 13.0
END DESCRIPTION:
XS GIS Cut Line= 3
      3600099.61     10508760.17      3600249.61     10508360.19
       3599899.6     10507960.18
#Sta/Elev= 30
  4546.5  388.66  4556.3  386.33  4610.6  381.18  4616.8  378.96    4696   368.4
  4732.5  365.76  4757.4  362.26  4762.8  362.86  4781.4  360.66  4808.2  359.98
  4900.4  359.77  4903.1  359.27  4906.4  359.77  5023.5  360.26  5044.4  362.42
  5129.8  361.41  5144.1  361.82  5150.7  363.64  5158.3  361.97  5228.5  367.33
  5285.5  374.08    5406  392.93  5426.9  398.75  5448.7  401.48  5455.4  404.64
  5477.2  406.84  5483.8  411.72  5491.4  411.07  5498.1  413.35  5505.2   411.6
#Mann= 4 ,-1 , 0
  4546.5     .05       0  4808.2     .16       0  4900.4     .07       0
  4906.4     .16       0
Bank Sta=4762.8,5044.4
XS Rating Curve= 0 ,0
Exp/Cntr=0.3,0.1

Type RM Length L Ch R = 1 ,5561    ,422,422,422
BEGIN DESCRIPTION:
THUNDERING SPRINGS BRANCH 12.0
END DESCRIPTION:
XS GIS Cut Line= 3
      3600749.61     10508460.19      3600649.61     10508310.19
      3600249.59     10507910.17
#Sta/Elev= 30
  4822.7  379.52  4825.7  379.52  4830.2  376.42  4902.3  367.49  4930.9   365.2
  4944.4  361.67  4953.4   360.4  4959.4   360.6  4980.4  357.52  4995.5  356.42
    4997  352.59  4999.7  352.09    5003  352.59  5006.5  352.59  5017.1  356.22
  5087.8  357.33  5130.3  356.46  5229.3  358.65  5243.4  358.07    5300  359.13
  5328.3  358.06  5342.4  358.39  5370.7  360.55  5416.4  365.69  5427.2  367.51
  5455.5  370.47  5469.7  371.13  5512.1   376.8  5540.4  381.48  5568.7  384.43
#Mann= 4 ,-1 , 0
  4822.7     .16       0    4997     .07       0    5003     .16       0
  5416.4     .05       0
Bank Sta=4995.5,5017.1
XS Rating Curve= 0 ,0
Exp/Cntr=0.3,0.1

Type RM Length L Ch R = 1 ,5139    ,544,544,544
BEGIN DESCRIPTION:
THUNDERING SPRINGS BRANCH 11.0
END DESCRIPTION:
XS GIS Cut Line= 3
      3601049.61     10508410.15      3601005.46     10507961.12
       3600299.6     10507760.18
#Sta/Elev= 30
  4786.2  376.58  4816.3  370.61  4846.5  367.45  4906.7  358.34  4940.7  355.98
  4946.9  353.38  4979.8  352.44  4987.1  352.42  4994.2  350.23  4996.9  349.73
  5000.2  350.23  5017.3  351.58  5137.9  351.34  5305.9  354.63  5393.5  354.05
  5451.4  355.22    5483   354.2  5690.6  355.09  5735.6  358.38    5763  362.58
  5769.5   364.4  5842.4  373.31  5847.6  372.32  5888.1  373.32  5908.9  376.01
  5915.3  378.09  5920.5  377.83  5949.2  383.32    5963  384.43  5971.3  385.83
#Mann= 7 ,-1 , 0
  4786.2     .16       0  4979.8     .05       0  4994.2     .03       0
  5000.2     .05       0  5393.5     .16       0    5763     .05       0
    5963     .16       0
Bank Sta=4987.1,5017.3
XS Rating Curve= 0 ,0
Exp/Cntr=0.3,0.1

Type RM Length L Ch R = 1 ,4595    ,491,491,491
BEGIN DESCRIPTION:
THUNDERING SPRINGS BRANCH 10.0
END DESCRIPTION:
XS GIS Cut Line= 3
      3601498.51     10508308.34      3601499.61     10508010.19
      3602151.27     10506738.94
#Sta/Elev= 30
    4704  368.56  4782.2  365.41  4982.4  350.24  4992.2  347.99    5005  346.87
  5010.4  348.14  5171.5  348.64  5321.2  346.02  5384.8  342.84  5387.6  342.34
  5390.8  342.84  5454.4  343.87  5552.8  349.68  5626.4  358.13  5648.6  359.04
  5654.2  360.97  5687.4  361.29  5698.9  363.15  5709.5  360.93  5842.7  359.39
  5848.4  360.76  5998.1     364  6085.9  364.07  6153.5  365.28  6236.7  371.93
  6316.9   383.1  6339.4  390.19  6369.9  396.39  6392.1  397.02  6430.7  390.41
#Mann= 5 ,-1 , 0
    4704     .16       0  4982.4     .05       0  5384.8     .03       0
  5390.8     .05       0  6085.9     .16       0
Bank Sta=4992.2,5010.4
XS Rating Curve= 0 ,0
Exp/Cntr=0.3,0.1

Type RM Length L Ch R = 1 ,4104    ,489,489,489
BEGIN DESCRIPTION:
THUNDERING SPRINGS BRANCH 9.0
END DESCRIPTION:
XS GIS Cut Line= 3
      3601849.61     10508560.16      3601899.61     10508160.19
      3602649.63     10507360.17
#Sta/Elev= 30
  4616.3  370.33  4654.1  365.05  4659.1  365.54  4686.8  362.53  4747.3  353.42
  4827.9  345.17  4938.8  343.83  5111.5  344.74  5426.9  341.27  5429.7  340.77
  5432.9  341.27  5507.7  343.27  5542.8  344.46  5547.4  344.68  5677.1  350.52
  5898.5  362.75  5960.4  367.85    6017  374.59  6023.9  376.53  6045.4  378.25
  6052.2   381.2  6059.5  381.73  6066.4  385.37  6073.7  383.91  6080.6  386.85
  6087.9   386.9  6094.7  389.28    6102  388.81  6108.9  391.08    6116  391.17
#Mann= 7 ,-1 , 0
  4616.3     .05       0  5426.9     .03       0  5432.9     .05       0
  5507.7     .16       0  5547.4     .05       0  5677.1      .1       0
  5898.5     .05       0
Bank Sta=4827.9,5542.8
XS Rating Curve= 0 ,0
Exp/Cntr=0.3,0.1

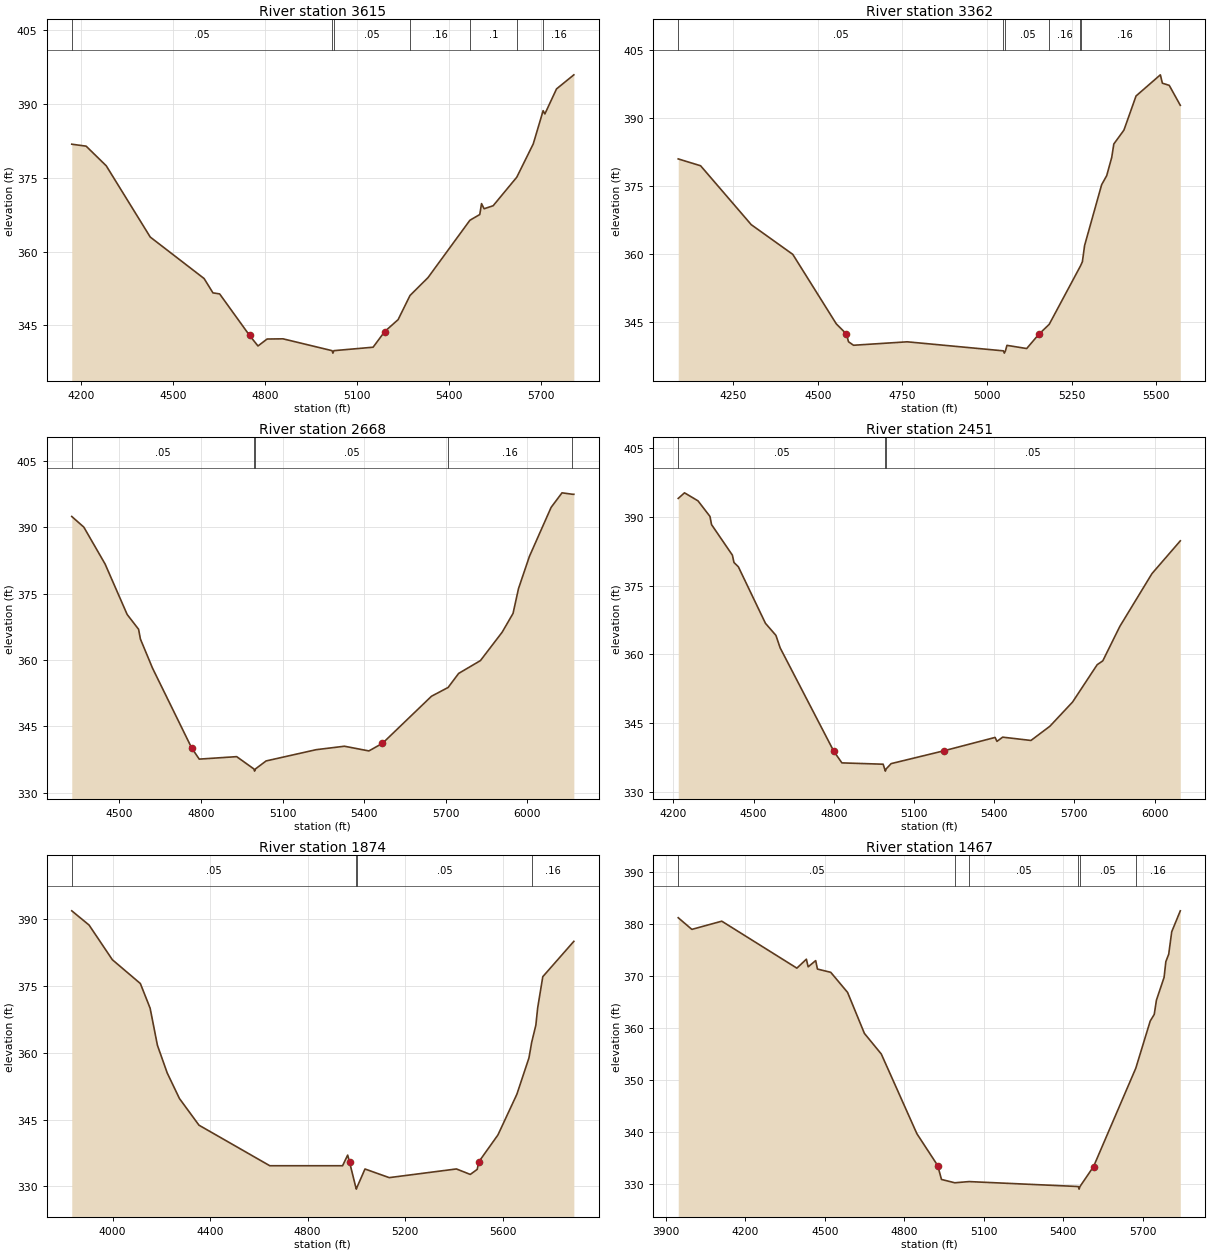
Type RM Length L Ch R = 1 ,3615    ,253,253,253
BEGIN DESCRIPTION:
THUNDERING SPRINGS BRANCH 8.0
END DESCRIPTION:
XS GIS Cut Line= 3
      3601831.84     10508738.91      3602123.51     10508537.51
      3602740.83     10507413.87
#Sta/Elev= 30
  4170.8  381.76  4217.7  381.36  4283.2  377.38  4426.6  362.93  4602.1  354.52
    4631  351.61  4652.8   351.4  4750.3  342.98  4777.8  340.84  4807.4  342.25
  4859.3  342.29  5019.2  339.89    5022  339.39  5025.2  339.89    5153  340.59
  5190.9  343.77  5234.5  346.18  5273.3  351.08    5332  354.71  5468.4  366.33
  5500.7   367.5  5506.4  369.71  5514.8  368.67  5544.3  369.28  5621.3  375.07
    5675  381.82  5707.2  388.56  5712.9   387.9  5750.8  392.97  5807.3  395.83
#Mann= 7 ,-1 , 0
  4170.8     .05       0  5019.2     .03       0  5025.2     .05       0
  5273.3     .16       0  5468.4      .1       0  5621.3     .05       0
  5707.2     .16       0
Bank Sta=4750.3,5190.9
XS Rating Curve= 0 ,0
Exp/Cntr=0.3,0.1

Type RM Length L Ch R = 1 ,3362    ,694,694,694
BEGIN DESCRIPTION:
THUNDERING SPRINGS BRANCH 7.0
END DESCRIPTION:
XS GIS Cut Line= 2
      3602054.08       10508975.       3602887.4     10507745.85
#Sta/Elev= 30
  4086.7  380.98  4152.9  379.47  4302.7  366.51  4425.5  359.98  4554.3  344.68
  4584.2  342.46  4590.3  340.75  4605.2  339.98  4763.9  340.74  5048.5  338.75
  5051.2  338.25  5054.5  338.75    5059  339.96  5117.3  339.26  5153.3   342.4
  5183.9  344.58  5274.4  357.15  5276.9  357.51  5282.1  358.36  5288.6  361.93
    5339   375.3    5354   377.3  5368.9  381.33    5375  384.26  5404.9  387.31
  5440.8  394.83  5512.7  399.48  5518.7  397.64    5539  397.16  5571.7  392.77
#Mann= 7 ,-1 , 0
  4086.7     .05       0  5048.5     .03       0  5054.5     .05       0
  5183.9     .16       0  5274.4     .05       0  5276.9     .16       0
    5539      .1       0
Bank Sta=4584.2,5153.3
XS Rating Curve= 0 ,0
Exp/Cntr=0.3,0.1

Type RM Length L Ch R = 1 ,2668    ,217,217,217
BEGIN DESCRIPTION:
THUNDERING SPRINGS BRANCH 6.0
END DESCRIPTION:
XS GIS Cut Line= 3
       3602109.6     10509211.14      3602859.63     10508711.12
      3602859.63     10507766.64
#Sta/Elev= 30
  4324.7  392.39  4369.1  389.98  4447.3  381.65  4528.4  370.26  4570.4  366.92
  4577.1  364.72  4621.5  358.16  4765.7  340.11  4793.4  337.61    4931  338.17
  4994.1   335.4  4996.8   334.9  5000.1   335.4  5039.2   337.2  5223.1  339.74
  5327.1  340.52  5417.1  339.46  5467.1  341.18  5647.1   351.8  5708.4  353.79
  5747.1  356.96  5827.1  359.85  5907.1  366.27  5947.1  370.51  5967.1   376.1
  6007.1  383.36  6087.1  394.45  6127.1  397.73    6165  397.41  6170.6   397.4
#Mann= 5 ,-1 , 0
  4324.7     .05       0  4994.1     .03       0  5000.1     .05       0
  5708.4     .16       0    6165      .1       0
Bank Sta=4765.7,5467.1
XS Rating Curve= 0 ,0
Exp/Cntr=0.3,0.1

Type RM Length L Ch R = 1 ,2451    ,577,577,577
BEGIN DESCRIPTION:
THUNDERING SPRINGS BRANCH 5.0
END DESCRIPTION:
XS GIS Cut Line= 3
      3602067.95      10509377.8      3602755.46     10509037.51
      3603549.62     10508260.18
#Sta/Elev= 30
    4218  394.09  4241.5  395.31  4291.9  393.56  4336.8  390.15  4342.6  388.37
  4420.7  381.69  4426.5   380.1    4443  379.15  4544.3  366.81  4583.5  364.17
  4599.2  361.46  4800.1  338.85  4830.3  336.32  4984.6  336.03  4990.2  335.02
  4992.9  334.52  4996.2  335.02  5014.5  336.16  5212.5  338.97  5403.4  341.88
  5410.5  341.02  5431.7  341.94  5537.7  341.22  5608.4  344.32  5693.3  349.61
  5785.3  357.76  5806.4  358.61  5870.1  366.13  5990.3  377.66  6096.4  384.82
#Mann= 3 ,-1 , 0
    4218     .05       0  4990.2     .03       0  4996.2     .05       0
Bank Sta=4800.1,5212.5
XS Rating Curve= 0 ,0
Exp/Cntr=0.3,0.1

Type RM Length L Ch R = 1 ,1874    ,407,407,407
BEGIN DESCRIPTION:
THUNDERING SPRINGS BRANCH 4.0
END DESCRIPTION:
XS GIS Cut Line= 3
      3602088.83     10509475.02      3602998.51     10509530.57
      3603849.64     10508760.16
#Sta/Elev= 30
  3832.9  391.88  3903.8  388.69  3999.4   380.9  4114.2  375.56  4154.3  370.02
  4184.3  361.68  4224.4  355.48  4274.5  349.75  4354.6  343.76  4645.2  334.65
  4943.7  334.65  4964.6  337.04  4972.1  335.52  4997.5   329.9  5000.2   329.4
  5003.5   329.9  5035.6  333.92    5135  331.98  5410.7  333.93  5467.5   332.7
  5495.9  333.83  5502.6  335.54    5581  341.57  5658.7  350.71  5708.1  358.85
  5719.5  362.39  5736.5  366.22  5743.9  370.07  5764.9  377.09  5892.3  385.03
#Mann= 4 ,-1 , 0
  3832.9     .05       0  4997.5     .03       0  5003.5     .05       0
  5719.5     .16       0
Bank Sta=4972.1,5502.6
XS Rating Curve= 0 ,0
Exp/Cntr=0.3,0.1

Type RM Length L Ch R = 1 ,1467    ,592,592,592
BEGIN DESCRIPTION:
THUNDERING SPRINGS BRANCH 3.0
END DESCRIPTION:
XS GIS Cut Line= 3
      3602817.93     10510370.88      3603499.61     10509610.19
      3603849.63     10508810.15
#Sta/Elev= 30
  3946.7  381.11  3998.1  378.87    4111  380.45  4394.4  371.42  4430.3  373.14
    4437  371.67  4465.4  372.87  4472.1  371.24  4522.2  370.62  4585.7  366.76
  4649.3  358.87    4713  354.91  4847.4  339.58  4925.9  333.46  4940.1  330.79
  4990.2  330.15  5043.9  330.38  5456.7  329.43  5459.5  328.93  5462.7  329.43
  5513.9  333.26  5673.4  352.18  5727.9  361.26  5743.1  362.53  5751.3  365.27
  5780.2  369.65  5786.8  372.67  5797.7  374.11    5809  378.42  5841.4  382.44
#Mann= 6 ,-1 , 0
  3946.7     .05       0  4990.2     .12       0  5043.9     .05       0
  5456.7     .07       0  5462.7     .05       0  5673.4     .16       0
Bank Sta=4925.9,5513.9
XS Rating Curve= 0 ,0
Exp/Cntr=0.3,0.1

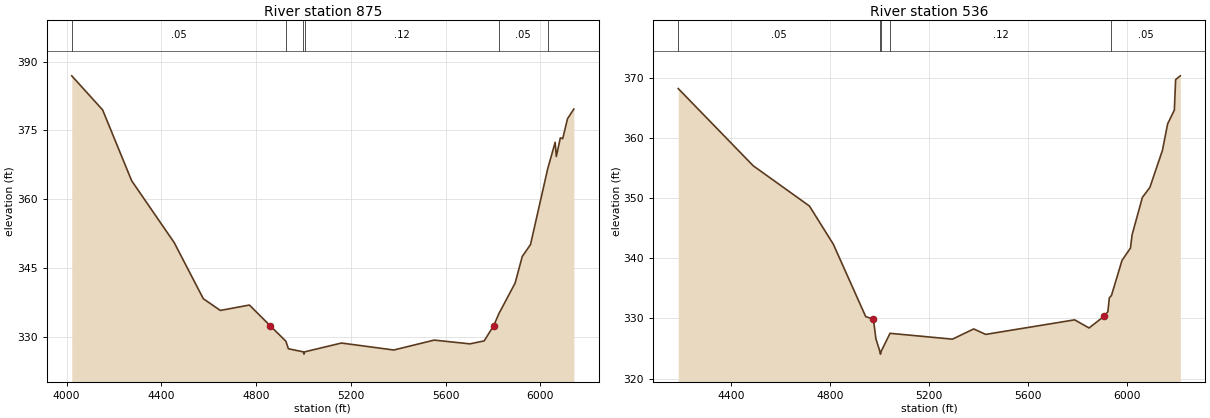
Type RM Length L Ch R = 1 ,875     ,339,339,339
BEGIN DESCRIPTION:
THUNDERING SPRINGS BRANCH 2.0
END DESCRIPTION:
XS GIS Cut Line= 3
      3603095.72     10510537.52      3603984.63     10509933.35
      3603887.57     10508893.46
#Sta/Elev= 30
  4022.2  386.88  4152.4  379.45  4275.1  363.98  4454.7  350.48  4577.4  338.25
  4649.3  335.69    4772  336.87  4858.8   332.4  4925.7  328.99  4936.7  327.33
  4999.5  326.66  5002.3  326.16  5005.5  326.66  5160.4  328.58  5381.4  327.06
  5552.1  329.22  5702.8   328.4    5763  329.05  5803.2  332.38  5824.9  334.98
  5893.6  341.67  5923.7  347.47  5958.5  350.07  6030.9  366.56  6062.5  372.38
  6067.5  369.27  6084.4  373.34  6094.5  373.17  6114.6  377.51  6141.4  379.63
#Mann= 6 ,-1 , 0
  4022.2     .05       0  4925.7     .12       0  4999.5     .07       0
  5005.5     .12       0  5824.9     .05       0  6030.9     .16       0
Bank Sta=4858.8,5803.2
XS Rating Curve= 0 ,0
Exp/Cntr=0.3,0.1

Type RM Length L Ch R = 1 ,536     ,0,0,0
BEGIN DESCRIPTION:
THUNDERING SPRINGS BRANCH 1.0
END DESCRIPTION:
XS GIS Cut Line= 3
      3603984.63     10510933.34      3604206.85     10510093.07
       3603949.6     10508960.17
#Sta/Elev= 30
  4185.9  368.21  4489.1  355.38  4716.7  348.68  4813.3  342.33  4944.3  330.29
  4975.3  329.88  4985.6  326.59  5001.2  324.56  5003.9  324.06  5007.2  324.56
  5042.6  327.52    5295  326.55  5381.2  328.25  5429.4  327.34  5789.5  329.76
  5847.6  328.41  5909.1  330.37  5923.9  331.12  5929.6  333.41  5938.3  333.81
  5980.9  339.64  6015.2   341.7  6021.9  343.92  6063.4  350.12  6093.7  351.78
  6144.5  357.94  6165.5  362.34  6192.7  364.64  6197.8   369.7  6216.8  370.33
#Mann= 5 ,-1 , 0
  4185.9     .05       0  5001.2     .03       0  5007.2     .05       0
  5042.6     .12       0  5938.3     .05       0
Bank Sta=4975.3,5909.1
XS Rating Curve= 0 ,0
Exp/Cntr=0.3,0.1

Chan Stop Cuts=-1
Use User Specified Reach Order=0
Composite Channel Slope=5