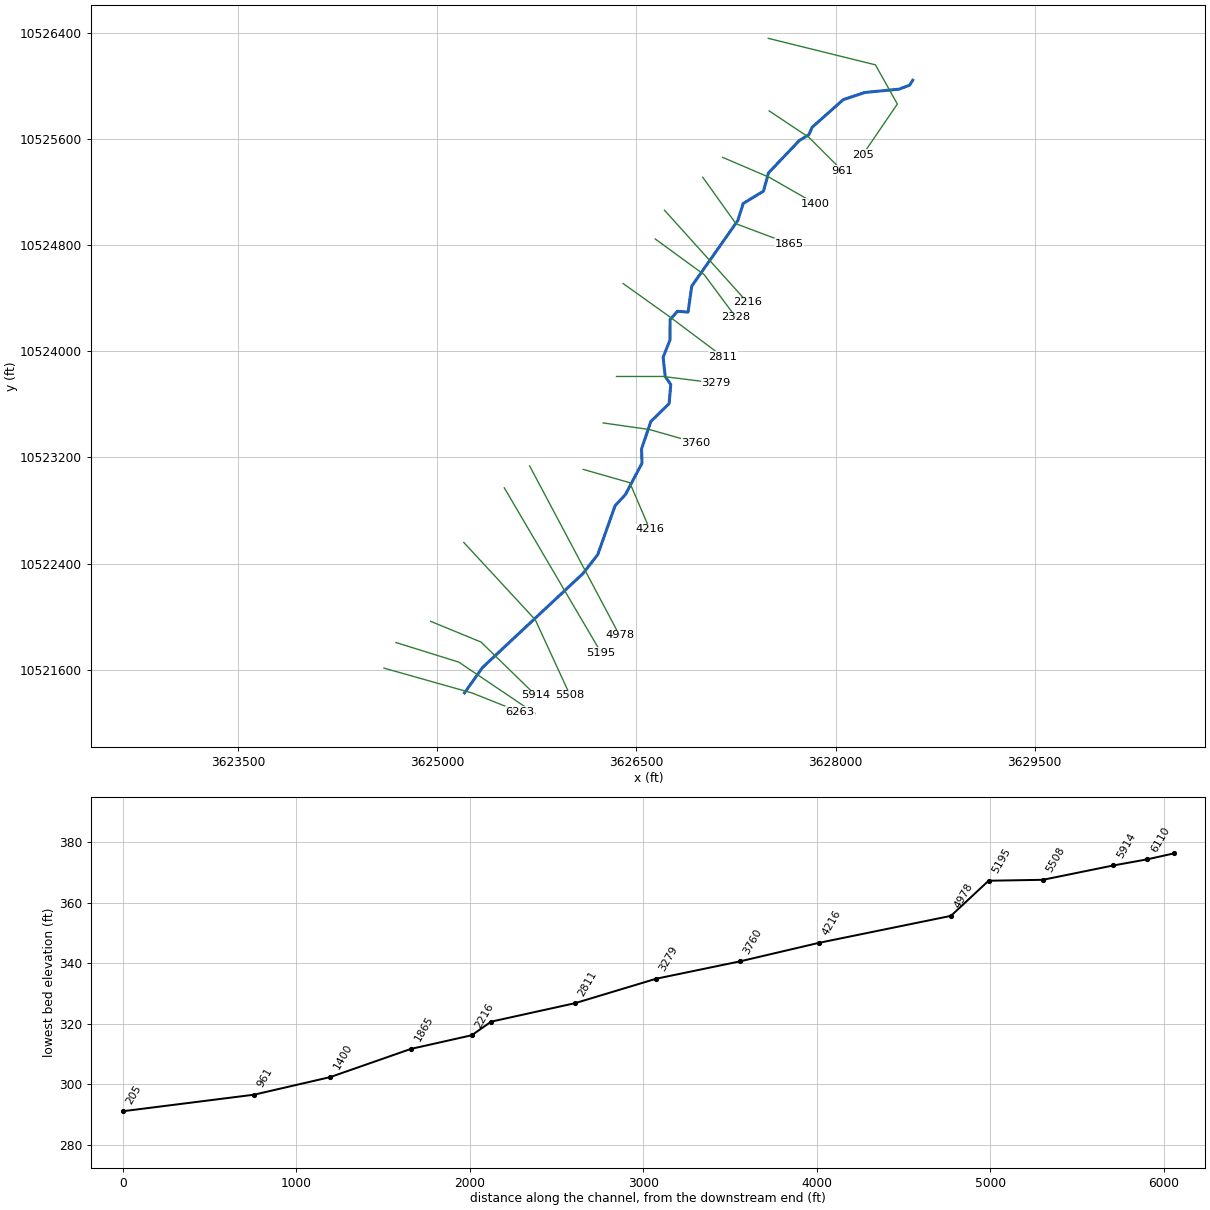
--- UNNAMED TRIB 1 TO BUFFALO CR.prj (project) ---

Proj Title=UNNAMED TRIB 1 TO BUFFALO CR Base Level Engineering
Current Plan=p01
Default Exp/Contr=0.3,0.1
English Units
Geom File=g01
Flow File=f01
Plan File=p01
Y Axis Title=Elevation
X Axis Title(PF)=Main Channel Distance
X Axis Title(XS)=Station
BEGIN DESCRIPTION:
UNNAMED TRIB 1 TO BUFFALO CR
END DESCRIPTION:
DSS Export Rating Curves= 0
DSS Export Rating Curve Sorted= 0
DSS Export Volume Flow Curves= 0
DXF OffsetX= 0
DXF OffsetY= 0
DXF ScaleX= 1
DXF ScaleY= 10

--- UNNAMED TRIB 1 TO BUFFALO CR.p01 (plan) ---

Plan Title=Multiple Run
Short Identifier=Multiple
Geom File=g01
Flow File=f01
Subcritical Flow
K Sum by GR= 0
Std Step Tol= 0.01
Critical Tol= 0.01
Num of Std Step Trials= 20
Max Error Tol= 0.3
Flow Tol Ratio= 0.001
Split Flow NTrial= 30
Split Flow Tol= 0.02
Split Flow Ratio= 0.02
Log Output Level= 0
Friction Slope Method= 1
Unsteady Friction Slope Method= 2
Unsteady Bridges Friction Slope Method= 1
Parabolic Critical Depth
Global Vel Dist=  1 , 1 , 1
Global Log Level= 0
CheckData=True
Encroach Param= -1, 0, 0, 0
BEGIN DESCRIPTION:
Multiple Run
END DESCRIPTION:

--- UNNAMED TRIB 1 TO BUFFALO CR.f01 (steady flow) ---

Flow Title=Multiple
Number of Profiles=7
Profile Names=10-year,25-year,50-year,1pct_min,100-year,1pct_plu,500-year
River Rch & RM= UNNAMED TRIB 1 T,Reach-1,6263
     480     631     752     656     887    1200    1228
Boundary for River Rch & Prof#=UNNAMED TRIB 1 T,Reach-1,1
Up Type=0
Dn Type=3
Dn Slope=0.005
Boundary for River Rch & Prof#=UNNAMED TRIB 1 T,Reach-1,2
Up Type=0
Dn Type=3
Dn Slope=0.005
Boundary for River Rch & Prof#=UNNAMED TRIB 1 T,Reach-1,3
Up Type=0
Dn Type=3
Dn Slope=0.005
Boundary for River Rch & Prof#=UNNAMED TRIB 1 T,Reach-1,4
Up Type=0
Dn Type=3
Dn Slope=0.005
Boundary for River Rch & Prof#=UNNAMED TRIB 1 T,Reach-1,5
Up Type=0
Dn Type=3
Dn Slope=0.005
Boundary for River Rch & Prof#=UNNAMED TRIB 1 T,Reach-1,6
Up Type=0
Dn Type=3
Dn Slope=0.005
Boundary for River Rch & Prof#=UNNAMED TRIB 1 T,Reach-1,7
Up Type=0
Dn Type=3
Dn Slope=0.005

--- UNNAMED TRIB 1 TO BUFFALO CR.g01 (geometry) ---

Geom Title=Existing Conditions
Program Version=4.10

River Reach=UNNAMED TRIB 1 T,Reach-1
Reach XY= 30
      3625204.75       10521427.      3625340.25       10521618.
      3626096.25       10522325.      3626208.25       10522468.
      3626339.25       10522837.        3626417.       10522921.
      3626541.75       10523157.      3626538.25       10523264.
      3626608.25       10523471.      3626746.25       10523606.
      3626758.25       10523749.       3626716.5       10523811.
        3626701.       10523955.      3626752.75       10524086.
        3626753.       10524239.       3626809.5       10524301.
      3626888.75       10524295.       3626916.5       10524491.
        3627263.       10524984.      3627304.25       10525113.
      3627456.75       10525206.      3627494.25       10525343.
       3627726.5       10525587.       3627798.5       10525631.
      3627823.25       10525687.       3628057.5       10525895.
      3628220.25       10525949.        3628478.       10525974.
       3628557.5       10526004.       3628580.5       10526041.

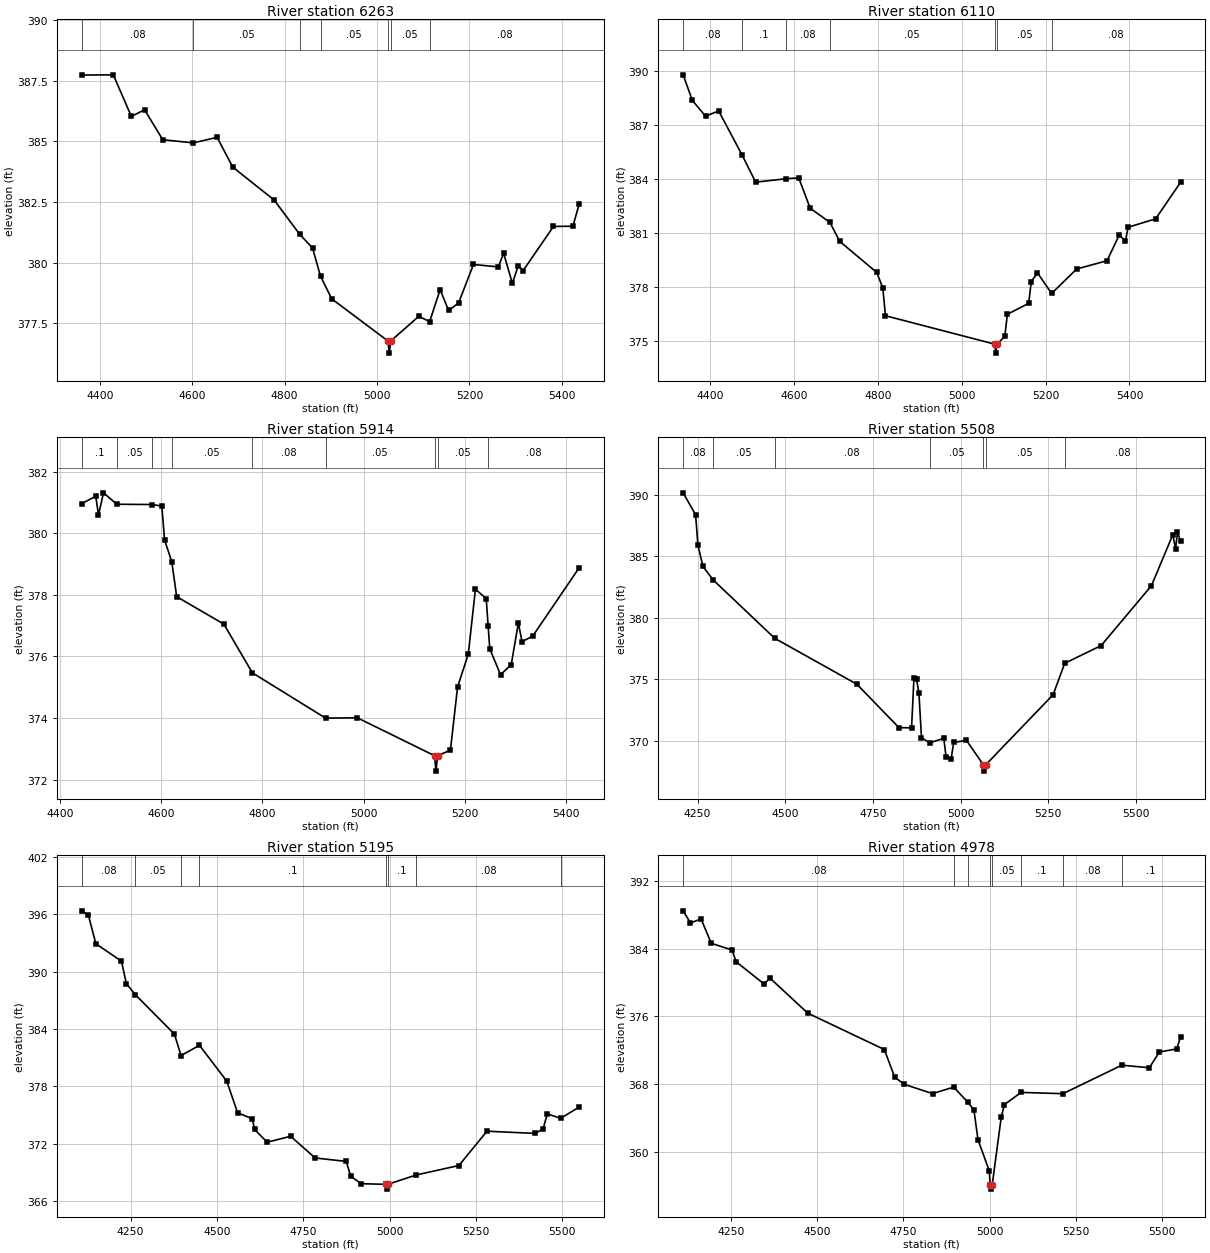
Type RM Length L Ch R = 1 ,6263    ,153,153,153
BEGIN DESCRIPTION:
UNNAMED TRIB 1 TO BUFFALO CR 13.0
END DESCRIPTION:
XS GIS Cut Line= 3
       3624598.8     10521613.66      3625262.88     10521426.15
      3625622.25     10521282.92
#Sta/Elev= 30
  4360.8  387.74    4429  387.75  4468.2  386.03  4496.7  386.31  4536.1  385.07
  4602.5  384.94  4653.7  385.17  4687.7  383.94  4777.3  382.58  4832.4  381.17
  4860.4   380.6  4877.7  379.43    4902   378.5  5023.7  376.76  5026.4  376.26
  5029.7  376.76  5090.4  377.78  5113.9  377.56  5136.6  378.88    5155  378.02
  5176.5  378.33  5208.8  379.92  5262.6  379.82  5274.1  380.38    5293  379.14
  5305.7  379.87  5316.4  379.67    5382  381.49  5424.1   381.5  5437.7  382.42
#Mann= 7 ,-1 , 0
  4360.8     .08       0  4602.5     .05       0  4832.4     .08       0
  4877.7     .05       0  5023.7     .04       0  5029.7     .05       0
  5113.9     .08       0
Bank Sta=5023.7,5029.7
XS Rating Curve= 0 ,0
Exp/Cntr=0.3,0.1

Type RM Length L Ch R = 1 ,6110    ,196,196,196
BEGIN DESCRIPTION:
Mapping XS 94b8f0b0
END DESCRIPTION:
XS GIS Cut Line= 3
      3624688.63     10521806.37      3625161.31     10521659.22
      3625735.07     10521272.82
#Sta/Elev= 30
  4335.1  389.79  4357.1  388.37  4388.5  387.49  4419.9  387.78  4475.8  385.33
  4508.1  383.82  4580.6  384.01  4610.9  384.06  4638.2  382.37  4685.5  381.58
  4708.5  380.53    4797   378.8  4811.4  377.95  4817.9  376.39  5078.3  374.81
    5081  374.31  5084.3  374.81  5102.6  375.25  5108.7  376.47  5159.6  377.08
  5165.7  378.29  5180.6  378.77  5214.3  377.63  5274.2  378.99  5346.5  379.45
  5375.6  380.88  5390.5  380.54  5396.6  381.31  5462.5  381.78  5521.9  383.81
#Mann= 7 ,-1 , 0
  4335.1     .08       0  4475.8      .1       0  4580.6     .08       0
  4685.5     .05       0  5078.3     .04       0  5084.3     .05       0
  5214.3     .08       0
Bank Sta=5078.3,5084.3
XS Rating Curve= 0 ,0
Exp/Cntr=0.3,0.1

Type RM Length L Ch R = 1 ,5914    ,406,406,406
BEGIN DESCRIPTION:
Mapping XS b1191297
END DESCRIPTION:
XS GIS Cut Line= 3
      3624949.97     10521966.07      3625329.72     10521809.83
       3625739.9      10521410.5
#Sta/Elev= 30
    4443  380.96  4470.6   381.2    4476  380.59  4485.9  381.31  4512.1  380.94
    4582  380.93  4601.2  380.88  4606.6  379.78  4620.8  379.08  4630.6  377.94
  4723.8  377.05  4780.1  375.47  4924.8     374  4987.7  374.01  5140.3  372.78
    5143  372.28  5146.3  372.78  5171.6  372.96  5185.7  375.01  5206.9  376.08
    5221  378.18  5242.3  377.88  5246.1     377  5249.3  376.25  5270.6  375.41
  5291.7  375.73  5305.9  377.09    5313  376.48  5334.2  376.66  5426.1  378.88
#Mann= 9 ,-1 , 0
    4443      .1       0  4512.1     .05       0    4582     .08       0
  4620.8     .05       0  4780.1     .08       0  4924.8     .05       0
  5140.3     .04       0  5146.3     .05       0  5246.1     .08       0
Bank Sta=5140.3,5146.3
XS Rating Curve= 0 ,0
Exp/Cntr=0.3,0.1

Type RM Length L Ch R = 1 ,5508    ,313,313,313
BEGIN DESCRIPTION:
UNNAMED TRIB 1 TO BUFFALO CR 12.0
END DESCRIPTION:
XS GIS Cut Line= 3
      3625199.58     10522560.22       3625738.3     10521977.53
      3625999.61     10521410.18
#Sta/Elev= 30
  4208.7  390.15  4244.2  388.37    4251  385.88  4265.2  384.17  4294.8  383.06
  4469.9  378.33    4704   374.6  4824.2  371.07    4860  371.06  4866.8   375.1
  4874.1  375.02  4880.9  373.92  4888.3  370.26  4911.4  369.84  4951.8   370.2
  4958.6  368.66  4972.8  368.55  4980.2  369.87  5016.6  370.04    5065  368.04
  5067.8  367.54    5071  368.04  5263.6  373.75  5296.6   376.3  5400.5  377.74
  5543.8   382.6  5604.9  386.75  5612.7  385.59  5618.2  386.94  5626.9  386.25
#Mann= 7 ,-1 , 0
  4208.7     .08       0  4294.8     .05       0  4469.9     .08       0
  4911.4     .05       0    5065     .04       0    5071     .05       0
  5296.6     .08       0
Bank Sta=5065,5071
XS Rating Curve= 0 ,0
Exp/Cntr=0.3,0.1

Type RM Length L Ch R = 1 ,5195    ,217,217,217
BEGIN DESCRIPTION:
UNNAMED TRIB 1 TO BUFFALO CR 11.0
END DESCRIPTION:
XS GIS Cut Line= 2
      3625504.71     10522971.33      3626233.91     10521729.95
#Sta/Elev= 30
    4109  396.35  4128.1   395.9  4149.6  392.91  4223.9  391.08  4237.9  388.74
  4264.2  387.57  4377.1  383.45  4396.3   381.2  4449.5  382.28  4528.5  378.54
  4559.9  375.23  4602.8  374.58    4609  373.47  4645.7  372.14  4713.4  372.76
  4784.4  370.49  4874.4  370.13  4887.4  368.58  4917.3   367.8  4988.6  367.73
  4991.3  367.23  4994.6  367.73  5076.8  368.71  5200.5   369.7  5281.7  373.29
  5420.9  373.06    5444  373.52  5456.4   375.1  5495.1  374.64  5548.7  375.82
#Mann= 8 ,-1 , 0
    4109     .08       0  4264.2     .05       0  4396.3     .08       0
  4449.5      .1       0  4988.6     .07       0  4994.6      .1       0
  5076.8     .08       0  5495.1      .1       0
Bank Sta=4988.6,4994.6
XS Rating Curve= 0 ,0
Exp/Cntr=0.3,0.1

Type RM Length L Ch R = 1 ,4978    ,762,762,762
BEGIN DESCRIPTION:
UNNAMED TRIB 1 TO BUFFALO CR 10.0
END DESCRIPTION:
XS GIS Cut Line= 2
      3625695.71     10523136.21      3626372.77     10521860.21
#Sta/Elev= 30
  4110.1  388.46  4131.5  387.03  4162.2   387.5  4191.8  384.63  4252.1  383.84
  4264.1  382.45  4345.7  379.81    4362  380.53    4472  376.39  4694.3   372.1
  4724.5  368.84  4752.2  367.99  4834.5   366.9  4895.7  367.66    4937  365.88
  4954.6  364.96  4966.4  361.46    4999   357.8  5001.7  356.13  5004.4  355.63
  5007.7  356.13  5033.9  364.13    5043   365.6  5091.6  367.04  5213.1  366.89
    5384  370.25  5464.1  369.95  5493.4  371.82  5543.3  372.16  5554.6  373.56
#Mann= 8 ,-1 , 0
  4110.1     .08       0  4895.7      .1       0    4937     .05       0
  5001.7     .04       0  5007.7     .05       0  5091.6      .1       0
  5213.1     .08       0    5384      .1       0
Bank Sta=5001.7,5007.7
XS Rating Curve= 0 ,0
Exp/Cntr=0.3,0.1

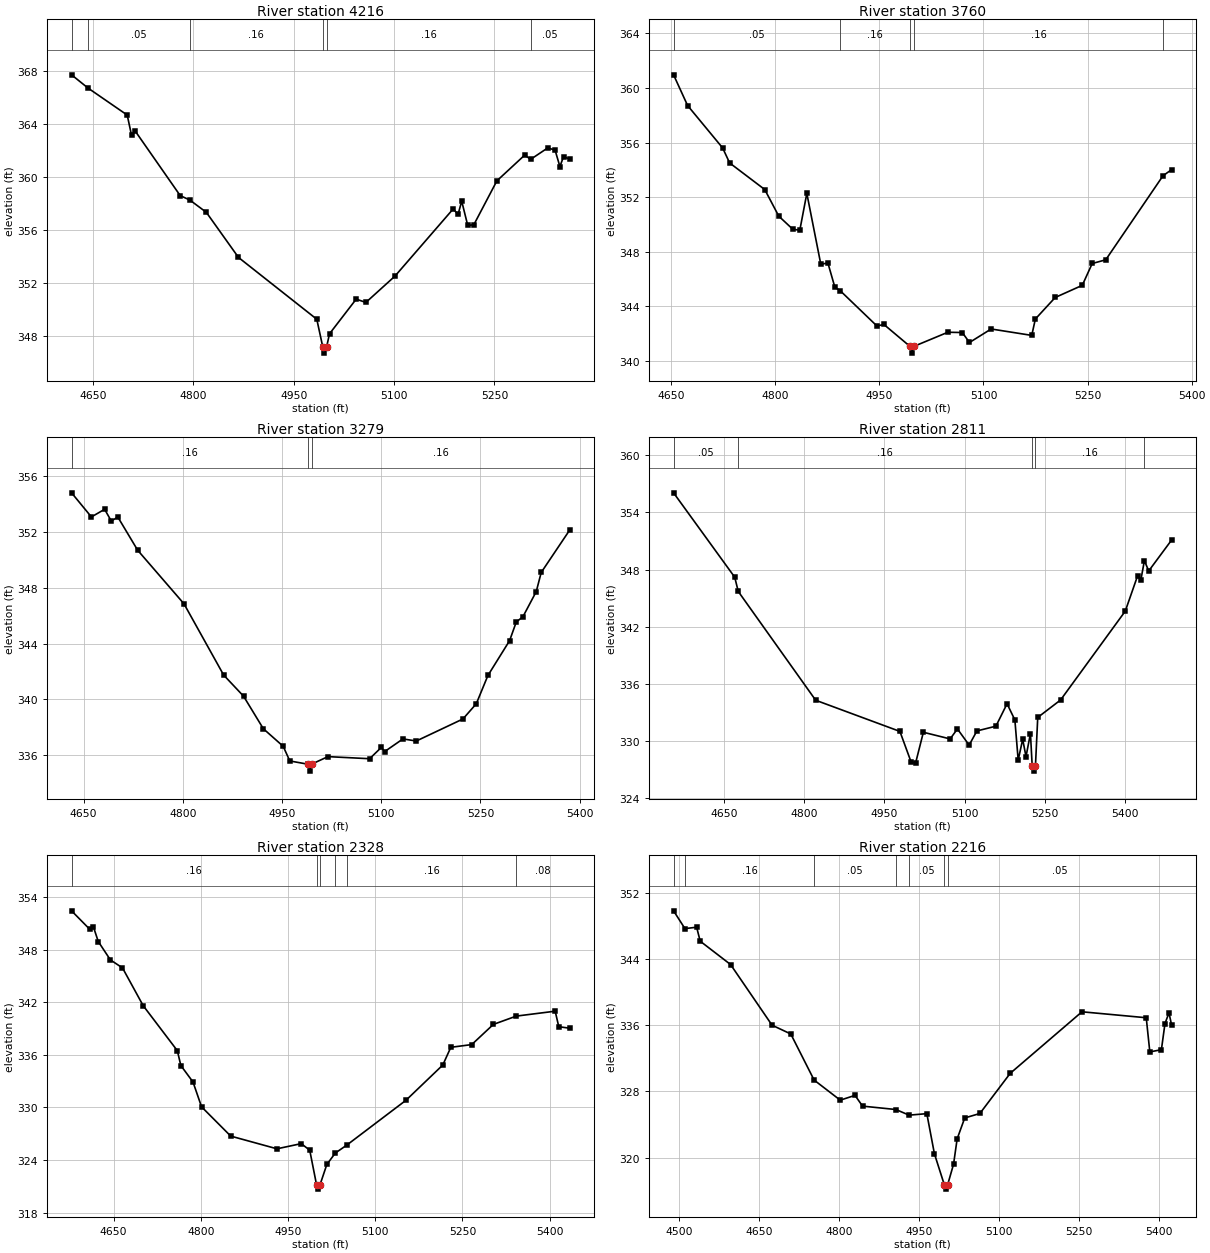
Type RM Length L Ch R = 1 ,4216    ,456,456,456
BEGIN DESCRIPTION:
UNNAMED TRIB 1 TO BUFFALO CR 9.0
END DESCRIPTION:
XS GIS Cut Line= 3
      3626099.65     10523110.18      3626449.61     10523010.19
      3626599.59     10522660.23
#Sta/Elev= 30
  4617.7  367.73  4642.3  366.73  4700.9  364.69  4707.4  363.16  4712.6   363.5
  4780.2   358.6  4794.5  358.27  4819.2  357.34  4867.3  353.93  4984.4  349.26
  4993.2   347.2  4995.9   346.7  4999.2   347.2  5003.4  348.16  5043.3  350.78
  5057.8  350.53  5101.3  352.52  5188.4   357.6  5195.6  357.18  5201.1  358.18
  5210.1  356.35  5219.2   356.4  5253.7  359.72  5295.4  361.67  5304.1  361.34
  5329.8  362.21  5340.7  362.04  5347.9   360.8  5353.4  361.55  5362.4  361.36
#Mann= 6 ,-1 , 0
  4617.7     .08       0  4642.3     .05       0  4794.5     .16       0
  4993.2     .07       0  4999.2     .16       0  5304.1     .05       0
Bank Sta=4993.2,4999.2
XS Rating Curve= 0 ,0
Exp/Cntr=0.3,0.1

Type RM Length L Ch R = 1 ,3760    ,481,481,481
BEGIN DESCRIPTION:
UNNAMED TRIB 1 TO BUFFALO CR 8.0
END DESCRIPTION:
XS GIS Cut Line= 3
      3626249.58     10523460.19      3626599.61     10523410.19
      3626949.62     10523310.19
#Sta/Elev= 30
  4653.5  360.97  4673.7  358.72  4724.2  355.61  4734.3  354.51  4784.9  352.56
  4805.1  350.61  4825.3  349.65  4835.4  349.58  4845.5  352.28  4865.7  347.07
  4875.8  347.19  4885.9   345.4  4893.3  345.16  4946.5  342.56  4956.6  342.67
    4994  341.07  4996.7  340.57    5000  341.07  5048.7   342.1  5069.5  342.08
  5079.9  341.35  5111.1  342.34  5169.6  341.87  5174.8  343.07  5203.4  344.65
  5242.4  345.54  5256.7  347.14  5276.2  347.41  5358.7  353.57  5371.1  354.02
#Mann= 5 ,-1 , 0
  4653.5     .05       0  4893.3     .16       0    4994     .07       0
    5000     .16       0  5358.7     .05       0
Bank Sta=4994,5000
XS Rating Curve= 0 ,0
Exp/Cntr=0.3,0.1

Type RM Length L Ch R = 1 ,3279    ,468,468,468
BEGIN DESCRIPTION:
UNNAMED TRIB 1 TO BUFFALO CR 7.0
END DESCRIPTION:
XS GIS Cut Line= 3
      3626349.65     10523810.19      3626699.61     10523810.19
      3627099.64     10523760.19
#Sta/Elev= 30
  4631.7  354.82  4661.7  353.09  4681.7  353.64  4691.7   352.8  4701.7  353.08
  4731.7   350.7  4801.7  346.86  4861.7  341.75  4891.7  340.24  4921.7   337.9
  4951.7  336.64  4961.7  335.59  4988.7  335.36  4991.5  334.86  4994.7  335.36
  5019.4   335.9  5082.4  335.75  5100.1  336.56  5105.1  336.26  5132.8  337.17
    5153  337.02  5223.5   338.6  5243.7  339.69  5261.3  341.72  5294.1  344.22
  5304.2  345.56  5314.2  345.93  5334.4  347.74  5341.9  349.11  5384.8  352.14
#Mann= 3 ,-1 , 0
  4631.7     .16       0  4988.7     .07       0  4994.7     .16       0
Bank Sta=4988.7,4994.7
XS Rating Curve= 0 ,0
Exp/Cntr=0.3,0.1

Type RM Length L Ch R = 1 ,2811    ,483,483,483
BEGIN DESCRIPTION:
UNNAMED TRIB 1 TO BUFFALO CR 6.0
END DESCRIPTION:
XS GIS Cut Line= 3
      3626399.64     10524510.16      3626749.61     10524260.19
      3627149.63     10523960.17
#Sta/Elev= 30
  4556.3  356.07  4670.5  347.19  4677.1  345.69  4821.7  334.24    4979  330.96
  4999.9  327.74  5008.3  327.63  5022.8  330.87  5072.8  330.17  5086.4  331.22
  5108.3  329.52  5122.8  331.01  5158.3  331.51  5179.1  333.87  5193.7  332.17
  5199.9  327.94  5208.3  330.13  5214.5  328.31  5222.8  330.74  5226.1  327.28
  5228.8  326.78  5232.1  327.28  5236.4  332.43  5279.1  334.27  5399.9  343.62
  5422.8  347.32  5429.1  346.93  5435.6  348.93  5443.7  347.85  5486.4   351.1
#Mann= 5 ,-1 , 0
  4556.3     .05       0  4677.1     .16       0  5226.1     .07       0
  5232.1     .16       0  5435.6     .05       0
Bank Sta=5226.1,5232.1
XS Rating Curve= 0 ,0
Exp/Cntr=0.3,0.1

Type RM Length L Ch R = 1 ,2328    ,112,112,112
BEGIN DESCRIPTION:
UNNAMED TRIB 1 TO BUFFALO CR 5.0
END DESCRIPTION:
XS GIS Cut Line= 3
      3626641.78     10524845.34      3627010.69     10524576.25
      3627249.35     10524255.15
#Sta/Elev= 30
  4577.6  352.43  4608.8  350.33    4615  350.64  4623.5  348.93  4644.4  346.83
  4665.2  345.92  4700.8  341.61  4759.5  336.48  4765.6  334.78  4786.5   332.9
  4801.2  330.07  4851.4  326.73  4930.9  325.28  4972.7  325.87  4987.3  325.12
    4999  321.18  5001.8  320.68    5005  321.18  5016.7  323.49  5031.2  324.79
  5051.4  325.72  5152.9  330.82  5216.2  334.84    5230  336.86    5266  337.17
  5303.1  339.47  5342.6  340.42  5409.5  340.98  5415.7  339.21  5434.3  339.04
#Mann= 6 ,-1 , 0
  4577.6     .16       0    4999     .07       0    5005     .16       0
  5031.2     .05       0  5051.4     .16       0  5342.6     .08       0
Bank Sta=4999,5005
XS Rating Curve= 0 ,0
Exp/Cntr=0.3,0.1

Type RM Length L Ch R = 1 ,2216    ,351,351,351
BEGIN DESCRIPTION:
Mapping XS e6d3cee5
END DESCRIPTION:
XS GIS Cut Line= 2
      3626711.22     10525062.35      3627335.43     10524368.78
#Sta/Elev= 30
  4490.3  349.82  4511.6  347.67  4533.5  347.84  4540.2  346.15  4597.1  343.33
  4674.8     336  4709.9  334.94  4753.6  329.37  4802.6  326.94  4830.2  327.52
  4844.4  326.22  4906.8  325.81  4931.6  325.13  4964.8  325.31    4979  320.47
  4997.7  316.69  5000.4  316.19  5003.7  316.69  5014.9  319.21  5021.6  322.26
  5035.8  324.79  5064.2  325.33    5121  330.18  5255.5  337.62  5375.9   336.9
  5382.6  332.77  5404.3  333.04    5411   336.2  5418.5  337.49  5423.4  336.02
#Mann= 7 ,-1 , 0
  4490.3     .05       0  4511.6     .16       0  4753.6     .05       0
  4906.8     .16       0  4931.6     .05       0  4997.7     .04       0
  5003.7     .05       0
Bank Sta=4997.7,5003.7
XS Rating Curve= 0 ,0
Exp/Cntr=0.3,0.1

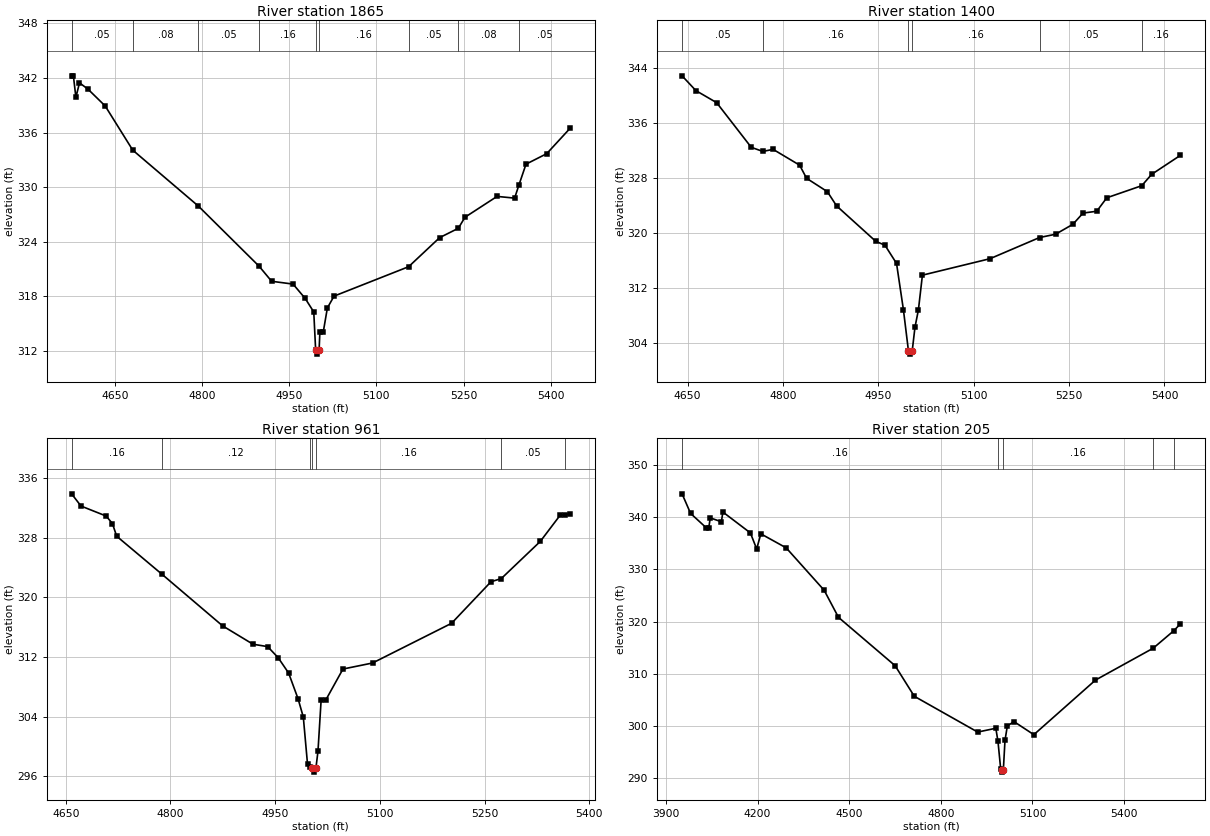
Type RM Length L Ch R = 1 ,1865    ,465,465,465
BEGIN DESCRIPTION:
UNNAMED TRIB 1 TO BUFFALO CR 4.0
END DESCRIPTION:
XS GIS Cut Line= 3
      3626999.58     10525310.23      3627249.61     10524960.19
      3627649.64     10524810.18
#Sta/Elev= 30
  4575.7  342.23  4578.8  342.23  4583.1  339.87  4589.3  341.46    4604  340.76
  4633.5  338.92  4680.9  334.07  4793.9  327.92  4898.3  321.32  4919.8  319.67
  4956.7  319.36  4977.6  317.78  4992.3   316.3  4995.5  312.17  4998.2  311.67
  5001.5  312.17  5002.8  314.05  5008.5  314.05  5015.7  316.74  5027.2  318.04
  5155.5  321.27  5208.8  324.46    5241  325.49  5252.4   326.7  5307.6  328.99
  5337.8   328.8    5345   330.2  5357.4  332.53    5393  333.68  5433.1  336.46
#Mann= 9 ,-1 , 0
  4575.7     .05       0  4680.9     .08       0  4793.9     .05       0
  4898.3     .16       0  4995.5     .07       0  5001.5     .16       0
  5155.5     .05       0    5241     .08       0    5345     .05       0
Bank Sta=4995.5,5001.5
XS Rating Curve= 0 ,0
Exp/Cntr=0.3,0.1

Type RM Length L Ch R = 1 ,1400    ,439,439,439
BEGIN DESCRIPTION:
UNNAMED TRIB 1 TO BUFFALO CR 3.0
END DESCRIPTION:
XS GIS Cut Line= 3
      3627149.63     10525460.18      3627499.61     10525310.19
      3627849.62     10525110.18
#Sta/Elev= 30
  4641.3  342.89    4663  340.74  4695.7  338.98  4750.1  332.48  4768.3  331.88
  4784.5  332.18  4826.2  329.88  4837.1  327.97  4869.8  326.02  4884.3  323.95
  4945.9  318.79  4960.4  318.22  4978.6  315.57  4989.4  308.84  4997.3  302.86
  5000.1  302.36  5003.3  302.86  5007.6  306.28    5013   308.8  5019.3  313.86
  5125.7  316.26  5203.5  319.34  5228.7  319.82    5256  321.27  5271.9   322.9
  5293.5  323.17  5309.3  325.13  5364.3  326.89  5379.8  328.54  5425.2  331.32
#Mann= 6 ,-1 , 0
  4641.3     .05       0  4768.3     .16       0  4997.3     .07       0
  5003.3     .16       0  5203.5     .05       0  5364.3     .16       0
Bank Sta=4997.3,5003.3
XS Rating Curve= 0 ,0
Exp/Cntr=0.3,0.1

Type RM Length L Ch R = 1 ,961     ,756,756,756
BEGIN DESCRIPTION:
UNNAMED TRIB 1 TO BUFFALO CR 2.0
END DESCRIPTION:
XS GIS Cut Line= 3
      3627499.64     10525810.17      3627799.61     10525610.19
      3628049.63     10525360.16
#Sta/Elev= 30
  4658.4  333.91  4671.9  332.27  4707.9  330.93  4716.9  329.92    4723  328.22
  4788.2  323.09  4874.7  316.19  4918.3  313.72  4939.3   313.4  4954.3  311.92
  4969.3  309.86  4982.9  306.39  4990.4  303.94  4996.4  297.64  5000.1  297.28
  5002.4  297.05  5005.1  296.55  5008.4  297.05  5011.4  299.35  5015.9   306.2
  5022.4   306.2  5047.2  310.39  5089.6   311.2  5202.8  316.53  5259.3  322.11
    5274  322.53    5330  327.53  5358.3  331.03  5365.4  331.12  5372.5  331.16
#Mann= 7 ,-1 , 0
  4658.4     .16       0  4788.2     .12       0  5000.1     .16       0
  5002.4     .07       0  5008.4     .16       0    5274     .05       0
  5365.4     .16       0
Bank Sta=5002.4,5008.4
XS Rating Curve= 0 ,0
Exp/Cntr=0.3,0.1

Type RM Length L Ch R = 1 ,205     ,0,0,0
BEGIN DESCRIPTION:
UNNAMED TRIB 1 TO BUFFALO CR 1.0
END DESCRIPTION:
XS GIS Cut Line= 4
      3627492.53     10526356.73      3628299.87     10526157.07
       3628464.8     10525861.93      3628204.51     10525480.17
#Sta/Elev= 30
  3952.9  344.51  3980.8  340.75  4032.3  337.98    4040  337.87  4045.2  339.89
  4081.5  339.15  4086.6  341.01  4176.5  337.01  4197.1  333.94  4210.9  336.83
  4293.8  334.14  4418.1     326    4465   320.8  4650.4  311.52  4713.2  305.65
  4920.7  298.78  4980.1  299.51  4987.2  296.97  4996.1  291.64  4998.8  291.59
  5001.6  291.09  5004.8  291.59  5010.1  297.17  5017.8  299.95  5039.5  300.79
  5104.6  298.28  5306.4  308.76  5495.4  314.88  5563.2  318.25  5584.7  319.57
#Mann= 5 ,-1 , 0
  3952.9     .16       0  4987.2     .07       0  5004.8     .16       0
  5495.4     .05       0  5563.2     .16       0
Bank Sta=4998.8,5004.8
XS Rating Curve= 0 ,0
Exp/Cntr=0.3,0.1

Chan Stop Cuts=-1
Use User Specified Reach Order=0
Composite Channel Slope=5