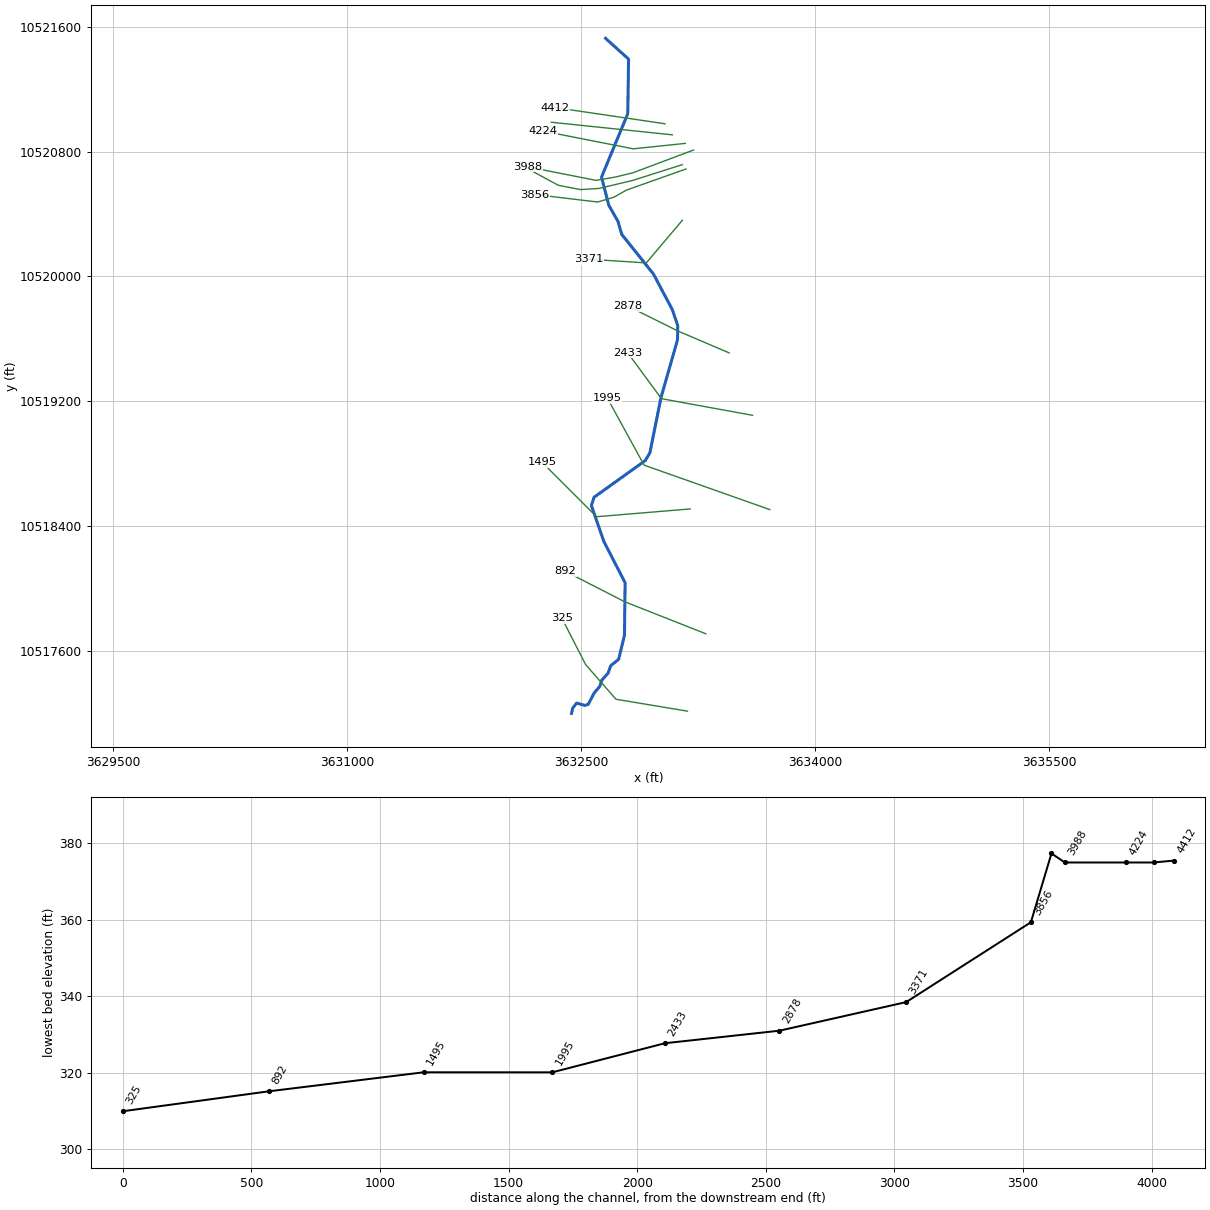
--- UNNAMED TRIB 1A1 TO BLISS CR.prj (project) ---

Proj Title=UNNAMED TRIB 1A1 TO BLISS CR Base Level Engineering
Current Plan=p01
Default Exp/Contr=0.3,0.1
English Units
Geom File=g01
Flow File=f01
Plan File=p01
Y Axis Title=Elevation
X Axis Title(PF)=Main Channel Distance
X Axis Title(XS)=Station
BEGIN DESCRIPTION:
UNNAMED TRIB 1A1 TO BLISS CR
END DESCRIPTION:
DSS Export Rating Curves= 0
DSS Export Rating Curve Sorted= 0
DSS Export Volume Flow Curves= 0
DXF OffsetX= 0
DXF OffsetY= 0
DXF ScaleX= 1
DXF ScaleY= 10

--- UNNAMED TRIB 1A1 TO BLISS CR.p01 (plan) ---

Plan Title=Multiple Run
Short Identifier=Multiple
Geom File=g01
Flow File=f01
Subcritical Flow
K Sum by GR= 0
Std Step Tol= 0.01
Critical Tol= 0.01
Num of Std Step Trials= 20
Max Error Tol= 0.3
Flow Tol Ratio= 0.001
Split Flow NTrial= 30
Split Flow Tol= 0.02
Split Flow Ratio= 0.02
Log Output Level= 0
Friction Slope Method= 1
Unsteady Friction Slope Method= 2
Unsteady Bridges Friction Slope Method= 1
Parabolic Critical Depth
Global Vel Dist=  1 , 1 , 1
Global Log Level= 0
CheckData=True
Encroach Param= -1, 0, 0, 0
BEGIN DESCRIPTION:
Multiple Run
END DESCRIPTION:

--- UNNAMED TRIB 1A1 TO BLISS CR.f01 (steady flow) ---

Flow Title=Multiple
Number of Profiles=7
Profile Names=10-year,25-year,50-year,1pct_min,100-year,1pct_plu,500-year
River Rch & RM= UNNAMED TRIB 1A1,Reach-1,4412
     334     428     501     431     583     789     783
Boundary for River Rch & Prof#=UNNAMED TRIB 1A1,Reach-1,1
Up Type=0
Dn Type=3
Dn Slope=0.005
Boundary for River Rch & Prof#=UNNAMED TRIB 1A1,Reach-1,2
Up Type=0
Dn Type=3
Dn Slope=0.005
Boundary for River Rch & Prof#=UNNAMED TRIB 1A1,Reach-1,3
Up Type=0
Dn Type=3
Dn Slope=0.005
Boundary for River Rch & Prof#=UNNAMED TRIB 1A1,Reach-1,4
Up Type=0
Dn Type=3
Dn Slope=0.005
Boundary for River Rch & Prof#=UNNAMED TRIB 1A1,Reach-1,5
Up Type=0
Dn Type=3
Dn Slope=0.005
Boundary for River Rch & Prof#=UNNAMED TRIB 1A1,Reach-1,6
Up Type=0
Dn Type=3
Dn Slope=0.005
Boundary for River Rch & Prof#=UNNAMED TRIB 1A1,Reach-1,7
Up Type=0
Dn Type=3
Dn Slope=0.005

--- UNNAMED TRIB 1A1 TO BLISS CR.g01 (geometry) ---

Geom Title=Existing Conditions
Program Version=4.10

River Reach=UNNAMED TRIB 1A1,Reach-1
Reach XY= 30
      3632657.25       10521526.      3632804.75       10521393.
      3632799.75       10521043.       3632631.5       10520637.
      3632678.25       10520456.       3632736.5       10520354.
      3632761.16     10520269.51        3632964.       10520016.
       3633085.5       10519787.      3633120.25       10519684.
       3633118.5       10519594.       3633012.5       10519223.
       3632941.5       10518870.      3632911.75       10518820.
      3632583.75       10518585.       3632566.5       10518532.
      3632646.25       10518302.      3632782.75       10518037.
       3632778.5       10517701.       3632741.5       10517547.
       3632690.5       10517505.       3632673.5       10517458.
        3632632.       10517411.      3632620.75       10517374.
      3632583.25       10517329.       3632546.5       10517258.
      3632524.75       10517251.      3632471.75       10517266.
      3632446.75       10517234.       3632439.5       10517200.

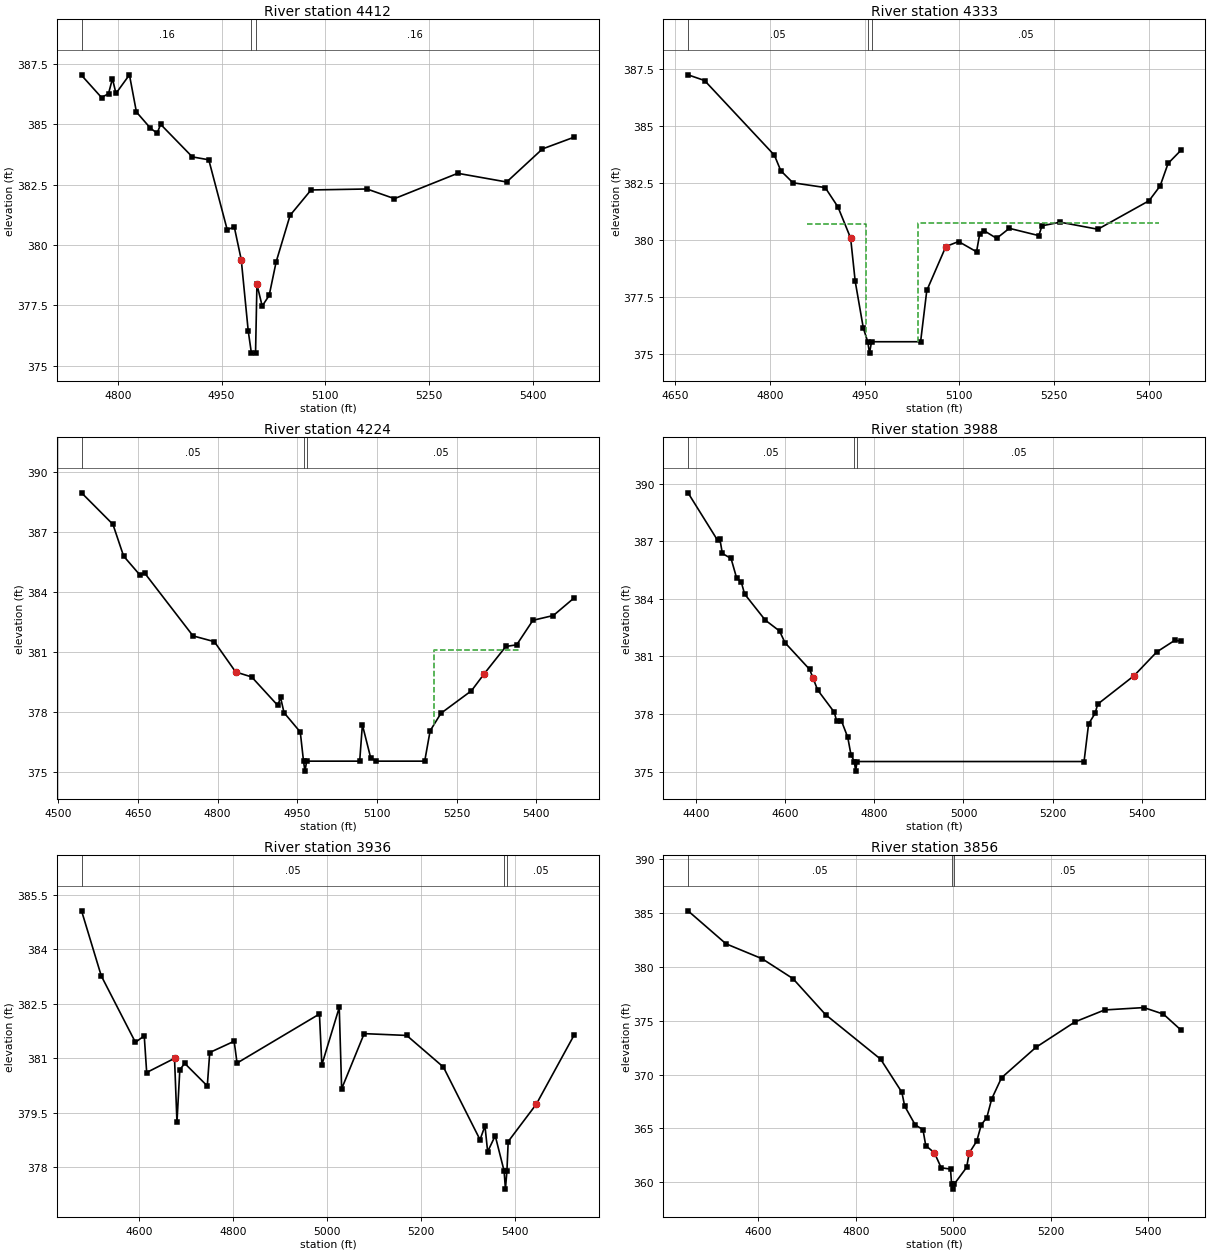
Type RM Length L Ch R = 1 ,4412    ,79,79,79
BEGIN DESCRIPTION:
UNNAMED TRIB 1A1 TO BLISS CR 9.0
END DESCRIPTION:
XS GIS Cut Line= 2
       3633038.2     10520978.57      3632332.71     10521082.45
#Sta/Elev= 30
  4747.4  387.03  4776.3  386.11  4786.4  386.27  4792.1  386.89  4797.2  386.28
  4816.7  387.05  4826.8  385.51  4847.1  384.84  4856.8  384.63  4861.8     385
  4907.7  383.65  4931.5  383.53  4958.2  380.63  4968.4  380.75  4978.5  379.39
  4988.6  376.44  4993.2  375.52  4999.2  375.52  5001.2  378.37  5008.8  377.47
  5018.9  377.91    5029   379.3  5049.2  381.23  5079.5  382.28  5160.4  382.32
  5200.2  381.92  5291.8  382.97  5362.6  382.61  5414.4  383.98  5460.5  384.47
#Mann= 3 ,-1 , 0
  4747.4     .16       0  4993.2     .03       0  4999.2     .16       0
Bank Sta=4978.5,5001.2
XS Rating Curve= 0 ,0
Exp/Cntr=0.3,0.1

Type RM Length L Ch R = 1 ,4333    ,109,109,109
BEGIN DESCRIPTION:
Mapping XS 2c93cdbc
END DESCRIPTION:
XS GIS Cut Line= 2
      3633085.69     10520907.57      3632309.58      10520988.3
#Sta/Elev= 30
  4670.3  387.24  4696.5  386.99  4807.1  383.71  4817.2  383.03  4836.4   382.5
  4887.5  382.29  4907.7  381.44  4927.8  380.07    4935  378.18  4947.9  376.12
  4954.9  375.52  4957.7  375.02  4960.9  375.52  5038.6  375.52  5048.4  377.77
  5078.6   379.7  5098.7  379.92  5127.2  379.47  5132.2  380.26  5138.9   380.4
    5159  380.06  5179.1   380.5  5225.8  380.18  5230.8  380.61  5259.5  380.77
  5319.3  380.46  5400.3  381.71  5417.9  382.36  5430.5  383.35  5450.6  383.92
#Mann= 3 ,-1 , 0
  4670.3     .05       0  4954.9     .03       0  4960.9     .05       0
#XS Ineff= 2 ,-1
 4859.09 4952.27  380.69 5034.09 5415.91  380.73
Permanent Ineff=
       F       F
Bank Sta=4927.8,5078.6
XS Rating Curve= 0 ,0
Exp/Cntr=0.3,0.1

Type RM Length L Ch R = 1 ,4224    ,236,236,236
BEGIN DESCRIPTION:
Mapping XS 32b83128
END DESCRIPTION:
XS GIS Cut Line= 3
      3633168.36      10520852.7       3632834.2     10520817.98
       3632253.1     10520932.29
#Sta/Elev= 30
  4543.7  388.97  4602.8  387.39  4622.9   385.8    4653  384.87  4663.1  384.93
  4753.6   381.8  4793.8  381.51    4834  379.99  4864.2  379.74  4913.4  378.31
  4918.5  378.72  4925.1  377.95  4955.7  376.98  4961.8  375.52  4964.5  375.02
  4967.8  375.52  5067.6  375.52  5072.7  377.34  5088.2   375.7  5098.4  375.52
  5190.1  375.52  5200.3  377.04  5220.7  377.92  5278.2  379.05  5302.2   379.9
    5343  381.27  5363.3  381.35  5393.9  382.58  5432.4  382.82  5471.9  383.71
#Mann= 3 ,-1 , 0
  4543.7     .05       0  4961.8     .03       0  4967.8     .05       0
#XS Ineff= 1 ,-1
 5207.27 5370.91  381.11
Permanent Ineff=
       F
Bank Sta=4834,5302.2
XS Rating Curve= 0 ,0
Exp/Cntr=0.3,0.1

Type RM Length L Ch R = 1 ,3988    ,52,52,52
BEGIN DESCRIPTION:
Mapping XS 300049c2
END DESCRIPTION:
XS GIS Cut Line= 5
      3633221.71      10520810.3      3632832.81     10520664.46
      3632718.23     10520636.68       3632596.7     10520615.85
      3632156.78     10520702.41
#Sta/Elev= 30
  4382.3  389.52  4448.5  387.05  4453.9  387.09  4459.3  386.36  4478.8   386.1
  4491.3  385.08    4502  384.85  4509.1  384.25  4555.4  382.89  4587.5  382.32
  4599.8  381.71    4655  380.32  4662.2  379.89  4672.9  379.25  4710.2  378.09
  4715.6  377.63  4726.3  377.64  4740.5  376.78  4747.7  375.87  4755.3  375.52
  4758.1  375.02  4761.3  375.52  5270.3  375.52  5280.5  377.48  5295.1  378.03
  5300.9  378.51  5382.4  379.99  5433.4  381.23  5474.1  381.84  5487.2  381.79
#Mann= 3 ,-1 , 0
  4382.3     .05       0  4755.3    .033       0  4761.3     .05       0
Bank Sta=4662.2,5382.4
XS Rating Curve= 0 ,0
Exp/Cntr=0.3,0.1

Type RM Length L Ch R = 1 ,3936    ,80,80,80
BEGIN DESCRIPTION:
UNNAMED TRIB 1A1 TO BLISS CR 8.0
END DESCRIPTION:
XS GIS Cut Line= 6
      3633148.78     10520716.54      3632832.81     10520615.85
      3632614.06     10520563.76        3632496.     10520556.82
      3632354.28     10520584.36      3632153.13     10520693.33
#Sta/Elev= 30
  4477.5  385.06  4519.4  383.27  4592.1  381.44  4610.8  381.62    4616  380.61
  4675.2     381  4680.4  379.24  4686.5  380.69    4697  380.86  4744.9  380.24
  4750.1  381.16    4802  381.47  4808.2  380.87  4983.4  382.22  4988.5  380.82
  5025.5   382.4  5030.6  380.16  5078.5  381.68    5169  381.63    5247  380.76
  5324.9  378.76  5335.4  379.14  5341.1  378.43  5357.2  378.87  5376.1   377.9
  5378.9   377.4  5382.1   377.9  5384.8  378.71  5444.7  379.74  5525.4  381.65
#Mann= 3 ,-1 , 0
  4477.5     .05       0  5376.1    .033       0  5382.1     .05       0
Bank Sta=4675.2,5444.7
XS Rating Curve= 0 ,0
Exp/Cntr=0.3,0.1

Type RM Length L Ch R = 1 ,3856    ,485,485,485
BEGIN DESCRIPTION:
Mapping XS 9b0690fb
END DESCRIPTION:
XS GIS Cut Line= 5
      3633173.04     10520688.75      3632791.14     10520553.35
      3632711.28     10520508.21      3632607.12     10520476.96
      3632204.37     10520525.15
#Sta/Elev= 30
  4455.7   385.2  4533.6  382.14  4607.9  380.75    4671  378.91  4738.1  375.56
    4851  371.43  4894.6  368.36  4900.3  367.08    4922  365.33  4937.9  364.89
  4943.6  363.41  4961.4  362.74  4975.3  361.35  4994.4  361.23  4996.6  359.87
  4999.4  359.37  5002.6  359.87  5027.5  361.39  5032.7  362.71  5048.3  363.83
  5057.5  365.34  5068.9  366.01    5079  367.75  5099.2  369.71  5169.7  372.53
  5250.2   374.9  5310.7     376  5391.2  376.22  5431.5  375.61    5467  374.15
#Mann= 3 ,-1 , 0
  4455.7     .05       0  4996.6     .03       0  5002.6     .05       0
Bank Sta=4961.4,5032.7
XS Rating Curve= 0 ,0
Exp/Cntr=0.3,0.1

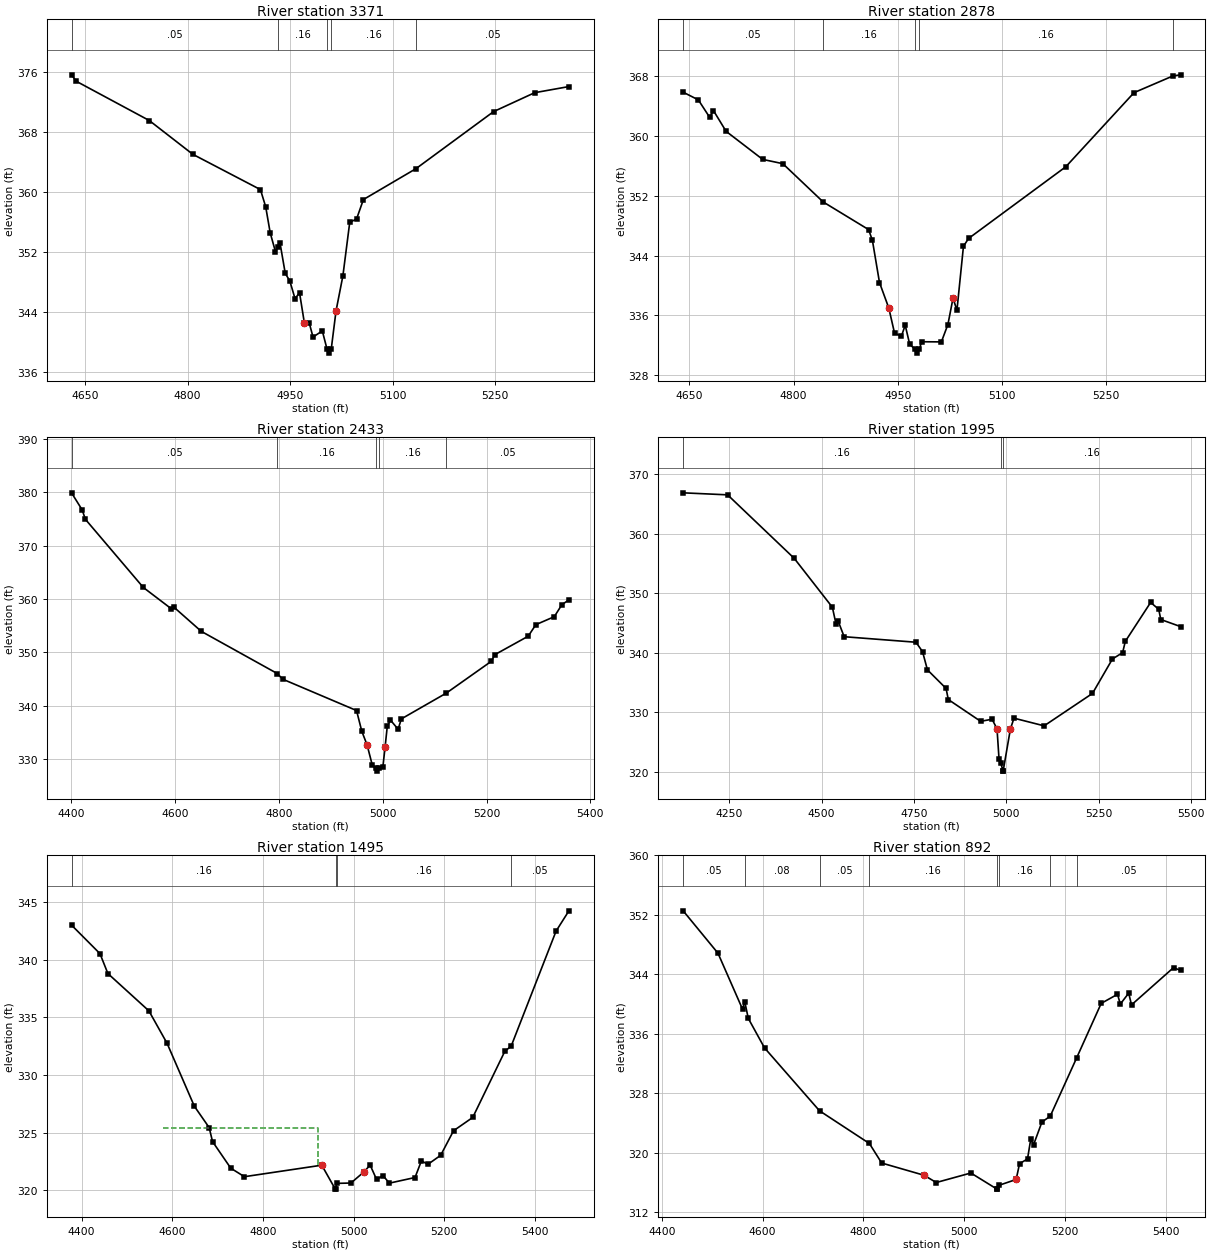
Type RM Length L Ch R = 1 ,3371    ,493,493,493
BEGIN DESCRIPTION:
UNNAMED TRIB 1A1 TO BLISS CR 7.0
END DESCRIPTION:
XS GIS Cut Line= 3
      3633149.61     10520360.19      3632918.44     10520086.86
      3632549.65     10520110.19
#Sta/Elev= 30
  4630.2  375.68  4637.3  374.81  4743.9  369.57  4807.6  365.05  4906.5  360.33
  4914.2  358.03  4920.8  354.54  4928.5  352.02  4932.3  352.71  4935.1  353.21
  4942.8  349.12  4949.4  348.13  4957.1  345.75  4963.7  346.53  4970.7  342.53
  4977.9  342.49  4983.4  340.61    4997  341.43    5004  338.96  5006.8  338.46
    5010  338.96  5017.1  344.12  5027.1  348.79  5037.1  355.95  5047.1   356.4
  5057.1     359    5134  363.13  5247.5  370.76  5307.6  373.29  5357.7  374.11
#Mann= 5 ,-1 , 0
  4630.2     .05       0  4932.3     .16       0    5004     .07       0
    5010     .16       0    5134     .05       0
Bank Sta=4970.7,5017.1
XS Rating Curve= 0 ,0
Exp/Cntr=0.3,0.1

Type RM Length L Ch R = 1 ,2878    ,445,445,445
BEGIN DESCRIPTION:
UNNAMED TRIB 1A1 TO BLISS CR 6.0
END DESCRIPTION:
XS GIS Cut Line= 3
      3633449.64     10519510.18       3633123.3     10519649.36
      3632799.63     10519810.18
#Sta/Elev= 30
  4641.1   365.8  4662.9  364.78  4679.3  362.44  4684.7  363.35  4702.9  360.58
  4755.6  356.83  4784.6  356.26  4842.7  351.15  4908.1  347.46  4913.6  346.02
  4923.8  340.39  4937.2  336.99  4945.5  333.62  4955.4  333.24  4960.8   334.7
  4967.3  332.15  4975.2  331.47  4977.9  330.97  4981.2  331.47  4984.4  332.49
  5012.9  332.47  5022.3  334.79  5029.7  338.31  5035.3  336.68  5044.7  345.23
  5052.1  346.28  5192.1  355.85  5290.3  365.74  5346.3  367.97  5357.3  368.12
#Mann= 5 ,-1 , 0
  4641.1     .05       0  4842.7     .16       0  4975.2     .07       0
  4981.2     .16       0  5346.3     .05       0
Bank Sta=4937.2,5029.7
XS Rating Curve= 0 ,0
Exp/Cntr=0.3,0.1

Type RM Length L Ch R = 1 ,2433    ,438,438,438
BEGIN DESCRIPTION:
UNNAMED TRIB 1A1 TO BLISS CR 5.0
END DESCRIPTION:
XS GIS Cut Line= 3
      3633599.66     10519110.18      3633015.66     10519216.72
      3632799.58     10519510.23
#Sta/Elev= 30
  4400.6  379.91    4421  376.72  4427.3  374.94  4538.9  362.15  4592.2   358.2
  4597.3   358.5  4650.5  353.92  4797.1  345.99  4807.2  344.95  4949.6  339.06
  4959.7  335.18  4969.9  332.61  4980.1  328.76    4987  328.19  4989.7  327.69
    4993  328.19  5000.4  328.53 5004.55  332.17  5008.8  336.09    5015  337.26
  5029.7  335.55  5035.9  337.49  5122.7  342.34  5209.4  348.31  5215.6  349.52
  5280.3  353.01    5295  355.17  5330.5  356.67  5345.1  358.91  5358.7  359.83
#Mann= 5 ,-1 , 0
  4400.6     .05       0  4797.1     .16       0    4987     .07       0
    4993     .16       0  5122.7     .05       0
Bank Sta=4969.9,5004.55
XS Rating Curve= 0 ,0
Exp/Cntr=0.3,0.1

Type RM Length L Ch R = 1 ,1995    ,500,500,500
BEGIN DESCRIPTION:
UNNAMED TRIB 1A1 TO BLISS CR 4.0
END DESCRIPTION:
XS GIS Cut Line= 3
       3633710.1      10518505.9      3632904.57     10518790.62
      3632668.47     10519221.16
#Sta/Elev= 30
  4125.8  366.84    4246   366.5  4426.2  355.83  4529.4  347.61  4539.2   344.8
  4544.5  345.38  4561.2  342.66  4755.6  341.73  4773.3  340.15  4786.5  337.09
  4836.9  333.97    4843   332.1  4930.5  328.44  4961.4  328.79  4974.8  327.17
  4980.1  322.18    4985  321.51  4990.8  320.07  4991.3  320.07 5010.91  327.13
  5020.6  328.97  5102.2  327.68    5233  333.13    5287  338.92  5314.5  339.98
  5321.8  341.88  5390.3  348.42  5412.1  347.27  5417.8  345.55  5471.2  344.36
#Mann= 3 ,-1 , 0
  4125.8     .16       0    4985     .08       0  4991.3     .16       0
Bank Sta=4974.8,5010.91
XS Rating Curve= 0 ,0
Exp/Cntr=0.3,0.1

Type RM Length L Ch R = 1 ,1495    ,603,603,603
BEGIN DESCRIPTION:
UNNAMED TRIB 1A1 TO BLISS CR 3.0
END DESCRIPTION:
XS GIS Cut Line= 3
      3633199.57     10518510.19      3632599.61     10518460.19
      3632249.62     10518810.18
#Sta/Elev= 30
  4377.8  343.02  4440.5  340.54    4458  338.81  4548.4  335.57  4588.5  332.75
  4648.7  327.28  4681.3  325.43  4688.8  324.21    4729   321.9  4759.1  321.16
  4929.7  322.16  4959.5  320.08    4960  320.08  4962.8  320.58    4994  320.61
  5022.3  321.56  5036.4  322.17  5050.6  320.92  5064.7  321.26  5078.8   320.6
  5135.4  321.09  5149.5  322.54  5163.7  322.23    5192  323.02  5220.3  325.15
  5262.7  326.31  5333.4  332.05  5347.5  332.51  5446.5   342.5  5474.8  344.26
#Mann= 4 ,-1 , 0
  4377.8     .16       0    4960     .08       0  4962.8     .16       0
  5347.5     .05       0
#XS Ineff= 1 ,-1
 4579.43 4921.49 325.349
Permanent Ineff=
       F
Bank Sta=4929.7,5022.3
XS Rating Curve= 0 ,0
Exp/Cntr=0.3,0.1

Type RM Length L Ch R = 1 ,892     ,567,567,567
BEGIN DESCRIPTION:
UNNAMED TRIB 1A1 TO BLISS CR 2.0
END DESCRIPTION:
XS GIS Cut Line= 3
      3633299.64     10517710.18      3632779.57     10517915.62
      3632399.57     10518110.21
#Sta/Elev= 30
  4442.5  352.53  4511.5  346.83  4560.2   339.3  4564.5  340.33  4571.6  338.06
  4603.8  334.09  4712.8  325.63  4811.7  321.23  4836.1   318.6  4919.9  316.96
  4944.3  315.98  5012.9  317.26  5064.7  315.09  5065.2  315.09    5068  315.59
  5102.7  316.39  5109.4  318.52  5125.2  319.15  5131.6  321.81  5137.2  321.06
  5153.8  324.12  5170.2   324.9  5222.9  332.79  5271.3  340.08  5303.6   341.3
  5309.2  339.99  5325.8  341.45  5331.4  339.88  5414.7  344.89  5428.6  344.51
#Mann= 8 ,-1 , 0
  4442.5     .05       0  4564.5     .08       0  4712.8     .05       0
  4811.7     .16       0  5065.2     .07       0    5068     .16       0
  5170.2     .08       0  5222.9     .05       0
Bank Sta=4919.9,5102.7
XS Rating Curve= 0 ,0
Exp/Cntr=0.3,0.1

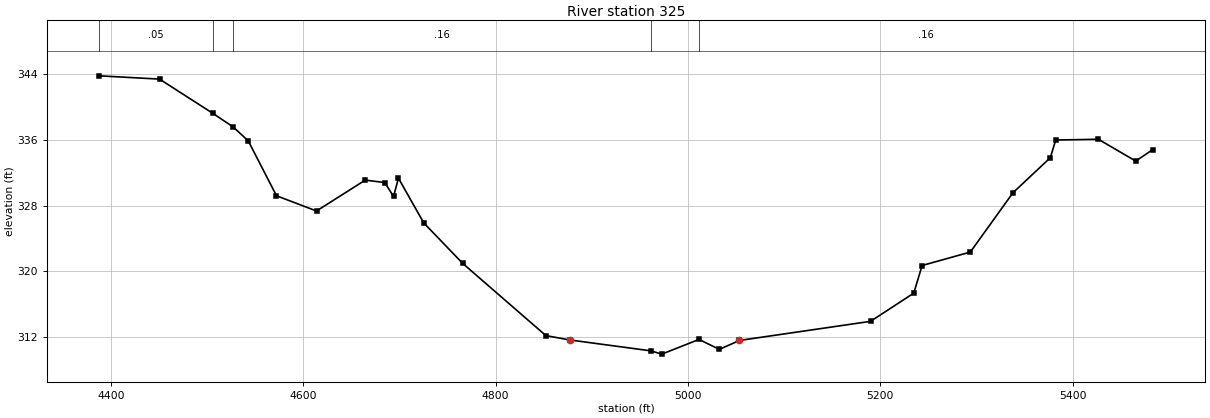
Type RM Length L Ch R = 1 ,325     ,0,0,0
BEGIN DESCRIPTION:
UNNAMED TRIB 1A1 TO BLISS CR 1.0
END DESCRIPTION:
XS GIS Cut Line= 4
      3633182.33     10517214.23      3632724.01     10517290.62
      3632529.57     10517512.84      3632376.81     10517811.41
#Sta/Elev= 30
    4388  343.83  4450.6  343.43  4506.2  339.24  4527.2  337.59  4542.8   335.9
  4572.2   329.2  4613.8  327.34  4664.5  331.11  4684.8  330.81  4693.9  329.11
    4699  331.34  4725.3  325.89  4765.9  320.94  4852.3  312.14  4877.1  311.61
  4961.5  310.28  4972.8  309.88  5011.5  311.67  5032.7  310.46  5053.6  311.55
  5189.9  313.88  5234.8  317.32  5243.5  320.69  5293.6  322.33    5338  329.57
  5376.8  333.84  5382.4     336  5426.8  336.09  5465.6  333.43  5483.3  334.83
#Mann= 5 ,-1 , 0
    4388     .05       0  4506.2     .16       0  4527.2     .16       0
  4961.5     .03       0  5011.5     .16       0
Bank Sta=4877.1,5053.6
XS Rating Curve= 0 ,0
Exp/Cntr=0.3,0.1

Chan Stop Cuts=-1
Use User Specified Reach Order=0
Composite Channel Slope=5