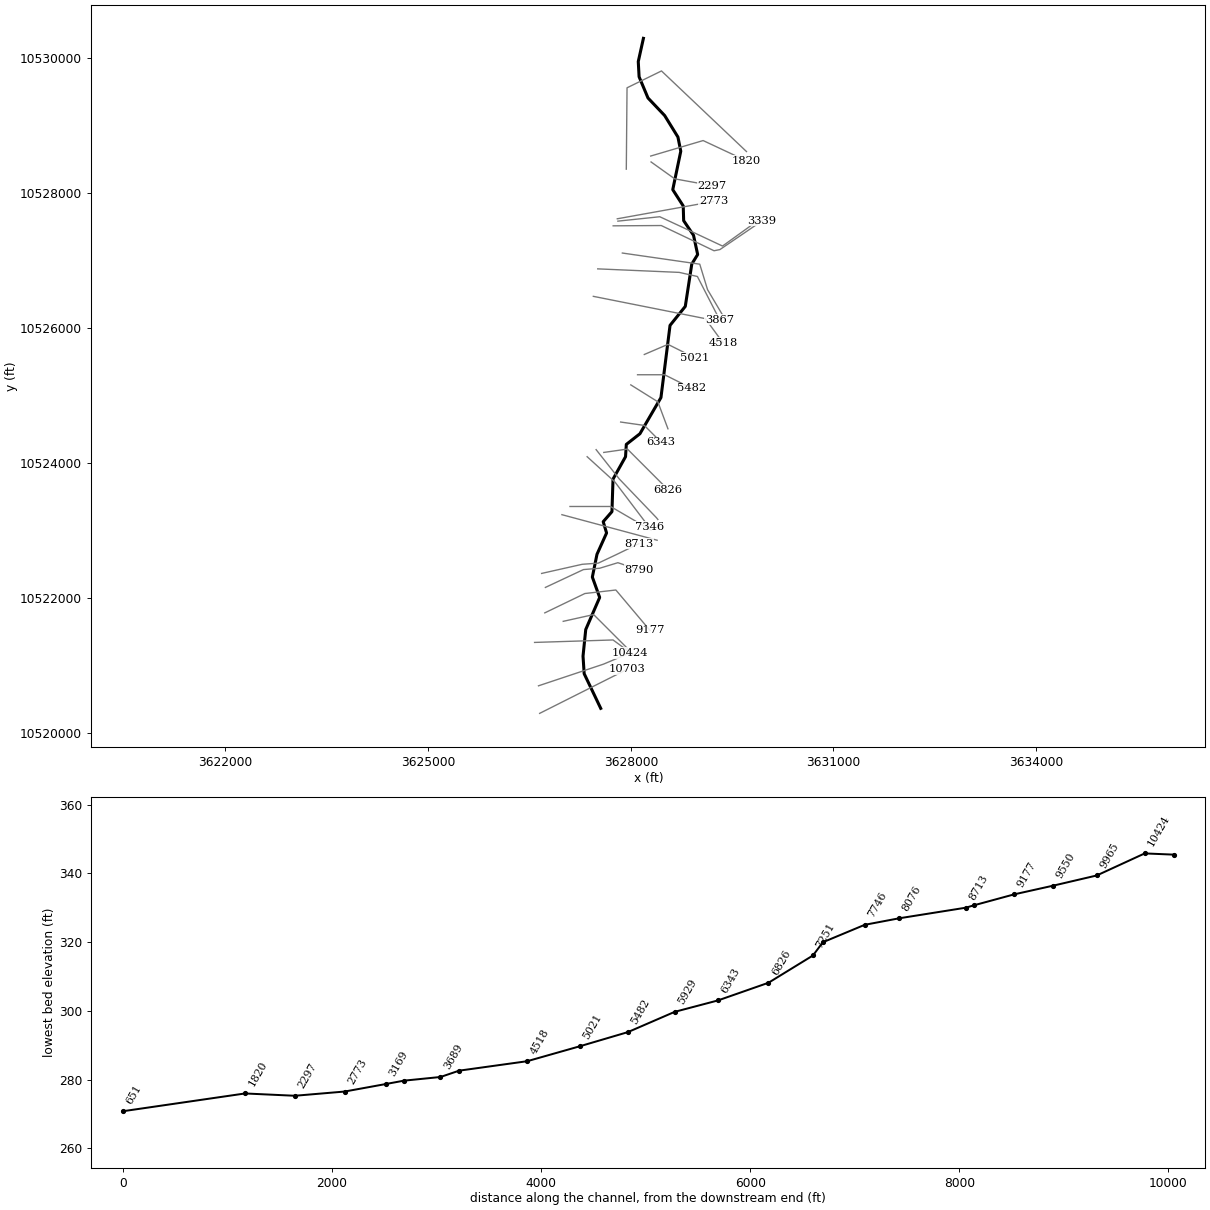
--- UNNAMED TRIB 2 TO BUFFALO CR.prj (project) ---

Proj Title=UNNAMED TRIB 2 TO BUFFALO CR Base Level Engineering
Current Plan=p01
Default Exp/Contr=0.3,0.1
English Units
Geom File=g01
Flow File=f01
Plan File=p01
Y Axis Title=Elevation
X Axis Title(PF)=Main Channel Distance
X Axis Title(XS)=Station
BEGIN DESCRIPTION:
UNNAMED TRIB 2 TO BUFFALO CR
END DESCRIPTION:
DSS Export Rating Curves= 0
DSS Export Rating Curve Sorted= 0
DSS Export Volume Flow Curves= 0
DXF OffsetX= 0
DXF OffsetY= 0
DXF ScaleX= 1
DXF ScaleY= 10

--- UNNAMED TRIB 2 TO BUFFALO CR.p01 (plan) ---

Plan Title=Multiple Run
Short Identifier=Multiple
Geom File=g01
Flow File=f01
Subcritical Flow
K Sum by GR= 0
Std Step Tol= 0.01
Critical Tol= 0.01
Num of Std Step Trials= 20
Max Error Tol= 0.3
Flow Tol Ratio= 0.001
Split Flow NTrial= 30
Split Flow Tol= 0.02
Split Flow Ratio= 0.02
Log Output Level= 0
Friction Slope Method= 1
Unsteady Friction Slope Method= 2
Unsteady Bridges Friction Slope Method= 1
Parabolic Critical Depth
Global Vel Dist=  1 , 1 , 1
Global Log Level= 0
CheckData=True
Encroach Param= -1, 0, 0, 0
BEGIN DESCRIPTION:
Multiple Run
END DESCRIPTION:

--- UNNAMED TRIB 2 TO BUFFALO CR.f01 (steady flow) ---

Flow Title=Multiple
Program Version=4.10
Number of Profiles= 7
Profile Names=10-year,25-year,50-year,1pct_min,100-year,1pct_plu,500-year
River Rch & RM=UNNAMED TRIB 2 T,Reach-1         ,10703
     706     952    1152    1020    1380    1866    1969
River Rch & RM=UNNAMED TRIB 2 T,Reach-1         ,4518
    1070    1481    1823    1640    2218    2999    3269
River Rch & RM=UNNAMED TRIB 2 T,Reach-1         ,3339
    1398    1956    2425    2193    2965    4010    4420
Boundary for River Rch & Prof#=UNNAMED TRIB 2 T,Reach-1         , 1
Up Type= 0
Dn Type= 3
Dn Slope=0.008
Boundary for River Rch & Prof#=UNNAMED TRIB 2 T,Reach-1         , 2
Up Type= 0
Dn Type= 3
Dn Slope=0.008
Boundary for River Rch & Prof#=UNNAMED TRIB 2 T,Reach-1         , 3
Up Type= 0
Dn Type= 3
Dn Slope=0.008
Boundary for River Rch & Prof#=UNNAMED TRIB 2 T,Reach-1         , 4
Up Type= 0
Dn Type= 3
Dn Slope=0.008
Boundary for River Rch & Prof#=UNNAMED TRIB 2 T,Reach-1         , 5
Up Type= 0
Dn Type= 3
Dn Slope=0.008
Boundary for River Rch & Prof#=UNNAMED TRIB 2 T,Reach-1         , 6
Up Type= 0
Dn Type= 3
Dn Slope=0.008
Boundary for River Rch & Prof#=UNNAMED TRIB 2 T,Reach-1         , 7
Up Type= 0
Dn Type= 3
Dn Slope=0.008
DSS Import GetInterval= 0
DSS Import GetPeak= 0
DSS Import FillOption= 0

--- UNNAMED TRIB 2 TO BUFFALO CR.g01 (geometry) ---

Geom Title=Existing Conditions
Program Version=4.10

River Reach=UNNAMED TRIB 2 T,Reach-1
Reach XY= 30
       3627554.5       10520372.       3627309.5       10520885.
       3627292.5       10521145.      3627332.75       10521539.
        3627539.       10522014.       3627430.5       10522315.
        3627499.       10522652.      3627641.25       10522968.
      3627591.25       10523135.      3627720.75       10523284.
       3627736.5       10523765.      3627921.75       10524097.
      3627933.25       10524279.      3628134.75       10524437.
        3628446.       10524972.       3628580.5       10526041.
      3628806.25       10526322.       3628902.5       10526949.
       3628989.5       10527090.        3628928.       10527375.
      3628782.25       10527591.      3628775.75       10527809.
      3628620.75       10528050.       3628739.5       10528619.
      3628697.25       10528829.        3628501.       10529147.
      3628254.25       10529407.       3628122.5       10529721.
      3628110.25       10529946.       3628186.5       10530290.

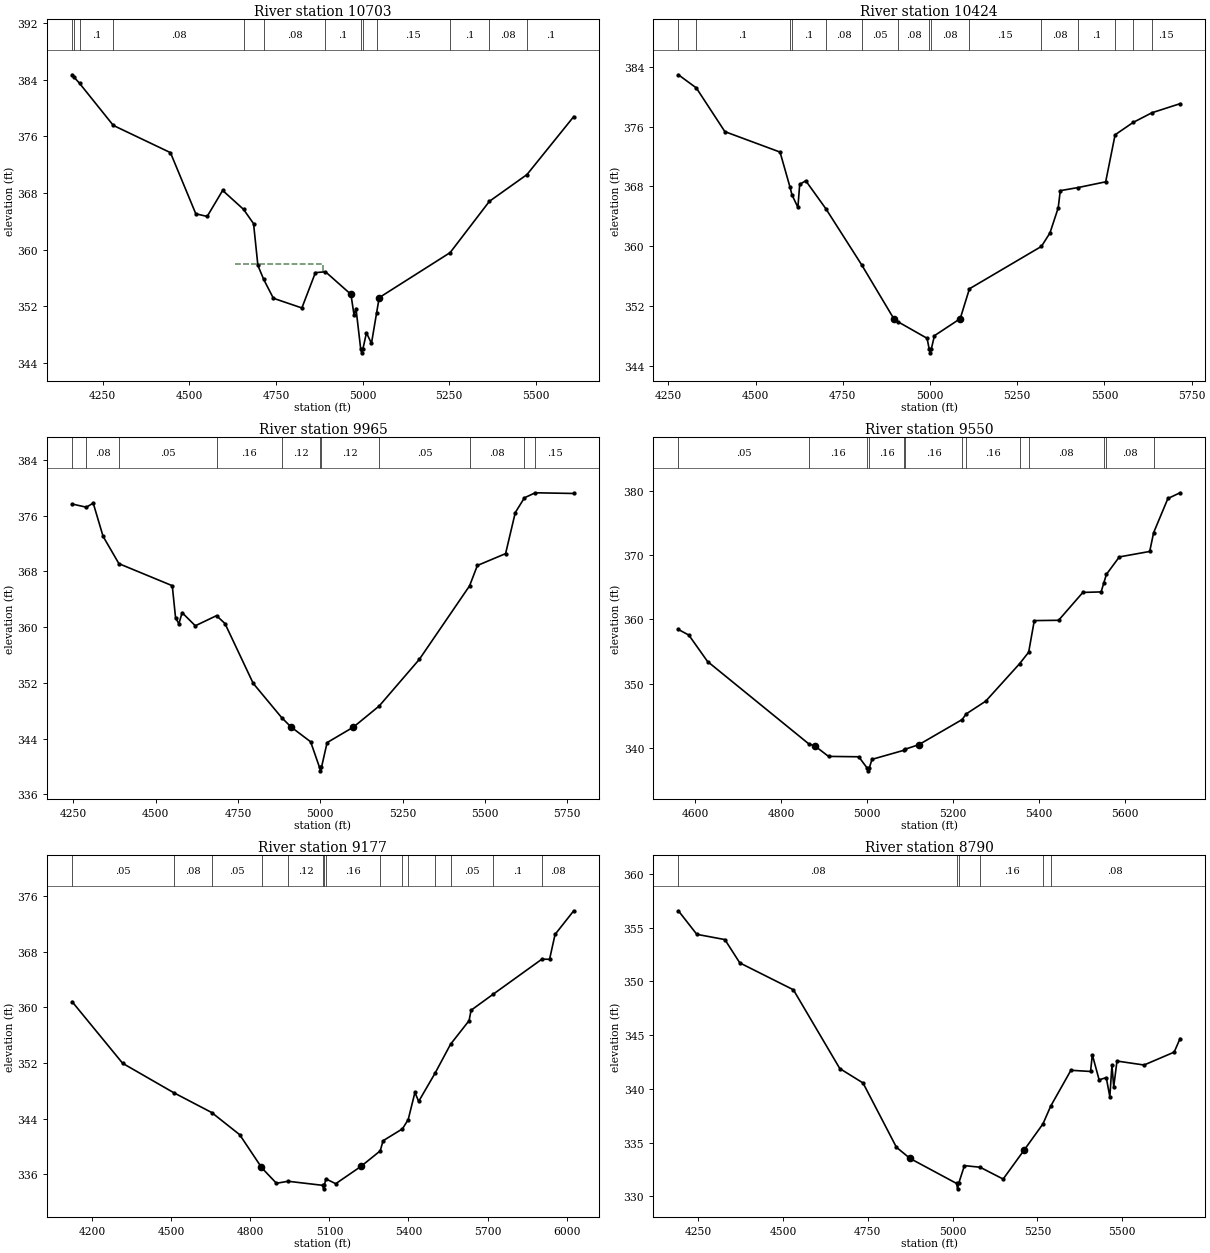
Type RM Length L Ch R = 1 ,10703   ,279,279,279
BEGIN DESCRIPTION:
UNNAMED TRIB 2 TO BUFFALO CR 22.0
END DESCRIPTION:
XS GIS Cut Line= 2
      3626650.52     10520297.67        3627944.     10520948.75
#Sta/Elev= 30
  4161.3  384.71  4166.5  384.41  4183.1  383.49  4280.3  377.56  4445.3  373.71
  4518.5  365.07  4551.3   364.7    4596  368.37  4656.3   365.7  4685.2  363.68
  4697.7  357.78  4714.5   355.8  4742.4  353.14  4824.7  351.77  4863.7  356.76
  4892.8  356.88  4966.3  353.69  4975.3  350.76  4980.9  351.69  4994.6  345.93
  4997.4  345.43  5000.6  345.93  5011.1  348.25  5025.6  346.77  5040.2  351.02
  5047.9  353.23  5252.7  359.59  5365.9  366.83  5474.4  370.61  5609.4   378.8
#Mann= 13 ,-1 , 0
  4161.3      .1       0  4166.5     .08       0  4183.1      .1       0
  4280.3     .08       0  4656.3      .1       0  4714.5     .08       0
  4892.8      .1       0  4994.6     .07       0  5000.6      .1       0
  5040.2     .15       0  5252.7      .1       0  5365.9     .08       0
  5474.4      .1       0
#XS Ineff= 1 ,-1
 4632.05  4886.7  357.96
Permanent Ineff=
       F
Bank Sta=4966.3,5047.9
XS Rating Curve= 0 ,0
Exp/Cntr=0.3,0.1

Type RM Length L Ch R = 1 ,10424   ,459,459,459
BEGIN DESCRIPTION:
UNNAMED TRIB 2 TO BUFFALO CR 21.0
END DESCRIPTION:
XS GIS Cut Line= 3
      3626633.18     10520705.67      3627596.74     10521026.86
      3627985.98      10521191.2
#Sta/Elev= 30
  4278.6  382.91  4329.9  381.16  4411.9  375.32    4570  372.59  4598.6  367.91
  4604.3  366.87  4621.2  365.22  4626.4  368.28  4643.8  368.76  4701.5  365.02
  4804.4  357.51  4896.8   350.3  4907.3  349.96  4991.6  347.73  4997.6  346.29
  5000.4  345.79  5003.6  346.29  5012.7  348.08  5086.5  350.35    5113  354.34
  5319.4     360  5343.8  361.79  5367.5  365.14  5373.4  367.44    5425  367.86
  5503.6  368.62  5530.6   374.9  5582.4  376.55  5636.2  377.84  5716.8  379.05
#Mann= 15 ,-1 , 0
  4278.6     .08       0  4329.9      .1       0  4598.6     .08       0
  4604.3      .1       0  4701.5     .08       0  4804.4     .05       0
  4907.3     .08       0  4997.6     .07       0  5003.6     .08       0
    5113     .15       0  5319.4     .08       0    5425      .1       0
  5530.6     .15       0  5582.4      .1       0  5636.2     .15       0
Bank Sta=4896.8,5086.5
XS Rating Curve= 0 ,0
Exp/Cntr=0.3,0.1

Type RM Length L Ch R = 1 ,9965    ,415,415,415
BEGIN DESCRIPTION:
UNNAMED TRIB 2 TO BUFFALO CR 20.0
END DESCRIPTION:
XS GIS Cut Line= 3
      3626575.48     10521347.91      3627736.96     10521384.37
       3628028.6     10521170.85
#Sta/Elev= 30
  4246.1  377.65  4289.6  377.19  4310.3  377.78  4340.3  373.01  4388.4  369.09
  4550.4  365.93  4560.4  361.34  4570.4  360.46  4580.4  362.06  4620.4  360.18
  4684.8  361.63  4710.5   360.5  4796.2  351.92  4882.4  347.02  4910.6  345.68
  4970.6  343.54  4997.6  339.87  5000.4  339.37  5003.6  339.87  5020.6  343.42
  5100.7  345.65  5178.8  348.67  5300.7  355.36  5453.3  365.91    5477  368.83
  5562.7  370.53  5592.1  376.42  5619.9  378.54  5652.8  379.26  5769.6  379.16
#Mann= 11 ,-1 , 0
  4246.1     .15       0  4289.6     .08       0  4388.4     .05       0
  4684.8     .16       0  4882.4     .12       0  4997.6     .07       0
  5003.6     .12       0  5178.8     .05       0  5453.3     .08       0
  5619.9      .1       0  5652.8     .15       0
Bank Sta=4910.6,5100.7
XS Rating Curve= 0 ,0
Exp/Cntr=0.3,0.1

Type RM Length L Ch R = 1 ,9550    ,373,373,373
BEGIN DESCRIPTION:
UNNAMED TRIB 2 TO BUFFALO CR 19.0
END DESCRIPTION:
XS GIS Cut Line= 3
      3626999.57     10521660.18      3627449.61     10521760.19
      3627949.59      10521260.2
#Sta/Elev= 30
  4561.1  358.44  4585.5  357.56    4629  353.45  4865.1   340.6  4878.7  340.31
  4910.7  338.67  4981.1  338.61  4999.9  336.92  5002.7  336.42  5005.9  336.92
  5011.9  338.21  5085.6  339.61  5088.4  339.77  5121.1   340.5  5221.9  344.41
  5231.1  345.28  5276.7  347.27  5355.5   353.1  5376.7   354.9  5389.8  359.82
  5446.4  359.87  5502.9  364.21  5545.4  364.29  5551.7  365.69  5557.7  367.02
  5587.8  369.74  5658.5  370.59  5667.7  373.52  5700.9  378.84  5729.2  379.73
#Mann= 13 ,-1 , 0
  4561.1     .05       0  4865.1     .16       0  4999.9     .07       0
  5005.9     .16       0  5085.6     .07       0  5088.4     .16       0
  5221.9     .05       0  5231.1     .16       0  5355.5     .05       0
  5376.7     .08       0  5551.7     .05       0  5557.7     .08       0
  5667.7      .1       0
Bank Sta=4878.7,5121.1
XS Rating Curve= 0 ,0
Exp/Cntr=0.3,0.1

Type RM Length L Ch R = 1 ,9177    ,387,387,387
BEGIN DESCRIPTION:
UNNAMED TRIB 2 TO BUFFALO CR 18.0
END DESCRIPTION:
XS GIS Cut Line= 4
      3626726.57     10521785.42       3627320.3     10522071.87
      3627778.63     10522123.95      3628283.73     10521525.12
#Sta/Elev= 30
  4123.3  360.83  4315.4  351.95  4508.8  347.73  4653.2  344.87  4759.5  341.68
  4842.2  336.98    4844  336.88    4899  334.69  4943.1  334.98  5075.2  334.39
  5077.9  333.89  5081.2  334.39  5086.1  335.33    5124  334.63 5220.17  337.13
  5292.8  339.35  5303.6  340.81  5377.1  342.52    5399  343.85  5424.5  347.76
  5438.8  346.47  5501.4  350.56  5559.8   354.7    5630  358.09  5637.7  359.59
  5720.6  361.87  5906.5  366.94  5935.5  366.92  5956.4   370.5  6027.2   373.9
#Mann= 15 ,-1 , 0
  4123.3     .05       0  4508.8     .08       0  4653.2     .05       0
    4844     .16       0  4943.1     .12       0  5075.2     .07       0
  5081.2     .12       0  5086.1     .16       0  5292.8     .05       0
  5377.1     .16       0    5399     .05       0  5501.4     .16       0
  5559.8     .05       0  5720.6      .1       0  5906.5     .08       0
Bank Sta=4842.2,5220.17
XS Rating Curve= 0 ,0
Exp/Cntr=0.3,0.1

Type RM Length L Ch R = 1 ,8790    ,77,77,77
BEGIN DESCRIPTION:
UNNAMED TRIB 2 TO BUFFALO CR 17.0
END DESCRIPTION:
XS GIS Cut Line= 5
      3626735.51     10522162.14      3627299.32     10522426.47
       3627538.9       10522446.      3627808.43     10522528.03
        3628126.     10522421.74
#Sta/Elev= 30
  4191.1  356.56  4245.4  354.37  4328.2  353.88  4372.3  351.71  4530.3  349.21
  4667.2  341.88  4735.7  340.54  4834.2  334.56  4874.3  333.52  5011.8  331.19
  5014.5  330.69  5017.8  331.19  5034.8  332.85    5081   332.7    5149   331.6
  5211.7  334.33  5266.4  336.73  5289.2  338.38  5348.9  341.72  5406.8  341.61
  5412.1  343.16  5432.1  340.83  5453.2  341.04  5463.7  339.25  5469.9  342.17
  5475.2  340.19  5484.8  342.58  5564.6  342.21  5653.5  343.41  5670.8  344.67
#Mann= 6 ,-1 , 0
  4191.1     .08       0  5011.8     .07       0  5017.8     .08       0
    5081     .16       0  5266.4     .05       0  5289.2     .08       0
Bank Sta=4874.3,5211.7
XS Rating Curve= 0 ,0
Exp/Cntr=0.3,0.1

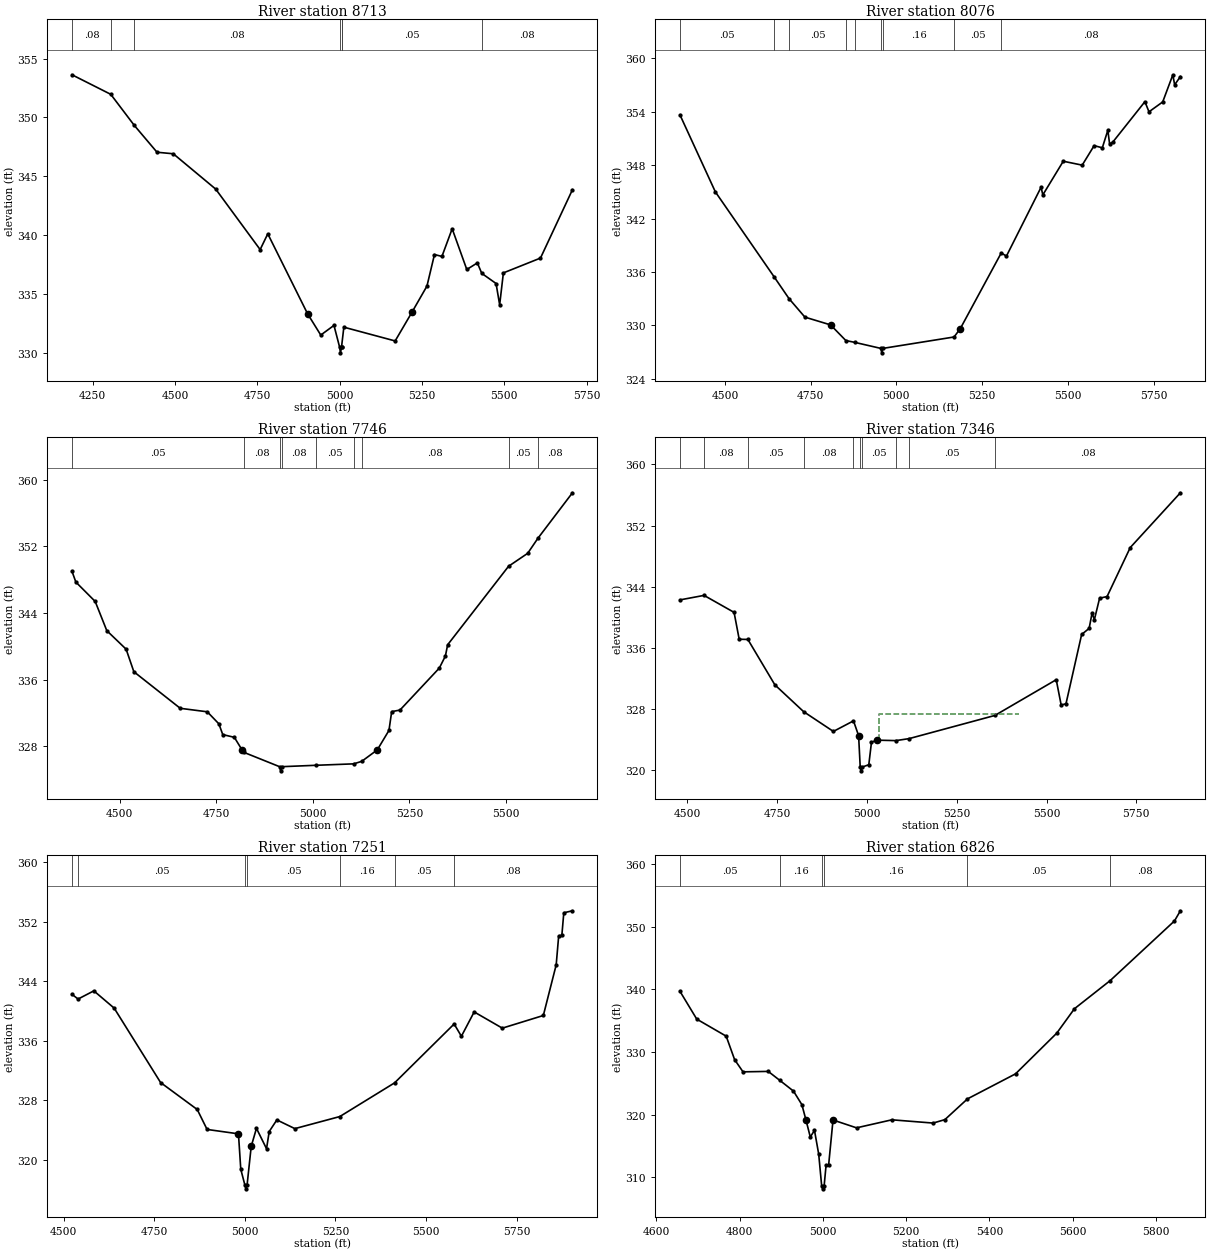
Type RM Length L Ch R = 1 ,8713    ,637,637,637
BEGIN DESCRIPTION:
Mapping XS ea66c954
END DESCRIPTION:
XS GIS Cut Line= 5
      3626679.55     10522369.18      3627281.09     10522504.59
      3627518.07     10522521.52      3627779.79     10522645.22
      3628118.37      10522809.3
#Sta/Elev= 30
    4187  353.62  4304.7  351.96  4376.2  349.32  4445.2  347.04  4494.6  346.91
  4623.4  343.91  4758.4  338.77  4781.6  340.11  4902.4  333.32  4942.5  331.51
  4982.6  332.33  4999.6   330.5  5002.4     330  5005.6   330.5  5005.7  330.52
  5012.6  332.18  5168.4  331.01  5219.9  333.47    5265  335.67  5287.8  338.35
  5310.5  338.19  5341.6  340.54    5386  337.08  5418.1  337.64  5431.5  336.75
  5474.9  335.89  5485.8  334.08  5497.1  336.79  5609.8  338.05  5706.9  343.86
#Mann= 7 ,-1 , 0
    4187     .08       0  4304.7     .05       0  4376.2     .08       0
  4999.6     .07       0  5005.6     .08       0  5005.7     .05       0
  5431.5     .08       0
Bank Sta=4902.4,5219.9
XS Rating Curve= 0 ,0
Exp/Cntr=0.3,0.1

Type RM Length L Ch R = 1 ,8076    ,330,330,330
BEGIN DESCRIPTION:
UNNAMED TRIB 2 TO BUFFALO CR 16.0
END DESCRIPTION:
XS GIS Cut Line= 2
      3626979.88     10523238.96      3628389.57      10522860.5
#Sta/Elev= 30
  4368.8  353.65  4472.1     345  4643.4  335.46  4687.1     333  4733.3  330.93
  4808.1  330.06  4852.7   328.3  4878.2   328.1  4954.7  327.42  4957.4  326.92
  4960.7  327.42  5168.3   328.7  5186.5  329.64  5305.8  338.13  5321.1  337.79
  5422.1  345.52  5427.2  344.66  5486.8  348.44    5542     348  5576.8  350.19
  5600.7  349.95  5616.8  351.92    5622  350.36  5631.7  350.61  5724.9  355.13
  5736.8  353.99  5776.8   355.1  5806.4  358.15  5811.6  357.02  5828.4  357.95
#Mann= 9 ,-1 , 0
  4368.8     .05       0  4643.4     .08       0  4687.1     .05       0
  4852.7     .08       0  4878.2     .16       0  4954.7     .07       0
  4960.7     .16       0  5168.3     .05       0  5305.8     .08       0
Bank Sta=4808.1,5186.5
XS Rating Curve= 0 ,0
Exp/Cntr=0.3,0.1

Type RM Length L Ch R = 1 ,7746    ,400,400,400
BEGIN DESCRIPTION:
UNNAMED TRIB 2 TO BUFFALO CR 15.0
END DESCRIPTION:
XS GIS Cut Line= 3
      3627099.56     10523360.19      3627699.61     10523360.19
      3628299.64     10523010.17
#Sta/Elev= 30
  4377.1  349.01  4387.1  347.72  4437.1  345.39  4467.1  341.88  4517.1  339.65
  4537.1  336.94  4657.1  332.54  4727.1  332.12  4757.1  330.67  4767.1  329.38
  4797.1  329.05  4817.1  327.53  4821.4  327.25  4914.1  325.52  4916.9  325.02
  4920.1  325.52  5009.4  325.69  5105.8  325.86  5126.6  326.16  5166.9  327.54
  5197.1  329.88  5204.1  332.14  5225.6  332.33  5327.4  337.38  5343.1  338.83
  5348.9  340.18  5506.5  349.62    5556  351.18  5582.3  352.98  5671.8  358.46
#Mann= 9 ,-1 , 0
  4377.1     .05       0  4821.4     .08       0  4914.1     .07       0
  4920.1     .08       0  5009.4     .05       0  5105.8     .16       0
  5126.6     .08       0  5506.5     .05       0  5582.3     .08       0
Bank Sta=4817.1,5166.9
XS Rating Curve= 0 ,0
Exp/Cntr=0.3,0.1

Type RM Length L Ch R = 1 ,7346    ,95,95,95
BEGIN DESCRIPTION:
UNNAMED TRIB 2 TO BUFFALO CR 14.0
END DESCRIPTION:
XS GIS Cut Line= 4
      3627353.58     10524097.03      3627676.49     10523803.03
      3627765.03      10523722.3      3628270.24     10523055.63
#Sta/Elev= 30
  4479.6  342.29  4546.7  342.88  4630.3  340.66  4644.5  337.15  4668.7  337.12
  4743.8  331.19    4824  327.68  4906.7   325.1  4962.7  326.48  4976.9  324.55
  4981.4  320.45  4984.1  319.95  4987.4  320.45  5005.3  320.75  5012.7  323.68
  5026.9  323.96  5080.4   323.9  5117.4  324.16  5356.3  327.19    5527  331.86
  5540.7  328.56  5554.1  328.71  5597.7  337.77  5618.6  338.57  5626.8  340.58
  5633.1  339.69  5647.7  342.51  5668.5  342.73    5733  349.13  5872.6  356.29
#Mann= 10 ,-1 , 0
  4479.6     .05       0  4546.7     .08       0  4668.7     .05       0
    4824     .08       0  4962.7     .05       0  4981.4     .04       0
  4987.4     .05       0  5080.4     .08       0  5117.4     .05       0
  5356.3     .08       0
#XS Ineff= 1 ,-1
 5033.64 5424.55  327.33
Permanent Ineff=
       F
Bank Sta=4976.9,5026.9
XS Rating Curve= 0 ,0
Exp/Cntr=0.3,0.1

Type RM Length L Ch R = 1 ,7251    ,425,425,425
BEGIN DESCRIPTION:
Mapping XS 937c5fcc
END DESCRIPTION:
XS GIS Cut Line= 4
      3627486.37     10524201.48      3627830.13     10523766.57
      3628379.61     10523193.65      3628400.42     10523167.65
#Sta/Elev= 30
  4522.9  342.24  4539.6   341.6  4583.2   342.7  4639.3  340.38  4767.5  330.38
  4868.6  326.76  4895.8  324.08  4982.4  323.49  4988.8  318.73  5000.2   316.6
    5003   316.1  5006.2   316.6  5017.6   321.8  5032.1  324.23  5059.9  321.49
  5067.3   323.8  5088.4  325.36  5138.1  324.19  5262.1  325.81  5413.4  330.34
  5577.8  338.25  5597.8   336.6  5633.1  339.87  5710.8  337.69    5824  339.39
  5859.5  346.19  5866.4   350.1  5875.1  350.14  5880.5  353.19  5904.4  353.46
#Mann= 7 ,-1 , 0
  4522.9     .08       0  4539.6     .05       0  5000.2     .04       0
  5006.2     .05       0  5262.1     .16       0  5413.4     .05       0
  5577.8     .08       0
Bank Sta=4982.4,5017.6
XS Rating Curve= 0 ,0
Exp/Cntr=0.3,0.1

Type RM Length L Ch R = 1 ,6826    ,483,483,483
BEGIN DESCRIPTION:
UNNAMED TRIB 2 TO BUFFALO CR 13.0
END DESCRIPTION:
XS GIS Cut Line= 3
      3627599.63     10524160.19      3627949.61     10524210.19
      3628549.64     10523610.16
#Sta/Elev= 30
  4656.7  339.68  4697.1  335.24  4767.8  332.52    4788  328.78  4808.2  326.83
  4868.8   326.9    4896   325.5  4929.4  323.76  4949.6   321.6  4959.7  319.08
  4969.8  316.44  4979.9  317.49    4990  313.71  4997.1  308.67  4999.9  308.17
  5003.1  308.67  5007.7  311.92  5013.8  311.92  5024.4  319.15  5080.9   317.9
  5165.8  319.18  5264.8  318.66  5293.1  319.21  5347.4  322.52  5462.8  326.51
  5561.8     333  5604.2  336.89  5689.9  341.37  5844.6   350.9  5858.8  352.52
#Mann= 6 ,-1 , 0
  4656.7     .05       0    4896     .16       0  4997.1     .07       0
  5003.1     .16       0  5347.4     .05       0  5689.9     .08       0
Bank Sta=4959.7,5024.4
XS Rating Curve= 0 ,0
Exp/Cntr=0.3,0.1

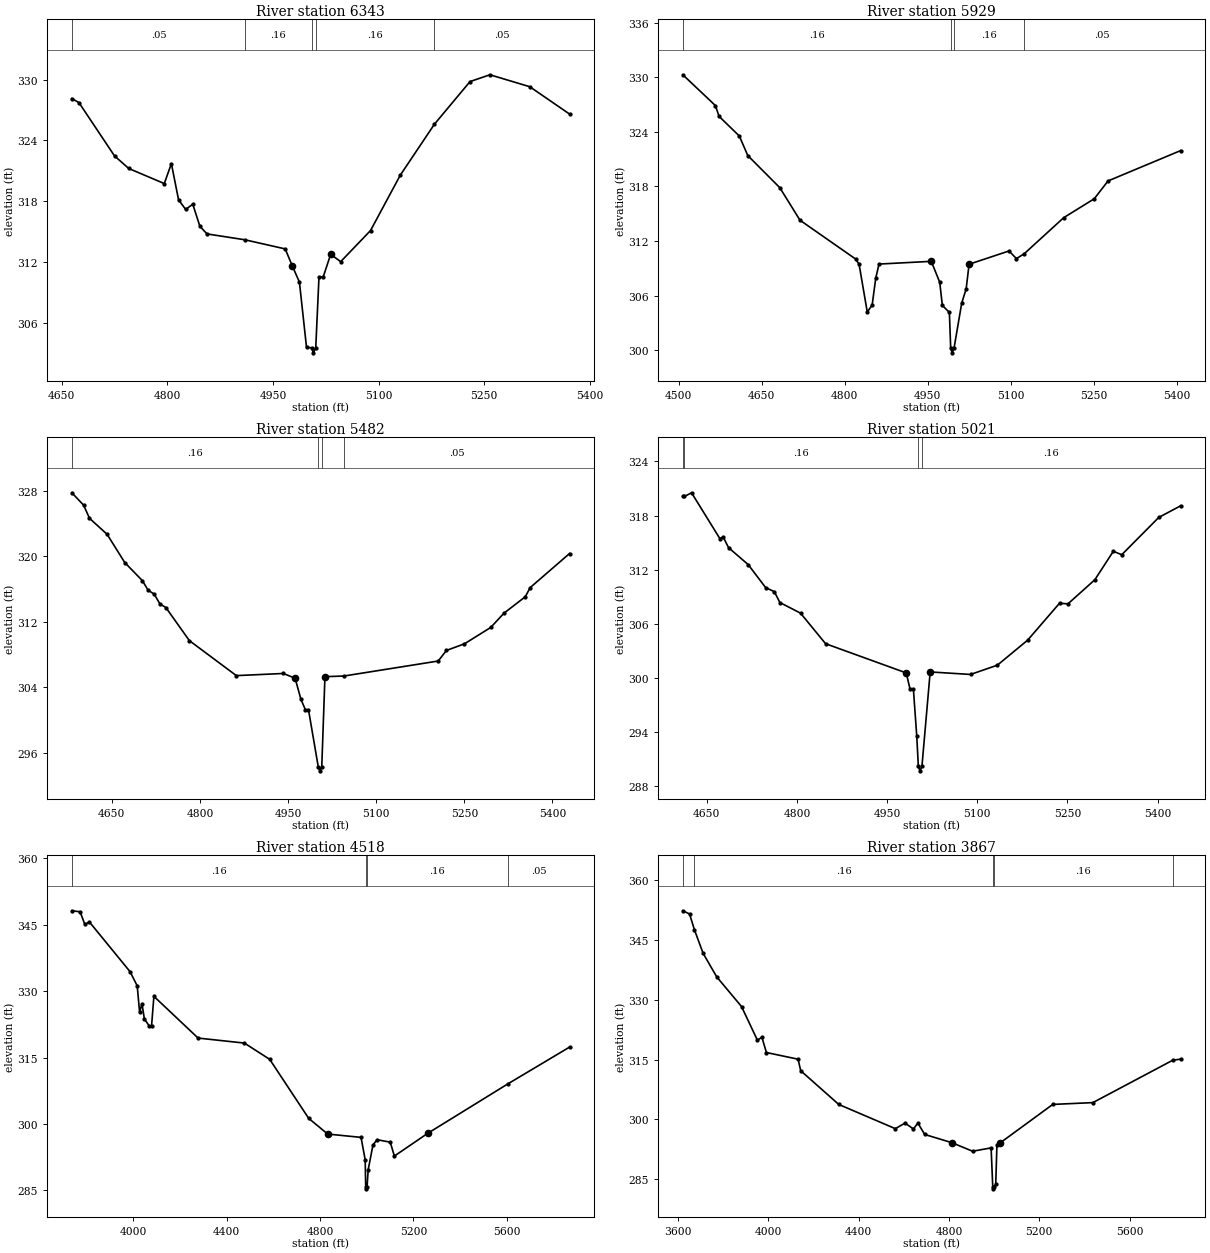
Type RM Length L Ch R = 1 ,6343    ,414,414,414
BEGIN DESCRIPTION:
UNNAMED TRIB 2 TO BUFFALO CR 12.0
END DESCRIPTION:
XS GIS Cut Line= 3
      3627849.58     10524610.19      3628199.61     10524560.19
      3628449.58     10524310.21
#Sta/Elev= 30
  4664.2  328.13  4674.3  327.73  4724.8  322.47    4745  321.23  4795.5  319.74
  4805.6  321.71  4815.8  318.13  4825.9  317.19    4836   317.7  4846.1  315.52
  4856.2  314.77  4910.1  314.19  4967.3  313.29  4977.4  311.61  4987.5  310.01
  4997.6  303.56  5004.7  303.53  5007.4  303.03  5010.7  303.53  5015.3  310.52
  5021.3  310.52  5031.9  312.76  5046.1  312.03  5088.5   315.1  5130.9  320.58
  5179.4  325.61  5229.9  329.81  5258.2  330.48  5314.8   329.3  5371.3   326.6
#Mann= 5 ,-1 , 0
  4664.2     .05       0  4910.1     .16       0  5004.7     .07       0
  5010.7     .16       0  5179.4     .05       0
Bank Sta=4977.4,5031.9
XS Rating Curve= 0 ,0
Exp/Cntr=0.3,0.1

Type RM Length L Ch R = 1 ,5929    ,447,447,447
BEGIN DESCRIPTION:
UNNAMED TRIB 2 TO BUFFALO CR 11.0
END DESCRIPTION:
XS GIS Cut Line= 3
      3627999.65     10525160.16      3628399.61     10524910.19
      3628549.63     10524510.14
#Sta/Elev= 30
  4507.6  330.28  4566.5  326.89    4573  325.71  4609.6  323.55  4624.9   321.4
  4682.7  317.87  4719.2  314.29  4819.5  310.03  4825.9  309.46  4840.7   304.2
  4849.5  304.95    4856  307.91  4861.9  309.47  4956.3  309.77  4971.6  307.47
  4976.3  304.93    4989  304.15  4991.4  300.21  4994.1  299.71  4997.4  300.21
  5011.3  305.18  5019.3  306.73  5024.6  309.45  5096.7  310.91  5110.1  310.07
  5124.1   310.6  5195.5  314.57  5250.7  316.65  5275.6  318.61  5406.5  321.94
#Mann= 4 ,-1 , 0
  4507.6     .16       0  4991.4     .07       0  4997.4     .16       0
  5124.1     .05       0
Bank Sta=4956.3,5024.6
XS Rating Curve= 0 ,0
Exp/Cntr=0.3,0.1

Type RM Length L Ch R = 1 ,5482    ,461,461,461
BEGIN DESCRIPTION:
UNNAMED TRIB 2 TO BUFFALO CR 10.0
END DESCRIPTION:
XS GIS Cut Line= 3
      3628099.59     10525310.19      3628499.61     10525310.19
      3628899.58      10525110.2
#Sta/Elev= 30
  4581.9  327.75  4601.9  326.24  4611.9  324.64  4641.9  322.68  4671.9  319.24
  4701.9  317.03  4711.9  315.84  4721.9   315.4  4731.9  314.18  4741.9  313.75
  4781.9  309.71  4861.9  305.44  4941.9   305.7  4961.9  305.12  4971.9  302.53
  4979.4  301.28  4984.7  301.28  5001.3  294.32    5004  293.82  5007.3  294.32
  5012.7  305.31  5045.1  305.39  5205.5  307.22  5219.5  308.51  5250.2  309.32
    5295  311.32  5317.3  313.05  5353.7  315.06  5362.1  316.18  5429.1  320.34
#Mann= 4 ,-1 , 0
  4581.9     .16       0  5001.3     .07       0  5007.3     .16       0
  5045.1     .05       0
Bank Sta=4961.9,5012.7
XS Rating Curve= 0 ,0
Exp/Cntr=0.3,0.1

Type RM Length L Ch R = 1 ,5021    ,503,503,503
BEGIN DESCRIPTION:
UNNAMED TRIB 2 TO BUFFALO CR 9.0
END DESCRIPTION:
XS GIS Cut Line= 3
      3628199.62     10525610.19      3628549.61     10525760.19
      3628949.62     10525560.18
#Sta/Elev= 30
  4610.1  320.12  4612.7  320.12  4624.6  320.53  4671.7  315.45  4677.2  315.63
  4686.2  314.44  4718.9  312.56  4747.9  310.01  4762.4  309.56  4771.5  308.36
  4805.9  307.18  4847.6  303.79  4981.8  300.55  4988.2  298.72  4993.7  298.72
  4999.3  293.51  5001.9  290.19  5004.6  289.69  5007.9  290.19  5021.6  300.66
  5088.7  300.38  5133.4  301.41  5183.7  304.18  5236.8  308.28  5250.8  308.21
  5295.5  310.88  5326.3  314.04  5340.3  313.66  5401.8  317.79  5438.1  319.08
#Mann= 4 ,-1 , 0
  4610.1     .05       0  4612.7     .16       0  5001.9     .07       0
  5007.9     .16       0
Bank Sta=4981.8,5021.6
XS Rating Curve= 0 ,0
Exp/Cntr=0.3,0.1

Type RM Length L Ch R = 1 ,4518    ,651,651,651
BEGIN DESCRIPTION:
UNNAMED TRIB 2 TO BUFFALO CR 8.0
END DESCRIPTION:
XS GIS Cut Line= 3
      3627445.04     10526470.79      3629103.07     10526140.92
      3629363.41     10525785.12
#Sta/Elev= 30
  3737.2  348.13  3772.4  347.91  3792.8  345.05  3812.6  345.59  3986.6  334.37
  4017.1  331.17  4027.3  325.22  4037.5  327.16  4047.7  323.71  4068.1  322.16
  4078.4  322.08  4088.5  328.81  4277.8  319.39    4476  318.26  4584.4  314.59
  4751.3  301.27  4832.8  297.72  4975.6  296.97  4993.4  291.89  4995.5  285.85
  4998.2  285.35  5001.5  285.85  5006.2  289.66  5026.6  295.24  5044.5  296.44
  5100.7  295.89  5118.3  292.75  5261.1  297.88  5603.8  309.03  5868.6  317.35
#Mann= 4 ,-1 , 0
  3737.2     .16       0  4995.5     .07       0  5001.5     .16       0
  5603.8     .05       0
Bank Sta=4832.8,5261.1
XS Rating Curve= 0 ,0
Exp/Cntr=0.3,0.1

Type RM Length L Ch R = 1 ,3867    ,178,178,178
BEGIN DESCRIPTION:
UNNAMED TRIB 2 TO BUFFALO CR 7.0
END DESCRIPTION:
XS GIS Cut Line= 4
      3627509.97     10526877.55      3628716.53     10526825.47
      3628985.63     10526764.71      3629314.32     10526124.63
#Sta/Elev= 30
  3622.3  352.26    3652  351.46  3673.8  347.47    3712  341.61  3772.1  335.72
  3882.2  328.26  3952.2  319.86  3972.3  320.56  3992.3  316.75  4132.4  315.08
  4144.1  312.19  4312.6  303.74  4562.8  297.68  4606.2  299.07  4642.9   297.6
  4662.9  299.08  4692.9  296.22    4813  294.17  4904.9  292.02  4986.9  292.86
  4994.2   283.1  4996.9   282.6  5000.2   283.1  5007.4  283.77  5012.7  293.67
  5027.9  294.15  5259.8  303.75  5437.3   304.2  5790.9  314.82  5825.4  315.09
#Mann= 5 ,-1 , 0
  3622.3     .05       0  3673.8     .16       0  4994.2     .07       0
  5000.2     .16       0  5790.9     .12       0
Bank Sta=4813,5027.9
XS Rating Curve= 0 ,0
Exp/Cntr=0.3,0.1

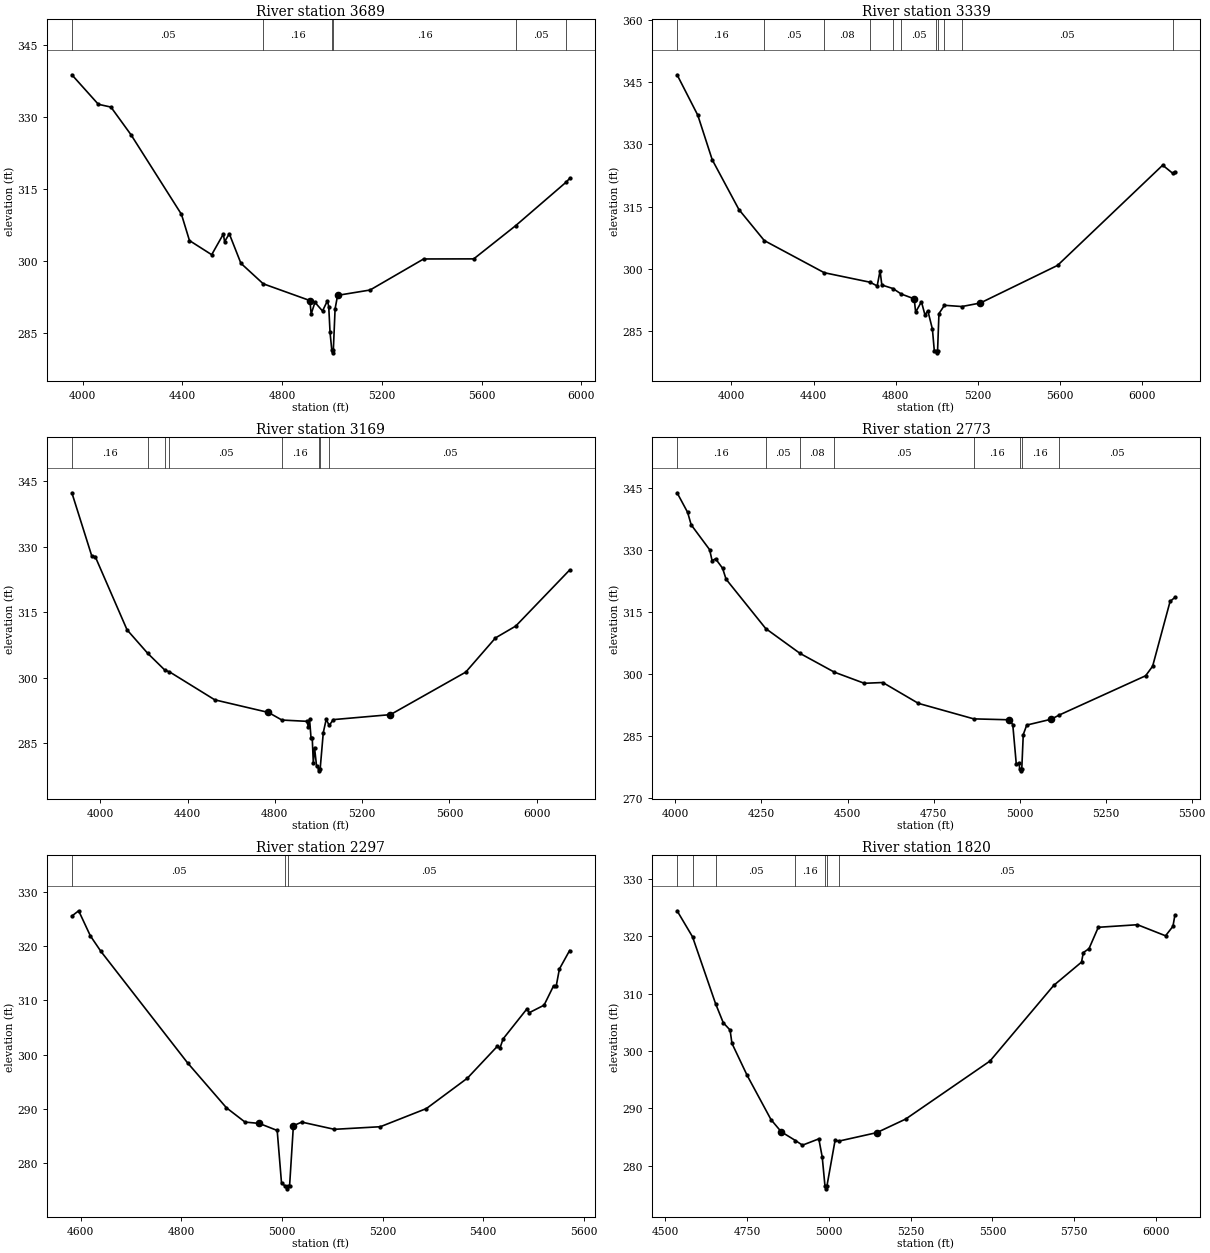
Type RM Length L Ch R = 1 ,3689    ,350,350,350
BEGIN DESCRIPTION:
UNNAMED TRIB 2 TO BUFFALO CR 6.0
END DESCRIPTION:
XS GIS Cut Line= 4
      3627874.53     10527111.93      3629020.35       10526947.
      3629135.73     10526570.21      3629362.28     10526187.41
#Sta/Elev= 30
  3956.5  338.79  4062.7  332.63  4113.2  332.05    4194  326.25  4396.1  309.66
  4428.2  304.19  4517.3  301.24    4564  305.54  4569.1  303.97    4588   305.6
  4634.5  299.45    4724  295.17  4911.3  291.67  4916.3  288.87  4931.5   291.3
  4961.8  289.49  4981.7  291.63  4986.8  290.42  4992.1  285.01  4999.2  281.26
    5002  280.76  5005.2  281.26  5012.3  289.94  5022.4  292.76  5152.6  293.87
  5367.4  300.35  5568.5  300.37  5736.3  307.29  5937.4  316.31    5953  317.15
#Mann= 6 ,-1 , 0
  3956.5     .05       0    4724     .16       0  4999.2     .07       0
  5005.2     .16       0  5736.3     .05       0  5937.4     .12       0
Bank Sta=4911.3,5022.4
XS Rating Curve= 0 ,0
Exp/Cntr=0.3,0.1

Type RM Length L Ch R = 1 ,3339    ,170,170,170
BEGIN DESCRIPTION:
Mapping XS 7fccc0c7
END DESCRIPTION:
XS GIS Cut Line= 6
      3627738.75     10527514.62      3628450.58     10527518.96
      3629006.13      10527254.2      3629231.83     10527145.69
      3629318.63     10527163.05      3629943.62      10527588.4
#Sta/Elev= 30
  3735.4  346.83  3836.3  337.05  3906.3  326.32  4036.3  314.29  4159.7   306.8
  4451.4  299.04  4674.6  296.74  4709.1  295.84  4723.1   299.5  4731.8  296.07
  4786.2  295.21  4825.7   293.9  4889.3  292.73  4896.2  289.52  4924.5  292.02
  4941.6  288.84  4955.7  289.84  4977.9  285.41    4987  280.23    4997  280.19
  4999.8  279.69    5003  280.19  5009.7  289.17  5036.5  291.17  5121.2  290.87
  5210.8  291.72  5586.7   300.8  6098.4     325  6147.1  323.05  6157.6  323.43
#Mann= 11 ,-1 , 0
  3735.4     .16       0  4159.7     .05       0  4451.4     .08       0
  4674.6     .05       0  4786.2     .16       0  4825.7     .05       0
    4997     .04       0    5003     .05       0  5036.5     .08       0
  5121.2     .05       0  6147.1      .1       0
Bank Sta=4889.3,5210.8
XS Rating Curve= 0 ,0
Exp/Cntr=0.3,0.1

Type RM Length L Ch R = 1 ,3169    ,396,396,396
BEGIN DESCRIPTION:
UNNAMED TRIB 2 TO BUFFALO CR 5.0
END DESCRIPTION:
XS GIS Cut Line= 5
      3627808.19     10527584.06      3628428.88     10527649.17
      3628858.56     10527449.51       3629357.7     10527215.14
      3629869.84     10527584.05
#Sta/Elev= 30
    3870   342.3  3961.9  327.74  3976.8  327.73  4122.8  310.97  4217.4   305.6
  4297.2   301.7  4316.4  301.39  4524.9  294.96  4770.6  292.08  4832.4  290.34
    4947  290.05  4953.5  288.76    4959  290.54  4965.7  286.28  4971.2  286.28
  4976.3  280.53  4981.8  284.06  4991.1   279.8  5001.7  279.23  5004.4  278.73
  5007.7  279.23  5021.9  287.47  5035.3  290.51    5049  289.11  5067.6  290.44
  5329.5  291.58  5674.6   301.3  5810.8  309.12  5903.7  311.83  6150.5  324.64
#Mann= 8 ,-1 , 0
    3870     .16       0  4217.4     .05       0  4297.2     .08       0
  4316.4     .05       0  4832.4     .16       0  5001.7     .07       0
  5007.7     .16       0    5049     .05       0
Bank Sta=4770.6,5329.5
XS Rating Curve= 0 ,0
Exp/Cntr=0.3,0.1

Type RM Length L Ch R = 1 ,2773    ,476,476,476
BEGIN DESCRIPTION:
UNNAMED TRIB 2 TO BUFFALO CR 4.0
END DESCRIPTION:
XS GIS Cut Line= 2
      3627799.52     10527618.78      3629223.17     10527874.86
#Sta/Elev= 30
  4004.7  343.74  4035.3  339.01  4045.7  335.99  4099.3  329.98  4106.4  327.34
  4116.6  327.78  4136.9   325.5    4147  322.86  4262.3  310.92  4362.1  304.91
  4461.8  300.38  4548.8  297.69  4602.5  297.88  4705.9  292.84  4866.9  289.09
    4970  288.87  4980.2  287.71  4990.4  278.18  4998.3  278.37  5000.4  277.03
  5003.1  276.53  5006.4  277.03  5010.7   285.3  5020.8  287.59    5092  289.01
  5114.8     290  5366.3  299.51  5386.6  301.81  5437.4  317.49  5451.2  318.43
#Mann= 8 ,-1 , 0
  4004.7     .16       0  4262.3     .05       0  4362.1     .08       0
  4461.8     .05       0  4866.9     .16       0  5000.4     .07       0
  5006.4     .16       0  5114.8     .05       0
Bank Sta=4970,5092
XS Rating Curve= 0 ,0
Exp/Cntr=0.3,0.1

Type RM Length L Ch R = 1 ,2297    ,477,477,477
BEGIN DESCRIPTION:
UNNAMED TRIB 2 TO BUFFALO CR 3.0
END DESCRIPTION:
XS GIS Cut Line= 3
      3628299.64     10528460.17      3628649.61     10528210.19
      3629199.62     10528110.19
#Sta/Elev= 30
  4582.5  325.49    4596  326.46  4619.3  321.84  4640.2  318.99  4812.3  298.49
  4889.7  290.21  4926.6  287.58  4954.8  287.34  4990.5  286.04  4999.1  276.37
  5006.5   275.8  5009.3   275.3  5012.5   275.8  5015.1   275.8  5022.7  286.92
  5039.3  287.58  5104.1  286.25  5195.5  286.73    5287  290.07  5368.3  295.65
    5428  301.53  5433.1  301.19  5439.5   302.9  5486.5  308.38  5491.6  307.72
  5520.8  309.09  5539.8  312.67  5544.9  312.59  5551.3  315.75  5571.6  319.15
#Mann= 3 ,-1 , 0
  4582.5     .05       0  5006.5     .03       0  5012.5     .05       0
Bank Sta=4954.8,5022.7
XS Rating Curve= 0 ,0
Exp/Cntr=0.3,0.1

Type RM Length L Ch R = 1 ,1820    ,1169,1169,1169
BEGIN DESCRIPTION:
UNNAMED TRIB 2 TO BUFFALO CR 2.0
END DESCRIPTION:
XS GIS Cut Line= 3
      3628294.32      10528547.6      3629070.37     10528776.77
      3629714.87     10528475.31
#Sta/Elev= 30
  4536.7  324.44  4583.9   319.9  4654.2  308.26  4677.8  304.92  4698.6  303.65
  4704.3  301.33  4750.8  295.74  4823.7  288.03    4855  285.91  4898.3  284.39
  4919.7  283.58  4969.7  284.68  4980.1  281.52  4988.5  276.47  4991.2  275.97
  4994.5  276.47  5019.6  284.49  5030.2  284.28    5147  285.77    5235  288.13
  5492.7  298.25  5687.3  311.43  5772.3  315.49  5777.8  317.16  5795.1  317.83
  5823.5  321.56  5943.2  322.01    6029  320.08  6051.6  321.73  6057.4  323.62
#Mann= 7 ,-1 , 0
  4536.7     .05       0  4583.9     .16       0  4654.2     .05       0
  4898.3     .16       0  4988.5     .07       0  4994.5     .16       0
  5030.2     .05       0
Bank Sta=4855,5147
XS Rating Curve= 0 ,0
Exp/Cntr=0.3,0.1

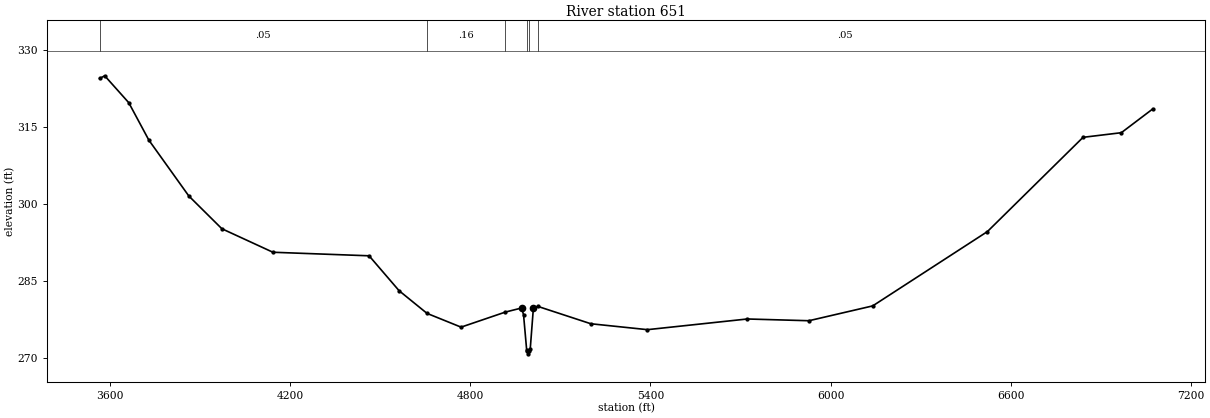
Type RM Length L Ch R = 1 ,651     ,0,0,0
BEGIN DESCRIPTION:
UNNAMED TRIB 2 TO BUFFALO CR 1.0
END DESCRIPTION:
XS GIS Cut Line= 4
      3627933.11     10528353.27      3627943.96     10529557.67
      3628453.95     10529807.24       3629711.8     10528614.45
#Sta/Elev= 30
  3566.6  324.45  3583.5  324.97  3663.5  319.73  3730.6  312.42  3863.5  301.55
  3973.5  295.17  4143.5  290.59  4463.6   289.9  4563.6  283.09  4656.5  278.68
  4769.8     276  4917.4  278.94  4971.2  279.73  4977.7  278.43  4988.1  271.57
  4990.7   271.3  4993.4   270.8  4996.7   271.3    5000  271.73  5010.6  279.81
  5025.5  280.04  5201.8  276.66  5390.1  275.51  5722.6  277.59  5927.7  277.25
  6140.1  280.14  6521.9  294.62  6840.3  312.98  6967.7  313.88  7072.3  318.51
#Mann= 6 ,-1 , 0
  3566.6     .05       0  4656.5     .16       0  4917.4     .12       0
  4990.7     .07       0  4996.7     .12       0  5025.5     .05       0
Bank Sta=4971.2,5010.6
XS Rating Curve= 0 ,0
Exp/Cntr=0.3,0.1

Chan Stop Cuts=-1
Use User Specified Reach Order=0
Composite Channel Slope=5