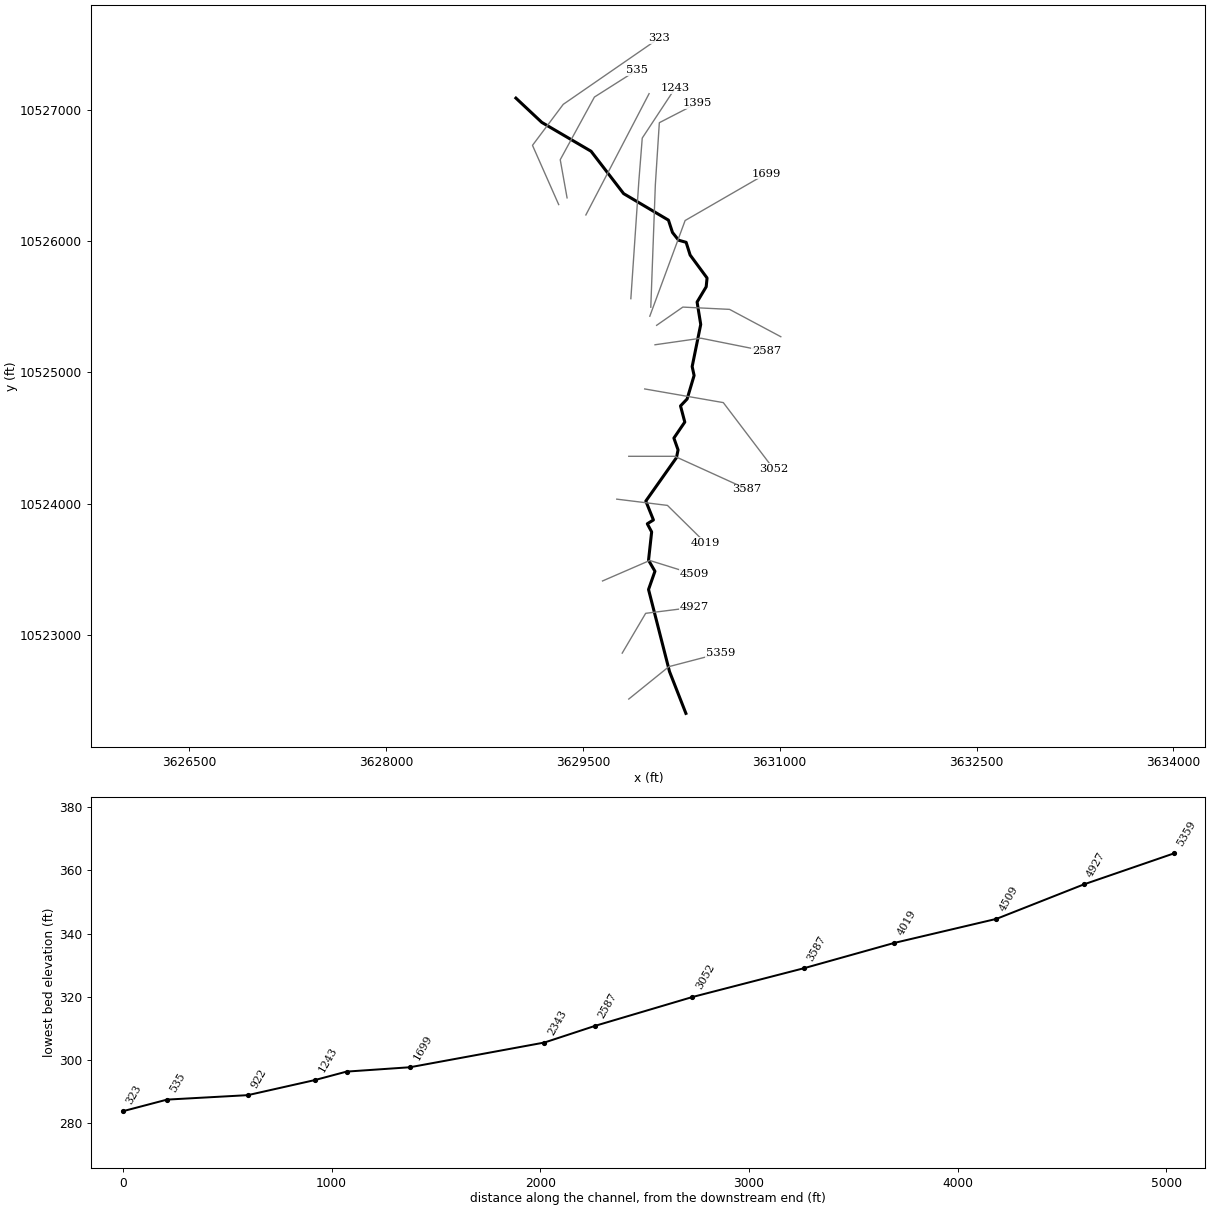
--- UNNAMED TRIB 3 TO BUFFALO CR.prj (project) ---

Proj Title=UNNAMED TRIB 3 TO BUFFALO CR Base Level Engineering
Current Plan=p01
Default Exp/Contr=0.3,0.1
English Units
Geom File=g01
Flow File=f01
Plan File=p01
Y Axis Title=Elevation
X Axis Title(PF)=Main Channel Distance
X Axis Title(XS)=Station
BEGIN DESCRIPTION:
UNNAMED TRIB 3 TO BUFFALO CR
END DESCRIPTION:
DSS Export Rating Curves= 0
DSS Export Rating Curve Sorted= 0
DSS Export Volume Flow Curves= 0
DXF OffsetX= 0
DXF OffsetY= 0
DXF ScaleX= 1
DXF ScaleY= 10

--- UNNAMED TRIB 3 TO BUFFALO CR.p01 (plan) ---

Plan Title=Multiple Run
Short Identifier=Multiple
Geom File=g01
Flow File=f01
Subcritical Flow
K Sum by GR= 0
Std Step Tol= 0.01
Critical Tol= 0.01
Num of Std Step Trials= 20
Max Error Tol= 0.3
Flow Tol Ratio= 0.001
Split Flow NTrial= 30
Split Flow Tol= 0.02
Split Flow Ratio= 0.02
Log Output Level= 0
Friction Slope Method= 1
Unsteady Friction Slope Method= 2
Unsteady Bridges Friction Slope Method= 1
Parabolic Critical Depth
Global Vel Dist=  1 , 1 , 1
Global Log Level= 0
CheckData=True
Encroach Param= -1, 0, 0, 0
BEGIN DESCRIPTION:
Multiple Run
END DESCRIPTION:

--- UNNAMED TRIB 3 TO BUFFALO CR.f01 (steady flow) ---

Flow Title=Multiple
Number of Profiles=7
Profile Names=10-year,25-year,50-year,1pct_min,100-year,1pct_plu,500-year
River Rch & RM= UNNAMED TRIB 3 T,Reach-1,5359
     615     823     991     873    1181    1598    1670
Boundary for River Rch & Prof#=UNNAMED TRIB 3 T,Reach-1,1
Up Type=0
Dn Type=3
Dn Slope=0.005
Boundary for River Rch & Prof#=UNNAMED TRIB 3 T,Reach-1,2
Up Type=0
Dn Type=3
Dn Slope=0.005
Boundary for River Rch & Prof#=UNNAMED TRIB 3 T,Reach-1,3
Up Type=0
Dn Type=3
Dn Slope=0.005
Boundary for River Rch & Prof#=UNNAMED TRIB 3 T,Reach-1,4
Up Type=0
Dn Type=3
Dn Slope=0.005
Boundary for River Rch & Prof#=UNNAMED TRIB 3 T,Reach-1,5
Up Type=0
Dn Type=3
Dn Slope=0.005
Boundary for River Rch & Prof#=UNNAMED TRIB 3 T,Reach-1,6
Up Type=0
Dn Type=3
Dn Slope=0.005
Boundary for River Rch & Prof#=UNNAMED TRIB 3 T,Reach-1,7
Up Type=0
Dn Type=3
Dn Slope=0.005

--- UNNAMED TRIB 3 TO BUFFALO CR.g01 (geometry) ---

Geom Title=Existing Conditions
Program Version=4.10

River Reach=UNNAMED TRIB 3 T,Reach-1
Reach XY= 30
        3630285.       10522401.        3630160.       10522720.
      3630000.25       10523345.        3630049.       10523484.
      3630000.25       10523568.        3630024.       10523784.
      3629990.75       10523846.       3630037.5       10523875.
       3629979.5       10524019.      3630213.25       10524350.
      3630225.25       10524409.       3630193.5       10524499.
       3630276.5       10524621.        3630244.       10524744.
      3630294.25       10524797.       3630347.5       10524976.
      3630332.75       10525044.        3630398.       10525365.
      3630370.25       10525536.      3630439.64     10525651.96
      3630446.25       10525719.      3630317.25       10525894.
      3630286.75       10525991.      3630229.25       10526007.
      3630182.75       10526066.        3630152.       10526160.
       3629810.5       10526362.      3629562.25       10526685.
      3629186.75       10526905.       3628989.5       10527090.

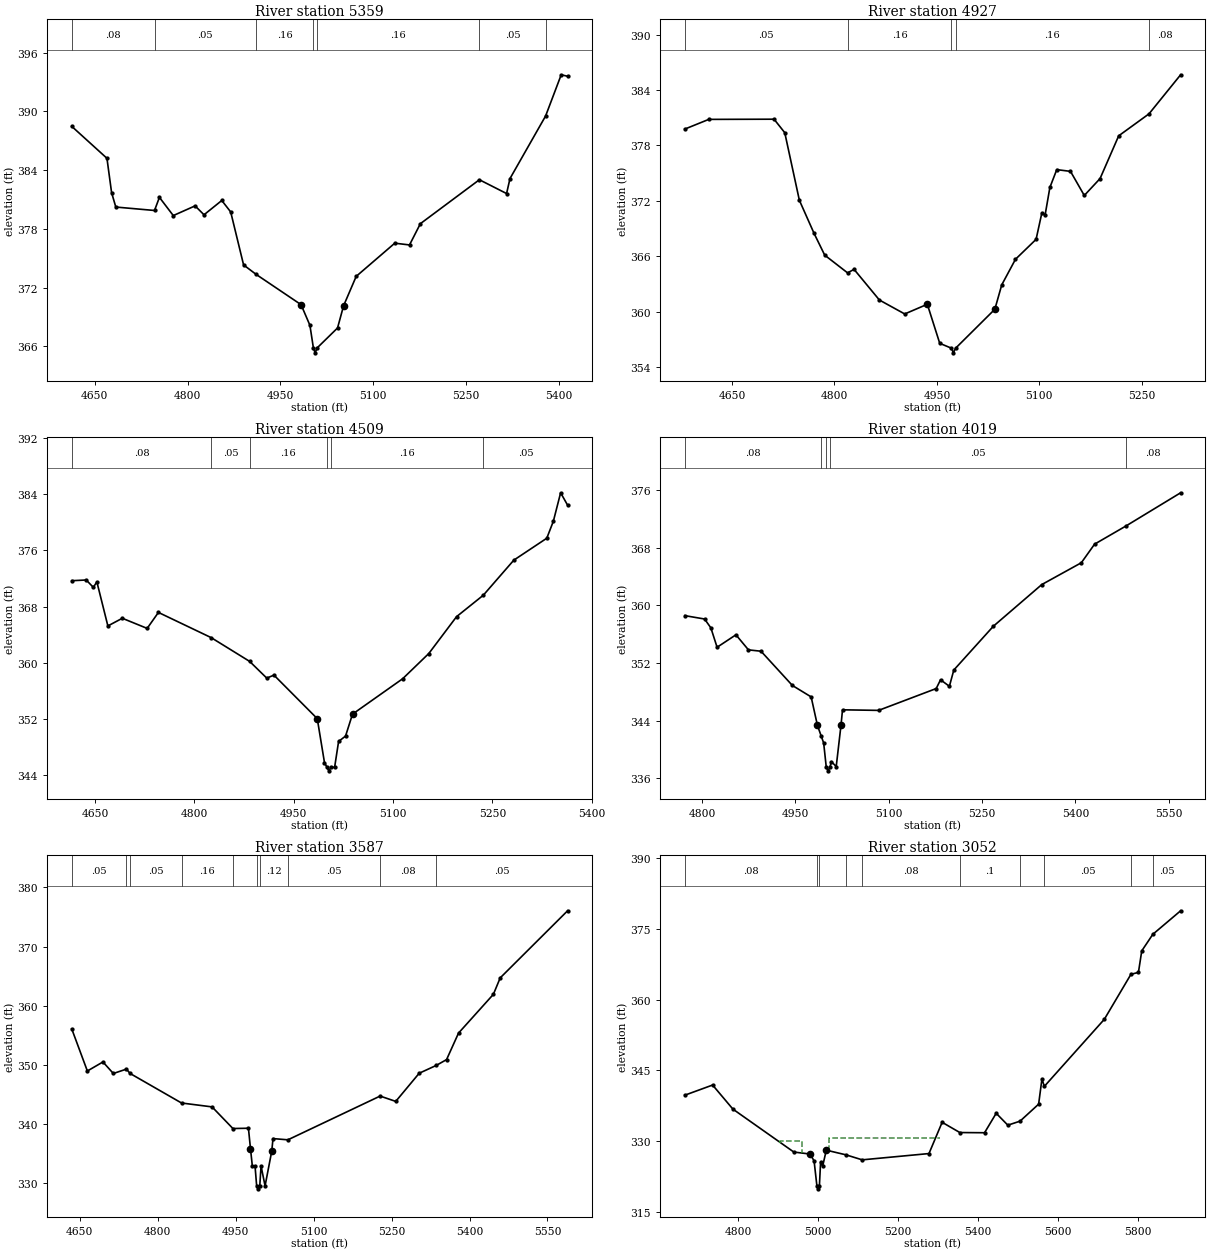
Type RM Length L Ch R = 1 ,5359    ,432,432,432
BEGIN DESCRIPTION:
UNNAMED TRIB 3 TO BUFFALO CR 12.0
END DESCRIPTION:
XS GIS Cut Line= 3
      3629849.62      10522510.2      3630155.44     10522757.22
      3630549.59     10522860.18
#Sta/Elev= 30
  4613.1  388.48  4669.9  385.22  4677.4  381.71  4684.2  380.24  4746.7  379.89
  4754.6  381.23    4777  379.37  4812.2  380.36  4826.6  379.45  4855.3  380.91
  4869.7  379.74  4890.5  374.33  4910.8  373.36  4983.3  370.27  4997.6  368.16
  5003.2  365.85    5006  365.35  5009.2  365.85  5042.2  367.89  5051.9  370.15
  5072.3  373.16  5134.6  376.55  5158.4  376.37  5175.9  378.54  5271.2  383.03
  5315.1  381.62  5320.6  383.15  5378.1  389.54  5403.3  393.75  5413.6   393.6
#Mann= 7 ,-1 , 0
  4613.1     .08       0  4746.7     .05       0  4910.8     .16       0
  5003.2     .07       0  5009.2     .16       0  5271.2     .05       0
  5378.1      .1       0
Bank Sta=4983.3,5051.9
XS Rating Curve= 0 ,0
Exp/Cntr=0.3,0.1

Type RM Length L Ch R = 1 ,4927    ,418,418,418
BEGIN DESCRIPTION:
UNNAMED TRIB 3 TO BUFFALO CR 11.0
END DESCRIPTION:
XS GIS Cut Line= 3
      3629799.62      10522860.2      3629978.36     10523163.47
      3630349.61     10523210.19
#Sta/Elev= 30
  4580.8  379.76  4615.9  380.81  4711.5  380.83  4727.2  379.37  4748.6  372.05
  4770.1  368.47  4785.7  366.11  4819.2  364.19  4828.7  364.57  4865.8  361.25
  4902.9  359.74    4936  360.79  4954.2  356.56  4971.4  356.03  4974.1  355.53
  4977.4  356.03  5034.9  360.25    5045  362.89  5065.1  365.66  5095.3  367.82
  5103.6  370.63  5108.6  370.49  5115.5  373.44  5125.6  375.37  5145.7  375.18
  5165.9  372.57    5189   374.4  5216.3  379.03  5260.7  381.41    5307  385.64
#Mann= 5 ,-1 , 0
  4580.8     .05       0  4819.2     .16       0  4971.4     .07       0
  4977.4     .16       0  5260.7     .08       0
Bank Sta=4936,5034.9
XS Rating Curve= 0 ,0
Exp/Cntr=0.3,0.1

Type RM Length L Ch R = 1 ,4509    ,490,490,490
BEGIN DESCRIPTION:
UNNAMED TRIB 3 TO BUFFALO CR 10.0
END DESCRIPTION:
XS GIS Cut Line= 3
      3629649.61     10523410.19      3630009.61     10523566.25
      3630349.59      10523460.2
#Sta/Elev= 30
  4614.9  371.67  4636.7  371.77  4647.4  370.73  4652.8   371.5  4669.4  365.24
  4691.2  366.33  4728.7  364.89  4745.7  367.16  4825.3  363.58  4883.4   360.2
  4909.3  357.82  4920.1  358.25  4985.5  352.06  4996.4  345.81  5000.2  345.14
    5003  344.64  5006.2  345.14  5011.7  345.14  5017.7  348.82  5028.2  349.58
  5038.7   352.7  5114.4  357.73  5153.9  361.32  5195.8  366.56  5236.2  369.61
  5282.2  374.59    5332  377.71  5341.9  380.12  5352.9  384.17  5363.4  382.41
#Mann= 6 ,-1 , 0
  4614.9     .08       0  4825.3     .05       0  4883.4     .16       0
  5000.2     .07       0  5006.2     .16       0  5236.2     .05       0
Bank Sta=4985.5,5038.7
XS Rating Curve= 0 ,0
Exp/Cntr=0.3,0.1

Type RM Length L Ch R = 1 ,4019    ,432,432,432
BEGIN DESCRIPTION:
UNNAMED TRIB 3 TO BUFFALO CR 9.0
END DESCRIPTION:
XS GIS Cut Line= 3
      3629758.06     10524033.72      3630144.37     10523985.97
      3630434.86     10523699.82
#Sta/Elev= 30
  4772.1  358.56  4803.9  358.09    4814  356.86    4824  354.17  4854.3   355.9
  4874.4  353.81  4894.6  353.62    4945  348.87  4975.2  347.28  4985.3  343.32
  4991.4  341.84  4995.3  340.89  4999.5  337.52  5002.3  337.02  5005.5  337.52
  5007.6   338.3  5015.5  337.62  5023.3  343.45  5025.6  345.49  5083.6  345.41
  5176.2  348.44  5183.2  349.66  5197.4  348.75  5204.5  351.01  5268.1  357.09
  5345.9  362.87  5409.5   365.9  5430.8  368.48  5481.2     371  5569.1  375.61
#Mann= 5 ,-1 , 0
  4772.1     .08       0  4991.4     .05       0  4999.5     .04       0
  5005.5     .05       0  5481.2     .08       0
Bank Sta=4985.3,5023.3
XS Rating Curve= 0 ,0
Exp/Cntr=0.3,0.1

Type RM Length L Ch R = 1 ,3587    ,535,535,535
BEGIN DESCRIPTION:
UNNAMED TRIB 3 TO BUFFALO CR 8.0
END DESCRIPTION:
XS GIS Cut Line= 3
      3629849.61     10524360.19      3630199.61     10524360.19
      3630749.65     10524110.17
#Sta/Elev= 30
  4634.5  356.07  4664.5  348.96  4694.5  350.49  4714.5  348.54  4739.7  349.28
  4746.8  348.54  4845.7  343.55  4904.5  342.89  4944.6  339.23  4974.5  339.28
 4978.41  335.84    4982  332.89  4987.2  332.89  4990.3  329.53    4993  329.03
  4996.3  329.53  4998.8  332.89  5006.5  329.53 5019.32  335.39  5021.8  337.53
  5050.4  337.32  5227.9  344.72    5258  343.82  5303.1  348.58  5336.1  349.91
  5355.8  350.89  5378.8  355.37  5445.9  361.93    5459  364.71  5588.7  376.06
#Mann= 10 ,-1 , 0
  4634.5     .05       0  4739.7     .08       0  4746.8     .05       0
  4845.7     .16       0  4944.6     .12       0  4990.3     .07       0
  4996.3     .12       0  5050.4     .05       0  5227.9     .08       0
  5336.1     .05       0
Bank Sta=4978.41,5019.32
XS Rating Curve= 0 ,0
Exp/Cntr=0.3,0.1

Type RM Length L Ch R = 1 ,3052    ,465,465,465
BEGIN DESCRIPTION:
UNNAMED TRIB 3 TO BUFFALO CR 7.0
END DESCRIPTION:
XS GIS Cut Line= 3
      3629971.09     10524873.56      3630570.08     10524769.39
        3630952.     10524265.95
#Sta/Elev= 30
  4667.1  339.74  4736.6  341.89  4787.4  336.79  4939.7   327.7  4980.3  327.28
  4990.4  325.83  4997.6  320.41  5000.3  319.91  5003.6  320.41  5006.7  325.59
  5011.8   324.7  5020.9   328.1  5070.1  327.11  5110.7  326.05  5277.7  327.38
  5310.6     334  5354.9  331.83  5416.7  331.79  5445.8  335.91  5474.9  333.39
  5505.4  334.24  5551.9  337.84  5560.2  343.17  5566.2  341.61  5716.2  355.81
  5782.7  365.33  5801.5  365.75  5809.8   370.3  5837.5  373.81    5907  378.79
#Mann= 10 ,-1 , 0
  4667.1     .08       0  4997.6     .07       0  5003.6     .08       0
  5070.1     .05       0  5110.7     .08       0  5354.9      .1       0
  5505.4     .08       0  5566.2     .05       0  5782.7     .08       0
  5837.5     .05       0
#XS Ineff= 2 ,-1
 4906.25 4961.14330.1458 5027.16 5306.36330.6741
Permanent Ineff=
       F       F
Bank Sta=4980.3,5020.9
XS Rating Curve= 0 ,0
Exp/Cntr=0.3,0.1

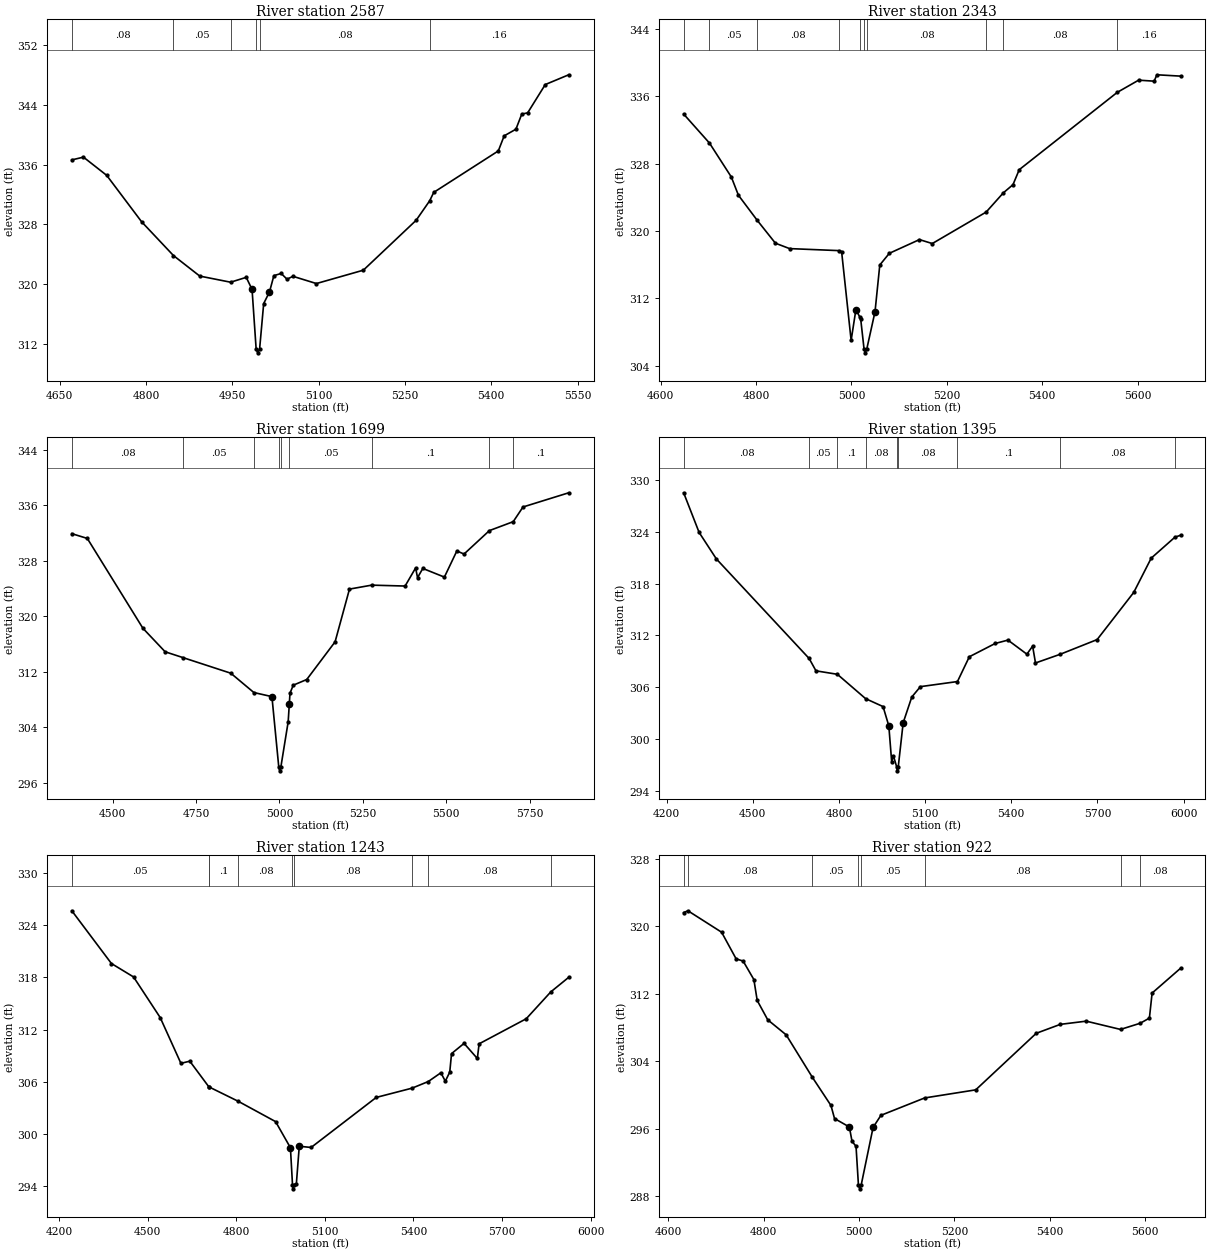
Type RM Length L Ch R = 1 ,2587    ,244,244,244
BEGIN DESCRIPTION:
UNNAMED TRIB 3 TO BUFFALO CR 6.0
END DESCRIPTION:
XS GIS Cut Line= 3
      3630049.57     10525210.18      3630399.61     10525260.19
      3630899.62     10525160.19
#Sta/Elev= 30
  4671.2  336.65  4691.4  337.02  4731.8  334.58  4792.5  328.36  4847.8  323.84
  4893.5  321.09  4947.1  320.27  4974.3  320.92  4984.4   319.3  4991.5  311.31
  4994.2  310.81  4997.5  311.31  5004.6  317.41  5014.7  318.97  5022.3  321.15
    5035  321.44  5045.2  320.67  5055.4  321.06  5096.2  320.09  5177.8  321.88
  5269.5  328.56  5293.1  331.18  5300.1   332.3  5412.3  337.85  5422.5  339.87
  5442.9  340.76  5453.1  342.79  5463.3  342.95  5493.9  346.74  5534.7  348.05
#Mann= 6 ,-1 , 0
  4671.2     .08       0  4847.8     .05       0  4947.1     .08       0
  4991.5     .07       0  4997.5     .08       0  5293.1     .16       0
Bank Sta=4984.4,5014.7
XS Rating Curve= 0 ,0
Exp/Cntr=0.3,0.1

Type RM Length L Ch R = 1 ,2343    ,644,644,644
BEGIN DESCRIPTION:
UNNAMED TRIB 3 TO BUFFALO CR 5.0
END DESCRIPTION:
XS GIS Cut Line= 4
      3630061.99     10525358.43      3630261.67     10525497.34
      3630617.58     10525479.98      3631008.22     10525271.64
#Sta/Elev= 30
    4648  333.89  4702.2  330.44    4748  326.41  4762.9  324.24  4802.6  321.24
  4840.5  318.54  4870.2   317.9  4973.6  317.66  4979.3  317.55  4999.3  306.99
  5009.3  310.65  5017.2  309.79  5019.3  309.56  5026.3  306.01  5029.1  305.51
  5032.3  306.01  5049.4   310.4  5059.4  315.95  5079.4  317.34  5142.6  318.97
  5169.5   318.5  5282.5  322.24  5318.6  324.53  5338.8   325.5  5351.9  327.28
  5557.5  336.47  5602.3  337.92  5634.9   337.8  5640.6  338.56  5690.3   338.4
#Mann= 10 ,-1 , 0
    4648     .08       0  4702.2     .05       0  4802.6     .08       0
  4973.6     .05       0  5017.2     .08       0  5026.3     .04       0
  5032.3     .08       0  5282.5      .1       0  5318.6     .08       0
  5557.5     .16       0
Bank Sta=5009.3,5049.4
XS Rating Curve= 0 ,0
Exp/Cntr=0.3,0.1

Type RM Length L Ch R = 1 ,1699    ,304,304,304
BEGIN DESCRIPTION:
UNNAMED TRIB 3 TO BUFFALO CR 4.0
END DESCRIPTION:
XS GIS Cut Line= 3
      3630009.93     10525427.88      3630279.03     10526157.07
      3630894.95     10526512.74
#Sta/Elev= 30
  4378.1  331.92  4424.5  331.23  4591.1  318.26  4657.7  314.87  4711.2  314.03
  4854.3  311.78  4923.4  308.99  4977.5   308.4  4998.1  298.19  5000.9  297.69
  5004.1  298.19  5026.2  304.78  5029.5  307.29  5031.6  308.89  5041.4  310.05
  5081.8  310.87  5166.7  316.31  5209.8  323.92  5276.3  324.49  5376.4  324.36
  5407.9  326.97  5413.7  325.57  5429.5   326.9  5494.1  325.65  5531.4  329.42
    5553  328.98  5628.9  332.36  5700.3  333.65  5729.6  335.77  5866.6  337.82
#Mann= 9 ,-1 , 0
  4378.1     .08       0  4711.2     .05       0  4923.4     .16       0
  4998.1     .07       0  5004.1     .16       0  5029.5     .05       0
  5276.3      .1       0  5628.9     .08       0  5700.3      .1       0
Bank Sta=4977.5,5029.5
XS Rating Curve= 0 ,0
Exp/Cntr=0.3,0.1

Type RM Length L Ch R = 1 ,1395    ,152,152,152
BEGIN DESCRIPTION:
UNNAMED TRIB 3 TO BUFFALO CR 3.0
END DESCRIPTION:
XS GIS Cut Line= 4
      3630017.42     10525496.41      3630052.14     10526429.55
      3630082.52     10526902.64      3630368.99     10527050.21
#Sta/Elev= 30
  4259.4  328.51  4313.2  323.92  4373.3  320.85  4696.3  309.32  4720.1  307.89
  4794.6  307.49  4892.9  304.67  4953.7  303.75  4973.7  301.52  4983.7  297.34
  4989.7  298.06  5000.7  296.81  5003.4  296.31  5006.7  296.81  5023.7  301.88
  5053.7  304.86  5083.7  306.06  5212.7  306.65    5254  309.52  5344.1  311.06
  5388.5  311.45  5454.4  309.82  5474.4  310.75  5484.4   308.8  5571.4  309.82
    5699  311.51  5826.4  316.97  5887.3  320.94  5969.9  323.37  5989.5  323.59
#Mann= 9 ,-1 , 0
  4259.4     .08       0  4696.3     .05       0  4794.6      .1       0
  4892.9     .08       0  5000.7     .07       0  5006.7     .08       0
  5212.7      .1       0  5571.4     .08       0  5969.9     .05       0
Bank Sta=4973.7,5023.7
XS Rating Curve= 0 ,0
Exp/Cntr=0.3,0.1

Type RM Length L Ch R = 1 ,1243    ,321,321,321
BEGIN DESCRIPTION:
Mapping XS f5013086
END DESCRIPTION:
XS GIS Cut Line= 4
      3629865.51     10525561.53      3629926.27     10526455.59
      3629952.31     10526785.45      3630203.31     10527166.27
#Sta/Elev= 30
    4243  325.69  4377.1  319.61  4452.1  318.06  4542.3  313.38  4612.5   308.1
  4642.6  308.35  4706.5  305.42  4708.3  305.37  4806.9  303.72  4933.2  301.38
  4983.4  298.37  4990.4  294.13  4993.1  293.63  4996.4  294.13  5003.4  294.16
  5013.4  298.54  5053.5   298.4  5274.1  304.17  5395.5  305.24  5450.2     306
    5493  307.01  5508.1  306.04  5523.1  307.09  5529.1  309.22  5571.5   310.4
  5616.5  308.66  5622.5  310.35  5782.1  313.24  5865.4  316.34  5926.1  318.02
#Mann= 9 ,-1 , 0
    4243     .05       0  4706.5     .08       0  4708.3      .1       0
  4806.9     .08       0  4990.4     .07       0  4996.4     .08       0
  5395.5      .1       0  5450.2     .08       0  5865.4     .05       0
Bank Sta=4983.4,5013.4
XS Rating Curve= 0 ,0
Exp/Cntr=0.3,0.1

Type RM Length L Ch R = 1 ,922     ,387,387,387
BEGIN DESCRIPTION:
UNNAMED TRIB 3 TO BUFFALO CR 2.0
END DESCRIPTION:
XS GIS Cut Line= 2
      3629522.65     10526199.56      3630004.38     10527123.96
#Sta/Elev= 30
  4631.9   321.6  4640.9  321.81  4711.5  319.27    4742  316.11  4756.7  315.85
  4779.2  313.66  4786.2  311.18  4808.3  308.89  4846.9  307.11  4902.1  302.06
  4940.9  298.74  4948.4  297.19  4979.5  296.19  4985.1  294.49  4993.5   293.9
  4998.5  289.36  5001.3  288.86  5004.5  289.36  5029.3  296.14  5045.7  297.57
  5137.4  299.63  5244.6  300.59  5371.5  307.29    5422  308.35  5476.4  308.73
  5548.3  307.75  5589.5  308.48  5608.9  309.09  5614.6  312.06  5674.3     315
#Mann= 8 ,-1 , 0
  4631.9     .05       0  4640.9     .08       0  4902.1     .05       0
  4998.5     .03       0  5004.5     .05       0  5137.4     .08       0
  5548.3     .05       0  5589.5     .08       0
Bank Sta=4979.5,5029.3
XS Rating Curve= 0 ,0
Exp/Cntr=0.3,0.1

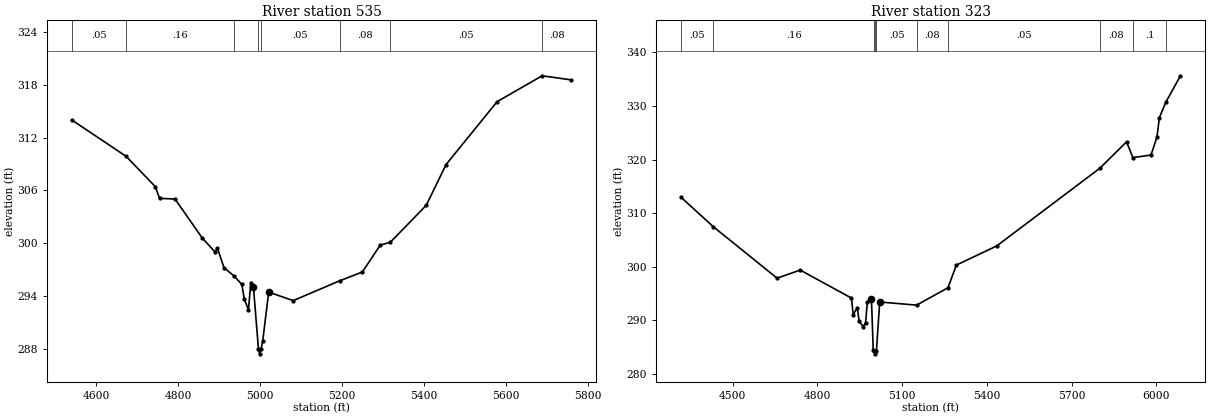
Type RM Length L Ch R = 1 ,535     ,212,212,212
BEGIN DESCRIPTION:
Mapping XS d8971430
END DESCRIPTION:
XS GIS Cut Line= 4
       3629379.4     10526329.71      3629327.31     10526620.52
      3629587.73     10527097.95      3629908.94     10527301.96
#Sta/Elev= 30
  4540.7  313.98  4672.9  309.87  4744.4  306.42  4754.5   305.1  4792.4  305.02
  4858.5  300.62  4890.1  299.01  4895.8  299.47  4911.9  297.24  4937.4  296.24
  4955.6  295.33  4961.3  293.69  4971.7  292.45  4977.4  295.54  4983.8  295.05
  4996.2  287.95    4999  287.45  5002.2  287.95  5006.6  288.94  5021.1  294.46
  5080.9  293.49  5194.5  295.74  5249.8  296.74  5293.5  299.79    5318  300.11
  5405.9  304.31  5454.3  308.94  5578.8  316.07  5688.9  319.01  5760.5  318.54
#Mann= 8 ,-1 , 0
  4540.7     .05       0  4672.9     .16       0  4937.4     .05       0
  4996.2     .03       0  5002.2     .05       0  5194.5     .08       0
    5318     .05       0  5688.9     .08       0
Bank Sta=4983.8,5021.1
XS Rating Curve= 0 ,0
Exp/Cntr=0.3,0.1

Type RM Length L Ch R = 1 ,323     ,0,0,0
BEGIN DESCRIPTION:
UNNAMED TRIB 3 TO BUFFALO CR 1.0
END DESCRIPTION:
XS GIS Cut Line= 4
       3629315.5     10526278.57      3629115.84     10526729.98
      3629350.21     10527042.48      3630078.79     10527545.55
#Sta/Elev= 30
  4316.2  312.99  4430.8  307.48  4656.9  297.88  4738.8  299.39  4920.4  294.17
  4926.6  291.08  4941.2  292.36  4947.6  289.84    4962  288.84  4970.4  289.58
  4976.6  293.43  4991.2  294.01  4997.6  284.42  5000.7  284.33  5002.8  284.27
  5005.5  283.77  5008.8  284.27  5020.4  293.44  5151.2  292.85  5262.3  296.09
    5292  300.32  5435.3   303.9  5800.3  318.38    5895  323.31  5917.3  320.36
  5981.5  320.84  6002.5  324.16  6011.3  327.83  6034.3  330.72  6085.8  335.62
#Mann= 10 ,-1 , 0
  4316.2     .05       0  4430.8     .16       0  5000.7     .05       0
  5002.8     .07       0  5008.8     .05       0  5151.2     .08       0
  5262.3     .05       0  5800.3     .08       0  5917.3      .1       0
  6034.3     .08       0
Bank Sta=4991.2,5020.4
XS Rating Curve= 0 ,0
Exp/Cntr=0.3,0.1

Chan Stop Cuts=-1
Use User Specified Reach Order=0
Composite Channel Slope=5