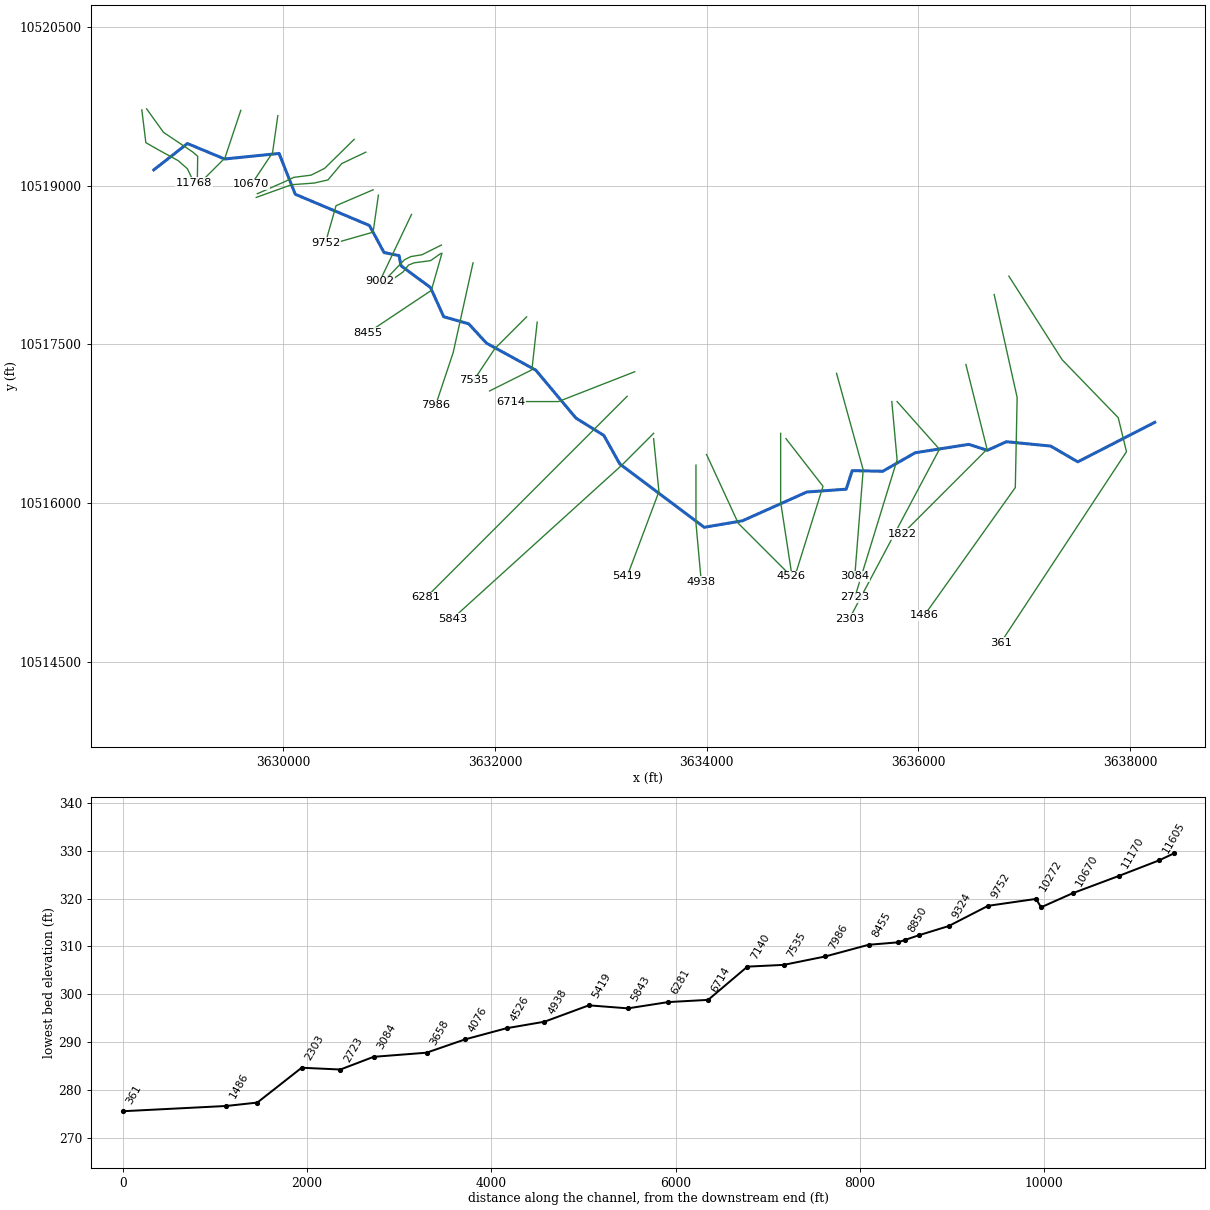
--- UNNAMED TRIBUTARY 1 TO BLISS CR.prj (project) ---

Proj Title=UNNAMED TRIBUTARY 1 TO BLISS CR Base Level Engineering
Current Plan=p01
Default Exp/Contr=0.3,0.1
English Units
Geom File=g01
Flow File=f01
Plan File=p01
Y Axis Title=Elevation
X Axis Title(PF)=Main Channel Distance
X Axis Title(XS)=Station
BEGIN DESCRIPTION:
UNNAMED TRIBUTARY 1 TO BLISS CR
END DESCRIPTION:
DSS Export Rating Curves= 0
DSS Export Rating Curve Sorted= 0
DSS Export Volume Flow Curves= 0
DXF OffsetX= 0
DXF OffsetY= 0
DXF ScaleX= 1
DXF ScaleY= 10

--- UNNAMED TRIBUTARY 1 TO BLISS CR.p01 (plan) ---

Plan Title=Multiple Run
Short Identifier=Multiple
Geom File=g01
Flow File=f01
Subcritical Flow
K Sum by GR= 0
Std Step Tol= 0.01
Critical Tol= 0.01
Num of Std Step Trials= 20
Max Error Tol= 0.3
Flow Tol Ratio= 0.001
Split Flow NTrial= 30
Split Flow Tol= 0.02
Split Flow Ratio= 0.02
Log Output Level= 0
Friction Slope Method= 1
Unsteady Friction Slope Method= 2
Unsteady Bridges Friction Slope Method= 1
Parabolic Critical Depth
Global Vel Dist=  1 , 1 , 1
Global Log Level= 0
CheckData=True
Encroach Param= -1, 0, 0, 0
BEGIN DESCRIPTION:
Multiple Run
END DESCRIPTION:

--- UNNAMED TRIBUTARY 1 TO BLISS CR.f01 (steady flow) ---

Flow Title=Multiple
Program Version=4.10
Number of Profiles= 7
Profile Names=10-year,25-year,50-year,1pct_min,100-year,1pct_plu,500-year
River Rch & RM=UNNAMED TRIBUTAR,Reach-1         ,11768
     523     693     828     726     982    1328    1371
River Rch & RM=UNNAMED TRIBUTAR,Reach-1         ,9002
     848    1157    1412    1260    1704    2304    2469
River Rch & RM=UNNAMED TRIBUTAR,Reach-1         ,7535
    1214    1693    2096    1895    2562    3465    3815
River Rch & RM=UNNAMED TRIBUTAR,Reach-1         ,7140
    1214    1693    2096    1895    2562    3465    3815
River Rch & RM=UNNAMED TRIBUTAR,Reach-1         ,6714
    2026    2889    3629    3320    4490    6072    6855
Boundary for River Rch & Prof#=UNNAMED TRIBUTAR,Reach-1         , 1
Up Type= 0
Dn Type= 3
Dn Slope=0.005
Boundary for River Rch & Prof#=UNNAMED TRIBUTAR,Reach-1         , 2
Up Type= 0
Dn Type= 3
Dn Slope=0.005
Boundary for River Rch & Prof#=UNNAMED TRIBUTAR,Reach-1         , 3
Up Type= 0
Dn Type= 3
Dn Slope=0.005
Boundary for River Rch & Prof#=UNNAMED TRIBUTAR,Reach-1         , 4
Up Type= 0
Dn Type= 3
Dn Slope=0.005
Boundary for River Rch & Prof#=UNNAMED TRIBUTAR,Reach-1         , 5
Up Type= 0
Dn Type= 3
Dn Slope=0.005
Boundary for River Rch & Prof#=UNNAMED TRIBUTAR,Reach-1         , 6
Up Type= 0
Dn Type= 3
Dn Slope=0.005
Boundary for River Rch & Prof#=UNNAMED TRIBUTAR,Reach-1         , 7
Up Type= 0
Dn Type= 3
Dn Slope=0.005
DSS Import GetInterval= 0
DSS Import GetPeak= 0
DSS Import FillOption= 0

--- UNNAMED TRIBUTARY 1 TO BLISS CR.g01 (geometry) ---

Geom Title=Existing Conditions
Program Version=4.10

River Reach=UNNAMED TRIBUTAR,Reach-1
Reach XY= 30
      3628777.75       10519148.       3629095.5       10519397.
      3629446.25       10519251.       3629961.5       10519303.
        3630114.       10518918.      3630814.75       10518623.
      3630952.75       10518368.        3631095.       10518338.
        3631113.       10518243.      3631391.75       10518037.
       3631516.5       10517761.      3631751.75       10517695.
       3631920.5       10517512.      3632386.25       10517257.
      3632765.75       10516804.      3633028.75       10516641.
      3633180.25       10516371.      3633977.25       10515773.
        3634338.       10515834.      3634946.75       10516106.
      3635318.75       10516133.       3635375.5       10516308.
      3635663.75       10516302.        3635971.       10516477.
       3636476.5       10516556.      3636652.75       10516500.
      3636831.75       10516581.      3637250.25       10516540.
       3637506.5       10516391.      3638233.75       10516764.

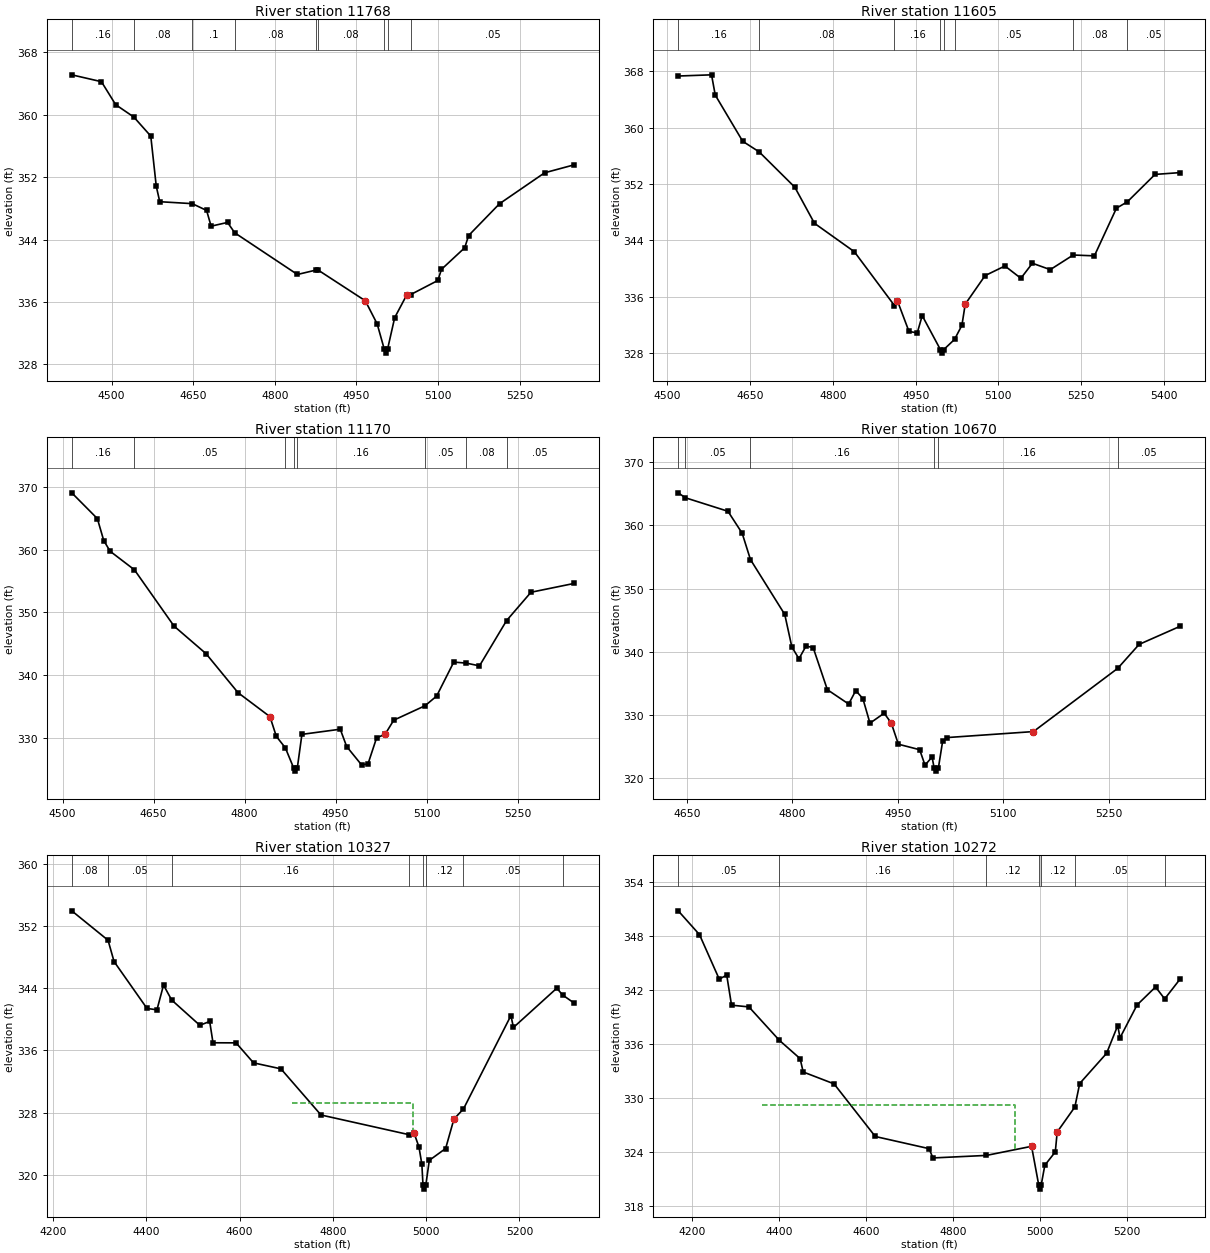
Type RM Length L Ch R = 1 ,11768   ,163,163,163
BEGIN DESCRIPTION:
UNNAMED TRIBUTARY 1 TO BLISS CR 26.0
END DESCRIPTION:
XS GIS Cut Line= 6
       3628664.6     10519714.33       3628702.8     10519405.26
      3628824.33     10519335.81      3629008.36     10519235.12
      3629095.16     10519158.73      3629157.67     10519026.78
#Sta/Elev= 30
  4426.8  365.13  4481.3  364.25  4507.5   361.3  4540.9  359.71    4572  357.27
  4582.1  350.83  4588.5  348.85  4648.2   348.6  4674.6  347.73  4682.9  345.71
  4713.1  346.19  4726.3  344.86  4841.5  339.51  4875.8  340.08  4879.3  340.09
  4966.3  336.14  4988.1  333.17  5001.2  329.92  5003.9  329.42  5007.2  329.92
  5020.3  333.97  5042.1  336.84  5049.9  336.94  5099.6  338.74  5106.3  340.17
    5149  342.94  5156.2  344.51    5213  348.59  5295.9  352.56  5349.6  353.57
#Mann= 9 ,-1 , 0
  4426.8     .16       0  4540.9     .08       0  4648.2      .1       0
  4726.3     .08       0  4875.8     .16       0  4879.3     .08       0
  5001.2     .07       0  5007.2     .08       0  5049.9     .05       0
Bank Sta=4966.3,5042.1
XS Rating Curve= 0 ,0
Exp/Cntr=0.3,0.1

Type RM Length L Ch R = 1 ,11605   ,435,435,435
BEGIN DESCRIPTION:
UNNAMED TRIBUTARY 1 TO BLISS CR 25.0
END DESCRIPTION:
XS GIS Cut Line= 5
      3628709.74     10519724.71      3628869.47     10519502.48
      3629143.78     10519318.45      3629192.39     10519276.79
      3629188.92     10519034.44
#Sta/Elev= 30
  4519.5  367.35  4579.9  367.52  4586.6  364.64  4636.4  358.07  4666.2  356.57
  4730.9  351.54  4766.5  346.41  4838.8  342.37  4911.6  334.71  4916.9   335.4
  4937.9  331.03  4952.9  330.83  4961.9  333.28  4994.9  328.45  4997.6  327.95
  5000.9  328.45  5020.5   329.9  5033.9  331.91  5039.9  334.91  5075.9  338.97
  5111.9  340.34  5140.8  338.59  5161.7  340.73  5194.1  339.82  5235.7   341.9
  5274.1  341.78  5314.1  348.56  5333.8  349.46  5384.1  353.36  5429.9  353.62
#Mann= 8 ,-1 , 0
  4519.5     .16       0  4666.2     .08       0  4911.6     .16       0
  4994.9     .07       0  5000.9     .16       0  5020.5     .05       0
  5235.7     .08       0  5333.8     .05       0
Bank Sta=4916.9,5039.9
XS Rating Curve= 0 ,0
Exp/Cntr=0.3,0.1

Type RM Length L Ch R = 1 ,11170   ,500,500,500
BEGIN DESCRIPTION:
UNNAMED TRIBUTARY 1 TO BLISS CR 24.0
END DESCRIPTION:
XS GIS Cut Line= 3
      3629599.61     10519710.18      3629449.61     10519260.19
       3629199.6     10519010.18
#Sta/Elev= 30
    4515  369.07  4557.2  364.96  4567.7  361.47  4578.2  359.76  4618.3   356.8
  4683.6  347.83  4736.4  343.43  4789.1  337.22  4841.8  333.39  4852.3  330.25
  4867.2  328.42  4880.9  325.21  4883.7  324.71  4886.9  325.21  4894.5  330.57
  4957.7  331.39  4968.3  328.63  4992.9   325.7  5003.5  325.87  5017.6     330
  5031.8   330.6  5045.9  332.83  5097.5  335.13  5116.6  336.67  5144.9  342.09
  5165.3  341.93  5187.3  341.49    5232  348.71  5272.2  353.22  5342.9  354.62
#Mann= 8 ,-1 , 0
    4515     .16       0  4618.3     .05       0  4867.2     .16       0
  4880.9     .07       0  4886.9     .16       0  5097.5     .05       0
  5165.3     .08       0    5232     .05       0
Bank Sta=4841.8,5031.8
XS Rating Curve= 0 ,0
Exp/Cntr=0.3,0.1

Type RM Length L Ch R = 1 ,10670   ,343,343,343
BEGIN DESCRIPTION:
UNNAMED TRIBUTARY 1 TO BLISS CR 23.0
END DESCRIPTION:
XS GIS Cut Line= 3
       3629949.6     10519660.15      3629899.61     10519310.19
      3629699.59     10519010.16
#Sta/Elev= 30
  4637.7  365.16  4647.8  364.38  4708.4  362.24  4728.6  358.77  4740.4   354.6
  4789.2  345.91  4799.3  340.76  4809.4   338.9  4819.5  340.91  4829.6  340.66
  4849.8     334  4880.1  331.73  4890.2  333.86  4900.3  332.59  4910.4   328.7
  4930.6  330.28  4940.7  328.72  4950.8  325.37  4981.1   324.5  4988.7  322.05
  4998.7  323.35  5001.7  321.61  5004.5  321.11  5007.7  321.61  5013.7   325.8
  5019.8  326.42  5142.9  327.37  5262.8  337.38  5293.2  341.17  5351.8  344.05
#Mann= 6 ,-1 , 0
  4637.7     .08       0  4647.8     .05       0  4740.4     .16       0
  5001.7     .07       0  5007.7     .16       0  5262.8     .05       0
Bank Sta=4940.7,5142.9
XS Rating Curve= 0 ,0
Exp/Cntr=0.3,0.1

Type RM Length L Ch R = 1 ,10327   ,55,55,55
BEGIN DESCRIPTION:
Mapping XS 8bf4eedb
END DESCRIPTION:
XS GIS Cut Line= 6
      3630671.18     10519436.91      3630391.63     10519162.57
      3630263.16     10519098.33      3630099.96      10519077.5
      3630016.63     10519037.57      3629756.18     10518922.97
#Sta/Elev= 30
    4240  353.94  4317.8  350.16  4330.7  347.42  4401.4  341.39  4422.7  341.22
  4436.8   344.4  4454.2  342.48  4514.6  339.23  4535.8  339.72  4542.9  336.98
  4592.4  336.97  4629.8   334.4  4688.6  333.63  4774.5   327.7    4964  325.16
  4973.7  325.44  4984.6  323.59  4990.8  321.38  4993.3  318.67  4996.1  318.17
  4999.3  318.67  5006.8  321.87  5041.8  323.39  5059.6  327.17  5080.1  328.48
  5181.8  340.47  5187.3  338.95  5280.3     344  5292.5  343.13  5316.8  342.11
#Mann= 8 ,-1 , 0
    4240     .08       0  4317.8     .05       0  4454.2     .16       0
    4964     .12       0  4993.3     .07       0  4999.3     .12       0
  5080.1     .05       0  5292.5      .1       0
#XS Ineff= 1 ,-1
 4712.73 4971.14  329.27
Permanent Ineff=
       F
Bank Sta=4973.7,5059.6
XS Rating Curve= 0 ,0
Exp/Cntr=0.3,0.1

Type RM Length L Ch R = 1 ,10272   ,520,520,520
BEGIN DESCRIPTION:
UNNAMED TRIBUTARY 1 TO BLISS CR 22.0
END DESCRIPTION:
XS GIS Cut Line= 6
      3630780.48     10519315.33      3630553.09     10519207.71
      3630422.88     10519053.19      3630292.67     10519023.68
      3630079.13     10519008.05      3629745.82     10518888.27
#Sta/Elev= 30
  4167.4   350.8  4216.3  348.16  4261.8  343.22    4279  343.67  4290.1  340.33
  4330.1  340.14    4400  336.44    4448   334.4    4455  332.92  4526.1   331.6
    4621  325.76    4745  324.41  4753.6  323.38  4876.7  323.66  4980.8  324.67
  4997.1  320.42  4999.8  319.92  5003.1  320.42  5011.3  322.57  5035.4  324.05
  5039.8  326.26  5080.4  329.03  5091.6  331.64  5153.5  334.99  5179.1  338.07
  5184.4  336.71  5223.7  340.36  5266.2  342.35  5287.2  341.03  5323.2  343.26
#Mann= 7 ,-1 , 0
  4167.4     .05       0    4400     .16       0  4876.7     .12       0
  4997.1     .07       0  5003.1     .12       0  5080.4     .05       0
  5287.2      .1       0
#XS Ineff= 1 ,-1
 4361.14 4941.82329.2713
Permanent Ineff=
       F
Bank Sta=4980.8,5039.8
XS Rating Curve= 0 ,0
Exp/Cntr=0.3,0.1

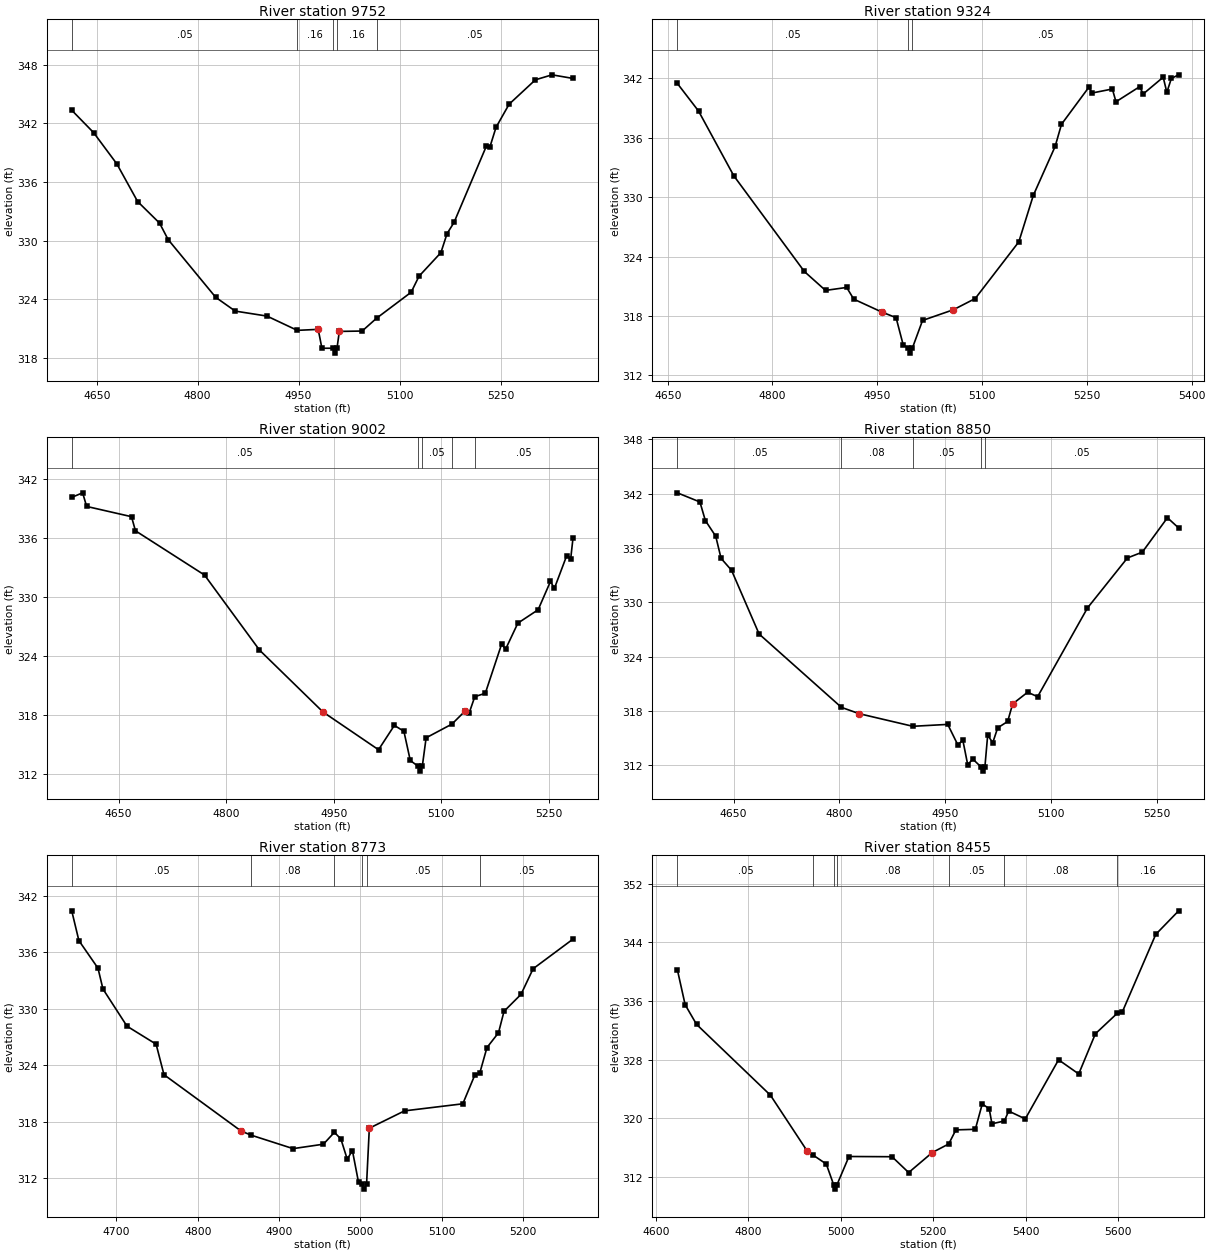
Type RM Length L Ch R = 1 ,9752    ,428,428,428
BEGIN DESCRIPTION:
UNNAMED TRIBUTARY 1 TO BLISS CR 21.0
END DESCRIPTION:
XS GIS Cut Line= 3
      3630849.57     10518960.17      3630499.61     10518810.19
       3630399.6     10518460.15
#Sta/Elev= 30
  4612.9  343.33  4645.5  341.03    4680  337.83  4710.8  333.99  4743.4  331.78
  4756.1   330.1  4826.8  324.19  4855.8  322.78    4903  322.27    4948  320.81
  4979.1  320.91  4984.6  318.98    5001  318.98  5003.8  318.48    5007  318.98
  5010.5   320.7  5044.4  320.74  5065.8  322.05  5117.2  324.71  5128.9  326.35
  5161.4  328.76  5170.5   330.7  5180.9  331.85    5229  339.67  5234.2  339.57
  5243.3  341.58  5262.8  343.95  5301.8  346.44  5326.5  346.95  5357.7  346.58
#Mann= 5 ,-1 , 0
  4612.9     .05       0    4948     .16       0    5001     .07       0
    5007     .16       0  5065.8     .05       0
Bank Sta=4979.1,5010.5
XS Rating Curve= 0 ,0
Exp/Cntr=0.3,0.1

Type RM Length L Ch R = 1 ,9324    ,322,322,322
BEGIN DESCRIPTION:
UNNAMED TRIBUTARY 1 TO BLISS CR 20.0
END DESCRIPTION:
XS GIS Cut Line= 3
      3630899.61     10518910.19      3630849.61     10518560.19
      3630499.57     10518460.18
#Sta/Elev= 30
  4663.8  341.47  4694.1  338.69  4744.6  332.15  4845.6  322.49  4875.9  320.58
  4906.2  320.88  4916.3   319.7  4956.7  318.39  4976.9  317.83    4987  315.11
  4994.2  314.75  4996.9  314.25  5000.2  314.75  5014.8  317.55    5059  318.63
  5090.2  319.76  5152.6  325.48  5173.4  330.18  5204.6  335.11  5213.7  337.35
  5252.7  341.07  5257.9  340.51  5286.5  340.91  5291.7  339.62  5325.5  341.14
  5330.7  340.41  5359.3   342.1  5364.5  340.57    5371  341.98  5381.4  342.34
#Mann= 3 ,-1 , 0
  4663.8     .05       0  4994.2     .03       0  5000.2     .05       0
Bank Sta=4956.7,5059
XS Rating Curve= 0 ,0
Exp/Cntr=0.3,0.1

Type RM Length L Ch R = 1 ,9002    ,152,152,152
BEGIN DESCRIPTION:
Mapping XS 898f2991
END DESCRIPTION:
XS GIS Cut Line= 2
      3631212.13     10518726.84      3630911.87     10518095.07
#Sta/Elev= 30
  4584.5  340.11  4599.7  340.57  4605.3  339.19  4667.9  338.15  4673.4  336.72
  4769.8  332.23  4846.5  324.62  4935.1  318.34  5012.6  314.51  5034.7  316.98
    5048  316.38  5056.9  313.42  5067.7  312.84  5070.5  312.34  5073.7  312.84
    5079  315.72    5115  317.11  5133.3  318.43  5138.9   318.2  5146.9  319.89
  5161.6  320.24  5184.3  325.21  5189.9  324.71    5207  327.35  5235.3  328.71
  5252.5  331.58    5258  330.88  5275.2   334.2  5280.7  333.85    5284  336.01
#Mann= 5 ,-1 , 0
  4584.5     .05       0  5067.7     .03       0  5073.7     .05       0
    5115     .16       0  5146.9     .05       0
Bank Sta=4935.1,5133.3
XS Rating Curve= 0 ,0
Exp/Cntr=0.3,0.1

Type RM Length L Ch R = 1 ,8850    ,77,77,77
BEGIN DESCRIPTION:
UNNAMED TRIBUTARY 1 TO BLISS CR 19.0
END DESCRIPTION:
XS GIS Cut Line= 5
       3631495.1     10518438.61      3631311.07      10518346.6
      3631205.17     10518329.24      3631146.14     10518299.72
      3630916.97     10518060.13
#Sta/Elev= 30
  4570.3  342.08  4602.3  341.07    4610  339.02  4624.7  337.29  4632.3  334.84
  4647.1  333.53  4686.2  326.49  4802.9  318.39  4828.2  317.69  4904.1   316.3
  4953.6  316.51  4967.8  314.26    4975  314.76  4981.9  312.06  4989.1  312.68
  5000.3  311.85    5003  311.35  5006.3  311.85  5010.2  315.32  5017.4  314.49
  5024.4  316.13  5038.5  316.83  5045.6  318.77  5066.8  320.06    5081  319.57
  5151.7  329.37  5208.3  334.89  5229.4  335.53    5265  339.33  5280.9   338.2
#Mann= 5 ,-1 , 0
  4570.3     .05       0  4802.9     .08       0  4904.1     .05       0
  5000.3     .04       0  5006.3     .05       0
Bank Sta=4828.2,5045.6
XS Rating Curve= 0 ,0
Exp/Cntr=0.3,0.1

Type RM Length L Ch R = 1 ,8773    ,318,318,318
BEGIN DESCRIPTION:
Mapping XS 6cab0435
END DESCRIPTION:
XS GIS Cut Line= 6
      3631486.44     10518357.03      3631392.67     10518291.04
      3631236.42     10518270.21      3631184.34     10518249.37
      3631132.25      10518183.4      3630964.19     10518067.32
#Sta/Elev= 30
    4645   340.4  4653.8  337.24  4677.3  334.31  4683.4   332.1    4713  328.15
  4748.8  326.24  4758.5     323  4853.5  317.01  4866.1  316.57  4917.3  315.15
  4954.6  315.62  4968.1  316.88  4976.1  316.18  4983.9  314.03  4990.3  314.94
  4997.8  311.58  5001.7  311.35  5004.5  310.85  5007.7  311.35  5011.1  317.32
  5054.4  319.16  5126.1  319.91    5141  322.99    5147  323.18  5155.8  325.88
    5170  327.45  5176.8  329.73  5197.7  331.53  5212.6  334.25  5261.7   337.4
#Mann= 6 ,-1 , 0
    4645     .05       0  4866.1     .08       0  4968.1     .05       0
  5001.7     .04       0  5007.7     .05       0    5147     .05       0
Bank Sta=4853.5,5011.1
XS Rating Curve= 0 ,0
Exp/Cntr=0.3,0.1

Type RM Length L Ch R = 1 ,8455    ,469,469,469
BEGIN DESCRIPTION:
UNNAMED TRIBUTARY 1 TO BLISS CR 18.0
END DESCRIPTION:
XS GIS Cut Line= 3
      3631499.61      10518360.2      3631399.61     10518010.19
      3630799.63     10517610.21
#Sta/Elev= 30
  4646.1  340.28    4663  335.49  4687.7  332.81  4847.6  323.15  4926.9  315.56
  4940.7  314.95  4968.5  313.76    4985  310.84  4987.8  310.34    4991  310.84
  5017.6  314.79  5110.8  314.76  5146.8   312.6  5197.9  315.33  5233.5   316.5
    5249  318.42  5291.1   318.5  5306.1  321.96  5321.1  321.31  5327.1  319.25
  5354.1  319.64  5363.2  320.99  5399.2  319.92  5471.3  327.98  5514.9  326.05
    5551  331.53  5598.4  334.33  5609.5  334.54  5681.7  345.09  5731.2   348.3
#Mann= 7 ,-1 , 0
  4646.1     .05       0  4940.7     .08       0    4985     .07       0
    4991     .08       0  5233.5     .05       0  5354.1     .08       0
  5598.4     .16       0
Bank Sta=4926.9,5197.9
XS Rating Curve= 0 ,0
Exp/Cntr=0.3,0.1

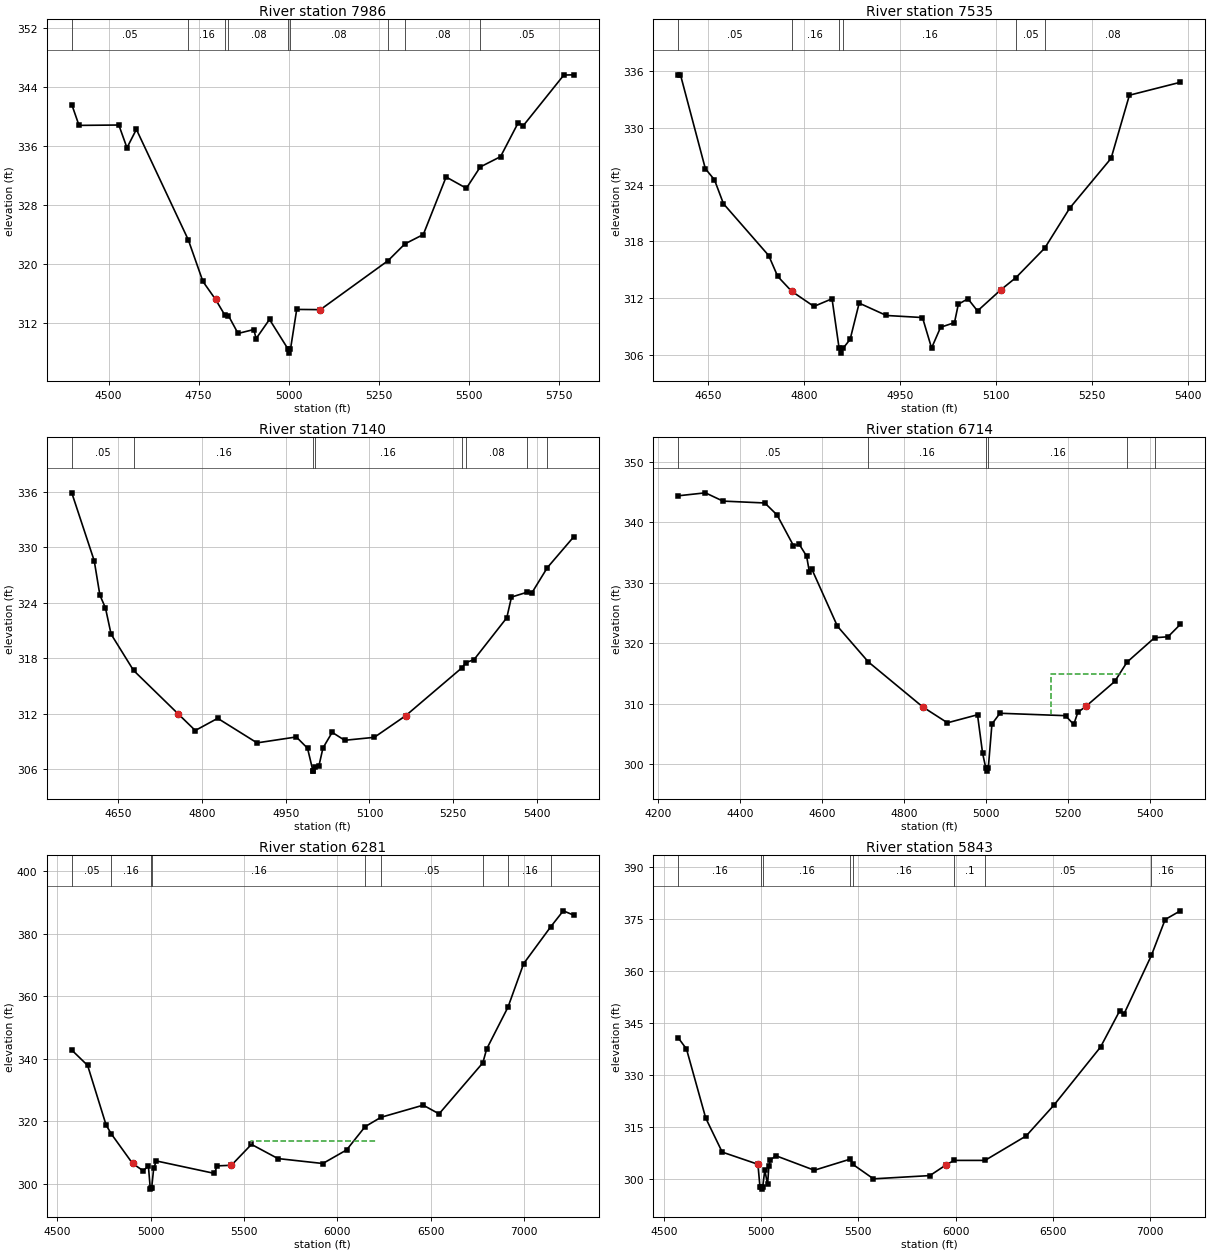
Type RM Length L Ch R = 1 ,7986    ,451,451,451
BEGIN DESCRIPTION:
UNNAMED TRIBUTARY 1 TO BLISS CR 17.0
END DESCRIPTION:
XS GIS Cut Line= 3
      3631793.46     10518269.78      3631605.96     10517422.56
      3631439.72     10516923.85
#Sta/Elev= 30
    4398  341.64  4418.1  338.81  4528.6  338.86  4551.2  335.77  4577.3  338.27
  4721.4  323.28    4762  317.63    4797   315.2  4822.8  313.07  4832.7     313
  4859.5  310.58  4903.1  311.11  4909.7  309.89  4946.8  312.48  4998.9  308.41
  5001.6  307.91  5004.9  308.41  5022.3  313.84  5087.9  313.81  5275.9  320.46
  5322.5  322.73  5373.6     324  5436.9  331.81  5493.1  330.28  5531.7  333.17
    5588  334.57  5637.1  339.18  5651.2  338.78  5763.6  345.64  5791.4  345.67
#Mann= 9 ,-1 , 0
    4398     .05       0  4721.4     .16       0  4822.8     .05       0
  4832.7     .08       0  4998.9     .07       0  5004.9     .08       0
  5275.9     .05       0  5322.5     .08       0  5531.7     .05       0
Bank Sta=4797,5087.9
XS Rating Curve= 0 ,0
Exp/Cntr=0.3,0.1

Type RM Length L Ch R = 1 ,7535    ,395,395,395
BEGIN DESCRIPTION:
UNNAMED TRIBUTARY 1 TO BLISS CR 16.0
END DESCRIPTION:
XS GIS Cut Line= 3
       3632299.6     10517760.18      3631999.61     10517460.19
      3631799.61     10517160.19
#Sta/Elev= 30
  4603.8  335.64  4607.3  335.64  4646.2  325.69  4660.4  324.52  4674.5  321.98
  4745.2  316.49  4759.3  314.28    4781  312.71  4815.9   311.1  4844.2  311.91
  4855.3  306.65  4858.1  306.15  4861.3  306.65  4872.5  307.61  4886.6  311.45
  4929.1  310.14  4985.6  309.92  4999.8  306.69  5013.9  308.89  5035.6  309.38
  5041.6  311.33  5056.6  311.91  5071.6  310.62  5107.7  312.84  5131.8  314.16
  5176.7  317.28  5215.8  321.52  5280.4  326.79    5309  333.48  5388.6  334.85
#Mann= 6 ,-1 , 0
  4603.8     .05       0    4781     .16       0  4855.3     .07       0
  4861.3     .16       0  5131.8     .05       0  5176.7     .08       0
Bank Sta=4781,5107.7
XS Rating Curve= 0 ,0
Exp/Cntr=0.3,0.1

Type RM Length L Ch R = 1 ,7140    ,426,426,426
BEGIN DESCRIPTION:
UNNAMED TRIBUTARY 1 TO BLISS CR 15.0
END DESCRIPTION:
XS GIS Cut Line= 3
      3632399.61     10517710.23      3632349.61     10517260.19
      3631949.64      10517060.2
#Sta/Elev= 30
  4566.4  335.92  4606.7  328.55  4616.8  324.84  4626.8  323.45  4636.9  320.61
  4677.1  316.69  4757.6  311.95  4787.8  310.18    4828   311.5  4898.5  308.84
  4968.9  309.48    4989  308.26  4998.8  305.78  4999.3  305.78  5002.1  306.28
  5009.2  306.29  5016.7  308.29  5033.2  309.98  5055.6  309.12  5108.7  309.44
  5164.9  311.78  5265.2  316.94  5273.4  317.54  5287.5  317.86  5346.2  322.39
  5354.6  324.63  5381.8  325.14    5391  325.07  5418.9  327.82  5466.4  331.17
#Mann= 8 ,-1 , 0
  4566.4     .05       0  4677.1     .16       0  4999.3     .07       0
  5002.1     .16       0  5265.2     .05       0  5273.4     .08       0
  5381.8     .05       0  5418.9     .08       0
Bank Sta=4757.6,5164.9
XS Rating Curve= 0 ,0
Exp/Cntr=0.3,0.1

Type RM Length L Ch R = 1 ,6714    ,433,433,433
BEGIN DESCRIPTION:
UNNAMED TRIBUTARY 1 TO BLISS CR 14.0
END DESCRIPTION:
XS GIS Cut Line= 3
      3633321.27     10517242.02      3632599.61     10516960.19
      3632149.65     10516960.19
#Sta/Elev= 30
  4249.6  344.42  4315.8  344.91  4358.7  343.54  4460.8  343.23  4490.6  341.25
  4530.5  336.19  4544.9  336.37  4562.7  334.43  4569.4  331.86  4574.8  332.38
  4637.9  322.83  4713.3  316.92  4846.4  309.45  4906.3  306.84  4979.6  308.17
  4992.1  301.76  4999.9  299.34  5002.6  298.84  5005.9  299.34  5014.8  306.63
  5034.3  308.42  5194.3  308.02  5214.3  306.56  5224.3  308.56  5244.3  309.58
  5314.3  313.68  5344.3  316.88  5411.5  320.92  5444.3  321.08  5474.3  323.13
#Mann= 6 ,-1 , 0
  4249.6     .05       0  4713.3     .16       0  4999.9     .07       0
  5005.9     .16       0  5344.3     .05       0  5411.5     .08       0
#XS Ineff= 1 ,-1
 5157.73 5340.68  314.86
Permanent Ineff=
       F
Bank Sta=4846.4,5244.3
XS Rating Curve= 0 ,0
Exp/Cntr=0.3,0.1

Type RM Length L Ch R = 1 ,6281    ,438,438,438
BEGIN DESCRIPTION:
UNNAMED TRIBUTARY 1 TO BLISS CR 13.0
END DESCRIPTION:
XS GIS Cut Line= 3
      3633249.58     10517010.16      3632949.61     10516710.19
      3631349.59     10515110.17
#Sta/Elev= 30
  4577.9  342.78  4662.7  337.88  4761.7  318.84    4790  315.97  4903.1  306.59
  4959.7  304.25    4988  305.72  4998.3  298.38  5001.6  298.88  5005.7  298.88
  5016.3  305.03  5030.4  307.38  5341.5   303.4  5355.7   305.8  5432.1     306
  5539.5  312.67    5681  308.14  5921.4  306.56  6048.6  310.89  6147.6  318.32
  6232.5  321.31  6458.8  325.19  6543.6  322.41  6777.8   338.7  6798.2  343.11
  6912.4  356.48  6996.2  370.38  7142.2  382.23  7208.3  387.24  7264.9  385.84
#Mann= 9 ,-1 , 0
  4577.9     .05       0    4790     .16       0  5001.6     .05       0
  5005.7     .16       0  6147.6     .16       0  6232.5     .05       0
  6777.8      .1       0  6912.4     .16       0  7142.2     .05       0
#XS Ineff= 1 ,-1
 5539.77 6204.55  313.64
Permanent Ineff=
       F
Bank Sta=4903.1,5432.1
XS Rating Curve= 0 ,0
Exp/Cntr=0.3,0.1

Type RM Length L Ch R = 1 ,5843    ,424,424,424
BEGIN DESCRIPTION:
UNNAMED TRIBUTARY 1 TO BLISS CR 12.0
END DESCRIPTION:
XS GIS Cut Line= 3
      3633499.59     10516660.17      3633199.61     10516360.19
      3631599.62      10514910.2
#Sta/Elev= 30
  4573.1  340.73  4615.5  337.52  4714.5  317.58  4799.3  307.76  4983.2  304.24
  4993.8  297.57  5001.4  297.57  5004.2  297.07  5007.4  297.57  5018.6  302.57
  5032.8  298.41  5039.6  303.81    5047  305.46  5075.4  306.71  5273.4  302.52
  5459.4  305.75  5470.9  304.24  5577.6  300.04  5868.1  300.98  5953.3  304.14
  5992.7  305.36  6151.6  305.36  6363.5  312.43  6505.5  321.26  6746.1  338.07
  6845.4  348.61  6866.3  347.56  7007.9  364.53  7078.6  374.88  7156.6  377.39
#Mann= 8 ,-1 , 0
  4573.1     .16       0  5001.4     .03       0  5007.4     .16       0
  5459.4     .08       0  5470.9     .16       0  5992.7      .1       0
  6151.6     .05       0  7007.9     .16       0
Bank Sta=4983.2,5953.3
XS Rating Curve= 0 ,0
Exp/Cntr=0.3,0.1

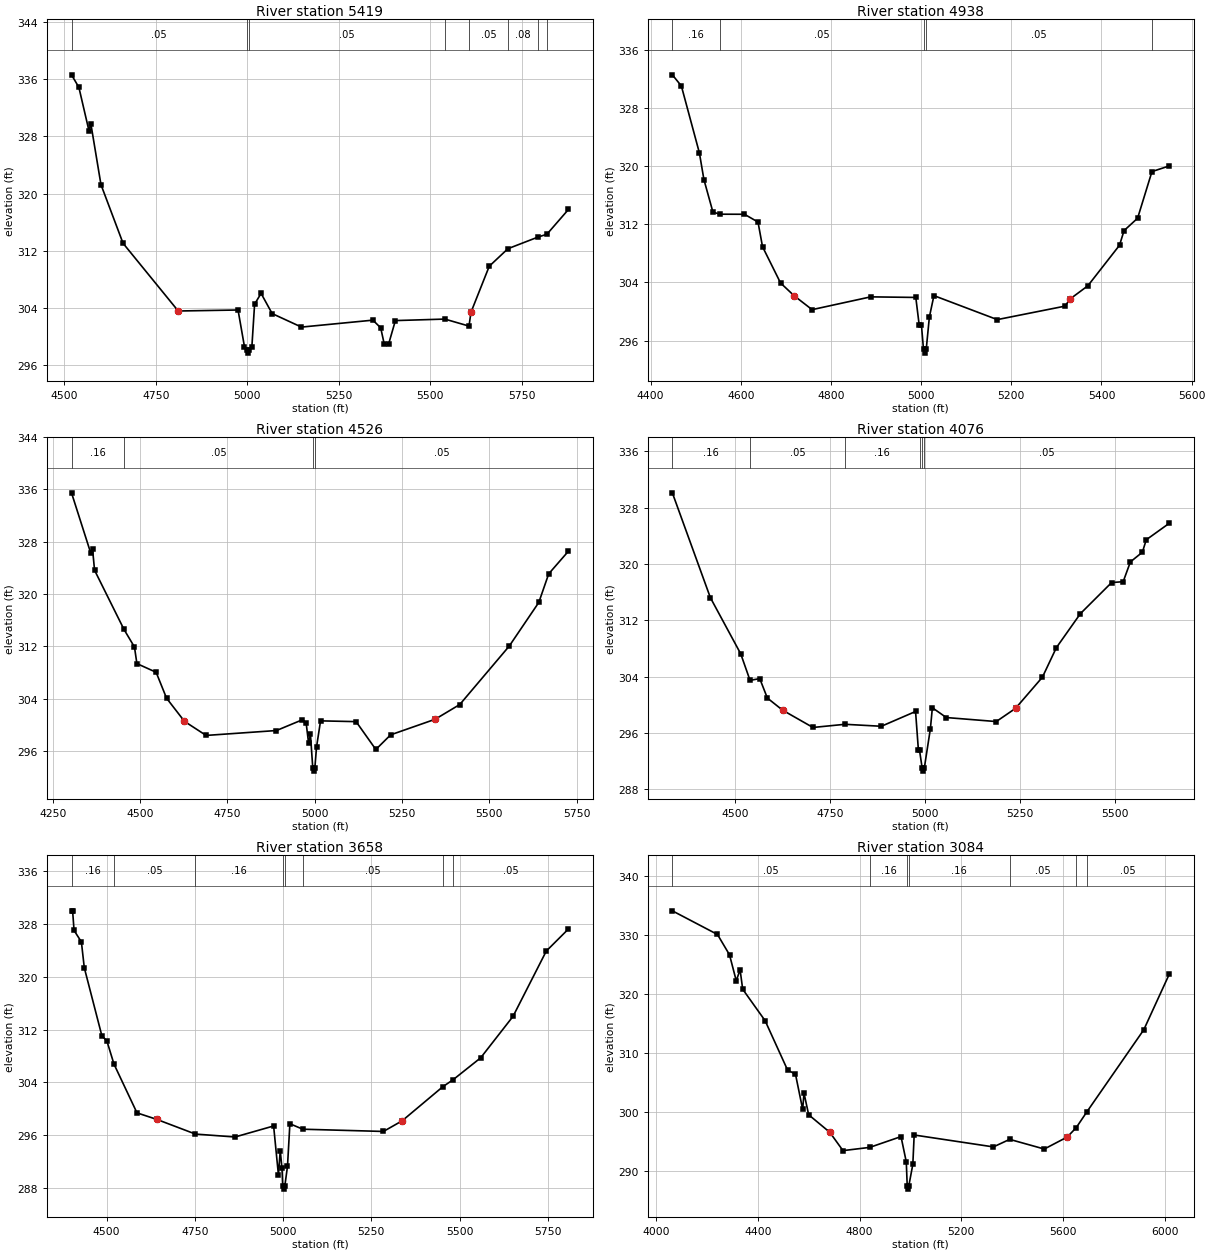
Type RM Length L Ch R = 1 ,5419    ,481,481,481
BEGIN DESCRIPTION:
UNNAMED TRIBUTARY 1 TO BLISS CR 11.0
END DESCRIPTION:
XS GIS Cut Line= 3
      3633499.61     10516610.15      3633549.61     10516110.19
      3633249.59     10515310.15
#Sta/Elev= 30
  4520.1  336.61  4540.2  334.86  4567.8  328.78  4572.8   329.8  4600.5  321.26
  4660.8  313.06  4811.5  303.59  4974.8  303.73  4992.4  298.58  4999.5   298.2
  5002.2   297.7  5005.5   298.2  5012.5  298.54    5020  304.55  5037.7  306.05
  5067.9  303.23    5148  301.34    5343  302.31  5364.3  301.24  5374.1  298.93
  5385.7  298.93  5404.4  302.25  5539.4  302.46  5605.4  301.48  5610.8  303.41
  5660.7  309.85  5711.7   312.3  5794.5  313.94  5818.1  314.32    5877  317.79
#Mann= 8 ,-1 , 0
  4520.1     .05       0  4999.5     .03       0  5005.5     .05       0
  5539.4     .08       0  5605.4     .05       0  5711.7     .08       0
  5794.5     .16       0  5818.1     .05       0
Bank Sta=4811.5,5610.8
XS Rating Curve= 0 ,0
Exp/Cntr=0.3,0.1

Type RM Length L Ch R = 1 ,4938    ,412,412,412
BEGIN DESCRIPTION:
UNNAMED TRIBUTARY 1 TO BLISS CR 10.0
END DESCRIPTION:
XS GIS Cut Line= 3
      3633899.61     10516360.23      3633899.61     10515810.19
      3633949.61     10515260.19
#Sta/Elev= 30
  4448.1  332.56  4468.1  331.03  4508.1  321.82  4518.1  318.16  4538.1  313.68
  4553.6  313.39  4608.1  313.38  4638.1  312.31  4648.1  308.92  4688.1  303.93
  4718.1  302.18  4758.1  300.26  4888.1  302.02  4988.1  301.94  4995.6  298.16
  5000.6  298.16  5005.2  294.78  5007.9  294.28  5011.2  294.78  5018.2  299.24
  5028.3  302.19  5168.8  298.89  5319.5  300.75  5329.5  301.69  5369.7  303.54
    5440  309.12    5450  311.13  5480.1  312.84  5511.9  319.25  5550.4  320.03
#Mann= 5 ,-1 , 0
  4448.1     .16       0  4553.6     .05       0  5005.2     .03       0
  5011.2     .05       0  5511.9     .08       0
Bank Sta=4718.1,5329.5
XS Rating Curve= 0 ,0
Exp/Cntr=0.3,0.1

Type RM Length L Ch R = 1 ,4526    ,450,450,450
BEGIN DESCRIPTION:
UNNAMED TRIBUTARY 1 TO BLISS CR 9.0
END DESCRIPTION:
XS GIS Cut Line= 3
      3633999.62     10516460.16      3634299.61     10515810.19
      3634799.63     10515310.16
#Sta/Elev= 30
    4304  335.49  4358.6  326.35  4364.1  326.94    4370  323.65  4454.1  314.61
  4484.3   311.9  4491.2  309.37  4546.3  308.04  4576.1  304.08  4627.5  300.53
  4689.4  298.38  4890.9  299.13  4965.2  300.78  4975.8  300.32  4982.7  297.26
  4988.2  298.54  4994.8  293.42  4997.6  292.92  5000.8  293.42  5005.6  296.61
  5017.1  300.61  5118.9  300.49  5175.4  296.23  5217.8  298.47  5345.1  300.85
  5415.8  303.11  5557.3  312.04  5642.1  318.73  5670.4   323.1    5727  326.57
#Mann= 4 ,-1 , 0
    4304     .16       0  4454.1     .05       0  4994.8     .03       0
  5000.8     .05       0
Bank Sta=4627.5,5345.1
XS Rating Curve= 0 ,0
Exp/Cntr=0.3,0.1

Type RM Length L Ch R = 1 ,4076    ,418,418,418
BEGIN DESCRIPTION:
UNNAMED TRIBUTARY 1 TO BLISS CR 8.0
END DESCRIPTION:
XS GIS Cut Line= 3
      3634699.61     10516660.24      3634699.61     10516010.19
      3634799.61     10515360.18
#Sta/Elev= 30
  4335.5  330.11  4435.5  315.23  4515.5  307.24  4539.9  303.48  4565.5  303.73
  4585.5  300.97  4625.5  299.25  4705.5  296.79  4789.7  297.24  4885.5  296.96
  4975.5  299.06    4983  293.56  4985.9  293.56  4992.7  291.09  4995.4  290.59
  4998.7  291.09  5014.6  296.64  5019.7  299.59  5056.4   298.2  5187.9  297.63
  5238.5   299.5  5309.3  303.93    5346  308.12  5409.2  312.95  5491.4  317.37
  5521.8  317.49  5540.8   320.3  5572.4  321.68  5582.5  323.44  5643.2  325.79
#Mann= 6 ,-1 , 0
  4335.5     .16       0  4539.9     .05       0  4789.7     .16       0
  4985.9     .05       0  4992.7     .03       0  4998.7     .05       0
Bank Sta=4625.5,5238.5
XS Rating Curve= 0 ,0
Exp/Cntr=0.3,0.1

Type RM Length L Ch R = 1 ,3658    ,574,574,574
BEGIN DESCRIPTION:
UNNAMED TRIBUTARY 1 TO BLISS CR 7.0
END DESCRIPTION:
XS GIS Cut Line= 3
      3634749.62     10516610.17      3635099.61     10516160.19
      3634849.61     10515360.21
#Sta/Elev= 30
  4400.4  330.03  4403.5  330.03  4407.6  327.06  4428.4  325.31  4436.6   321.4
  4486.3   311.1  4500.8  310.26  4520.7  306.78  4585.9  299.38    4642  298.39
  4751.7  296.16  4863.7  295.72  4973.1  297.39  4986.7  289.98  4991.9  293.67
  4996.7  290.99  4998.9  288.31  5001.6  287.81  5004.9  288.31  5012.4  291.27
  5019.2  297.73  5055.8   296.9  5284.3  296.56  5337.2  298.17  5452.2  303.33
  5482.5  304.44  5559.8  307.73  5651.5  314.02  5745.8  323.93  5808.6  327.28
#Mann= 8 ,-1 , 0
  4400.4     .16       0  4520.7     .05       0  4751.7     .16       0
  4998.9     .07       0  5004.9     .16       0  5055.8     .05       0
  5452.2     .16       0  5482.5     .05       0
Bank Sta=4642,5337.2
XS Rating Curve= 0 ,0
Exp/Cntr=0.3,0.1

Type RM Length L Ch R = 1 ,3084    ,361,361,361
BEGIN DESCRIPTION:
UNNAMED TRIBUTARY 1 TO BLISS CR 6.0
END DESCRIPTION:
XS GIS Cut Line= 3
      3635227.55     10517226.84      3635479.28     10516315.41
      3635399.61     10515310.21
#Sta/Elev= 30
  4064.1  334.15  4241.5  330.14  4288.9  326.69  4315.4  322.28  4330.4  324.17
  4340.7  320.85  4428.8  315.52  4517.1  307.15  4548.2  306.45  4576.5  300.47
  4581.7  303.23  4600.1  299.56  4683.1  296.59    4735  293.48  4840.2  294.03
  4963.2  295.86  4983.9  291.56  4987.6  287.45  4990.4  286.95  4993.6  287.45
  5009.6  291.15  5014.9  296.13  5326.4  294.11  5390.4  295.39  5526.5  293.75
  5616.8  295.79  5652.1  297.38  5694.1  300.07  5917.7  313.98    6018  323.42
#Mann= 7 ,-1 , 0
  4064.1     .05       0  4840.2     .16       0  4987.6     .07       0
  4993.6     .16       0  5390.4     .05       0  5652.1     .16       0
  5694.1     .05       0
Bank Sta=4683.1,5616.8
XS Rating Curve= 0 ,0
Exp/Cntr=0.3,0.1

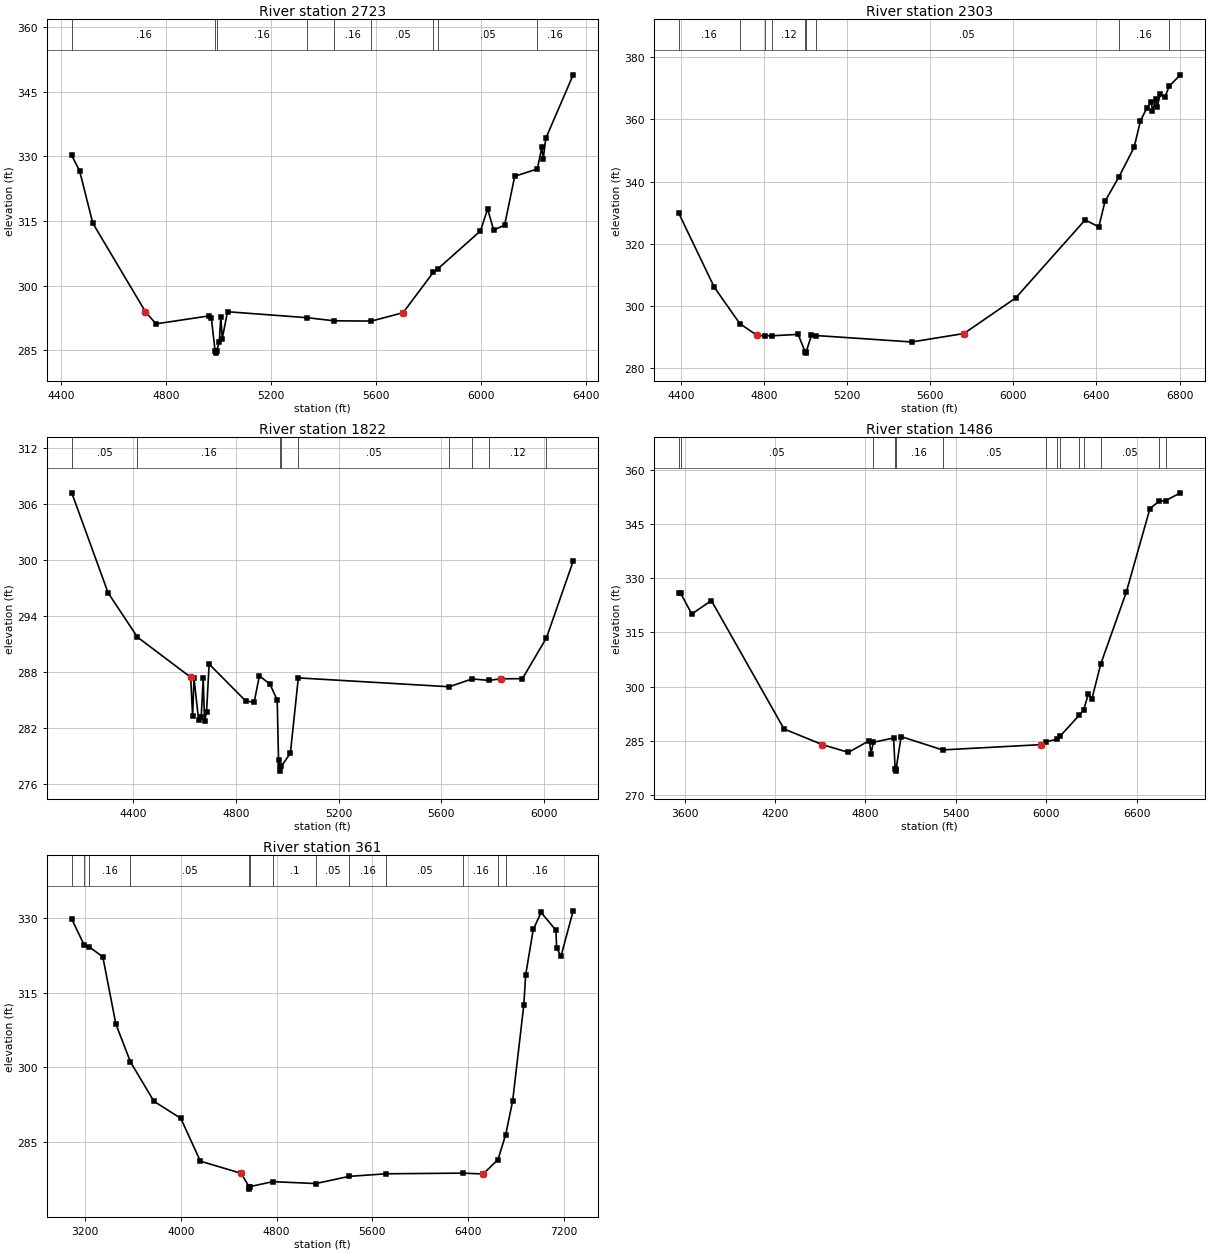
Type RM Length L Ch R = 1 ,2723    ,420,420,420
BEGIN DESCRIPTION:
UNNAMED TRIBUTARY 1 TO BLISS CR 5.0
END DESCRIPTION:
XS GIS Cut Line= 3
      3635749.61     10516960.21      3635799.61     10516410.19
      3635399.62     10515110.22
#Sta/Elev= 30
  4439.3  330.23  4469.4  326.63  4519.6   314.5  4720.5   293.9  4760.6   291.1
  4961.5  292.94  4971.5  292.52  4986.1   284.8  4988.8   284.3  4992.1   284.8
    5002  286.94  5007.9  292.76  5013.2  287.67  5033.4  293.92  5337.9  292.53
  5439.8  291.81  5582.4  291.75    5703   293.7  5818.7  303.11  5836.9  303.96
    5998   312.7  6025.4  317.78  6048.3   312.9  6090.2  314.06  6128.7   325.4
  6214.9  327.09  6232.1  332.11  6237.3  329.34  6247.1  334.19  6351.7  348.97
#Mann= 9 ,-1 , 0
  4439.3     .16       0  4986.1     .07       0  4992.1     .16       0
  5337.9     .05       0  5439.8     .16       0  5582.4     .05       0
  5818.7     .16       0  5836.9     .05       0  6214.9     .16       0
Bank Sta=4720.5,5703
XS Rating Curve= 0 ,0
Exp/Cntr=0.3,0.1

Type RM Length L Ch R = 1 ,2303    ,481,481,481
BEGIN DESCRIPTION:
UNNAMED TRIBUTARY 1 TO BLISS CR 4.0
END DESCRIPTION:
XS GIS Cut Line= 3
      3635799.62     10516960.17      3636199.61     10516510.19
      3635349.62     10514910.21
#Sta/Elev= 30
  4389.8   329.7    4560  305.93  4682.6  294.22  4764.8  290.43    4802  290.27
  4838.2  290.26  4963.8  290.72    4997  285.17  4999.8  284.67    5003  285.17
  5027.7  290.39    5049  290.35  5510.6  288.27  5761.9  290.99    6011  302.46
  6345.2  327.61  6411.1  325.39  6441.3  333.68  6506.7  341.32  6581.3  351.06
  6611.1  359.47  6641.6  363.59  6663.6  365.79  6669.2  362.69  6685.6  366.67
  6691.2  363.91  6707.5  368.22  6729.5  367.21  6749.9  370.72  6803.6   374.4
#Mann= 9 ,-1 , 0
  4389.8     .16       0  4682.6     .12       0    4802     .16       0
  4838.2     .12       0    4997     .07       0    5003     .12       0
    5049     .05       0  6506.7     .16       0  6749.9     .05       0
Bank Sta=4764.8,5761.9
XS Rating Curve= 0 ,0
Exp/Cntr=0.3,0.1

Type RM Length L Ch R = 1 ,1822    ,336,336,336
BEGIN DESCRIPTION:
UNNAMED TRIBUTARY 1 TO BLISS CR 3.0
END DESCRIPTION:
XS GIS Cut Line= 3
       3636449.6     10517310.23      3636649.61     10516510.19
      3635849.63     10515710.21
#Sta/Elev= 30
  4159.4  307.22  4301.2  296.51  4415.6  291.76  4623.3  287.46    4631  283.26
  4636.2  287.38  4654.2  282.88  4664.5  283.22  4672.3  287.34  4677.4  282.74
  4685.1  283.72  4695.4  288.87  4837.2  284.94  4870.7  284.76  4891.3   287.6
  4932.5  286.73  4960.9  285.01    4966  278.61  4970.8   277.9  4973.5   277.4
  4976.8   277.9  5012.3  279.33  5043.2  287.39  5631.9  286.44  5721.1  287.28
  5786.3  287.12  5832.6  287.29  5917.4  287.31  6011.1  291.68  6115.4   299.9
#Mann= 9 ,-1 , 0
  4159.4     .05       0  4415.6     .16       0  4970.8     .07       0
  4976.8     .16       0  5043.2     .05       0  5631.9     .12       0
  5721.1     .05       0  5786.3     .12       0  6011.1     .05       0
Bank Sta=4623.3,5832.6
XS Rating Curve= 0 ,0
Exp/Cntr=0.3,0.1

Type RM Length L Ch R = 1 ,1486    ,1125,1125,1125
BEGIN DESCRIPTION:
UNNAMED TRIBUTARY 1 TO BLISS CR 2.0
END DESCRIPTION:
XS GIS Cut Line= 4
       3636716.6     10517971.19      3636933.61     10516998.99
      3636916.24      10516148.3       3636056.9     10514941.74
#Sta/Elev= 30
  3562.6  325.86  3574.2  325.85    3648   320.1  3778.3  323.82  4260.4  288.34
  4514.4  284.02  4687.6  281.87  4827.6  285.14  4837.6  281.51  4853.8  284.67
  4987.6  285.84  4998.1  277.19  5000.9  276.69  5004.1  277.19  5037.6  286.23
    5313  282.55    5965  284.01  5998.4  284.79  6070.8  285.47  6094.7  286.43
  6219.8  292.14  6249.8  293.61  6279.7  297.99  6303.1  296.55  6363.2  306.36
  6531.7  326.09  6689.1  349.23  6750.3   351.3  6793.1  351.43  6890.9  353.59
#Mann= 14 ,-1 , 0
  3562.6     .08       0  3574.2     .05       0  4853.8     .16       0
  4998.1     .07       0  5004.1     .16       0    5313     .05       0
  5998.4     .16       0  6070.8     .12       0  6094.7     .16       0
  6219.8     .05       0  6249.8     .16       0  6363.2     .05       0
  6750.3     .16       0  6793.1     .05       0
Bank Sta=4514.4,5965
XS Rating Curve= 0 ,0
Exp/Cntr=0.3,0.1

Type RM Length L Ch R = 1 ,361     ,0,0,0
BEGIN DESCRIPTION:
UNNAMED TRIBUTARY 1 TO BLISS CR 1.0
END DESCRIPTION:
XS GIS Cut Line= 5
      3636855.47     10518144.84      3637358.95      10517354.9
      3637888.47     10516808.02      3637966.59     10516486.84
      3636777.37     10514681.31
#Sta/Elev= 30
  3088.3  329.79  3190.9  324.64  3232.2  324.24    3348  322.21  3457.1  308.71
  3579.3   301.1  3775.4  293.21  3999.7   289.8  4163.2   281.2  4502.7  278.77
  4570.5  276.09  4573.2  275.59  4576.5  276.09  4768.8  277.09  5127.6  276.71
  5406.7  278.15  5716.9  278.67  6357.3   278.8    6526  278.63  6649.6   281.5
  6714.7  286.51    6773   293.3  6866.4  312.59  6881.4  318.51  6944.9   327.7
  7010.9  331.11  7134.4  327.55  7140.4  324.03  7176.6  322.32  7278.8  331.44
#Mann= 13 ,-1 , 0
  3088.3     .05       0  3190.9     .08       0  3232.2     .16       0
  3579.3     .05       0  4570.5     .07       0  4576.5     .05       0
  4768.8      .1       0  5127.6     .05       0  5406.7     .16       0
  5716.9     .05       0  6357.3     .16       0  6649.6     .05       0
  6714.7     .16       0
Bank Sta=4502.7,6526
XS Rating Curve= 0 ,0
Exp/Cntr=0.3,0.1

Chan Stop Cuts=-1
Use User Specified Reach Order=0
Composite Channel Slope=5