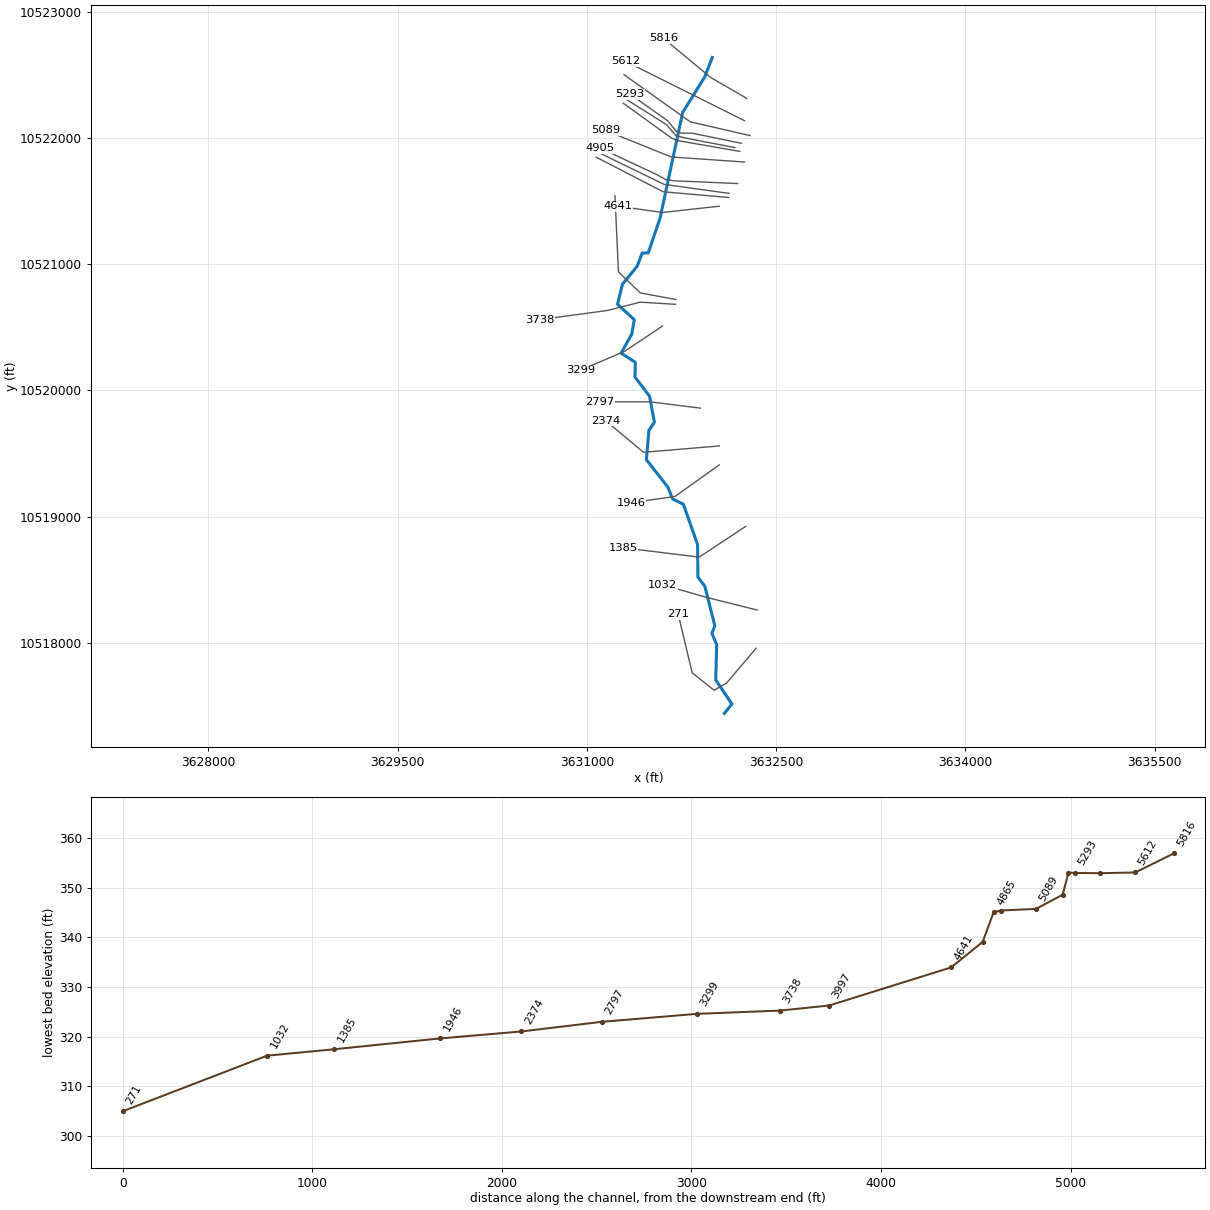
--- UNNAMED TRIBUTARY 1A TO BLISS CR.prj (project) ---

Proj Title=UNNAMED TRIBUTARY 1A TO BLISS CR Base Level Engineering
Current Plan=p01
Default Exp/Contr=0.3,0.1
English Units
Geom File=g01
Flow File=f01
Plan File=p01
Y Axis Title=Elevation
X Axis Title(PF)=Main Channel Distance
X Axis Title(XS)=Station
BEGIN DESCRIPTION:
UNNAMED TRIBUTARY 1A TO BLISS CR
END DESCRIPTION:
DSS Export Rating Curves= 0
DSS Export Rating Curve Sorted= 0
DSS Export Volume Flow Curves= 0
DXF OffsetX= 0
DXF OffsetY= 0
DXF ScaleX= 1
DXF ScaleY= 10

--- UNNAMED TRIBUTARY 1A TO BLISS CR.p01 (plan) ---

Plan Title=Multiple Run
Short Identifier=Multiple
Geom File=g01
Flow File=f01
Subcritical Flow
K Sum by GR= 0
Std Step Tol= 0.01
Critical Tol= 0.01
Num of Std Step Trials= 20
Max Error Tol= 0.3
Flow Tol Ratio= 0.001
Split Flow NTrial= 30
Split Flow Tol= 0.02
Split Flow Ratio= 0.02
Log Output Level= 0
Friction Slope Method= 1
Unsteady Friction Slope Method= 2
Unsteady Bridges Friction Slope Method= 1
Parabolic Critical Depth
Global Vel Dist=  1 , 1 , 1
Global Log Level= 0
CheckData=True
Encroach Param= -1, 0, 0, 0
BEGIN DESCRIPTION:
Multiple Run
END DESCRIPTION:

--- UNNAMED TRIBUTARY 1A TO BLISS CR.f01 (steady flow) ---

Flow Title=Multiple
Number of Profiles=7
Profile Names=10-year,25-year,50-year,1pct_min,100-year,1pct_plu,500-year
River Rch & RM= UNNAMED TRIBUTAR,Reach-1,5816
     301     384     449     386     521     705     697
River Rch & RM= UNNAMED TRIBUTAR,Reach-1,3738
     568     754     905     795    1075    1453    1507
Boundary for River Rch & Prof#=UNNAMED TRIBUTAR,Reach-1,1
Up Type=0
Dn Type=3
Dn Slope=0.005
Boundary for River Rch & Prof#=UNNAMED TRIBUTAR,Reach-1,2
Up Type=0
Dn Type=3
Dn Slope=0.005
Boundary for River Rch & Prof#=UNNAMED TRIBUTAR,Reach-1,3
Up Type=0
Dn Type=3
Dn Slope=0.005
Boundary for River Rch & Prof#=UNNAMED TRIBUTAR,Reach-1,4
Up Type=0
Dn Type=3
Dn Slope=0.005
Boundary for River Rch & Prof#=UNNAMED TRIBUTAR,Reach-1,5
Up Type=0
Dn Type=3
Dn Slope=0.005
Boundary for River Rch & Prof#=UNNAMED TRIBUTAR,Reach-1,6
Up Type=0
Dn Type=3
Dn Slope=0.005
Boundary for River Rch & Prof#=UNNAMED TRIBUTAR,Reach-1,7
Up Type=0
Dn Type=3
Dn Slope=0.005

--- UNNAMED TRIBUTARY 1A TO BLISS CR.g01 (geometry) ---

Geom Title=Existing Conditions
Program Version=4.10

River Reach=UNNAMED TRIBUTAR,Reach-1
Reach XY= 30
      3631994.56     10522638.99      3631934.25       10522484.
      3631759.75       10522203.      3631580.25       10521364.
      3631486.75       10521090.      3631439.25       10521089.
      3631398.75       10520984.      3631282.75       10520842.
       3631243.5       10520683.        3631376.       10520561.
       3631356.5       10520446.        3631272.       10520296.
       3631384.5       10520223.      3631381.75       10520106.
      3631497.25       10519954.      3631535.75       10519749.
      3631492.25       10519684.      3631472.25       10519451.
      3631641.25       10519236.        3631680.       10519140.
       3631765.5       10519098.      3631877.75       10518779.
      3631880.75       10518520.      3631935.25       10518449.
      3632014.75       10518134.      3631991.25       10518075.
      3632029.25       10517986.      3632021.75       10517706.
      3632149.75       10517515.        3632090.       10517441.

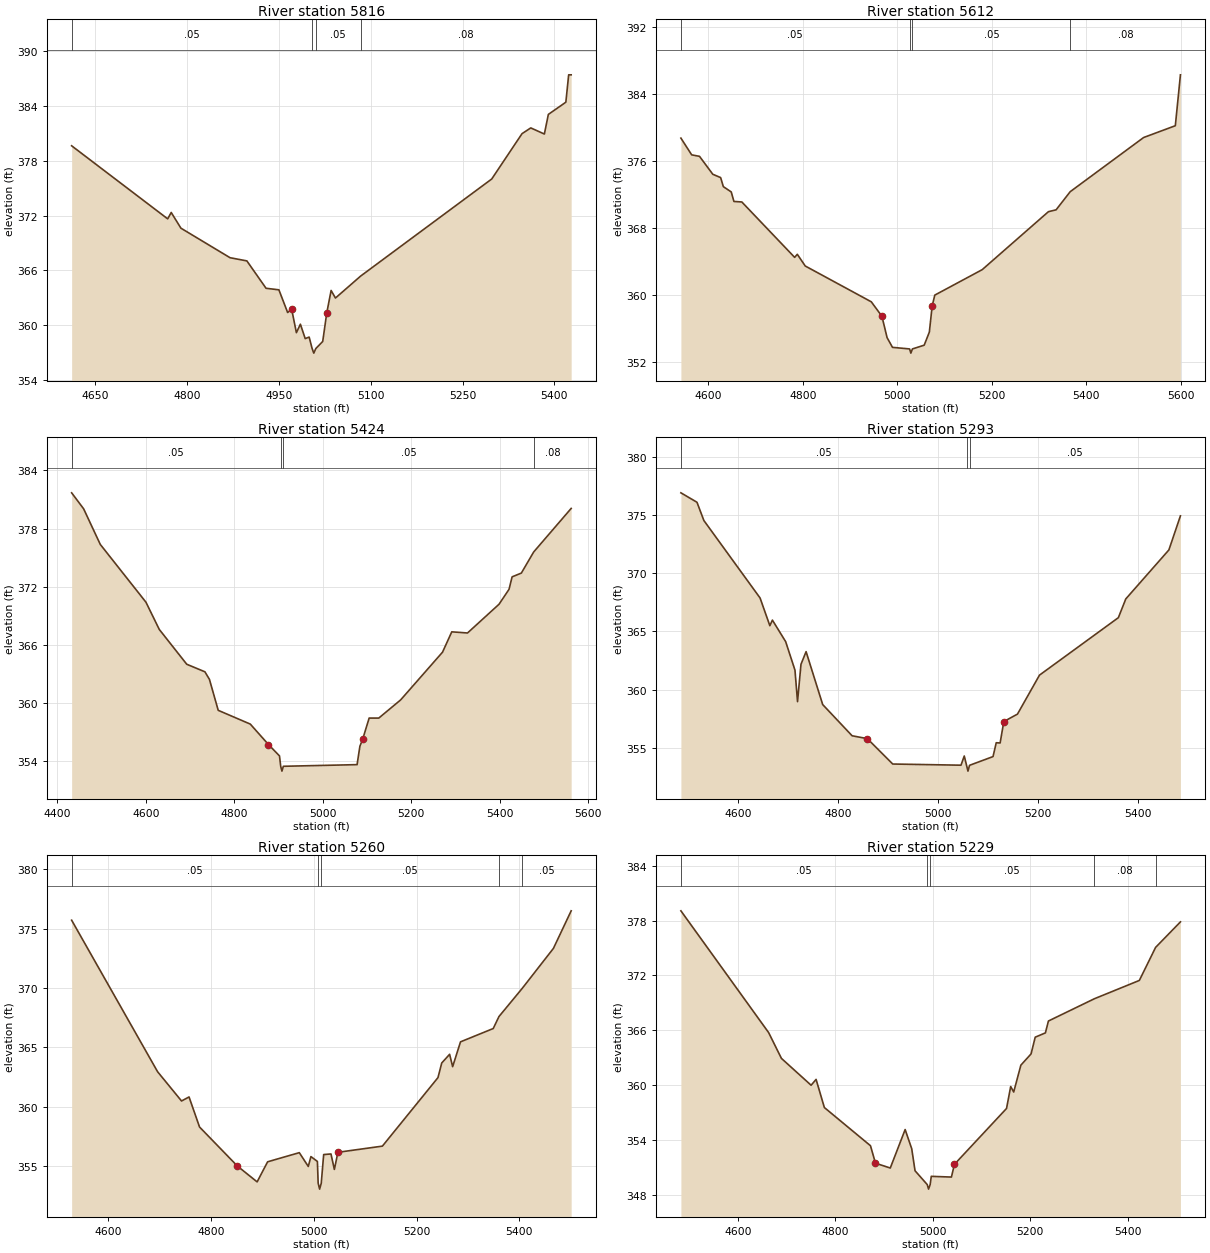
Type RM Length L Ch R = 1 ,5816    ,204,204,204
BEGIN DESCRIPTION:
UNNAMED TRIBUTARY 1A TO BLISS CR 12.0
END DESCRIPTION:
XS GIS Cut Line= 3
      3632267.34     10522314.74       3631982.6     10522479.68
      3631607.59     10522790.45
#Sta/Elev= 30
  4611.3  379.66  4768.2  371.65    4774  372.35  4789.8  370.63  4870.1  367.39
  4897.6  367.04  4928.9  364.04  4949.9  363.87  4964.2  361.38  4970.7  361.76
  4978.5  359.17    4985   360.1  4992.9  358.52  4999.3  358.69  5004.2  357.43
  5006.9  356.93  5010.2  357.43  5021.5  358.21    5028   361.3  5035.2   363.8
  5042.3  362.97  5083.5  365.38  5297.6  376.02  5347.1  380.99  5361.4  381.62
  5383.6  380.95  5390.1   383.1  5418.7  384.44  5423.3  387.44  5427.4  387.44
#Mann= 4 ,-1 , 0
  4611.3     .05       0  5004.2     .03       0  5010.2     .05       0
  5083.5     .08       0
Bank Sta=4970.7,5028
XS Rating Curve= 0 ,0
Exp/Cntr=0.3,0.1

Type RM Length L Ch R = 1 ,5612    ,188,188,188
BEGIN DESCRIPTION:
Mapping XS e372cbae
END DESCRIPTION:
XS GIS Cut Line= 2
      3632249.98     10522137.66      3631304.22     10522609.67
#Sta/Elev= 30
  4542.2  378.78    4565  376.78  4581.6   376.6  4609.7  374.46  4626.3  374.06
    4632  372.98  4648.7  372.35  4654.4  371.21  4671.1  371.15  4782.9  364.53
  4788.5   364.9  4805.3   363.5  4945.1  359.22  4967.5   357.5  4978.5  354.94
  4989.9  353.78  5026.1  353.59  5028.8  353.09  5032.1  353.59    5057  354.04
  5067.9   355.6  5073.8  358.68  5079.4  360.02  5179.7  363.06  5319.9  369.99
  5336.1  370.21    5366  372.38  5521.3  378.85  5588.4  380.26  5599.2  386.34
#Mann= 4 ,-1 , 0
  4542.2     .05       0  5026.1     .03       0  5032.1     .05       0
    5366     .08       0
Bank Sta=4967.5,5073.8
XS Rating Curve= 0 ,0
Exp/Cntr=0.3,0.1

Type RM Length L Ch R = 1 ,5424    ,131,131,131
BEGIN DESCRIPTION:
Mapping XS 21307c9b
END DESCRIPTION:
XS GIS Cut Line= 3
      3632293.36     10522019.61       3631819.4     10522128.99
      3631295.11     10522502.24
#Sta/Elev= 30
    4432  381.69  4459.1  380.04  4496.8  376.36  4600.1  370.39  4630.2  367.58
  4692.4  363.98  4733.5   363.2  4743.7  362.42  4763.6  359.22  4836.1   357.8
  4877.2  355.69  4902.2  354.51  4904.9  353.44  4907.7  352.94  4910.9  353.44
  5077.7  353.61  5084.1  355.52  5090.2  356.21    5105  358.42  5126.8  358.42
  5176.3   360.3    5271  365.23  5291.9  367.33  5327.5  367.21  5398.8  370.18
  5421.4  371.72  5428.4  373.01  5449.3   373.4  5477.2  375.58    5562  380.08
#Mann= 4 ,-1 , 0
    4432     .05       0  4904.9     .03       0  4910.9     .05       0
  5477.2     .08       0
Bank Sta=4877.2,5090.2
XS Rating Curve= 0 ,0
Exp/Cntr=0.3,0.1

Type RM Length L Ch R = 1 ,5293    ,33,33,33
BEGIN DESCRIPTION:
Mapping XS 35581e4b
END DESCRIPTION:
XS GIS Cut Line= 6
      3632224.53     10521958.37       3631833.9      10522039.1
      3631749.27      10522039.1       3631708.9     10522053.42
       3631641.2     10522136.76      3631343.81     10522347.14
#Sta/Elev= 30
    4486  376.91  4518.1   376.1  4531.9  374.53  4644.2  367.87  4663.7  365.49
  4668.8  365.97  4695.3  364.12  4713.9  361.67    4719  358.96  4725.9  362.17
  4736.1  363.26  4769.3  358.71    4828  356.03  4858.6  355.78  4909.2   353.6
  5045.6   353.5  5052.1  354.29  5056.7  353.49  5059.5  352.99  5062.7  353.49
  5109.6  354.24    5116  355.43  5123.8  355.41  5131.1  357.25  5158.4  357.89
  5202.4  361.24    5360  366.18  5374.8  367.79  5460.9     372    5484  374.93
#Mann= 3 ,-1 , 0
    4486     .05       0  5056.7     .03       0  5062.7     .05       0
Bank Sta=4858.6,5131.1
XS Rating Curve= 0 ,0
Exp/Cntr=0.3,0.1

Type RM Length L Ch R = 1 ,5260    ,31,31,31
BEGIN DESCRIPTION:
Mapping XS 0761932e
END DESCRIPTION:
XS GIS Cut Line= 5
      3632173.77     10521924.51      3631789.63     10521998.74
       3631707.6     10522018.27      3631630.78     10522106.81
      3631310.45     10522308.64
#Sta/Elev= 30
  4529.3   375.7  4696.5  362.94    4743  360.48  4757.6  360.82    4778  358.29
  4851.7     355    4890  353.67  4910.4  355.36    4972  356.13  4989.5  354.97
  4994.6   355.8  5007.2  355.39  5008.7  353.56  5011.5  353.06  5014.7  353.56
  5019.4  355.97  5033.6  356.02  5040.2  354.72  5047.1  356.16  5133.6  356.68
  5241.7  362.45    5249  363.68  5264.3  364.41  5270.2  363.37  5285.5  365.46
  5349.1  366.58  5360.3  367.59  5405.5  369.96  5466.2  373.33  5500.7  376.49
#Mann= 5 ,-1 , 0
  4529.3     .05       0  5008.7     .03       0  5014.7     .05       0
  5360.3     .08       0  5405.5     .05       0
Bank Sta=4851.7,5047.1
XS Rating Curve= 0 ,0
Exp/Cntr=0.3,0.1

Type RM Length L Ch R = 1 ,5229    ,140,140,140
BEGIN DESCRIPTION:
Mapping XS 01e7f936
END DESCRIPTION:
XS GIS Cut Line= 4
       3632212.8     10521894.57      3631732.34      10521977.9
      3631675.05     10521997.44      3631288.59     10522276.26
#Sta/Elev= 30
  4483.2  379.06  4663.2  365.73  4689.4  362.91  4750.3  359.97  4760.5  360.61
  4777.5  357.53  4872.1  353.35  4882.3  351.44  4912.7  350.91  4943.2  355.12
  4956.7  353.02  4963.5  350.61  4988.5   349.1  4991.2   348.6  4994.5   349.1
  4996.8     350  5038.1  349.92  5044.4  351.32  5151.2  357.43  5159.7  359.83
  5165.9  359.23  5180.6  362.17  5201.5   363.4    5210  365.23  5230.9   365.7
  5237.1     367  5331.5  369.44  5423.6  371.44    5457  375.06  5507.9  377.85
#Mann= 5 ,-1 , 0
  4483.2     .05       0  4988.5     .03       0  4994.5     .05       0
  5331.5     .08       0    5457     .05       0
Bank Sta=4882.3,5044.4
XS Rating Curve= 0 ,0
Exp/Cntr=0.3,0.1

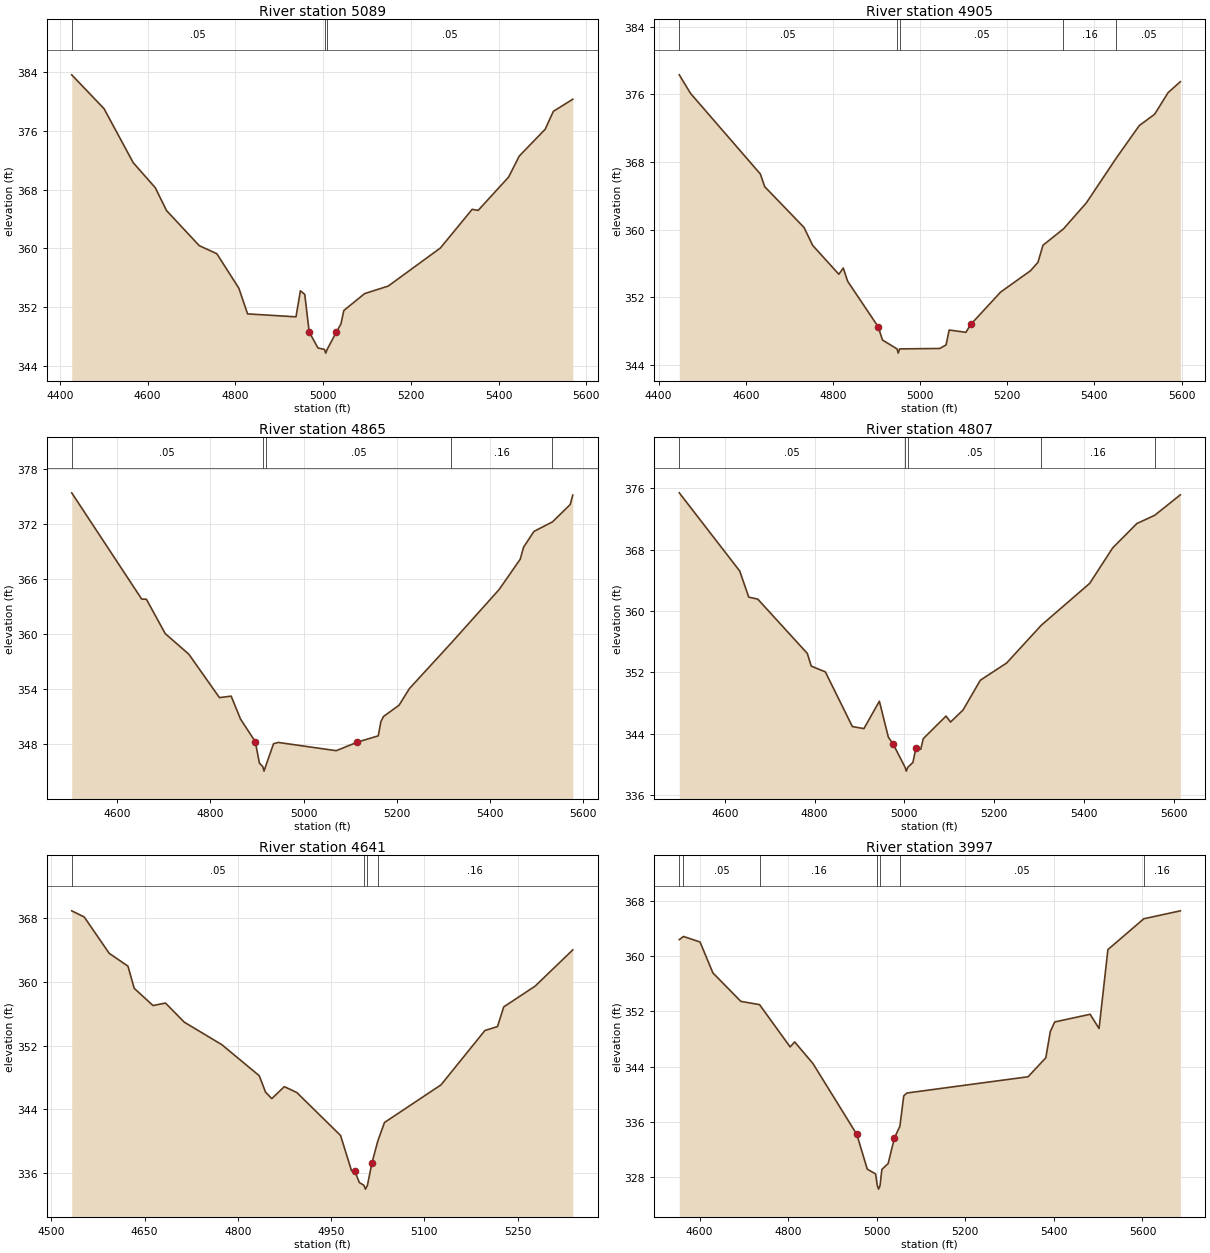
Type RM Length L Ch R = 1 ,5089    ,184,184,184
BEGIN DESCRIPTION:
UNNAMED TRIBUTARY 1A TO BLISS CR 11.0
END DESCRIPTION:
XS GIS Cut Line= 3
      3632249.58     10521810.19      3631668.99     10521850.43
      3631149.63     10522060.18
#Sta/Elev= 30
  4427.2  383.63  4500.9  379.02  4567.5  371.66  4617.6  368.27  4643.4  365.15
  4717.9  360.38    4758  359.28  4808.1  354.59  4828.1  351.09  4938.4  350.69
  4948.4  354.23  4958.4  353.74  4968.5  348.62  4988.5  346.45  5003.4  346.25
  5006.1  345.75  5009.4  346.25  5030.1  348.59  5040.9  349.73  5047.4  351.55
  5094.8  353.85  5148.7  354.88  5267.5  360.06  5339.9  365.32  5353.6  365.18
  5423.1  369.72  5447.2  372.57  5506.3  376.22    5525  378.66  5569.3  380.31
#Mann= 3 ,-1 , 0
  4427.2     .05       0  5003.4    .035       0  5009.4     .05       0
Bank Sta=4968.5,5030.1
XS Rating Curve= 0 ,0
Exp/Cntr=0.3,0.1

Type RM Length L Ch R = 1 ,4905    ,40,40,40
BEGIN DESCRIPTION:
Mapping XS ebceb186
END DESCRIPTION:
XS GIS Cut Line= 5
      3632195.42      10521639.8      3631691.98      10521661.5
      3631622.53     10521672.35      3631557.43     10521709.24
       3631104.2     10521921.76
#Sta/Elev= 30
  4447.6  378.31  4473.4  376.12  4633.6  366.59  4643.6  365.09  4733.7  360.28
  4753.7  358.15  4813.7  354.74  4823.8  355.48  4833.8  353.92  4903.8  348.55
  4913.8  346.97  4947.2  345.92  4949.9  345.42  4953.2  345.92  5045.1  345.97
  5059.6  346.38  5066.8  348.15  5105.2  347.88  5116.3  348.81  5184.7  352.63
  5253.2  355.15  5270.5  356.15    5282  358.17    5329   360.1  5381.4  363.17
  5450.4  368.49  5502.9  372.31  5538.1  373.65  5569.1  376.21  5597.2   377.5
#Mann= 5 ,-1 , 0
  4447.6     .05       0  4947.2    .035       0  4953.2     .05       0
    5329     .16       0  5450.4     .05       0
Bank Sta=4903.8,5116.3
XS Rating Curve= 0 ,0
Exp/Cntr=0.3,0.1

Type RM Length L Ch R = 1 ,4865    ,58,58,58
BEGIN DESCRIPTION:
Mapping XS 6263567f
END DESCRIPTION:
XS GIS Cut Line= 3
      3632128.21     10521561.67      3631611.68     10521633.29
      3631114.74     10521875.28
#Sta/Elev= 30
    4503  375.43    4653  363.84  4663.1  363.82  4703.5  360.07    4754  357.83
  4819.7  353.09  4844.8  353.25    4865  350.74  4896.5  348.29  4905.4  345.94
  4912.5  345.57  4915.3  345.07  4918.5  345.57  4935.7  348.06  4945.8   348.2
  5070.1   347.3  5115.2  348.23  5160.2  348.92  5165.8  350.47  5171.4  351.03
  5204.7  352.26    5227  354.08  5316.8  359.06  5419.4  364.89  5464.5  368.19
  5471.7   369.5  5493.9  371.22  5533.6  372.26  5571.6  374.15  5577.2  375.18
#Mann= 5 ,-1 , 0
    4503     .05       0  4912.5    .035       0  4918.5     .05       0
  5316.8     .16       0  5533.6     .05       0
Bank Sta=4896.5,5115.2
XS Rating Curve= 0 ,0
Exp/Cntr=0.3,0.1

Type RM Length L Ch R = 1 ,4807    ,166,166,166
BEGIN DESCRIPTION:
Mapping XS a9bd307d
END DESCRIPTION:
XS GIS Cut Line= 3
      3632123.83     10521529.12      3631605.17     10521574.69
      3631075.66     10521848.13
#Sta/Elev= 30
  4498.3  375.43    4633  365.22  4653.1  361.81  4673.2  361.55  4783.6  354.46
  4792.4   352.8  4823.8  352.05    4884  344.91  4909.7  344.64  4944.2  348.22
  4964.3  343.51  4974.3  342.69  5001.5  339.59  5004.2  339.09  5007.5  339.59
    5019  340.23  5025.4  342.06  5036.3  341.94    5042  343.33  5092.7  346.28
  5102.8   345.5  5130.6  347.07  5169.2  350.96  5227.8  353.21    5305  358.14
  5412.9  363.61  5464.1  368.24    5518  371.42  5557.6  372.49  5614.9  375.17
#Mann= 5 ,-1 , 0
  4498.3     .05       0  5001.5    .035       0  5007.5     .05       0
    5305     .16       0  5557.6     .05       0
Bank Sta=4974.3,5025.4
XS Rating Curve= 0 ,0
Exp/Cntr=0.3,0.1

Type RM Length L Ch R = 1 ,4641    ,644,644,644
BEGIN DESCRIPTION:
UNNAMED TRIBUTARY 1A TO BLISS CR 10.0
END DESCRIPTION:
XS GIS Cut Line= 3
      3632049.58     10521460.19      3631599.61     10521410.19
      3631249.61     10521460.19
#Sta/Elev= 30
  4532.6  368.95  4552.7  368.18  4592.9  363.61  4623.1  361.99  4633.2   359.2
  4663.4  357.04  4683.5  357.35  4713.7  354.95  4774.1  352.12  4834.4  348.21
  4844.5  346.15  4854.5  345.33  4874.7  346.84  4894.8   346.1  4965.2   340.7
  4982.8  336.27  4987.9  336.27  4995.4  334.78  5002.5  334.45  5005.3  333.95
  5008.5  334.45  5015.6  337.22  5025.3  340.04  5035.9  342.33  5126.8  347.06
  5197.5   353.9  5217.7  354.39  5227.8  356.87  5278.3  359.48  5338.9  364.04
#Mann= 4 ,-1 , 0
  4532.6     .05       0  5002.5    .035       0  5008.5     .05       0
  5025.3     .16       0
Bank Sta=4987.9,5015.6
XS Rating Curve= 0 ,0
Exp/Cntr=0.3,0.1

Type RM Length L Ch R = 1 ,3997    ,259,259,259
BEGIN DESCRIPTION:
UNNAMED TRIBUTARY 1A TO BLISS CR 9.0
END DESCRIPTION:
XS GIS Cut Line= 4
      3631705.73     10520720.71      3631424.48     10520772.79
      3631250.87     10520939.46      3631223.09     10521543.63
#Sta/Elev= 30
  4554.1  362.37  4563.6  362.83    4601  362.03    4630  357.56  4693.1  353.44
  4735.3  352.97  4804.4  346.85  4814.6  347.57  4855.9  344.45    4955  334.19
  4978.6  329.16  4997.4  328.47  5001.4  326.77  5004.1  326.27  5007.4  326.77
  5011.6  329.13  5025.7  329.96  5039.9  333.67  5052.3  335.38    5061  339.77
  5068.2  340.18  5341.8  342.53  5381.8  345.28  5391.9  349.07  5401.9  350.46
  5481.9  351.57    5502  349.51    5522  360.93    5603  365.39  5685.6  366.54
#Mann= 7 ,-1 , 0
  4554.1     .16       0  4563.6     .05       0  4735.3     .16       0
  5001.4     .07       0  5007.4     .16       0  5052.3     .05       0
    5603     .16       0
Bank Sta=4955,5039.9
XS Rating Curve= 0 ,0
Exp/Cntr=0.3,0.1

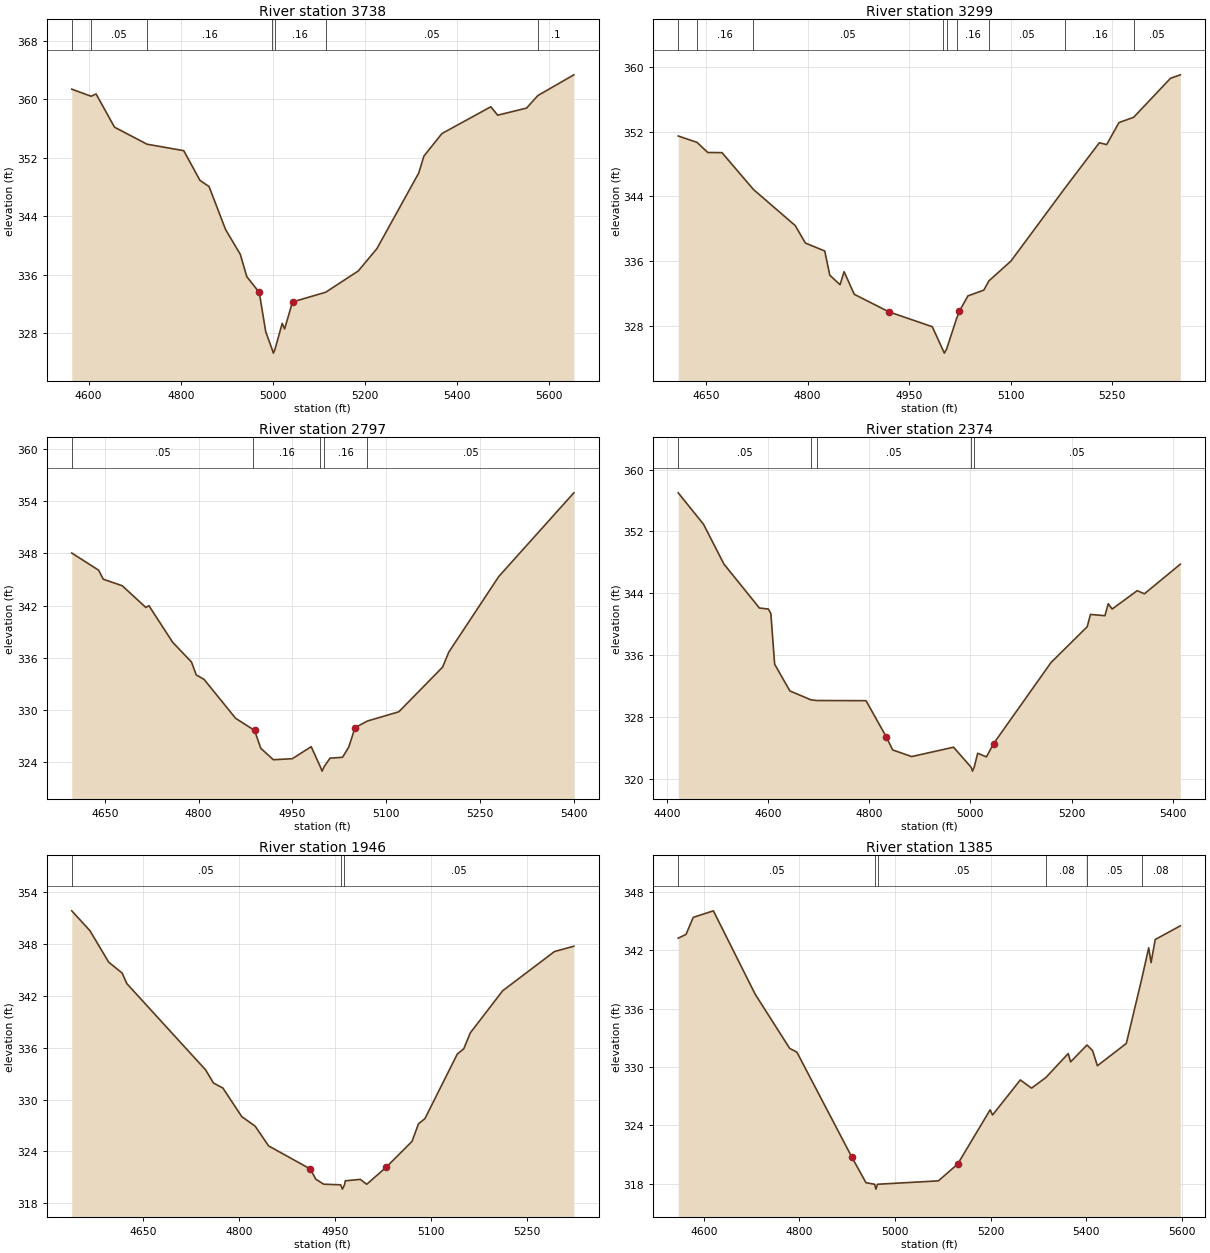
Type RM Length L Ch R = 1 ,3738    ,439,439,439
BEGIN DESCRIPTION:
UNNAMED TRIBUTARY 1A TO BLISS CR 8.0
END DESCRIPTION:
XS GIS Cut Line= 4
      3631702.26     10520682.51      3631424.48     10520699.88
      3631164.06      10520633.9      3630625.84     10520560.98
#Sta/Elev= 30
  4563.3  361.35  4605.3  360.38  4616.1  360.69  4656.1  356.15  4726.8  353.82
  4806.4  352.94  4841.6  348.88  4861.4  348.03  4897.2  342.16  4929.2  338.76
  4943.4   335.7  4970.4  333.55  4984.4  328.18  4998.4  325.75  5001.1  325.25
  5004.4  325.75  5020.2  329.32  5025.4  328.56  5042.6  332.25  5114.7  333.58
  5185.4  336.49  5225.8  339.54  5316.6  349.88  5327.9   352.2    5367  355.28
  5473.1  358.94  5488.1  357.79  5550.7  358.76  5575.4  360.48  5653.4  363.31
#Mann= 7 ,-1 , 0
  4563.3     .16       0  4605.3     .05       0  4726.8     .16       0
  4998.4     .07       0  5004.4     .16       0  5114.7     .05       0
  5575.4      .1       0
Bank Sta=4970.4,5042.6
XS Rating Curve= 0 ,0
Exp/Cntr=0.3,0.1

Type RM Length L Ch R = 1 ,3299    ,502,502,502
BEGIN DESCRIPTION:
UNNAMED TRIBUTARY 1A TO BLISS CR 7.0
END DESCRIPTION:
XS GIS Cut Line= 3
      3631599.61     10520510.19      3631299.61     10520310.19
      3630949.65     10520160.21
#Sta/Elev= 30
  4609.1  351.46  4636.9  350.67  4652.7  349.42  4673.7   349.4  4720.2  344.84
  4781.9  340.37  4796.9  338.21  4825.4  337.23  4832.9  334.23    4848  333.06
    4854  334.67    4869  331.87  4920.1   329.7  4984.2  327.86  4999.3  325.09
    5002  324.59  5005.3  325.09  5020.2   328.9  5024.1  329.77  5036.8  331.67
  5060.3  332.39  5067.9  333.54  5100.2  335.97  5180.5  345.06  5230.8  350.62
  5241.7   350.4  5259.8  353.12  5281.6  353.78  5335.9   358.6  5350.4  359.03
#Mann= 9 ,-1 , 0
  4609.1     .05       0  4636.9     .16       0  4720.2     .05       0
  4999.3     .03       0  5005.3     .05       0  5020.2     .16       0
  5067.9     .05       0  5180.5     .16       0  5281.6     .05       0
Bank Sta=4920.1,5024.1
XS Rating Curve= 0 ,0
Exp/Cntr=0.3,0.1

Type RM Length L Ch R = 1 ,2797    ,423,423,423
BEGIN DESCRIPTION:
UNNAMED TRIBUTARY 1A TO BLISS CR 6.0
END DESCRIPTION:
XS GIS Cut Line= 3
      3631899.64     10519860.18      3631499.61     10519910.19
      3631099.66     10519910.19
#Sta/Elev= 30
  4597.1  348.05    4640  346.08  4647.5  345.04  4677.8  344.29  4715.5   341.8
  4720.6  341.99  4758.4   337.8  4788.6  335.52  4796.2  334.04  4808.8  333.52
  4859.2  329.05  4887.4  327.76  4889.4  327.69  4899.5   325.6  4919.6  324.29
  4949.9  324.41  4980.1  325.79  4994.7  323.48  4997.5  322.98  5000.7  323.48
  5010.2  324.47  5030.2  324.57  5040.2  325.75  5050.2  327.98  5070.1  328.74
  5120.2   329.8  5190.2  334.93  5200.2  336.66  5280.2  345.36  5400.2  354.97
#Mann= 5 ,-1 , 0
  4597.1     .05       0  4887.4     .16       0  4994.7     .07       0
  5000.7     .16       0  5070.1     .05       0
Bank Sta=4889.4,5050.2
XS Rating Curve= 0 ,0
Exp/Cntr=0.3,0.1

Type RM Length L Ch R = 1 ,2374    ,428,428,428
BEGIN DESCRIPTION:
UNNAMED TRIBUTARY 1A TO BLISS CR 5.0
END DESCRIPTION:
XS GIS Cut Line= 3
      3632049.56     10519560.18      3631449.61     10519510.19
      3631149.64     10519760.16
#Sta/Elev= 30
  4422.4  356.99  4472.5  352.92  4512.7  347.79  4582.9  342.11  4600.5  341.98
  4605.5   341.4    4613  334.85  4643.1   331.4  4685.1  330.24  4697.5  330.16
  4793.6  330.14  4833.8  325.45  4846.3  323.78  4883.9  322.92  4966.7  324.13
  5001.4  321.54  5004.1  321.04  5007.4  321.54  5014.4  323.35  5031.6  322.88
  5045.9   324.6  5159.2  335.06  5230.8  339.69  5237.3  341.28  5265.9  341.12
  5272.4  342.66  5280.2  341.98  5329.7  344.35    5344  343.95  5414.9  347.77
#Mann= 5 ,-1 , 0
  4422.4     .05       0  4685.1     .08       0  4697.5     .05       0
  5001.4     .03       0  5007.4     .05       0
Bank Sta=4833.8,5045.9
XS Rating Curve= 0 ,0
Exp/Cntr=0.3,0.1

Type RM Length L Ch R = 1 ,1946    ,561,561,561
BEGIN DESCRIPTION:
UNNAMED TRIBUTARY 1A TO BLISS CR 4.0
END DESCRIPTION:
XS GIS Cut Line= 3
       3632049.6     10519410.18      3631699.61     10519160.19
      3631349.57     10519110.18
#Sta/Elev= 30
  4539.3  351.82  4567.6  349.53    4597  345.88  4617.9  344.63  4625.3   343.4
  4748.2  333.43  4760.5  331.91  4775.2  331.33  4804.7  328.02  4825.6  326.92
  4846.5  324.64  4911.6  321.97  4920.2  320.79  4932.5  320.21    4959  320.14
  4961.8  319.64    4965  320.14  4966.3   320.6  4989.6  320.77  4999.7   320.2
    5030  322.17  5070.4  325.16  5080.5  327.19  5090.6   327.8  5141.1  335.26
  5151.2  335.87  5161.3   337.7  5211.8  342.57  5292.7  347.11    5323  347.73
#Mann= 3 ,-1 , 0
  4539.3     .05       0    4959     .03       0    4965     .05       0
Bank Sta=4911.6,5030
XS Rating Curve= 0 ,0
Exp/Cntr=0.3,0.1

Type RM Length L Ch R = 1 ,1385    ,353,353,353
BEGIN DESCRIPTION:
UNNAMED TRIBUTARY 1A TO BLISS CR 3.0
END DESCRIPTION:
XS GIS Cut Line= 3
      3632259.76     10518923.17      3631890.68     10518679.51
       3631287.5       10518753.
#Sta/Elev= 30
  4546.7  343.24    4563  343.63  4578.1  345.38  4620.2  346.05  4707.5  337.49
  4779.8  331.91  4794.8  331.53  4909.2  320.79  4939.3  318.11  4957.4  317.95
  4960.1  317.45  4963.4  317.95  5090.8   318.3  5131.1  320.03  5198.9   325.6
    5204  325.07    5262  328.67  5285.6  327.83  5315.5  328.92  5362.2  331.38
  5367.2  330.53  5401.5  332.26  5413.1  331.69  5423.2  330.13  5483.7  332.42
  5515.7     339  5530.5  342.25  5535.5  340.73  5544.1   343.1  5596.6  344.51
#Mann= 6 ,-1 , 0
  4546.7     .05       0  4957.4     .03       0  4963.4     .05       0
  5315.5     .08       0  5401.5     .05       0  5515.7     .08       0
Bank Sta=4909.2,5131.1
XS Rating Curve= 0 ,0
Exp/Cntr=0.3,0.1

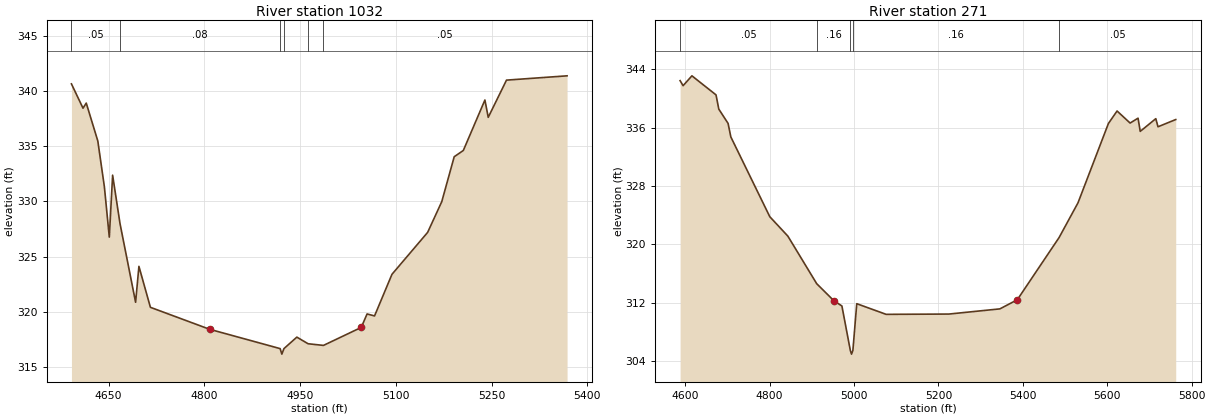
Type RM Length L Ch R = 1 ,1032    ,761,761,761
BEGIN DESCRIPTION:
UNNAMED TRIBUTARY 1A TO BLISS CR 2.0
END DESCRIPTION:
XS GIS Cut Line= 3
      3632349.66     10518260.18      3631949.61     10518360.19
      3631599.57      10518460.2
#Sta/Elev= 30
  4591.8  340.64  4609.9  338.44    4615   338.9  4633.1  335.47  4643.4  331.32
  4651.1  326.76  4656.3  332.37  4667.9  327.98  4692.3  320.86  4697.5  324.11
  4715.5   320.4  4808.3  318.41  4918.7  316.66  4921.4  316.16  4924.7  316.66
  4944.9   317.7  4962.5   317.1  4986.6  316.95  5045.8  318.58  5054.9   319.8
  5066.6  319.62  5093.9  323.39  5149.8  327.19  5171.9  329.97  5191.4  334.04
  5205.7  334.61  5239.5  339.18  5244.7  337.61  5273.3  340.98  5368.2  341.37
#Mann= 6 ,-1 , 0
  4591.8     .05       0  4667.9     .08       0  4918.7     .04       0
  4924.7     .08       0  4962.5     .16       0  4986.6     .05       0
Bank Sta=4808.3,5045.8
XS Rating Curve= 0 ,0
Exp/Cntr=0.3,0.1

Type RM Length L Ch R = 1 ,271     ,0,0,0
BEGIN DESCRIPTION:
UNNAMED TRIBUTARY 1A TO BLISS CR 1.0
END DESCRIPTION:
XS GIS Cut Line= 5
      3632342.07     10517957.28      3632105.96     10517679.51
      3632008.74     10517623.95      3631835.12     10517762.84
      3631724.67     10518225.36
#Sta/Elev= 30
  4587.9  342.43    4595  341.74  4615.9  343.09    4673  340.48  4679.6  338.53
  4701.6  336.57  4708.1  334.72  4800.4  323.79  4843.2  321.13  4911.6  314.61
  4952.5  312.26  4971.3  311.56  4991.3  305.46  4994.1  304.96  4997.3  305.46
  5006.5  311.87  5076.1  310.41  5224.9  310.45  5345.7  311.16  5386.9  312.41
  5485.9  320.93  5530.8   325.7  5602.8  336.56  5623.3  338.27  5654.2  336.62
    5673  337.29  5678.2  335.48  5715.1  337.22  5720.3  336.11  5762.3   337.1
#Mann= 5 ,-1 , 0
  4587.9     .05       0  4911.6     .16       0  4991.3     .07       0
  4997.3     .16       0  5485.9     .05       0
Bank Sta=4952.5,5386.9
XS Rating Curve= 0 ,0
Exp/Cntr=0.3,0.1

Chan Stop Cuts=-1
Use User Specified Reach Order=0
Composite Channel Slope=5