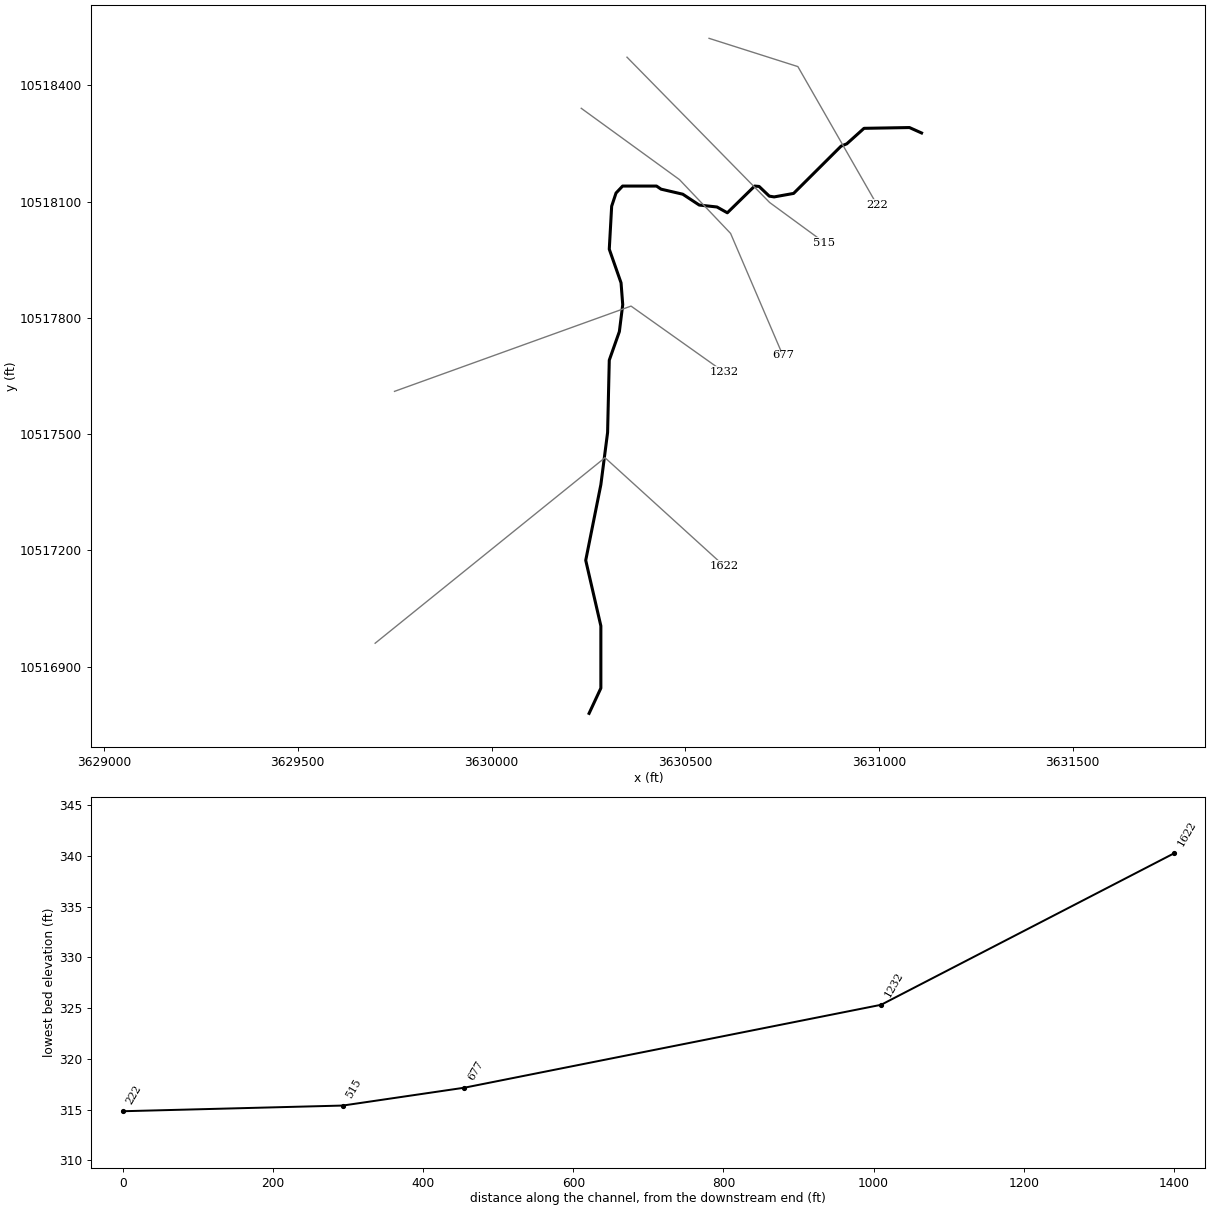
--- UNNAMED TRIBUTARY 1B TO BLISS CR.prj (project) ---

Proj Title=UNNAMED TRIBUTARY 1B TO BLISS CR Base Level Engineering
Current Plan=p01
Default Exp/Contr=0.3,0.1
English Units
Geom File=g01
Flow File=f01
Plan File=p01
Y Axis Title=Elevation
X Axis Title(PF)=Main Channel Distance
X Axis Title(XS)=Station
BEGIN DESCRIPTION:
UNNAMED TRIBUTARY 1B TO BLISS CR
END DESCRIPTION:
DSS Export Rating Curves= 0
DSS Export Rating Curve Sorted= 0
DSS Export Volume Flow Curves= 0
DXF OffsetX= 0
DXF OffsetY= 0
DXF ScaleX= 1
DXF ScaleY= 10

--- UNNAMED TRIBUTARY 1B TO BLISS CR.p01 (plan) ---

Plan Title=Multiple Run
Short Identifier=Multiple
Geom File=g01
Flow File=f01
Subcritical Flow
K Sum by GR= 0
Std Step Tol= 0.01
Critical Tol= 0.01
Num of Std Step Trials= 20
Max Error Tol= 0.3
Flow Tol Ratio= 0.001
Split Flow NTrial= 30
Split Flow Tol= 0.02
Split Flow Ratio= 0.02
Log Output Level= 0
Friction Slope Method= 1
Unsteady Friction Slope Method= 2
Unsteady Bridges Friction Slope Method= 1
Parabolic Critical Depth
Global Vel Dist=  1 , 1 , 1
Global Log Level= 0
CheckData=True
Encroach Param= -1, 0, 0, 0
BEGIN DESCRIPTION:
Multiple Run
END DESCRIPTION:

--- UNNAMED TRIBUTARY 1B TO BLISS CR.f01 (steady flow) ---

Flow Title=Multiple
Number of Profiles=7
Profile Names=10-year,25-year,50-year,1pct_min,100-year,1pct_plu,500-year
River Rch & RM= UNNAMED TRIBUTAR,Reach-1,1622
     481     634     757     663     897    1213    1250
Boundary for River Rch & Prof#=UNNAMED TRIBUTAR,Reach-1,1
Up Type=0
Dn Type=3
Dn Slope=0.005
Boundary for River Rch & Prof#=UNNAMED TRIBUTAR,Reach-1,2
Up Type=0
Dn Type=3
Dn Slope=0.005
Boundary for River Rch & Prof#=UNNAMED TRIBUTAR,Reach-1,3
Up Type=0
Dn Type=3
Dn Slope=0.005
Boundary for River Rch & Prof#=UNNAMED TRIBUTAR,Reach-1,4
Up Type=0
Dn Type=3
Dn Slope=0.005
Boundary for River Rch & Prof#=UNNAMED TRIBUTAR,Reach-1,5
Up Type=0
Dn Type=3
Dn Slope=0.005
Boundary for River Rch & Prof#=UNNAMED TRIBUTAR,Reach-1,6
Up Type=0
Dn Type=3
Dn Slope=0.005
Boundary for River Rch & Prof#=UNNAMED TRIBUTAR,Reach-1,7
Up Type=0
Dn Type=3
Dn Slope=0.005

--- UNNAMED TRIBUTARY 1B TO BLISS CR.g01 (geometry) ---

Geom Title=Existing Conditions
Program Version=4.10

River Reach=UNNAMED TRIBUTAR,Reach-1
Reach XY= 30
      3630251.74     10516779.18      3630282.12     10516844.29
      3630282.12     10517004.88      3630243.06     10517174.15
      3630282.12     10517369.46      3630299.49     10517504.01
      3630303.83     10517690.64      3630329.87     10517764.42
      3630338.55     10517833.87      3630334.21     10517890.29
      3630303.83      10517977.1        3630310.       10518088.
      3630321.25       10518122.      3630338.25       10518140.
      3630425.75       10518140.       3630437.5       10518132.
       3630493.5       10518119.        3630536.       10518091.
      3630581.75       10518086.       3630608.5       10518071.
        3630679.       10518140.       3630690.5       10518139.
      3630716.75       10518114.      3630729.25       10518112.
       3630779.5       10518121.        3630902.       10518243.
      3630916.75       10518249.      3630961.25       10518289.
       3631078.5       10518291.      3631109.75       10518277.

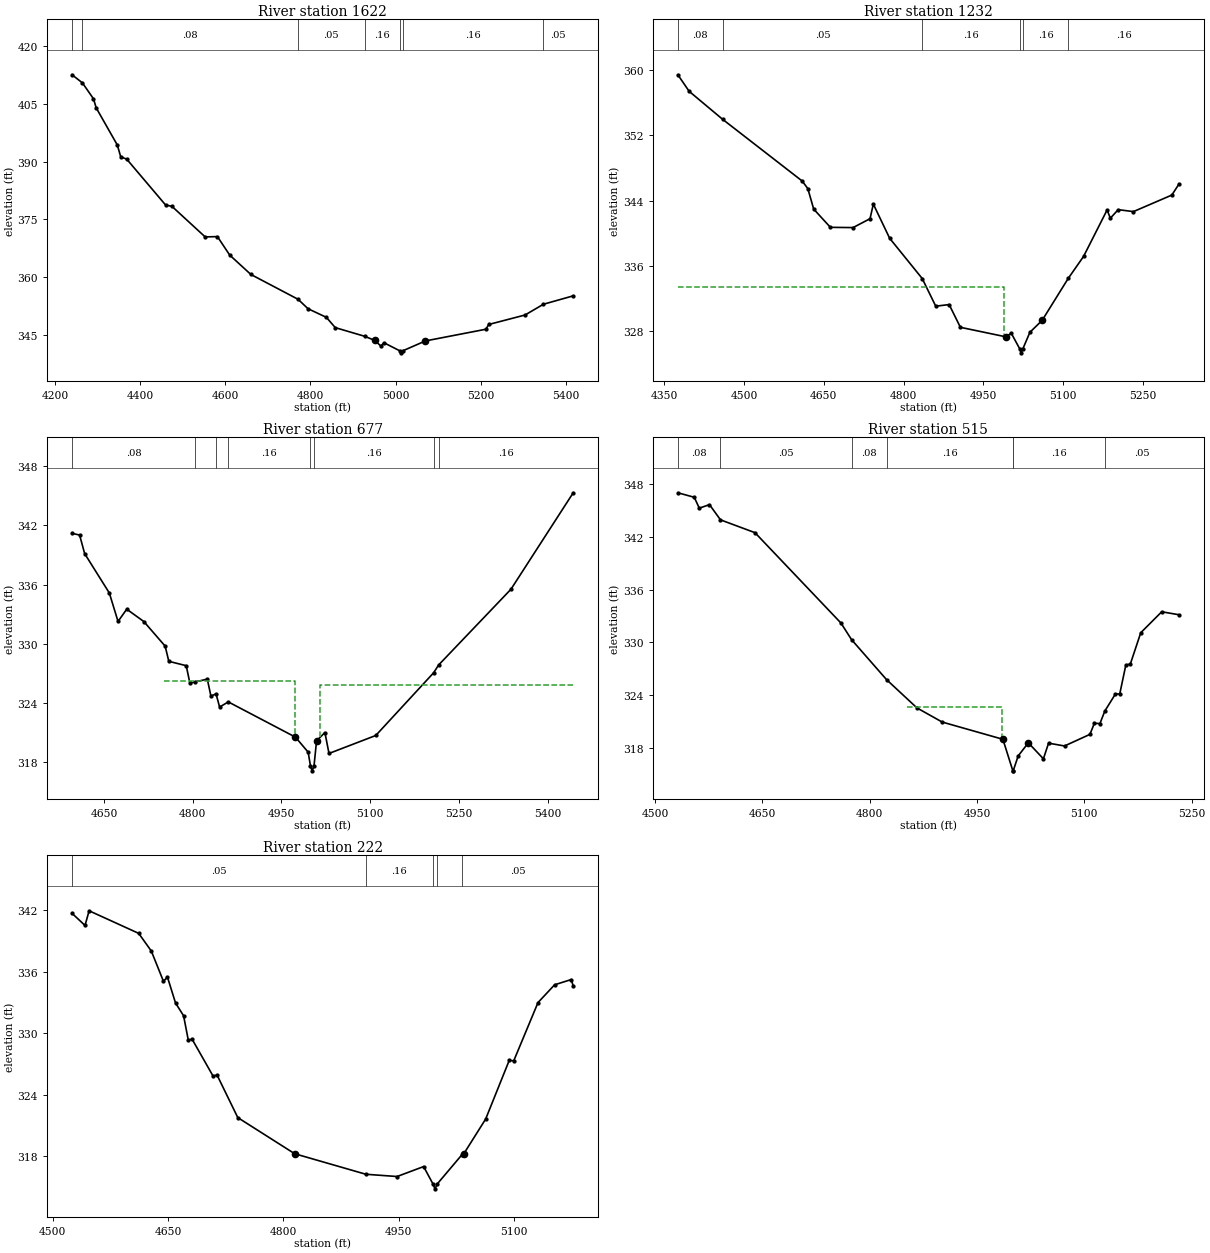
Type RM Length L Ch R = 1 ,1622    ,390,390,390
BEGIN DESCRIPTION:
UNNAMED TRIBUTARY 1B TO BLISS CR 3.0
END DESCRIPTION:
XS GIS Cut Line= 3
      3629699.62      10516960.2      3630292.75       10517439.
      3630599.63     10517160.17
#Sta/Elev= 30
  4240.1  412.58  4264.5  410.47  4290.4  406.34  4296.9  403.96  4346.4  394.31
  4354.4  391.25  4368.6  390.62    4460  378.67  4474.4  378.38  4552.7   370.4
  4581.5  370.48  4610.3  365.68  4659.9  360.64  4770.9  354.17  4794.2  351.72
  4837.4  349.47  4858.2   346.8  4927.1  344.55  4950.9  343.48  4965.3  342.01
  4972.6  342.86  5010.2  340.74    5013  340.24  5016.2  340.74    5070  343.34
  5211.9  346.38  5218.6  347.62  5303.8  350.08    5347  352.88    5417  355.07
#Mann= 7 ,-1 , 0
  4240.1     .05       0  4264.5     .08       0  4770.9     .05       0
  4927.1     .16       0  5010.2     .07       0  5016.2     .16       0
    5347     .05       0
Bank Sta=4950.9,5070
XS Rating Curve= 0 ,0
Exp/Cntr=0.3,0.1

Type RM Length L Ch R = 1 ,1232    ,555,555,555
BEGIN DESCRIPTION:
UNNAMED TRIBUTARY 1B TO BLISS CR 2.0
END DESCRIPTION:
XS GIS Cut Line= 3
      3629749.58     10517610.18      3630359.98     10517830.26
       3630599.6     10517660.19
#Sta/Elev= 30
  4375.5  359.42  4396.8  357.39  4459.9  353.95  4609.4  346.39    4620  345.46
    4631  342.95  4662.5  340.71  4705.1  340.68    4737  341.77  4743.2  343.56
  4773.9  339.37  4835.2  334.43  4860.6  331.04  4885.8  331.24    4907  328.45
  4992.1  327.29  5002.7  327.72  5018.5  325.82  5021.3  325.32  5024.5  325.82
  5037.7  327.84  5060.7   329.3  5109.7  334.44  5138.6  337.14  5182.9  342.84
    5189  341.83  5203.8  342.88  5232.4  342.64  5304.7  344.67  5318.2  346.03
#Mann= 6 ,-1 , 0
  4375.5     .08       0  4459.9     .05       0  4835.2     .16       0
  5018.5     .07       0  5024.5     .16       0  5109.7     .16       0
#XS Ineff= 2 , 0
         4988.86  333.41
Permanent Ineff=
       F       F
Bank Sta=4992.1,5060.7
XS Rating Curve= 0 ,0
Exp/Cntr=0.3,0.1

Type RM Length L Ch R = 1 ,677     ,162,162,162
BEGIN DESCRIPTION:
Mapping XS 44c5aa0d
END DESCRIPTION:
XS GIS Cut Line= 4
      3630231.49     10518340.69      3630484.98     10518156.65
      3630616.92     10518017.76       3630751.6     10517703.52
#Sta/Elev= 30
  4596.2   341.2    4609  341.03  4617.5  339.15  4659.2  335.16  4673.9  332.28
  4688.6  333.52  4717.5  332.27  4753.5  329.78  4759.7  328.24  4789.1   327.8
  4795.3  326.03  4803.9  326.15  4824.7  326.44  4830.8  324.73  4839.5  324.94
  4845.5  323.61  4860.2  324.13  4973.7  320.56  4995.1  319.04    4999  317.65
  5001.8  317.15    5005  317.65  5009.3  320.19  5023.4  321.03  5030.3  318.91
  5109.3  320.73  5207.2  327.09  5215.5  327.87  5337.7  335.54  5442.9  345.31
#Mann= 8 ,-1 , 0
  4596.2     .08       0  4803.9     .05       0  4839.5     .08       0
  4860.2     .16       0    4999     .07       0    5005     .16       0
  5207.2     .08       0  5215.5     .16       0
#XS Ineff= 2 ,-1
 4751.82 4973.41  326.26 5015.68  5442.9  325.86
Permanent Ineff=
       F       F
Bank Sta=4973.7,5009.3
XS Rating Curve= 0 ,0
Exp/Cntr=0.3,0.1

Type RM Length L Ch R = 1 ,515     ,293,293,293
BEGIN DESCRIPTION:
Mapping XS 6e193428
END DESCRIPTION:
XS GIS Cut Line= 3
      3630349.59     10518472.59      3630717.62     10518097.62
      3630858.77     10517994.34
#Sta/Elev= 30
    4532  347.03  4554.9  346.52    4562  345.28  4576.2  345.68  4591.6  343.95
  4639.8  342.49  4759.9  332.21  4774.7  330.32  4823.6  325.77  4866.1  322.55
  4901.4  320.94  4986.2  318.98  5000.1  315.39  5000.6  315.39  5007.5  317.08
  5021.7  318.58  5042.8  316.76    5050  318.54  5072.3  318.22  5107.8  319.54
    5114   320.8  5121.8  320.77  5128.6  322.19  5143.3  324.12  5149.5  324.15
    5158  327.44  5164.2  327.53  5178.8   331.1  5208.1  333.49  5232.3  333.15
#Mann= 7 ,-1 , 0
    4532     .08       0  4591.6     .05       0  4774.7     .08       0
  4823.6     .16       0  5000.1     .07       0  5000.6     .16       0
  5128.6     .05       0
#XS Ineff= 1 ,-1
 4851.82    4985 322.661
Permanent Ineff=
       F
Bank Sta=4986.2,5021.7
XS Rating Curve= 0 ,0
Exp/Cntr=0.3,0.1

Type RM Length L Ch R = 1 ,222     ,0,0,0
BEGIN DESCRIPTION:
UNNAMED TRIBUTARY 1B TO BLISS CR 1.0
END DESCRIPTION:
XS GIS Cut Line= 3
      3630561.33     10518521.24      3630790.54     10518448.31
      3630995.01     10518091.35
#Sta/Elev= 30
  4525.2  341.67  4542.1  340.49  4547.4  341.92  4611.9  339.72  4628.3     338
  4644.1  335.05  4649.3  335.46  4659.8  332.94  4670.3  331.69  4676.3  329.36
  4681.6  329.38  4708.6  325.82  4713.8  325.92  4740.8  321.77  4814.8  318.25
  4907.4  316.25    4948  316.03  4982.5     317  4994.5  315.33  4997.3  314.83
  5000.5  315.33  5032.2  318.14  5034.9  318.26  5063.2  321.63  5093.9  327.35
  5099.7   327.3  5131.3  332.98  5152.9  334.71  5174.5  335.22  5177.1   334.6
#Mann= 5 ,-1 , 0
  4525.2     .05       0  4907.4     .16       0  4994.5     .07       0
  5000.5     .16       0  5032.2     .05       0
Bank Sta=4814.8,5034.9
XS Rating Curve= 0 ,0
Exp/Cntr=0.3,0.1

Chan Stop Cuts=-1
Use User Specified Reach Order=0
Composite Channel Slope=5