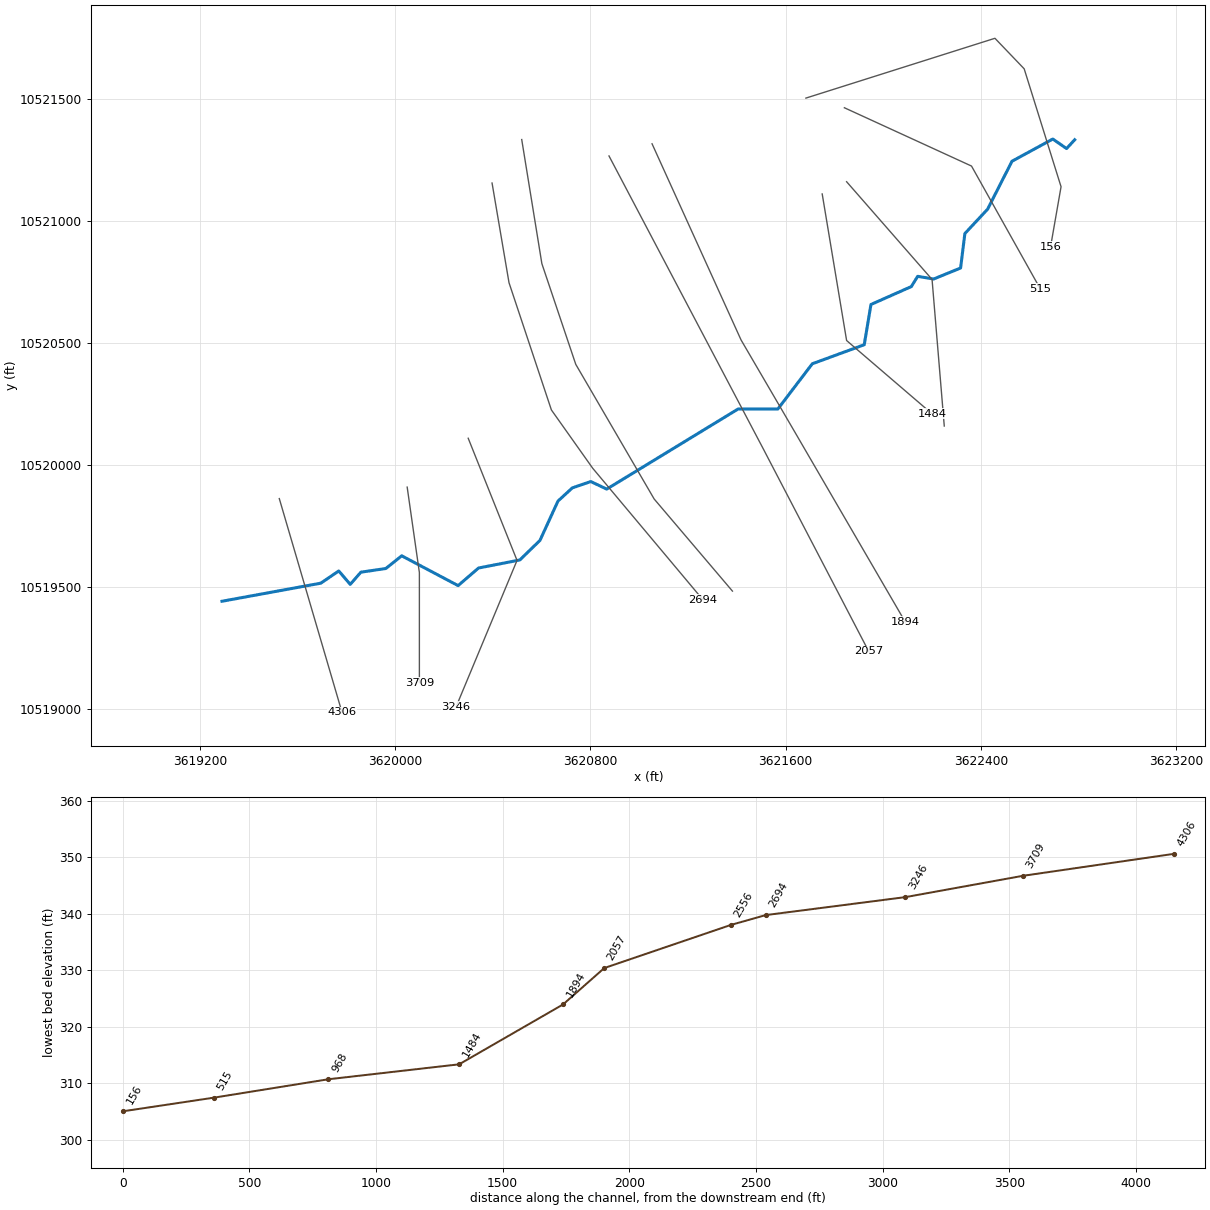
--- UNNAMED TRIBUTARY TO CANE BR.prj (project) ---

Proj Title=UNNAMED TRIBUTARY TO CANE BR Base Level Engineering
Current Plan=p01
Default Exp/Contr=0.3,0.1
English Units
Geom File=g01
Flow File=f01
Plan File=p01
BEGIN DESCRIPTION:
UNNAMED TRIBUTARY TO CANE BR
END DESCRIPTION:

--- UNNAMED TRIBUTARY TO CANE BR.p01 (plan) ---

Plan Title=Multiple Run
Short Identifier=Multiple
Geom File=g01
Flow File=f01
Subcritical Flow
K Sum by GR= 0
Std Step Tol= 0.01
Critical Tol= 0.01
Num of Std Step Trials= 20
Max Error Tol= 0.3
Flow Tol Ratio= 0.001
Split Flow NTrial= 30
Split Flow Tol= 0.02
Split Flow Ratio= 0.02
Log Output Level= 0
Friction Slope Method= 1
Unsteady Friction Slope Method= 2
Unsteady Bridges Friction Slope Method= 1
Parabolic Critical Depth
Global Vel Dist=  1 , 1 , 1
Global Log Level= 0
CheckData=True
Encroach Param= -1, 0, 0, 0
BEGIN DESCRIPTION:
Multiple Run
END DESCRIPTION:

--- UNNAMED TRIBUTARY TO CANE BR.f01 (steady flow) ---

Flow Title=Multiple
Number of Profiles=7
Profile Names=10-year,25-year,50-year,1pct_min,100-year,1pct_plu,500-year
River Rch & RM= UNNAMED TRIBUTAR,Reach-1,4306
     759    1033    1259    1124    1520    2055    2202
Boundary for River Rch & Prof#=UNNAMED TRIBUTAR,Reach-1,1
Up Type=0
Dn Type=3
Dn Slope=0.005
Boundary for River Rch & Prof#=UNNAMED TRIBUTAR,Reach-1,2
Up Type=0
Dn Type=3
Dn Slope=0.005
Boundary for River Rch & Prof#=UNNAMED TRIBUTAR,Reach-1,3
Up Type=0
Dn Type=3
Dn Slope=0.005
Boundary for River Rch & Prof#=UNNAMED TRIBUTAR,Reach-1,4
Up Type=0
Dn Type=3
Dn Slope=0.005
Boundary for River Rch & Prof#=UNNAMED TRIBUTAR,Reach-1,5
Up Type=0
Dn Type=3
Dn Slope=0.005
Boundary for River Rch & Prof#=UNNAMED TRIBUTAR,Reach-1,6
Up Type=0
Dn Type=3
Dn Slope=0.005
Boundary for River Rch & Prof#=UNNAMED TRIBUTAR,Reach-1,7
Up Type=0
Dn Type=3
Dn Slope=0.005

--- UNNAMED TRIBUTARY TO CANE BR.g01 (geometry) ---

Geom Title=Existing Conditions

River Reach=UNNAMED TRIBUTAR,Reach-1
Reach XY= 30
      3619291.00     10519443.00      3619695.75     10519517.00
      3619769.50     10519567.00      3619816.25     10519512.00
      3619860.00     10519562.00      3619962.00     10519577.00
      3620027.25     10519629.00      3620258.25     10519507.00
      3620341.75     10519579.00      3620511.00     10519612.00
      3620593.50     10519692.00      3620667.25     10519853.00
      3620726.00     10519907.00      3620801.75     10519933.00
      3620867.00     10519902.00      3621405.25     10520230.00
      3621568.00     10520230.00      3621709.00     10520415.00
      3621921.75     10520493.00      3621949.25     10520657.69
      3622114.75     10520731.00      3622140.75     10520773.00
      3622206.00     10520762.00      3622316.50     10520807.00
      3622334.00     10520948.00      3622427.25     10521048.00
      3622527.00     10521244.00      3622694.25     10521335.00
      3622750.50     10521296.00      3622784.00     10521332.00

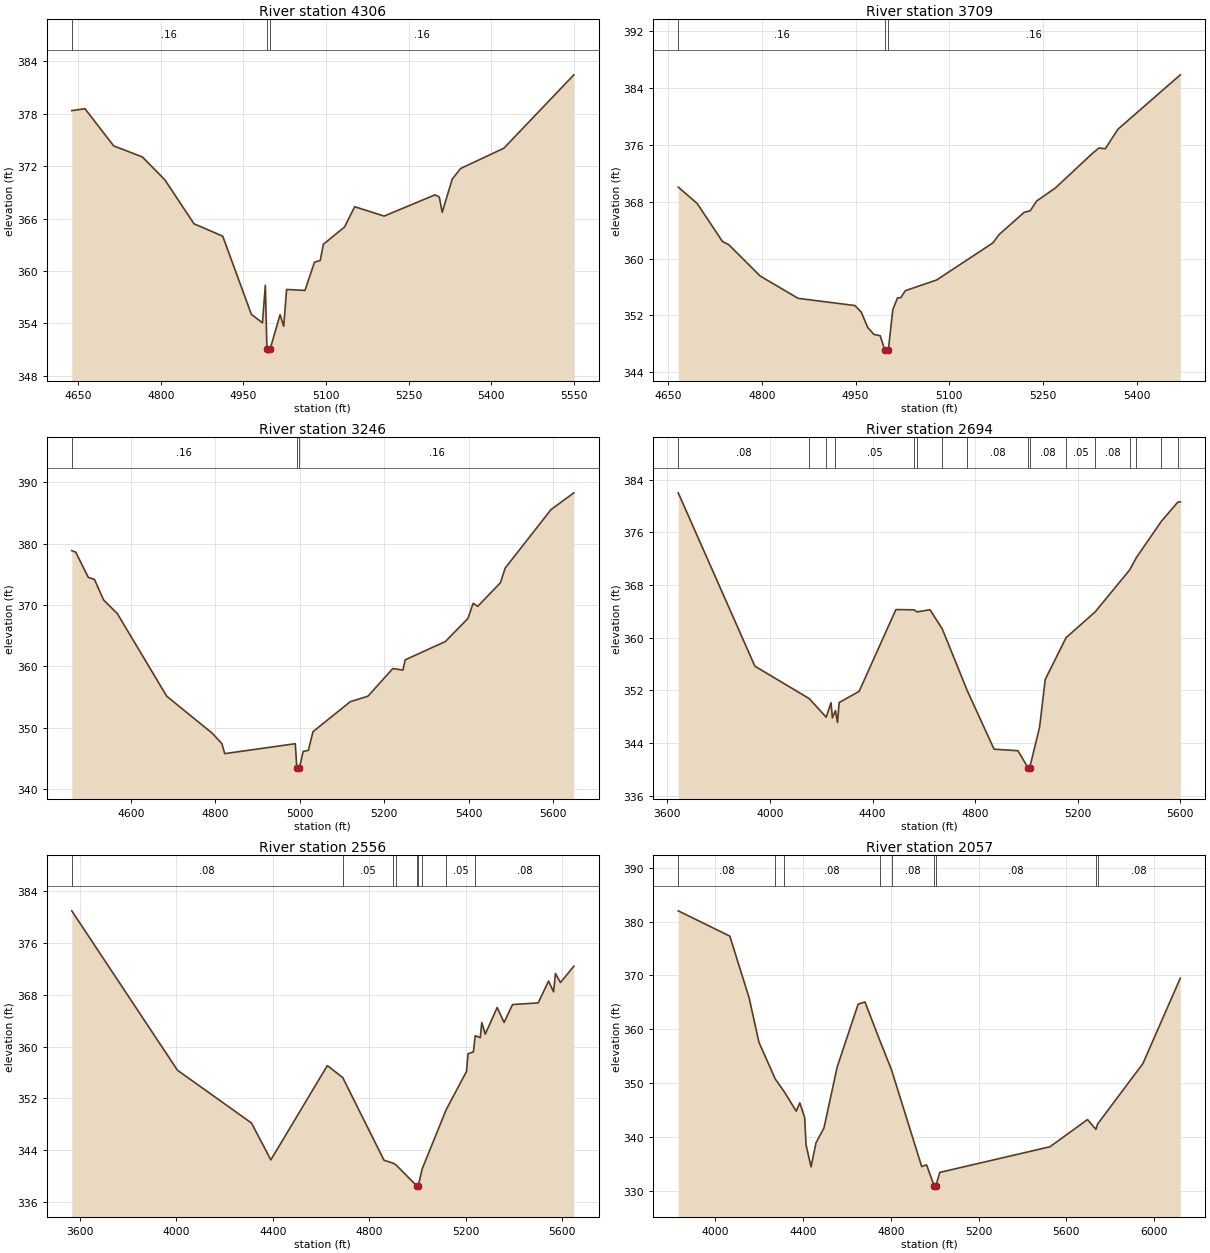
Type RM Length L Ch R = 1,4306,597,597,597
BEGIN DESCRIPTION:
UNNAMED TRIBUTARY TO CANE BR 9.0
END DESCRIPTION:
XS GIS Cut Line= 2
      3619525.75     10519863.24      3619782.71     10518988.19
#Sta/Elev= 30
  4638.1  378.35  4662.1  378.57  4714.2  374.32  4766.3  373.05  4807.2  370.43
  4860.1  365.40  4912.3  363.98  4964.4  355.02  4984.5  354.06  4989.7  358.36
  4992.6  351.09  4995.4  350.59  4998.6  351.09  5016.5  355.00  5023.1  353.66
  5028.3  357.88  5061.7  357.77  5079.0  361.00  5089.4  361.20  5095.1  363.05
  5133.6  365.03  5152.0  367.35  5205.6  366.28  5297.9  368.71  5305.7  368.47
  5311.0  366.71  5329.2  370.51  5344.3  371.72  5423.0  374.05  5550.1  382.45
#Mann=3,-1,0
  4638.1    0.16       0  4992.6    0.07       0  4998.6    0.16       0
Bank Sta=4992.6,4998.6
Exp/Cntr=0.3,0.1

Type RM Length L Ch R = 1,3709,463,463,463
BEGIN DESCRIPTION:
UNNAMED TRIBUTARY TO CANE BR 8.0
END DESCRIPTION:
XS GIS Cut Line= 3
      3620049.61     10519910.16      3620099.61     10519560.19
      3620099.61     10519110.21
#Sta/Elev= 30
  4666.3  370.04  4696.6  367.74  4737.0  362.40  4747.1  361.95  4797.6  357.53
  4858.2  354.40  4949.1  353.39  4959.2  352.47  4969.3  350.35  4979.4  349.33
  4989.5  349.15  4996.6  347.20  4999.4  346.70  5002.6  347.20  5009.7  352.81
  5017.3  354.48  5022.3  354.48  5029.8  355.48  5079.8  356.98  5169.8  362.19
  5179.8  363.37  5219.8  366.48  5229.8  366.72  5239.8  368.08  5269.8  369.91
  5329.8  374.83  5339.8  375.54  5349.8  375.43  5369.8  378.16  5469.8  385.82
#Mann=3,-1,0
  4666.3    0.16       0  4996.6    0.07       0  5002.6    0.16       0
Bank Sta=4996.6,5002.6
Exp/Cntr=0.3,0.1

Type RM Length L Ch R = 1,3246,552,552,552
BEGIN DESCRIPTION:
UNNAMED TRIBUTARY TO CANE BR 7.0
END DESCRIPTION:
XS GIS Cut Line= 3
      3620299.62     10520110.15      3620499.61     10519610.19
      3620249.60     10519010.17
#Sta/Elev= 30
  4460.3  378.88  4469.7  378.63  4499.3  374.53  4514.1  374.17  4535.7  370.83
  4568.0  368.63  4685.1  355.15  4792.8  349.12  4815.7  347.42  4822.4  345.79
  4989.4  347.41  4993.1  343.44  4995.8  342.94  4999.1  343.44  5008.0  346.14
  5020.4  346.33  5031.3  349.37  5119.6  354.26  5161.3  355.15  5220.3  359.66
  5244.2  359.41  5249.6  361.08  5344.9  364.07  5398.0  367.82  5410.4  370.29
  5421.3  369.80  5474.9  373.64  5486.3  376.04  5594.6  385.56  5648.8  388.30
#Mann=3,-1,0
  4460.3    0.16       0  4993.1    0.07       0  4999.1    0.16       0
Bank Sta=4993.1,4999.1
Exp/Cntr=0.3,0.1

Type RM Length L Ch R = 1,2694,138,138,138
BEGIN DESCRIPTION:
UNNAMED TRIBUTARY TO CANE BR 6.0
END DESCRIPTION:
XS GIS Cut Line= 5
      3620397.29     10521154.86      3620466.73     10520746.89
      3620640.34     10520226.06      3620809.61     10519987.34
      3621261.00     10519449.15
#Sta/Elev= 30
  3642.3  382.00  3941.2  355.69  4153.1  350.77  4219.3  347.94  4238.1  350.15
  4243.4  347.84  4255.2  348.95  4263.5  347.15  4269.8  350.17  4347.8  351.87
  4491.1  364.28  4561.5  364.24  4573.6  363.93  4624.1  364.26  4672.1  361.33
  4769.9  351.93  4873.9  343.09  4966.8  342.86  5006.7  340.26  5009.5  339.76
  5012.7  340.26  5051.4  346.42  5073.5  353.68  5154.6  360.01  5267.9  363.92
  5402.6  370.29  5429.3  372.20  5526.6  377.69  5590.7  380.60  5600.2  380.62
#Mann=16,-1,0
  3642.3    0.08       0  4153.1    0.05       0  4219.3    0.08       0
  4255.2    0.05       0  4561.5    0.16       0  4573.6    0.08       0
  4672.1    0.05       0  4769.9    0.08       0  5006.7    0.07       0
  5012.7    0.08       0  5154.6    0.05       0  5267.9    0.08       0
  5402.6    0.05       0  5429.3    0.08       0  5526.6    0.05       0
  5590.7    0.08       0
Bank Sta=5006.7,5012.7
Exp/Cntr=0.3,0.1

Type RM Length L Ch R = 1,2556,499,499,499
BEGIN DESCRIPTION:
UNNAMED TRIBUTARY TO CANE BR 5.0
END DESCRIPTION:
XS GIS Cut Line= 5
      3620518.80     10521332.88      3620601.28     10520825.02
      3620740.17     10520412.69      3621061.35     10519861.48
      3621381.95     10519484.55
#Sta/Elev= 30
  3566.0  380.94  4004.4  356.35  4311.4  348.21  4391.6  342.52  4626.1  357.07
  4689.8  355.22  4861.0  342.47  4896.9  342.04  4910.0  341.78  4997.0  338.51
  4999.7  338.01  5003.0  338.51  5019.8  341.18  5119.0  350.27  5203.1  356.16
  5209.6  358.90  5231.6  359.16  5239.4  361.68  5260.2  361.38  5266.7  363.71
  5281.0  361.91  5330.4  366.03  5359.0  363.72  5394.1  366.48  5500.7  366.74
  5543.5  370.11  5564.3  368.45  5572.1  371.28  5592.9  369.88  5648.4  372.40
#Mann=9,-1,0
  3566.0    0.08       0  4689.8    0.05       0  4896.9    0.08       0
  4910.0    0.05       0  4997.0    0.04       0  5003.0    0.05       0
  5019.8    0.08       0  5119.0    0.05       0  5239.4    0.08       0
Bank Sta=4997,5003
Exp/Cntr=0.3,0.1

Type RM Length L Ch R = 1,2057,163,163,163
BEGIN DESCRIPTION:
Mapping XS dd0b6136
END DESCRIPTION:
XS GIS Cut Line= 3
      3620876.28     10521265.75      3621509.95     10520063.51
      3621939.64     10519238.85
#Sta/Elev= 30
  3830.8  381.98  4066.0  377.29  4154.1  365.84  4198.8  357.61  4273.6  350.78
  4314.9  348.41  4368.7  344.85  4385.1  346.39  4407.1  343.69  4413.6  338.61
  4436.2  334.53  4458.8  338.98  4495.2  341.74  4555.7  353.08  4651.0  364.68
  4682.2  365.09  4750.2  357.91  4803.4  352.48  4940.8  334.58  4962.9  334.90
  4998.3  330.90  5001.0  330.40  5004.3  330.90  5023.3  333.50  5525.4  338.25
  5696.5  343.29  5735.0  341.48  5742.4  342.45  5949.1  353.67  6119.7  369.50
#Mann=9,-1,0
  3830.8    0.08       0  4273.6     0.1       0  4314.9    0.08       0
  4750.2    0.05       0  4803.4    0.08       0  4998.3    0.07       0
  5004.3    0.08       0  5735.0    0.05       0  5742.4    0.08       0
Bank Sta=4998.3,5004.3
Exp/Cntr=0.3,0.1

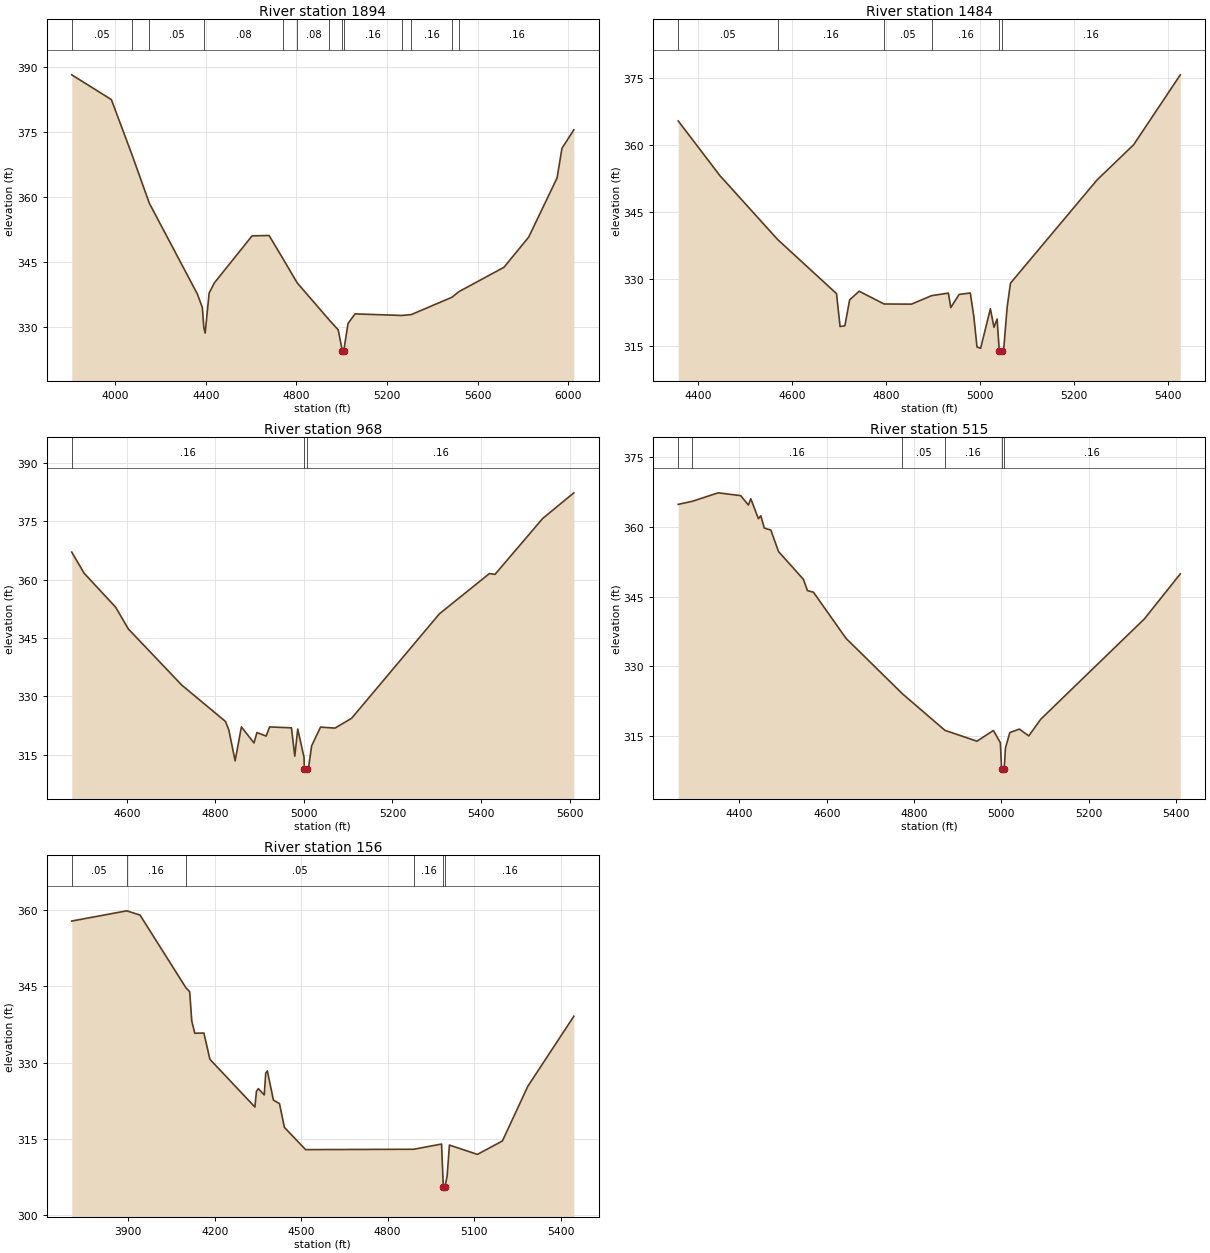
Type RM Length L Ch R = 1,1894,410,410,410
BEGIN DESCRIPTION:
UNNAMED TRIBUTARY TO CANE BR 4.0
END DESCRIPTION:
XS GIS Cut Line= 4
      3621052.67     10521315.45      3621417.25     10520512.52
      3621642.94     10520126.23      3622089.97     10519358.04
#Sta/Elev= 30
  3807.6  388.23  3982.6  382.51  4073.5  369.80  4150.3  358.57  4362.5  337.61
  4384.5  334.47  4391.1  329.84  4396.9  328.59  4414.5  337.84  4437.5  340.18
  4604.1  351.04  4679.3  351.13  4740.0  345.82  4803.6  340.18  4946.1  331.55
  4984.5  329.36  5003.0  324.46  5005.7  323.96  5009.0  324.46  5028.0  330.81
  5058.9  333.02  5265.0  332.66  5307.5  332.86  5487.0  336.86  5518.3  338.17
  5716.6  343.77  5826.4  350.77  5951.6  364.43  5973.1  371.27  6025.6  375.53
#Mann=13,-1,0
  3807.6    0.05       0  4073.5    0.08       0  4150.3    0.05       0
  4391.1    0.08       0  4740.0    0.05       0  4803.6    0.08       0
  4946.1    0.16       0  5003.0    0.07       0  5009.0    0.16       0
  5265.0    0.12       0  5307.5    0.16       0  5487.0    0.05       0
  5518.3    0.16       0
Bank Sta=5003,5009
Exp/Cntr=0.3,0.1

Type RM Length L Ch R = 1,1484,516,516,516
BEGIN DESCRIPTION:
UNNAMED TRIBUTARY TO CANE BR 3.0
END DESCRIPTION:
XS GIS Cut Line= 3
      3621749.60     10521110.22      3621849.61     10520510.19
      3622199.62     10520210.18
#Sta/Elev= 30
  4357.3  365.37  4446.0  353.13  4569.0  338.82  4694.4  326.70  4702.0  319.33
  4712.2  319.50  4722.3  325.30  4742.6  327.24  4795.7  324.38  4854.1  324.35
  4897.0  326.25  4932.7  326.82  4937.7  323.58  4955.5  326.52  4979.3  326.85
  4987.0  321.46  4993.6  314.76  5001.3  314.46  5022.1  323.30  5029.8  319.17
  5036.4  321.02  5041.1  313.88  5043.8  313.38  5047.1  313.88  5050.7  314.53
  5057.8  323.68  5064.9  329.04  5249.3  352.16  5327.3  360.05  5426.6  375.69
#Mann=6,-1,0
  4357.3    0.05       0  4569.0    0.16       0  4795.7    0.05       0
  4897.0    0.16       0  5041.1    0.07       0  5047.1    0.16       0
Bank Sta=5041.1,5047.1
Exp/Cntr=0.3,0.1

Type RM Length L Ch R = 1,968,453,453,453
BEGIN DESCRIPTION:
UNNAMED TRIBUTARY TO CANE BR 2.0
END DESCRIPTION:
XS GIS Cut Line= 3
      3621849.58     10521160.22      3622199.61     10520760.19
      3622249.61     10520160.22
#Sta/Elev= 30
  4475.9  367.07  4503.9  361.64  4575.1  352.90  4603.6  347.32  4724.1  332.89
  4822.8  323.53  4830.4  321.41  4844.7  313.39  4858.9  322.12  4887.4  317.99
  4894.0  320.66  4914.9  319.76  4922.5  322.11  4971.9  321.88  4979.4  314.60
  4986.1  321.57  5000.3  314.29  5001.1  311.24  5003.9  310.74  5007.1  311.24
  5010.0  311.24  5017.5  317.25  5037.6  322.06  5070.2  321.81  5107.8  324.34
  5306.0  351.21  5418.9  361.56  5431.4  361.34  5539.3  375.75  5609.5  382.33
#Mann=3,-1,0
  4475.9    0.16       0  5001.1    0.07       0  5007.1    0.16       0
Bank Sta=5001.1,5007.1
Exp/Cntr=0.3,0.1

Type RM Length L Ch R = 1,515,359,359,359
BEGIN DESCRIPTION:
Mapping XS 40aefaf0
END DESCRIPTION:
XS GIS Cut Line= 3
      3621840.42     10521463.04      3622361.26     10521224.32
      3622643.39     10520720.82
#Sta/Elev= 30
  4259.7  364.89  4291.2  365.53  4351.4  367.37  4402.9  366.76  4420.4  364.74
  4425.9  366.09  4443.4  361.80  4448.9  362.43  4456.8  359.79  4471.9  359.35
  4489.4  354.74  4546.4  348.76  4555.8  346.32  4569.4  345.99  4643.9  336.07
  4773.1  324.14  4870.6  316.26  4944.0  313.92  4981.7  316.23  4997.6  313.59
  5000.4  307.98  5003.1  307.48  5006.4  307.98  5009.3  312.47  5019.3  315.78
  5041.0  316.53  5062.7  315.06  5090.1  318.65  5327.5  340.24  5409.8  349.94
#Mann=6,-1,0
  4259.7    0.05       0  4291.2    0.16       0  4773.1    0.05       0
  4870.6    0.16       0  5000.4    0.07       0  5006.4    0.16       0
Bank Sta=5000.4,5006.4
Exp/Cntr=0.3,0.1

Type RM Length L Ch R = 1,156,0,0,0
BEGIN DESCRIPTION:
UNNAMED TRIBUTARY TO CANE BR 1.0
END DESCRIPTION:
XS GIS Cut Line= 5
      3621682.83     10521502.52      3622457.18     10521747.33
      3622576.97     10521622.33      3622728.01     10521139.69
      3622684.94     10520893.30
#Sta/Elev= 30
  3704.6  357.87  3895.4  359.88  3941.4  359.04  4100.2  344.75  4113.5  343.95
  4120.7  338.19  4131.2  335.77  4162.7  335.81  4183.7  330.64  4339.7  321.24
  4345.0  324.33  4351.5  324.86  4372.1  323.63  4377.3  327.95  4382.9  328.36
  4403.9  322.60  4424.9  321.92  4441.9  317.24  4515.4  312.85  4890.4  312.92
  4987.0  313.95  4993.0  305.57  4995.7  305.07  4999.0  305.57  5006.4  307.68
  5014.2  313.75  5111.2  311.91  5197.9  314.55  5286.4  325.35  5445.7  339.12
#Mann=6,-1,0
  3704.6    0.05       0  3895.4    0.16       0  4100.2    0.05       0
  4890.4    0.16       0  4993.0    0.07       0  4999.0    0.16       0
Bank Sta=4993,4999
Exp/Cntr=0.3,0.1

Chan Stop Cuts=-1