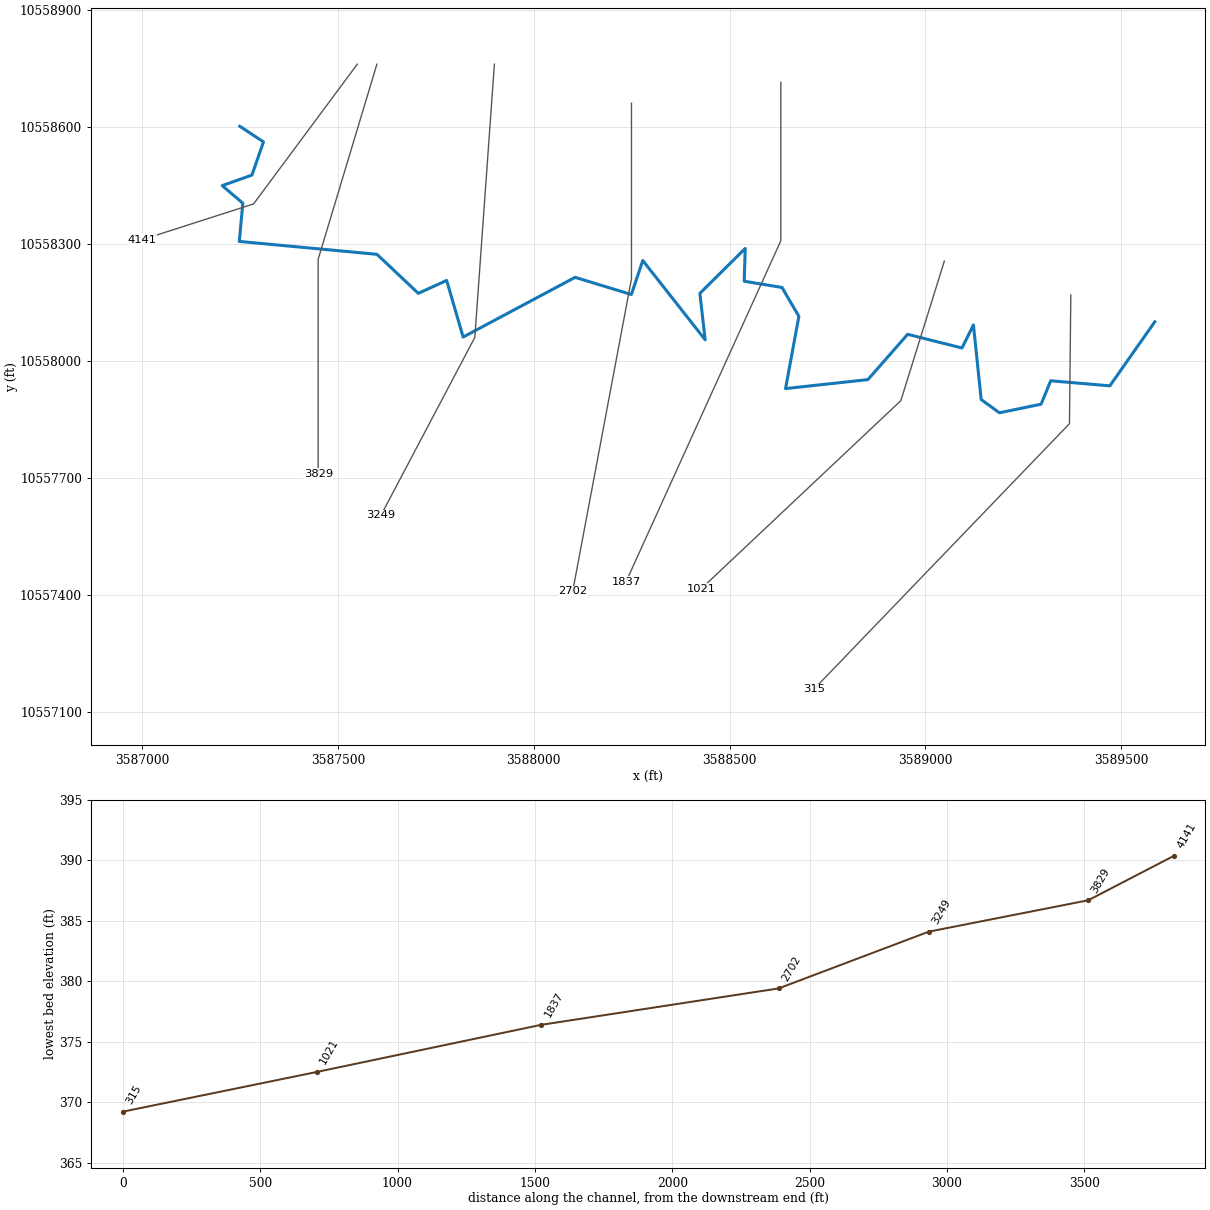
--- UNT 002 IN BUCR.prj (project) ---

Proj Title=UNT 002 IN BUCR Base Level Engineering
Current Plan=p01
Default Exp/Contr=0.3,0.1
English Units
Geom File=g01
Flow File=f01
Plan File=p01
Y Axis Title=Elevation
X Axis Title(PF)=Main Channel Distance
X Axis Title(XS)=Station
BEGIN DESCRIPTION:
UNT 002 IN BUCR
END DESCRIPTION:
DSS Export Rating Curves= 0
DSS Export Rating Curve Sorted= 0
DSS Export Volume Flow Curves= 0
DXF OffsetX= 0
DXF OffsetY= 0
DXF ScaleX= 1
DXF ScaleY= 10

--- UNT 002 IN BUCR.p01 (plan) ---

Plan Title=Multiple Run
Short Identifier=Multiple
Geom File=g01
Flow File=f01
Subcritical Flow
K Sum by GR= 0
Std Step Tol= 0.01
Critical Tol= 0.01
Num of Std Step Trials= 20
Max Error Tol= 0.3
Flow Tol Ratio= 0.001
Split Flow NTrial= 30
Split Flow Tol= 0.02
Split Flow Ratio= 0.02
Log Output Level= 0
Friction Slope Method= 1
Unsteady Friction Slope Method= 2
Unsteady Bridges Friction Slope Method= 1
Parabolic Critical Depth
Global Vel Dist=  1 , 1 , 1
Global Log Level= 0
CheckData=True
Encroach Param= -1, 0, 0, 0
BEGIN DESCRIPTION:
Multiple Run
END DESCRIPTION:

--- UNT 002 IN BUCR.f01 (steady flow) ---

Flow Title=Multiple
Program Version=4.10
Number of Profiles= 7
Profile Names=10-year,25-year,50-year,1pct_min,100-year,1pct_plu,500-year
River Rch & RM=UNT 002 IN BUCR,Reach-1         ,4141
    1136    1577    1944    1750    2367    3201    3495
Boundary for River Rch & Prof#=UNT 002 IN BUCR,Reach-1         , 1
Up Type= 0
Dn Type= 3
Dn Slope=0.004
Boundary for River Rch & Prof#=UNT 002 IN BUCR,Reach-1         , 2
Up Type= 0
Dn Type= 3
Dn Slope=0.004
Boundary for River Rch & Prof#=UNT 002 IN BUCR,Reach-1         , 3
Up Type= 0
Dn Type= 3
Dn Slope=0.004
Boundary for River Rch & Prof#=UNT 002 IN BUCR,Reach-1         , 4
Up Type= 0
Dn Type= 3
Dn Slope=0.004
Boundary for River Rch & Prof#=UNT 002 IN BUCR,Reach-1         , 5
Up Type= 0
Dn Type= 3
Dn Slope=0.004
Boundary for River Rch & Prof#=UNT 002 IN BUCR,Reach-1         , 6
Up Type= 0
Dn Type= 3
Dn Slope=0.004
Boundary for River Rch & Prof#=UNT 002 IN BUCR,Reach-1         , 7
Up Type= 0
Dn Type= 3
Dn Slope=0.004
DSS Import GetInterval= 0
DSS Import GetPeak= 0
DSS Import FillOption= 0

--- UNT 002 IN BUCR.g01 (geometry) ---

Geom Title=Existing Conditions
Program Version=4.10

River Reach=UNT 002 IN BUCR ,Reach-1
Reach XY= 30
      3587249.61       10558601.        3587310.       10558561.
       3587280.5       10558476.      3587204.75       10558449.
      3587257.25       10558404.      3587248.25       10558306.
      3587599.75       10558273.      3587705.25       10558173.
      3587777.75       10558206.      3587819.75       10558061.
      3588105.75       10558214.      3588249.25       10558170.
       3588278.5       10558257.      3588437.75       10558054.
      3588424.25       10558173.        3588540.       10558288.
       3588537.5       10558204.        3588634.       10558188.
        3588677.       10558114.        3588643.       10557929.
      3588853.25       10557952.      3588954.75       10558068.
       3589093.5       10558033.      3589122.75       10558092.
       3589142.5       10557901.        3589189.       10557867.
       3589295.5       10557889.        3589320.       10557949.
        3589471.       10557936.      3589585.75       10558100.

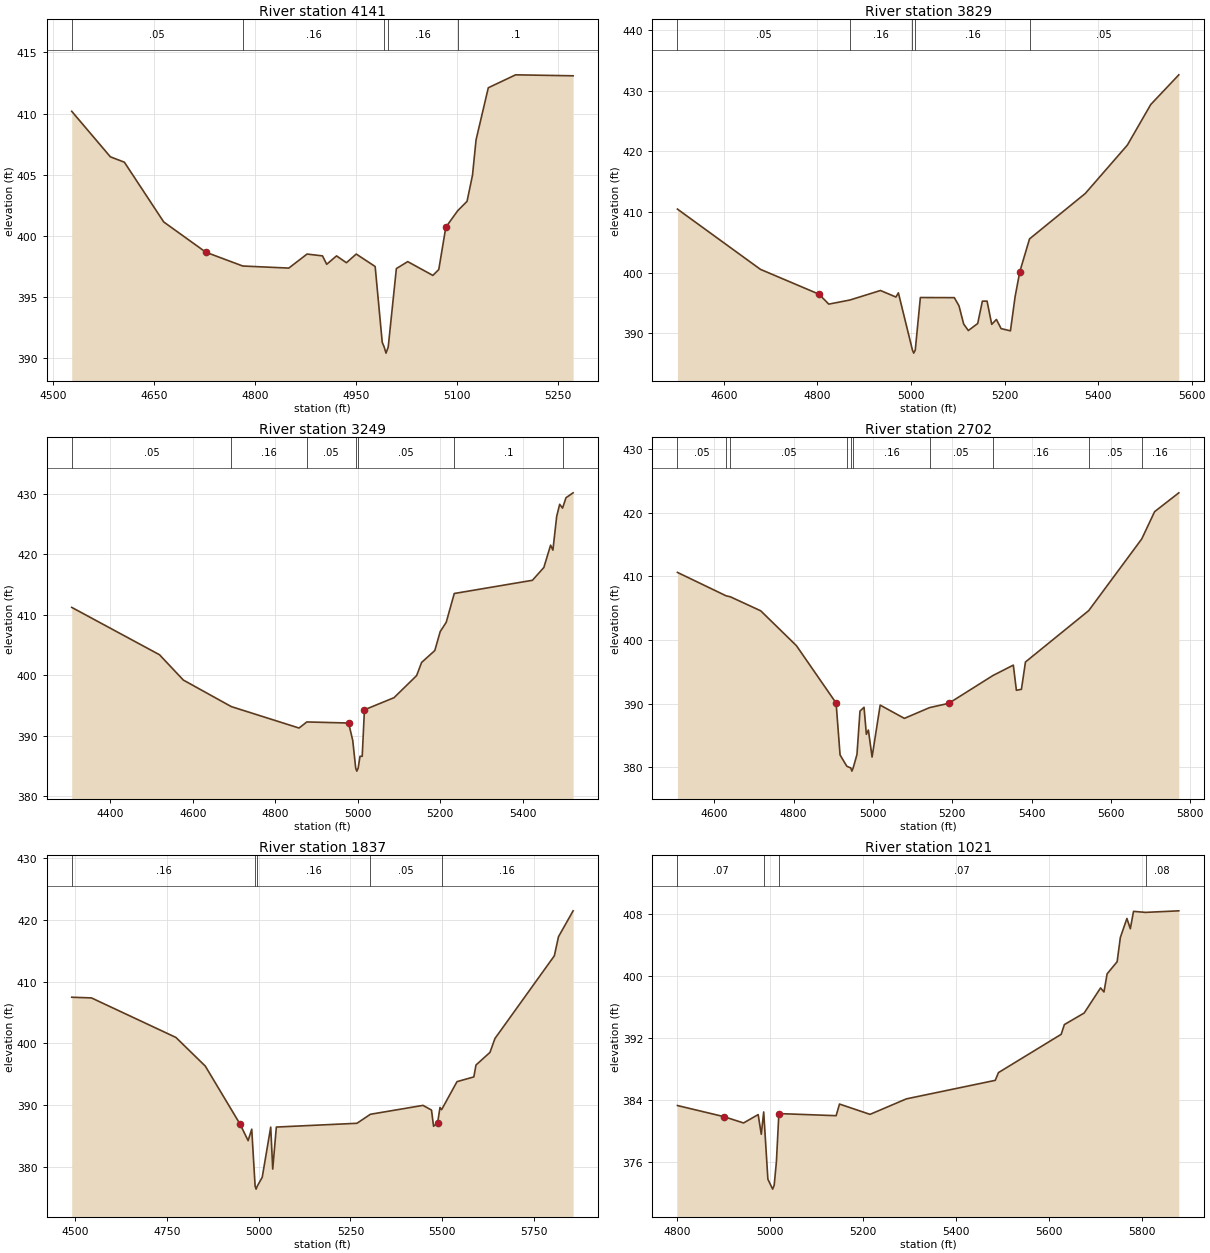
Type RM Length L Ch R = 1 ,4141    ,312,312,312
BEGIN DESCRIPTION:
UNT 002 IN BUCR 5.0
END DESCRIPTION:
XS GIS Cut Line= 3
      3587549.59     10558760.16      3587284.65     10558402.05
      3586999.64      10558310.2
#Sta/Elev= 30
  4527.4  410.18  4584.8  406.45  4605.6  406.01  4664.1  401.11  4726.7  398.63
  4781.5   397.5  4849.9  397.33    4877  398.48    4900  398.33  4906.2  397.64
  4920.8  398.33  4935.5  397.77  4950.1  398.48  4978.2  397.46  4988.7  391.25
  4991.6  390.86  4994.3  390.36  4997.6  390.86  5009.7  397.29  5026.6  397.86
  5063.9  396.73  5072.7  397.21  5083.2  400.68  5100.8  402.03  5114.7   402.8
  5122.8  404.94  5128.1  407.84  5146.3  412.11  5186.9  413.17  5272.3  413.09
#Mann= 5 ,-1 , 0
  4527.4     .05       0  4781.5     .16       0  4991.6     .07       0
  4997.6     .16       0  5100.8      .1       0
Bank Sta=4726.7,5083.2
XS Rating Curve= 0 ,0
Exp/Cntr=0.3,0.1

Type RM Length L Ch R = 1 ,3829    ,580,580,580
BEGIN DESCRIPTION:
UNT 002 IN BUCR 4.0
END DESCRIPTION:
XS GIS Cut Line= 3
       3587599.6     10558760.16      3587449.61     10558260.19
      3587449.61     10557710.17
#Sta/Elev= 30
  4500.6  410.47  4678.1  400.52  4803.3  396.42  4824.2  394.78  4869.4  395.46
  4934.7  397.03  4967.8  395.95    4973  396.64  5003.1  387.19  5005.8  386.69
  5009.1  387.19    5020  395.87  5092.6  395.85  5102.6   394.5  5112.6  391.49
  5122.6  390.42  5142.6  391.58  5152.6  395.27  5162.6  395.28  5172.6  391.44
  5182.6  392.25  5192.6  390.74  5212.6  390.37  5222.6  396.03  5232.6  400.13
  5253.4  405.55  5372.6  413.05  5462.6  421.04  5512.6  427.74  5572.6  432.64
#Mann= 5 ,-1 , 0
  4500.6     .05       0  4869.4     .16       0  5003.1     .07       0
  5009.1     .16       0  5253.4     .05       0
Bank Sta=4803.3,5232.6
XS Rating Curve= 0 ,0
Exp/Cntr=0.3,0.1

Type RM Length L Ch R = 1 ,3249    ,547,547,547
BEGIN DESCRIPTION:
UNT 002 IN BUCR 3.0
END DESCRIPTION:
XS GIS Cut Line= 3
      3587899.61      10558760.2      3587849.61     10558060.19
      3587610.25     10557604.86
#Sta/Elev= 30
  4306.1  411.23  4519.1  403.38  4576.8  399.19  4693.2  394.79  4857.5  391.24
  4876.4  392.25  4977.8  392.07  4987.8  389.16  4994.9   384.6  4997.6   384.1
  5000.9   384.6  5005.4  386.56  5010.7  386.56  5016.1  394.26  5087.9  396.27
  5142.7  399.93  5154.8  402.11  5186.8  404.08  5199.9  407.22  5214.5  408.76
    5234  413.53  5423.6  415.72  5451.3  417.84  5467.7  421.54  5473.3  420.72
  5482.4  426.29  5489.7  428.31  5496.7  427.68    5505   429.4  5522.3  430.21
#Mann= 7 ,-1 , 0
  4306.1     .05       0  4693.2     .16       0  4876.4     .05       0
  4994.9     .03       0  5000.9     .05       0    5234      .1       0
  5496.7     .05       0
Bank Sta=4977.8,5016.1
XS Rating Curve= 0 ,0
Exp/Cntr=0.3,0.1

Type RM Length L Ch R = 1 ,2702    ,865,865,865
BEGIN DESCRIPTION:
UNT 002 IN BUCR 2.0
END DESCRIPTION:
XS GIS Cut Line= 3
      3588249.61     10558660.23      3588249.61     10558210.19
      3588099.61     10557410.17
#Sta/Elev= 30
  4507.4   410.6    4630  406.93  4640.9  406.77  4717.4  404.57  4807.4   399.1
  4907.4   390.1  4917.4  381.95  4934.5  380.17  4944.4  379.91  4947.2  379.41
  4950.4  379.91    4960  382.02  4967.6  388.83  4977.8  389.43  4983.7  385.19
  4988.8  385.86  4998.1  381.62  5018.5  389.77  5079.5  387.69  5143.1  389.38
  5191.4  390.05  5302.6  394.41  5354.2  396.05  5361.9   392.1  5374.6  392.25
  5384.8  396.54  5544.2   404.6    5678  415.86  5710.3  420.13  5771.4  423.09
#Mann= 10 ,-1 , 0
  4507.4     .05       0    4630     .16       0  4640.9     .05       0
  4934.5     .16       0  4944.4     .07       0  4950.4     .16       0
  5143.1     .05       0  5302.6     .16       0  5544.2     .05       0
    5678     .16       0
Bank Sta=4907.4,5191.4
XS Rating Curve= 0 ,0
Exp/Cntr=0.3,0.1

Type RM Length L Ch R = 1 ,1837    ,816,816,816
BEGIN DESCRIPTION:
Mapping XS d6e9cec9
END DESCRIPTION:
XS GIS Cut Line= 3
      3588630.93     10558713.91      3588630.93     10558307.69
      3588235.67     10557433.96
#Sta/Elev= 30
    4491  407.47  4544.7  407.36  4774.7  400.96  4854.7  396.32  4949.4  386.92
  4971.3  384.25  4981.1  386.11  4990.3   376.9    4993   376.4  4996.3   376.9
  5009.7  378.32  5032.8  386.44  5038.3  379.65  5048.1  386.45  5267.6  387.06
  5304.3  388.52  5447.5  389.96  5470.6   389.2  5476.2  386.58  5487.2  387.13
  5493.7  389.62  5498.1  389.26    5540   393.8  5585.9  394.57  5591.7  396.49
  5629.8  398.54  5643.4  400.79  5805.1  414.18  5816.4  417.27  5856.2  421.46
#Mann= 5 ,-1 , 0
    4491     .16       0  4990.3     .07       0  4996.3     .16       0
  5304.3     .05       0  5498.1     .16       0
Bank Sta=4949.4,5487.2
XS Rating Curve= 0 ,0
Exp/Cntr=0.3,0.1

Type RM Length L Ch R = 1 ,1021    ,706,706,706
BEGIN DESCRIPTION:
Mapping XS 9633cab2
END DESCRIPTION:
XS GIS Cut Line= 3
      3589048.47     10558255.75      3588937.35     10557898.08
      3588426.94     10557415.45
#Sta/Elev= 30
  4801.3   383.3  4901.4  381.86  4943.3  381.05  4974.7  382.13  4981.4  379.59
  4986.6  382.47  4995.6  373.79  5005.8  372.51  5009.1  373.01  5013.9  376.05
  5019.2  382.26  5142.2  381.99  5149.4  383.49    5215  382.16  5293.1  384.16
    5484  386.55  5490.9  387.55  5625.6  392.49  5632.5  393.75    5675  395.24
  5710.2  398.48  5717.5  397.96  5724.3   400.3  5745.8  401.86  5752.7  404.99
  5766.8  407.44  5774.1  406.12    5781  408.36  5806.8  408.23  5878.3  408.43
#Mann= 4 ,-1 , 0
  4801.3     .07       0  4986.6     .05       0  5019.2     .07       0
  5806.8     .08       0
Bank Sta=4901.4,5019.2
XS Rating Curve= 0 ,0
Exp/Cntr=0.3,0.1

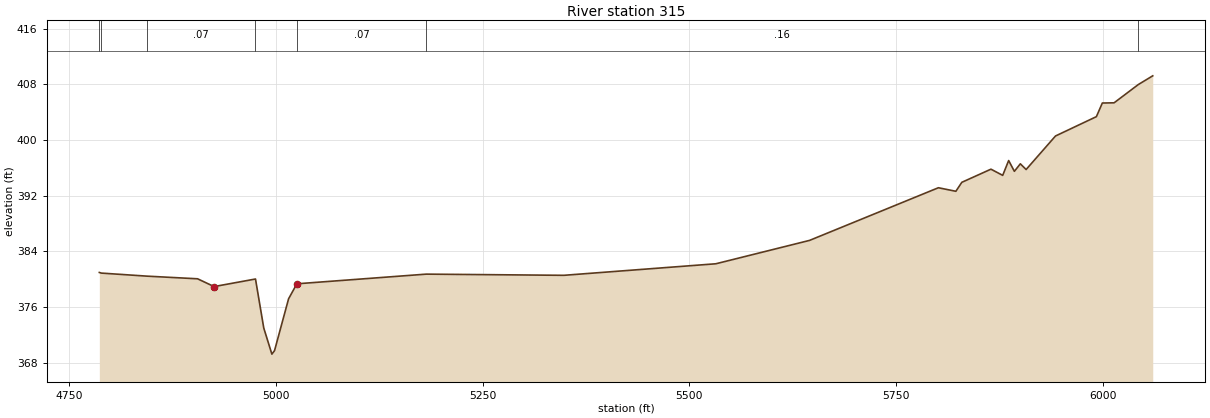
Type RM Length L Ch R = 1 ,315     ,0,0,0
BEGIN DESCRIPTION:
UNT 002 IN BUCR 1.0
END DESCRIPTION:
XS GIS Cut Line= 3
      3589371.37     10558168.89       3589367.9     10557839.05
       3588715.1     10557158.48
#Sta/Elev= 30
    4787  380.97  4789.4  380.88  4844.7  380.44  4905.7  380.06  4925.7  378.94
  4975.7  380.03  4985.7  372.98  4995.5  369.23  4998.7  369.73  5015.7  377.19
  5025.7  379.34  5182.1  380.73  5348.3  380.56    5532  382.22  5645.2  385.58
  5800.9  393.15    5822  392.64  5829.2  393.93  5864.4  395.82  5878.6  394.93
  5885.8  397.06  5892.7  395.51  5899.9  396.59  5906.9  395.77  5942.4  400.59
  5991.8  403.37    5999  405.33  6013.2  405.36  6042.4  407.98  6059.9  409.24
#Mann= 7 ,-1 , 0
    4787     .12       0  4789.4     .16       0  4844.7     .07       0
  4975.7     .05       0  5025.7     .07       0  5182.1     .16       0
  6042.4     .05       0
Bank Sta=4925.7,5025.7
XS Rating Curve= 0 ,0
Exp/Cntr=0.3,0.1

Chan Stop Cuts=-1
Use User Specified Reach Order=0
Composite Channel Slope=5