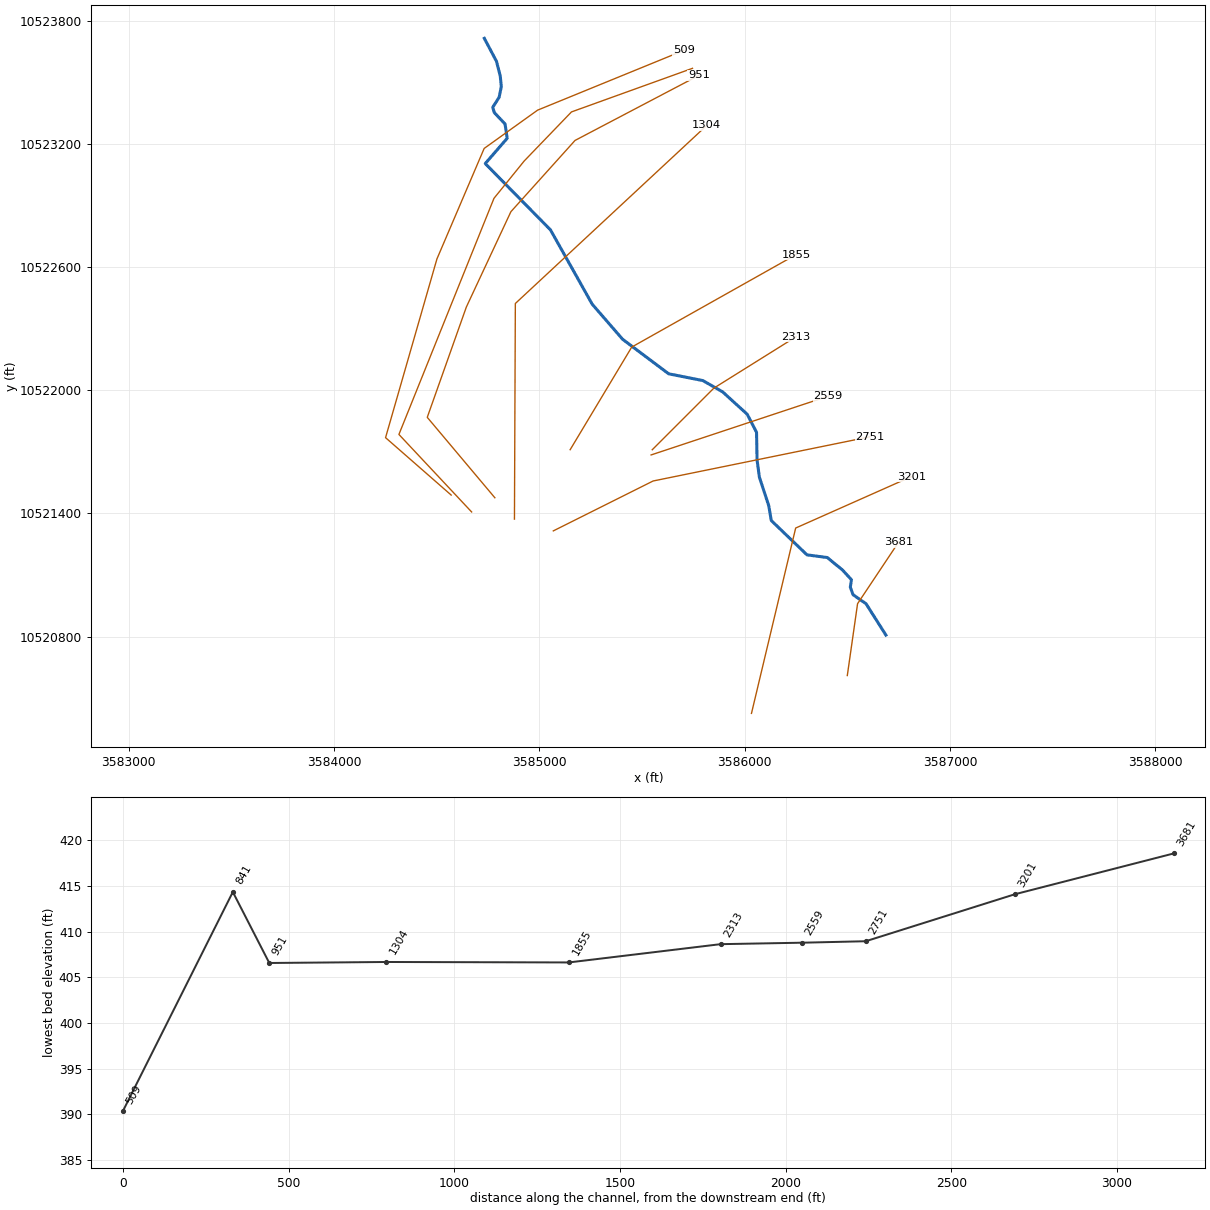
--- UNT 018 IN BUCR.prj (project) ---

Proj Title=UNT 018 IN BUCR Base Level Engineering
Current Plan=p01
Default Exp/Contr=0.3,0.1
English Units
Geom File=g01
Flow File=f01
Plan File=p01
Y Axis Title=Elevation
X Axis Title(PF)=Main Channel Distance
X Axis Title(XS)=Station
BEGIN DESCRIPTION:
UNT 018 IN BUCR
END DESCRIPTION:
DSS Export Rating Curves= 0
DSS Export Rating Curve Sorted= 0
DSS Export Volume Flow Curves= 0
DXF OffsetX= 0
DXF OffsetY= 0
DXF ScaleX= 1
DXF ScaleY= 10

--- UNT 018 IN BUCR.p01 (plan) ---

Plan Title=Multiple Run
Short Identifier=Multiple
Geom File=g01
Flow File=f01
Subcritical Flow
K Sum by GR= 0
Std Step Tol= 0.01
Critical Tol= 0.01
Num of Std Step Trials= 20
Max Error Tol= 0.3
Flow Tol Ratio= 0.001
Split Flow NTrial= 30
Split Flow Tol= 0.02
Split Flow Ratio= 0.02
Log Output Level= 0
Friction Slope Method= 1
Unsteady Friction Slope Method= 2
Unsteady Bridges Friction Slope Method= 1
Parabolic Critical Depth
Global Vel Dist=  1 , 1 , 1
Global Log Level= 0
CheckData=True
Encroach Param= -1, 0, 0, 0
BEGIN DESCRIPTION:
Multiple Run
END DESCRIPTION:

--- UNT 018 IN BUCR.f01 (steady flow) ---

Flow Title=Multiple
Program Version=4.10
Number of Profiles= 7
Profile Names=10-year,25-year,50-year,1pct_min,100-year,1pct_plu,500-year
River Rch & RM=UNT 018 IN BUCR,Reach-1         ,3681
    1540    2196    2760    2533    3425    4633    5259
Boundary for River Rch & Prof#=UNT 018 IN BUCR,Reach-1         , 1
Up Type= 0
Dn Type= 3
Dn Slope=0.04
Boundary for River Rch & Prof#=UNT 018 IN BUCR,Reach-1         , 2
Up Type= 0
Dn Type= 3
Dn Slope=0.04
Boundary for River Rch & Prof#=UNT 018 IN BUCR,Reach-1         , 3
Up Type= 0
Dn Type= 3
Dn Slope=0.04
Boundary for River Rch & Prof#=UNT 018 IN BUCR,Reach-1         , 4
Up Type= 0
Dn Type= 3
Dn Slope=0.04
Boundary for River Rch & Prof#=UNT 018 IN BUCR,Reach-1         , 5
Up Type= 0
Dn Type= 3
Dn Slope=0.04
Boundary for River Rch & Prof#=UNT 018 IN BUCR,Reach-1         , 6
Up Type= 0
Dn Type= 3
Dn Slope=0.04
Boundary for River Rch & Prof#=UNT 018 IN BUCR,Reach-1         , 7
Up Type= 0
Dn Type= 3
Dn Slope=0.04
DSS Import GetInterval= 0
DSS Import GetPeak= 0
DSS Import FillOption= 0

--- UNT 018 IN BUCR.g01 (geometry) ---

Geom Title=Existing Conditions
Program Version=4.10

River Reach=UNT 018 IN BUCR ,Reach-1
Reach XY= 30
       3586687.7     10520807.21      3586590.75       10520960.
       3586527.5       10521004.      3586514.25       10521041.
      3586519.75       10521077.       3586476.5       10521124.
        3586402.       10521185.      3586303.25       10521198.
       3586129.5       10521365.       3586116.5       10521439.
       3586071.5       10521576.        3586060.       10521660.
       3586057.5       10521795.        3586012.       10521883.
      3585892.25       10521992.        3585796.       10522047.
      3585629.25       10522080.      3585405.25       10522248.
        3585257.       10522419.      3585053.75       10522781.
        3584736.       10523104.      3584842.75       10523227.
       3584832.5       10523297.      3584780.25       10523352.
       3584772.5       10523378.      3584803.75       10523427.
      3584814.25       10523479.        3584809.       10523531.
      3584790.75       10523602.       3584731.5       10523714.

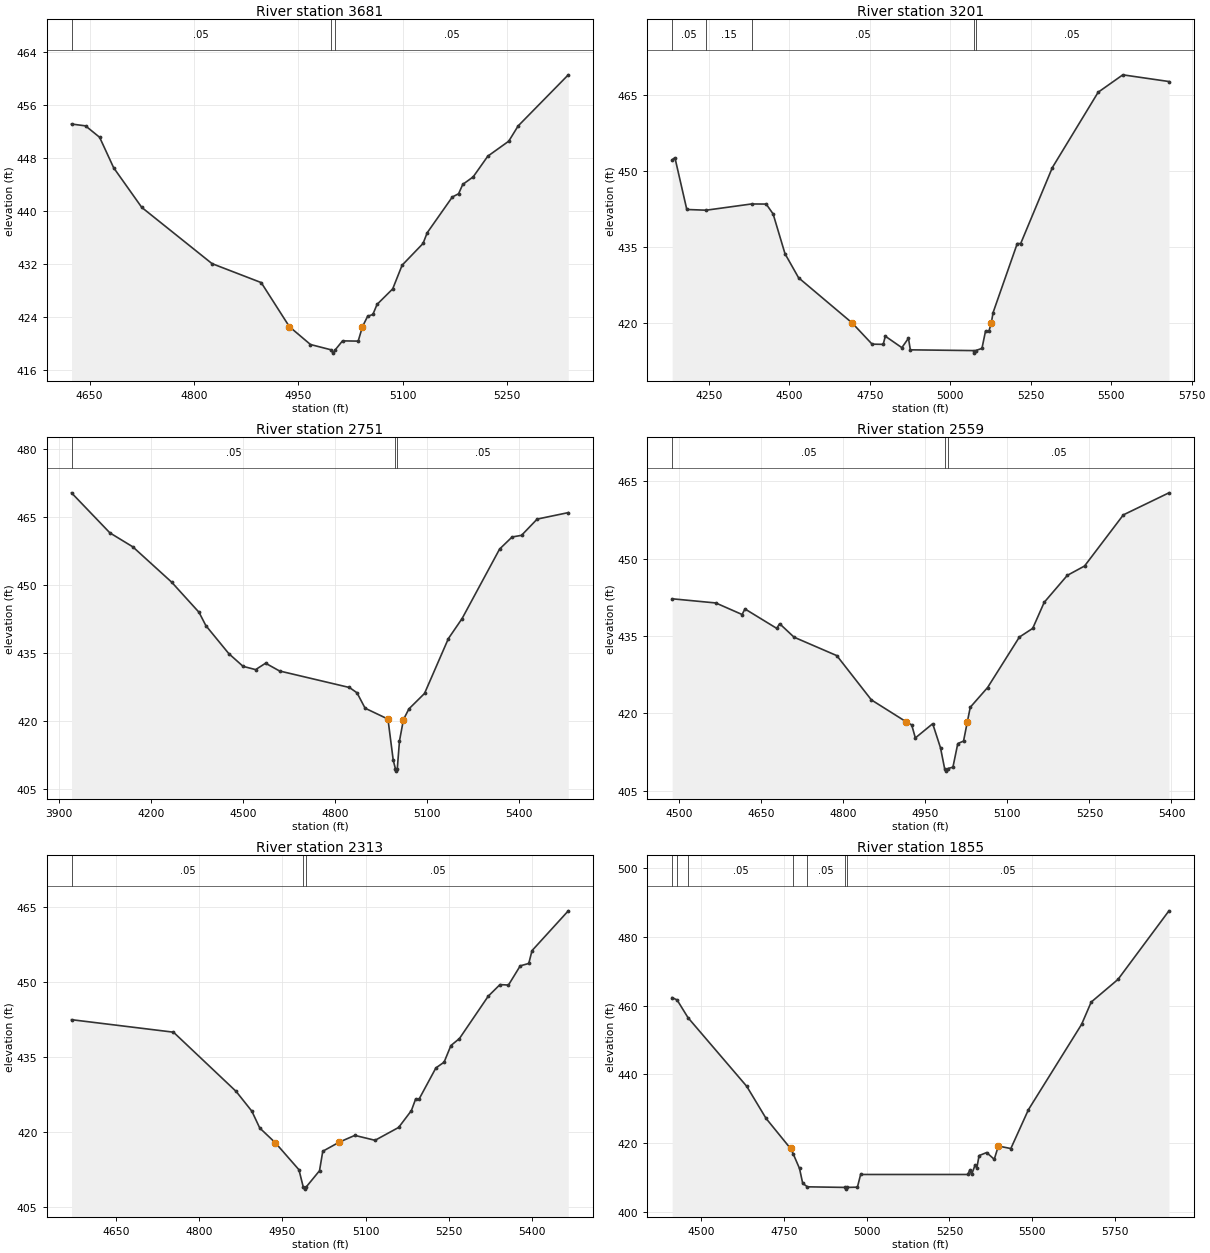
Type RM Length L Ch R = 1 ,3681    ,480,480,480
BEGIN DESCRIPTION:
UNT 018 IN BUCR 6.0
END DESCRIPTION:
XS GIS Cut Line= 3
      3586499.61     10520610.18      3586549.61     10520960.19
       3586749.6     10521260.18
#Sta/Elev= 30
  4624.1  453.12  4644.3  452.84  4664.5  451.12  4684.7  446.52  4725.1  440.54
  4826.1  432.06  4896.8   429.2  4937.3  422.55  4967.6  419.86  4997.2  419.06
  4999.9  418.56  5003.2  419.06  5013.7  420.41  5036.2  420.37  5042.3  422.55
  5049.8  424.12  5057.3  424.39  5063.3  425.91  5085.8  428.25  5099.3  431.82
  5129.4   435.1  5135.4  436.72  5171.5  442.11  5180.5   442.6  5186.5  444.01
  5201.5  445.15  5222.5  448.27  5252.6  450.53  5266.1  452.83  5338.2  460.54
#Mann= 3 ,-1 , 0
  4624.1     .05       0  4997.2     .03       0  5003.2     .05       0
Bank Sta=4937.3,5042.3
XS Rating Curve= 0 ,0
Exp/Cntr=0.3,0.1

Type RM Length L Ch R = 1 ,3201    ,450,450,450
BEGIN DESCRIPTION:
UNT 018 IN BUCR 5.0
END DESCRIPTION:
XS GIS Cut Line= 3
      3586032.82     10520425.93      3586248.09     10521328.69
      3586810.58     10521578.68
#Sta/Elev= 30
  4135.8  452.22  4144.4  452.62  4181.3  442.41  4241.6  442.27  4382.6   443.5
    4428  443.48  4449.5  441.53  4486.5  433.68  4528.6  428.95  4695.3  420.03
    4757  415.86  4791.6  415.82  4798.1  417.43  4849.5  415.17  4870.1  417.03
  4875.8  414.74  5072.4  414.59  5075.2  414.09  5078.4  414.59  5098.4  415.02
  5109.6  418.47  5120.2  418.46  5127.4  420.02  5132.9  422.07  5208.1   435.7
  5218.7  435.69  5317.2  450.68  5459.5  465.53  5536.1  468.96  5679.4  467.64
#Mann= 5 ,-1 , 0
  4135.8     .05       0  4241.6     .15       0  4382.6     .05       0
  5072.4    .033       0  5078.4     .05       0
Bank Sta=4695.3,5127.4
XS Rating Curve= 0 ,0
Exp/Cntr=0.3,0.1

Type RM Length L Ch R = 1 ,2751    ,192,192,192
BEGIN DESCRIPTION:
UNT 018 IN BUCR 4.0
END DESCRIPTION:
XS GIS Cut Line= 3
      3585067.57     10521314.81      3585553.65     10521557.85
      3586609.16     10521773.12
#Sta/Elev= 30
  3939.8  470.28  4065.1  461.45  4139.8  458.38  4266.3  450.61  4355.8  443.95
  4378.1  441.02  4452.9  434.85  4499.5  432.04  4540.4  431.32    4573  432.73
  4618.5  431.02  4846.5  427.38  4871.2  426.21  4897.6  422.82  4972.2  420.42
  4989.4  411.35  4996.6  409.45  4999.4  408.95  5002.6  409.45  5009.8  415.62
  5022.8  420.32  5040.5  422.66  5091.5  426.07  5169.3  438.16    5214  442.57
  5336.4  457.89  5377.2  460.55  5407.9  460.91  5458.9  464.49  5560.5  465.92
#Mann= 3 ,-1 , 0
  3939.8     .05       0  4996.6     .03       0  5002.6     .05       0
Bank Sta=4972.2,5022.8
XS Rating Curve= 0 ,0
Exp/Cntr=0.3,0.1

Type RM Length L Ch R = 1 ,2559    ,246,246,246
BEGIN DESCRIPTION:
Mapping XS c67d7334
END DESCRIPTION:
XS GIS Cut Line= 2
      3585543.85     10521684.73      3586406.07     10521970.69
#Sta/Elev= 30
    4487  442.23  4566.8  441.42  4614.9  439.18  4620.1  440.26  4678.2  436.49
  4683.5   437.4  4709.9  434.78  4788.1   431.2  4851.3  422.61  4914.5  418.39
    4925  417.76  4931.7  415.23  4963.4  417.99  4977.7  413.31  4985.2  409.29
    4988  408.79  4991.2  409.29  5000.4  409.56  5009.3  414.14  5019.8  414.62
  5026.8  418.37  5032.1  421.18  5063.8  425.01  5121.9   434.8  5146.3  436.49
  5167.3  441.54  5209.5  446.77  5241.1  448.59    5312  458.51  5395.4  462.79
#Mann= 3 ,-1 , 0
    4487     .05       0  4985.2     .03       0  4991.2     .05       0
Bank Sta=4914.5,5026.8
XS Rating Curve= 0 ,0
Exp/Cntr=0.3,0.1

Type RM Length L Ch R = 1 ,2313    ,458,458,458
BEGIN DESCRIPTION:
UNT 018 IN BUCR 3.0
END DESCRIPTION:
XS GIS Cut Line= 3
      3585549.58     10521710.16      3585849.61     10522010.19
       3586249.6     10522260.18
#Sta/Elev= 30
  4569.6  442.53  4753.5  440.03  4866.6  428.17  4894.9  424.22  4909.1  420.86
  4937.3   417.9  4979.8  412.51  4987.4  409.13  4990.1  408.63  4993.4  409.13
  5016.9  412.31  5022.8  416.21  5052.9  418.05  5080.6  419.38  5117.1   418.4
  5159.6  420.97  5182.6  424.34  5190.3  426.67  5196.2  426.59  5226.8  432.88
  5241.6  434.03  5253.9  437.36  5269.3  438.76  5321.2  447.23  5342.4  449.55
  5357.7  449.46  5378.9   453.3  5394.3  453.78  5400.2  456.35  5465.6  464.31
#Mann= 3 ,-1 , 0
  4569.6     .05       0  4987.4     .03       0  4993.4     .05       0
Bank Sta=4937.3,5052.9
XS Rating Curve= 0 ,0
Exp/Cntr=0.3,0.1

Type RM Length L Ch R = 1 ,1855    ,551,551,551
BEGIN DESCRIPTION:
UNT 018 IN BUCR 2.0
END DESCRIPTION:
XS GIS Cut Line= 3
      3585149.63     10521710.23      3585449.61     10522210.19
      3586249.58     10522660.17
#Sta/Elev= 30
  4412.1  462.33    4427  461.65  4460.2  456.47  4637.5  436.52  4695.8   427.2
  4769.7  418.45  4778.5  416.74  4796.9  412.63  4806.6  408.29    4821   407.3
  4933.8  407.13  4936.6  406.63  4939.8  407.13  4971.8   407.2  4981.5  410.89
  5304.9  410.89    5311  412.07  5316.7  410.89  5326.9  413.51  5332.7  412.87
  5339.4  416.38  5362.3  417.27  5385.2   415.3  5397.7  419.17  5435.3  418.43
  5488.5  429.74  5649.1  454.55  5678.1  461.03  5759.1  467.63    5913  487.57
#Mann= 7 ,-1 , 0
  4412.1     .15       0    4427      .1       0  4460.2     .05       0
  4778.5      .1       0    4821     .05       0  4933.8    .033       0
  4939.8     .05       0
Bank Sta=4769.7,5397.7
XS Rating Curve= 0 ,0
Exp/Cntr=0.3,0.1

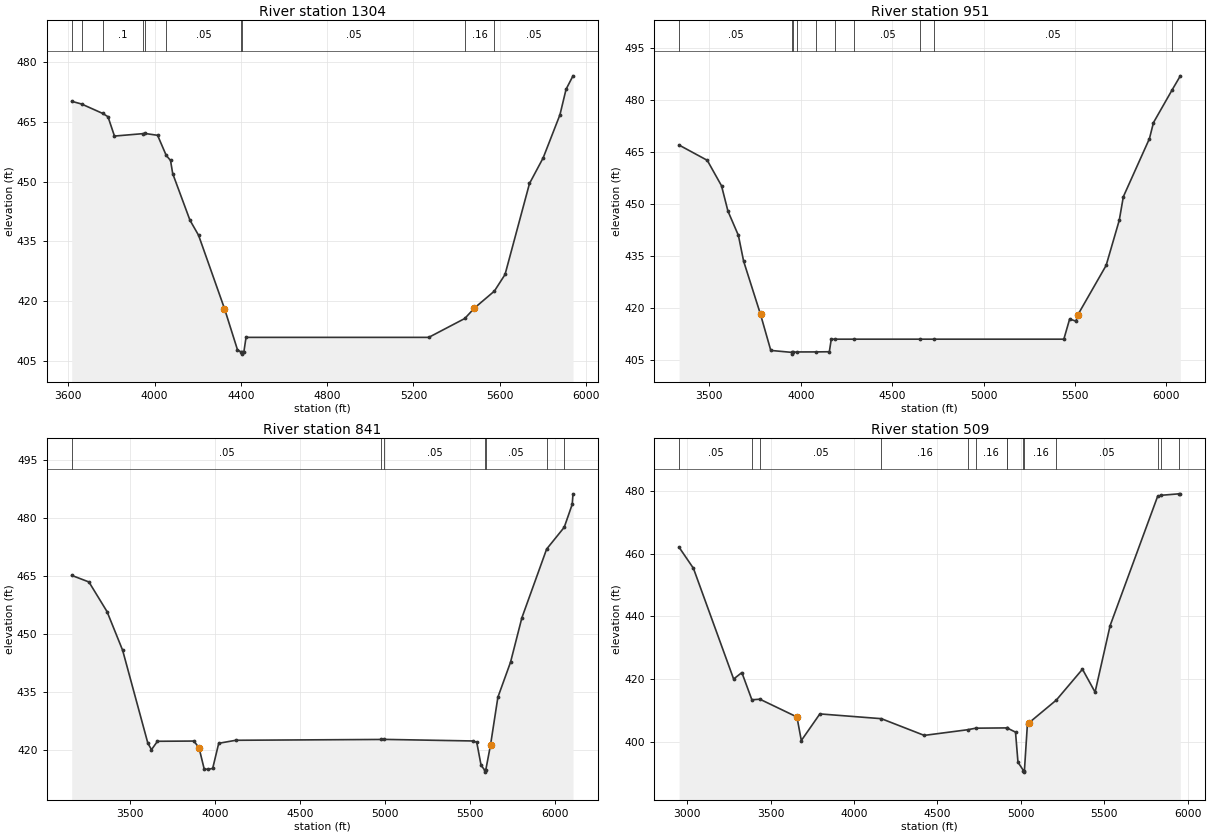
Type RM Length L Ch R = 1 ,1304    ,353,353,353
BEGIN DESCRIPTION:
Mapping XS 0c02f4d5
END DESCRIPTION:
XS GIS Cut Line= 3
       3584878.3     10521372.08      3584882.64     10522422.44
      3585815.18     10523289.92
#Sta/Elev= 30
  3615.5  470.18  3661.1   469.5  3759.2  467.13  3783.6  466.31  3813.6  461.45
  3946.3  462.06  3955.5   462.1  4013.6  461.64  4053.6  456.59  4073.6  455.32
  4083.6  452.03  4163.6  440.32  4203.6  436.53  4323.6  418.13  4383.6  407.83
  4400.6  407.18  4403.4  406.68  4406.6  407.18  4413.6  407.24  4423.6  410.89
  5270.7  410.89  5437.8  415.63  5482.7  418.26    5575  422.51  5624.4  426.68
  5737.8  449.54  5801.3  455.99    5879   466.8  5907.3   473.2  5939.5  476.58
#Mann= 10 ,-1 , 0
  3615.5      .1       0  3661.1     .05       0  3759.2      .1       0
  3946.3     .15       0  3955.5      .1       0  4053.6     .05       0
  4400.6    .035       0  4406.6     .05       0  5437.8     .16       0
    5575     .05       0
Bank Sta=4323.6,5482.7
XS Rating Curve= 0 ,0
Exp/Cntr=0.3,0.1

Type RM Length L Ch R = 1 ,951     ,110,110,110
BEGIN DESCRIPTION:
Mapping XS e3b929b2
END DESCRIPTION:
XS GIS Cut Line= 6
      3584782.83     10521476.24      3584453.58     10521867.92
      3584643.93     10522405.08      3584860.94     10522869.49
      3585173.44     10523216.71      3585775.72     10523533.01
#Sta/Elev= 30
  3334.8  466.96  3488.8  462.56  3566.9   455.2    3602  447.89  3659.2  440.87
  3687.8  433.42  3780.2  418.06  3836.4  407.64    3952  407.07  3954.7  406.57
    3958  407.07  3977.5   407.2    4083  407.21  4156.6  407.26  4167.2  410.89
  4188.6  410.89  4294.1  410.89  4654.5  410.89  4729.9  410.89  5439.2  410.89
  5470.9  416.71  5505.4  416.09    5516  417.95  5670.5   432.2  5742.3  445.24
  5764.5  452.03  5907.4  468.83  5929.4  473.45  6030.4   482.8  6076.4  486.96
#Mann= 10 ,-1 , 0
  3334.8     .05       0    3952    .035       0    3958     .05       0
  3977.5      .1       0    4083     .05       0  4188.6      .1       0
  4294.1     .05       0  4654.5      .1       0  4729.9     .05       0
  6030.4     .08       0
Bank Sta=3780.2,5516
XS Rating Curve= 0 ,0
Exp/Cntr=0.3,0.1

Type RM Length L Ch R = 1 ,841     ,332,332,332
BEGIN DESCRIPTION:
Mapping XS e0381b37
END DESCRIPTION:
XS GIS Cut Line= 6
      3584669.71       10521407.      3584315.56     10521784.59
      3584778.48     10522934.59      3584926.05     10523116.88
      3585156.08      10523355.6       3585745.5     10523567.96
#Sta/Elev= 30
  3156.9  465.23  3258.1  463.53  3364.5  455.88  3456.4  445.87  3604.9  421.83
  3626.3  420.15  3661.5  422.32  3875.6  422.38    3906  420.65  3936.5  415.14
  3961.4  415.06  3986.5  415.32    4022   421.8  4122.9  422.58  4979.5  422.79
  4994.5  422.81  5516.1   422.4  5540.5  422.07  5565.9  416.13  5587.5  414.84
  5590.3  414.34  5593.5  414.84  5621.9  421.44  5664.9  433.71  5739.3  442.77
  5806.1  454.26  5951.8  472.04  6055.4  477.68  6102.4  483.62    6107  486.33
#Mann= 7 ,-1 , 0
  3156.9     .05       0  4979.5     .16       0  4994.5     .05       0
  5587.5     .03       0  5593.5     .05       0  5951.8      .1       0
  6055.4     .08       0
Bank Sta=3906,5621.9
XS Rating Curve= 0 ,0
Exp/Cntr=0.3,0.1

Type RM Length L Ch R = 1 ,509     ,0,0,0
BEGIN DESCRIPTION:
UNT 018 IN BUCR 1.0
END DESCRIPTION:
XS GIS Cut Line= 6
      3584570.15     10521489.27      3584250.46     10521768.96
       3584500.7     10522639.45      3584730.73     10523177.65
      3584991.15     10523364.28      3585702.93     10523655.06
#Sta/Elev= 30
    2951  462.04    3037  455.33  3278.1  420.03  3327.4  422.09  3387.5  413.41
  3435.5   413.6  3657.7  407.93  3683.9  400.42  3795.1  408.91  4163.7  407.39
    4421  402.06  4680.4  403.86  4729.7  404.36  4916.7  404.45  4917.1  404.44
  4968.2   403.1  4982.9  393.53  5015.6  390.85  5018.3  390.35  5021.6  390.85
  5039.5  405.64    5048  406.03  5212.9  413.32  5369.6  423.16  5445.2  415.85
  5535.4  437.06  5820.2  478.26  5840.7   478.6  5945.8  479.06  5956.5  479.07
#Mann= 14 ,-1 , 0
    2951     .05       0  3387.5     .16       0  3435.5     .05       0
  4163.7     .16       0  4680.4     .05       0  4729.7     .16       0
  4916.7     .05       0  4917.1     .16       0  5015.6     .07       0
  5021.6     .16       0  5212.9     .05       0  5820.2     .08       0
  5840.7     .15       0  5945.8      .1       0
Bank Sta=3657.7,5048
XS Rating Curve= 0 ,0
Exp/Cntr=0.3,0.1

Chan Stop Cuts=-1
Use User Specified Reach Order=0
Composite Channel Slope=5