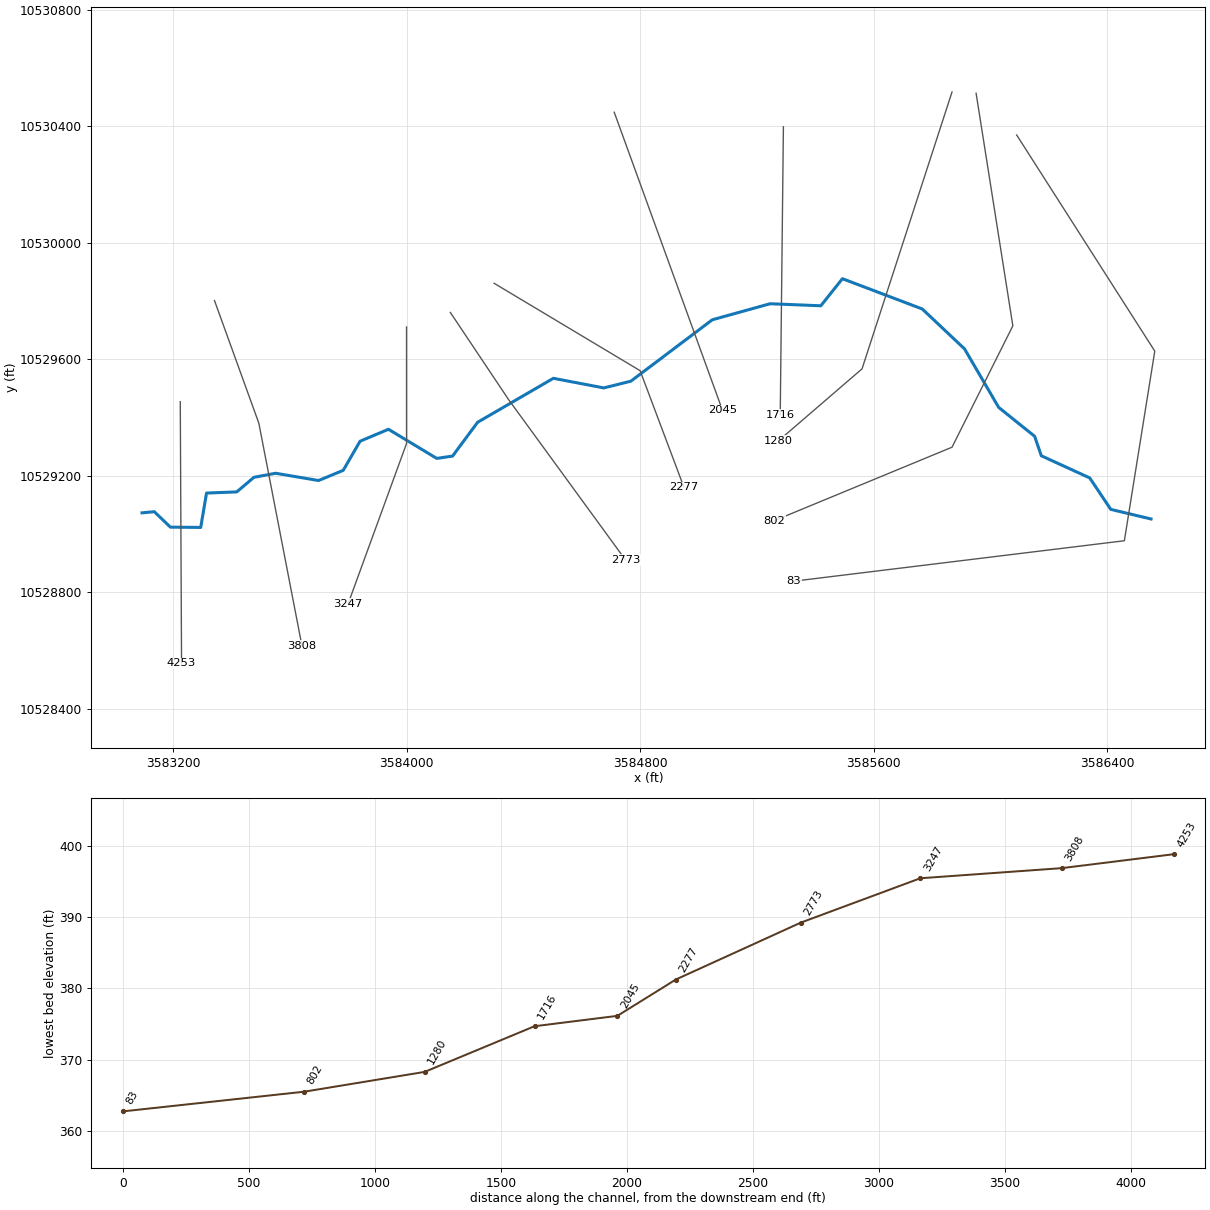
--- UNT 020 IN BUCR.prj (project) ---

Proj Title=UNT 020 IN BUCR Base Level Engineering
Current Plan=p01
Default Exp/Contr=0.3,0.1
English Units
Geom File=g01
Flow File=f01
Plan File=p01
Y Axis Title=Elevation
X Axis Title(PF)=Main Channel Distance
X Axis Title(XS)=Station
BEGIN DESCRIPTION:
UNT 020 IN BUCR
END DESCRIPTION:
DSS Export Rating Curves= 0
DSS Export Rating Curve Sorted= 0
DSS Export Volume Flow Curves= 0
DXF OffsetX= 0
DXF OffsetY= 0
DXF ScaleX= 1
DXF ScaleY= 10

--- UNT 020 IN BUCR.p01 (plan) ---

Plan Title=Multiple Run
Short Identifier=Multiple
Geom File=g01
Flow File=f01
Subcritical Flow
K Sum by GR= 0
Std Step Tol= 0.01
Critical Tol= 0.01
Num of Std Step Trials= 20
Max Error Tol= 0.3
Flow Tol Ratio= 0.001
Split Flow NTrial= 30
Split Flow Tol= 0.02
Split Flow Ratio= 0.02
Log Output Level= 0
Friction Slope Method= 1
Unsteady Friction Slope Method= 2
Unsteady Bridges Friction Slope Method= 1
Parabolic Critical Depth
Global Vel Dist=  1 , 1 , 1
Global Log Level= 0
CheckData=True
Encroach Param= -1, 0, 0, 0
BEGIN DESCRIPTION:
Multiple Run
END DESCRIPTION:

--- UNT 020 IN BUCR.f01 (steady flow) ---

Flow Title=Multiple
Number of Profiles=7
Profile Names=10-year,25-year,50-year,1pct_min,100-year,1pct_plu,500-year
River Rch & RM= UNT 020 IN BUCR,Reach-1,4253
    1174    1630    2011    1810    2448    3311    3617
Boundary for River Rch & Prof#=UNT 020 IN BUCR,Reach-1,1
Up Type=0
Dn Type=3
Dn Slope=0.005
Boundary for River Rch & Prof#=UNT 020 IN BUCR,Reach-1,2
Up Type=0
Dn Type=3
Dn Slope=0.005
Boundary for River Rch & Prof#=UNT 020 IN BUCR,Reach-1,3
Up Type=0
Dn Type=3
Dn Slope=0.005
Boundary for River Rch & Prof#=UNT 020 IN BUCR,Reach-1,4
Up Type=0
Dn Type=3
Dn Slope=0.005
Boundary for River Rch & Prof#=UNT 020 IN BUCR,Reach-1,5
Up Type=0
Dn Type=3
Dn Slope=0.005
Boundary for River Rch & Prof#=UNT 020 IN BUCR,Reach-1,6
Up Type=0
Dn Type=3
Dn Slope=0.005
Boundary for River Rch & Prof#=UNT 020 IN BUCR,Reach-1,7
Up Type=0
Dn Type=3
Dn Slope=0.005

--- UNT 020 IN BUCR.g01 (geometry) ---

Geom Title=Existing Conditions
Program Version=4.10

River Reach=UNT 020 IN BUCR ,Reach-1
Reach XY= 30
      3583093.75       10529072.      3583135.75       10529076.
      3583190.75       10529023.      3583294.75       10529022.
       3583314.5       10529140.        3583418.       10529144.
        3583477.       10529194.        3583551.       10529208.
      3583698.25       10529183.      3583782.75       10529218.
       3583840.5       10529318.      3583937.75       10529359.
        3584103.       10529259.      3584157.25       10529267.
        3584243.       10529383.       3584502.5       10529534.
      3584675.25       10529501.      3584767.75       10529524.
        3585047.       10529735.      3585244.75       10529790.
       3585418.5       10529783.       3585492.5       10529876.
        3585766.       10529772.      3585910.75       10529635.
      3586027.75       10529434.      3586150.75       10529335.
      3586173.75       10529268.       3586339.5       10529192.
       3586411.5       10529084.       3586549.5       10529051.

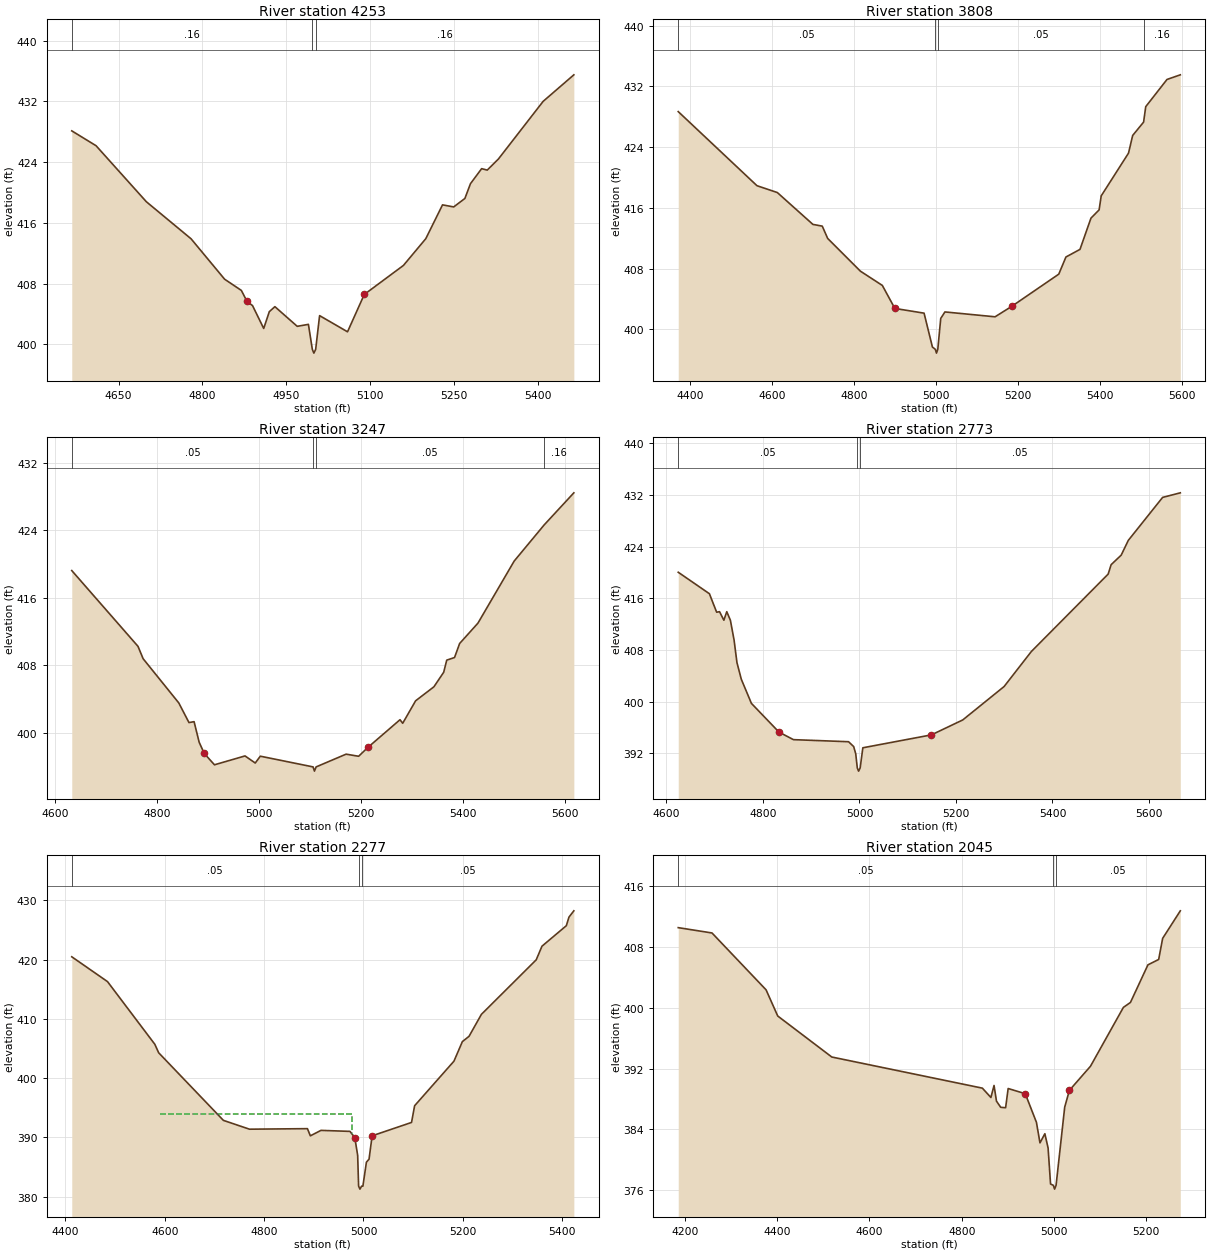
Type RM Length L Ch R = 1 ,4253    ,445,445,445
BEGIN DESCRIPTION:
UNT 020 IN BUCR 8.0
END DESCRIPTION:
XS GIS Cut Line= 2
      3583224.66      10529453.7        3583229.     10528555.21
#Sta/Elev= 30
  4566.3  428.13  4609.8  426.17  4699.8  418.79  4779.8  413.91  4839.8  408.59
  4869.8  407.11  4879.8  405.68  4889.8  405.11  4909.8   402.1  4919.8  404.31
  4929.8  404.97  4969.8  402.38  4989.8  402.64  4996.8  399.35  4999.6  398.85
  5002.8  399.35  5009.8  403.79  5059.8  401.66  5089.8  406.58  5159.8   410.4
  5199.8  413.92  5229.8  418.38  5249.8  418.11  5269.8  419.22  5279.8  421.17
  5299.8  423.15  5309.8  422.96  5329.8  424.42  5409.8  432.01  5464.8  435.51
#Mann= 3 ,-1 , 0
  4566.3     .16       0  4996.8     .07       0  5002.8     .16       0
Bank Sta=4879.8,5089.8
XS Rating Curve= 0 ,0
Exp/Cntr=0.3,0.1

Type RM Length L Ch R = 1 ,3808    ,561,561,561
BEGIN DESCRIPTION:
UNT 020 IN BUCR 7.0
END DESCRIPTION:
XS GIS Cut Line= 3
      3583341.83     10529800.94      3583493.75      10529379.9
      3583641.32     10528616.03
#Sta/Elev= 30
  4371.2  428.67  4563.4  418.92  4613.1  418.02  4699.9  413.83  4722.8   413.6
  4735.9  411.99    4816  407.67  4869.4   405.8    4900  402.77  4971.3  402.15
  4991.7  397.69  4998.8  397.39  5001.6  396.89  5004.8  397.39    5012  401.46
  5022.2  402.31  5144.6  401.67  5185.2  403.04  5300.1  407.28  5317.6  409.54
  5351.9  410.54  5378.7  414.65  5398.6  415.74  5403.7  417.58  5470.4  423.21
  5480.5  425.53  5507.2  427.29  5512.4  429.32  5564.3   432.9  5596.8  433.51
#Mann= 4 ,-1 , 0
  4371.2     .05       0  4998.8     .03       0  5004.8     .05       0
  5507.2     .16       0
Bank Sta=4900,5185.2
XS Rating Curve= 0 ,0
Exp/Cntr=0.3,0.1

Type RM Length L Ch R = 1 ,3247    ,474,474,474
BEGIN DESCRIPTION:
UNT 020 IN BUCR 6.0
END DESCRIPTION:
XS GIS Cut Line= 3
      3583999.61     10529710.18      3583999.61     10529310.19
      3583799.62     10528760.21
#Sta/Elev= 30
  4632.6  419.23  4762.6  410.25  4772.6  408.79  4842.6  403.55  4862.6  401.22
  4872.6  401.33  4882.6  398.89  4892.6  397.56  4912.6  396.22  4972.6  397.27
  4992.6  396.43  5002.6  397.24  5106.1  395.97  5108.8  395.47  5112.1  395.97
  5170.9  397.48  5195.5  397.23  5213.5  398.27  5276.7  401.56    5282  401.14
  5307.3   403.8  5343.2  405.46  5362.4  407.18  5368.4  408.62  5383.7  408.93
  5393.7  410.59  5429.6     413  5500.8  420.36  5559.6  424.64  5617.8  428.44
#Mann= 4 ,-1 , 0
  4632.6     .05       0  5106.1     .03       0  5112.1     .05       0
  5559.6     .16       0
Bank Sta=4892.6,5213.5
XS Rating Curve= 0 ,0
Exp/Cntr=0.3,0.1

Type RM Length L Ch R = 1 ,2773    ,496,496,496
BEGIN DESCRIPTION:
UNT 020 IN BUCR 5.0
END DESCRIPTION:
XS GIS Cut Line= 3
      3584149.62     10529760.17      3584349.61     10529460.19
      3584749.61     10528910.19
#Sta/Elev= 30
  4624.4  420.02    4689   416.7    4704  413.84    4710  413.92    4719   412.6
    4725  413.92  4732.5   412.6  4740.1  409.55  4746.1  406.05  4755.1  403.47
  4776.1  399.73  4833.2  395.29  4863.2  394.12  4977.4   393.8    4988  393.05
  4992.3  391.93  4995.5  389.75  4998.2  389.25  5001.5  389.75    5007  392.86
  5149.2  394.86  5214.1  397.17  5299.8  402.34  5356.3  407.76  5515.5  419.74
  5521.6  421.19  5542.5  422.67  5557.2  424.95  5628.3   431.6    5665  432.31
#Mann= 3 ,-1 , 0
  4624.4     .05       0  4995.5     .03       0  5001.5     .05       0
Bank Sta=4833.2,5149.2
XS Rating Curve= 0 ,0
Exp/Cntr=0.3,0.1

Type RM Length L Ch R = 1 ,2277    ,232,232,232
BEGIN DESCRIPTION:
UNT 020 IN BUCR 4.0
END DESCRIPTION:
XS GIS Cut Line= 3
      3584299.62     10529860.18      3584799.61     10529560.19
      3584949.61     10529160.18
#Sta/Elev= 30
    4413  420.49  4484.9   416.3  4580.1  405.72  4587.9  404.28  4718.1  392.87
  4770.6  391.38  4887.2  391.47  4893.1  390.26  4914.5  391.18  4972.8  391.01
  4982.5  389.97  4988.3  386.96  4990.2  381.76  4992.9  381.26  4996.2  381.76
  4998.8  381.76  5005.9  385.81  5011.2  386.32  5017.4  390.26  5096.7  392.52
  5102.9  395.34  5182.1  402.87    5199  406.17  5212.4  407.06  5237.3  410.77
  5347.6  419.98  5359.2  422.28  5408.2  425.74  5413.5  427.19  5423.3  428.25
#Mann= 3 ,-1 , 0
    4413     .05       0  4990.2     .03       0  4996.2     .05       0
#XS Ineff= 1 ,-1
 4590.91 4976.82  393.95
Permanent Ineff=
       F
Bank Sta=4982.5,5017.4
XS Rating Curve= 0 ,0
Exp/Cntr=0.3,0.1

Type RM Length L Ch R = 1 ,2045    ,329,329,329
BEGIN DESCRIPTION:
Mapping XS 37997951
END DESCRIPTION:
XS GIS Cut Line= 2
      3584710.93     10530447.49      3585081.67     10529424.18
#Sta/Elev= 30
  4185.5  410.52  4258.7  409.82  4375.9  402.35  4401.2  398.91  4518.4  393.52
  4844.8  389.43  4863.3   388.2  4870.1  389.78  4875.4  387.72  4884.6  386.91
  4895.2  386.86  4900.7  389.38  4937.8   388.7    4962  384.94  4969.7  382.24
  4980.3  383.44  4987.3  381.56  4992.6  376.84  4998.6  376.66  5001.4  376.16
  5004.6  376.66  5023.3  386.94  5033.5  389.14  5079.2  392.31  5150.5  400.04
  5165.8  400.69  5203.7  405.63    5227  406.34  5235.6  409.11  5273.9  412.73
#Mann= 3 ,-1 , 0
  4185.5     .05       0  4998.6     .03       0  5004.6     .05       0
Bank Sta=4937.8,5033.5
XS Rating Curve= 0 ,0
Exp/Cntr=0.3,0.1

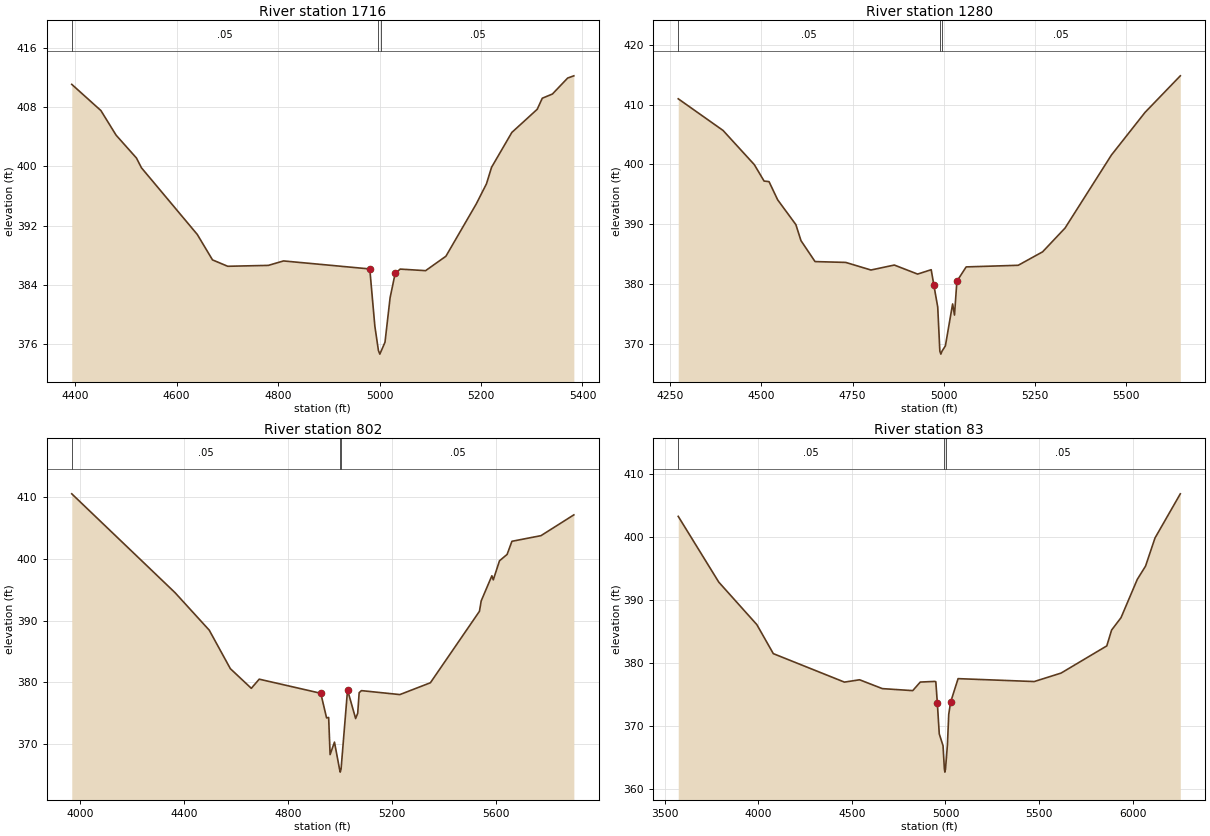
Type RM Length L Ch R = 1 ,1716    ,436,436,436
BEGIN DESCRIPTION:
UNT 020 IN BUCR 3.0
END DESCRIPTION:
XS GIS Cut Line= 2
      3585290.37     10530397.56      3585279.52     10529408.02
#Sta/Elev= 30
  4393.4  411.06  4450.8  407.53  4480.8  404.21  4520.8  401.14  4530.8  399.81
  4640.8  390.83  4670.8   387.4  4700.8  386.54  4780.8  386.66  4810.8  387.26
  4980.8  386.18  4990.8  378.46  4997.8   375.2  5000.6   374.7  5003.8   375.2
  5010.8  376.31  5020.8  382.29  5030.8  385.58  5040.8  386.16  5090.8  385.95
  5130.8  387.89  5190.8  394.96  5210.8  397.66  5220.8  399.88  5260.8  404.58
  5310.8   407.7  5320.8  409.19  5340.8  409.76  5370.8  411.91    5383  412.21
#Mann= 3 ,-1 , 0
  4393.4     .05       0  4997.8     .03       0  5003.8     .05       0
Bank Sta=4980.8,5030.8
XS Rating Curve= 0 ,0
Exp/Cntr=0.3,0.1

Type RM Length L Ch R = 1 ,1280    ,478,478,478
BEGIN DESCRIPTION:
UNT 020 IN BUCR 2.0
END DESCRIPTION:
XS GIS Cut Line= 3
      3585867.89     10530517.06      3585559.73     10529566.54
      3585273.97     10529319.75
#Sta/Elev= 30
  4271.7  410.97  4394.6  405.68  4480.4  399.96  4507.1  397.22  4520.7  397.12
  4544.4  394.08  4594.3  389.94  4608.3  387.26  4646.9  383.76    4731  383.62
  4800.2  382.35  4864.2  383.18  4928.1  381.67  4965.4   382.4  4972.7  379.81
  4983.3  376.16  4989.1  368.79  4991.9  368.29  4995.1  368.79  5004.3  369.67
  5024.1  376.68  5029.3  374.82  5035.8  380.47  5061.3  382.87    5204  383.14
  5270.9  385.39  5332.4  389.36  5459.6  401.57  5551.8   408.7  5648.5  414.81
#Mann= 3 ,-1 , 0
  4271.7     .05       0  4989.1     .03       0  4995.1     .05       0
Bank Sta=4972.7,5035.8
XS Rating Curve= 0 ,0
Exp/Cntr=0.3,0.1

Type RM Length L Ch R = 1 ,802     ,719,719,719
BEGIN DESCRIPTION:
Mapping XS a0d42741
END DESCRIPTION:
XS GIS Cut Line= 4
      3585950.35      10530512.7      3586076.22      10529714.1
      3585867.89     10529297.44      3585260.27     10529045.71
#Sta/Elev= 30
  3967.4  410.48  4364.8  394.51  4496.4  388.45  4577.6  382.23  4658.3  379.05
  4688.7  380.53  4925.6  378.25  4947.9  374.27  4955.9  374.34  4961.5  368.34
  4978.3  370.36  4997.7  366.01  5000.4  365.51  5003.7  366.01  5028.6  378.79
  5059.7  374.17  5067.7  375.03  5073.3  378.35  5082.1  378.68  5229.9  378.04
  5347.4  379.95  5536.2   391.5  5542.9  393.18    5584  397.24  5589.4  396.58
  5613.3  399.66  5642.6  400.69  5661.1  402.81  5772.9  403.72  5899.4  407.08
#Mann= 3 ,-1 , 0
  3967.4     .05       0  4997.7     .03       0  5003.7     .05       0
Bank Sta=4925.6,5028.6
XS Rating Curve= 0 ,0
Exp/Cntr=0.3,0.1

Type RM Length L Ch R = 1 ,83      ,0,0,0
BEGIN DESCRIPTION:
UNT 020 IN BUCR 1.0
END DESCRIPTION:
XS GIS Cut Line= 4
      3586089.27     10530369.45      3586562.33      10529627.3
      3586458.16     10528976.26      3585325.37     10528837.37
#Sta/Elev= 30
  3573.3  403.27  3789.8  392.85    3993  386.12    4081  381.52  4460.6  377.01
  4541.6  377.38  4663.1  375.98  4825.2  375.66  4865.7  377.02  4943.5  377.12
  4948.6  377.07  4956.8  373.66    4967  368.81  4987.2  366.93  4994.3  363.25
  4997.1  362.75  5000.3  363.25  5010.6  367.09  5017.6  371.91  5027.7  373.85
  5067.5  377.56    5474   377.1  5617.3  378.44  5861.5  382.75    5887  385.25
  5937.4  387.22  6024.2  393.28  6068.4  395.39  6118.8  399.84    6254  406.84
#Mann= 3 ,-1 , 0
  3573.3     .05       0  4994.3     .03       0  5000.3     .05       0
Bank Sta=4956.8,5027.7
XS Rating Curve= 0 ,0
Exp/Cntr=0.3,0.1

Chan Stop Cuts=-1
Use User Specified Reach Order=0
Composite Channel Slope=5