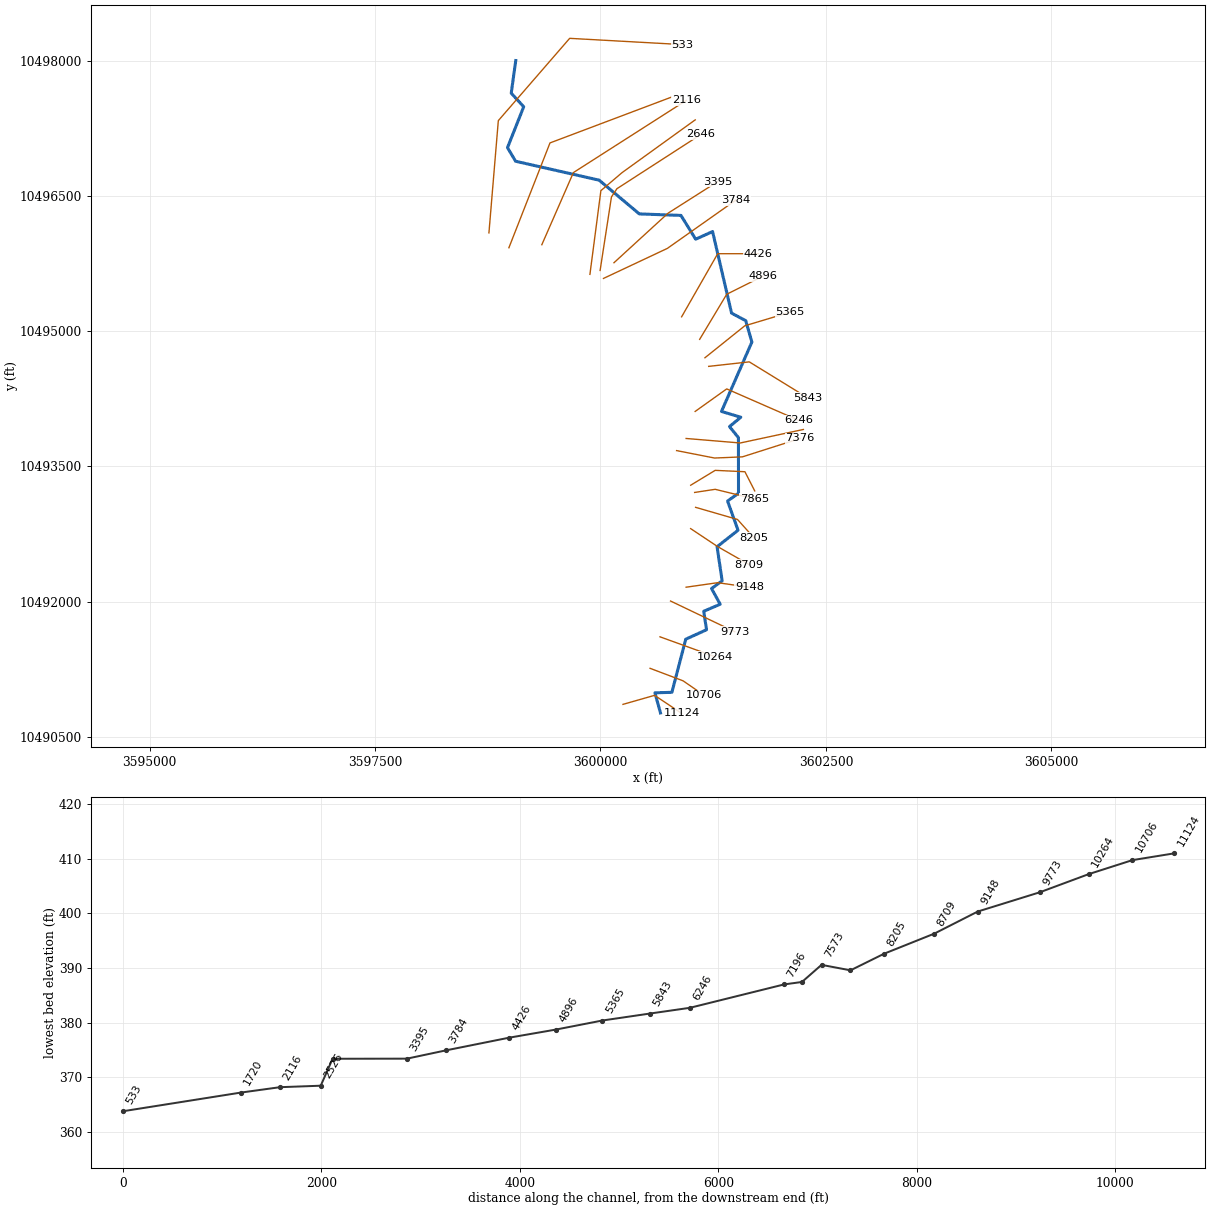
--- UNT 036 IN BUCR.prj (project) ---

Proj Title=UNT 036 IN BUCR Base Level Engineering
Current Plan=p01
Default Exp/Contr=0.3,0.1
English Units
Geom File=g01
Flow File=f01
Plan File=p01
Y Axis Title=Elevation
X Axis Title(PF)=Main Channel Distance
X Axis Title(XS)=Station
BEGIN DESCRIPTION:
UNT 036 IN BUCR
END DESCRIPTION:
DSS Export Rating Curves= 0
DSS Export Rating Curve Sorted= 0
DSS Export Volume Flow Curves= 0
DXF OffsetX= 0
DXF OffsetY= 0
DXF ScaleX= 1
DXF ScaleY= 10

--- UNT 036 IN BUCR.p01 (plan) ---

Plan Title=Multiple Run
Program Version=4.10
Short Identifier=Multiple
Geom File=g01
Flow File=f01
Subcritical Flow
K Sum by GR= 0
Std Step Tol= 0.01
Critical Tol= 0.01
Num of Std Step Trials= 20
Max Error Tol= 0.3
Flow Tol Ratio= 0.001
Split Flow NTrial= 30
Split Flow Tol= 0.02
Split Flow Ratio= 0.02
Log Output Level= 0
Friction Slope Method= 1
Unsteady Friction Slope Method= 2
Unsteady Bridges Friction Slope Method= 1
Parabolic Critical Depth
Global Vel Dist= 1 , 1 , 1
Global Log Level= 0
CheckData=True
Encroach Param=-1 ,0,0, 0
BEGIN DESCRIPTION:
Multiple Run
END DESCRIPTION:
Computation Interval=1HOUR
Output Interval=1HOUR
Run HTab= 0
Run UNet= 0
Run PostProcess= 0
Run WQNet= 0
UNET Theta= 1
UNET Theta Warmup= 1
UNET ZTol= 0.02
UNET ZSATol= 0.05
UNET MxIter= 20
UNET MaxInSteps= 0
UNET DtIC= 0
UNET DtMin= 0
UNET MaxCRTS= 20
UNET WFStab= 2
UNET SFStab= 1
UNET WFX= 1
UNET SFX= 1
UNET DSS MLevel= 4
UNET DZMax Abort= 100
UNET Convert EG Bridges= 0
UNET Use Existing IB Tables=-1
UNET Froude Reduction=False
UNET Froude Limit= 1
UNET Froude Power= 10
UNET Time Slicing=0,0, 5
UNET Junction Losses=0
Instantaneous Interval=1HOUR
Write IC File= 0
Write IC File at Sim End=0
Echo Input=False
Echo Parameters=False
Echo Output=False
Write Detailed= 0
WQ AD Non Conservative
WQ ULTIMATE=-1
WQ Max Comp Step=1HOUR
WQ Output Interval=15MIN
WQ Output Selected Increments= 0
WQ Output face flow=0
WQ Output face velocity=0
WQ Output face area=0
WQ Output face dispersion=0
WQ Output cell volume=0
WQ Output cell surface area=0
WQ Output cell continuity=0
WQ Output cumulative cell continuity=0
WQ Output face conc=0
WQ Output face dconc_dx=0
WQ Output face courant=0
WQ Output face peclet=0
WQ Output face adv mass=0
WQ Output face disp mass=0
WQ Output cell mass=0
WQ Output cell source sink temp=0
WQ Output cell source sink nsm=0
WQ Output MaxMinRange=-1
WQ Daily Max Min Mean=-1
WQ Daily Range=0
WQ Daily Time=0
WQ Create Restart=0
WQ Fixed Restart=0
WQ System Summary=0
WQ Use Fixed Temperature=0
Sorting and Armoring Iterations= 10
XS Update Threshold= 0.02
Hydraulics Update Threshold= 0.02
Energy Slope Method= 1
Volume Change Method= 0
XS Weighting Method= 0
Number of US Weighted Cross Sections= 1
Number of DS Weighted Cross Sections= 1
Upstream XS Weight=0.25
Main XS Weight=0.5
Downstream XS Weight=0.25
Number of DS XS's Weighted with US Boundary= 1
Upstream Boundary Weight= 1
Weight of XSs Associated with US Boundary= 0
Number of US XS's Weighted with DS Boundary= 1
Downstream Boundary Weight= 0.5
Weight of XSs Associated with DS Boundary= 0.5
Sediment Output Level= 4
Mass or Volume Output= 0
Output Increment Type= 1
Profile and TS Output Increment= 10
XS Output Flag= 0
XS Output Increment= 10
Disregard all LS=0
Disregard all Conn=0
Disregard all Breaches=0
Disregard all Pumps=0

--- UNT 036 IN BUCR.f01 (steady flow) ---

Flow Title=Multiple
Program Version=4.10
Number of Profiles= 7
Profile Names=10-year,25-year,50-year,1pct_min,100-year,1pct_plu,500-year
River Rch & RM=UNT 036 IN BUCR,Reach-1         ,11124
    1069    1486    1835    1655    2238    3027    3318
River Rch & RM=UNT 036 IN BUCR,Reach-1         ,7376
    2202    3175    4015    3697    5000    6762    7740
River Rch & RM=UNT 036 IN BUCR,Reach-1         ,7196
    2202    3175    4015    3697    5000    6762    7740
Boundary for River Rch & Prof#=UNT 036 IN BUCR,Reach-1         , 1
Up Type= 0
Dn Type= 3
Dn Slope=0.004
Boundary for River Rch & Prof#=UNT 036 IN BUCR,Reach-1         , 2
Up Type= 0
Dn Type= 3
Dn Slope=0.004
Boundary for River Rch & Prof#=UNT 036 IN BUCR,Reach-1         , 3
Up Type= 0
Dn Type= 3
Dn Slope=0.004
Boundary for River Rch & Prof#=UNT 036 IN BUCR,Reach-1         , 4
Up Type= 0
Dn Type= 3
Dn Slope=0.004
Boundary for River Rch & Prof#=UNT 036 IN BUCR,Reach-1         , 5
Up Type= 0
Dn Type= 3
Dn Slope=0.004
Boundary for River Rch & Prof#=UNT 036 IN BUCR,Reach-1         , 6
Up Type= 0
Dn Type= 3
Dn Slope=0.004
Boundary for River Rch & Prof#=UNT 036 IN BUCR,Reach-1         , 7
Up Type= 0
Dn Type= 3
Dn Slope=0.004
DSS Import GetInterval= 0
DSS Import GetPeak= 0
DSS Import FillOption= 0

--- UNT 036 IN BUCR.g01 (geometry) ---

Geom Title=Existing Conditions
Program Version=4.10

River Reach=UNT 036 IN BUCR ,Reach-1
Reach XY= 30
      3600665.11     10490765.03       3600603.5       10490988.
      3600791.75       10490994.      3600945.25       10491583.
       3601175.5       10491688.        3601145.       10491893.
      3601327.25       10491971.       3601231.5       10492145.
      3601348.75       10492231.      3601292.75       10492609.
        3601525.       10492792.        3601409.       10493116.
      3601530.25       10493203.      3601529.25       10493820.
      3601430.25       10493942.      3601555.75       10494046.
       3601341.5       10494110.       3601678.5       10494880.
       3601610.5       10495117.      3601453.25       10495201.
      3601242.75       10496106.      3601055.25       10496021.
      3600892.25       10496285.      3600430.57     10496301.66
      3599985.25       10496676.      3599058.75       10496886.
        3598969.       10497037.      3599148.75       10497491.
      3599010.25       10497641.       3599060.5       10498003.

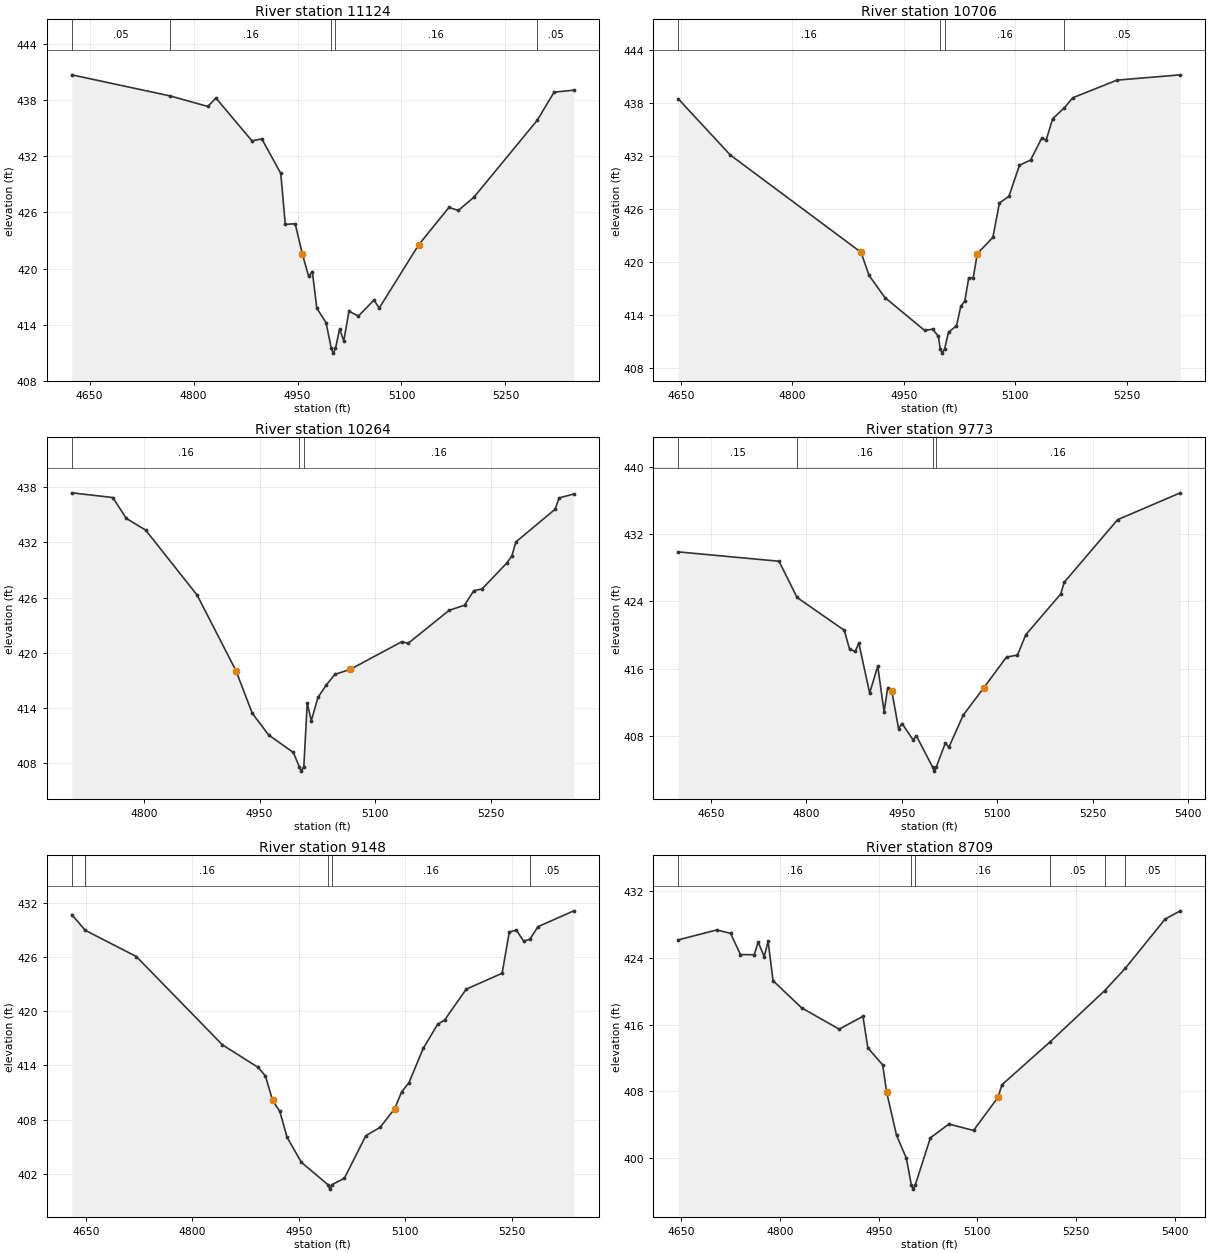
Type RM Length L Ch R = 1 ,11124   ,418,418,418
BEGIN DESCRIPTION:
UNT 036 IN BUCR 20.0
END DESCRIPTION:
XS GIS Cut Line= 3
      3600249.62     10490860.19      3600599.61     10490960.19
      3600899.57     10490760.21
#Sta/Elev= 30
  4624.2  440.69  4766.5  438.43  4820.5  437.31  4832.2  438.21  4884.2  433.64
  4898.5  433.84  4925.8  430.16  4932.3  424.72  4946.6  424.78    4957  421.53
  4966.1  419.15  4971.3  419.68  4977.8  415.76  4991.2   414.2  4998.7  411.46
  5001.5  410.96  5004.7  411.46  5010.7  413.54  5016.7  412.27  5024.2  415.44
  5037.8  414.92  5060.3  416.63  5067.8  415.77  5124.9  422.54  5168.5  426.53
    5182   426.2  5204.5  427.62  5295.8  435.83  5320.2  438.84  5348.7  439.05
#Mann= 5 ,-1 , 0
  4624.2     .05       0  4766.5     .16       0  4998.7     .07       0
  5004.7     .16       0  5295.8     .05       0
Bank Sta=4957,5124.9
XS Rating Curve= 0 ,0
Exp/Cntr=0.3,0.1

Type RM Length L Ch R = 1 ,10706   ,442,442,442
BEGIN DESCRIPTION:
UNT 036 IN BUCR 19.0
END DESCRIPTION:
XS GIS Cut Line= 3
      3600549.57      10491260.2      3600915.63      10491121.4
      3601149.59      10490960.2
#Sta/Elev= 30
  4646.4  438.46  4716.5  432.11  4892.4  421.12  4903.1  418.52  4924.5  416.01
    4978  412.29  4988.7  412.44  4996.5  411.63  4998.9  410.23  5001.6  409.73
  5004.9  410.23  5010.1  412.11  5020.8  412.81  5026.6  415.02    5032  415.62
  5037.3  418.24  5043.3  418.24  5048.8  420.96  5069.8  422.81  5078.6   426.7
  5091.3  427.43  5105.6  430.96  5120.5  431.54  5135.4  433.99  5141.5   433.8
  5150.3  436.22    5166  437.44  5177.3  438.58  5236.8  440.57    5322  441.17
#Mann= 4 ,-1 , 0
  4646.4     .16       0  4998.9     .07       0  5004.9     .16       0
    5166     .05       0
Bank Sta=4892.4,5048.8
XS Rating Curve= 0 ,0
Exp/Cntr=0.3,0.1

Type RM Length L Ch R = 1 ,10264   ,491,491,491
BEGIN DESCRIPTION:
UNT 036 IN BUCR 18.0
END DESCRIPTION:
XS GIS Cut Line= 2
      3600659.56     10491609.67      3601271.56     10491388.31
#Sta/Elev= 30
  4706.6  437.39  4759.8  436.88  4777.2  434.62  4802.4  433.34  4869.1  426.28
  4919.3  418.09  4940.6  413.44  4961.9  411.08  4993.8  409.19  5001.4  407.66
  5004.2  407.16  5007.4  407.66  5011.8  414.54  5017.1  412.64  5025.7  415.16
  5036.3   416.5  5047.7  417.67  5067.7  418.22  5134.4  421.22  5142.6  421.04
  5195.8  424.63  5215.7  425.18  5227.7  426.76  5238.4  426.95  5270.3  429.75
    5277  430.52  5282.3  432.06    5333   435.6  5338.3  436.84  5357.4  437.26
#Mann= 3 ,-1 , 0
  4706.6     .16       0  5001.4     .07       0  5007.4     .16       0
Bank Sta=4919.3,5067.7
XS Rating Curve= 0 ,0
Exp/Cntr=0.3,0.1

Type RM Length L Ch R = 1 ,9773    ,625,625,625
BEGIN DESCRIPTION:
UNT 036 IN BUCR 17.0
END DESCRIPTION:
XS GIS Cut Line= 2
      3600776.73     10492006.82      3601488.58     10491666.09
#Sta/Elev= 30
  4598.5  429.87  4756.9  428.76  4785.3  424.46  4859.6  420.56  4867.8  418.32
  4876.8  418.06  4882.3  419.05  4899.4  413.12  4912.1  416.31  4922.1  410.89
  4927.6  413.67  4934.3  413.33  4944.8   408.9  4950.3   409.5  4967.4  407.58
    4973  408.01  4998.2  404.35  5000.9  403.85  5004.2  404.35  5018.3  407.18
  5023.9  406.69  5046.5   410.5  5078.4   413.7  5114.5  417.39  5131.7  417.62
  5144.9  420.05  5199.7  424.87  5205.2  426.26  5289.1  433.69  5387.7  436.88
#Mann= 4 ,-1 , 0
  4598.5     .15       0  4785.3     .16       0  4998.2     .07       0
  5004.2     .16       0
Bank Sta=4934.3,5078.4
XS Rating Curve= 0 ,0
Exp/Cntr=0.3,0.1

Type RM Length L Ch R = 1 ,9148    ,439,439,439
BEGIN DESCRIPTION:
UNT 036 IN BUCR 16.0
END DESCRIPTION:
XS GIS Cut Line= 3
       3600949.6     10492160.19      3601299.61     10492210.19
      3601649.59     10492160.19
#Sta/Elev= 30
  4630.3  430.68  4649.4  428.94  4721.2  426.05  4842.4  416.29    4893  413.78
  4903.1  412.83  4913.2  410.13  4923.3  408.93  4933.4  406.08  4953.6   403.3
    4991  400.83  4993.7  400.33    4997  400.83  5014.2  401.53  5044.5  406.24
  5064.7  407.17  5084.9  409.21    5095   411.1  5105.1  412.08  5125.3   415.9
  5145.5  418.54  5155.6  419.05  5185.9  422.44  5236.4   424.2  5246.5  428.77
  5256.6  428.95  5266.7  427.75  5275.7  427.97  5286.9  429.35  5337.4   431.1
#Mann= 5 ,-1 , 0
  4630.3      .1       0  4649.4     .16       0    4991     .07       0
    4997     .16       0  5275.7     .05       0
Bank Sta=4913.2,5084.9
XS Rating Curve= 0 ,0
Exp/Cntr=0.3,0.1

Type RM Length L Ch R = 1 ,8709    ,504,504,504
BEGIN DESCRIPTION:
UNT 036 IN BUCR 15.0
END DESCRIPTION:
XS GIS Cut Line= 3
      3600999.64     10492810.17      3601299.61     10492610.19
      3601649.59      10492410.2
#Sta/Elev= 30
  4645.1  426.15  4703.6  427.34  4724.7  426.93  4739.7  424.39  4760.7  424.37
  4766.7   425.9  4775.8  424.14  4781.8  425.98  4789.3  421.26  4832.8     418
  4889.9  415.45    4926  416.99  4933.5  413.21    4956  411.17    4962  407.92
  4977.1  402.74  4992.1  399.97  4999.6  396.78  5002.4  396.28  5005.6  396.78
  5028.6  402.43  5056.7  404.08  5094.2  403.31  5131.6   407.3  5137.3  408.78
  5210.7  413.93  5293.7  420.07  5324.9  422.73  5385.7  428.65  5408.7  429.63
#Mann= 6 ,-1 , 0
  4645.1     .16       0  4999.6     .07       0  5005.6     .16       0
  5210.7     .05       0  5293.7     .16       0  5324.9     .05       0
Bank Sta=4962,5131.6
XS Rating Curve= 0 ,0
Exp/Cntr=0.3,0.1

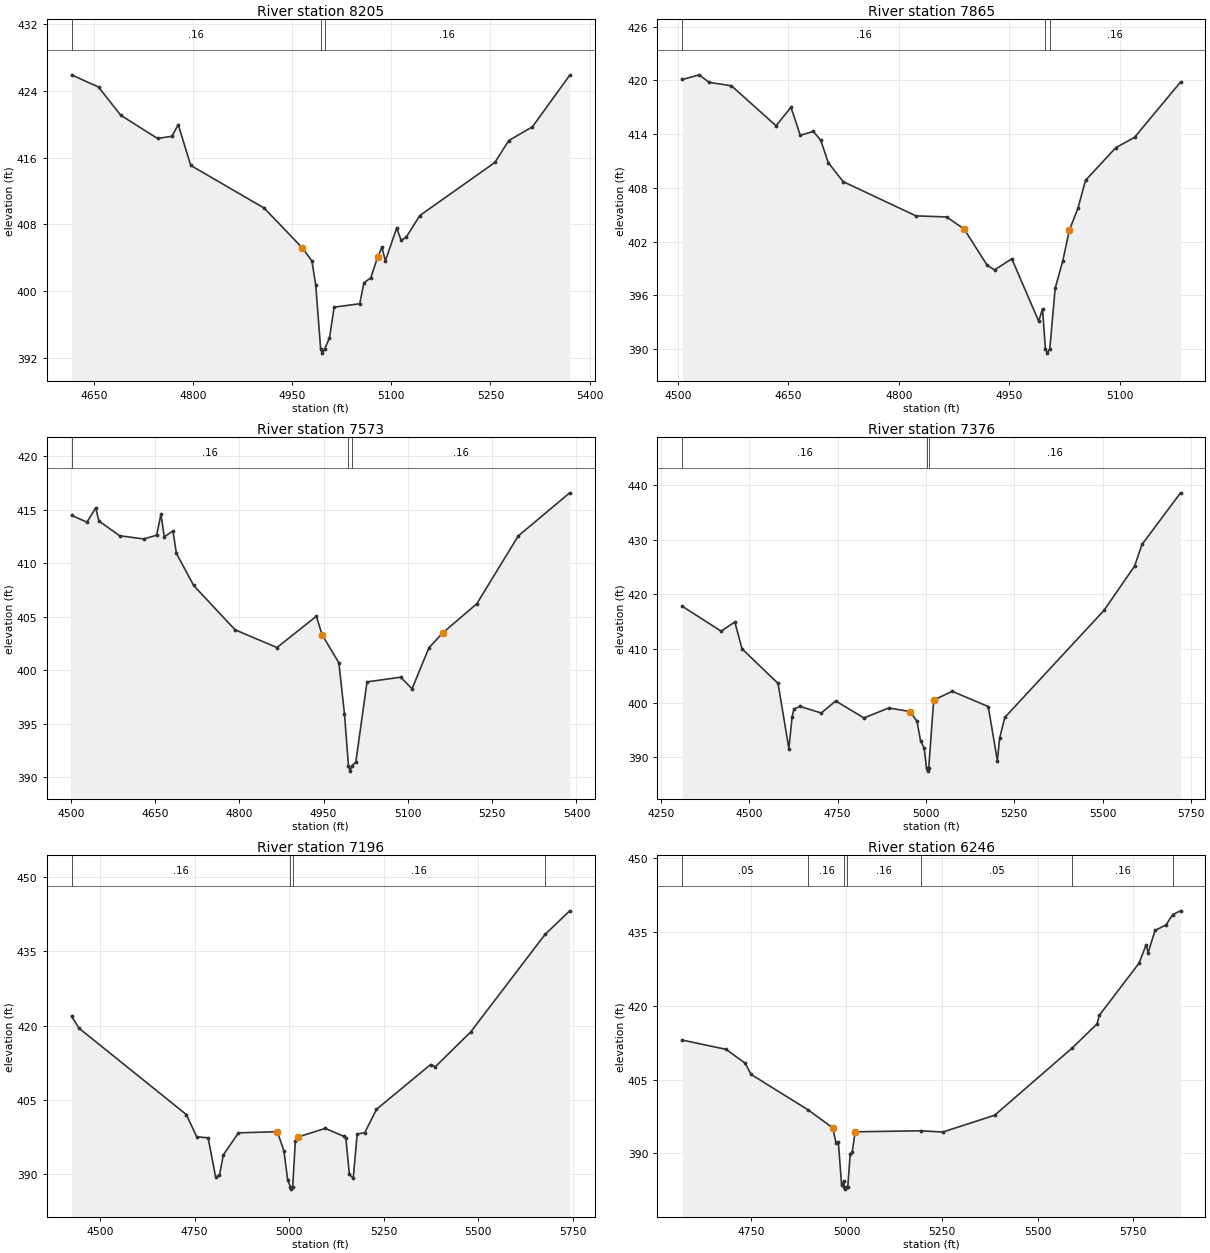
Type RM Length L Ch R = 1 ,8205    ,340,340,340
BEGIN DESCRIPTION:
UNT 036 IN BUCR 14.0
END DESCRIPTION:
XS GIS Cut Line= 3
      3601054.52     10493046.31      3601518.93     10492911.76
      3601699.61     10492710.19
#Sta/Elev= 30
  4615.8  425.89  4656.6  424.43  4690.2  421.06    4746  418.28  4767.8  418.55
  4777.3  419.94  4796.2  415.06  4907.4  409.96  4964.7  405.24  4979.7  403.64
  4985.5  400.74  4992.9  393.12  4995.6  392.62  4998.9  393.12  5006.3  394.42
  5013.3  398.12  5052.1  398.52  5058.4  401.02  5068.8  401.62  5079.2  404.09
  5085.7  405.27  5090.9  403.65    5108  407.57  5114.8  406.11  5122.2  406.45
  5143.1  409.07  5256.7  415.41  5277.7  418.03  5313.6  419.68    5370  425.84
#Mann= 3 ,-1 , 0
  4615.8     .16       0  4992.9     .07       0  4998.9     .16       0
Bank Sta=4964.7,5079.2
XS Rating Curve= 0 ,0
Exp/Cntr=0.3,0.1

Type RM Length L Ch R = 1 ,7865    ,292,292,292
BEGIN DESCRIPTION:
Mapping XS d0da7def
END DESCRIPTION:
XS GIS Cut Line= 3
      3601043.82     10493211.42      3601271.29     10493246.15
      3601704.96     10493140.33
#Sta/Elev= 30
  4506.1  420.09  4529.1  420.61  4542.3  419.77  4572.7  419.39  4633.3  414.93
  4653.6  416.99  4666.2  413.86  4683.9   414.3    4694  413.32  4704.2  410.82
  4724.4   408.7  4823.3  404.88    4865  404.76  4888.9   403.4  4919.8  399.39
    4930  398.85  4953.5  400.09    4990  393.13  4995.2  394.52  4999.1  390.07
  5001.9  389.57  5005.1  390.07  5012.4  396.82  5022.7  399.85  5031.7   403.3
  5043.3  405.72  5053.6  408.84  5094.7  412.48  5120.2  413.64  5182.6   419.8
#Mann= 3 ,-1 , 0
  4506.1     .16       0  4999.1     .07       0  5005.1     .16       0
Bank Sta=4888.9,5031.7
XS Rating Curve= 0 ,0
Exp/Cntr=0.3,0.1

Type RM Length L Ch R = 1 ,7573    ,197,197,197
BEGIN DESCRIPTION:
Mapping XS 6e071d88
END DESCRIPTION:
XS GIS Cut Line= 4
      3601000.25     10493291.53      3601271.53     10493456.47
      3601601.39     10493441.28      3601709.92     10493228.56
#Sta/Elev= 30
  4501.5  414.47  4528.9  413.84  4544.4  415.18  4550.2  413.95    4587  412.57
  4629.7  412.27  4652.9  412.62  4660.6  414.58  4666.5  412.47    4682  413.02
    4688  410.93  4718.8  407.92  4792.4  403.78  4867.1  402.12  4937.2  405.05
  4947.2  403.33  4977.2  400.69  4987.2  395.89  4994.3  391.07    4997  390.57
  5000.3  391.07  5007.3   391.4  5027.3  398.91  5087.3  399.35  5107.4  398.26
  5137.4  402.09  5161.8  403.48  5222.8  406.22  5296.4  412.55    5388  416.58
#Mann= 3 ,-1 , 0
  4501.5     .16       0  4994.3     .07       0  5000.3     .16       0
Bank Sta=4947.2,5161.8
XS Rating Curve= 0 ,0
Exp/Cntr=0.3,0.1

Type RM Length L Ch R = 1 ,7376    ,180,180,180
BEGIN DESCRIPTION:
UNT 036 IN BUCR 13.0
END DESCRIPTION:
XS GIS Cut Line= 4
      3600843.98     10493675.66      3601265.02     10493593.18
      3601573.18     10493606.21      3602213.38      10493810.2
#Sta/Elev= 30
    4311  417.76  4420.6   413.2  4459.4  414.88  4479.8  409.94  4581.7  403.58
  4612.3   391.6  4621.5  397.45  4626.6  398.82  4642.8  399.36    4704  398.14
  4744.8  400.35  4824.7  397.23  4894.8  399.06  4954.8  398.41  4974.8  396.63
  4984.9  393.01  4994.9  391.72  5001.9  387.94  5004.6  387.44  5007.9  387.94
  5022.1  400.51  5074.5  402.13  5176.4  399.32  5202.2  389.39  5208.6  393.47
  5223.2  397.32  5503.8  417.01  5590.5  425.18  5611.5  429.15  5720.4  438.65
#Mann= 3 ,-1 , 0
    4311     .16       0  5001.9     .07       0  5007.9     .16       0
Bank Sta=4954.8,5022.1
XS Rating Curve= 0 ,0
Exp/Cntr=0.3,0.1

Type RM Length L Ch R = 1 ,7196    ,950,950,950
BEGIN DESCRIPTION:
UNT 036 IN BUCR 12.0
END DESCRIPTION:
XS GIS Cut Line= 3
      3600949.64     10493810.19      3601549.61     10493760.19
      3602249.57     10493910.18
#Sta/Elev= 30
  4424.7  421.87  4444.7  419.45  4728.2  402.05  4755.8  397.55  4785.9  397.35
    4806  389.39    4816  389.79  4826.1  393.88  4866.2  398.35    4969  398.58
  4986.6  394.69  4996.6  388.76  5003.7  387.49  5006.4  386.99  5009.7  387.49
  5016.7  396.68  5024.2  397.52  5095.8  399.25  5145.2  397.64  5150.3  397.33
  5159.7  389.97  5169.9  389.18  5180.2  398.08  5200.6  398.41  5231.3  403.09
  5374.5  412.13  5387.2   411.7    5481  418.75  5677.3  438.39  5742.6  443.16
#Mann= 4 ,-1 , 0
  4424.7     .16       0  5003.7     .07       0  5009.7     .16       0
  5677.3     .05       0
Bank Sta=4969,5024.2
XS Rating Curve= 0 ,0
Exp/Cntr=0.3,0.1

Type RM Length L Ch R = 1 ,6246    ,403,403,403
BEGIN DESCRIPTION:
UNT 036 IN BUCR 11.0
END DESCRIPTION:
XS GIS Cut Line= 3
      3601049.65     10494110.21      3601399.61     10494360.19
      3602199.62     10494010.18
#Sta/Elev= 30
  4570.6  413.03  4684.8  411.15  4735.2  408.32    4750  406.07  4900.2   398.8
  4963.8  395.19  4972.4  392.17  4978.6  392.35  4987.2  383.55  4993.3  384.33
  4994.6  383.21  4997.3  382.71  5000.6  383.21  5003.4  383.21  5009.6  389.83
  5015.1  390.34  5022.5  394.37  5194.8  394.58  5251.7  394.32  5387.8  397.75
  5590.3  411.41  5655.6  416.33  5661.4  418.07  5765.9  428.73  5783.8  432.41
  5789.3  430.83  5807.2  435.33  5836.1  436.48  5853.5  438.57  5873.9  439.33
#Mann= 7 ,-1 , 0
  4570.6     .05       0  4900.2     .16       0  4994.6     .07       0
  5000.6     .16       0  5194.8     .05       0  5590.3     .16       0
  5853.5     .05       0
Bank Sta=4963.8,5022.5
XS Rating Curve= 0 ,0
Exp/Cntr=0.3,0.1

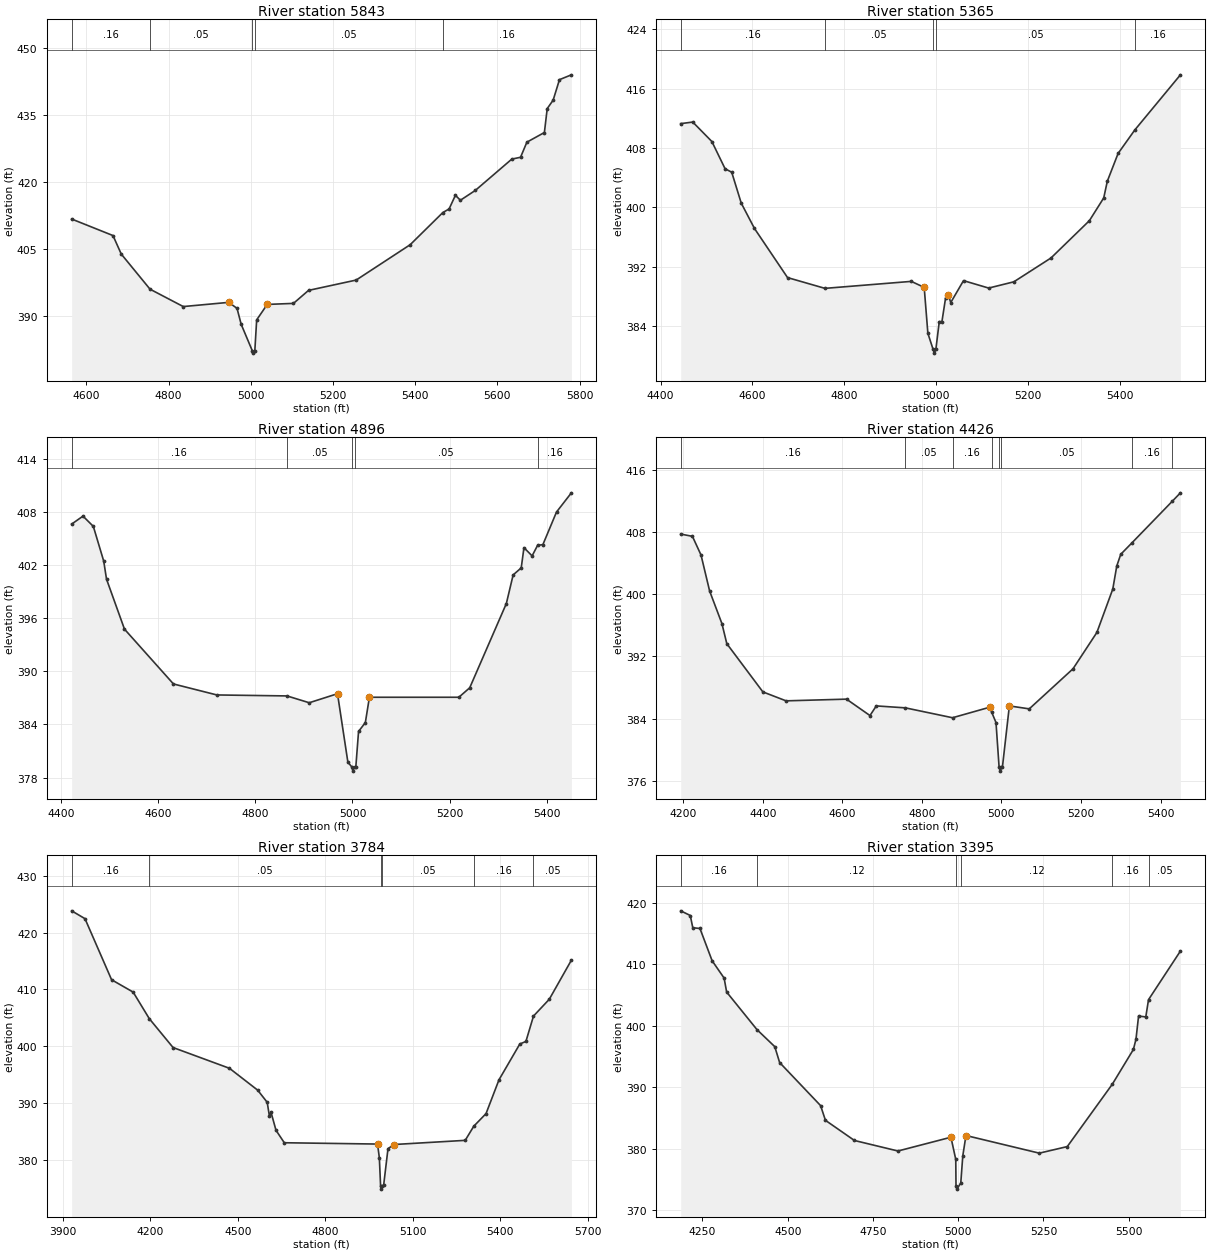
Type RM Length L Ch R = 1 ,5843    ,478,478,478
BEGIN DESCRIPTION:
UNT 036 IN BUCR 10.0
END DESCRIPTION:
XS GIS Cut Line= 3
      3601199.64     10494610.19      3601649.61     10494660.19
      3602299.65     10494260.16
#Sta/Elev= 30
  4564.1  411.67  4664.7  407.97  4684.8  403.83  4754.8  395.97  4835.7  392.08
  4946.4  393.02  4966.5  391.68  4976.6  388.11  5003.8  382.16  5006.5  381.66
  5009.8  382.16  5014.3   389.1    5040  392.56  5103.8  392.79  5140.5   395.7
  5256.4  398.01  5387.8  405.92  5467.4  413.13  5482.5  413.92  5497.9  416.99
    5510  415.87  5546.3  418.07  5635.1  425.08  5656.4  425.49  5671.8  428.87
  5714.4  431.03  5721.3  436.39  5735.7  438.27  5751.1  442.86  5780.1  443.94
#Mann= 5 ,-1 , 0
  4564.1     .16       0  4754.8     .05       0  5003.8     .03       0
  5009.8     .05       0  5467.4     .16       0
Bank Sta=4946.4,5040
XS Rating Curve= 0 ,0
Exp/Cntr=0.3,0.1

Type RM Length L Ch R = 1 ,5365    ,469,469,469
BEGIN DESCRIPTION:
UNT 036 IN BUCR 9.0
END DESCRIPTION:
XS GIS Cut Line= 3
      3601158.04      10494705.6      3601599.61     10495060.19
      3602099.58     10495210.18
#Sta/Elev= 30
  4443.8  411.29  4470.1   411.5  4511.7  408.88  4540.5  405.21  4554.9  404.75
  4575.7  400.58  4604.5  397.17  4676.5  390.56    4758  389.11    4946  390.05
  4974.1  389.24  4982.1  383.06  4993.5  380.89  4996.3  380.39  4999.5  380.89
  5006.9  384.63  5012.7  384.63  5020.6  387.79  5026.6  388.24  5031.9   387.2
  5059.7  390.15  5114.5  389.15  5169.3  389.99  5250.2   393.2  5333.8  398.22
  5365.1  401.29  5372.9  403.54  5396.4  407.28  5432.8  410.44  5532.1  417.86
#Mann= 5 ,-1 , 0
  4443.8     .16       0    4758     .05       0  4993.5     .03       0
  4999.5     .05       0  5432.8     .16       0
Bank Sta=4974.1,5026.6
XS Rating Curve= 0 ,0
Exp/Cntr=0.3,0.1

Type RM Length L Ch R = 1 ,4896    ,470,470,470
BEGIN DESCRIPTION:
UNT 036 IN BUCR 8.0
END DESCRIPTION:
XS GIS Cut Line= 3
      3601099.59     10494910.16      3601399.61     10495410.19
      3601799.57     10495610.17
#Sta/Elev= 30
    4421  406.62  4444.4  407.52  4465.7  406.36  4487.1  402.44  4492.9   400.4
  4529.9  394.76  4630.9  388.57  4720.4  387.33    4865  387.22  4910.8  386.45
  4969.1  387.47  4990.5  379.74  4998.2  379.23    5001  378.73  5004.2  379.23
  5006.9  379.23  5012.5  383.21  5026.5  384.21  5034.9  387.07  5219.3  387.07
  5241.7  388.14  5317.2  397.65  5331.2  400.88  5347.9  401.68  5353.5  403.96
  5370.3  403.03  5381.5  404.21  5392.6  404.31  5420.6  407.98  5451.3  410.15
#Mann= 5 ,-1 , 0
    4421     .16       0    4865     .05       0  4998.2     .03       0
  5004.2     .05       0  5381.5     .16       0
Bank Sta=4969.1,5034.9
XS Rating Curve= 0 ,0
Exp/Cntr=0.3,0.1

Type RM Length L Ch R = 1 ,4426    ,642,642,642
BEGIN DESCRIPTION:
UNT 036 IN BUCR 7.0
END DESCRIPTION:
XS GIS Cut Line= 3
      3600899.61     10495160.18      3601299.61     10495860.19
      3601749.58     10495860.19
#Sta/Elev= 30
  4193.8  407.71  4223.3  407.42  4244.9  405.02  4266.5   400.4  4297.5   396.2
  4309.7  393.63  4400.4  387.43  4458.7  386.28  4610.6   386.5  4669.6  384.39
  4685.5  385.63  4758.6  385.38  4877.1  384.11  4970.5  385.46  4975.2  384.87
  4986.4  383.49  4994.2  377.75  4996.9  377.25  5000.2  377.75  5002.5  377.75
    5020  385.63    5070  385.25    5180   390.4    5240  395.07    5280  400.65
    5290  403.61    5300  405.11  5328.1  406.58  5429.8  411.94    5450  413.01
#Mann= 8 ,-1 , 0
  4193.8     .16       0  4758.6     .05       0  4877.1     .16       0
  4975.2     .05       0  4994.2     .03       0  5000.2     .05       0
  5328.1     .16       0  5429.8     .05       0
Bank Sta=4970.5,5020
XS Rating Curve= 0 ,0
Exp/Cntr=0.3,0.1

Type RM Length L Ch R = 1 ,3784    ,389,389,389
BEGIN DESCRIPTION:
UNT 036 IN BUCR 6.0
END DESCRIPTION:
XS GIS Cut Line= 3
      3600033.06     10495585.82      3600741.37     10495919.14
      3601501.53     10496455.42
#Sta/Elev= 30
  3930.8  423.81  3976.5  422.43  4067.7   411.7  4141.6  409.53    4197  404.86
  4278.4  399.79  4471.8  396.14  4568.5   392.3  4601.2  390.16  4608.5   387.8
  4614.1  388.44  4631.3  385.25  4659.7  383.06  4979.4  382.83  4985.6   380.4
  4989.9  375.41  4992.7  374.91  4995.9  375.41  5000.4  375.63  5015.2  382.02
  5036.1  382.75  5279.9  383.48  5309.4  385.97  5351.3  388.18  5395.7  394.12
  5467.1  400.41    5488  400.86    5514  405.32  5568.1  408.27  5643.9  415.14
#Mann= 6 ,-1 , 0
  3930.8     .16       0    4197     .05       0  4989.9     .03       0
  4995.9     .05       0  5309.4     .16       0    5514     .05       0
Bank Sta=4979.4,5036.1
XS Rating Curve= 0 ,0
Exp/Cntr=0.3,0.1

Type RM Length L Ch R = 1 ,3395    ,749,749,749
BEGIN DESCRIPTION:
UNT 036 IN BUCR 5.0
END DESCRIPTION:
XS GIS Cut Line= 3
      3600149.57     10495760.16      3600749.61     10496310.19
       3601299.6     10496660.18
#Sta/Elev= 30
  4186.1  418.67  4214.2  417.91  4221.6  415.92  4242.6   415.8  4278.3  410.55
  4313.5  407.73  4320.9  405.46  4409.9  399.35  4462.1  396.58  4476.3     394
  4596.5  386.99  4610.7   384.6  4695.8  381.32  4823.4  379.61  4978.8  381.85
    4993  378.24  4993.7  373.91  4996.4  373.41  5007.7  374.41  5013.6  378.83
  5022.9  382.13    5238  379.26  5320.1  380.33  5452.3  390.48    5514  396.12
  5521.6  397.78  5529.2  401.55  5550.4  401.42  5558.4  404.22    5652  412.13
#Mann= 6 ,-1 , 0
  4186.1     .16       0  4409.9     .12       0  4993.7     .05       0
  5007.7     .12       0  5452.3     .16       0  5558.4     .05       0
Bank Sta=4978.8,5022.9
XS Rating Curve= 0 ,0
Exp/Cntr=0.3,0.1

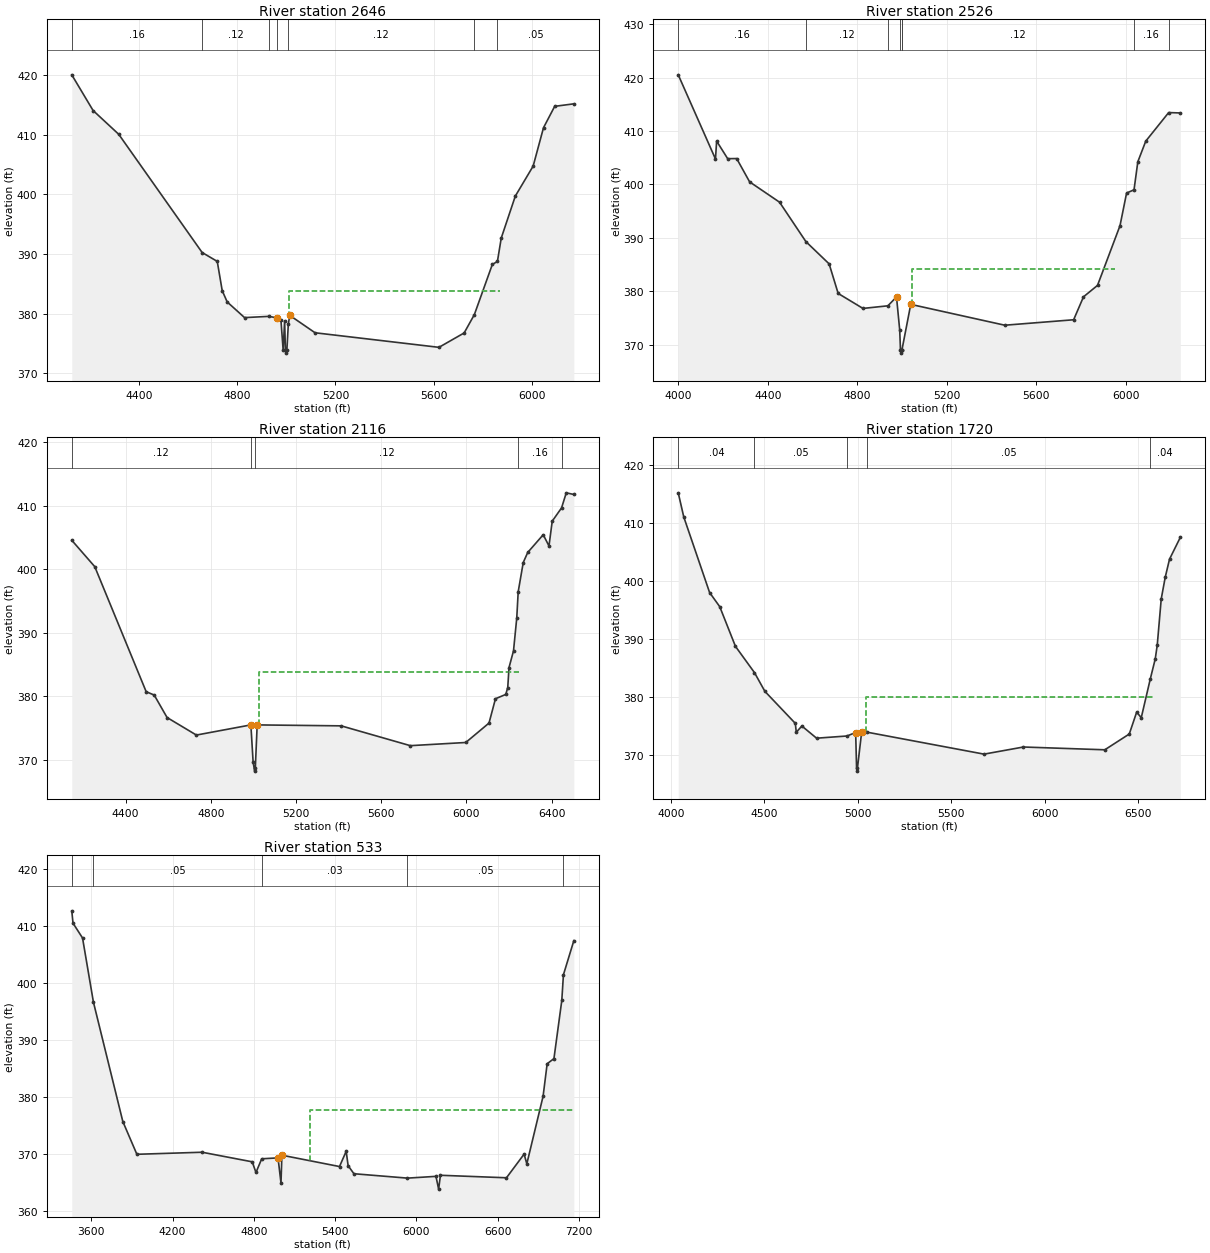
Type RM Length L Ch R = 1 ,2646    ,120,120,120
BEGIN DESCRIPTION:
UNT 036 IN BUCR 4.0
END DESCRIPTION:
XS GIS Cut Line= 4
      3599995.71     10495674.35      3600121.58     10496490.32
      3600182.34     10496581.47      3601115.03     10497184.46
#Sta/Elev= 30
  4125.7  420.02  4212.6  414.04    4317  410.06  4656.9  390.25  4718.5  388.76
  4738.7  383.86  4758.9  381.97  4829.8  379.34  4928.9  379.55  4962.8  379.29
    4978  378.94    4987   373.9    4993  378.77  4996.2  373.89    4999  373.39
  5002.2  373.89  5008.1  378.27  5014.1  379.71  5117.1   376.8  5621.8  374.36
  5724.5  376.77  5766.1  379.84  5839.4  388.25  5860.1  388.75  5875.7  392.67
  5933.1  399.71  6005.7  404.73  6047.9  411.16  6093.4  414.74  6171.5  415.16
#Mann= 7 ,-1 , 0
  4125.7     .16       0  4656.9     .12       0  4928.9     .08       0
  4962.8     .05       0  5008.1     .12       0  5766.1     .08       0
  5860.1     .05       0
#XS Ineff= 1 ,-1
 5012.78 5872.16383.7467
Permanent Ineff=
       F
Bank Sta=4962.8,5014.1
XS Rating Curve= 0 ,0
Exp/Cntr=0.3,0.1

Type RM Length L Ch R = 1 ,2526    ,410,410,410
BEGIN DESCRIPTION:
UNT 036 IN BUCR 3.0
END DESCRIPTION:
XS GIS Cut Line= 4
      3599882.86     10495630.96      3600004.39     10496559.76
      3600238.76     10496759.42      3601050.28     10497345.27
#Sta/Elev= 30
  3999.4  420.51    4166  404.76  4171.1  408.12  4220.5  404.83  4260.8  404.85
  4318.7  400.49  4452.5  396.69  4570.3  389.32  4674.3  385.15  4714.7  379.62
  4825.6  376.82  4937.1  377.31  4975.6  378.97  4989.9   372.8  4993.4  368.96
  4996.2  368.46  4999.4  368.96  4999.8  369.04  5039.3  377.58  5459.9  373.68
  5767.8   374.7  5811.9  378.99  5874.6  381.13  5975.2   392.3  6004.6   398.4
  6037.9  399.01  6054.9  404.25  6090.4  408.11  6192.8  413.45  6244.9  413.38
#Mann= 8 ,-1 , 0
  3999.4     .16       0  4570.3     .12       0  4937.1     .08       0
  4993.4     .05       0  4999.4     .08       0  4999.8     .12       0
  6037.9     .16       0  6192.8     .05       0
#XS Ineff= 1 ,-1
 5044.32 5954.55  384.18
Permanent Ineff=
       F
Bank Sta=4975.6,5039.3
XS Rating Curve= 0 ,0
Exp/Cntr=0.3,0.1

Type RM Length L Ch R = 1 ,2116    ,396,396,396
BEGIN DESCRIPTION:
UNT 036 IN BUCR 2.0
END DESCRIPTION:
XS GIS Cut Line= 3
       3599349.6     10495960.17      3599699.61     10496760.19
       3600949.6     10497560.18
#Sta/Elev= 30
  4147.6  404.55  4255.6  400.39  4496.9   380.7  4534.7  380.17  4595.1  376.63
  4732.7  373.87  4988.5  375.47    4999  369.64  5006.2  368.19  5009.4  368.69
  5018.1  375.47  5412.6  375.32  5737.1   372.2  5997.5   372.7  6106.6  375.76
  6136.9  379.59  6185.3  380.27  6194.6  381.36  6200.5   384.5  6221.6  387.13
  6236.9  392.32  6243.6  396.43  6267.3  401.04  6288.4  402.63  6361.1  405.42
  6388.2  403.65  6403.4  407.56  6447.3  409.65  6469.3  412.02  6504.9  411.76
#Mann= 5 ,-1 , 0
  4147.6     .12       0  4988.5     .05       0  5009.4     .12       0
  6243.6     .16       0  6447.3     .05       0
#XS Ineff= 1 ,-1
 5024.43 6246.59383.7289
Permanent Ineff=
       F
Bank Sta=4988.5,5018.1
XS Rating Curve= 0 ,0
Exp/Cntr=0.3,0.1

Type RM Length L Ch R = 1 ,1720    ,1187,1187,1187
BEGIN DESCRIPTION:
Mapping XS 0d8c5fd6
END DESCRIPTION:
XS GIS Cut Line= 3
      3598984.44     10495926.12      3599440.15     10497089.28
       3600785.1     10497596.89
#Sta/Elev= 30
  4038.8   415.2  4068.4  411.04  4206.7     398    4261  395.56    4345  388.72
  4446.8  384.19  4502.5  380.96  4665.2  375.44  4670.6  373.91  4700.4  374.98
  4779.1  372.88  4941.9  373.26  4988.3  373.86  4993.2   367.7  4995.9   367.2
  5020.5  373.97  5050.5  373.91  5675.3  370.13    5886  371.36  6321.6  370.88
  6452.5   373.6  6492.1  377.38  6516.6  376.41  6564.9  383.09  6591.5  386.56
  6602.2  388.94  6623.5   396.9  6644.9  400.64  6667.9  403.76  6725.6  407.52
#Mann= 5 ,-1 , 0
  4038.8     .04       0  4446.8     .05       0  4941.9     .03       0
  5050.5     .05       0  6564.9     .04       0
#XS Ineff= 1 ,-1
 5043.18 6577.27380.0523
Permanent Ineff=
       F
Bank Sta=4988.3,5020.5
XS Rating Curve= 0 ,0
Exp/Cntr=0.3,0.1

Type RM Length L Ch R = 1 ,533     ,0,0,0
BEGIN DESCRIPTION:
UNT 036 IN BUCR 1.0
END DESCRIPTION:
XS GIS Cut Line= 4
      3598763.07     10496090.98      3598867.24     10497336.67
      3599658.24     10498249.75      3600906.41     10498180.41
#Sta/Elev= 30
  3455.3   412.6  3464.5  410.43  3534.8  407.84  3615.1   396.6  3832.3  375.65
  3936.2   369.9  4417.9  370.26  4787.9  368.58  4815.8  366.71  4858.1  369.11
  4978.7  369.27  5000.6  364.87  5007.2  369.74  5432.7  367.75  5482.1  370.43
  5496.4   367.9  5539.1  366.49  5934.8  365.72  6145.1  366.03  6164.9  363.79
  6178.1  366.22  6665.9  365.78  6796.1  369.93  6816.2  368.23  6936.3  380.07
  6966.4  385.78  7016.5  386.68  7074.5  396.88  7086.6  401.39  7163.5  407.37
#Mann= 5 ,-1 , 0
  3455.3     .16       0  3615.1     .05       0  4858.1     .03       0
  5934.8     .05       0  7086.6     .16       0
#XS Ineff= 1 ,-1
 5216.76 7287.78377.7199
Permanent Ineff=
       F
Bank Sta=4978.7,5007.2
XS Rating Curve= 0 ,0
Exp/Cntr=0.3,0.1

Chan Stop Cuts=-1
Use User Specified Reach Order=0
Composite Channel Slope=5