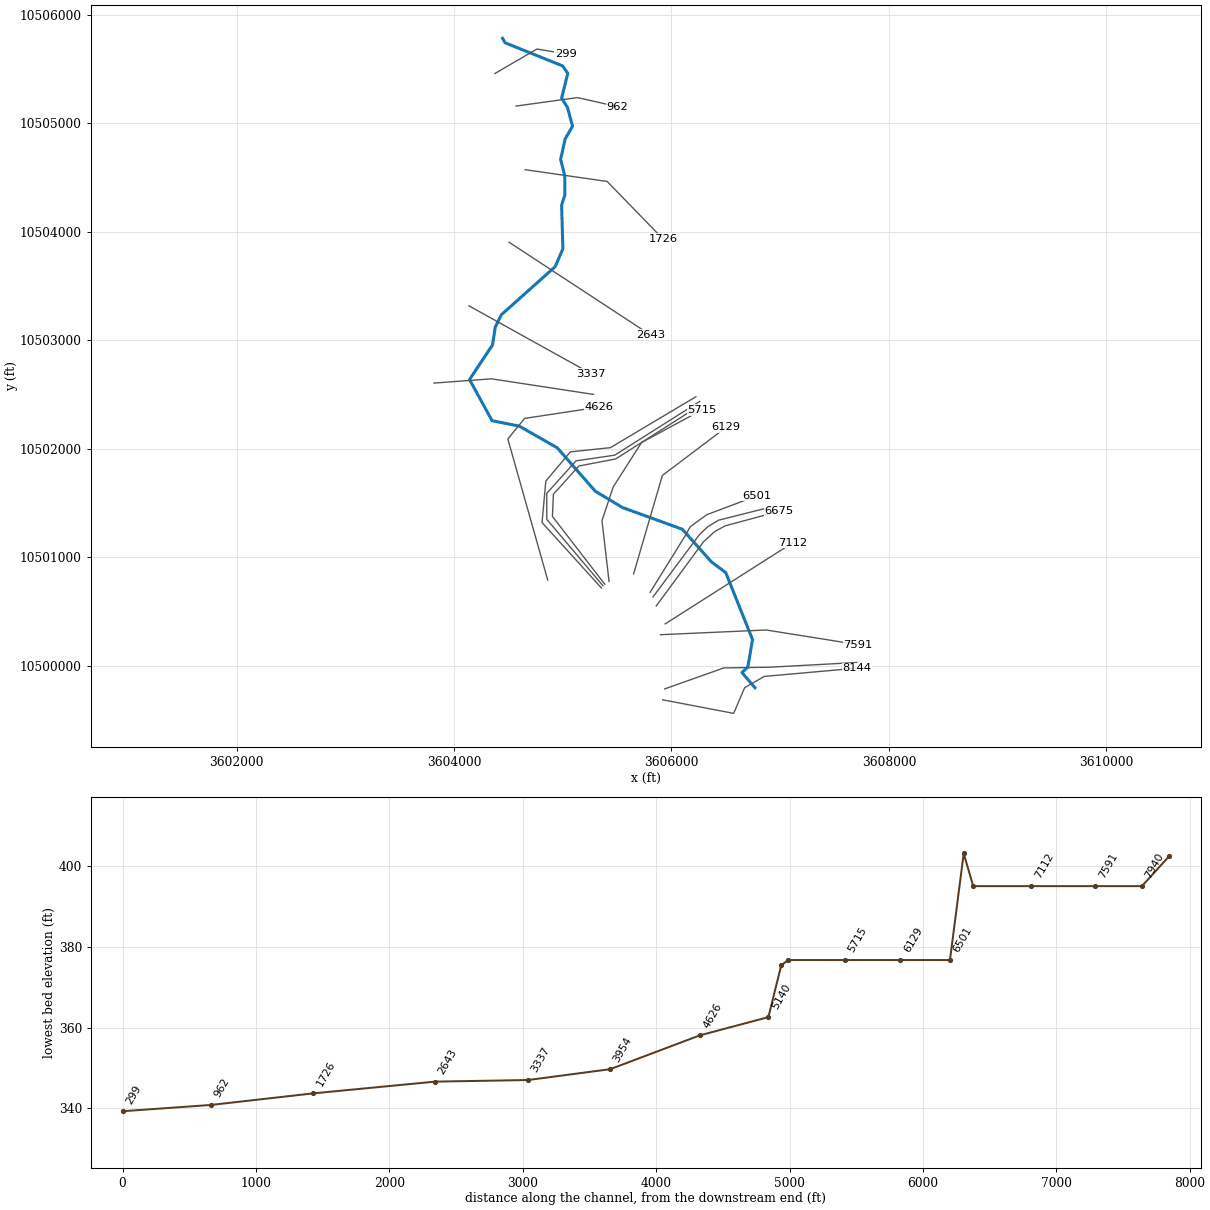
--- UNT 038 IN BUCR.prj (project) ---

Proj Title=UNT 038 IN BUCR Base Level Engineering
Current Plan=p01
Default Exp/Contr=0.3,0.1
English Units
Geom File=g01
Flow File=f01
Plan File=p01
Y Axis Title=Elevation
X Axis Title(PF)=Main Channel Distance
X Axis Title(XS)=Station
BEGIN DESCRIPTION:
UNT 038 IN BUCR
END DESCRIPTION:
DSS Export Rating Curves= 0
DSS Export Rating Curve Sorted= 0
DSS Export Volume Flow Curves= 0
DXF OffsetX= 0
DXF OffsetY= 0
DXF ScaleX= 1
DXF ScaleY= 10

--- UNT 038 IN BUCR.p01 (plan) ---

Plan Title=Multiple Run
Short Identifier=Multiple
Geom File=g01
Flow File=f01
Subcritical Flow
K Sum by GR= 0
Std Step Tol= 0.01
Critical Tol= 0.01
Num of Std Step Trials= 20
Max Error Tol= 0.3
Flow Tol Ratio= 0.001
Split Flow NTrial= 30
Split Flow Tol= 0.02
Split Flow Ratio= 0.02
Log Output Level= 0
Friction Slope Method= 1
Unsteady Friction Slope Method= 2
Unsteady Bridges Friction Slope Method= 1
Parabolic Critical Depth
Global Vel Dist=  1 , 1 , 1
Global Log Level= 0
CheckData=True
Encroach Param= -1, 0, 0, 0
BEGIN DESCRIPTION:
Multiple Run
END DESCRIPTION:

--- UNT 038 IN BUCR.f01 (steady flow) ---

Flow Title=Multiple
Program Version=4.10
Number of Profiles= 7
Profile Names=10-year,25-year,50-year,1pct_min,100-year,1pct_plu,500-year
River Rch & RM=UNT 038 IN BUCR,Reach-1         ,8144
    1024    1416    1742    1564    2116    2861    3112
Boundary for River Rch & Prof#=UNT 038 IN BUCR,Reach-1         , 1
Up Type= 0
Dn Type= 3
Dn Slope=0.005
Boundary for River Rch & Prof#=UNT 038 IN BUCR,Reach-1         , 2
Up Type= 0
Dn Type= 3
Dn Slope=0.005
Boundary for River Rch & Prof#=UNT 038 IN BUCR,Reach-1         , 3
Up Type= 0
Dn Type= 3
Dn Slope=0.005
Boundary for River Rch & Prof#=UNT 038 IN BUCR,Reach-1         , 4
Up Type= 0
Dn Type= 3
Dn Slope=0.005
Boundary for River Rch & Prof#=UNT 038 IN BUCR,Reach-1         , 5
Up Type= 0
Dn Type= 3
Dn Slope=0.005
Boundary for River Rch & Prof#=UNT 038 IN BUCR,Reach-1         , 6
Up Type= 0
Dn Type= 3
Dn Slope=0.005
Boundary for River Rch & Prof#=UNT 038 IN BUCR,Reach-1         , 7
Up Type= 0
Dn Type= 3
Dn Slope=0.005
DSS Import GetInterval= 0
DSS Import GetPeak= 0
DSS Import FillOption= 0

--- UNT 038 IN BUCR.g01 (geometry) ---

Geom Title=Existing Conditions
Program Version=4.10

River Reach=UNT 038 IN BUCR ,Reach-1
Reach XY= 30
      3606767.94     10499800.14      3606647.75       10499940.
        3606702.       10499990.       3606745.5       10500244.
      3606499.61     10500860.19      3606366.66     10500960.53
      3606099.61     10501260.19      3605549.61     10501460.19
      3605299.61     10501610.19      3604949.61     10502010.19
      3604599.61     10502210.19      3604349.61     10502260.19
      3604142.75       10502639.      3604354.25       10502958.
      3604379.25       10503121.       3604435.5       10503236.
      3604929.75       10503678.       3605001.5       10503843.
       3604989.5       10504245.       3605019.5       10504339.
      3605018.25       10504517.       3604980.5       10504667.
        3605022.       10504855.        3605090.       10504973.
      3605043.25       10505147.       3604989.5       10505230.
       3605046.5       10505459.        3604999.       10505528.
      3604469.75       10505741.      3604446.75       10505782.

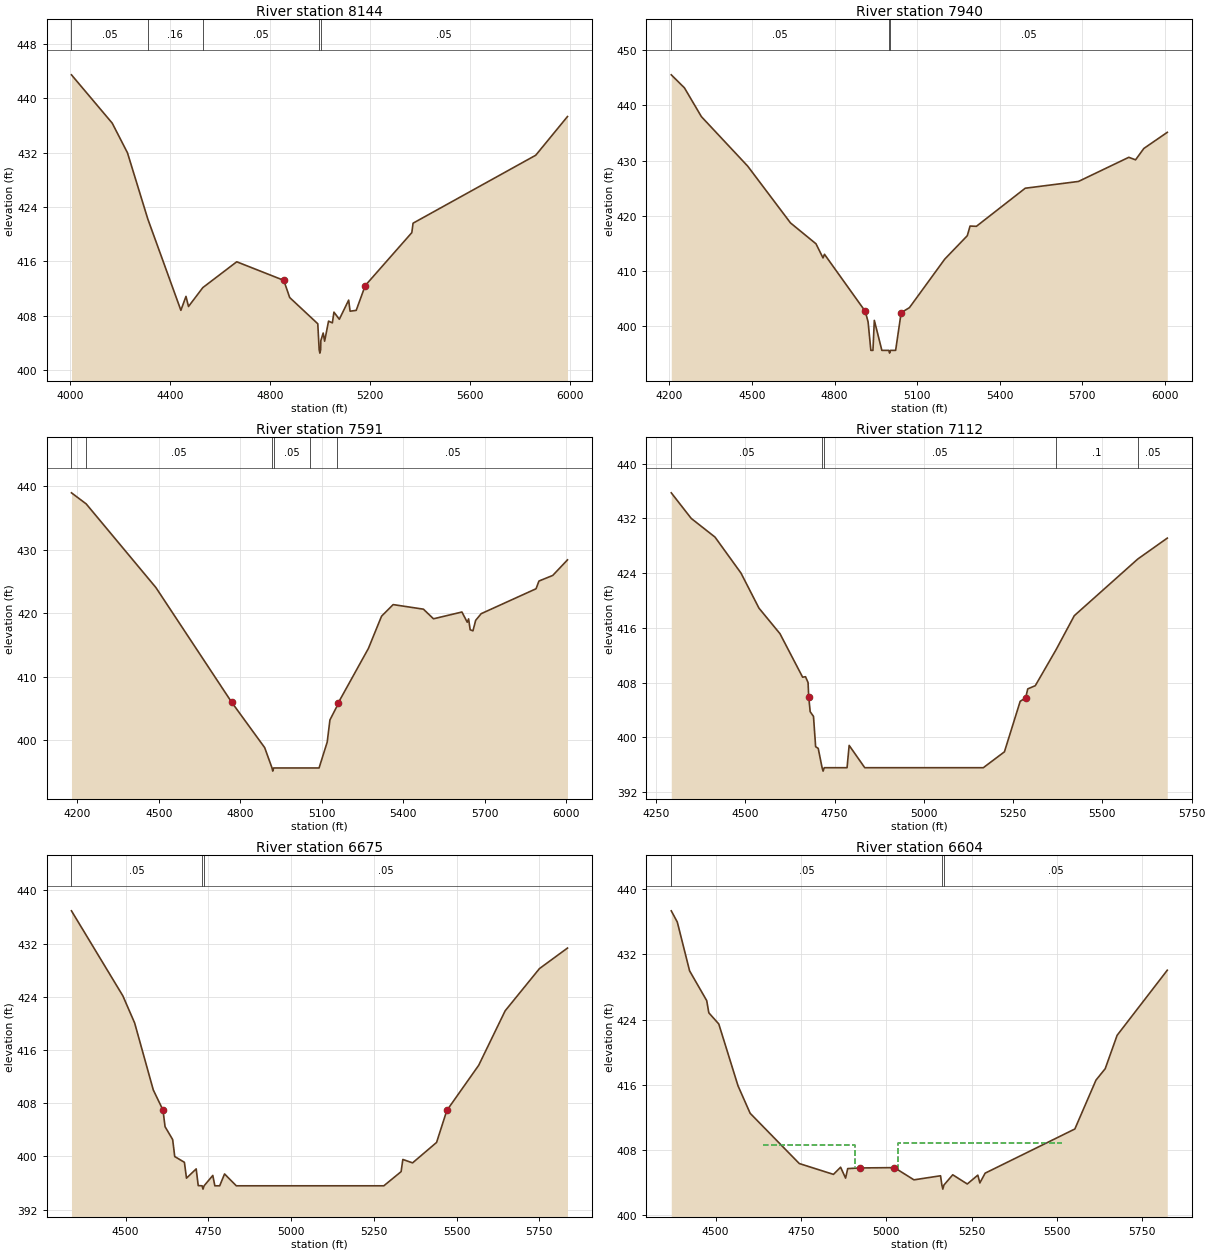
Type RM Length L Ch R = 1 ,8144    ,204,204,204
BEGIN DESCRIPTION:
UNT 038 IN BUCR 2.0
END DESCRIPTION:
XS GIS Cut Line= 5
      3605919.34      10499689.1      3606572.13      10499564.1
      3606672.82     10499800.21      3606853.38     10499904.38
      3607706.09     10499980.63
#Sta/Elev= 30
  4005.3  443.44  4168.5  436.33  4229.6  431.96    4311  422.22  4443.4  408.79
  4463.8  410.84  4473.9  409.35  4531.2  412.13    4667  415.93  4855.3   413.2
    4879  410.67  4991.5  406.81    4997  402.99  4999.8  402.49    5003  402.99
  5003.7  404.32  5013.1  405.45  5018.9  404.25  5034.6   407.2  5049.9  406.94
  5056.2  408.52  5077.7  407.47  5115.1  410.29  5120.8  408.66  5145.3  408.78
  5181.5  412.43    5368  420.22    5373  421.61  5864.2  431.61  5991.2   437.3
#Mann= 5 ,-1 , 0
  4005.3     .05       0    4311     .16       0  4531.2     .05       0
    4997     .03       0    5003     .05       0
Bank Sta=4855.3,5181.5
XS Rating Curve= 0 ,0
Exp/Cntr=0.3,0.1

Type RM Length L Ch R = 1 ,7940    ,349,349,349
BEGIN DESCRIPTION:
Mapping XS c4d3c62e
END DESCRIPTION:
XS GIS Cut Line= 4
      3605938.18     10499789.66      3606481.24      10499982.7
      3606901.69      10499989.3      3607704.67      10500032.7
#Sta/Elev= 30
  4207.1  445.55  4254.9  443.19  4316.6  437.96  4484.6  428.99    4640  418.69
  4732.6   414.9  4758.1  412.34  4763.4     413  4911.8  402.63  4921.8  400.72
  4931.8  395.57  4939.4  395.57  4944.4  401.01  4971.8  395.57    4997  395.57
  4999.8  395.07    5003  395.57  5021.8  395.57  5041.8  402.41  5071.9  403.32
  5200.4  412.14    5282  416.37    5292  418.12    5315  418.07  5492.3  424.98
  5685.6  426.21  5868.4  430.59  5892.9  430.13  5922.9  432.19  6008.1  435.12
#Mann= 3 ,-1 , 0
  4207.1     .05       0    4997     .03       0    5003     .05       0
Bank Sta=4911.8,5041.8
XS Rating Curve= 0 ,0
Exp/Cntr=0.3,0.1

Type RM Length L Ch R = 1 ,7591    ,479,479,479
BEGIN DESCRIPTION:
UNT 038 IN BUCR 1.9
END DESCRIPTION:
XS GIS Cut Line= 3
      3605899.12     10500288.78      3606871.31     10500332.18
      3607713.27     10500197.64
#Sta/Elev= 30
  4178.7  438.99    4233  437.24  4489.5  424.04  4767.8  405.98  4889.9  398.78
  4916.9  395.57  4919.7  395.07  4922.9  395.57  5058.3  395.57  5090.1  395.57
  5120.1  399.66  5130.1  403.15  5157.2  405.41  5160.3  405.81  5271.7  414.43
  5320.1  419.52  5362.8  421.35  5474.2  420.63  5511.3  419.11    5616  420.18
  5635.5  418.57  5640.5   419.1  5646.3  417.38  5656.5  417.21  5666.6  418.87
  5686.9  419.92  5888.8  423.85  5899.5  425.07  5950.2  425.95  6004.5  428.41
#Mann= 6 ,-1 , 0
  4178.7      .1       0    4233     .05       0  4916.9    .033       0
  4922.9     .05       0  5058.3     .16       0  5157.2     .05       0
Bank Sta=4767.8,5160.3
XS Rating Curve= 0 ,0
Exp/Cntr=0.3,0.1

Type RM Length L Ch R = 1 ,7112    ,437,437,437
BEGIN DESCRIPTION:
UNT 038 IN BUCR 1.8
END DESCRIPTION:
XS GIS Cut Line= 2
       3605942.5     10500388.62      3607114.33     10501135.11
#Sta/Elev= 30
  4292.3  435.75  4348.2  432.01  4414.8  429.28  4487.6  424.02  4537.9   418.9
  4596.8  415.16  4660.3   408.8  4668.3  408.87  4675.5  408.02 4677.27  405.96
  4681.4  403.76  4690.7  403.07  4696.7  398.64  4703.9   398.4  4714.8  395.57
  4717.6  395.07  4720.8  395.57  4784.7  395.57  4790.6  398.83  4834.3  395.57
  5166.4  395.57  5225.5  397.89  5269.7  405.28  5284.8  405.77  5290.9  407.09
    5312  407.56  5370.3  412.83  5421.2  417.79    5599  426.07  5681.7  429.13
#Mann= 5 ,-1 , 0
  4292.3     .05       0  4714.8    .033       0  4720.8     .05       0
  5370.3      .1       0    5599     .05       0
Bank Sta=4677.27,5284.8
XS Rating Curve= 0 ,0
Exp/Cntr=0.3,0.1

Type RM Length L Ch R = 1 ,6675    ,71,71,71
BEGIN DESCRIPTION:
UNT 038 IN BUCR 1.7
END DESCRIPTION:
XS GIS Cut Line= 5
      3605860.04     10500553.56      3606294.05     10501143.81
      3606398.22      10501239.3       3606493.7     10501291.38
      3606991.42     10501425.55
#Sta/Elev= 30
  4336.6  436.92  4491.9  424.13  4527.4  420.06  4583.8  409.98    4613  406.96
  4619.3  404.46  4642.3  402.52  4648.5  399.97  4677.8   399.1    4684  396.72
  4713.3  398.11  4719.5   395.6  4731.2  395.57  4733.9  395.07  4737.2  395.57
  4763.5  397.13  4769.7  395.57  4784.3  395.57    4799  397.35  4834.5  395.57
  5280.1  395.57  5332.3   397.7  5337.5  399.53  5366.9  399.02  5439.4  402.09
  5470.4   406.9  5566.6  413.69  5646.5  421.88  5750.1  428.23  5834.8  431.32
#Mann= 3 ,-1 , 0
  4336.6     .05       0  4731.2     .03       0  4737.2     .05       0
Bank Sta=4613,5470.4
XS Rating Curve= 0 ,0
Exp/Cntr=0.3,0.1

Type RM Length L Ch R = 1 ,6604    ,103,103,103
BEGIN DESCRIPTION:
Mapping XS 643d3aa0
END DESCRIPTION:
XS GIS Cut Line= 5
      3605829.62     10500635.97      3606259.33     10501213.26
      3606333.11      10501282.7      3606432.94     10501343.47
      3606932.06     10501469.33
#Sta/Elev= 30
  4370.2  437.34  4387.9  435.96  4423.9  429.97    4474  426.32  4480.2  424.82
  4509.4  423.45  4565.7  415.86  4601.2  412.49  4745.1  406.32  4845.2  404.99
  4866.1  405.87  4880.7  404.53  4886.9   405.7    4924  405.78  5023.7  405.82
  5080.9  404.32  5158.8  404.82  5162.7  403.68  5165.5  403.18  5168.7  403.68
  5194.5  404.94  5237.1  403.81    5268   404.9  5273.9  403.94  5289.4  405.14
  5552.1  410.56    5614  416.56    5641  417.96  5675.9  422.06  5822.8  430.05
#Mann= 3 ,-1 , 0
  4370.2     .05       0  5162.7     .03       0  5168.7     .05       0
#XS Ineff= 2 ,-1
 4637.73 4908.75  408.61 5034.55 5515.23  408.86
Permanent Ineff=
       F       F
Bank Sta=4924,5023.7
XS Rating Curve= 0 ,0
Exp/Cntr=0.3,0.1

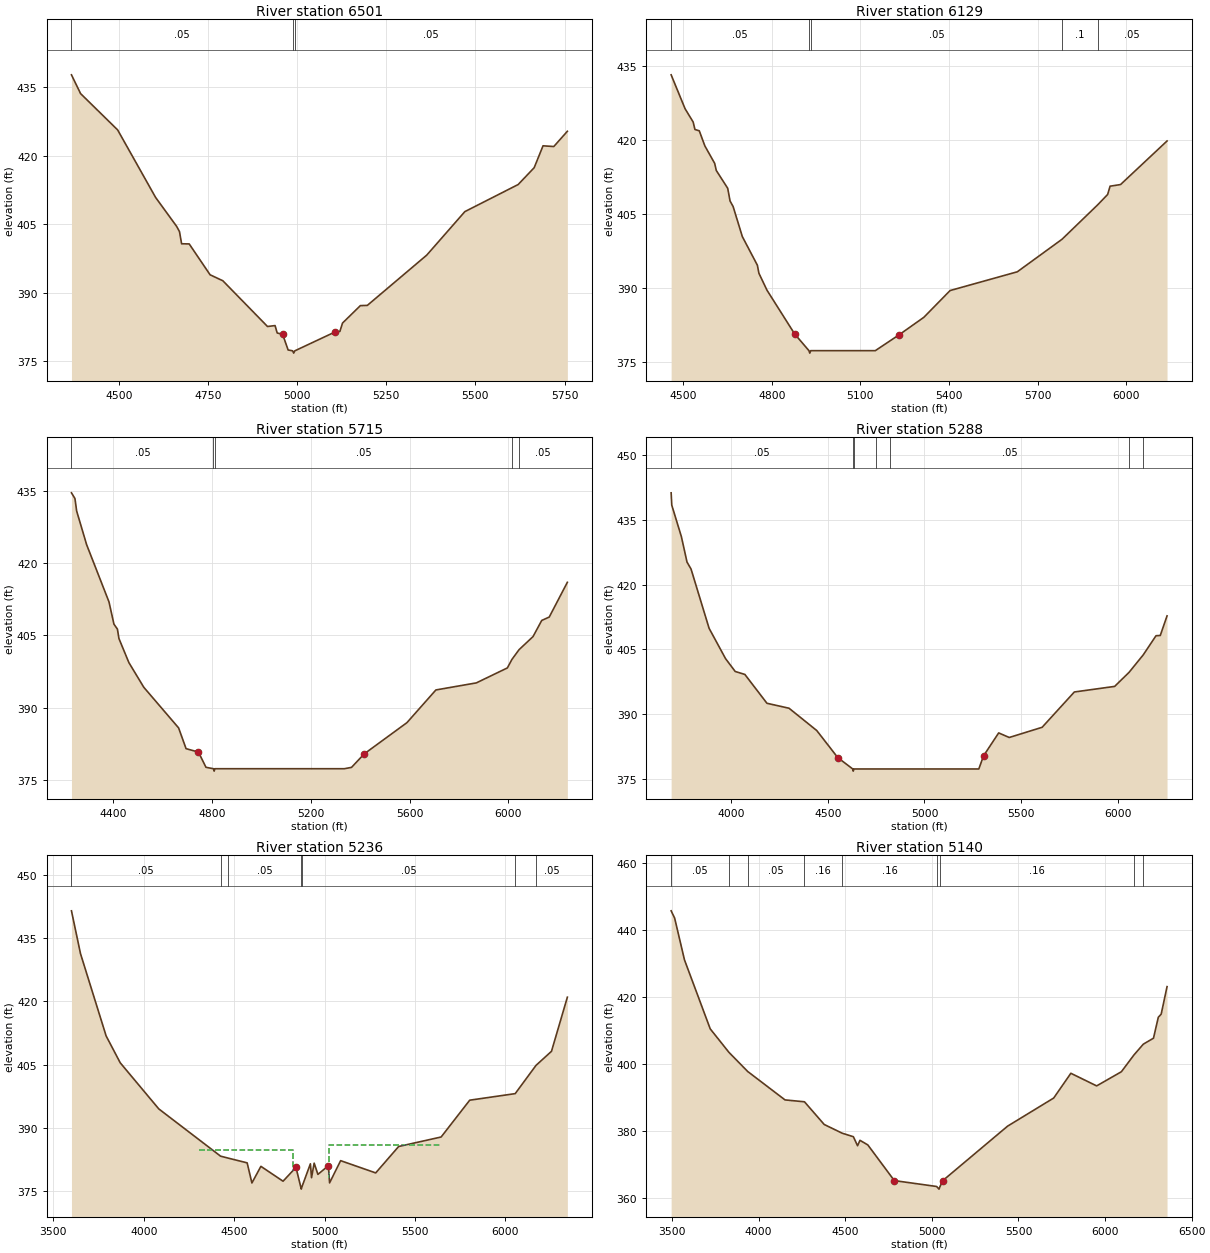
Type RM Length L Ch R = 1 ,6501    ,372,372,372
BEGIN DESCRIPTION:
Mapping XS 34a03d41
END DESCRIPTION:
XS GIS Cut Line= 6
      3605803.61     10500679.43      3606129.12     10501204.58
      3606172.52      10501282.7      3606272.35     10501356.49
      3606328.77     10501395.55      3606788.83     10501569.15
#Sta/Elev= 30
  4366.3  437.69  4391.9  433.58  4495.9  425.63  4602.5  410.84  4661.3  404.53
  4669.5  403.36  4675.4   400.7  4696.7  400.67  4755.4  393.91  4791.2   392.6
  4916.5  382.59  4937.7  382.79  4943.7  381.17    4959  380.88  4974.3  377.45
  4987.1  377.26  4989.9  376.76  4993.1  377.26  5106.2   381.4  5119.6  381.51
    5127  383.34  5177.1  387.16  5196.6  387.21  5363.4  398.22  5470.3  407.74
  5619.9  413.67  5664.9  417.36  5689.7  422.15  5719.9  421.99    5758  425.33
#Mann= 3 ,-1 , 0
  4366.3     .05       0  4987.1     .03       0  4993.1     .05       0
Bank Sta=4959,5106.2
XS Rating Curve= 0 ,0
Exp/Cntr=0.3,0.1

Type RM Length L Ch R = 1 ,6129    ,414,414,414
BEGIN DESCRIPTION:
Mapping XS cb382032
END DESCRIPTION:
XS GIS Cut Line= 3
       3605651.7     10500848.72      3605916.45     10501755.79
      3606502.39      10502198.5
#Sta/Elev= 30
  4459.1  433.29  4506.3   426.4  4533.6  423.71  4539.8  422.18  4554.4  421.92
  4573.3  418.85  4606.5  415.31    4612  413.86  4650.6  410.25  4658.6  407.67
    4669  406.53  4700.2  400.43  4751.1  394.62  4756.3  392.99  4783.6  389.55
  4877.3  380.66  4925.8  377.26  4928.6  376.76  4931.8  377.26  5150.5  377.26
  5231.5   380.5  5314.8  384.03  5403.7  389.47  5631.3  393.28  5782.8  399.89
  5903.1  406.86  5937.2  408.98  5945.5  410.67  5980.9     411  6138.4  419.85
#Mann= 5 ,-1 , 0
  4459.1     .05       0  4925.8    .033       0  4931.8     .05       0
  5782.8      .1       0  5903.1     .05       0
Bank Sta=4877.3,5231.5
XS Rating Curve= 0 ,0
Exp/Cntr=0.3,0.1

Type RM Length L Ch R = 1 ,5715    ,427,427,427
BEGIN DESCRIPTION:
Mapping XS 43c6a577
END DESCRIPTION:
XS GIS Cut Line= 5
        3605426.      10500779.2      3605360.89     10501339.13
      3605465.06     10501651.63      3605725.47     10502059.61
      3606280.99     10502359.07
#Sta/Elev= 30
  4230.5   434.7  4244.6  433.51  4251.6   430.9  4291.9  423.91  4382.5  411.99
  4402.6  407.35  4416.7  406.32  4422.8  404.36    4463  399.36  4523.4  394.22
  4664.4  385.76  4694.6  381.44  4744.9  380.72  4775.1  377.56  4805.5  377.26
  4808.3  376.76  4811.5  377.26  5335.4  377.26  5364.7  377.54  5416.3  380.36
    5589  386.85  5706.3  393.66  5870.1  395.13  5995.8  398.25    6014     400
    6043  402.04  6099.6  404.77  6134.9  408.13  6165.3  408.84  6238.7  416.07
#Mann= 5 ,-1 , 0
  4230.5     .05       0  4805.5    .033       0  4811.5     .05       0
    6014      .1       0    6043     .05       0
Bank Sta=4744.9,5416.3
XS Rating Curve= 0 ,0
Exp/Cntr=0.3,0.1

Type RM Length L Ch R = 1 ,5288    ,52,52,52
BEGIN DESCRIPTION:
Mapping XS 44e3396f
END DESCRIPTION:
XS GIS Cut Line= 6
      3605386.93     10500753.19      3604905.16     10501378.19
      3604913.84     10501582.18      3605148.22      10501842.6
      3605486.76      10501907.7       3606215.3     10502371.78
#Sta/Elev= 30
  3690.9  441.28  3694.1  438.43  3743.9  431.11  3772.9  425.23  3793.7  423.62
    3887  409.87  3972.2  402.83    4022  399.86  4071.8  399.18    4186  392.49
  4300.1  391.34  4443.3  386.17  4552.1  379.89  4629.2  377.26  4631.9  376.76
  4635.2  377.26  4748.6  377.26  4824.3  377.26  5280.7  377.26  5305.2  380.31
  5383.3  385.62  5437.9  384.56  5607.8  386.92  5774.3  395.11  5982.5   396.4
    6057  399.66  6130.4  403.72  6196.3  408.15  6218.3  408.21  6253.3  412.75
#Mann= 7 ,-1 , 0
  3690.9     .05       0  4629.2     .03       0  4635.2     .05       0
  4748.6      .1       0  4824.3     .05       0    6057      .1       0
  6130.4     .05       0
Bank Sta=4552.1,5305.2
XS Rating Curve= 0 ,0
Exp/Cntr=0.3,0.1

Type RM Length L Ch R = 1 ,5236    ,96,96,96
BEGIN DESCRIPTION:
Mapping XS 8f249856
END DESCRIPTION:
XS GIS Cut Line= 6
      3605369.54      10500740.2      3604853.08     10501352.15
      3604853.08     10501590.86      3605122.18     10501890.34
      3605478.08     10501942.42       3606259.3      10502437.2
#Sta/Elev= 30
  3600.4  441.52  3650.4  431.35  3792.1  411.81  3870.1  405.43  4083.3  394.48
  4424.9  383.26  4468.2  382.78  4571.8  381.67  4598.1  376.89  4647.8  380.84
  4770.3  377.31  4841.7  380.59  4868.3  375.93    4871  375.43  4874.3  375.93
  4921.5  381.44  4927.8  378.14  4942.3   381.6  4963.1  378.93  5021.2     381
  5027.5  376.91  5088.7  382.19  5282.6  379.28  5409.4  385.55  5644.4  387.81
  5802.4  396.55  6053.9  398.11  6168.8  404.81  6254.5  408.16  6342.3  421.01
#Mann= 7 ,-1 , 0
  3600.4     .05       0  4424.9     .16       0  4468.2     .05       0
  4868.3     .03       0  4874.3     .05       0  6053.9      .1       0
  6168.8     .05       0
#XS Ineff= 2 ,-1
 4306.25 4822.73384.8185 5025.57 5644.32385.9239
Permanent Ineff=
       F       F
Bank Sta=4841.7,5021.2
XS Rating Curve= 0 ,0
Exp/Cntr=0.3,0.1

Type RM Length L Ch R = 1 ,5140    ,514,514,514
BEGIN DESCRIPTION:
Mapping XS 48b34203
END DESCRIPTION:
XS GIS Cut Line= 6
      3605356.56     10500718.46      3604809.68     10501321.76
       3604844.4     10501703.71      3605070.09     10501972.81
      3605439.02     10502011.87      3606224.57      10502480.6
#Sta/Elev= 30
  3495.1  445.75  3515.3  443.58  3572.1   431.1  3720.7  410.49    3829  403.46
  3937.2  397.75  4152.6  389.26  4264.8   388.7  4378.8  381.92  4482.9  379.31
  4547.1  378.27  4571.3  375.57  4585.3  377.19  4630.6  375.81  4783.5  365.16
  5027.6   363.4  5041.7  362.61    5045  363.11  5062.7  365.13  5437.5  381.43
  5703.5  389.82  5802.6  397.22  5951.5  393.45  6094.3  397.68  6167.4  402.73
  6221.2  405.93  6279.6   407.7  6307.5  413.96  6324.1  414.89  6357.9   423.1
#Mann= 9 ,-1 , 0
  3495.1     .05       0    3829     .16       0  3937.2     .05       0
  4264.8     .16       0  4482.9     .16       0  5027.6     .07       0
    5045     .16       0  6167.4      .1       0  6221.2     .05       0
Bank Sta=4783.5,5062.7
XS Rating Curve= 0 ,0
Exp/Cntr=0.3,0.1

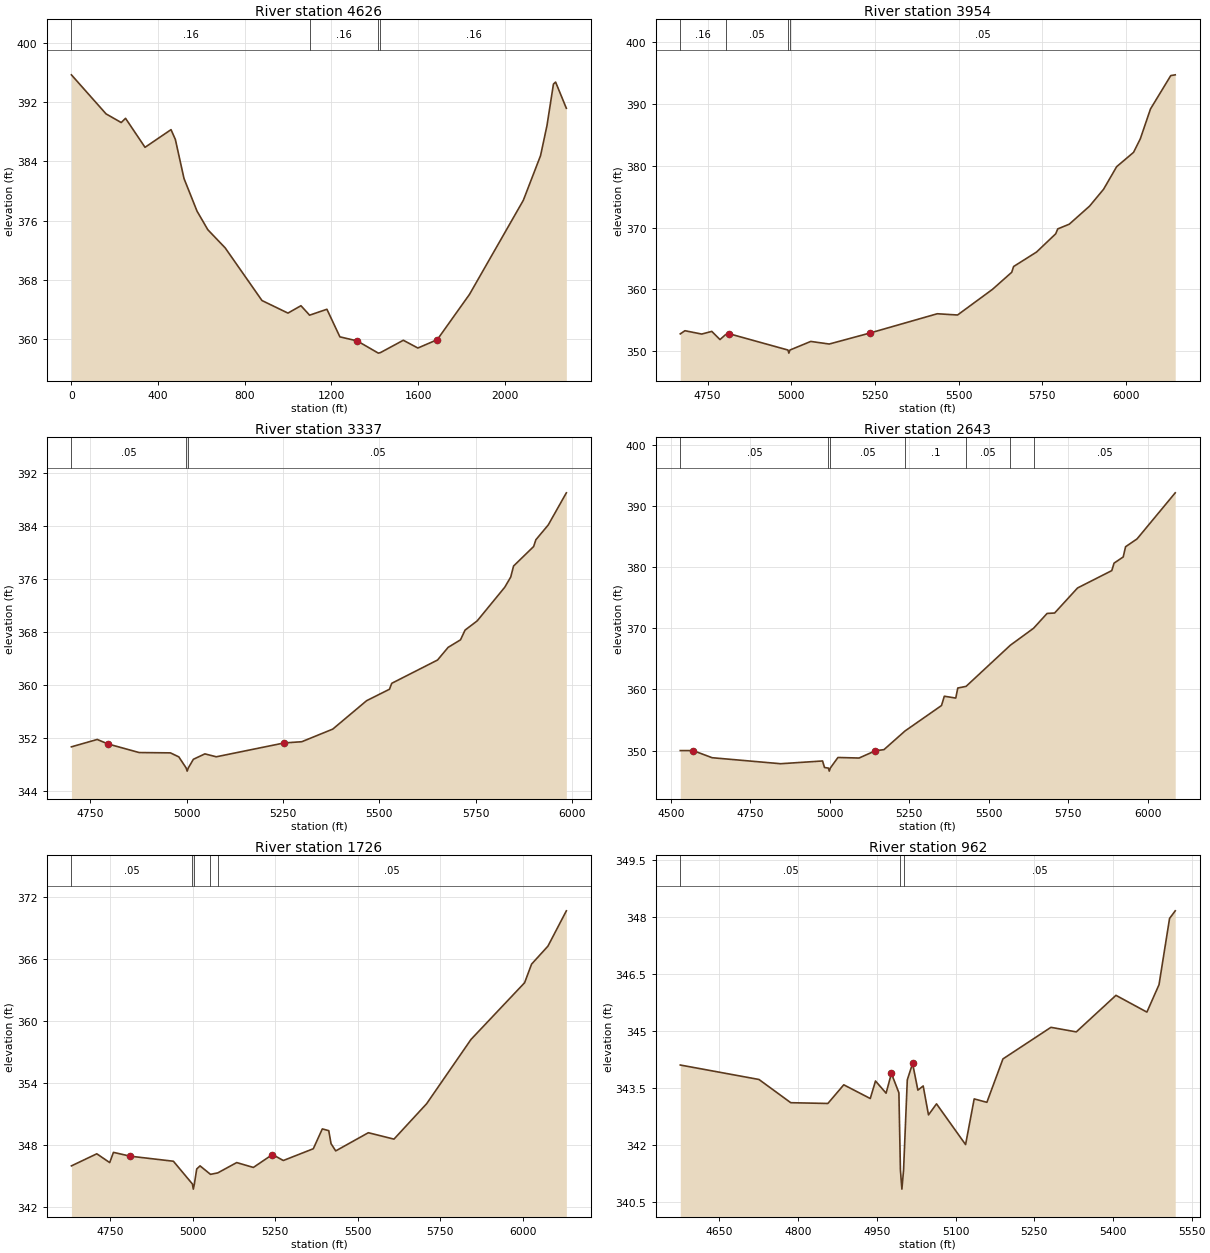
Type RM Length L Ch R = 1 ,4626    ,672,672,672
BEGIN DESCRIPTION:
Mapping XS 252501e5
END DESCRIPTION:
XS GIS Cut Line= 4
     3604861.759    10500792.251     3604495.178    10502091.119
     3604649.085    10502280.966     3605334.849    10502385.132
#Sta/Elev= 30
       0  395.71  159.87  390.43  229.82  389.26   249.8  389.83  339.73  385.91
  459.64   388.3  479.62  386.98  519.59  381.69  579.54  377.29   629.5  374.77
  709.44  372.32   879.3   365.2  999.21   363.5 1059.15   364.5 1099.09  363.22
 1178.96  364.02 1238.86  360.29 1318.73  359.74 1416.29  358.09  1425.9  358.16
 1531.54  359.83 1598.76  358.78 1688.12  359.91 1837.04  366.04 2085.25  378.75
 2164.67  384.78 2194.46  388.86 2224.24  394.46 2234.17  394.73 2283.81  391.19
#Mann= 4 ,-1 , 0
       0     .16       0 1099.09     .16       0 1416.29     .07       0
  1425.9     .16       0
Bank Sta=1318.73,1688.12
XS Rating Curve= 0 ,0
Exp/Cntr=0.3,0.1

Type RM Length L Ch R = 1 ,3954    ,617,617,617
BEGIN DESCRIPTION:
Mapping XS 399576f2
END DESCRIPTION:
XS GIS Cut Line= 3
      3603815.74     10502606.49      3604345.27     10502645.55
      3605282.72     10502502.33
#Sta/Elev= 30
  4668.3  352.82  4682.2  353.33  4732.3  352.79  4762.4  353.22    4787   351.9
  4803.5  352.69  4812.6  352.87  4990.1  350.21  4992.8  349.71  4996.1  350.21
  5058.3   351.6  5113.4  351.18    5234  352.94  5436.3  356.07    5497  355.87
  5601.1     360  5658.9  362.77  5664.5   363.7  5733.1  366.04  5790.4  368.99
  5796.5  369.78  5830.9  370.54  5891.6  373.46  5933.5  376.19  5972.5  379.83
  6023.1  382.15  6043.3  384.34  6073.6  389.15  6134.3  394.55  6147.6  394.67
#Mann= 4 ,-1 , 0
  4668.3     .16       0  4803.5     .05       0  4990.1     .03       0
  4996.1     .05       0
Bank Sta=4812.6,5234
XS Rating Curve= 0 ,0
Exp/Cntr=0.3,0.1

Type RM Length L Ch R = 1 ,3337    ,694,694,694
BEGIN DESCRIPTION:
Mapping XS 4bf91a64
END DESCRIPTION:
XS GIS Cut Line= 2
      3604136.94     10503318.29      3605259.33     10502694.26
#Sta/Elev= 30
    4701  350.68    4768  351.79  4795.6  351.12  4876.7  349.82  4957.9  349.77
  4979.6  349.17  4998.5  347.52  5001.3  347.02  5004.5  347.52  5017.4   348.8
  5047.3  349.62  5076.9  349.18  5253.3  351.27  5298.7  351.45  5379.1  353.35
  5466.9  357.63  5526.3  359.36  5532.1  360.25    5651  363.76  5678.5  365.67
  5710.5   366.8  5722.4  368.27  5753.9  369.66  5825.3  374.72  5840.9  376.27
  5848.2  377.92  5900.3  380.86  5906.1  381.88  5938.1   384.1  5985.2  388.95
#Mann= 3 ,-1 , 0
    4701     .05       0  4998.5     .03       0  5004.5     .05       0
Bank Sta=4795.6,5253.3
XS Rating Curve= 0 ,0
Exp/Cntr=0.3,0.1

Type RM Length L Ch R = 1 ,2643    ,917,917,917
BEGIN DESCRIPTION:
Mapping XS 0a1c321e
END DESCRIPTION:
XS GIS Cut Line= 2
      3604505.83     10503904.25      3605806.31     10503050.27
#Sta/Elev= 30
    4530  349.99  4570.6  349.98  4630.2  348.82  4845.6  347.84  4977.2  348.29
  4983.4  347.22  4995.5  347.13  4998.3  346.63  5001.5  347.13  5025.6  348.86
  5091.9  348.77  5143.2  349.96  5170.2  350.14  5236.4  353.19  5351.1  357.35
    5360  358.87  5395.9  358.57  5402.3  360.21  5428.3  360.48  5567.4   367.2
  5640.3  369.97    5683   372.4  5706.7  372.47  5778.7  376.56  5886.4   379.4
  5893.5  380.62  5922.3  381.63  5929.7   383.3  5965.8  384.58  6085.8  392.11
#Mann= 7 ,-1 , 0
    4530     .05       0  4995.5     .03       0  5001.5     .05       0
  5236.4      .1       0  5428.3     .05       0  5567.4      .1       0
  5640.3     .05       0
Bank Sta=4570.6,5143.2
XS Rating Curve= 0 ,0
Exp/Cntr=0.3,0.1

Type RM Length L Ch R = 1 ,1726    ,764,764,764
BEGIN DESCRIPTION:
Mapping XS 7fc2c0fd
END DESCRIPTION:
XS GIS Cut Line= 3
      3604653.43     10504572.24      3605408.67     10504463.73
      3605922.36     10503933.85
#Sta/Elev= 30
  4631.8  345.96  4708.8  347.13  4747.9  346.28  4759.3  347.27  4809.8   346.9
  4941.1  346.41  4998.7  344.21  5001.5  343.71  5004.7  344.21  5011.8  345.66
  5021.9  345.96  5053.6  345.14  5075.5  345.28  5133.1  346.28  5183.6  345.81
  5241.5  347.06  5274.5  346.48  5365.4  347.62  5392.7  349.54  5412.2  349.37
  5419.2  348.11  5433.3  347.41  5532.3  349.17    5610  348.55  5709.1  351.98
  5843.6   358.2  6006.2  363.69  6027.3  365.49  6076.9  367.23  6132.8  370.65
#Mann= 5 ,-1 , 0
  4631.8     .05       0  4998.7     .03       0  5004.7     .05       0
  5053.6     .16       0  5075.5     .05       0
Bank Sta=4809.8,5241.5
XS Rating Curve= 0 ,0
Exp/Cntr=0.3,0.1

Type RM Length L Ch R = 1 ,962     ,663,663,663
BEGIN DESCRIPTION:
Mapping XS 865e561a
END DESCRIPTION:
XS GIS Cut Line= 3
      3604570.98     10505158.17      3605135.23      10505236.3
      3605499.79     10505153.84
#Sta/Elev= 30
  4575.3  344.11  4725.3  343.73  4785.9  343.12  4856.6   343.1  4886.9  343.59
  4937.4  343.23  4947.4  343.69  4967.6  343.37  4977.7  343.89    4992  343.38
  4994.9  341.35  4997.7  340.85  5000.9  341.35    5008  343.72  5018.1  344.15
  5028.2  343.45  5038.3  343.56  5048.4   342.8  5063.7  343.09  5119.1  342.02
  5135.5  343.22  5159.7  343.13  5190.3  344.27  5281.8   345.1  5330.1  344.98
  5405.7  345.94  5464.7   345.5  5487.8  346.22  5507.9  347.96  5518.7  348.16
#Mann= 3 ,-1 , 0
  4575.3     .05       0  4994.9     .03       0  5000.9     .05       0
Bank Sta=4977.7,5018.1
XS Rating Curve= 0 ,0
Exp/Cntr=0.3,0.1

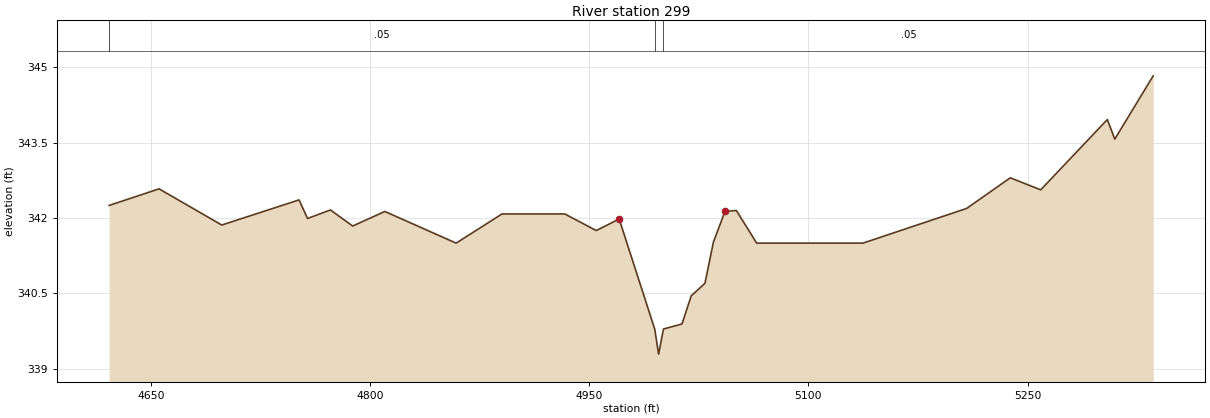
Type RM Length L Ch R = 1 ,299     ,0,0,0
BEGIN DESCRIPTION:
UNT 038 IN BUCR 1.0
END DESCRIPTION:
XS GIS Cut Line= 3
      3604375.66     10505457.64      3604761.97     10505683.35
      3605025.64     10505640.12
#Sta/Elev= 30
  4621.4  342.25  4655.6  342.58  4698.5  341.86  4751.4  342.36  4757.2  341.99
  4772.9  342.16  4788.1  341.84  4810.1  342.13  4858.9   341.5  4890.3  342.08
  4933.3  342.08  4954.8  341.75  4970.5  341.98  4994.8  339.79  4997.5  339.29
  5000.8  339.79  5013.5  339.89  5019.8  340.45  5029.2   340.7    5035  341.52
  5042.9  342.13  5050.7  342.15  5064.6   341.5  5137.4   341.5  5208.3  342.19
  5238.2   342.8    5259  342.56  5304.6  343.96  5309.7  343.57    5336  344.83
#Mann= 3 ,-1 , 0
  4621.4     .05       0  4994.8     .03       0  5000.8     .05       0
Bank Sta=4970.5,5042.9
XS Rating Curve= 0 ,0
Exp/Cntr=0.3,0.1

Chan Stop Cuts=-1
Use User Specified Reach Order=0
Composite Channel Slope=5