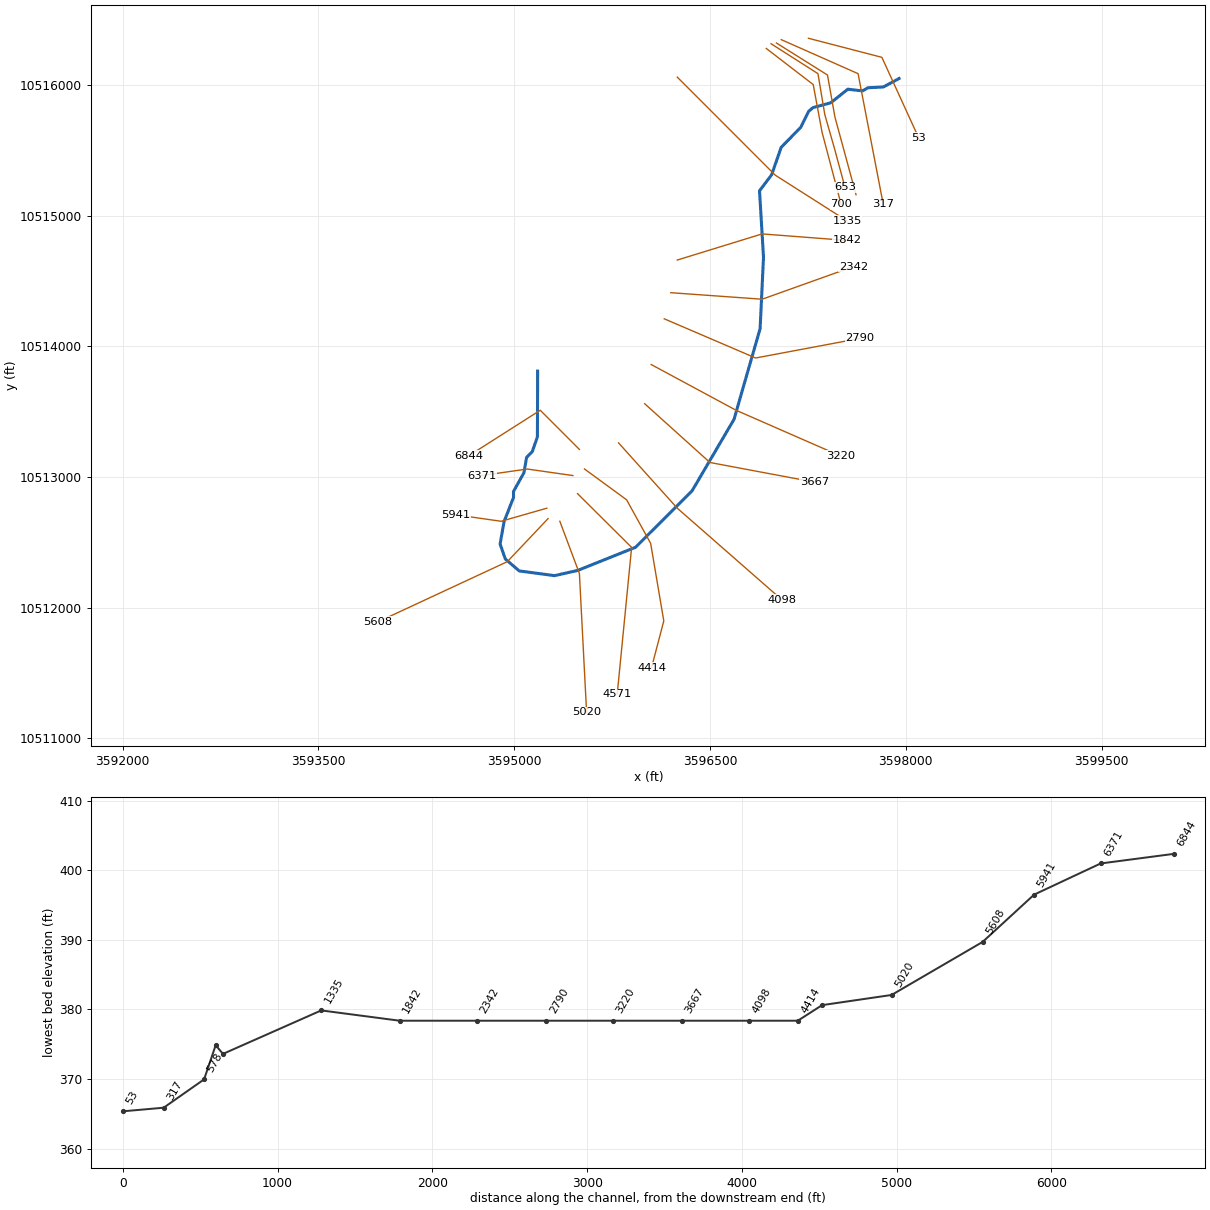
--- UNT 044 IN BUCR.prj (project) ---

Proj Title=UNT 044 IN BUCR Base Level Engineering
Current Plan=p01
Default Exp/Contr=0.3,0.1
English Units
Geom File=g01
Flow File=f01
Plan File=p01
BEGIN DESCRIPTION:
UNT 044 IN BUCR
END DESCRIPTION:

--- UNT 044 IN BUCR.p01 (plan) ---

Plan Title=Multiple Run
Short Identifier=Multiple
Geom File=g01
Flow File=f01
Subcritical Flow
K Sum by GR= 0
Std Step Tol= 0.01
Critical Tol= 0.01
Num of Std Step Trials= 20
Max Error Tol= 0.3
Flow Tol Ratio= 0.001
Split Flow NTrial= 30
Split Flow Tol= 0.02
Split Flow Ratio= 0.02
Log Output Level= 0
Friction Slope Method= 1
Unsteady Friction Slope Method= 2
Unsteady Bridges Friction Slope Method= 1
Parabolic Critical Depth
Global Vel Dist=  1 , 1 , 1
Global Log Level= 0
CheckData=True
Encroach Param= -1, 0, 0, 0
BEGIN DESCRIPTION:
Multiple Run
END DESCRIPTION:

--- UNT 044 IN BUCR.f01 (steady flow) ---

Flow Title=Multiple
Number of Profiles=7
Profile Names=10-year,25-year,50-year,1pct_min,100-year,1pct_plu,500-year
River Rch & RM= UNT 044 IN BUCR,Reach-1,6844
    1664    2373    2980    2731    3693    4994    5654
Boundary for River Rch & Prof#=UNT 044 IN BUCR,Reach-1,1
Up Type=0
Dn Type=3
Dn Slope=0.005
Boundary for River Rch & Prof#=UNT 044 IN BUCR,Reach-1,2
Up Type=0
Dn Type=3
Dn Slope=0.005
Boundary for River Rch & Prof#=UNT 044 IN BUCR,Reach-1,3
Up Type=0
Dn Type=3
Dn Slope=0.005
Boundary for River Rch & Prof#=UNT 044 IN BUCR,Reach-1,4
Up Type=0
Dn Type=3
Dn Slope=0.005
Boundary for River Rch & Prof#=UNT 044 IN BUCR,Reach-1,5
Up Type=0
Dn Type=3
Dn Slope=0.005
Boundary for River Rch & Prof#=UNT 044 IN BUCR,Reach-1,6
Up Type=0
Dn Type=3
Dn Slope=0.005
Boundary for River Rch & Prof#=UNT 044 IN BUCR,Reach-1,7
Up Type=0
Dn Type=3
Dn Slope=0.005

--- UNT 044 IN BUCR.g01 (geometry) ---

Geom Title=Existing Conditions

River Reach=UNT 044 IN BUCR,Reach-1
Reach XY= 30
      3595179.81     10513810.28      3595177.75     10513306.00
      3595138.50     10513194.00      3595095.00     10513149.00
      3595074.25     10513031.00      3594994.50     10512888.00
      3594995.00     10512842.00      3594922.50     10512659.00
      3594892.00     10512486.00      3594932.00     10512371.00
      3595038.75     10512280.00      3595309.00     10512244.00
      3595487.25     10512284.00      3595929.50     10512461.00
      3596363.25     10512894.00      3596684.25     10513441.00
      3596884.00     10514135.00      3596910.00     10514682.00
      3596879.50     10515190.00      3596972.75     10515314.00
      3597045.50     10515523.00      3597195.25     10515676.00
      3597256.25     10515799.00      3597289.25     10515827.00
      3597425.50     10515864.00      3597556.00     10515968.00
      3597668.50     10515955.00      3597710.25     10515979.00
      3597828.50     10515985.00      3597948.75     10516050.00

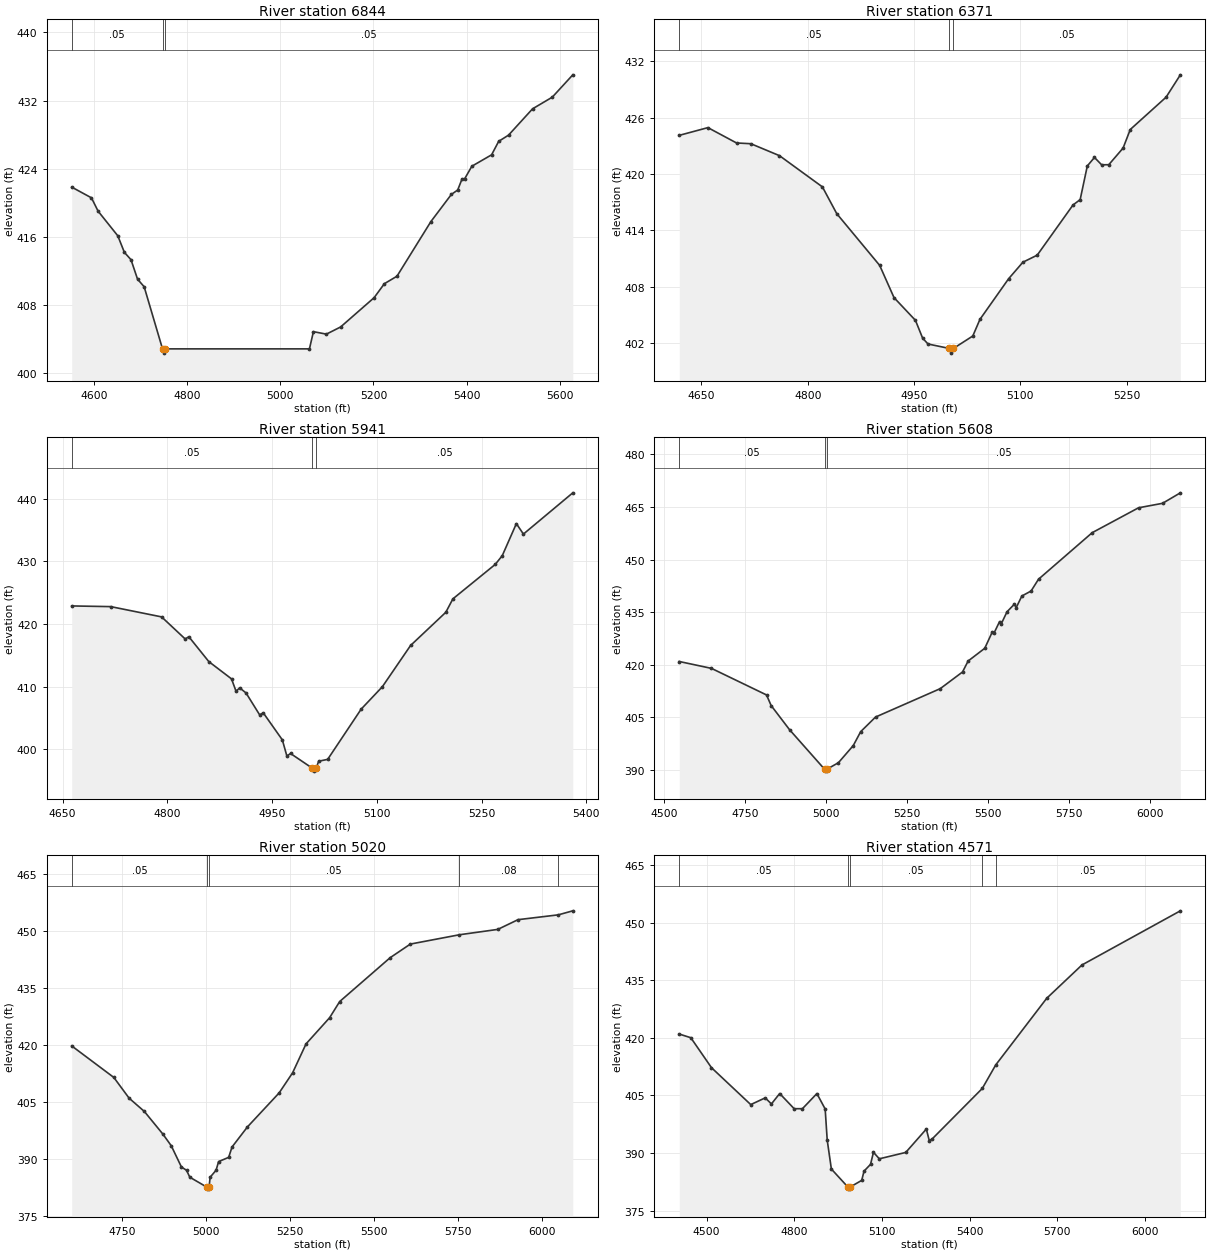
Type RM Length L Ch R = 1,6844,473,473,473
BEGIN DESCRIPTION:
UNT 044 IN BUCR 15.0
END DESCRIPTION:
XS GIS Cut Line= 3
      3595499.61     10513210.19      3595199.61     10513510.19
      3594649.60     10513160.18
#Sta/Elev= 30
  4551.9  421.84  4594.3  420.58  4608.5  419.02  4650.9  416.12  4665.0  414.18
  4679.2  413.32  4693.3  411.03  4707.5  410.14  4746.9  402.85  4749.6  402.35
  4752.9  402.85  5062.5  402.85  5071.0  404.87  5098.9  404.58  5129.4  405.42
  5201.4  408.86  5223.4  410.50  5250.5  411.38  5323.3  417.79  5367.3  420.98
  5380.9  421.50  5390.2  422.79  5396.1  422.84  5411.3  424.29  5453.7  425.63
  5468.9  427.21  5490.1  427.94  5541.7  431.03  5584.1  432.40  5628.1  435.02
#Mann=3,-1,0
  4551.9    0.05       0  4746.9   0.033       0  4752.9    0.05       0
Bank Sta=4746.9,4752.9
Exp/Cntr=0.3,0.1

Type RM Length L Ch R = 1,6371,430,430,430
BEGIN DESCRIPTION:
UNT 044 IN BUCR 14.0
END DESCRIPTION:
XS GIS Cut Line= 3
      3595449.60     10513010.19      3595099.61     10513060.19
      3594749.61     10513010.19
#Sta/Elev= 30
  4618.8  424.11  4659.2  424.93  4699.6  423.30  4719.8  423.22  4760.2  421.95
  4820.8  418.63  4841.0  415.79  4901.6  410.29  4921.8  406.87  4952.1  404.45
  4962.2  402.56  4969.8  401.94  4999.7  401.47  5002.4  400.97  5005.7  401.47
  5033.0  402.79  5043.1  404.56  5083.5  408.87  5103.7  410.63  5123.9  411.38
  5174.4  416.71  5184.5  417.28  5194.6  420.86  5204.7  421.76  5214.8  420.98
  5224.9  420.99  5245.1  422.76  5255.2  424.73  5305.7  428.16  5325.9  430.54
#Mann=3,-1,0
  4618.8    0.05       0  4999.7    0.03       0  5005.7    0.05       0
Bank Sta=4999.7,5005.7
Exp/Cntr=0.3,0.1

Type RM Length L Ch R = 1,5941,333,333,333
BEGIN DESCRIPTION:
UNT 044 IN BUCR 13.0
END DESCRIPTION:
XS GIS Cut Line= 3
      3595249.59     10512760.18      3594899.61     10512660.19
      3594549.65     10512710.18
#Sta/Elev= 30
  4663.2  422.88  4719.1  422.77  4791.9  421.13  4825.7  417.60  4830.9  417.96
  4859.5  413.99  4892.0  411.23  4898.5  409.25  4903.7  409.79  4912.8  408.98
  4932.3  405.48  4937.5  405.80  4964.8  401.48  4971.3  398.90  4976.5  399.31
  5007.3  396.99  5010.0  396.49  5013.3  396.99  5016.8  398.07  5029.7  398.37
  5077.7  406.40  5108.0  409.97  5148.4  416.56  5198.9  421.87  5209.0  424.01
  5269.6  429.51  5279.7  430.91  5299.9  436.03  5310.0  434.36  5380.7  440.95
#Mann=3,-1,0
  4663.2    0.05       0  5007.3    0.03       0  5013.3    0.05       0
Bank Sta=5007.3,5013.3
Exp/Cntr=0.3,0.1

Type RM Length L Ch R = 1,5608,588,588,588
BEGIN DESCRIPTION:
UNT 044 IN BUCR 12.0
END DESCRIPTION:
XS GIS Cut Line= 3
      3595259.60     10512680.76      3594947.07     10512350.87
      3593957.51     10511890.81
#Sta/Elev= 30
  4546.8  420.95  4646.1  418.99  4816.0  411.41  4830.1  408.40  4886.8  401.52
  4995.3  390.19  4998.0  389.69  5001.3  390.19  5037.7  392.09  5083.5  396.98
  5106.4  400.95  5152.2  405.11  5351.8  413.21  5420.5  417.96  5437.8  421.09
  5489.1  424.72  5512.0  429.31  5517.5  429.02  5534.9  432.35  5540.4  431.77
  5557.8  435.13  5580.7  437.32  5586.2  436.34  5603.6  439.63  5632.0  441.05
  5654.9  444.41  5820.6  457.69  5963.4  464.78  6037.6  466.06  6092.5  469.05
#Mann=3,-1,0
  4546.8    0.05       0  4995.3    0.03       0  5001.3    0.05       0
Bank Sta=4995.3,5001.3
Exp/Cntr=0.3,0.1

Type RM Length L Ch R = 1,5020,449,449,449
BEGIN DESCRIPTION:
UNT 044 IN BUCR 11.0
END DESCRIPTION:
XS GIS Cut Line= 3
      3595349.62     10512660.15      3595499.61     10512260.19
      3595554.66     10511197.27
#Sta/Elev= 30
  4599.9  419.79  4725.3  411.48  4770.7  406.03  4816.1  402.53  4871.3  396.56
  4896.2  393.49  4926.5  387.89  4941.6  387.04  4951.4  385.21  5002.7  382.57
  5005.4  382.07  5008.7  382.57  5011.9  385.20  5029.6  387.05  5037.1  389.32
  5067.1  390.44  5077.1  393.17  5123.0  398.46  5217.3  407.41  5257.4  412.71
  5297.4  420.33  5367.5  427.21  5397.6  431.48  5547.8  443.03  5607.8  446.61
  5754.1  449.07  5868.2  450.48  5928.3  453.04  6048.2  454.31  6091.4  455.37
#Mann=5,-1,0
  4599.9    0.05       0  5002.7    0.03       0  5008.7    0.05       0
  5754.1    0.08       0  6048.2    0.05       0
Bank Sta=5002.7,5008.7
Exp/Cntr=0.3,0.1

Type RM Length L Ch R = 1,4571,157,157,157
BEGIN DESCRIPTION:
UNT 044 IN BUCR 10.0
END DESCRIPTION:
XS GIS Cut Line= 3
      3595485.30     10512871.67      3595899.61     10512460.19
      3595789.08     10511335.23
#Sta/Elev= 30
  4406.8  421.00  4446.2  420.05  4517.0  412.24  4651.3  402.63  4700.8  404.38
  4722.0  402.80  4750.3  405.51  4799.8  401.56  4828.1  401.56  4877.6  405.50
  4905.9  401.48  4912.9  393.38  4927.1  385.85  4984.2  381.11  4987.0  380.61
  4990.2  381.11  5030.9  382.89  5038.9  385.30  5061.1  387.07  5071.1  390.20
  5091.2  388.51  5181.6  390.17  5252.0  396.26  5262.0  393.26  5272.1  393.69
  5443.5  406.84  5489.4  412.96  5664.0  430.33  5784.5  439.00  6121.1  453.10
#Mann=5,-1,0
  4406.8    0.05       0  4984.2    0.03       0  4990.2    0.05       0
  5443.5    0.15       0  5489.4    0.05       0
Bank Sta=4984.2,4990.2
Exp/Cntr=0.3,0.1

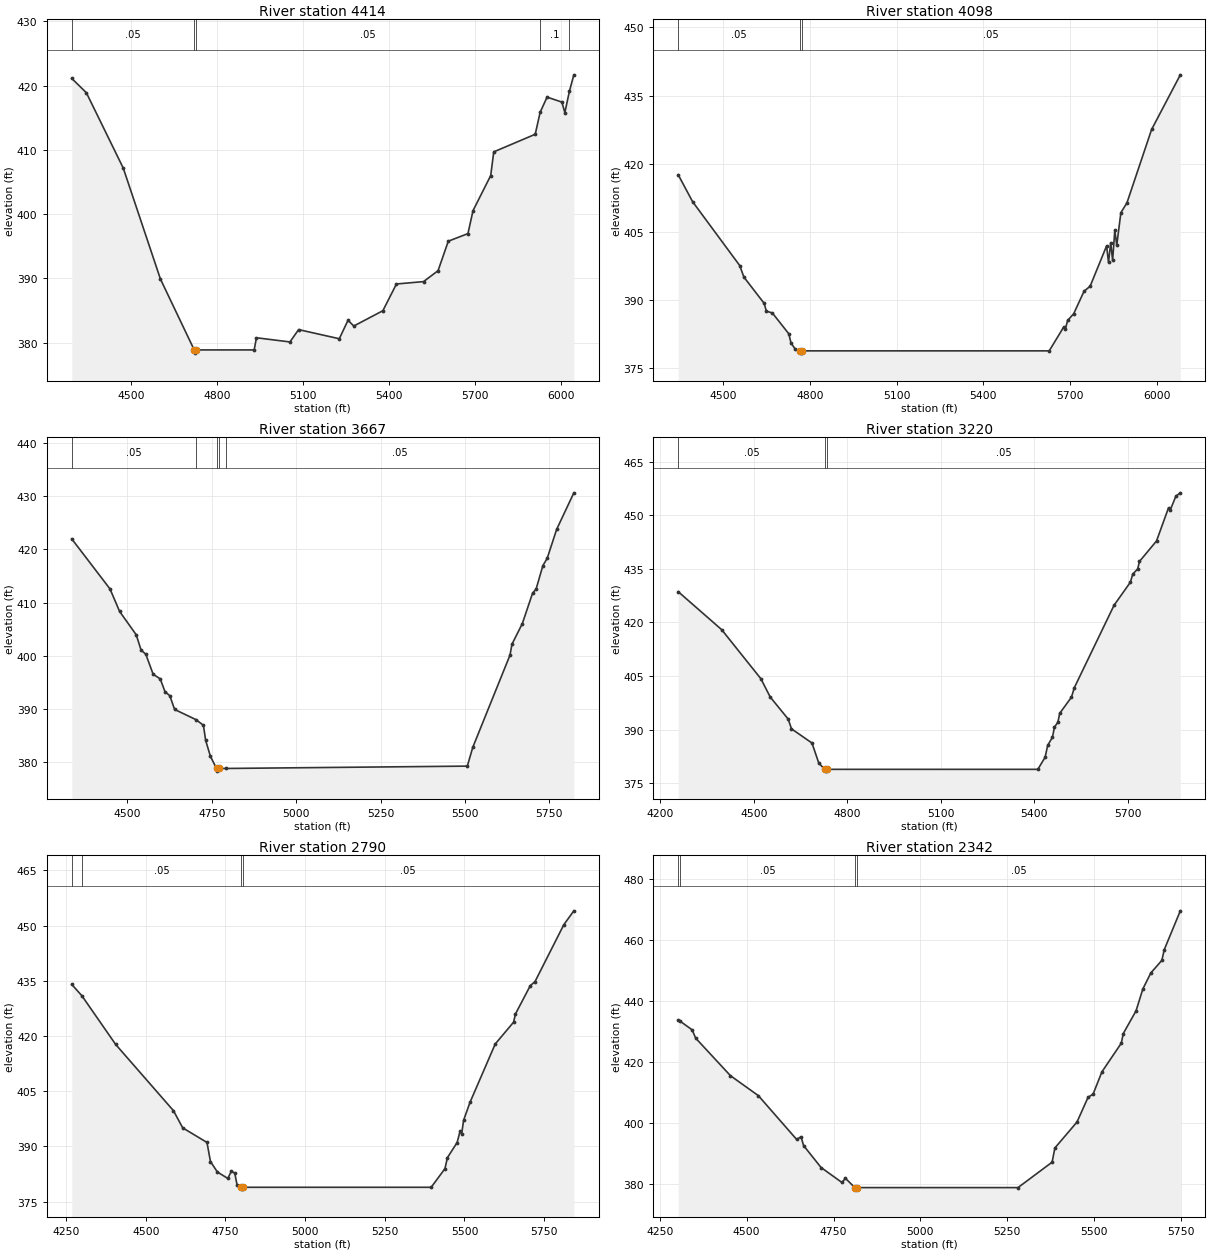
Type RM Length L Ch R = 1,4414,316,316,316
BEGIN DESCRIPTION:
Mapping XS 9784ba72
END DESCRIPTION:
XS GIS Cut Line= 5
      3595538.43     10513060.58      3595861.31     10512824.50
      3596045.34     10512491.16      3596146.03     10511897.41
      3596052.28     10511539.77
#Sta/Elev= 30
  4292.6  421.12  4343.6  418.89  4472.4  407.16  4602.1  389.90  4720.1  378.87
  4722.8  378.37  4726.1  378.87  4929.3  378.87  4937.4  380.76  5054.2  380.11
  5084.5  382.03  5226.5  380.61  5256.9  383.48  5277.2  382.59  5378.6  384.97
  5426.0  389.13  5520.6  389.50  5571.3  391.20  5607.0  395.79  5675.6  396.97
  5693.4  400.55  5755.1  406.01  5765.7  409.69  5910.5  412.43  5927.6  415.84
  5951.8  418.21  6003.5  417.44  6013.9  415.80  6030.1  419.18  6045.3  421.68
#Mann=5,-1,0
  4292.6    0.05       0  4720.1    0.03       0  4726.1    0.05       0
  5927.6     0.1       0  6030.1    0.05       0
Bank Sta=4720.1,4726.1
Exp/Cntr=0.3,0.1

Type RM Length L Ch R = 1,4098,431,431,431
BEGIN DESCRIPTION:
UNT 044 IN BUCR 9.0
END DESCRIPTION:
XS GIS Cut Line= 3
      3595799.60     10513260.20      3596249.61     10512760.19
      3597049.60     10512060.19
#Sta/Elev= 30
  4345.3  417.57  4395.0  411.66  4558.0  397.61  4572.2  395.10  4642.4  389.30
  4649.9  387.61  4670.8  387.19  4727.6  382.62  4735.1  380.61  4748.9  379.33
  4767.2  378.87  4770.0  378.37  4773.2  378.87  5627.8  378.87  5677.2  384.04
  5683.8  383.73  5691.4  385.55  5712.3  387.02  5748.3  391.98  5769.2  393.07
  5826.2  401.96  5832.8  398.31  5840.4  402.65  5847.0  398.76  5854.6  405.43
  5861.3  402.07  5875.5  409.24  5896.4  411.39  5981.8  427.54  6081.0  439.55
#Mann=3,-1,0
  4345.3    0.05       0  4767.2    0.03       0  4773.2    0.05       0
Bank Sta=4767.2,4773.2
Exp/Cntr=0.3,0.1

Type RM Length L Ch R = 1,3667,447,447,447
BEGIN DESCRIPTION:
UNT 044 IN BUCR 8.0
END DESCRIPTION:
XS GIS Cut Line= 3
      3595999.63     10513560.17      3596499.61     10513110.19
      3597299.61     10512960.19
#Sta/Elev= 30
  4335.7  421.96  4448.9  412.57  4477.3  408.35  4526.6  403.96  4540.8  401.11
  4555.0  400.30  4576.7  396.55  4597.6  395.69  4611.8  393.28  4626.0  392.53
  4640.2  389.95  4704.0  388.02  4725.5  386.97  4732.2  384.12  4746.4  381.12
  4764.3  378.87  4767.1  378.37  4770.3  378.87  4792.4  378.87  5506.9  379.31
  5523.0  382.83  5633.2  400.14  5639.2  402.21  5669.7  406.06  5700.2  411.79
  5710.4  412.52  5730.7  416.96  5743.4  418.32  5771.4  423.75  5822.3  430.61
#Mann=5,-1,0
  4335.7    0.05       0  4704.0    0.07       0  4764.3    0.03       0
  4770.3    0.07       0  4792.4    0.05       0
Bank Sta=4764.3,4770.3
Exp/Cntr=0.3,0.1

Type RM Length L Ch R = 1,3220,430,430,430
BEGIN DESCRIPTION:
UNT 044 IN BUCR 7.0
END DESCRIPTION:
XS GIS Cut Line= 3
      3596049.57     10513860.21      3596699.61     10513510.19
      3597499.61     10513160.19
#Sta/Elev= 30
  4257.3  428.58  4396.9  417.94  4522.6  404.22  4552.6  399.10  4610.2  392.94
  4620.8  390.21  4686.5  386.24  4708.4  380.64  4727.3  378.87  4730.1  378.37
  4733.3  378.87  5411.5  378.87  5434.9  382.26  5443.1  385.57  5458.3  387.84
  5464.9  390.67  5475.9  392.08  5481.7  394.54  5519.5  399.07  5528.5  401.70
  5656.3  424.81  5708.6  431.24  5716.0  433.48  5732.0  434.96  5737.8  437.06
  5792.4  442.77  5831.0  452.06  5836.4  451.41  5854.4  455.28  5868.8  456.25
#Mann=3,-1,0
  4257.3    0.05       0  4727.3    0.03       0  4733.3    0.05       0
Bank Sta=4727.3,4733.3
Exp/Cntr=0.3,0.1

Type RM Length L Ch R = 1,2790,448,448,448
BEGIN DESCRIPTION:
UNT 044 IN BUCR 6.0
END DESCRIPTION:
XS GIS Cut Line= 3
      3596149.62     10514210.18      3596849.61     10513910.19
      3597649.61     10514060.19
#Sta/Elev= 30
  4267.8  434.02  4299.7  430.92  4405.6  417.70  4586.9  399.70  4615.9  395.03
  4692.1  391.06  4703.0  385.88  4724.7  383.03  4757.4  381.28  4768.2  383.17
  4779.1  382.78  4786.4  379.55  4797.9  378.87  4800.6  378.37  4803.9  378.87
  5395.6  378.87  5438.9  383.95  5446.5  386.92  5477.0  391.04  5486.4  394.14
  5491.4  393.47  5497.4  397.10  5517.7  402.02  5596.6  417.83  5654.2  423.76
  5660.2  426.01  5706.8  433.72  5721.2  434.75  5811.9  450.27  5843.3  454.03
#Mann=4,-1,0
  4267.8    0.07       0  4299.7    0.05       0  4797.9    0.03       0
  4803.9    0.05       0
Bank Sta=4797.9,4803.9
Exp/Cntr=0.3,0.1

Type RM Length L Ch R = 1,2342,500,500,500
BEGIN DESCRIPTION:
UNT 044 IN BUCR 5.0
END DESCRIPTION:
XS GIS Cut Line= 3
      3596199.59     10514410.19      3596899.61     10514360.19
      3597599.60     10514610.19
#Sta/Elev= 30
  4303.1  433.72  4307.8  433.49  4343.2  430.58  4353.2  427.88  4453.5  415.55
  4533.7  409.02  4644.0  394.65  4656.5  395.55  4664.0  392.63  4714.2  385.46
  4774.3  380.55  4784.3  381.93  4811.4  378.87  4814.2  378.37  4817.4  378.87
  5281.0  378.87  5379.2  387.21  5387.2  391.87  5450.9  400.38  5482.7  408.48
  5497.1  409.51  5522.6  416.83  5578.3  426.21  5584.1  429.39  5620.8  436.83
  5640.4  444.00  5663.3  449.24  5695.1  453.37  5702.0  456.88  5748.2  469.61
#Mann=4,-1,0
  4303.1    0.07       0  4307.8    0.05       0  4811.4   0.033       0
  4817.4    0.05       0
Bank Sta=4811.4,4817.4
Exp/Cntr=0.3,0.1

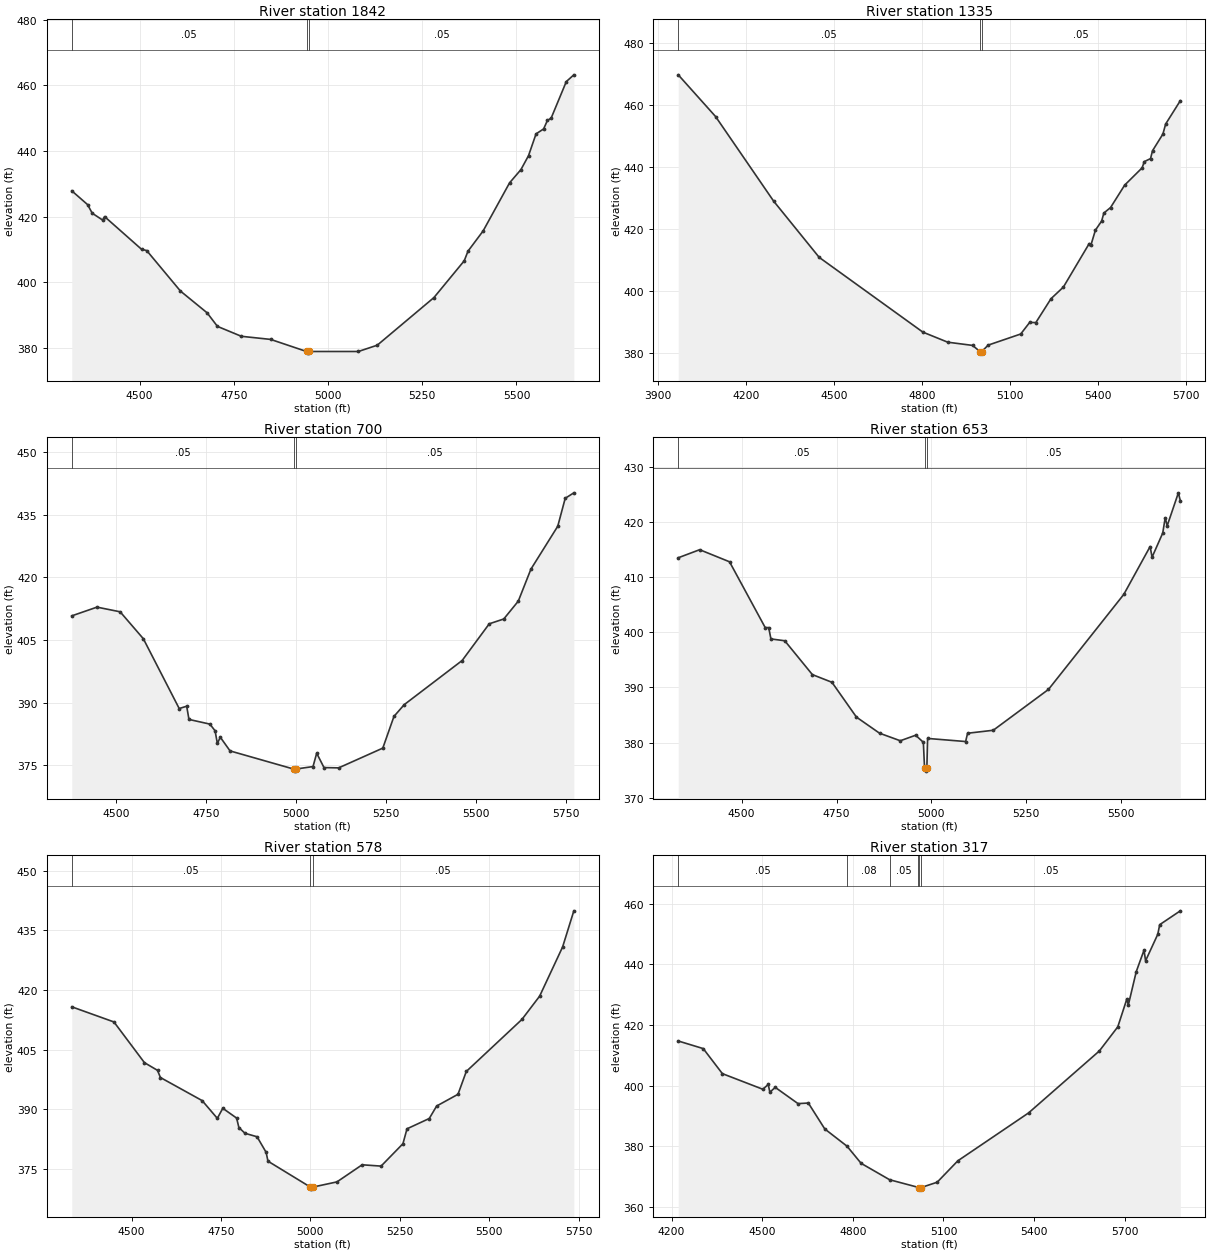
Type RM Length L Ch R = 1,1842,507,507,507
BEGIN DESCRIPTION:
UNT 044 IN BUCR 4.0
END DESCRIPTION:
XS GIS Cut Line= 3
      3596249.59     10514660.18      3596899.61     10514860.19
      3597549.59     10514810.19
#Sta/Elev= 30
  4320.2  427.84  4362.1  423.64  4374.5  421.01  4402.0  418.93  4407.2  419.99
  4505.3  410.02  4519.0  409.63  4608.6  397.28  4679.2  390.66  4706.7  386.52
  4770.1  383.50  4847.9  382.55  4943.0  378.87  4945.8  378.37  4949.0  378.87
  5080.5  378.87  5130.7  380.79  5281.1  395.31  5361.4  406.51  5371.4  409.45
  5411.5  415.61  5481.7  430.27  5511.8  434.30  5531.9  438.54  5551.9  445.19
  5572.0  446.70  5582.0  449.27  5592.0  450.00  5632.2  461.13  5652.2  463.19
#Mann=3,-1,0
  4320.2    0.05       0  4943.0   0.033       0  4949.0    0.05       0
Bank Sta=4943,4949
Exp/Cntr=0.3,0.1

Type RM Length L Ch R = 1,1335,635,635,635
BEGIN DESCRIPTION:
UNT 044 IN BUCR 3.0
END DESCRIPTION:
XS GIS Cut Line= 3
      3596249.61     10516060.19      3596999.61     10515310.19
      3597549.62     10514960.18
#Sta/Elev= 30
  3969.3  469.65  4096.6  456.20  4294.6  428.91  4450.1  410.75  4803.7  386.63
  4888.5  383.38  4973.4  382.34  4998.7  380.35  5001.4  379.85  5004.7  380.35
  5026.4  382.43  5137.5  386.02  5168.0  389.75  5189.1  389.71  5240.8  397.41
  5283.1  401.17  5371.2  415.21  5377.1  414.75  5392.3  419.53  5413.5  422.46
  5421.1  425.05  5444.0  426.83  5492.2  434.07  5551.5  439.62  5559.1  441.64
  5580.3  442.62  5587.1  445.16  5622.6  450.55  5631.9  453.78  5681.9  461.30
#Mann=3,-1,0
  3969.3    0.05       0  4998.7    0.03       0  5004.7    0.05       0
Bank Sta=4998.7,5004.7
Exp/Cntr=0.3,0.1

Type RM Length L Ch R = 1,700,47,47,47
BEGIN DESCRIPTION:
UNT 044 IN BUCR 2.0
END DESCRIPTION:
XS GIS Cut Line= 4
      3596931.41     10516279.71      3597290.82     10516003.64
      3597358.53     10515639.06      3597504.35     10515087.01
#Sta/Elev= 30
  4376.7  410.78  4446.8  412.87  4511.1  411.75  4575.5  405.31  4675.2  388.59
  4696.0  389.14  4702.3  385.98  4760.4  384.86  4774.9  383.26  4781.2  380.23
  4789.4  381.72  4816.5  378.44  4993.1  374.10  4995.9  373.60  4999.1  374.10
  5047.0  374.69  5057.2  377.89  5077.5  374.45  5118.2  374.38  5240.9  379.11
  5271.9  386.70  5300.3  389.51  5461.4  400.09  5536.7  408.88  5577.0  410.03
  5617.3  414.30  5652.4  421.96  5727.0  432.24  5747.7  438.93  5771.7  440.24
#Mann=3,-1,0
  4376.7    0.05       0  4993.1    0.03       0  4999.1    0.05       0
Bank Sta=4993.1,4999.1
Exp/Cntr=0.3,0.1

Type RM Length L Ch R = 1,653,75,75,75
BEGIN DESCRIPTION:
Mapping XS 90ebc027
END DESCRIPTION:
XS GIS Cut Line= 5
      3596967.92     10516316.13      3597327.28     10516086.98
      3597379.36     10515774.48      3597452.28     10515519.27
      3597534.66     10515215.48
#Sta/Elev= 30
  4332.9  413.49  4389.4  414.95  4468.1  412.76  4562.0  400.86  4571.3  400.84
  4577.2  398.79  4613.6  398.46  4686.4  392.33  4738.0  390.94  4802.6  384.63
  4863.4  381.72  4918.1  380.35  4958.6  381.35  4978.9  380.07  4982.1  375.35
  4984.8  374.85  4988.1  375.35  4990.1  380.77  5090.3  380.21  5095.5  381.71
  5163.1  382.25  5308.7  389.65  5507.2  406.86  5576.5  415.52  5581.7  413.60
  5609.8  417.97  5616.3  420.74  5621.5  419.28  5651.0  425.25  5656.1  423.83
#Mann=3,-1,0
  4332.9    0.05       0  4982.1    0.03       0  4988.1    0.05       0
Bank Sta=4982.1,4988.1
Exp/Cntr=0.3,0.1

Type RM Length L Ch R = 1,578,261,261,261
BEGIN DESCRIPTION:
Mapping XS 496d4d2d
END DESCRIPTION:
XS GIS Cut Line= 4
      3597009.59     10516321.34      3597400.19     10516076.56
      3597457.48     10515753.64      3597618.93     10515159.93
#Sta/Elev= 30
  4332.5  415.79  4450.5  411.98  4535.7  401.75  4572.3  399.81  4580.4  398.01
  4697.2  392.20  4739.6  387.74  4754.9  390.27  4793.5  387.81  4799.9  385.43
  4817.0  383.98  4850.7  383.11  4876.1  379.19  4881.2  376.97  5000.1  370.44
  5002.8  369.94  5006.1  370.44  5074.2  371.76  5144.6  376.06  5197.6  375.73
  5258.7  381.36  5270.1  385.11  5332.3  387.70  5353.0  390.84  5412.7  393.79
  5435.9  399.53  5591.4  412.61  5641.0  418.47  5705.3  430.85  5736.7  439.93
#Mann=3,-1,0
  4332.5    0.05       0  5000.1    0.03       0  5006.1    0.05       0
Bank Sta=5000.1,5006.1
Exp/Cntr=0.3,0.1

Type RM Length L Ch R = 1,317,264,264,264
BEGIN DESCRIPTION:
Mapping XS bb085319
END DESCRIPTION:
XS GIS Cut Line= 3
      3597046.02     10516347.40      3597634.57     10516086.98
      3597827.28     10515086.97
#Sta/Elev= 30
  4222.0  414.74  4304.8  412.23  4368.1  403.97  4502.0  398.82  4519.9  400.40
  4525.3  397.84  4543.1  399.44  4618.5  394.08  4652.7  394.27  4707.1  385.72
  4780.8  380.03  4827.4  374.38  4921.7  368.97  5016.2  366.46  5019.3  366.37
  5022.0  365.87  5025.3  366.37  5079.2  368.15  5147.5  375.21  5381.7  391.01
  5615.9  411.44  5677.0  419.40  5706.9  428.55  5712.0  426.63  5738.1  437.60
  5763.9  444.71  5769.0  441.20  5809.4  449.94  5815.8  453.11  5884.0  457.68
#Mann=6,-1,0
  4222.0    0.05       0  4780.8    0.08       0  4921.7    0.05       0
  5016.2     0.1       0  5019.3    0.03       0  5025.3    0.05       0
Bank Sta=5019.3,5025.3
Exp/Cntr=0.3,0.1

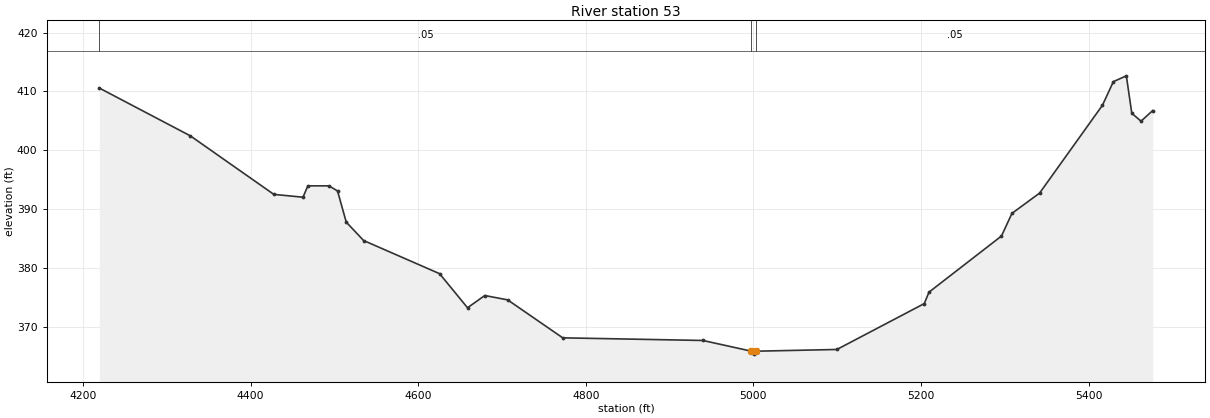
Type RM Length L Ch R = 1,53,0,0,0
BEGIN DESCRIPTION:
UNT 044 IN BUCR 1.0
END DESCRIPTION:
XS GIS Cut Line= 3
      3597254.40     10516357.80      3597816.86     10516211.98
      3598098.10     10515597.43
#Sta/Elev= 30
  4219.6  410.57  4328.3  402.44  4427.8  392.50  4462.6  392.02  4468.4  393.95
  4493.6  393.95  4503.8  393.08  4514.2  387.79  4534.9  384.66  4625.6  379.02
  4658.9  373.23  4679.5  375.31  4706.8  374.57  4772.5  368.12  4939.8  367.67
  4997.6  365.85  5000.3  365.35  5003.6  365.85  5099.6  366.14  5203.9  373.94
  5209.5  375.88  5296.0  385.42  5308.5  389.27  5341.5  392.72  5416.5  407.65
  5429.5  411.66  5445.0  412.65  5451.5  406.29  5462.5  404.94  5476.5  406.75
#Mann=3,-1,0
  4219.6    0.05       0  4997.6    0.03       0  5003.6    0.05       0
Bank Sta=4997.6,5003.6
Exp/Cntr=0.3,0.1

Chan Stop Cuts=-1