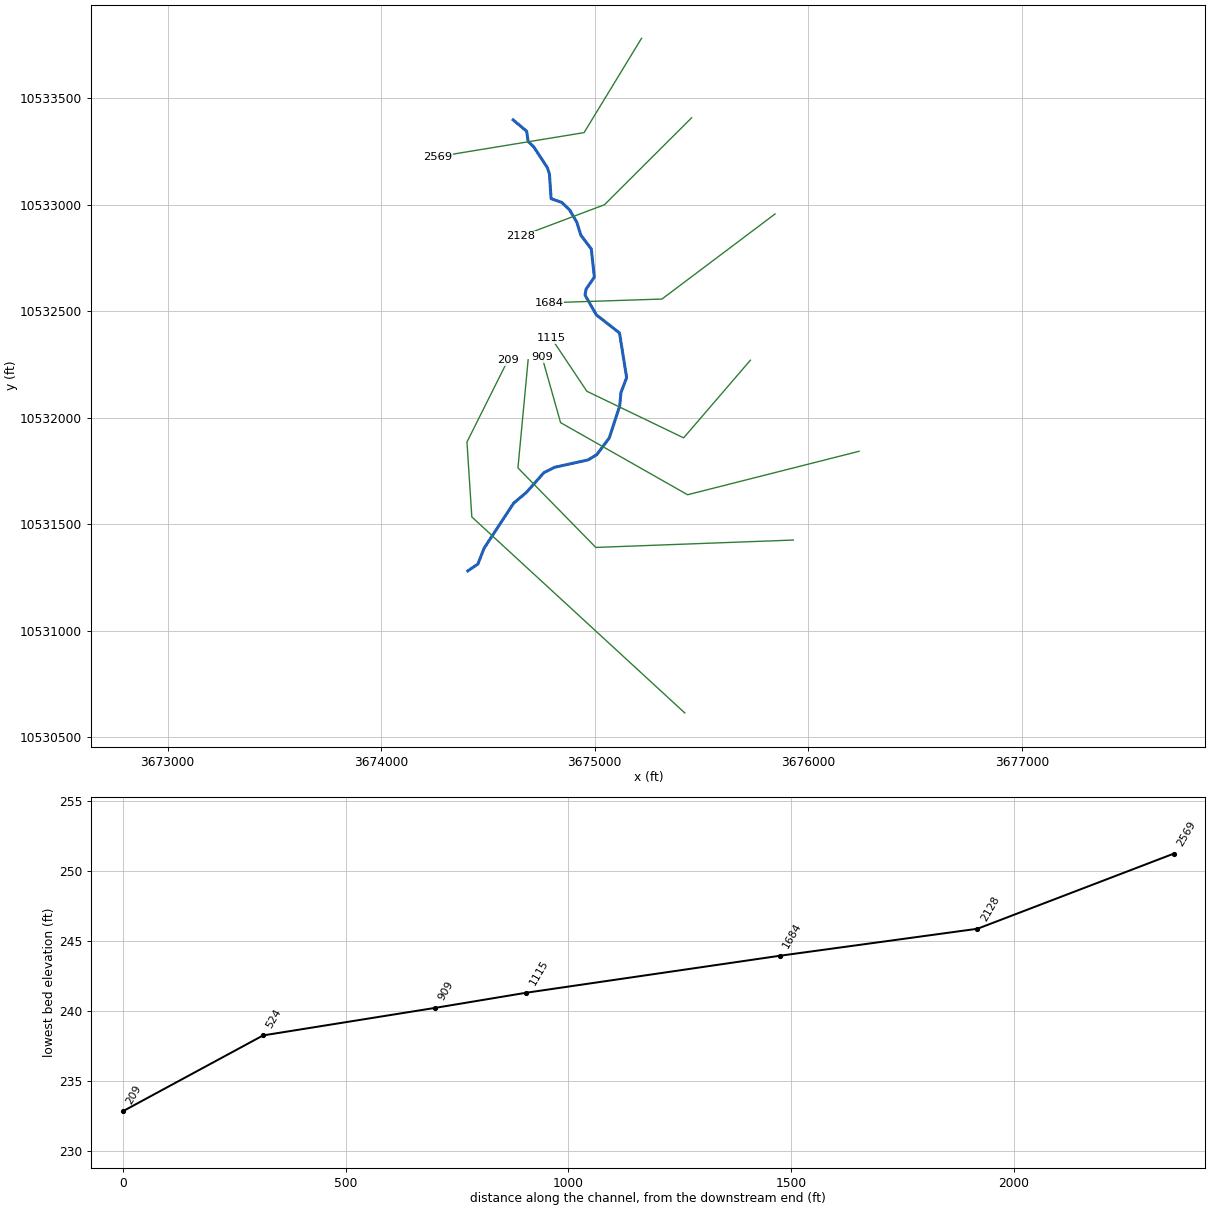
--- UNT 04839 IN BUCR.prj (project) ---

Proj Title=UNT 04839 IN BUCR Base Level Engineering
Current Plan=p01
Default Exp/Contr=0.3,0.1
English Units
Geom File=g01
Flow File=f01
Plan File=p01
Y Axis Title=Elevation
X Axis Title(PF)=Main Channel Distance
X Axis Title(XS)=Station
BEGIN DESCRIPTION:
UNT 04839 IN BUCR
END DESCRIPTION:
DSS Export Rating Curves= 0
DSS Export Rating Curve Sorted= 0
DSS Export Volume Flow Curves= 0
DXF OffsetX= 0
DXF OffsetY= 0
DXF ScaleX= 1
DXF ScaleY= 10

--- UNT 04839 IN BUCR.p01 (plan) ---

Plan Title=Multiple Run
Short Identifier=Multiple
Geom File=g01
Flow File=f01
Subcritical Flow
K Sum by GR= 0
Std Step Tol= 0.01
Critical Tol= 0.01
Num of Std Step Trials= 20
Max Error Tol= 0.3
Flow Tol Ratio= 0.001
Split Flow NTrial= 30
Split Flow Tol= 0.02
Split Flow Ratio= 0.02
Log Output Level= 0
Friction Slope Method= 1
Unsteady Friction Slope Method= 2
Unsteady Bridges Friction Slope Method= 1
Parabolic Critical Depth
Global Vel Dist=  1 , 1 , 1
Global Log Level= 0
CheckData=True
Encroach Param= -1, 0, 0, 0
BEGIN DESCRIPTION:
Multiple Run
END DESCRIPTION:

--- UNT 04839 IN BUCR.f01 (steady flow) ---

Flow Title=Multiple
Program Version=4.10
Number of Profiles= 7
Profile Names=10-year,25-year,50-year,1pct_min,100-year,1pct_plu,500-year
River Rch & RM=UNT 04839 IN BUC,Reach-1         ,2569
     502     677     822     734     993    1342    1453
Boundary for River Rch & Prof#=UNT 04839 IN BUC,Reach-1         , 1
Up Type= 0
Dn Type= 3
Dn Slope=0.015
Boundary for River Rch & Prof#=UNT 04839 IN BUC,Reach-1         , 2
Up Type= 0
Dn Type= 3
Dn Slope=0.015
Boundary for River Rch & Prof#=UNT 04839 IN BUC,Reach-1         , 3
Up Type= 0
Dn Type= 3
Dn Slope=0.015
Boundary for River Rch & Prof#=UNT 04839 IN BUC,Reach-1         , 4
Up Type= 0
Dn Type= 3
Dn Slope=0.015
Boundary for River Rch & Prof#=UNT 04839 IN BUC,Reach-1         , 5
Up Type= 0
Dn Type= 3
Dn Slope=0.015
Boundary for River Rch & Prof#=UNT 04839 IN BUC,Reach-1         , 6
Up Type= 0
Dn Type= 3
Dn Slope=0.015
Boundary for River Rch & Prof#=UNT 04839 IN BUC,Reach-1         , 7
Up Type= 0
Dn Type= 3
Dn Slope=0.015
DSS Import GetInterval= 0
DSS Import GetPeak= 0
DSS Import FillOption= 0

--- UNT 04839 IN BUCR.g01 (geometry) ---

Geom Title=Existing Conditions
Program Version=4.10

River Reach=UNT 04839 IN BUC,Reach-1
Reach XY= 30
        3674618.       10533399.      3674681.25       10533346.
      3674688.25       10533298.      3674714.25       10533273.
      3674778.25       10533175.        3674788.       10533145.
      3674795.75       10533029.       3674845.5       10533012.
        3674882.       10532977.        3674916.       10532919.
        3674935.       10532858.        3674984.       10532793.
      3674998.25       10532661.      3674959.75       10532605.
       3674954.5       10532577.       3675007.5       10532484.
        3675116.       10532399.       3675149.5       10532189.
      3675122.75       10532119.        3675117.       10532056.
        3675068.       10531906.        3675009.       10531827.
       3674968.5       10531803.      3674810.75       10531768.
        3674762.       10531743.       3674679.5       10531650.
       3674620.5       10531600.      3674482.25       10531389.
      3674452.75       10531314.      3674405.75       10531282.

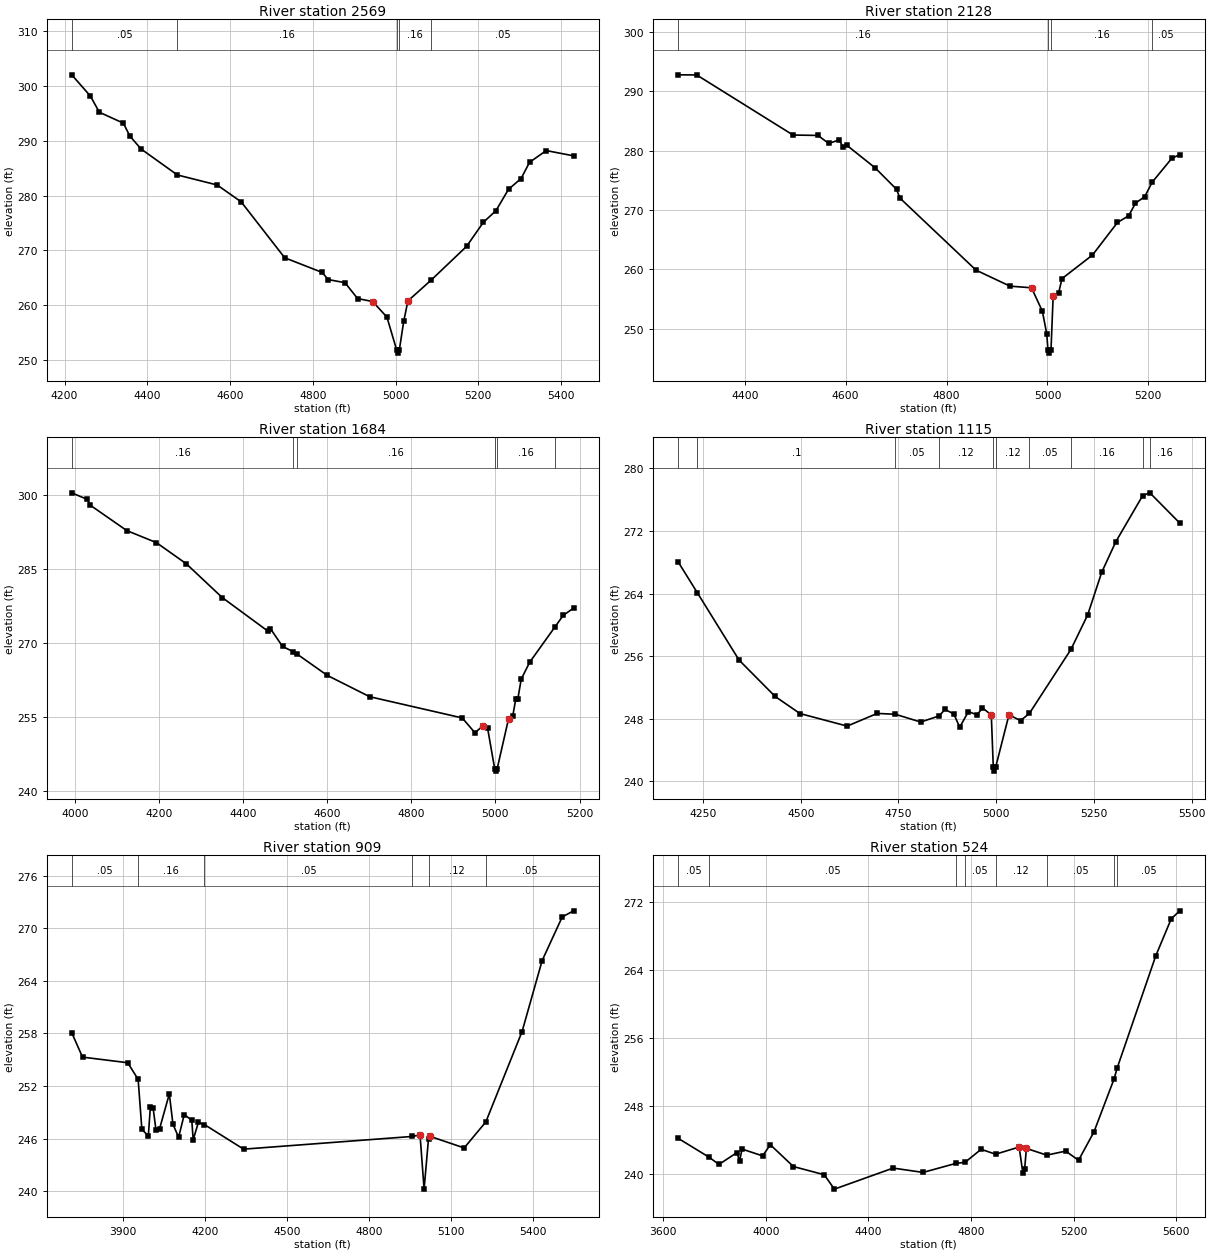
Type RM Length L Ch R = 1 ,2569    ,441,441,441
BEGIN DESCRIPTION:
UNT 04839 IN BUCR 2.0
END DESCRIPTION:
XS GIS Cut Line= 3
      3675219.19     10533782.05       3674950.1     10533339.35
      3674264.49     10533226.53
#Sta/Elev= 30
  4217.5  302.07  4262.7  298.18  4284.1  295.24  4342.2  293.25  4357.7  290.92
  4384.9  288.54  4472.7  283.79  4568.9  281.96    4627  278.88  4732.2  268.67
  4822.5     266  4837.4  264.69  4877.9  264.12  4908.3  261.23  4944.9  260.67
  4979.3  257.83  5003.1  251.76  5005.8  251.26  5009.1  251.76  5019.8  257.04
    5030  260.79  5086.7  264.63  5171.8  270.75  5212.4  275.15  5242.8  277.27
  5273.2  281.17  5303.6  283.14  5323.9  286.09  5364.4  288.24  5430.4  287.28
#Mann= 5 ,-1 , 0
  4217.5     .05       0  4472.7     .16       0  5003.1     .07       0
  5009.1     .16       0  5086.7     .05       0
Bank Sta=4944.9,5030
XS Rating Curve= 0 ,0
Exp/Cntr=0.3,0.1

Type RM Length L Ch R = 1 ,2128    ,444,444,444
BEGIN DESCRIPTION:
Mapping XS c2619062
END DESCRIPTION:
XS GIS Cut Line= 3
      3675453.57      10533408.8      3675045.58     10533000.81
      3674654.91     10532853.22
#Sta/Elev= 30
  4267.6  292.77  4304.8  292.75  4495.7  282.63  4545.2  282.56  4566.4  281.21
  4587.6  281.82  4594.7  280.54  4601.8  280.94  4658.3  277.11  4700.8  273.49
  4707.8  271.99  4858.4  259.87  4925.8  257.17  4968.4   256.9  4989.9  252.95
  4998.6  249.14    5001  246.39  5003.7  245.89    5007  246.39  5011.3  255.53
    5022  255.97  5028.8  258.44  5089.2  262.41  5138.8   267.9    5161  269.03
  5174.4  271.14    5193  272.27  5207.3  274.65  5246.5  278.71  5262.2  279.32
#Mann= 4 ,-1 , 0
  4267.6     .16       0    5001     .07       0    5007     .16       0
  5207.3     .05       0
Bank Sta=4968.4,5011.3
XS Rating Curve= 0 ,0
Exp/Cntr=0.3,0.1

Type RM Length L Ch R = 1 ,1684    ,569,569,569
BEGIN DESCRIPTION:
Mapping XS e93b896c
END DESCRIPTION:
XS GIS Cut Line= 3
      3675844.19      10532957.4      3675314.68      10532558.1
      3674785.15     10532540.74
#Sta/Elev= 30
  3992.9  300.43  4029.9  299.09  4036.2  297.96  4123.5  292.78  4194.3  290.32
  4265.1  286.04  4350.5  279.19  4458.7   272.4    4465   272.9  4494.1  269.25
  4518.9  268.22  4528.5  267.71  4600.3  263.39  4701.2  259.06  4921.3  254.75
  4951.3  251.75  4971.3  253.21  4981.3  252.79  4998.3  244.46  5001.1  243.96
  5004.3  244.46  5031.4  254.61  5041.4  255.18  5048.3  258.51  5053.3  258.57
  5061.4  262.61  5081.4  266.03  5140.9  273.13  5161.4  275.57  5185.9  277.04
#Mann= 6 ,-1 , 0
  3992.9     .16       0  4518.9     .05       0  4528.5     .16       0
  4998.3     .07       0  5004.3     .16       0  5140.9     .05       0
Bank Sta=4971.3,5031.4
XS Rating Curve= 0 ,0
Exp/Cntr=0.3,0.1

Type RM Length L Ch R = 1 ,1115    ,206,206,206
BEGIN DESCRIPTION:
Mapping XS 7aa034db
END DESCRIPTION:
XS GIS Cut Line= 4
      3675728.91     10532271.08       3675416.4     10531906.48
      3674963.27     10532125.23      3674796.62     10532375.21
#Sta/Elev= 30
  4185.8  268.08  4235.1  264.13  4342.2   255.5  4434.4  250.86  4498.1  248.67
  4618.8  247.07  4695.7  248.69  4742.1  248.58  4806.8  247.59    4854  248.37
    4869   249.2  4891.6  248.62  4906.7  246.92  4928.9  248.93  4951.1   248.5
  4964.9  249.39  4987.5   248.5  4992.6  241.82  4995.3  241.32  4998.6  241.82
  5032.7  248.51  5062.2  247.77  5084.8  248.68  5191.3  256.87    5234  261.27
  5270.1  266.73  5306.1  270.62  5374.8  276.51  5393.1  276.86  5469.6     273
#Mann= 10 ,-1 , 0
  4185.8     .05       0  4235.1      .1       0  4742.1     .05       0
    4854     .12       0  4992.6     .07       0  4998.6     .12       0
  5084.8     .05       0  5191.3     .16       0  5374.8     .05       0
  5393.1     .16       0
Bank Sta=4987.5,5032.7
XS Rating Curve= 0 ,0
Exp/Cntr=0.3,0.1

Type RM Length L Ch R = 1 ,909     ,385,385,385
BEGIN DESCRIPTION:
Mapping XS 1fabb5bd
END DESCRIPTION:
XS GIS Cut Line= 4
      3676237.74     10531843.49      3675434.78      10531639.5
      3674840.16     10531978.04      3674753.51     10532285.66
#Sta/Elev= 30
  3714.4  258.07  3753.7  255.29  3918.8  254.65  3956.8  252.75  3970.4  247.06
    3994  246.28  4001.4  249.61  4011.7  249.45    4022  246.93  4034.9   247.1
  4070.7   251.1  4083.9  247.63  4104.5  246.15  4125.2  248.74  4152.6  248.08
  4157.8  245.87  4176.8  247.84  4198.7   247.6  4341.9  244.79    4958  246.24
  4986.1  246.42  5000.9  240.23    5017  245.98  5022.8  246.25  5147.2  244.93
  5226.2  247.89  5358.7  258.21    5432  266.31  5505.2  271.28  5546.7  271.98
#Mann= 6 ,-1 , 0
  3714.4     .05       0  3956.8     .16       0  4198.7     .05       0
    4958     .12       0    5017     .12       0  5226.2     .05       0
Bank Sta=4986.1,5022.8
XS Rating Curve= 0 ,0
Exp/Cntr=0.3,0.1

Type RM Length L Ch R = 1 ,524     ,315,315,315
BEGIN DESCRIPTION:
Mapping XS 76b82b48
END DESCRIPTION:
XS GIS Cut Line= 4
      3675929.61     10531426.83      3675005.09      10531392.1
      3674640.51     10531765.37      3674688.25     10532273.18
#Sta/Elev= 30
  3657.2  244.25  3777.3  242.04  3817.3  241.17  3887.4  242.56  3897.4  241.59
  3907.4  242.97  3987.4  242.17  4017.5  243.48  4107.5  240.92  4227.6  239.96
  4267.4  238.27  4496.5  240.74  4613.2  240.23  4742.2   241.3  4776.6  241.41
  4839.5  242.94  4896.1  242.37  4987.9  243.21  5002.1  240.21  5009.2  240.61
  5016.2  243.05  5095.2  242.26  5169.3  242.73  5219.5  241.66  5279.7  244.99
  5358.7  251.25  5370.1  252.48  5520.8  265.66  5581.1     270  5614.2  270.93
#Mann= 8 ,-1 , 0
  3657.2     .05       0  3777.3     .05       0  4742.2     .07       0
  4776.6     .05       0  4896.1     .12       0  5095.2     .05       0
  5358.7     .12       0  5370.1     .05       0
Bank Sta=4987.9,5016.2
XS Rating Curve= 0 ,0
Exp/Cntr=0.3,0.1

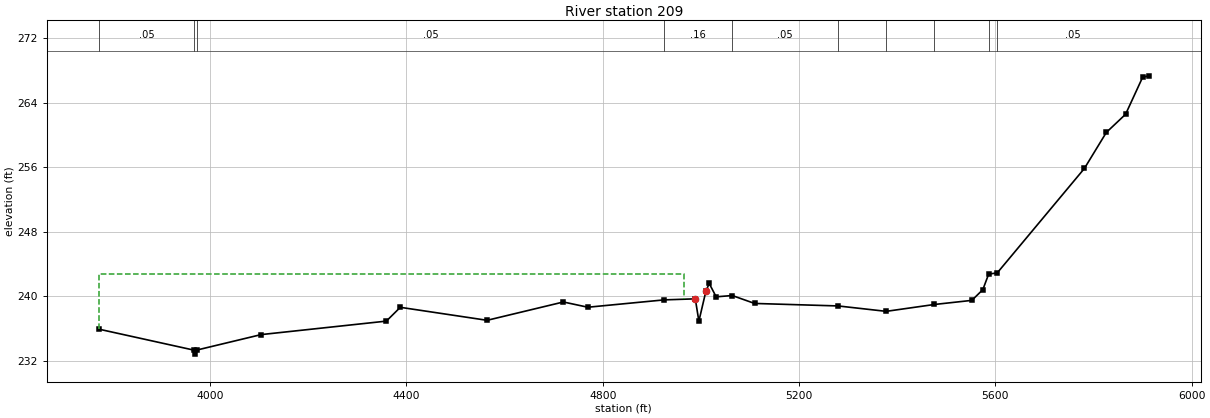
Type RM Length L Ch R = 1 ,209     ,0,0,0
BEGIN DESCRIPTION:
UNT 04839 IN BUCR 1.0
END DESCRIPTION:
XS GIS Cut Line= 4
      3675421.77     10530615.18      3674424.61     10531535.19
      3674401.79     10531886.89      3674593.47     10532271.05
#Sta/Elev= 30
  3773.6  235.94  3966.6  233.35  3969.3  232.85  3972.6  233.35    4104  235.27
  4359.1  236.94  4387.5  238.65  4564.4  237.04  4719.8  239.31  4769.7  238.66
    4925  239.57  4988.6   239.7  4995.9  236.93  5010.1  240.62  5016.9  241.61
  5031.1  239.95  5063.9  240.11  5109.4  239.13  5279.5  238.82  5377.6  238.15
  5475.6     239  5552.1  239.51  5574.5  240.84  5586.4  242.77  5603.8  242.91
  5781.4  255.85  5826.2  260.32  5865.4  262.57    5900  267.14  5912.1  267.33
#Mann= 10 ,-1 , 0
  3773.6     .05       0  3966.6     .07       0  3972.6     .05       0
    4925     .16       0  5063.9     .05       0  5279.5     .07       0
  5377.6     .12       0  5475.6     .05       0  5586.4     .07       0
  5603.8     .05       0
#XS Ineff= 1 ,-1
 3723.01 4965.91 242.771
Permanent Ineff=
       F
Bank Sta=4988.6,5010.1
XS Rating Curve= 0 ,0
Exp/Cntr=0.3,0.1

Chan Stop Cuts=-1
Use User Specified Reach Order=0
Composite Channel Slope=5