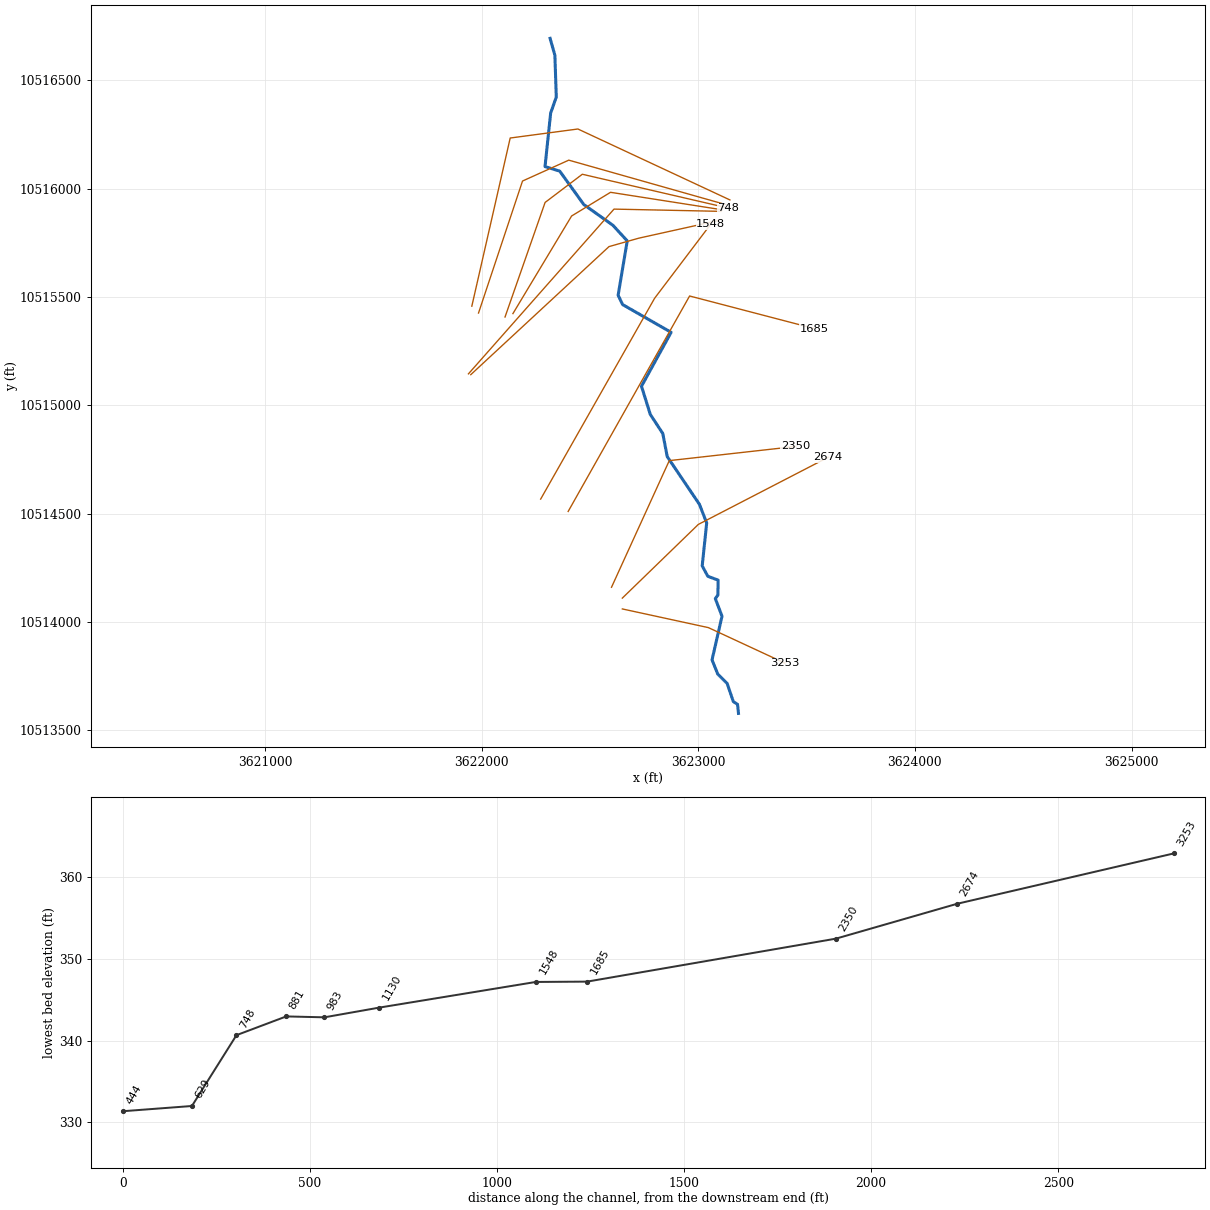
--- UNT 052 IN BUCR.prj (project) ---

Proj Title=UNT 052 IN BUCR Base Level Engineering
Current Plan=p01
Default Exp/Contr=0.3,0.1
English Units
Geom File=g01
Flow File=f01
Plan File=p01
BEGIN DESCRIPTION:
UNT 052 IN BUCR
END DESCRIPTION:

--- UNT 052 IN BUCR.p01 (plan) ---

Plan Title=Multiple Run
Short Identifier=Multiple
Geom File=g01
Flow File=f01
Subcritical Flow
K Sum by GR= 0
Std Step Tol= 0.01
Critical Tol= 0.01
Num of Std Step Trials= 20
Max Error Tol= 0.3
Flow Tol Ratio= 0.001
Split Flow NTrial= 30
Split Flow Tol= 0.02
Split Flow Ratio= 0.02
Log Output Level= 0
Friction Slope Method= 1
Unsteady Friction Slope Method= 2
Unsteady Bridges Friction Slope Method= 1
Parabolic Critical Depth
Global Vel Dist=  1 , 1 , 1
Global Log Level= 0
CheckData=True
Encroach Param= -1, 0, 0, 0
BEGIN DESCRIPTION:
Multiple Run
END DESCRIPTION:

--- UNT 052 IN BUCR.f01 (steady flow) ---

Flow Title=Multiple
Number of Profiles=7
Profile Names=10-year,25-year,50-year,1pct_min,100-year,1pct_plu,500-year
River Rch & RM= UNT 052 IN BUCR,Reach-1,3253
     636     850    1023     901    1218    1648    1720
Boundary for River Rch & Prof#=UNT 052 IN BUCR,Reach-1,1
Up Type=0
Dn Type=3
Dn Slope=0.005
Boundary for River Rch & Prof#=UNT 052 IN BUCR,Reach-1,2
Up Type=0
Dn Type=3
Dn Slope=0.005
Boundary for River Rch & Prof#=UNT 052 IN BUCR,Reach-1,3
Up Type=0
Dn Type=3
Dn Slope=0.005
Boundary for River Rch & Prof#=UNT 052 IN BUCR,Reach-1,4
Up Type=0
Dn Type=3
Dn Slope=0.005
Boundary for River Rch & Prof#=UNT 052 IN BUCR,Reach-1,5
Up Type=0
Dn Type=3
Dn Slope=0.005
Boundary for River Rch & Prof#=UNT 052 IN BUCR,Reach-1,6
Up Type=0
Dn Type=3
Dn Slope=0.005
Boundary for River Rch & Prof#=UNT 052 IN BUCR,Reach-1,7
Up Type=0
Dn Type=3
Dn Slope=0.005

--- UNT 052 IN BUCR.g01 (geometry) ---

Geom Title=Existing Conditions

River Reach=UNT 052 IN BUCR,Reach-1
Reach XY= 30
      3623185.75     10513578.12      3623181.32     10513619.70
      3623161.79     10513632.72      3623133.58     10513716.06
      3623090.18     10513759.46      3623063.70     10513825.00
      3623109.71     10514026.82      3623078.75     10514107.97
      3623090.61     10514124.04      3623091.91     10514193.05
      3623044.17     10514210.85      3623018.25     10514259.00
      3623039.00     10514457.00      3623005.50     10514543.00
      3622857.00     10514763.00      3622836.25     10514870.00
      3622778.75     10514958.00      3622738.00     10515088.00
      3622874.75     10515337.00      3622651.00     10515465.00
      3622630.25     10515508.00      3622672.25     10515759.00
      3622606.25     10515831.00      3622471.50     10515927.00
      3622360.75     10516081.00      3622292.75     10516102.00
      3622318.75     10516349.00      3622344.75     10516423.00
      3622338.25     10516616.00      3622316.00     10516694.00

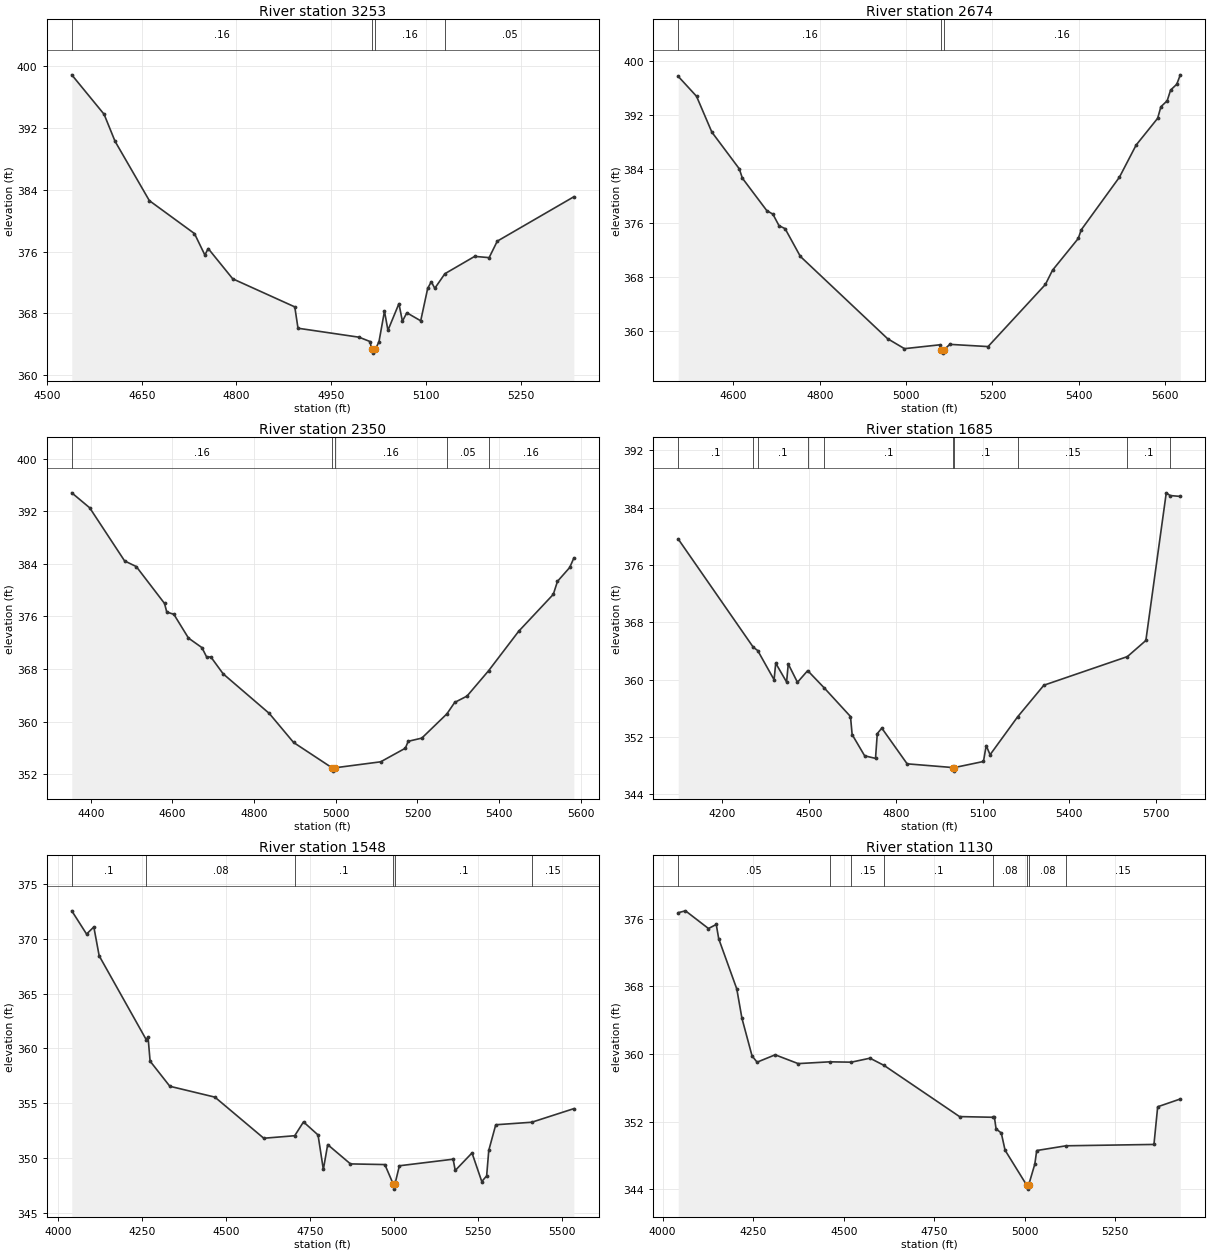
Type RM Length L Ch R = 1,3253,579,579,579
BEGIN DESCRIPTION:
UNT 052 IN BUCR 7.0
END DESCRIPTION:
XS GIS Cut Line= 3
      3622649.62     10514060.19      3623046.86     10513973.95
      3623399.61     10513810.19
#Sta/Elev= 30
  4539.1  398.85  4590.3  393.75  4607.7  390.25  4662.0  382.58  4733.5  378.32
  4750.0  375.54  4755.2  376.39  4794.1  372.47  4892.4  368.84  4897.5  366.08
  4994.2  364.92  5011.6  364.36  5014.1  363.36  5016.8  362.86  5020.1  363.36
  5025.8  364.34  5034.5  368.29  5040.0  365.81  5057.4  369.26  5062.9  366.98
  5069.9  368.08  5091.9  367.04  5103.0  371.25  5108.7  372.09  5114.2  371.24
  5130.2  373.13  5177.4  375.37  5200.3  375.21  5213.2  377.34  5334.5  383.08
#Mann=4,-1,0
  4539.1    0.16       0  5014.1    0.07       0  5020.1    0.16       0
  5130.2    0.05       0
Bank Sta=5014.1,5020.1
Exp/Cntr=0.3,0.1

Type RM Length L Ch R = 1,2674,324,324,324
BEGIN DESCRIPTION:
UNT 052 IN BUCR 6.0
END DESCRIPTION:
XS GIS Cut Line= 3
      3622649.57     10514110.15      3623000.42     10514450.31
      3623599.57     10514760.17
#Sta/Elev= 30
  4472.0  397.71  4514.4  394.76  4549.9  389.45  4613.4  384.02  4620.6  382.63
  4677.2  377.82  4691.3  377.30  4705.5  375.59  4719.6  375.15  4754.9  371.04
  4957.0  358.85  4996.1  357.37  5079.0  357.95  5081.7  357.21  5084.4  356.71
  5087.7  357.21  5101.2  358.01  5189.8  357.68  5322.6  366.88  5339.1  368.99
  5398.8  373.70  5405.6  374.97  5494.1  382.77  5532.8  387.53  5582.7  391.50
  5590.2  393.21  5604.8  394.10  5612.7  395.68  5627.0  396.55  5635.2  397.94
#Mann=3,-1,0
  4472.0    0.16       0  5081.7    0.07       0  5087.7    0.16       0
Bank Sta=5081.7,5087.7
Exp/Cntr=0.3,0.1

Type RM Length L Ch R = 1,2350,665,665,665
BEGIN DESCRIPTION:
UNT 052 IN BUCR 5.0
END DESCRIPTION:
XS GIS Cut Line= 3
      3622599.62     10514160.21      3622866.31     10514744.79
      3623449.62     10514810.19
#Sta/Elev= 30
  4353.6  394.83  4397.5  392.55  4483.0  384.46  4511.6  383.60  4580.7  377.99
  4586.2  376.69  4603.7  376.32  4639.4  372.71  4672.3  371.26  4683.8  369.84
  4694.3  369.83  4724.4  367.26  4837.2  361.24  4896.7  356.82  4991.1  352.95
  4993.8  352.45  4997.1  352.95  5110.1  353.87  5170.5  355.94  5177.4  356.99
  5210.8  357.48  5272.2  361.17  5291.3  362.91  5321.5  363.88  5374.6  367.76
  5447.9  373.74  5532.8  379.37  5543.0  381.35  5573.0  383.46  5583.1  384.91
#Mann=5,-1,0
  4353.6    0.16       0  4991.1    0.07       0  4997.1    0.16       0
  5272.2    0.05       0  5374.6    0.16       0
Bank Sta=4991.1,4997.1
Exp/Cntr=0.3,0.1

Type RM Length L Ch R = 1,1685,137,137,137
BEGIN DESCRIPTION:
UNT 052 IN BUCR 4.0
END DESCRIPTION:
XS GIS Cut Line= 3
      3622399.61     10514510.19      3622960.13     10515504.70
      3623536.40     10515354.15
#Sta/Elev= 30
  4047.1  379.62  4306.7  364.51  4322.0  364.05  4378.7  359.97  4384.4  362.28
  4422.0  359.65  4427.8  362.17  4459.6  359.61  4495.0  361.24  4552.4  358.82
  4643.1  354.83  4648.8  352.31  4692.1  349.34  4729.7  348.98  4735.8  352.44
  4751.4  353.21  4839.1  348.22  4996.9  347.70  4999.6  347.20  5002.9  347.70
  5103.2  348.55  5112.6  350.77  5126.1  349.49  5221.3  354.78  5312.2  359.20
  5601.2  363.20  5665.1  365.45  5735.7  386.08  5748.8  385.70  5784.3  385.58
#Mann=10,-1,0
  4047.1     0.1       0  4306.7    0.08       0  4322.0     0.1       0
  4495.0    0.08       0  4552.4     0.1       0  4996.9    0.07       0
  5002.9     0.1       0  5221.3    0.15       0  5601.2     0.1       0
  5748.8    0.15       0
Bank Sta=4996.9,5002.9
Exp/Cntr=0.3,0.1

Type RM Length L Ch R = 1,1548,418,418,418
BEGIN DESCRIPTION:
UNT 052 IN BUCR 3.0
END DESCRIPTION:
XS GIS Cut Line= 3
      3622272.65     10514567.24      3622798.67     10515494.29
      3623058.04     10515836.65
#Sta/Elev= 30
  4040.2  372.54  4084.3  370.42  4105.9  371.07  4121.8  368.44  4261.8  360.80
  4267.4  361.03  4273.5  358.83  4332.3  356.54  4466.5  355.55  4612.1  351.80
  4704.2  352.03  4730.4  353.29  4773.7  352.10  4789.5  348.95  4802.4  351.22
  4870.3  349.46  4972.7  349.40  4997.1  347.66  4999.8  347.16  5003.1  347.66
  5016.0  349.29  5176.1  349.89  5182.3  348.86  5232.3  350.46  5261.4  347.85
  5275.9  348.37  5282.2  350.69  5303.0  353.03  5410.2  353.26  5535.6  354.50
#Mann=6,-1,0
  4040.2     0.1       0  4261.8    0.08       0  4704.2     0.1       0
  4997.1    0.07       0  5003.1     0.1       0  5410.2    0.15       0
Bank Sta=4997.1,5003.1
Exp/Cntr=0.3,0.1

Type RM Length L Ch R = 1,1130,147,147,147
BEGIN DESCRIPTION:
Mapping XS 80b410c6
END DESCRIPTION:
XS GIS Cut Line= 4
      3621950.05     10515141.55      3622588.05     10515732.67
      3622726.07     10515771.73      3623090.65     10515852.46
#Sta/Elev= 30
  4043.0  376.69  4063.0  376.91  4126.5  374.82  4148.0  375.30  4154.8  373.61
  4204.7  367.68  4218.9  364.22  4246.9  359.76  4260.8  359.03  4310.7  359.90
  4374.2  358.86  4461.0  359.07  4521.1  359.03  4572.6  359.50  4611.7  358.64
  4819.9  352.60  4911.3  352.52  4916.2  352.52  4920.8  351.15  4935.2  350.66
  4945.6  348.63  5004.9  344.53  5007.7  344.03  5010.9  344.53  5027.8  346.99
  5033.0  348.59  5114.2  349.15  5356.8  349.31  5367.1  353.76  5429.6  354.68
#Mann=8,-1,0
  4043.0    0.05       0  4461.0    0.08       0  4521.1    0.15       0
  4611.7     0.1       0  4911.3    0.08       0  5004.9    0.07       0
  5010.9    0.08       0  5114.2    0.15       0
Bank Sta=5004.9,5010.9
Exp/Cntr=0.3,0.1

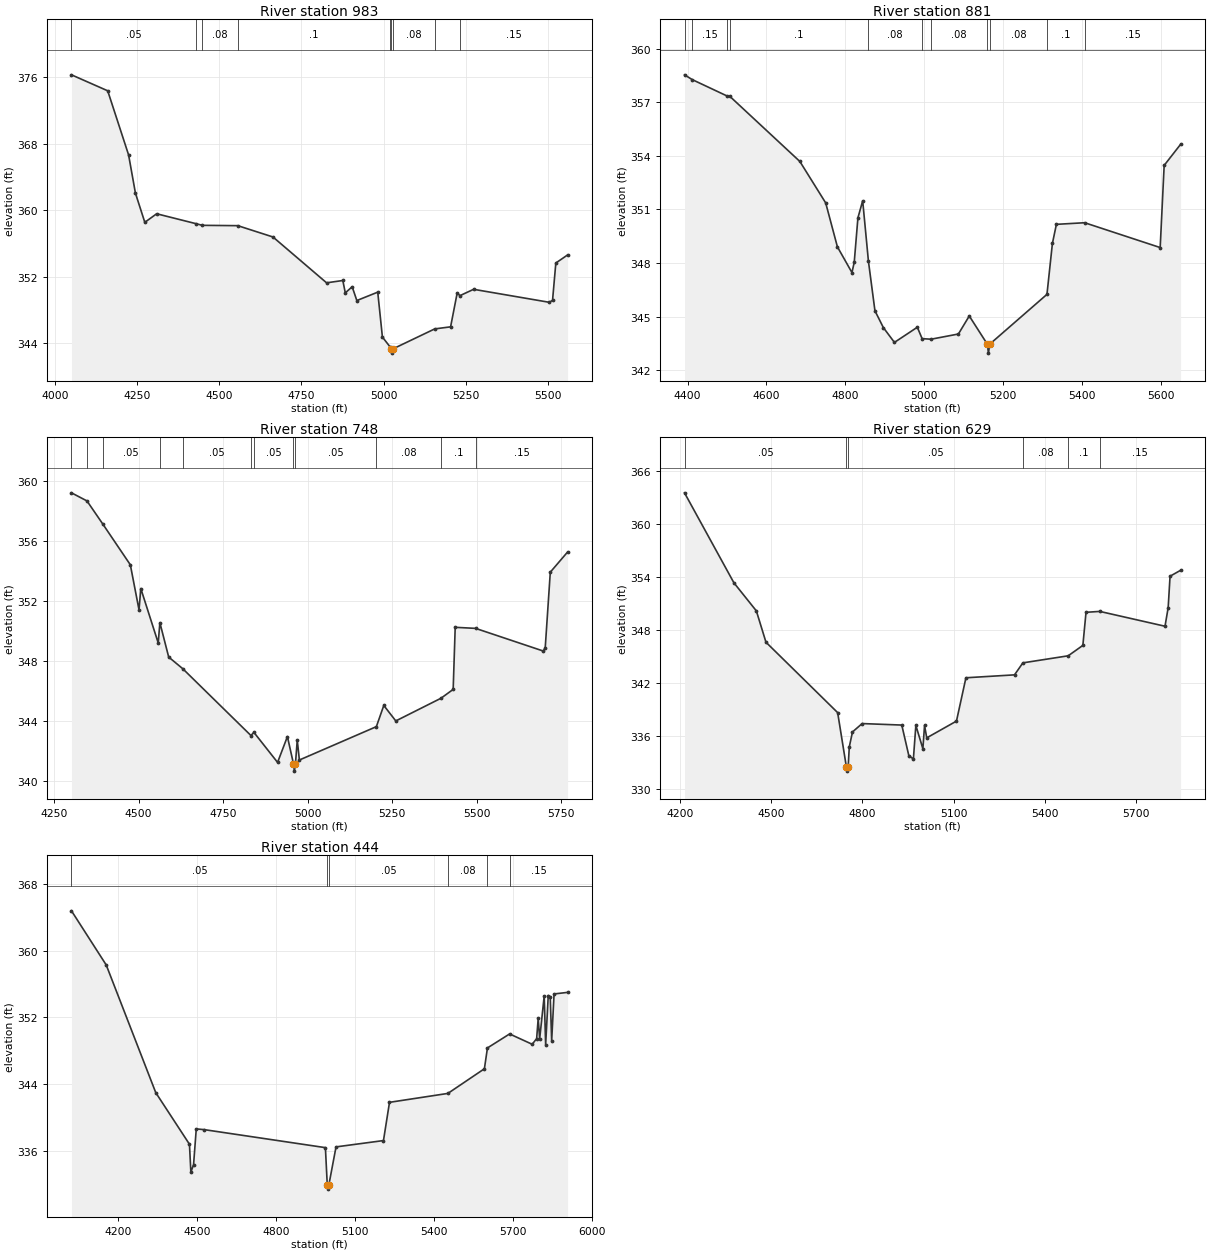
Type RM Length L Ch R = 1,983,102,102,102
BEGIN DESCRIPTION:
UNT 052 IN BUCR 2.0
END DESCRIPTION:
XS GIS Cut Line= 3
      3621939.29     10515145.32      3622611.17     10515905.75
      3623105.33     10515895.34
#Sta/Elev= 30
  4050.4  376.29  4160.6  374.37  4224.1  366.67  4245.0  362.06  4273.5  358.56
  4309.5  359.59  4428.2  358.41  4448.4  358.20  4556.3  358.16  4663.3  356.80
  4826.4  351.29  4875.8  351.57  4883.3  350.08  4904.2  350.82  4918.4  349.16
  4982.0  350.17  4996.2  344.77  5020.3  343.55  5021.7  343.34  5024.4  342.84
  5027.7  343.34  5155.2  345.75  5203.6  346.00  5223.6  350.06  5232.1  349.75
  5273.6  350.51  5503.7  348.95  5513.7  349.18  5523.7  353.67  5559.4  354.64
#Mann=9,-1,0
  4050.4    0.05       0  4428.2    0.15       0  4448.4    0.08       0
  4556.3     0.1       0  5020.3    0.08       0  5021.7    0.07       0
  5027.7    0.08       0  5155.2     0.1       0  5232.1    0.15       0
Bank Sta=5021.7,5027.7
Exp/Cntr=0.3,0.1

Type RM Length L Ch R = 1,881,133,133,133
BEGIN DESCRIPTION:
Mapping XS 200611d7
END DESCRIPTION:
XS GIS Cut Line= 4
      3622144.60     10515423.37      3622415.45     10515873.92
      3622595.14     10515983.29      3623110.80     10515902.55
#Sta/Elev= 30
  4392.3  358.53  4412.1  358.26  4499.8  357.35  4507.0  357.33  4684.8  353.68
  4750.3  351.36  4780.0  348.90  4816.9  347.46  4822.7  348.04  4832.0  350.52
  4844.1  351.48  4858.7  348.09  4875.2  345.32  4896.5  344.38  4924.6  343.55
  4982.7  344.40  4994.8  343.76  5017.7  343.73  5086.8  344.02  5114.4  345.03
  5160.2  343.45  5163.0  342.95  5166.2  343.45  5311.4  346.24  5325.2  349.09
  5335.3  350.16  5407.0  350.25  5598.5  348.86  5608.6  353.46  5650.3  354.64
#Mann=11,-1,0
  4392.3    0.05       0  4412.1    0.15       0  4499.8    0.08       0
  4507.0     0.1       0  4858.7    0.08       0  4994.8     0.1       0
  5017.7    0.08       0  5160.2    0.07       0  5166.2    0.08       0
  5311.4     0.1       0  5407.0    0.15       0
Bank Sta=5160.2,5166.2
Exp/Cntr=0.3,0.1

Type RM Length L Ch R = 1,748,119,119,119
BEGIN DESCRIPTION:
Mapping XS 05ce9994
END DESCRIPTION:
XS GIS Cut Line= 4
      3622108.16     10515407.79      3622293.05     10515936.42
      3622464.93     10516066.62      3623139.41     10515910.37
#Sta/Elev= 30
  4301.4  359.18  4347.3  358.64  4393.9  357.11  4475.6  354.39  4501.3  351.39
  4506.6  352.81  4558.1  349.19  4563.0  350.54  4589.1  348.25  4630.5  347.48
  4832.4  343.03  4841.2  343.24  4911.3  341.24  4940.4  342.96  4958.2  341.16
  4961.0  340.66  4964.2  341.16  4969.5  342.72  4975.8  341.40  5203.6  343.62
  5225.6  345.03  5261.1  344.00  5394.8  345.51  5430.9  346.10  5436.9  350.23
  5497.2  350.16  5697.7  348.65  5703.3  348.87  5718.3  353.90  5769.4  355.24
#Mann=12,-1,0
  4301.4    0.05       0  4347.3    0.15       0  4393.9    0.05       0
  4563.0     0.1       0  4630.5    0.05       0  4832.4    0.08       0
  4841.2    0.05       0  4958.2    0.03       0  4964.2    0.05       0
  5203.6    0.08       0  5394.8     0.1       0  5497.2    0.15       0
Bank Sta=4958.2,4964.2
Exp/Cntr=0.3,0.1

Type RM Length L Ch R = 1,629,185,185,185
BEGIN DESCRIPTION:
Mapping XS 911ede2c
END DESCRIPTION:
XS GIS Cut Line= 4
      3621985.76     10515426.01      3622188.89     10516035.37
      3622402.43     10516131.73      3623128.96     10515926.01
#Sta/Elev= 30
  4215.2  363.55  4377.7  353.35  4451.5  350.17  4483.1  346.62  4718.9  338.64
  4747.5  332.51  4750.3  332.01  4753.5  332.51  4757.2  334.77  4767.7  336.45
  4799.4  337.40  4929.8  337.23  4953.0  333.76  4968.0  333.39  4976.1  337.19
  4999.2  334.55  5004.7  337.19  5011.9  335.78  5109.7  337.68  5140.8  342.59
  5300.6  342.92  5328.1  344.28  5477.2  345.08  5525.4  346.26  5535.8  350.01
  5581.1  350.11  5795.6  348.43  5806.0  350.54  5812.2  354.10  5846.9  354.77
#Mann=6,-1,0
  4215.2    0.05       0  4747.5    0.03       0  4753.5    0.05       0
  5328.1    0.08       0  5477.2     0.1       0  5581.1    0.15       0
Bank Sta=4747.5,4753.5
Exp/Cntr=0.3,0.1

Type RM Length L Ch R = 1,444,0,0,0
BEGIN DESCRIPTION:
UNT 052 IN BUCR 1.0
END DESCRIPTION:
XS GIS Cut Line= 4
      3621954.92     10515457.80      3622132.01     10516233.87
      3622444.51     10516275.54      3623146.09     10515948.13
#Sta/Elev= 30
  4022.5  364.78  4154.6  358.28  4342.9  342.95  4470.9  336.76  4476.3  333.42
  4486.5  334.29  4496.8  338.60  4527.5  338.51  4987.6  336.35  4994.7  331.87
  4997.4  331.37  5000.7  331.87  5028.0  336.44  5208.3  337.20  5231.2  341.79
  5453.1  342.86  5591.9  345.82  5603.5  348.32  5687.7  350.00  5773.5  348.76
  5790.5  349.44  5796.4  351.88  5801.9  349.39  5819.2  354.57  5824.7  348.72
  5834.6  354.61  5842.1  354.44  5847.6  349.19  5856.7  354.80  5908.0  354.99
#Mann=6,-1,0
  4022.5    0.05       0  4994.7    0.03       0  5000.7    0.05       0
  5453.1    0.08       0  5603.5     0.1       0  5687.7    0.15       0
Bank Sta=4994.7,5000.7
Exp/Cntr=0.3,0.1

Chan Stop Cuts=-1