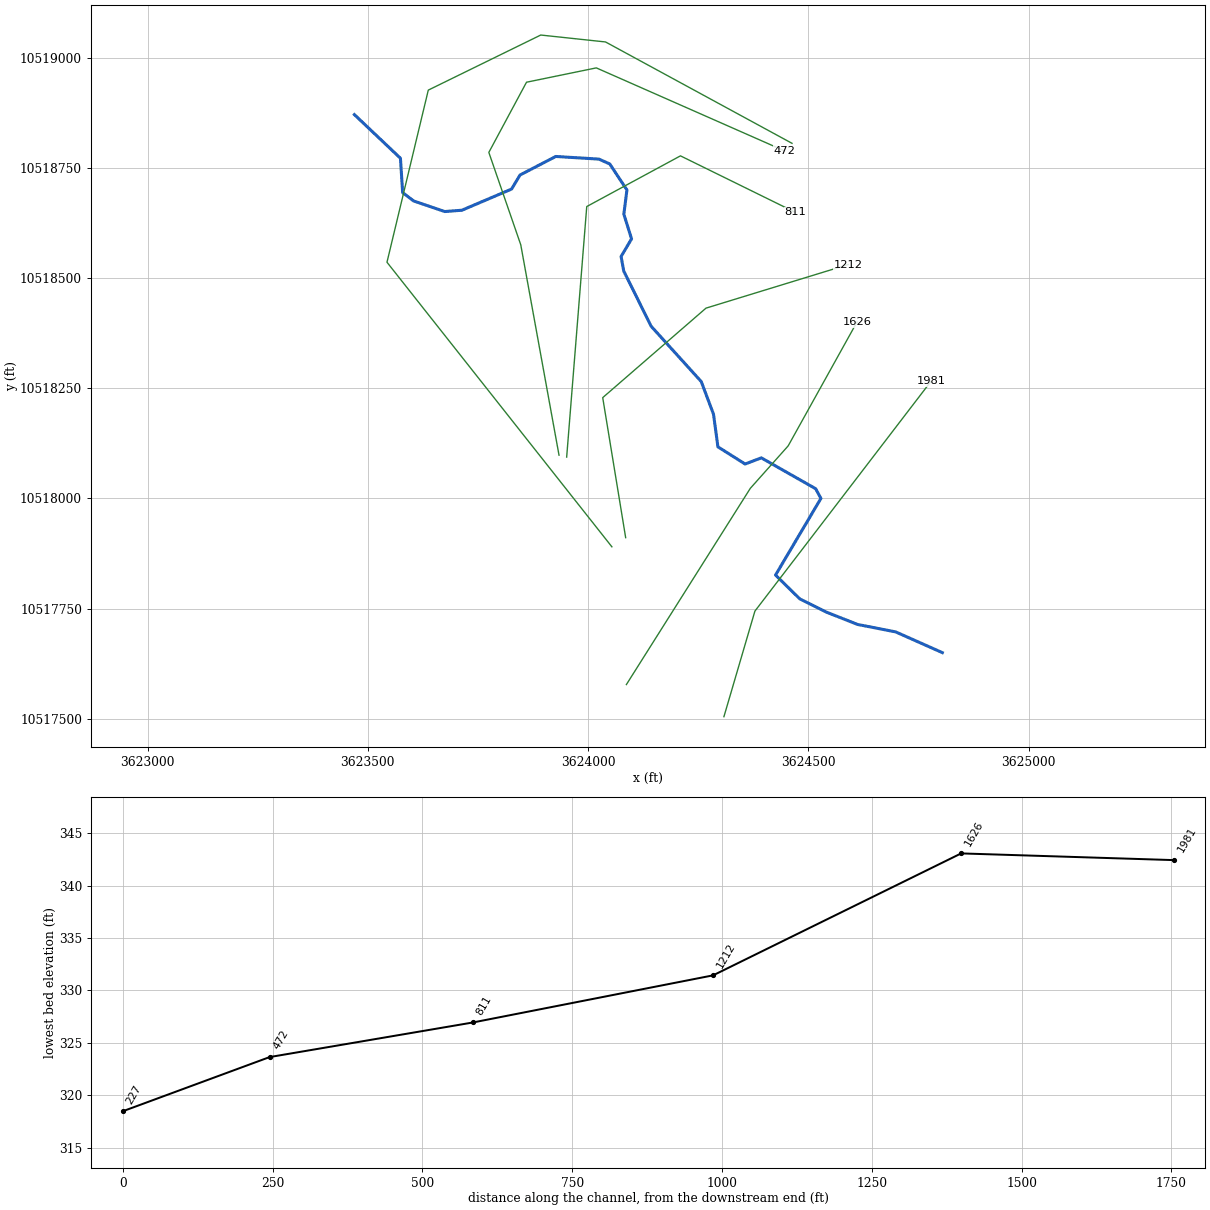
--- UNT 053 IN BUCR.prj (project) ---

Proj Title=UNT 053 IN BUCR Base Level Engineering
Current Plan=p01
Default Exp/Contr=0.3,0.1
English Units
Geom File=g01
Flow File=f01
Plan File=p01
BEGIN DESCRIPTION:
UNT 053 IN BUCR
END DESCRIPTION:

--- UNT 053 IN BUCR.p01 (plan) ---

Plan Title=Multiple Run
Short Identifier=Multiple
Geom File=g01
Flow File=f01
Subcritical Flow
K Sum by GR= 0
Std Step Tol= 0.01
Critical Tol= 0.01
Num of Std Step Trials= 20
Max Error Tol= 0.3
Flow Tol Ratio= 0.001
Split Flow NTrial= 30
Split Flow Tol= 0.02
Split Flow Ratio= 0.02
Log Output Level= 0
Friction Slope Method= 1
Unsteady Friction Slope Method= 2
Unsteady Bridges Friction Slope Method= 1
Parabolic Critical Depth
Global Vel Dist=  1 , 1 , 1
Global Log Level= 0
CheckData=True
Encroach Param= -1, 0, 0, 0
BEGIN DESCRIPTION:
Multiple Run
END DESCRIPTION:

--- UNT 053 IN BUCR.f01 (steady flow) ---

Flow Title=Multiple
Number of Profiles=7
Profile Names=10-year,25-year,50-year,1pct_min,100-year,1pct_plu,500-year
River Rch & RM= UNT 053 IN BUCR,Reach-1,1981
     499     658     784     684     925    1251    1282
Boundary for River Rch & Prof#=UNT 053 IN BUCR,Reach-1,1
Up Type=0
Dn Type=3
Dn Slope=0.005
Boundary for River Rch & Prof#=UNT 053 IN BUCR,Reach-1,2
Up Type=0
Dn Type=3
Dn Slope=0.005
Boundary for River Rch & Prof#=UNT 053 IN BUCR,Reach-1,3
Up Type=0
Dn Type=3
Dn Slope=0.005
Boundary for River Rch & Prof#=UNT 053 IN BUCR,Reach-1,4
Up Type=0
Dn Type=3
Dn Slope=0.005
Boundary for River Rch & Prof#=UNT 053 IN BUCR,Reach-1,5
Up Type=0
Dn Type=3
Dn Slope=0.005
Boundary for River Rch & Prof#=UNT 053 IN BUCR,Reach-1,6
Up Type=0
Dn Type=3
Dn Slope=0.005
Boundary for River Rch & Prof#=UNT 053 IN BUCR,Reach-1,7
Up Type=0
Dn Type=3
Dn Slope=0.005

--- UNT 053 IN BUCR.g01 (geometry) ---

Geom Title=Existing Conditions

River Reach=UNT 053 IN BUCR,Reach-1
Reach XY= 30
      3624803.75     10517650.00      3624698.00     10517697.00
      3624611.25     10517714.00      3624540.50     10517742.00
      3624480.25     10517772.00      3624425.25     10517826.00
      3624528.25     10518000.00      3624516.25     10518022.00
      3624393.00     10518092.00      3624356.25     10518078.00
      3624294.50     10518117.00      3624284.50     10518191.00
      3624256.75     10518265.00      3624142.93     10518390.73
      3624080.75     10518516.00      3624074.75     10518549.00
      3624098.50     10518589.00      3624081.00     10518645.00
      3624088.00     10518700.00      3624049.00     10518759.00
      3624024.50     10518770.00      3623926.50     10518776.00
      3623845.50     10518734.00      3623826.25     10518702.00
      3623713.50     10518654.00      3623674.50     10518651.00
      3623604.00     10518675.00      3623579.00     10518694.00
      3623574.00     10518772.00      3623469.50     10518871.00

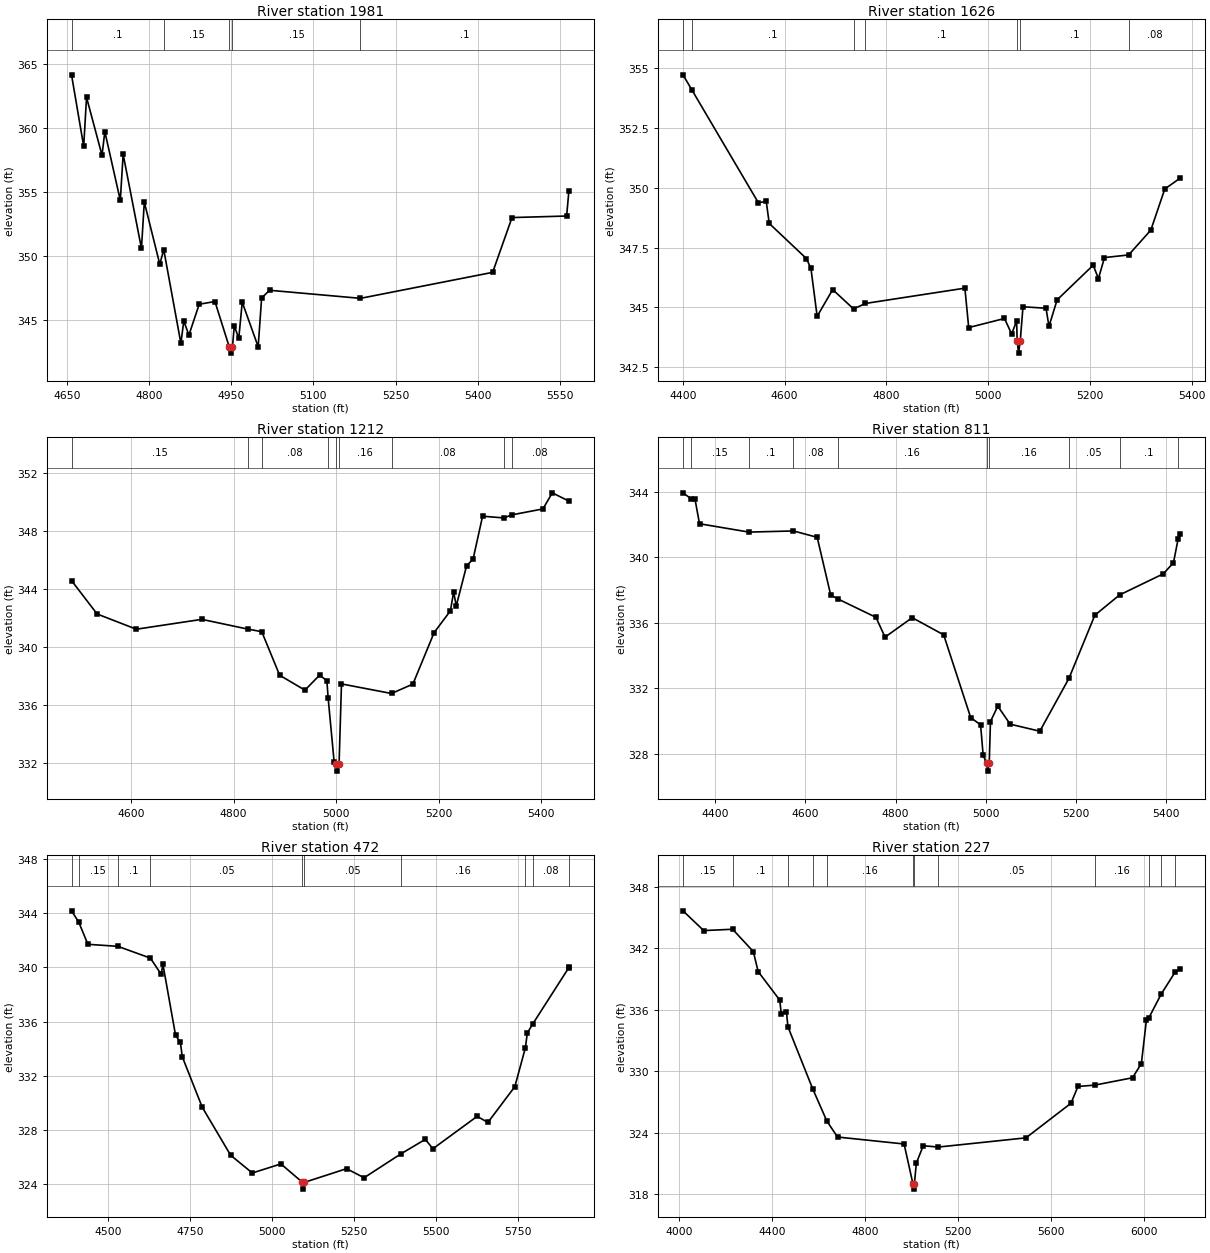
Type RM Length L Ch R = 1,1981,355,355,355
BEGIN DESCRIPTION:
UNT 053 IN BUCR 3.0
END DESCRIPTION:
XS GIS Cut Line= 4
      3624308.13     10517504.64      3624378.44     10517744.21
      3624532.08     10517944.73      3624778.52     10518266.39
#Sta/Elev= 30
  4658.6  364.18  4680.8  358.59  4686.0  362.42  4714.2  357.90  4719.4  359.74
  4747.6  354.37  4752.8  357.97  4786.2  350.62  4791.4  354.24  4819.6  349.39
  4826.9  350.52  4858.2  343.20  4863.4  344.95  4872.8  343.85  4891.6  346.26
  4920.3  346.47  4946.3  342.94  4949.0  342.44  4952.3  342.94  4955.6  344.57
  4963.8  343.60  4970.1  346.42  4999.2  342.94  5005.5  346.75  5020.0  347.35
  5185.9  346.72  5427.1  348.75  5462.4  353.03  5562.1  353.15  5566.1  355.07
#Mann=5,-1,0
  4658.6     0.1       0  4826.9    0.15       0  4946.3    0.07       0
  4952.3    0.15       0  5185.9     0.1       0
Bank Sta=4946.3,4952.3
Exp/Cntr=0.3,0.1

Type RM Length L Ch R = 1,1626,414,414,414
BEGIN DESCRIPTION:
UNT 053 IN BUCR 2.0
END DESCRIPTION:
XS GIS Cut Line= 4
      3624086.78     10517577.56      3624368.02     10518022.85
      3624453.96     10518119.21      3624610.20     10518400.44
#Sta/Elev= 30
  4400.2  354.73  4417.9  354.09  4548.5  349.37  4563.8  349.44  4569.7  348.51
  4642.7  347.04  4651.7  346.63  4663.9  344.62  4694.4  345.74  4735.5  344.93
  4758.9  345.16  4954.3  345.80  4961.8  344.15  5032.1  344.53  5046.3  343.88
  5056.0  344.43  5057.1  343.58  5059.8  343.08  5063.1  343.58  5068.5  345.02
  5113.8  344.96  5119.6  344.20  5135.6  345.31  5206.5  346.76  5216.8  346.20
  5228.7  347.08  5276.2  347.19  5319.8  348.23  5347.2  349.95  5377.7  350.41
#Mann=7,-1,0
  4400.2    0.08       0  4417.9     0.1       0  4735.5    0.15       0
  4758.9     0.1       0  5057.1    0.07       0  5063.1     0.1       0
  5276.2    0.08       0
Bank Sta=5057.1,5063.1
Exp/Cntr=0.3,0.1

Type RM Length L Ch R = 1,1212,401,401,401
BEGIN DESCRIPTION:
Mapping XS 2cc21b5e
END DESCRIPTION:
XS GIS Cut Line= 4
      3624085.14     10517910.93      3624033.05     10518228.66
      3624267.42     10518431.79      3624590.38     10518530.76
#Sta/Elev= 30
  4483.8  344.57  4533.7  342.27  4610.2  341.22  4737.9  341.90  4827.4  341.23
  4854.8  341.05  4889.7  338.05  4939.0  337.02  4967.5  338.05  4981.8  337.68
  4984.3  336.47  4996.0  332.06  4999.6  331.94  5002.4  331.44  5005.6  331.94
  5010.3  337.45  5107.9  336.79  5149.6  337.44  5191.0  340.99  5222.8  342.49
  5229.0  343.79  5234.2  342.83  5254.2  345.58  5267.0  346.06  5285.5  349.01
  5326.8  348.89  5342.3  349.10  5403.2  349.51  5421.5  350.62  5453.7  350.05
#Mann=9,-1,0
  4483.8    0.15       0  4827.4     0.1       0  4854.8    0.08       0
  4984.3    0.16       0  4999.6    0.07       0  5005.6    0.16       0
  5107.9    0.08       0  5326.8    0.05       0  5342.3    0.08       0
Bank Sta=4999.6,5005.6
Exp/Cntr=0.3,0.1

Type RM Length L Ch R = 1,811,339,339,339
BEGIN DESCRIPTION:
Mapping XS 87acddab
END DESCRIPTION:
XS GIS Cut Line= 4
      3623951.24     10518093.73      3623996.82     10518662.36
      3624209.49     10518777.38      3624469.89     10518649.35
#Sta/Elev= 30
  4328.8  343.95  4347.2  343.58  4355.3  343.58  4365.4  342.06  4475.0  341.55
  4573.7  341.62  4626.3  341.23  4656.3  337.70  4672.5  337.46  4756.6  336.34
  4776.7  335.13  4836.9  336.32  4906.7  335.27  4966.6  330.21  4988.5  329.77
  4994.2  327.91  5001.7  327.44  5004.4  326.94  5007.7  327.44  5010.4  329.97
  5026.6  330.91  5054.1  329.81  5119.8  329.38  5184.4  332.61  5241.8  336.47
  5296.7  337.71  5393.6  339.00  5416.1  339.68  5426.2  341.10  5431.2  341.41
#Mann=10,-1,0
  4328.8     0.1       0  4347.2    0.15       0  4475.0     0.1       0
  4573.7    0.08       0  4672.5    0.16       0  5001.7    0.07       0
  5007.7    0.16       0  5184.4    0.05       0  5296.7     0.1       0
  5426.2    0.08       0
Bank Sta=5001.7,5007.7
Exp/Cntr=0.3,0.1

Type RM Length L Ch R = 1,472,245,245,245
BEGIN DESCRIPTION:
Mapping XS 1dacc668
END DESCRIPTION:
XS GIS Cut Line= 6
      3623933.89     10518098.11      3623847.08     10518575.55
      3623774.61     10518785.19      3623860.10     10518944.48
      3624018.52     10518977.03      3624445.37     10518788.82
#Sta/Elev= 30
  4389.5  344.17  4411.6  343.33  4439.4  341.70  4531.0  341.55  4630.0  340.68
  4663.0  339.48  4668.0  340.24  4706.7  334.98  4721.4  334.47  4727.0  333.41
  4788.0  329.68  4874.6  326.14  4940.7  324.83  5027.8  325.50  5093.6  324.14
  5096.3  323.64  5099.6  324.14  5228.1  325.15  5281.4  324.48  5394.2  326.25
  5468.0  327.31  5491.3  326.62  5626.1  329.01  5658.9  328.56  5741.0  331.20
  5773.1  334.06  5779.1  335.16  5795.2  335.81  5905.1  339.96  5905.6  340.03
#Mann=10,-1,0
  4389.5     0.1       0  4411.6    0.15       0  4531.0     0.1       0
  4630.0    0.05       0  5093.6    0.03       0  5099.6    0.05       0
  5394.2    0.16       0  5773.1    0.05       0  5795.2    0.08       0
  5905.1    0.15       0
Bank Sta=5093.6,5099.6
Exp/Cntr=0.3,0.1

Type RM Length L Ch R = 1,227,0,0,0
BEGIN DESCRIPTION:
UNT 053 IN BUCR 1.0
END DESCRIPTION:
XS GIS Cut Line= 6
      3624053.86     10517890.14      3623543.46     10518535.95
      3623637.21     10518926.58      3623892.42     10519051.58
      3624039.46     10519035.87      3624462.66     10518805.83
#Sta/Elev= 30
  4015.9  345.66  4105.1  343.73  4229.3  343.86  4318.3  341.68  4339.1  339.73
  4432.1  336.93  4438.5  335.58  4461.0  335.75  4467.1  334.34  4573.5  328.28
  4634.8  325.11  4680.5  323.56  4966.8  322.88  5004.9  318.97  5007.7  318.47
  5010.9  318.97  5019.4  321.01  5049.1  322.71  5113.8  322.58  5490.8  323.48
  5684.4  326.86  5714.5  328.50  5786.3  328.63  5949.1  329.35  5987.2  330.74
  6009.0  335.02  6018.1  335.15  6072.8  337.54  6133.1  339.70  6154.5  339.97
#Mann=12,-1,0
  4015.9    0.15       0  4229.3     0.1       0  4467.1    0.07       0
  4573.5    0.05       0  4634.8    0.16       0  5004.9    0.07       0
  5010.9    0.16       0  5113.8    0.05       0  5786.3    0.16       0
  6018.1    0.05       0  6072.8    0.08       0  6133.1    0.15       0
Bank Sta=5004.9,5010.9
Exp/Cntr=0.3,0.1

Chan Stop Cuts=-1