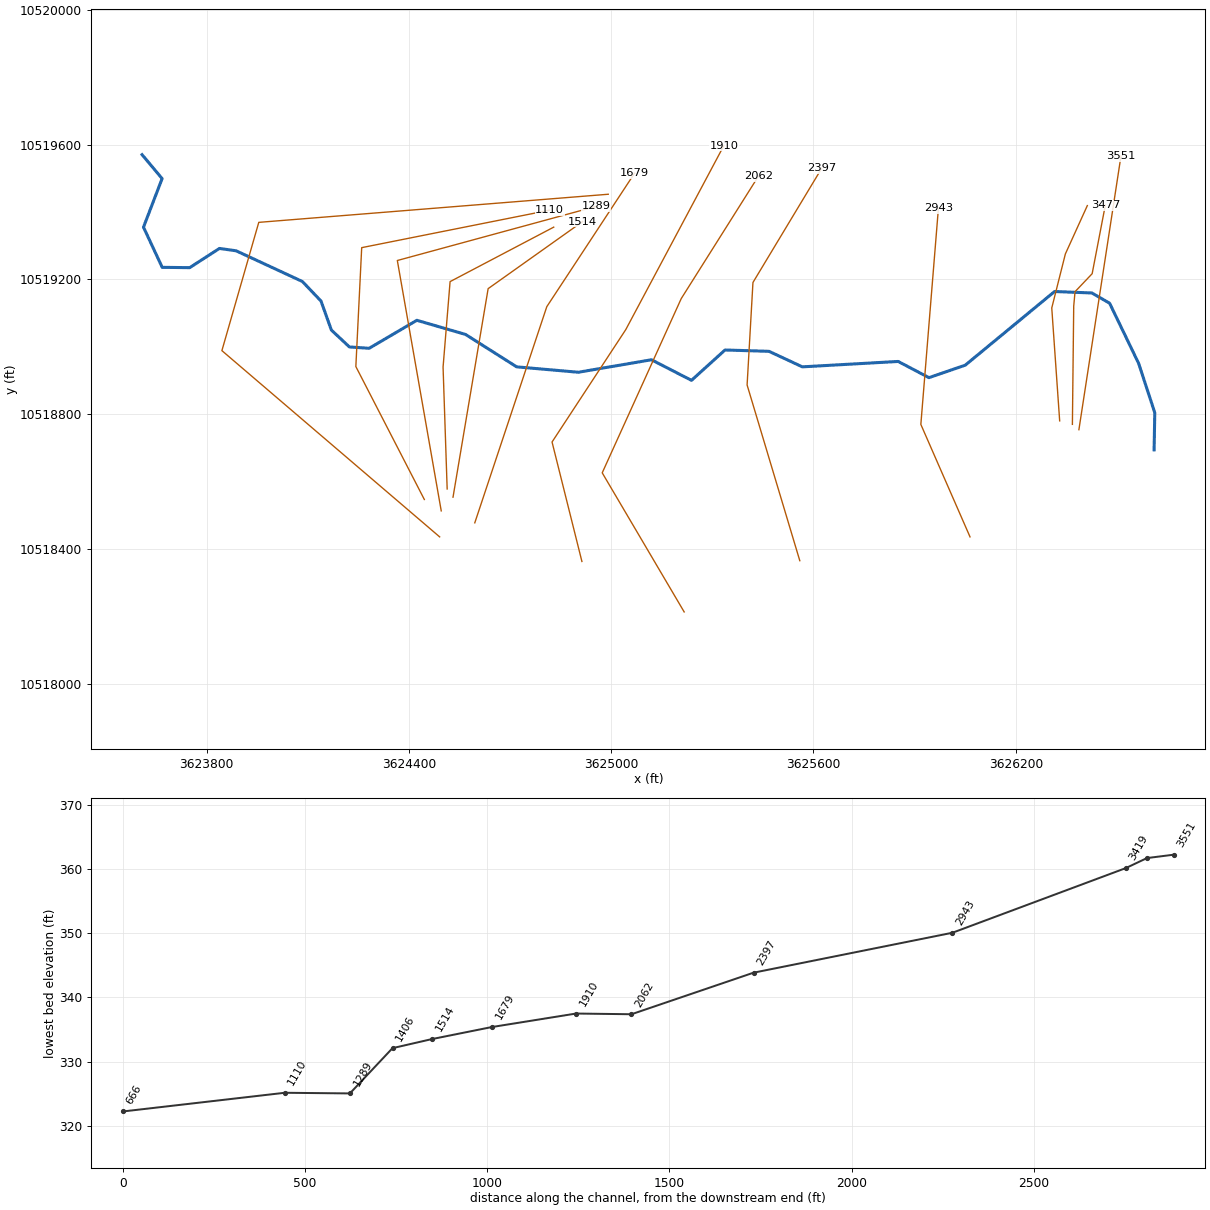
--- UNT 054 IN BUCR.prj (project) ---

Proj Title=UNT 054 IN BUCR Base Level Engineering
Current Plan=p01
Default Exp/Contr=0.3,0.1
English Units
Geom File=g01
Flow File=f01
Plan File=p01
Y Axis Title=Elevation
X Axis Title(PF)=Main Channel Distance
X Axis Title(XS)=Station
BEGIN DESCRIPTION:
UNT 054 IN BUCR
END DESCRIPTION:
DSS Export Rating Curves= 0
DSS Export Rating Curve Sorted= 0
DSS Export Volume Flow Curves= 0
DXF OffsetX= 0
DXF OffsetY= 0
DXF ScaleX= 1
DXF ScaleY= 10

--- UNT 054 IN BUCR.p01 (plan) ---

Plan Title=Multiple Run
Short Identifier=Multiple
Geom File=g01
Flow File=f01
Subcritical Flow
K Sum by GR= 0
Std Step Tol= 0.01
Critical Tol= 0.01
Num of Std Step Trials= 20
Max Error Tol= 0.3
Flow Tol Ratio= 0.001
Split Flow NTrial= 30
Split Flow Tol= 0.02
Split Flow Ratio= 0.02
Log Output Level= 0
Friction Slope Method= 1
Unsteady Friction Slope Method= 2
Unsteady Bridges Friction Slope Method= 1
Parabolic Critical Depth
Global Vel Dist=  1 , 1 , 1
Global Log Level= 0
CheckData=True
Encroach Param= -1, 0, 0, 0
BEGIN DESCRIPTION:
Multiple Run
END DESCRIPTION:

--- UNT 054 IN BUCR.f01 (steady flow) ---

Flow Title=Multiple
Number of Profiles=7
Profile Names=10-year,25-year,50-year,1pct_min,100-year,1pct_plu,500-year
River Rch & RM= UNT 054 IN BUCR,Reach-1,3551
     309     393     458     392     530     717     704
Boundary for River Rch & Prof#=UNT 054 IN BUCR,Reach-1,1
Up Type=0
Dn Type=3
Dn Slope=0.005
Boundary for River Rch & Prof#=UNT 054 IN BUCR,Reach-1,2
Up Type=0
Dn Type=3
Dn Slope=0.005
Boundary for River Rch & Prof#=UNT 054 IN BUCR,Reach-1,3
Up Type=0
Dn Type=3
Dn Slope=0.005
Boundary for River Rch & Prof#=UNT 054 IN BUCR,Reach-1,4
Up Type=0
Dn Type=3
Dn Slope=0.005
Boundary for River Rch & Prof#=UNT 054 IN BUCR,Reach-1,5
Up Type=0
Dn Type=3
Dn Slope=0.005
Boundary for River Rch & Prof#=UNT 054 IN BUCR,Reach-1,6
Up Type=0
Dn Type=3
Dn Slope=0.005
Boundary for River Rch & Prof#=UNT 054 IN BUCR,Reach-1,7
Up Type=0
Dn Type=3
Dn Slope=0.005

--- UNT 054 IN BUCR.g01 (geometry) ---

Geom Title=Existing Conditions
Program Version=4.10

River Reach=UNT 054 IN BUCR ,Reach-1
Reach XY= 30
      3626610.25       10518695.      3626612.25       10518805.
       3626564.5       10518951.      3626478.28     10519129.59
      3626425.76     10519159.97      3626315.08     10519164.31
      3626050.25       10518946.       3625942.5       10518909.
      3625851.25       10518957.        3625567.       10518941.
      3625468.25       10518987.      3625337.75       10518991.
      3625238.25       10518901.       3625119.5       10518962.
      3624902.75       10518925.      3624719.75       10518941.
      3624568.25       10519037.      3624423.75       10519079.
      3624282.25       10518996.      3624223.75       10519000.
      3624170.25       10519050.       3624139.5       10519136.
      3624084.25       10519194.      3623887.75       10519285.
      3623838.25       10519292.        3623750.       10519235.
       3623668.5       10519236.        3623613.       10519355.
      3623668.25       10519499.      3623608.75       10519570.

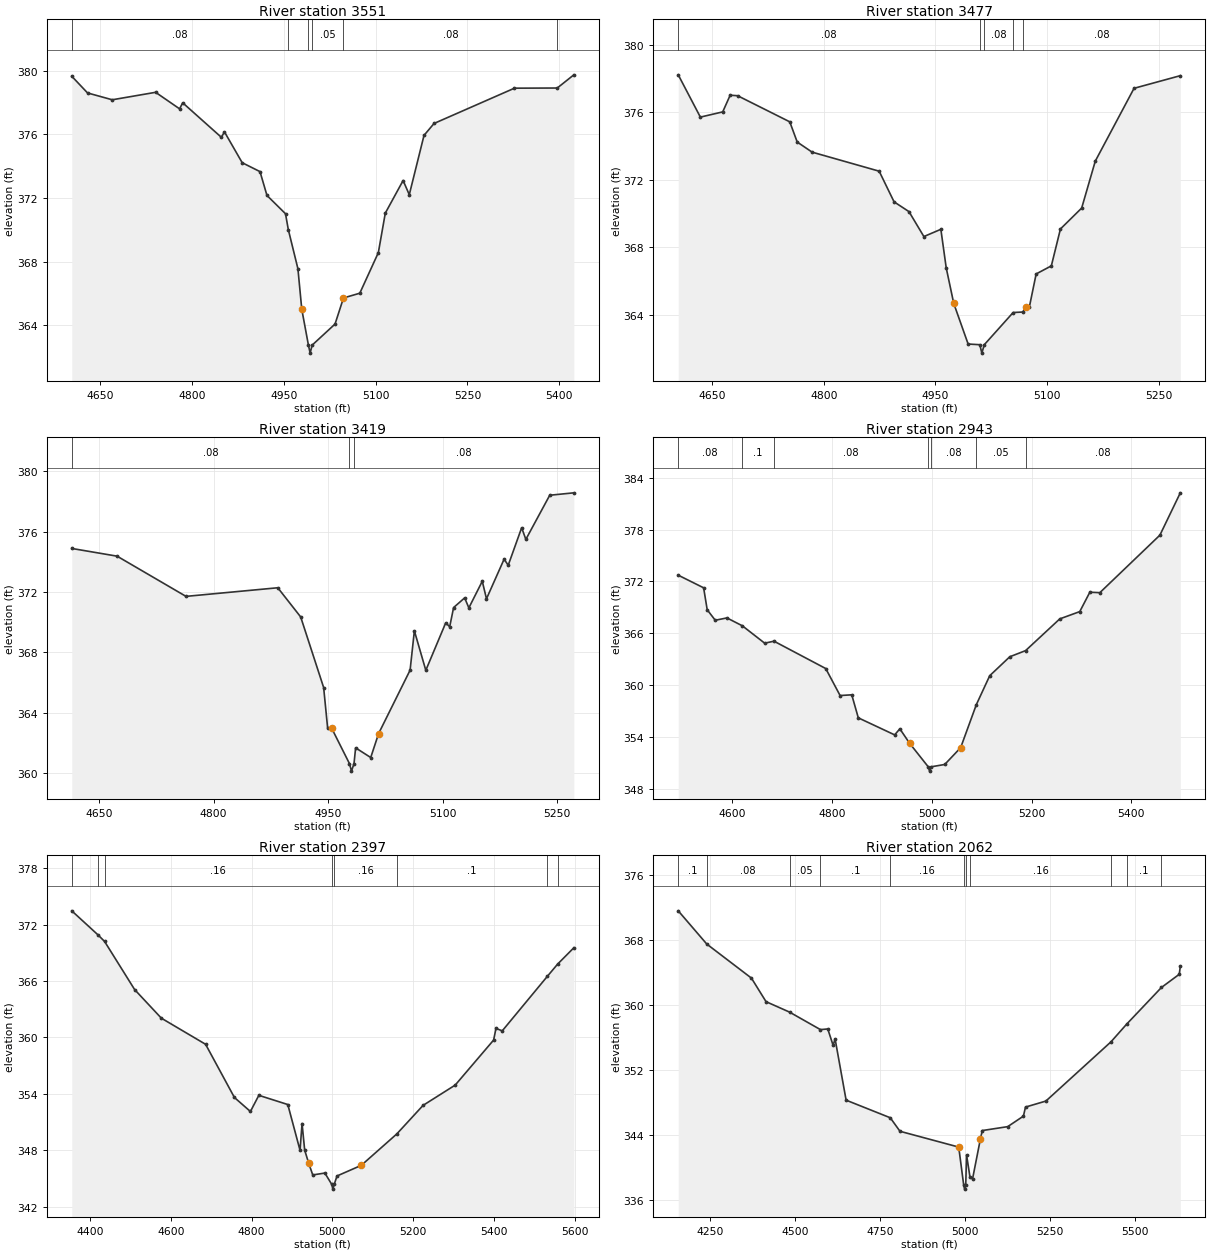
Type RM Length L Ch R = 1 ,3551    ,74,74,74
BEGIN DESCRIPTION:
UNT 054 IN BUCR 6.0
END DESCRIPTION:
XS GIS Cut Line= 2
      3626387.22     10518754.71      3626512.05     10519566.16
#Sta/Elev= 30
  4603.1  379.66  4628.9  378.61  4669.3  378.18  4740.2  378.65  4779.4  377.61
  4784.5  377.99  4847.7  375.82  4852.8  376.16  4881.8  374.22  4910.9  373.66
  4922.3  372.16  4952.6  371.01  4957.2  370.01  4972.9  367.55  4979.2     365
  4990.1  362.74  4992.9  362.24  4996.1  362.74  5033.6  364.07  5047.4  365.71
  5074.1  366.01  5104.4  368.56  5115.8  371.05  5144.9   373.1    5155  372.21
  5179.1  375.94  5195.5  376.69    5327  378.91    5397  378.92  5424.1  379.75
#Mann= 6 ,-1 , 0
  4603.1     .08       0  4957.2     .05       0  4990.1     .04       0
  4996.1     .05       0  5047.4     .08       0    5397     .05       0
Bank Sta=4979.2,5047.4
XS Rating Curve= 0 ,0
Exp/Cntr=0.3,0.1

Type RM Length L Ch R = 1 ,3477    ,58,58,58
BEGIN DESCRIPTION:
Mapping XS a67f78ff
END DESCRIPTION:
XS GIS Cut Line= 5
      3626367.93      10518770.5      3626371.83     10519120.75
      3626375.74     10519163.72      3626426.52      10519217.1
      3626465.57     10519420.19
#Sta/Elev= 30
  4604.7  378.23  4634.4  375.72  4664.4  376.03  4674.4  377.02  4684.4  376.99
  4754.4  375.44  4764.4  374.24  4784.4  373.64  4874.4  372.51  4894.4  370.69
  4914.4  370.11  4934.4  368.63  4957.2  369.06  4964.4  366.77  4974.5  364.66
  4993.8  362.25  5009.5  362.21  5012.2  361.71  5015.5  362.21  5054.2  364.12
    5067  364.15  5071.8  364.43  5075.9  364.43  5085.1  366.41  5105.5  366.89
  5117.7  369.08  5146.2  370.32  5164.5  373.11  5216.5  377.43  5278.6  378.18
#Mann= 5 ,-1 , 0
  4604.7     .08       0  5009.5     .07       0  5015.5     .08       0
  5054.2     .05       0    5067     .08       0
Bank Sta=4974.5,5071.8
XS Rating Curve= 0 ,0
Exp/Cntr=0.3,0.1

Type RM Length L Ch R = 1 ,3419    ,476,476,476
BEGIN DESCRIPTION:
Mapping XS 023e82b4
END DESCRIPTION:
XS GIS Cut Line= 4
      3626330.17     10518780.89      3626306.73     10519115.54
      3626347.09      10519275.7      3626412.21     10519418.96
#Sta/Elev= 30
  4614.1  374.88  4673.5  374.37  4763.8  371.71  4884.1  372.28  4914.1  370.35
  4944.2  365.68  4949.4  363.01  4954.5  363.01    4978  360.65  4980.7  360.15
    4984  360.65  4986.1  361.69  5005.9  361.05  5016.2  362.63  5057.5  366.83
  5063.1  369.43  5078.1  366.82  5104.2  369.96  5109.4   369.7  5114.5  370.97
    5129  371.61  5134.5  370.95  5152.1  372.71  5157.6  371.55  5180.7  374.17
  5186.1  373.77  5203.7  376.25  5209.2  375.48  5240.5   378.4  5272.1  378.56
#Mann= 3 ,-1 , 0
  4614.1     .08       0    4978     .07       0    4984     .08       0
Bank Sta=4954.5,5016.2
XS Rating Curve= 0 ,0
Exp/Cntr=0.3,0.1

Type RM Length L Ch R = 1 ,2943    ,546,546,546
BEGIN DESCRIPTION:
UNT 054 IN BUCR 5.0
END DESCRIPTION:
XS GIS Cut Line= 3
       3626064.3       10518437.      3625918.46     10518770.33
      3625970.55     10519410.98
#Sta/Elev= 30
  4491.7  372.73  4542.6  371.27  4549.8  368.73  4565.9  367.52  4589.3  367.79
  4620.2  366.88    4665  364.87  4683.7   365.1  4787.4  361.94  4816.2  358.82
  4839.6   358.9  4852.7  356.24  4925.6  354.27    4936  354.97  4955.7  353.29
  4992.9  350.58  4995.6  350.08  4998.9  350.58    5026  350.85  5057.9  352.79
  5089.4  357.77  5116.2  361.11  5156.4   363.3  5188.1  364.01  5256.7  367.68
  5296.7  368.52  5316.9  370.76    5337  370.71  5457.4  377.36  5498.3  382.25
#Mann= 7 ,-1 , 0
  4491.7     .08       0  4620.2      .1       0  4683.7     .08       0
  4992.9     .07       0  4998.9     .08       0  5089.4     .05       0
  5188.1     .08       0
Bank Sta=4955.7,5057.9
XS Rating Curve= 0 ,0
Exp/Cntr=0.3,0.1

Type RM Length L Ch R = 1 ,2397    ,335,335,335
BEGIN DESCRIPTION:
Mapping XS c3c8bfd9
END DESCRIPTION:
XS GIS Cut Line= 4
      3625559.44     10518366.42      3625403.18     10518887.29
      3625420.54     10519191.11      3625624.54     10519529.67
#Sta/Elev= 30
  4354.5  373.47  4419.2  370.92  4435.8  370.21  4510.2  365.09  4576.3  362.05
  4685.9  359.27  4757.3  353.61  4796.9  352.12  4817.8  353.84  4889.5  352.86
  4919.8  347.99  4924.8  350.84  4931.3  348.01  4941.3  346.61  4951.3  345.37
  4981.3  345.57  4998.4  344.36  5001.1  343.86  5004.4  344.36  5011.4  345.26
  5071.5  346.39  5159.4  349.73  5224.5  352.77  5304.1  354.93  5399.2  359.72
  5405.1  360.96  5420.6   360.7  5532.3   366.5  5557.7   367.8  5597.9  369.54
#Mann= 8 ,-1 , 0
  4354.5     .08       0  4419.2     .05       0  4435.8     .16       0
  4998.4     .07       0  5004.4     .16       0  5159.4      .1       0
  5532.3     .15       0  5557.7      .1       0
Bank Sta=4941.3,5071.5
XS Rating Curve= 0 ,0
Exp/Cntr=0.3,0.1

Type RM Length L Ch R = 1 ,2062    ,152,152,152
BEGIN DESCRIPTION:
UNT 054 IN BUCR 4.0
END DESCRIPTION:
XS GIS Cut Line= 4
      3625216.54     10518214.55      3624973.49     10518626.87
      3625207.86     10519143.37      3625437.04     10519506.59
#Sta/Elev= 30
  4156.6  371.55  4240.5  367.47  4371.7  363.29  4414.6   360.4  4483.6  359.12
  4574.4  356.97    4596  357.05  4611.7  355.04  4617.5  355.83  4649.9  348.31
  4779.6  346.15  4808.2  344.49  4980.8  342.55  4995.4  337.89  4998.1  337.39
  5001.4  337.89  5003.8  341.59  5013.7  338.92  5021.4  338.64  5044.5  343.55
    5050  344.58  5124.7  345.06  5170.9  346.35    5177  347.46  5236.9   348.2
  5428.2  355.47    5474  357.63  5576.4  362.14  5628.8  363.76  5631.9  364.74
#Mann= 11 ,-1 , 0
  4156.6      .1       0  4240.5     .08       0  4483.6     .05       0
  4574.4      .1       0  4779.6     .16       0  4995.4     .07       0
  5001.4     .15       0  5013.7     .16       0  5428.2     .15       0
    5474      .1       0  5576.4     .15       0
Bank Sta=4980.8,5044.5
XS Rating Curve= 0 ,0
Exp/Cntr=0.3,0.1

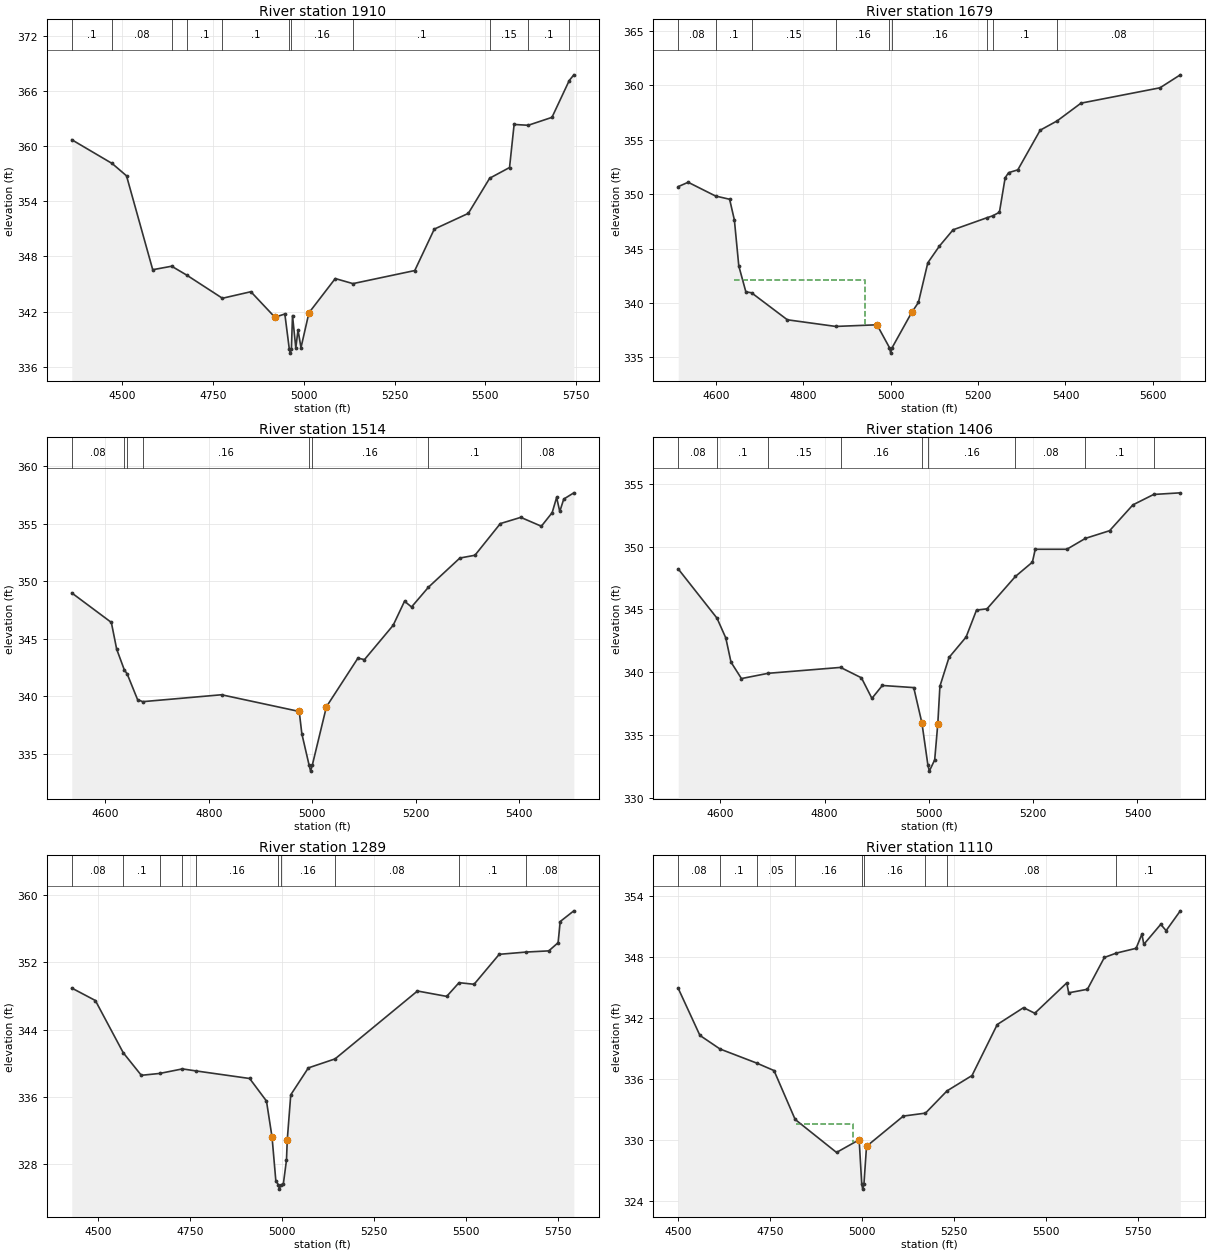
Type RM Length L Ch R = 1 ,1910    ,231,231,231
BEGIN DESCRIPTION:
UNT 054 IN BUCR 3.0
END DESCRIPTION:
XS GIS Cut Line= 4
      3624913.25     10518364.12      3624824.71     10518718.25
      3625043.46     10519051.58      3625333.99     10519596.32
#Sta/Elev= 30
  4362.1  360.68  4473.1   358.1  4512.7  356.76  4584.8  346.56  4636.9  346.94
  4677.7  345.99  4776.5  343.46  4854.8  344.17  4920.8   341.4  4948.2  341.75
  4960.3     338    4963   337.5  4966.3     338  4969.3  341.58  4978.4  338.06
  4984.4  340.02  4992.6  338.09  5014.5  341.88  5086.9   345.6  5135.6  345.05
  5305.6  346.47  5359.3  350.97  5452.9  352.68  5511.7   356.5  5566.3  357.66
  5578.9  362.34  5617.6  362.25    5683  363.11  5730.5  367.11  5743.2  367.73
#Mann= 11 ,-1 , 0
  4362.1      .1       0  4473.1     .08       0  4636.9     .15       0
  4677.7      .1       0  4776.5      .1       0  4960.3     .07       0
  4966.3     .16       0  5135.6      .1       0  5511.7     .15       0
  5617.6      .1       0  5730.5     .08       0
Bank Sta=4920.8,5014.5
XS Rating Curve= 0 ,0
Exp/Cntr=0.3,0.1

Type RM Length L Ch R = 1 ,1679    ,165,165,165
BEGIN DESCRIPTION:
UNT 054 IN BUCR 2.0
END DESCRIPTION:
XS GIS Cut Line= 3
      3624595.55     10518478.66      3624809.09     10519119.29
      3625069.51     10519515.12
#Sta/Elev= 30
  4513.7  350.68  4536.4  351.08    4599  349.82  4631.3  349.52  4642.2  347.62
  4652.3   343.4  4668.5  341.02  4681.4  340.94  4763.4  338.46  4874.2  337.85
  4968.6     338  4997.2   335.9  4999.9   335.4  5003.2   335.9    5048  339.13
  5063.4  340.05  5084.9  343.69  5111.2  345.21  5142.8  346.72  5220.6  347.83
  5233.5     348  5248.8  348.33  5261.9  351.49  5269.8  351.96  5290.9  352.22
  5342.1  355.86  5380.8  356.71  5435.5  358.34  5616.3  359.75  5662.8  360.94
#Mann= 9 ,-1 , 0
  4513.7     .08       0    4599      .1       0  4681.4     .15       0
  4874.2     .16       0  4997.2     .07       0  5003.2     .16       0
  5220.6     .15       0  5233.5      .1       0  5380.8     .08       0
#XS Ineff= 1 ,-1
 4641.82  4941.7342.1468
Permanent Ineff=
       F
Bank Sta=4968.6,5048
XS Rating Curve= 0 ,0
Exp/Cntr=0.3,0.1

Type RM Length L Ch R = 1 ,1514    ,108,108,108
BEGIN DESCRIPTION:
Mapping XS eb43aa9c
END DESCRIPTION:
XS GIS Cut Line= 3
        3624531.     10518554.71      3624635.17      10519172.8
      3624915.51     10519371.81
#Sta/Elev= 30
  4534.9  348.99  4611.4  346.43  4621.7  344.11  4636.4  342.32  4642.1  341.95
  4662.1  339.73  4672.1  339.55  4824.4  340.15  4974.6   338.7  4979.7  336.76
  4993.8  334.02  4996.6  333.52  4999.8  334.02  5027.2  339.11  5088.1  343.33
  5100.7   343.2  5156.2  346.18  5178.2  348.27  5191.7  347.77  5224.5  349.49
  5285.2  352.02  5314.3  352.26  5363.4  355.01  5402.9  355.55  5442.7  354.78
  5463.6  355.96  5472.2  357.28  5478.3  356.06    5486  357.14  5505.5  357.68
#Mann= 8 ,-1 , 0
  4534.9     .08       0  4636.4      .1       0  4642.1     .15       0
  4672.1     .16       0  4993.8     .07       0  4999.8     .16       0
  5224.5      .1       0  5402.9     .08       0
Bank Sta=4974.6,5027.2
XS Rating Curve= 0 ,0
Exp/Cntr=0.3,0.1

Type RM Length L Ch R = 1 ,1406    ,117,117,117
BEGIN DESCRIPTION:
Mapping XS 849c1c0a
END DESCRIPTION:
XS GIS Cut Line= 4
      3624513.64     10518579.06      3624501.49     10518940.17
      3624522.32     10519193.64      3624829.64     10519355.11
#Sta/Elev= 30
  4519.3  348.23  4593.6  344.31  4610.5  342.73  4620.5   340.8  4640.5  339.49
  4691.7  339.91  4830.6  340.38  4870.6  339.55  4890.7  337.91  4910.7  338.94
  4970.9  338.77  4986.6  335.95    4998  332.61  5000.8  332.11  5011.1  333.01
 5017.05  335.89  5021.1  338.88  5038.5  341.17  5071.3   342.8  5091.3  344.95
  5111.4  345.05  5165.8  347.63  5198.4  348.77    5204   349.8  5264.5   349.8
  5300.2  350.67  5346.5  351.28  5391.2  353.34    5431  354.17  5482.1   354.3
#Mann= 9 ,-1 , 0
  4519.3     .08       0  4593.6      .1       0  4691.7     .15       0
  4830.6     .16       0  4986.6     .08       0    4998     .16       0
  5165.8     .08       0  5300.2      .1       0    5431     .08       0
Bank Sta=4986.6,5017.05
XS Rating Curve= 0 ,0
Exp/Cntr=0.3,0.1

Type RM Length L Ch R = 1 ,1289    ,179,179,179
BEGIN DESCRIPTION:
Mapping XS 31b7d15e
END DESCRIPTION:
XS GIS Cut Line= 3
      3624496.05     10518514.06      3624365.85     10519256.21
      3624955.33     10519416.59
#Sta/Elev= 30
  4429.3  348.96  4493.4  347.48  4569.2  341.27  4618.3  338.59  4668.1  338.81
    4730  339.35    4767  339.11  4912.7  338.21  4958.4  335.53  4973.6  331.23
  4983.8  326.07  4990.9  325.56  4993.7  325.06  4996.9  325.56  5004.1  325.63
  5012.8  328.52 5014.89   330.9  5024.4  336.27  5072.2  339.47  5144.8  340.54
  5368.7  348.61  5448.2  347.97  5481.7   349.6  5522.6  349.41  5590.9  352.97
  5664.2  353.24  5725.6  353.38  5750.9  354.35  5756.7  356.87  5793.7  358.14
#Mann= 10 ,-1 , 0
  4429.3     .08       0  4569.2      .1       0  4668.1     .15       0
    4730     .08       0    4767     .16       0  4990.9     .05       0
  4996.9     .16       0  5144.8     .08       0  5481.7      .1       0
  5664.2     .08       0
Bank Sta=4973.6,5014.89
XS Rating Curve= 0 ,0
Exp/Cntr=0.3,0.1

Type RM Length L Ch R = 1 ,1110    ,444,444,444
BEGIN DESCRIPTION:
Mapping XS c6159f00
END DESCRIPTION:
XS GIS Cut Line= 4
      3624445.92     10518547.83      3624242.81      10518941.9
      3624260.17     10519294.33      3624817.51     10519405.45
#Sta/Elev= 30
  4500.5  344.92  4559.4  340.29  4614.1  338.95  4714.1  337.56  4760.8  336.83
  4818.2  332.02  4930.7  328.77  4992.2  330.02  4999.2  325.66  5001.9  325.16
  5005.2  325.66  5012.2  329.37  5112.3  332.35  5172.4  332.64    5231  334.83
  5298.9  336.34  5367.5  341.36  5438.9  343.02  5469.5  342.47  5556.5  345.46
  5561.6  344.48  5612.6  344.83  5658.6  347.96  5691.1  348.39  5744.8  348.86
  5760.7  350.26  5765.8  349.25  5811.8  351.22  5826.4   350.6    5865  352.55
#Mann= 9 ,-1 , 0
  4500.5     .08       0  4614.1      .1       0  4714.1     .05       0
  4818.2     .16       0  4999.2     .07       0  5005.2     .16       0
  5172.4     .05       0    5231     .08       0  5691.1      .1       0
#XS Ineff= 1 ,-1
 4821.82 4976.36331.6186
Permanent Ineff=
       F
Bank Sta=4992.2,5012.2
XS Rating Curve= 0 ,0
Exp/Cntr=0.3,0.1

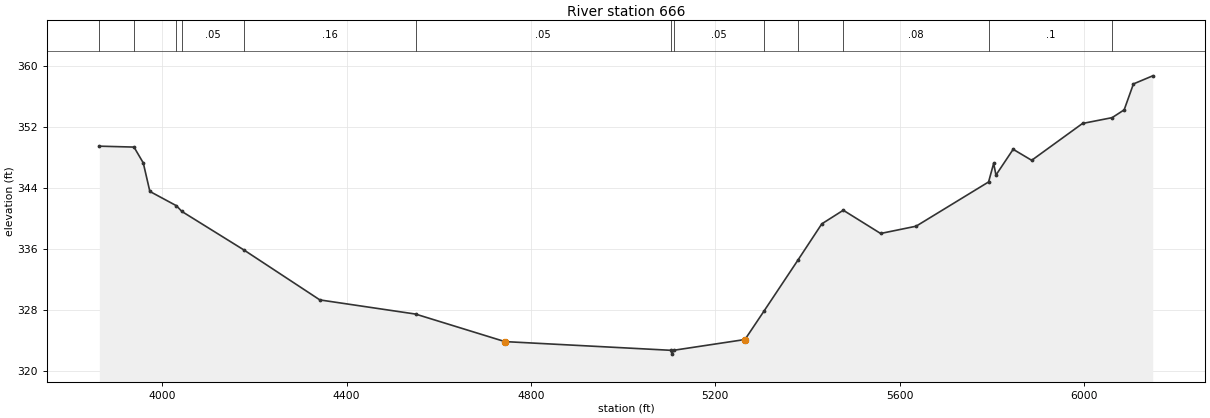
Type RM Length L Ch R = 1 ,666     ,0,0,0
BEGIN DESCRIPTION:
UNT 054 IN BUCR 1.0
END DESCRIPTION:
XS GIS Cut Line= 4
       3624491.4     10518436.98      3623845.55     10518989.08
      3623954.92     10519369.29      3624991.39     10519452.62
#Sta/Elev= 30
  3863.7  349.45  3938.9  349.33    3959  347.26  3973.3  343.53  4030.9  341.66
  4042.8  340.91  4177.4  335.87  4342.1  329.34  4549.6  327.49  4743.3  323.89
  5103.3  322.75    5106  322.25  5109.3  322.75  5264.2  324.16  5305.3  327.86
  5378.6   334.5  5430.9  339.29  5477.5  341.07  5558.5  338.03  5635.4  338.98
  5792.7  344.77  5803.7   347.2  5808.7  345.67    5846  349.04  5886.2   347.6
  5996.5  352.42  6060.7  353.18  6086.8   354.2  6106.9  357.59  6148.8  358.65
#Mann= 13 ,-1 , 0
  3863.7     .08       0  3938.9     .05       0  4030.9     .08       0
  4042.8     .05       0  4177.4     .16       0  4549.6     .05       0
  5103.3     .03       0  5109.3     .05       0  5305.3     .16       0
  5378.6     .05       0  5477.5     .08       0  5792.7      .1       0
  6060.7     .08       0
Bank Sta=4743.3,5264.2
XS Rating Curve= 0 ,0
Exp/Cntr=0.3,0.1

Chan Stop Cuts=-1
Use User Specified Reach Order=0
Composite Channel Slope=5