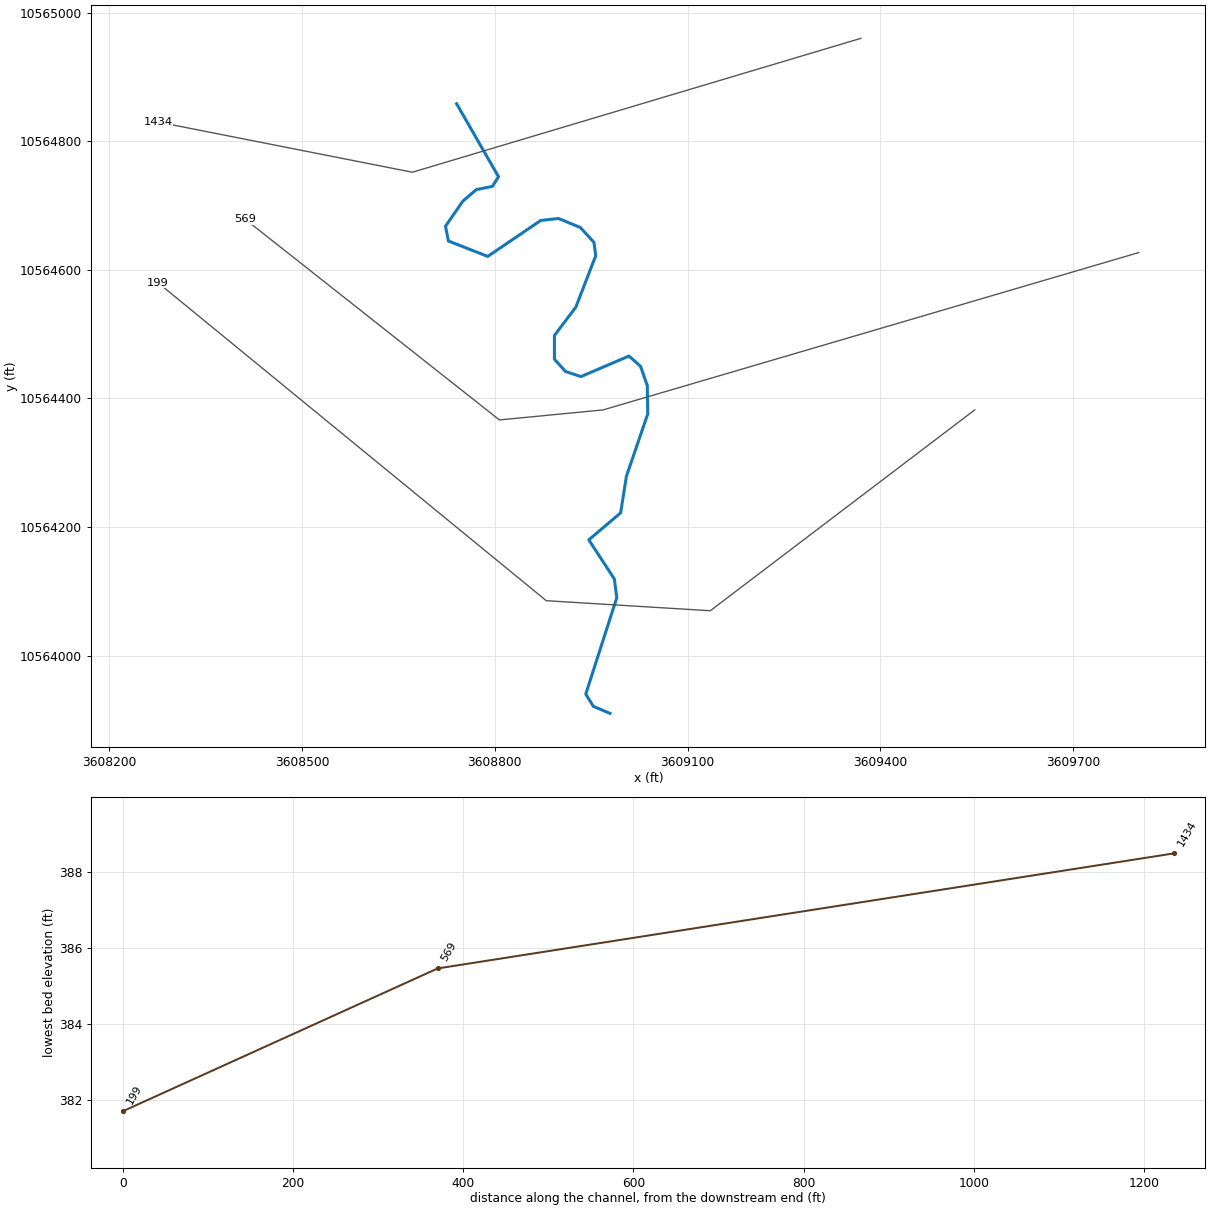
--- UNT 060 IN BUCR.prj (project) ---

Proj Title=UNT 060 IN BUCR Base Level Engineering
Current Plan=p01
Default Exp/Contr=0.3,0.1
English Units
Geom File=g01
Flow File=f01
Plan File=p01
BEGIN DESCRIPTION:
UNT 060 IN BUCR
END DESCRIPTION:

--- UNT 060 IN BUCR.p01 (plan) ---

Plan Title=Multiple Run
Short Identifier=Multiple
Geom File=g01
Flow File=f01
Subcritical Flow
K Sum by GR= 0
Std Step Tol= 0.01
Critical Tol= 0.01
Num of Std Step Trials= 20
Max Error Tol= 0.3
Flow Tol Ratio= 0.001
Split Flow NTrial= 30
Split Flow Tol= 0.02
Split Flow Ratio= 0.02
Log Output Level= 0
Friction Slope Method= 1
Unsteady Friction Slope Method= 2
Unsteady Bridges Friction Slope Method= 1
Parabolic Critical Depth
Global Vel Dist=  1 , 1 , 1
Global Log Level= 0
CheckData=True
Encroach Param= -1, 0, 0, 0
BEGIN DESCRIPTION:
Multiple Run
END DESCRIPTION:

--- UNT 060 IN BUCR.f01 (steady flow) ---

Flow Title=Multiple
Number of Profiles=7
Profile Names=10-year,25-year,50-year,1pct_min,100-year,1pct_plu,500-year
River Rch & RM= UNT 060 IN BUCR,Reach-1,1434
    1093    1513    1863    1676    2266    3065    3340
Boundary for River Rch & Prof#=UNT 060 IN BUCR,Reach-1,1
Up Type=0
Dn Type=3
Dn Slope=0.005
Boundary for River Rch & Prof#=UNT 060 IN BUCR,Reach-1,2
Up Type=0
Dn Type=3
Dn Slope=0.005
Boundary for River Rch & Prof#=UNT 060 IN BUCR,Reach-1,3
Up Type=0
Dn Type=3
Dn Slope=0.005
Boundary for River Rch & Prof#=UNT 060 IN BUCR,Reach-1,4
Up Type=0
Dn Type=3
Dn Slope=0.005
Boundary for River Rch & Prof#=UNT 060 IN BUCR,Reach-1,5
Up Type=0
Dn Type=3
Dn Slope=0.005
Boundary for River Rch & Prof#=UNT 060 IN BUCR,Reach-1,6
Up Type=0
Dn Type=3
Dn Slope=0.005
Boundary for River Rch & Prof#=UNT 060 IN BUCR,Reach-1,7
Up Type=0
Dn Type=3
Dn Slope=0.005

--- UNT 060 IN BUCR.g01 (geometry) ---

Geom Title=Existing Conditions

River Reach=UNT 060 IN BUCR,Reach-1
Reach XY= 30
      3608740.59     10564858.50      3608805.75     10564745.00
      3608796.25     10564730.00      3608771.25     10564725.00
      3608750.25     10564707.00      3608723.25     10564668.00
      3608727.75     10564645.00      3608789.00     10564621.00
      3608871.50     10564677.00      3608899.25     10564680.00
      3608933.00     10564666.00      3608954.25     10564643.00
      3608957.00     10564622.00      3608926.00     10564542.00
      3608892.75     10564498.00      3608892.75     10564461.00
      3608910.00     10564442.00      3608934.00     10564434.00
      3609008.75     10564466.00      3609026.75     10564450.00
      3609037.25     10564420.00      3609038.00     10564376.00
      3609004.75     10564279.00      3608995.75     10564222.00
      3608946.25     10564180.00      3608986.00     10564119.00
      3608989.75     10564090.00      3608941.50     10563940.00
      3608953.25     10563921.00      3608979.25     10563910.00

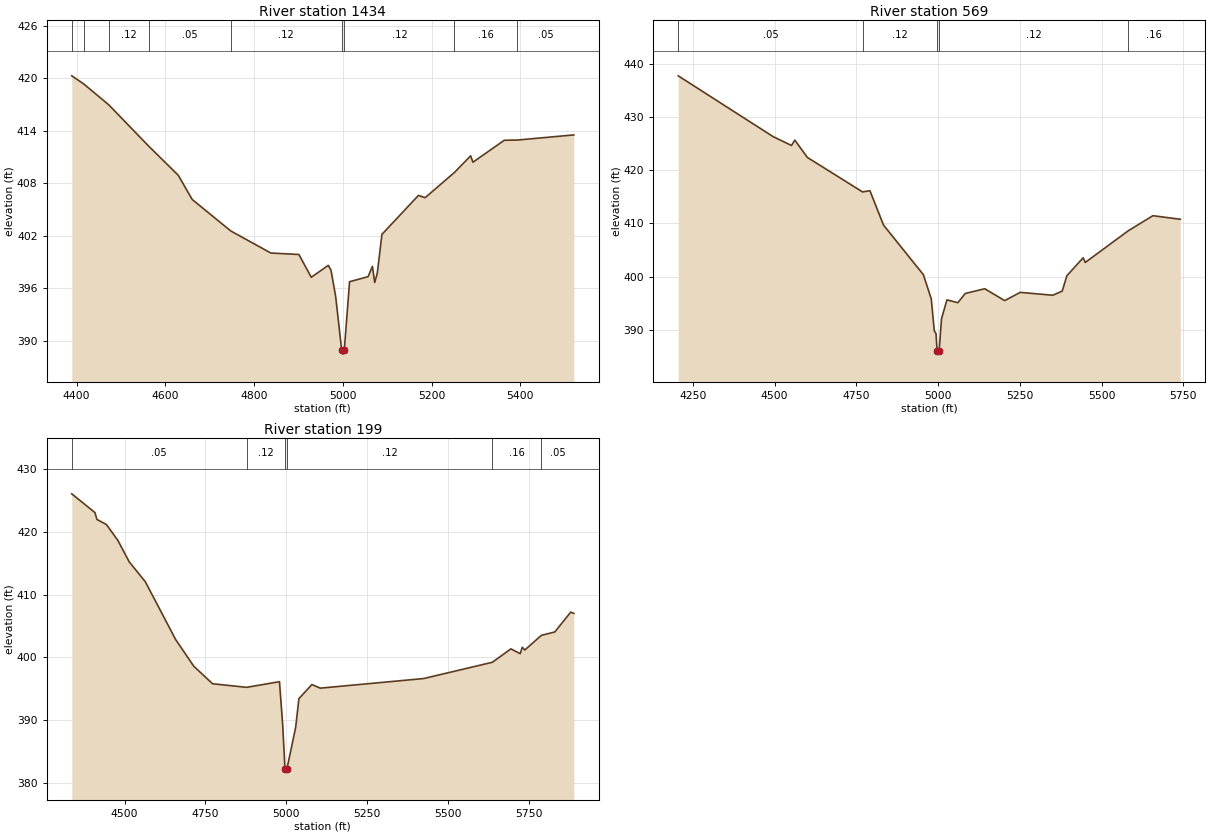
Type RM Length L Ch R = 1,1434,865,865,865
BEGIN DESCRIPTION:
UNT 060 IN BUCR 2.0
END DESCRIPTION:
XS GIS Cut Line= 3
      3609369.64     10564960.33      3608671.72     10564752.00
      3608275.91     10564830.12
#Sta/Elev= 30
  4389.0  420.27  4415.8  419.35  4472.4  416.96  4562.0  412.26  4629.1  408.91
  4660.4  406.15  4747.7  402.54  4837.8  400.03  4901.0  399.86  4928.9  397.26
  4967.3  398.62  4973.4  398.06  4983.9  395.06  4997.4  388.98  5000.2  388.48
  5003.4  388.98  5015.2  396.75  5056.9  397.33  5066.7  398.50  5071.9  396.66
  5077.8  397.75  5088.2  402.16  5170.5  406.61  5185.6  406.35  5251.6  409.23
  5288.2  411.13  5293.3  410.40  5364.1  412.91  5392.6  412.93  5520.8  413.52
#Mann=9,-1,0
  4389.0    0.12       0  4415.8    0.05       0  4472.4    0.12       0
  4562.0    0.05       0  4747.7    0.12       0  4997.4    0.07       0
  5003.4    0.12       0  5251.6    0.16       0  5392.6    0.05       0
Bank Sta=4997.4,5003.4
Exp/Cntr=0.3,0.1

Type RM Length L Ch R = 1,569,370,370,370
BEGIN DESCRIPTION:
Mapping XS 8a605761
END DESCRIPTION:
XS GIS Cut Line= 4
      3609801.89     10564626.99      3608968.59     10564382.20
      3608807.13     10564366.58      3608411.33     10564679.05
#Sta/Elev= 30
  4205.6  437.73  4495.2  426.33  4551.9  424.65  4562.0  425.66  4600.5  422.40
  4769.2  415.92  4791.6  416.16  4833.3  409.69  4955.1  400.38  4979.2  395.82
  4988.5  389.82  4993.7  389.34  4997.1  385.96  4999.8  385.46  5003.1  385.96
  5010.5  392.08  5027.1  395.65  5060.5  395.12  5083.1  396.85  5142.7  397.74
  5203.7  395.51  5251.2  397.06  5350.6  396.52  5379.5  397.29  5393.9  400.19
  5443.6  403.56  5450.0  402.68  5581.8  408.64  5656.8  411.46  5740.6  410.79
#Mann=5,-1,0
  4205.6    0.05       0  4769.2    0.12       0  4997.1    0.07       0
  5003.1    0.12       0  5581.8    0.16       0
Bank Sta=4997.1,5003.1
Exp/Cntr=0.3,0.1

Type RM Length L Ch R = 1,199,0,0,0
BEGIN DESCRIPTION:
UNT 060 IN BUCR 1.0
END DESCRIPTION:
XS GIS Cut Line= 4
      3609546.74     10564382.22      3609135.26     10564069.70
      3608880.05     10564085.33      3608275.89     10564580.11
#Sta/Elev= 30
  4336.3  426.05  4407.9  423.07  4414.2  421.97  4443.3  421.17  4478.7  418.65
  4514.0  415.22  4563.9  412.04  4657.5  402.85  4713.7  398.59  4771.9  395.79
  4877.2  395.22  4978.9  396.12  4988.9  389.22  4995.9  382.21  4998.7  381.71
  5001.9  382.21  5029.0  388.85  5039.0  393.42  5079.1  395.66  5105.3  395.09
  5425.0  396.62  5637.4  399.21  5694.9  401.35  5723.6  400.58  5730.1  401.60
  5738.0  401.17  5789.1  403.50  5830.6  404.04  5880.1  407.21  5889.6  407.00
#Mann=6,-1,0
  4336.3    0.05       0  4877.2    0.12       0  4995.9    0.07       0
  5001.9    0.12       0  5637.4    0.16       0  5789.1    0.05       0
Bank Sta=4995.9,5001.9
Exp/Cntr=0.3,0.1

Chan Stop Cuts=-1