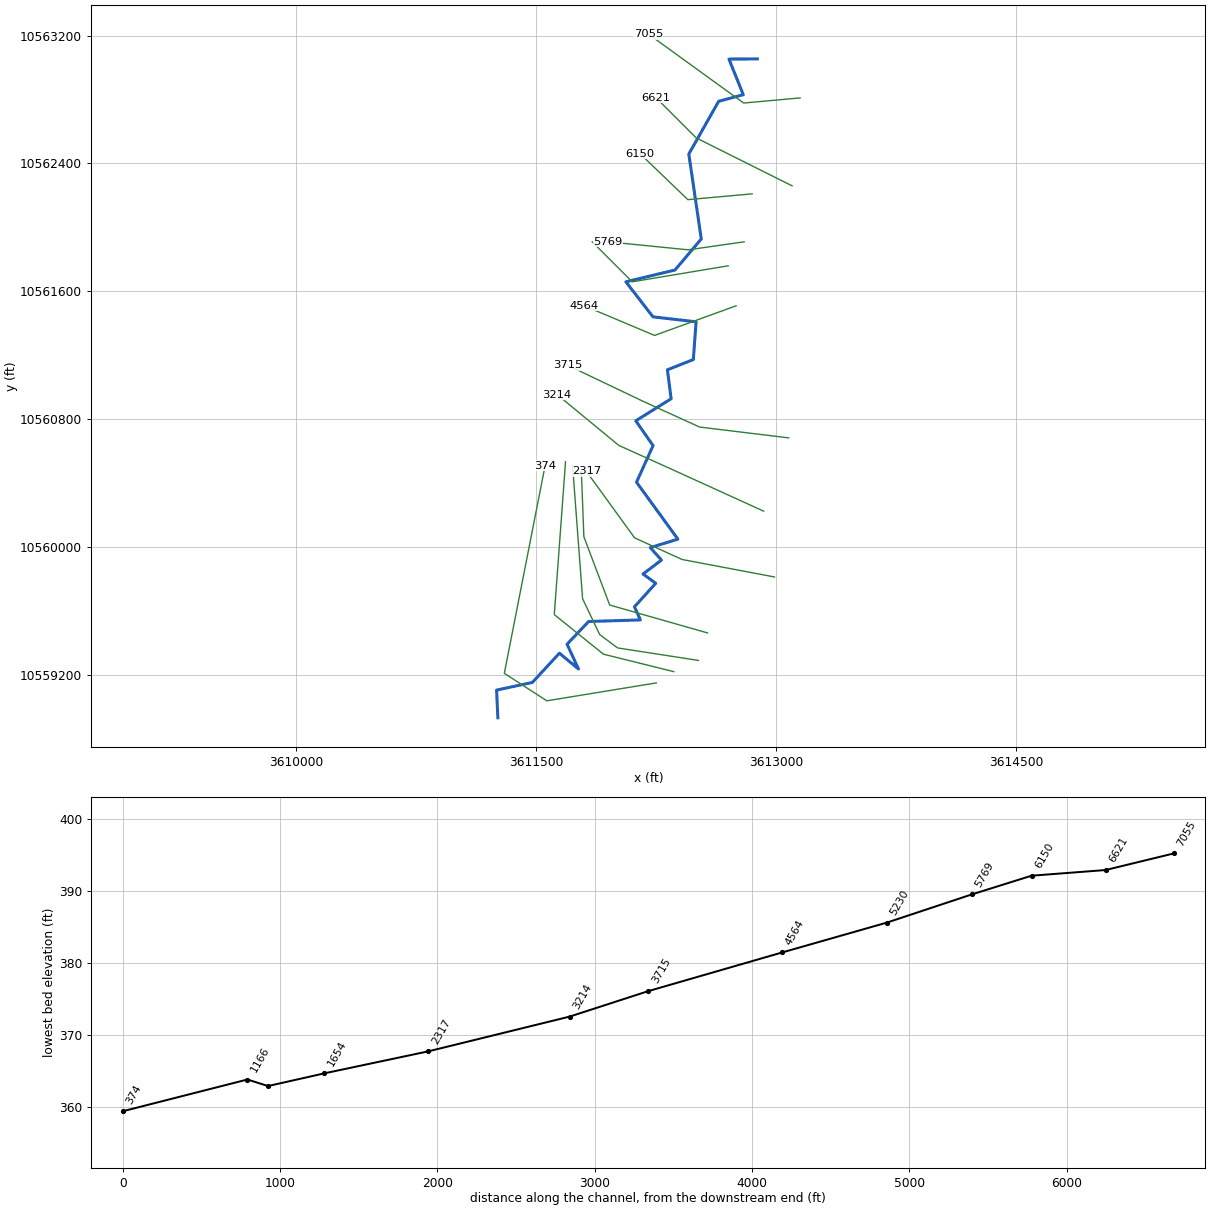
--- UNT 063 IN BUCR.prj (project) ---

Proj Title=UNT 063 IN BUCR Base Level Engineering
Current Plan=p01
Default Exp/Contr=0.3,0.1
English Units
Geom File=g01
Flow File=f01
Plan File=p01
Y Axis Title=Elevation
X Axis Title(PF)=Main Channel Distance
X Axis Title(XS)=Station
BEGIN DESCRIPTION:
UNT 063 IN BUCR
END DESCRIPTION:
DSS Export Rating Curves= 0
DSS Export Rating Curve Sorted= 0
DSS Export Volume Flow Curves= 0
DXF OffsetX= 0
DXF OffsetY= 0
DXF ScaleX= 1
DXF ScaleY= 10

--- UNT 063 IN BUCR.p01 (plan) ---

Plan Title=Multiple Run
Short Identifier=Multiple
Geom File=g01
Flow File=f01
Subcritical Flow
K Sum by GR= 0
Std Step Tol= 0.01
Critical Tol= 0.01
Num of Std Step Trials= 20
Max Error Tol= 0.3
Flow Tol Ratio= 0.001
Split Flow NTrial= 30
Split Flow Tol= 0.02
Split Flow Ratio= 0.02
Log Output Level= 0
Friction Slope Method= 1
Unsteady Friction Slope Method= 2
Unsteady Bridges Friction Slope Method= 1
Parabolic Critical Depth
Global Vel Dist=  1 , 1 , 1
Global Log Level= 0
CheckData=True
Encroach Param= -1, 0, 0, 0
BEGIN DESCRIPTION:
Multiple Run
END DESCRIPTION:

--- UNT 063 IN BUCR.f01 (steady flow) ---

Flow Title=Multiple
Number of Profiles=7
Profile Names=10-year,25-year,50-year,1pct_min,100-year,1pct_plu,500-year
River Rch & RM= UNT 063 IN BUCR,Reach-1,7055
    1242    1738    2156    1954    2642    3573    3952
Boundary for River Rch & Prof#=UNT 063 IN BUCR,Reach-1,1
Up Type=0
Dn Type=3
Dn Slope=0.005
Boundary for River Rch & Prof#=UNT 063 IN BUCR,Reach-1,2
Up Type=0
Dn Type=3
Dn Slope=0.005
Boundary for River Rch & Prof#=UNT 063 IN BUCR,Reach-1,3
Up Type=0
Dn Type=3
Dn Slope=0.005
Boundary for River Rch & Prof#=UNT 063 IN BUCR,Reach-1,4
Up Type=0
Dn Type=3
Dn Slope=0.005
Boundary for River Rch & Prof#=UNT 063 IN BUCR,Reach-1,5
Up Type=0
Dn Type=3
Dn Slope=0.005
Boundary for River Rch & Prof#=UNT 063 IN BUCR,Reach-1,6
Up Type=0
Dn Type=3
Dn Slope=0.005
Boundary for River Rch & Prof#=UNT 063 IN BUCR,Reach-1,7
Up Type=0
Dn Type=3
Dn Slope=0.005

--- UNT 063 IN BUCR.g01 (geometry) ---

Geom Title=Existing Conditions
Program Version=4.10

River Reach=UNT 063 IN BUCR ,Reach-1
Reach XY= 30
      3612881.75       10563054.       3612704.5       10563053.
      3612794.25       10562830.      3612640.25       10562789.
       3612453.5       10562459.       3612531.5       10561928.
      3612367.25       10561734.      3612060.25       10561660.
       3612229.5       10561441.        3612499.       10561410.
      3612481.75       10561174.      3612319.75       10561110.
        3612343.       10560929.        3612122.       10560791.
        3612230.       10560636.       3612126.5       10560407.
      3612385.25       10560051.      3612212.75       10559998.
       3612282.5       10559920.      3612167.25       10559833.
      3612246.75       10559775.      3612113.75       10559628.
      3612150.75       10559546.        3611827.       10559536.
      3611692.25       10559394.      3611763.75       10559239.
      3611644.75       10559338.      3611475.25       10559155.
       3611251.5       10559107.       3611259.5       10558934.

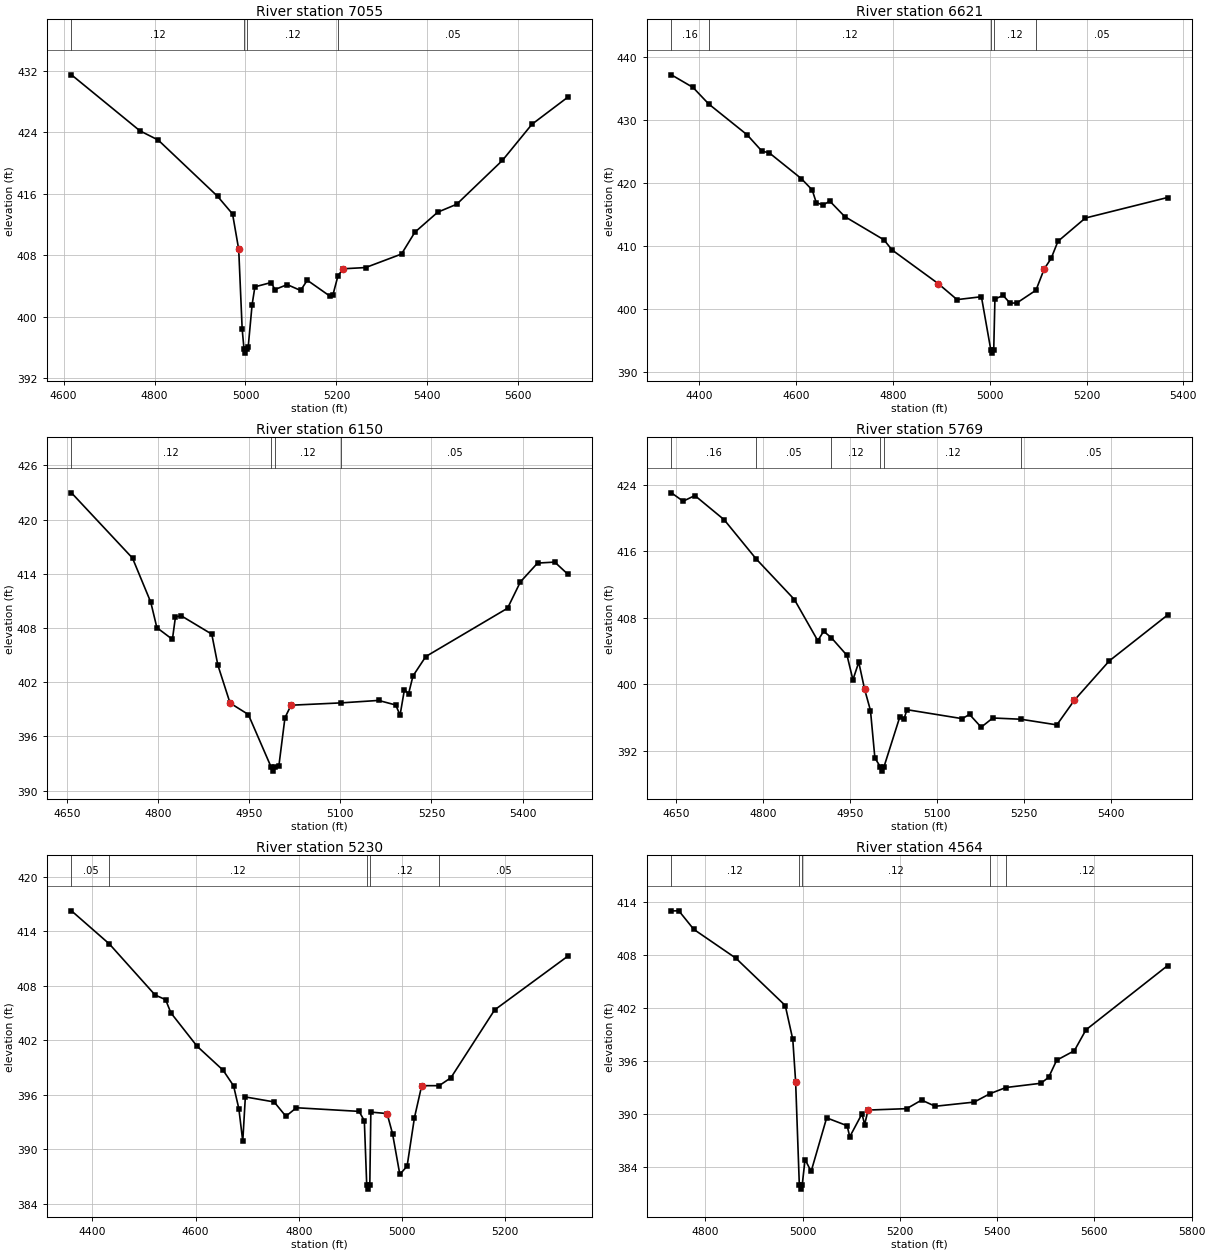
Type RM Length L Ch R = 1 ,7055    ,434,434,434
BEGIN DESCRIPTION:
UNT 063 IN BUCR 10.0
END DESCRIPTION:
XS GIS Cut Line= 3
      3613149.61     10562810.19      3612796.72     10562778.04
      3612199.64     10563210.16
#Sta/Elev= 30
  4617.2  431.48  4767.8  424.19    4808  422.99  4938.5  415.67  4971.6  413.36
  4985.1  408.75  4992.7  398.38  4996.8  395.75  4999.6  395.25  5002.8  395.75
    5006  396.08  5014.5  401.53  5020.7  403.88  5056.3  404.44  5064.8  403.53
  5091.8  404.17  5121.2  403.41  5135.9  404.74  5186.2  402.65  5192.4  402.85
  5203.5  405.33  5214.9  406.23  5264.3  406.39  5343.2  408.15  5372.6  410.99
  5422.9   413.6  5464.6  414.63  5565.2  420.34  5630.1  425.04  5708.6  428.55
#Mann= 4 ,-1 , 0
  4617.2     .12       0  4996.8     .07       0  5002.8     .12       0
  5203.5     .05       0
Bank Sta=4985.1,5214.9
XS Rating Curve= 0 ,0
Exp/Cntr=0.3,0.1

Type RM Length L Ch R = 1 ,6621    ,471,471,471
BEGIN DESCRIPTION:
UNT 063 IN BUCR 9.0
END DESCRIPTION:
XS GIS Cut Line= 3
      3613099.62     10562260.18      3612499.61     10562560.19
       3612249.6      10562810.2
#Sta/Elev= 30
  4342.8  437.15  4387.5  435.14  4419.8  432.52  4499.3  427.61  4530.1  424.99
  4544.1   424.8  4611.1  420.66  4633.5  418.86  4641.9  416.85  4655.9  416.47
  4669.8  417.09  4700.6  414.64  4781.6  410.94  4798.4  409.33  4893.4     404
  4932.6  401.44  4982.9   401.9  5002.3  393.44    5005  392.94  5008.3  393.44
  5010.8  401.54  5027.8   402.1  5041.9  400.88  5056.1  400.91  5095.5  402.93
  5112.6  406.32  5126.8  407.98  5140.9   410.7  5197.5   414.4  5367.2  417.66
#Mann= 5 ,-1 , 0
  4342.8     .16       0  4419.8     .12       0  5002.3     .07       0
  5008.3     .12       0  5095.5     .05       0
Bank Sta=4893.4,5112.6
XS Rating Curve= 0 ,0
Exp/Cntr=0.3,0.1

Type RM Length L Ch R = 1 ,6150    ,381,381,381
BEGIN DESCRIPTION:
UNT 063 IN BUCR 8.0
END DESCRIPTION:
XS GIS Cut Line= 3
      3612849.66     10562210.19      3612447.76     10562173.87
      3612149.61     10562460.19
#Sta/Elev= 30
  4657.3  422.97  4757.8  415.74  4787.9  410.85  4797.9  408.04  4823.5  406.74
  4828.5  409.23  4838.1  409.35  4888.3  407.32  4898.3   403.9  4918.4  399.69
  4948.5  398.42  4985.7  392.65  4988.4  392.15  4991.7  392.65  4998.7  392.68
  5008.8  398.06  5018.8  399.45  5101.9  399.71    5163  399.98  5191.3  399.47
  5198.3  398.34  5205.5  401.16  5212.4  400.73  5219.6  402.69  5240.7  404.84
  5375.3  410.19  5396.4   413.1  5424.7  415.19    5453   415.3  5474.2  413.98
#Mann= 4 ,-1 , 0
  4657.3     .12       0  4985.7     .07       0  4991.7     .12       0
  5101.9     .05       0
Bank Sta=4918.4,5018.8
XS Rating Curve= 0 ,0
Exp/Cntr=0.3,0.1

Type RM Length L Ch R = 1 ,5769    ,539,539,539
BEGIN DESCRIPTION:
UNT 063 IN BUCR 7.0
END DESCRIPTION:
XS GIS Cut Line= 3
      3612799.66      10561910.2      3612449.61     10561860.19
       3611949.6     10561910.19
#Sta/Elev= 30
  4641.6  423.06  4661.8  422.05  4682.1  422.73  4732.6  419.82  4787.7  415.11
  4853.8  410.21  4894.2  405.25  4904.3  406.39  4917.7   405.6  4944.7  403.47
  4954.8  400.54  4964.9  402.66    4975  399.39  4985.1  396.84  4992.7  391.13
  5002.3  390.04    5005  389.54  5008.3  390.04  5035.4     396  5042.9  395.81
    5048  396.94  5143.4  395.86    5156  396.37  5176.1  394.83  5196.2  395.94
  5244.6  395.79  5306.7  395.11  5336.9  398.08  5397.2  402.82  5497.7  408.34
#Mann= 6 ,-1 , 0
  4641.6     .16       0  4787.7     .05       0  4917.7     .12       0
  5002.3     .07       0  5008.3     .12       0  5244.6     .05       0
Bank Sta=4975,5336.9
XS Rating Curve= 0 ,0
Exp/Cntr=0.3,0.1

Type RM Length L Ch R = 1 ,5230    ,666,666,666
BEGIN DESCRIPTION:
UNT 063 IN BUCR 6.0
END DESCRIPTION:
XS GIS Cut Line= 3
      3612699.65      10561760.2      3612099.61     10561660.19
      3611849.59     10561910.21
#Sta/Elev= 30
  4359.4  416.27  4432.9  412.62  4521.6     407  4541.9  406.49  4552.1  405.04
  4602.8  401.37  4653.4  398.72  4673.7     397  4683.9  394.49  4691.5  390.89
  4696.5  395.78  4752.3  395.23  4775.1  393.65  4795.4  394.59    4917  394.19
  4927.2  393.16  4931.8  386.13  4934.5  385.63  4937.8  386.13  4939.8  394.11
  4971.3  393.95  4981.9  391.73    4996  387.25  5010.1  388.16  5024.3  393.48
  5038.4  397.02  5072.2  397.02    5095  397.89  5179.8  405.36  5321.3  411.26
#Mann= 5 ,-1 , 0
  4359.4     .05       0  4432.9     .12       0  4931.8     .07       0
  4937.8     .12       0  5072.2     .05       0
Bank Sta=4971.3,5038.4
XS Rating Curve= 0 ,0
Exp/Cntr=0.3,0.1

Type RM Length L Ch R = 1 ,4564    ,849,849,849
BEGIN DESCRIPTION:
UNT 063 IN BUCR 5.0
END DESCRIPTION:
XS GIS Cut Line= 3
      3612749.65      10561510.2      3612239.42     10561324.91
      3611799.58      10561510.2
#Sta/Elev= 30
  4730.3  412.94  4745.6  412.95  4776.2  410.86  4862.7   407.6  4964.4  402.24
  4979.9   398.4  4985.7  393.64  4993.3  381.98  4996.1  381.48  4999.3  381.98
  5005.1  384.83  5017.6  383.48  5049.5  389.54  5091.6  388.65    5097   387.4
  5122.2     390  5127.6  388.77  5134.6  390.42  5214.1  390.58  5244.7  391.55
  5272.7  390.85  5352.7  391.32  5385.2  392.27  5418.1  392.97  5489.9  393.45
  5505.9  394.12  5522.5  396.06  5558.8  397.13  5582.6  399.49  5750.4  406.75
#Mann= 5 ,-1 , 0
  4730.3     .12       0  4993.3     .07       0  4999.3     .12       0
  5385.2     .05       0  5418.1     .12       0
Bank Sta=4985.7,5134.6
XS Rating Curve= 0 ,0
Exp/Cntr=0.3,0.1

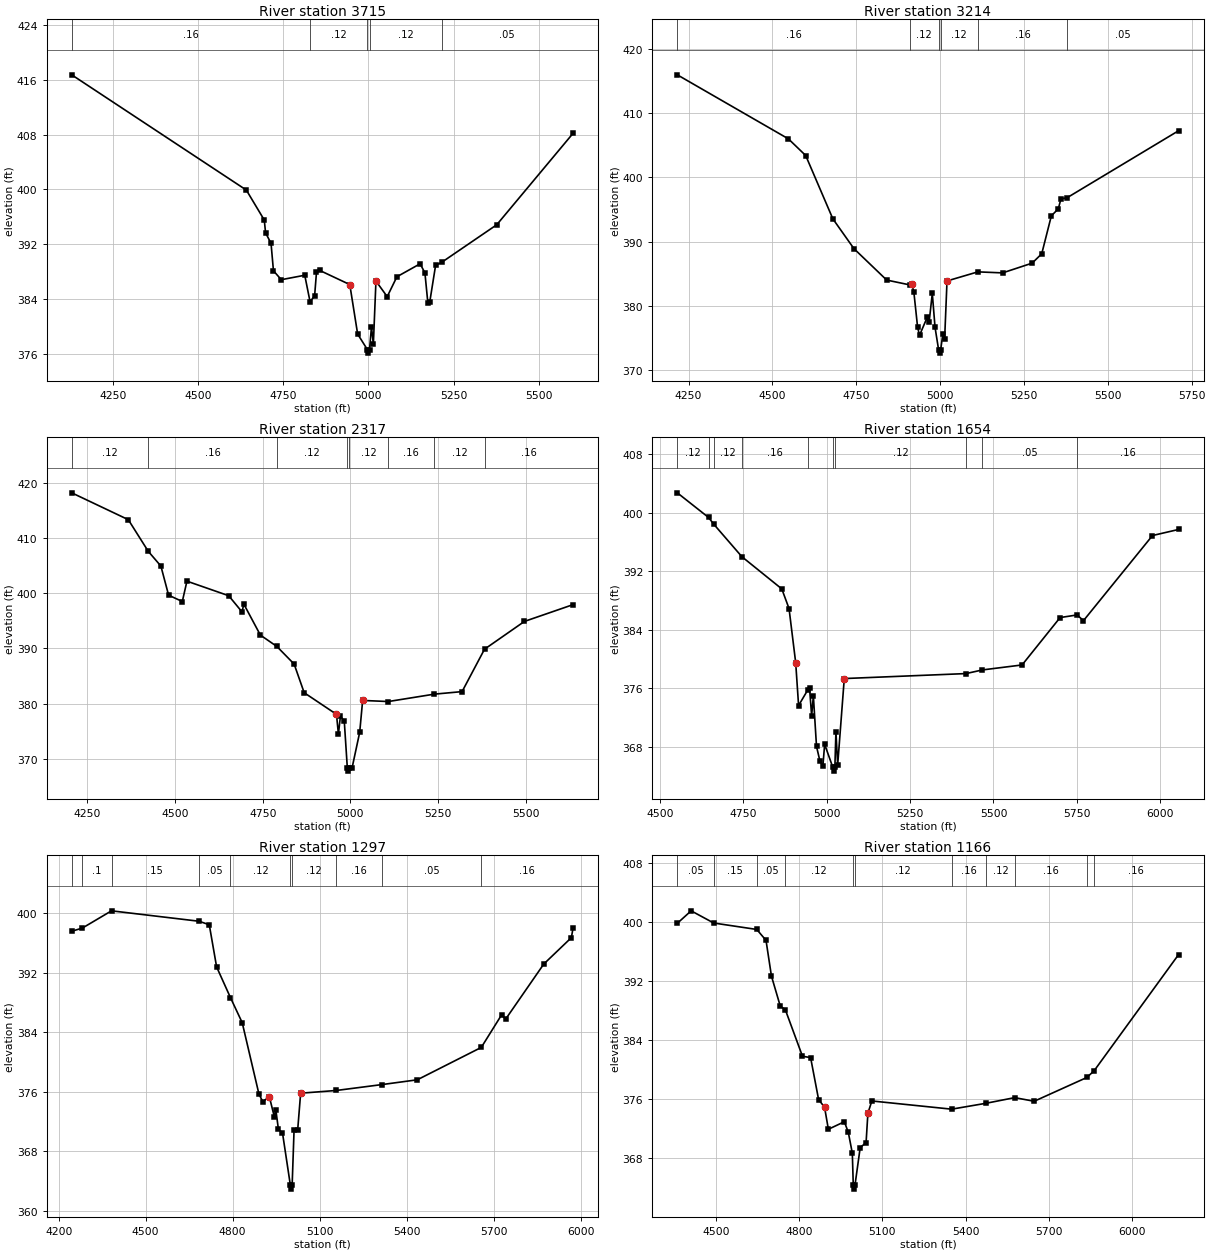
Type RM Length L Ch R = 1 ,3715    ,501,501,501
BEGIN DESCRIPTION:
UNT 063 IN BUCR 4.0
END DESCRIPTION:
XS GIS Cut Line= 4
      3613077.94     10560684.29      3612520.67       10560752.
      3612166.51     10560913.45      3611697.76     10561137.41
#Sta/Elev= 30
  4129.9  416.71    4642   399.9  4694.6  395.53  4698.4  393.66  4714.4  392.14
  4721.5  388.13  4744.5  386.83  4813.3  387.48  4828.8  383.63  4842.2  384.47
  4847.7  387.91  4857.3  388.18  4945.4  386.12  4968.4   378.9  4997.2  376.62
  4999.9  376.12  5003.2  376.62    5009  379.96  5014.5  377.43  5022.1  386.63
  5055.1  384.36  5083.6  387.26  5151.6  389.15  5165.7  387.83  5174.3  383.45
  5179.8  383.55    5197  388.92  5214.5  389.35  5376.3  394.84    5600  408.17
#Mann= 5 ,-1 , 0
  4129.9     .16       0  4828.8     .12       0  4997.2     .07       0
  5003.2     .12       0  5214.5     .05       0
Bank Sta=4945.4,5022.1
XS Rating Curve= 0 ,0
Exp/Cntr=0.3,0.1

Type RM Length L Ch R = 1 ,3214    ,897,897,897
BEGIN DESCRIPTION:
UNT 063 IN BUCR 3.0
END DESCRIPTION:
XS GIS Cut Line= 4
      3612921.69     10560225.97      3612338.38     10560491.58
      3612015.47     10560637.41      3611630.08      10560955.1
#Sta/Elev= 30
  4216.4  416.03  4547.6  406.03  4599.2  403.43  4680.2  393.54    4743  388.89
  4840.7  383.98  4909.1  383.23  4915.5   383.4  4921.8  382.07  4932.8  376.65
  4938.6  375.35  4961.8  378.19  4967.2   377.4  4976.7  381.89  4984.9  376.59
  4995.6  373.07  4998.4  372.57  5001.6  373.07    5008  375.49  5013.5  374.77
  5020.6  383.84  5112.6  385.26  5186.3   385.1  5274.3  386.62    5303  388.08
  5331.7  394.01  5352.5  395.11  5360.3  396.66  5378.4  396.83  5711.1   407.3
#Mann= 6 ,-1 , 0
  4216.4     .16       0  4909.1     .12       0  4995.6     .07       0
  5001.6     .12       0  5112.6     .16       0  5378.4     .05       0
Bank Sta=4915.5,5020.6
XS Rating Curve= 0 ,0
Exp/Cntr=0.3,0.1

Type RM Length L Ch R = 1 ,2317    ,663,663,663
BEGIN DESCRIPTION:
UNT 063 IN BUCR 2.0
END DESCRIPTION:
XS GIS Cut Line= 4
      3612989.42      10559814.5       3612411.3     10559923.87
      3612114.42     10560059.29      3611812.36     10560475.93
#Sta/Elev= 30
  4205.5  418.22  4366.8  413.35  4423.6  407.62  4459.7  404.94  4481.7  399.66
  4520.8  398.51    4534   402.2  4653.1  399.56  4691.1  396.62  4696.1  398.05
  4743.4  392.42  4790.4  390.36  4839.7  387.16  4868.3  381.97  4960.4  378.05
  4965.9  374.45  4971.6   377.7  4982.6  376.83  4991.4  368.25  4994.2  367.75
  4997.4  368.25  5004.6  368.26  5026.6   374.8    5035  380.57  5108.1  380.37
  5239.3  381.71  5318.5  382.17  5382.5  389.86  5496.3   394.9  5634.8  397.94
#Mann= 8 ,-1 , 0
  4205.5     .12       0  4423.6     .16       0  4790.4     .12       0
  4991.4     .07       0  4997.4     .12       0  5108.1     .16       0
  5239.3     .12       0  5382.5     .16       0
Bank Sta=4960.4,5035
XS Rating Curve= 0 ,0
Exp/Cntr=0.3,0.1

Type RM Length L Ch R = 1 ,1654    ,357,357,357
BEGIN DESCRIPTION:
Mapping XS 43b7c409
END DESCRIPTION:
XS GIS Cut Line= 4
      3612570.75     10559464.58      3611958.77     10559639.06
      3611797.31     10560066.15      3611781.68     10560474.99
#Sta/Elev= 30
  4552.6  402.74  4646.2  399.37  4662.2  398.43  4746.2     394  4865.7   389.6
  4887.4  386.91  4907.3  379.52    4916  373.65  4942.8  375.73  4948.9  376.02
  4955.1  372.24  4960.3  374.97  4969.7  368.06  4980.1  366.03  4988.9  365.43
  4994.1  368.35  5018.7  365.18  5021.5  364.68  5024.7  365.18  5027.9  370.09
  5033.1   365.5  5052.9  377.34  5417.6  378.02  5466.9  378.52  5585.7   379.2
  5699.6  385.68  5750.6  386.04  5769.7  385.26  5976.5   396.9  6054.7  397.73
#Mann= 10 ,-1 , 0
  4552.6     .12       0  4646.2     .16       0  4662.2     .12       0
  4746.2     .16       0  4942.8     .12       0  5018.7     .07       0
  5024.7     .12       0  5417.6     .16       0  5466.9     .05       0
  5750.6     .16       0
Bank Sta=4907.3,5052.9
XS Rating Curve= 0 ,0
Exp/Cntr=0.3,0.1

Type RM Length L Ch R = 1 ,1297    ,131,131,131
BEGIN DESCRIPTION:
Mapping XS 8c3a1c1e
END DESCRIPTION:
XS GIS Cut Line= 5
      3612513.48     10559292.71      3612008.25     10559370.83
      3611896.27     10559454.17       3611789.5     10559678.13
      3611727.03     10560505.74
#Sta/Elev= 30
    4245  397.55  4281.5  397.97  4382.2  400.29  4684.2  398.89  4719.4  398.42
  4744.7  392.76  4792.4  388.64    4833  385.27  4890.6   375.7  4903.9  374.66
  4926.5  375.34  4943.7  372.64  4949.2   373.5  4957.9  370.94  4971.9  370.48
  4999.2  363.42  5001.9  362.92  5005.2  363.42  5011.8  370.82  5024.4  370.91
  5034.5   375.8  5158.1  376.17  5315.2  376.96  5436.8   377.6  5657.6  381.95
  5727.6  386.32  5741.5  385.74  5873.2  393.15  5968.3  396.69  5973.9  397.95
#Mann= 10 ,-1 , 0
    4245     .05       0  4281.5      .1       0  4382.2     .15       0
  4684.2     .05       0  4792.4     .12       0  4999.2     .07       0
  5005.2     .12       0  5158.1     .16       0  5315.2     .05       0
  5657.6     .16       0
Bank Sta=4926.5,5034.5
XS Rating Curve= 0 ,0
Exp/Cntr=0.3,0.1

Type RM Length L Ch R = 1 ,1166    ,792,792,792
BEGIN DESCRIPTION:
Mapping XS d70aa5be
END DESCRIPTION:
XS GIS Cut Line= 4
      3612359.81      10559222.4       3611919.7     10559331.77
      3611612.41     10559579.17      3611682.72     10560534.89
#Sta/Elev= 30
  4361.2   399.8    4411  401.49  4492.4  399.84  4647.4  398.97  4680.8   397.5
  4700.4  392.66  4732.4  388.57  4750.3  388.12  4812.2  381.81  4841.5  381.63
  4870.3  375.95  4891.8  374.91  4905.5  371.93  4963.1  372.95  4977.4  371.51
  4991.8   368.7  4995.3  364.33    4998  363.83  5001.3  364.33  5020.2  369.46
  5041.4  370.12  5047.9  374.09  5062.2  375.76  5349.7  374.65    5474  375.45
  5576.8  376.21  5647.2  375.72    5837  378.94  5863.2  379.85  6167.5  395.57
#Mann= 11 ,-1 , 0
  4361.2     .05       0  4492.4     .15       0  4647.4     .05       0
  4750.3     .12       0  4995.3     .07       0  5001.3     .12       0
  5349.7     .16       0    5474     .12       0  5576.8     .16       0
    5837     .05       0  5863.2     .16       0
Bank Sta=4891.8,5047.9
XS Rating Curve= 0 ,0
Exp/Cntr=0.3,0.1

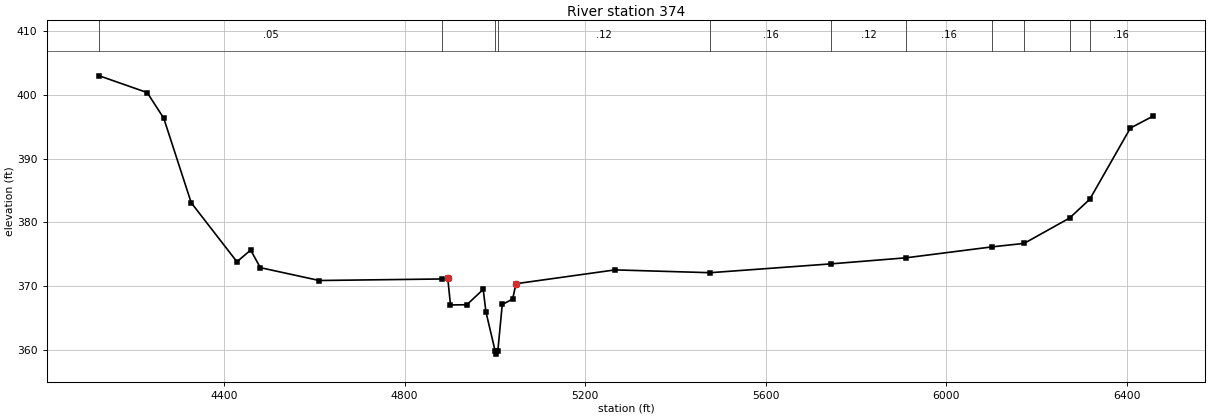
Type RM Length L Ch R = 1 ,374     ,0,0,0
BEGIN DESCRIPTION:
UNT 063 IN BUCR 1.0
END DESCRIPTION:
XS GIS Cut Line= 4
      3612250.46     10559152.09      3611565.54     10559040.11
      3611299.91     10559211.98      3611554.87     10560510.18
#Sta/Elev= 30
  4123.9  402.93  4229.9  400.31  4266.6   396.3  4327.4  383.09  4428.7  373.86
  4459.1  375.69  4480.5  372.94  4611.1  370.93  4882.6  371.17  4895.7  371.29
  4901.7  367.11  4937.9  367.14  4974.2  369.54  4980.2  366.05  5000.6  359.92
  5003.4  359.42  5006.6  359.92  5016.4  367.18  5039.4  368.03  5046.8  370.43
  5266.3  372.59    5477  372.15  5744.4  373.53  5910.9  374.48  6101.4  376.19
  6172.3  376.73    6273  380.69  6317.9  383.64  6407.8  394.77  6457.3   396.6
#Mann= 11 ,-1 , 0
  4123.9     .05       0  4882.6     .12       0  5000.6     .07       0
  5006.6     .12       0    5477     .16       0  5744.4     .12       0
  5910.9     .16       0  6101.4     .12       0  6172.3     .16       0
    6273     .05       0  6317.9     .16       0
Bank Sta=4895.7,5046.8
XS Rating Curve= 0 ,0
Exp/Cntr=0.3,0.1

Chan Stop Cuts=-1
Use User Specified Reach Order=0
Composite Channel Slope=5