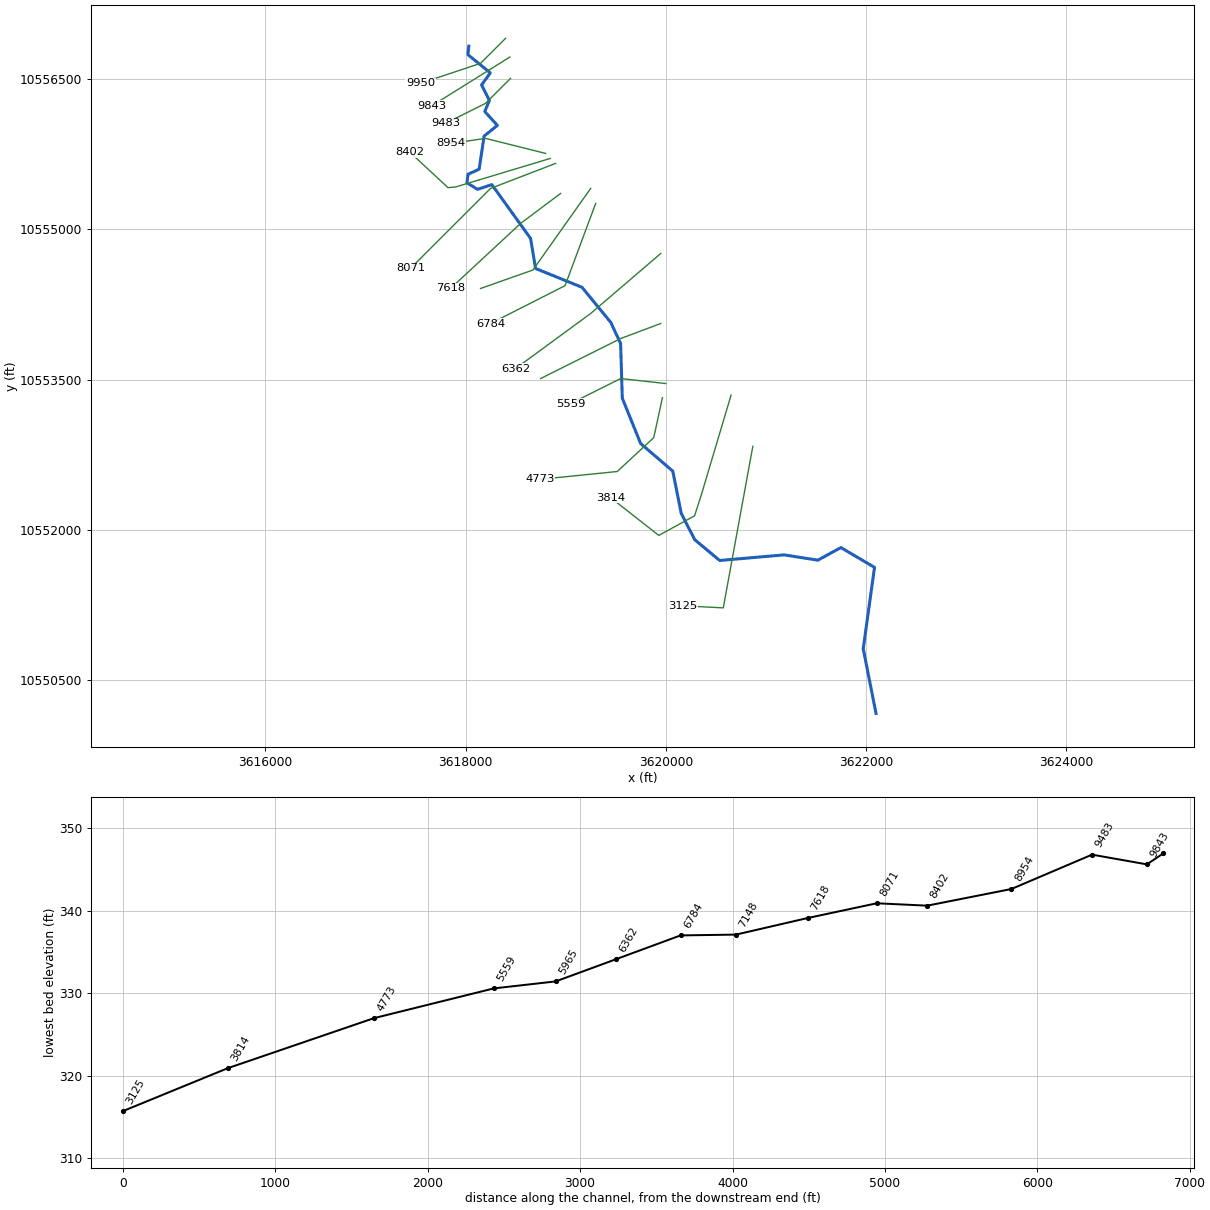
--- UNT 068 IN BUCR.prj (project) ---

Proj Title=UNT 068 IN BUCR Base Level Engineering
Current Plan=p01
Default Exp/Contr=0.3,0.1
English Units
Geom File=g01
Flow File=f01
Plan File=p01
Y Axis Title=Elevation
X Axis Title(PF)=Main Channel Distance
X Axis Title(XS)=Station
BEGIN DESCRIPTION:
UNT 068 IN BUCR
END DESCRIPTION:
DSS Export Rating Curves= 0
DSS Export Rating Curve Sorted= 0
DSS Export Volume Flow Curves= 0
DXF OffsetX= 0
DXF OffsetY= 0
DXF ScaleX= 1
DXF ScaleY= 10

--- UNT 068 IN BUCR.p01 (plan) ---

Plan Title=Multiple Run
Short Identifier=Multiple
Geom File=g01
Flow File=f01
Subcritical Flow
K Sum by GR= 0
Std Step Tol= 0.01
Critical Tol= 0.01
Num of Std Step Trials= 20
Max Error Tol= 0.3
Flow Tol Ratio= 0.001
Split Flow NTrial= 30
Split Flow Tol= 0.02
Split Flow Ratio= 0.02
Log Output Level= 0
Friction Slope Method= 1
Unsteady Friction Slope Method= 2
Unsteady Bridges Friction Slope Method= 1
Parabolic Critical Depth
Global Vel Dist=  1 , 1 , 1
Global Log Level= 0
CheckData=True
Encroach Param= -1, 0, 0, 0
BEGIN DESCRIPTION:
Multiple Run
END DESCRIPTION:

--- UNT 068 IN BUCR.f01 (steady flow) ---

Flow Title=Multiple
Number of Profiles=7
Profile Names=10-year,25-year,50-year,1pct_min,100-year,1pct_plu,500-year
River Rch & RM= UNT 068 IN BUCR,Reach-1,9950
    1183    1636    2011    1805    2441    3301    3582
River Rch & RM= UNT 068 IN BUCR,Reach-1,8071
    1821    2567    3198    2901    3924    5306    5891
Boundary for River Rch & Prof#=UNT 068 IN BUCR,Reach-1,1
Up Type=0
Dn Type=3
Dn Slope=0.005
Boundary for River Rch & Prof#=UNT 068 IN BUCR,Reach-1,2
Up Type=0
Dn Type=3
Dn Slope=0.005
Boundary for River Rch & Prof#=UNT 068 IN BUCR,Reach-1,3
Up Type=0
Dn Type=3
Dn Slope=0.005
Boundary for River Rch & Prof#=UNT 068 IN BUCR,Reach-1,4
Up Type=0
Dn Type=3
Dn Slope=0.005
Boundary for River Rch & Prof#=UNT 068 IN BUCR,Reach-1,5
Up Type=0
Dn Type=3
Dn Slope=0.005
Boundary for River Rch & Prof#=UNT 068 IN BUCR,Reach-1,6
Up Type=0
Dn Type=3
Dn Slope=0.005
Boundary for River Rch & Prof#=UNT 068 IN BUCR,Reach-1,7
Up Type=0
Dn Type=3
Dn Slope=0.005

--- UNT 068 IN BUCR.g01 (geometry) ---

Geom Title=Existing Conditions
Program Version=4.10

River Reach=UNT 068 IN BUCR ,Reach-1
Reach XY= 30
       3618032.5       10556832.       3618023.5       10556747.
       3618247.5       10556565.       3618160.5       10556445.
       3618238.5       10556290.        3618192.       10556179.
      3618317.75       10556040.       3618185.5       10555933.
       3618135.5       10555602.        3618025.       10555552.
       3618013.5       10555467.        3618120.       10555401.
        3618263.       10555448.      3618649.61     10554910.19
      3618699.61     10554610.19        3619163.       10554422.
      3619450.75       10554071.      3619548.75       10553860.
       3619565.5       10553314.       3619748.5       10552861.
      3620069.75       10552585.      3620154.25       10552162.
      3620288.75       10551900.        3620538.       10551692.
       3621182.5       10551748.       3621518.5       10551695.
        3621749.       10551821.       3622084.5       10551623.
        3621972.       10550810.       3622099.5       10550164.

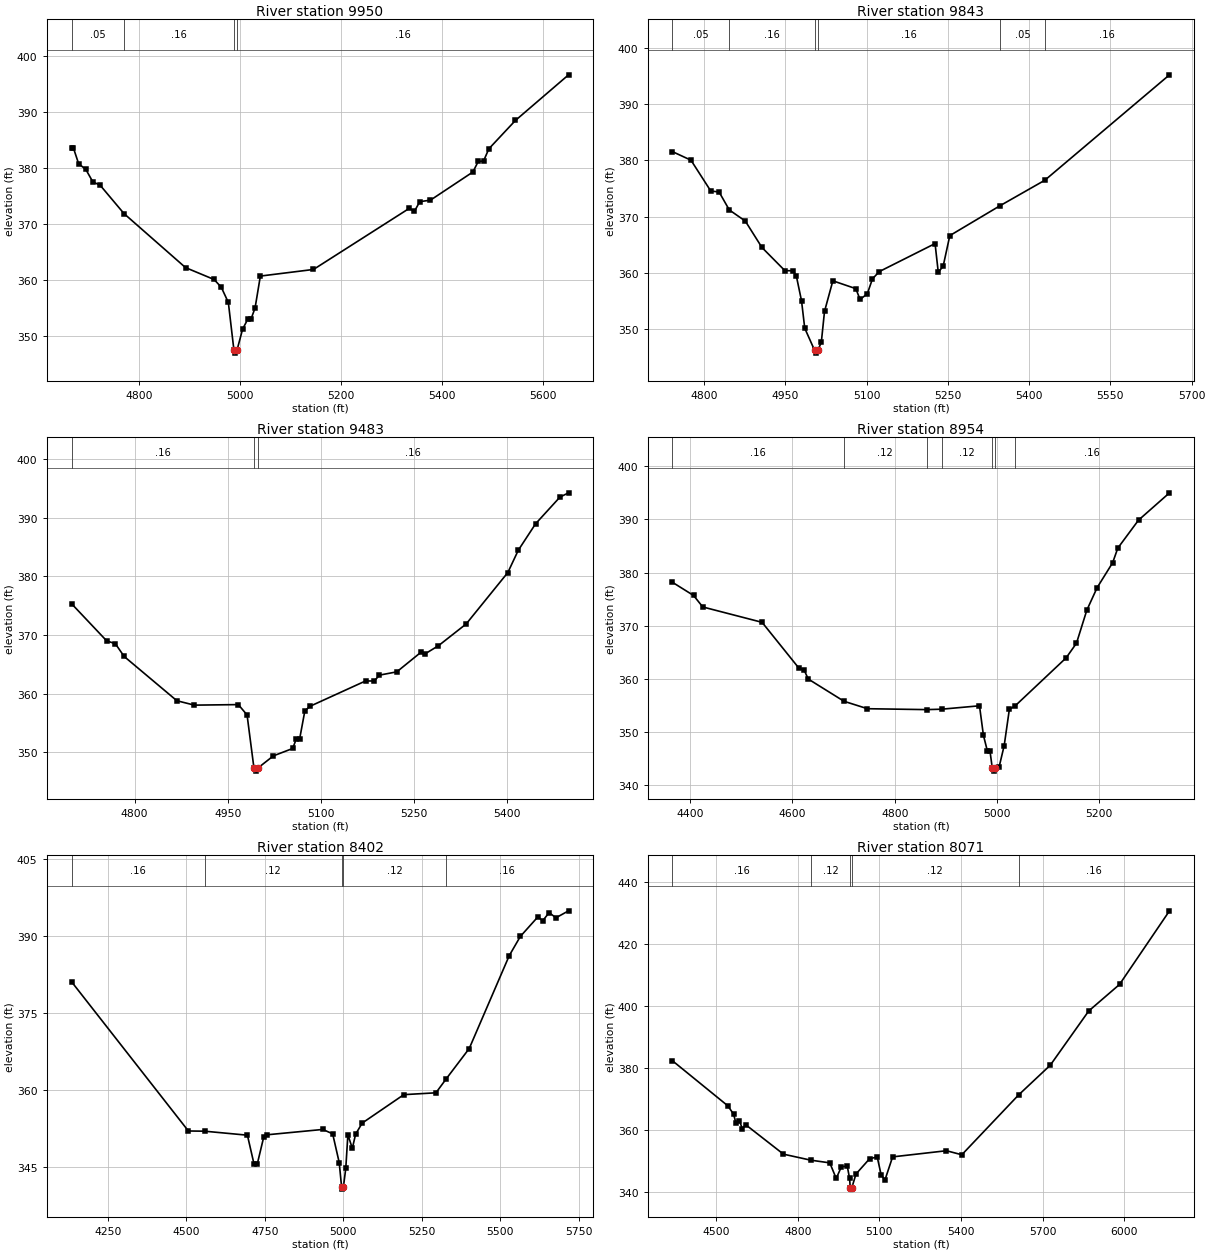
Type RM Length L Ch R = 1 ,9950    ,107,107,107
BEGIN DESCRIPTION:
UNT 068 IN BUCR 12.0
END DESCRIPTION:
XS GIS Cut Line= 3
      3618399.59     10556910.17      3618149.61     10556660.19
      3617549.59     10556460.18
#Sta/Elev= 30
  4665.5  383.65    4669  383.65  4679.6  380.77  4693.8  379.76  4707.9  377.51
    4722  376.96  4769.6  371.87  4891.7  362.23  4948.3  360.11  4962.5  358.74
  4976.6  356.01  4987.7  347.47  4990.5  346.97  4993.7  347.47  5004.9  351.26
  5015.5  353.08  5021.7  353.08  5029.6  355.02  5040.1  360.72  5145.5   361.9
  5335.3  372.79  5345.8  372.27  5356.3     374  5377.4  374.26  5461.7  379.29
  5472.3  381.17  5482.8  381.24  5493.4  383.43  5546.1  388.49  5651.5  396.63
#Mann= 4 ,-1 , 0
  4665.5     .05       0  4769.6     .16       0  4987.7     .07       0
  4993.7     .16       0
Bank Sta=4987.7,4993.7
XS Rating Curve= 0 ,0
Exp/Cntr=0.3,0.1

Type RM Length L Ch R = 1 ,9843    ,360,360,360
BEGIN DESCRIPTION:
Mapping XS 9333ad54
END DESCRIPTION:
XS GIS Cut Line= 3
      3618443.18     10556723.55      3618054.25     10556480.47
       3617665.4     10556237.44
#Sta/Elev= 30
  4741.9  381.58  4776.1  380.05  4812.6  374.56    4828  374.38  4846.8  371.18
  4876.3   369.2    4907  364.49  4949.4  360.35  4964.7  360.33  4970.6  359.36
  4980.1  354.97    4986  350.09  5004.2  346.14    5007  345.64  5010.2  346.14
  5016.6  347.57  5022.5  353.08  5037.9  358.54  5080.3  357.14  5088.1  355.21
  5101.5  356.23    5111  358.89  5123.5  360.18  5226.5  365.18  5232.4  360.07
  5241.4  361.13  5253.7   366.6    5346  371.91  5429.1  376.48  5659.1  395.28
#Mann= 6 ,-1 , 0
  4741.9     .05       0  4846.8     .16       0  5004.2     .07       0
  5010.2     .16       0    5346     .05       0  5429.1     .16       0
Bank Sta=5004.2,5010.2
XS Rating Curve= 0 ,0
Exp/Cntr=0.3,0.1

Type RM Length L Ch R = 1 ,9483    ,529,529,529
BEGIN DESCRIPTION:
UNT 068 IN BUCR 11.0
END DESCRIPTION:
XS GIS Cut Line= 3
      3618449.58     10556510.16      3618199.61     10556260.19
      3617799.63      10556060.2
#Sta/Elev= 30
  4698.5  375.34    4755  369.02  4769.2  368.51  4783.3  366.35  4868.2  358.81
  4896.4  358.06  4967.2  358.15  4981.3  356.39  4992.4  347.32  4995.2  346.82
  4998.4  347.32  5023.7  349.42  5054.8  350.68  5060.4  352.25    5066  352.31
  5074.4  357.09  5082.8  357.87  5172.2  362.18  5186.2  362.17  5194.6  363.17
  5222.5  363.73  5261.6  367.08  5267.2  366.74  5289.6  368.18  5334.3  371.89
  5401.4  380.65  5418.2  384.44  5446.1  388.95  5485.3  393.49  5499.2  394.22
#Mann= 3 ,-1 , 0
  4698.5     .16       0  4992.4     .07       0  4998.4     .16       0
Bank Sta=4992.4,4998.4
XS Rating Curve= 0 ,0
Exp/Cntr=0.3,0.1

Type RM Length L Ch R = 1 ,8954    ,552,552,552
BEGIN DESCRIPTION:
UNT 068 IN BUCR 10.0
END DESCRIPTION:
XS GIS Cut Line= 3
      3618799.65     10555760.18      3618199.61     10555910.19
      3617849.57     10555860.18
#Sta/Elev= 30
  4365.3  378.17  4406.6  375.69  4424.6  373.53  4540.6  370.64  4612.7  362.01
    4623  361.64  4630.8  359.98  4700.8  355.79  4746.7  354.39  4862.3  354.22
  4891.8   354.3  4965.8  354.94  4973.5  349.39  4981.2  346.45  4986.3  346.45
  4990.9  343.15  4993.7  342.65  4996.9  343.15    5004  343.36  5014.1  347.46
  5024.2  354.26  5035.7  354.94  5135.3  363.96  5155.5  366.72  5175.7  372.92
  5195.9  377.17  5226.2  381.85  5236.3   384.6  5276.8  389.86  5337.4     395
#Mann= 7 ,-1 , 0
  4365.3     .16       0  4700.8     .12       0  4862.3     .16       0
  4891.8     .12       0  4990.9     .07       0  4996.9     .12       0
  5035.7     .16       0
Bank Sta=4990.9,4996.9
XS Rating Curve= 0 ,0
Exp/Cntr=0.3,0.1

Type RM Length L Ch R = 1 ,8402    ,331,331,331
BEGIN DESCRIPTION:
UNT 068 IN BUCR 9.0
END DESCRIPTION:
XS GIS Cut Line= 4
      3618845.97     10555709.65      3617901.48     10555424.92
      3617825.09     10555417.97      3617443.85     10555771.49
#Sta/Elev= 30
  4134.3  381.05  4506.5  351.96  4558.1  351.92  4694.5  351.14  4715.4  345.57
  4725.8  345.49  4746.7  350.84  4757.2  351.22  4934.7  352.26  4966.1   351.4
  4986.9  345.81  4994.4  341.13  4997.1  340.63  5000.4  341.13  5007.8  344.66
  5014.5  351.23  5028.7  348.58  5039.2  351.34  5060.1   353.5  5192.7  359.04
    5295   359.4  5327.5   362.1    5401  368.03  5528.5  386.13  5563.7  389.86
  5620.4  393.73  5634.6  392.89  5655.6  394.52  5677.1   393.5  5717.4  394.86
#Mann= 5 ,-1 , 0
  4134.3     .16       0  4558.1     .12       0  4994.4     .07       0
  5000.4     .12       0  5327.5     .16       0
Bank Sta=4994.4,5000.4
XS Rating Curve= 0 ,0
Exp/Cntr=0.3,0.1

Type RM Length L Ch R = 1 ,8071    ,453,453,453
BEGIN DESCRIPTION:
UNT 068 IN BUCR 8.0
END DESCRIPTION:
XS GIS Cut Line= 3
      3618899.62     10555660.19      3618249.61     10555410.19
      3617449.61     10554610.19
#Sta/Elev= 30
    4339  382.27  4542.6  367.76    4564  365.05  4572.6  362.07  4585.4  362.94
  4596.2  360.33  4607.9   361.7  4747.2  352.18  4846.9  350.26  4917.6  349.38
  4941.2  344.36  4960.4  348.15  4981.9  348.32  4990.4  344.35  4992.8  341.42
  4995.5  340.92  4998.8  341.42    5014   345.8  5063.7  350.68    5092   351.3
  5106.1  345.63  5120.3  343.83  5148.6  351.31  5346.6  353.29  5403.1  351.99
    5612  371.27  5728.4  380.84  5869.8  398.31    5983  406.85  6166.8  430.57
#Mann= 5 ,-1 , 0
    4339     .16       0  4846.9     .12       0  4992.8     .07       0
  4998.8     .12       0    5612     .16       0
Bank Sta=4992.8,4998.8
XS Rating Curve= 0 ,0
Exp/Cntr=0.3,0.1

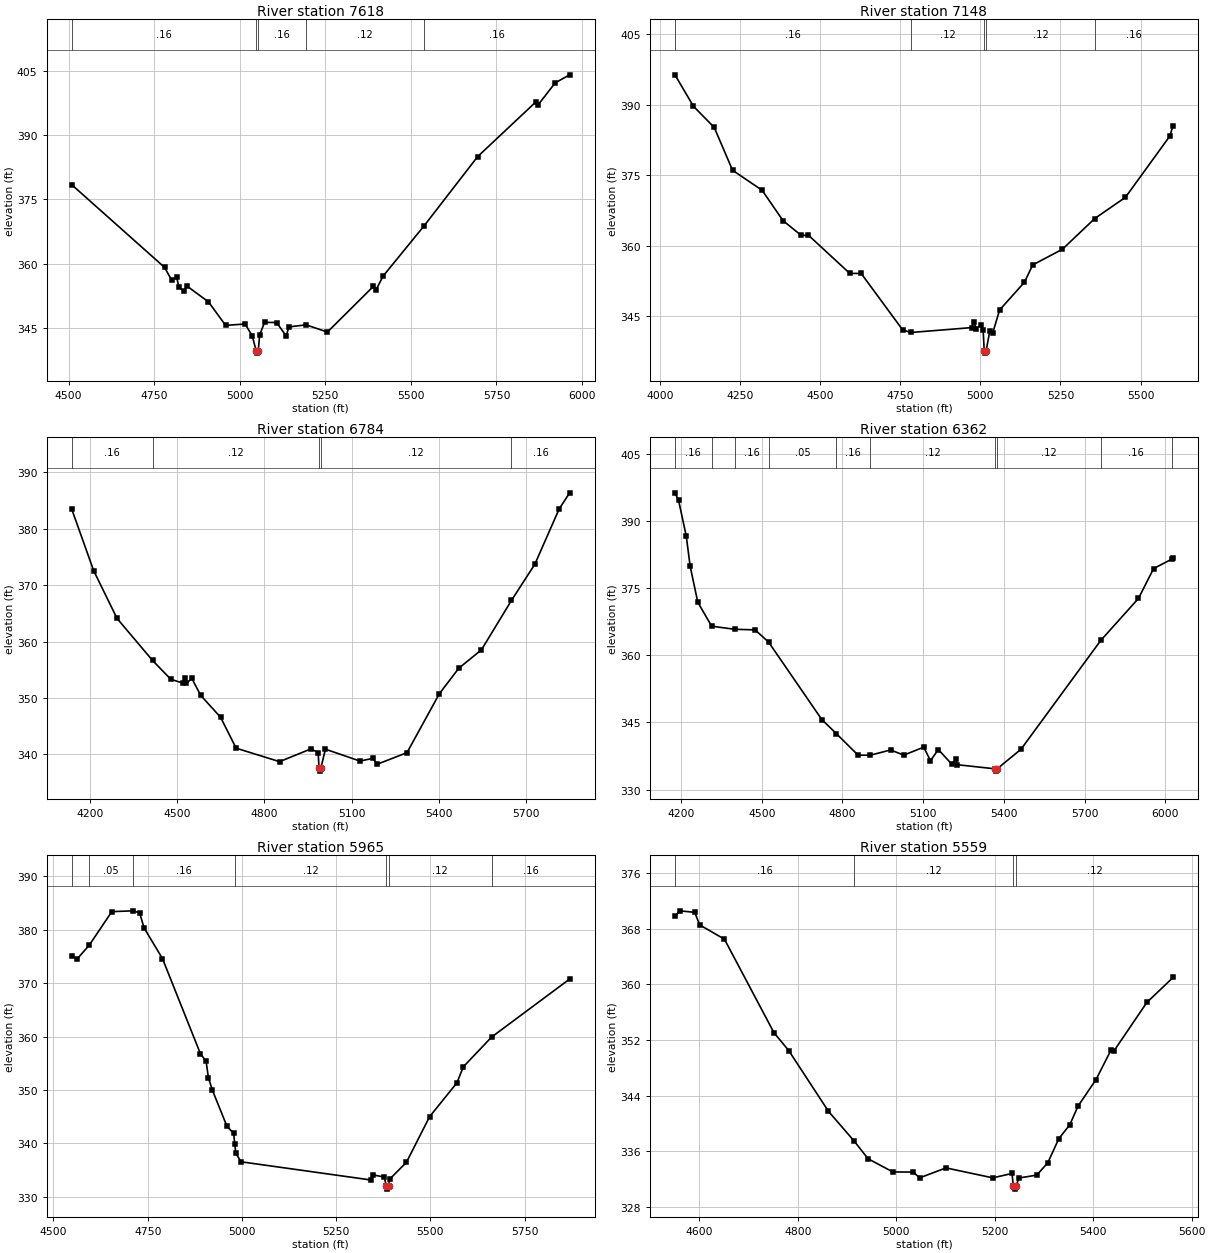
Type RM Length L Ch R = 1 ,7618    ,470,470,470
BEGIN DESCRIPTION:
UNT 068 IN BUCR 7.0
END DESCRIPTION:
XS GIS Cut Line= 3
      3618949.63      10555360.2      3618549.61     10555060.19
      3617849.59     10554410.17
#Sta/Elev= 30
  4508.6  378.48  4780.5  359.13  4801.3  356.12  4815.9   356.8  4822.2  354.46
  4836.7  353.65  4845.1  354.82  4908.6   351.1  4958.6  345.61  5015.7  345.93
  5036.7  343.12  5047.9  339.63  5050.6  339.13  5053.9  339.63  5058.2   343.4
  5072.4  346.31  5107.6  346.28  5135.9   343.1  5143.2  345.25  5193.7  345.73
  5256.1  344.05  5390.7  354.74  5397.8  353.84  5418.8  357.12  5538.9  368.88
  5694.9     385  5864.9  397.76  5871.8  397.11  5921.6  402.23  5963.9   404.1
#Mann= 5 ,-1 , 0
  4508.6     .16       0  5047.9     .07       0  5053.9     .16       0
  5193.7     .12       0  5538.9     .16       0
Bank Sta=5047.9,5053.9
XS Rating Curve= 0 ,0
Exp/Cntr=0.3,0.1

Type RM Length L Ch R = 1 ,7148    ,364,364,364
BEGIN DESCRIPTION:
UNT 068 IN BUCR 6.0
END DESCRIPTION:
XS GIS Cut Line= 3
      3619249.63     10555410.22      3618673.02     10554594.99
      3618149.63      10554410.2
#Sta/Elev= 30
  4047.5   396.4  4105.4  389.69    4170  385.21  4227.3  376.07  4319.5  371.81
  4384.8  365.32  4441.4  362.21    4464  362.23  4592.8  354.11  4628.5  354.09
    4758  342.05  4784.2  341.52  4973.2  342.56  4979.3  343.82  4987.9  342.34
  5002.7  343.12  5008.9  341.95  5012.2  337.62  5014.9  337.12  5018.2  337.62
  5029.8  341.93  5038.4  341.34  5060.3  346.32  5137.7  352.22  5163.3   355.9
  5256.1  359.25  5356.9  365.79  5452.7  370.31    5591  383.34  5601.1  385.58
#Mann= 5 ,-1 , 0
  4047.5     .16       0  4784.2     .12       0  5012.2     .07       0
  5018.2     .12       0  5356.9     .16       0
Bank Sta=5012.2,5018.2
XS Rating Curve= 0 ,0
Exp/Cntr=0.3,0.1

Type RM Length L Ch R = 1 ,6784    ,422,422,422
BEGIN DESCRIPTION:
UNT 068 IN BUCR 5.0
END DESCRIPTION:
XS GIS Cut Line= 3
       3619299.6     10555260.18       3618994.2     10554438.74
      3618249.58     10554060.17
#Sta/Elev= 30
  4137.1  383.56    4213  372.57  4293.3   364.1  4415.2  356.65  4478.5  353.29
  4520.2  352.63  4525.5  353.62  4531.8  352.59  4550.5  353.45  4580.9  350.45
  4649.2  346.57  4702.5  341.09  4851.9   338.7  4959.4  340.96  4984.4  340.32
  4987.6  337.52  4990.3  337.02  4993.6  337.52  5009.4  340.91  5128.4   338.8
  5172.9   339.3  5186.9  338.23  5289.8   340.3    5401  350.75  5467.8  355.27
  5545.6  358.53  5648.7  367.29  5729.2  373.72  5812.6  383.51  5848.8  386.37
#Mann= 5 ,-1 , 0
  4137.1     .16       0  4415.2     .12       0  4987.6     .07       0
  4993.6     .12       0  5648.7     .16       0
Bank Sta=4987.6,4993.6
XS Rating Curve= 0 ,0
Exp/Cntr=0.3,0.1

Type RM Length L Ch R = 1 ,6362    ,397,397,397
BEGIN DESCRIPTION:
UNT 068 IN BUCR 4.0
END DESCRIPTION:
XS GIS Cut Line= 3
      3619949.59     10554760.17      3619249.61     10554160.19
       3618499.6     10553610.18
#Sta/Elev= 30
  4177.1  396.24  4190.8  394.54  4219.3  386.58  4233.6   379.9  4262.1  371.83
  4313.7  366.48  4399.3  365.79  4475.1  365.66  4525.3  362.94  4723.1  345.66
  4777.3  342.51  4858.1   337.7  4903.4  337.69  4978.8  338.86  5028.2  337.71
  5102.1  339.49  5127.2  336.47  5156.5  338.96  5206.7  335.67  5221.3  336.77
  5227.5  335.57  5368.8  334.64  5371.6  334.14  5374.8  334.64  5463.7  339.01
  5760.4   363.3  5900.6  372.68  5956.9  379.34  6023.9  381.43  6029.1  381.72
#Mann= 10 ,-1 , 0
  4177.1     .16       0  4313.7     .12       0  4399.3     .16       0
  4525.3     .05       0  4777.3     .16       0  4903.4     .12       0
  5368.8     .07       0  5374.8     .12       0  5760.4     .16       0
  6023.9     .05       0
Bank Sta=5368.8,5374.8
XS Rating Curve= 0 ,0
Exp/Cntr=0.3,0.1

Type RM Length L Ch R = 1 ,5965    ,406,406,406
BEGIN DESCRIPTION:
UNT 068 IN BUCR 3.0
END DESCRIPTION:
XS GIS Cut Line= 3
      3619949.62     10554060.19      3619549.61     10553910.19
      3618749.64     10553510.21
#Sta/Elev= 30
    4548  375.08  4563.1  374.57  4594.6   377.1  4654.8  383.41  4711.2  383.56
  4728.7  383.17  4740.2  380.38  4789.2  374.61  4889.8  356.81  4904.9  355.39
  4911.1   352.3  4921.8  349.95  4960.1  343.23    4978  341.88  4980.9  339.96
  4983.6  338.18  4997.6  336.56  5341.4  333.16    5347  334.11  5377.7  333.71
  5383.1  331.94  5385.8  331.44  5389.1  331.94  5391.7  333.28  5436.4  336.46
  5497.9     345  5570.6  351.37  5587.3  354.34  5662.5  359.92  5869.6  370.79
#Mann= 7 ,-1 , 0
    4548     .08       0  4594.6     .05       0  4711.2     .16       0
  4980.9     .12       0  5383.1     .07       0  5389.1     .12       0
  5662.5     .16       0
Bank Sta=5383.1,5389.1
XS Rating Curve= 0 ,0
Exp/Cntr=0.3,0.1

Type RM Length L Ch R = 1 ,5559    ,786,786,786
BEGIN DESCRIPTION:
UNT 068 IN BUCR 2.0
END DESCRIPTION:
XS GIS Cut Line= 3
      3619999.57     10553460.19      3619549.61     10553510.19
      3619049.57     10553260.17
#Sta/Elev= 30
  4550.4  369.84  4560.4  370.58  4590.6  370.36  4600.7  368.56    4651   366.5
  4751.6  353.07  4781.8  350.48  4862.3  341.77  4914.8  337.47  4942.8  334.95
  4993.1  333.06  5033.9  333.04  5047.9  332.22    5101  333.64    5196  332.21
  5235.1  332.84  5237.7  331.09  5240.5  330.59  5243.7  331.09  5249.1  332.19
  5285.4   332.6  5307.8  334.38  5330.2  337.84  5352.5  339.84  5369.3  342.53
  5405.6  346.31  5436.4   350.6    5442  350.43    5509  357.41  5562.2     361
#Mann= 4 ,-1 , 0
  4550.4     .16       0  4914.8     .12       0  5237.7     .07       0
  5243.7     .12       0
Bank Sta=5237.7,5243.7
XS Rating Curve= 0 ,0
Exp/Cntr=0.3,0.1

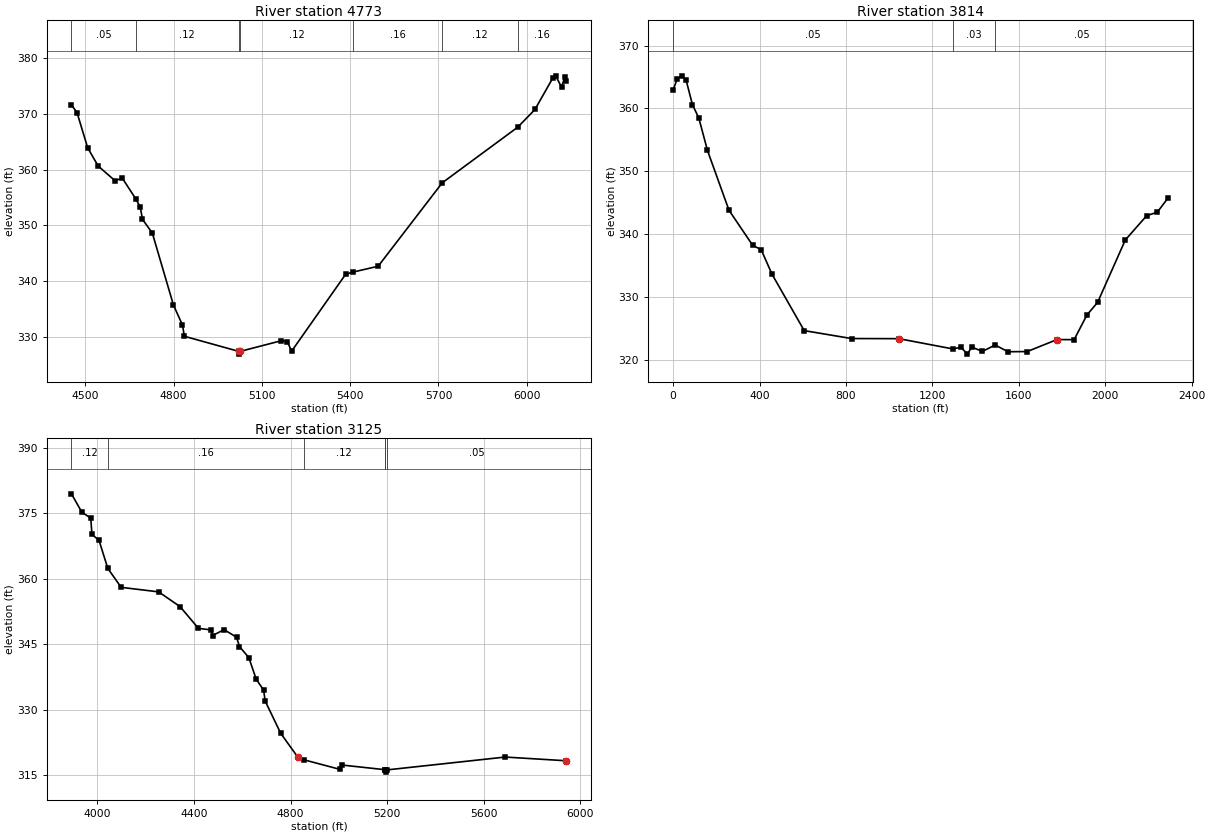
Type RM Length L Ch R = 1 ,4773    ,959,959,959
BEGIN DESCRIPTION:
Mapping XS f0655a5f
END DESCRIPTION:
XS GIS Cut Line= 4
      3619966.42     10553318.92      3619879.62     10552919.64
      3619515.03      10552581.1       3618743.5     10552503.08
#Sta/Elev= 30
  4452.8  371.58    4472  370.16  4508.1  363.88  4543.6  360.63  4601.2  357.99
  4625.5  358.47  4672.1   354.7  4686.9  353.24  4694.3  351.09  4727.8  348.62
  4799.4  335.77  4830.1  332.19  4836.6  330.17    5021  327.48  5023.7  326.98
    5027  327.48  5165.2  329.37  5186.7  329.21  5200.9   327.5  5384.5  341.26
  5409.1  341.65    5495   342.7  5712.7  357.62  5969.9   367.6  6027.7  370.74
  6088.1  376.34  6098.1  376.76  6118.3  374.72  6128.3  376.47  6134.4  375.88
#Mann= 7 ,-1 , 0
  4452.8     .05       0  4672.1     .12       0    5021     .07       0
    5027     .12       0  5409.1     .16       0  5712.7     .12       0
  5969.9     .16       0
Bank Sta=5021,5027
XS Rating Curve= 0 ,0
Exp/Cntr=0.3,0.1

Type RM Length L Ch R = 1 ,3814    ,689,689,689
BEGIN DESCRIPTION:
Mapping XS e8316c45
END DESCRIPTION:
XS GIS Cut Line= 5
     3620652.185    10553344.986     3620357.046    10552355.403
     3620287.602    10552138.389     3619930.159    10551942.544
     3619447.521    10552321.016
#Sta/Elev= 30
       0  362.94    19.9  364.73   39.79  365.19   59.69   364.6   89.54  360.62
  119.38  358.45  159.18  353.32  258.66  343.81   368.1  338.24  407.89  337.52
  457.64  333.64  606.87  324.65  825.74  323.39 1044.61  323.37  1293.1  321.75
  1332.6  321.98 1362.22  320.91 1381.97  322.03 1431.34  321.34 1490.59  322.36
 1549.84  321.29 1638.71  321.32 1776.91  323.23 1855.87  323.21  1915.1  327.14
 1964.45  329.14 2092.77  339.08 2191.47  342.93 2240.82   343.5 2290.18  345.74
#Mann= 3 ,-1 , 0
       0     .05       0  1293.1     .03       0 1490.59     .05       0
Bank Sta=1044.61,1776.91
XS Rating Curve= 0 ,0
Exp/Cntr=0.3,0.1

Type RM Length L Ch R = 1 ,3125    ,0,0,0
BEGIN DESCRIPTION:
UNT 068 IN BUCR 1.0
END DESCRIPTION:
XS GIS Cut Line= 3
      3620869.19     10552832.79      3620574.06     10551218.25
      3620166.72     10551239.83
#Sta/Elev= 30
  3892.8  379.41  3936.1   375.2  3972.8  373.85  3977.9  370.13  4007.3  368.73
  4043.5  362.33  4098.8     358  4254.1  356.96  4342.7  353.58  4418.9   348.6
  4472.1  348.25  4477.2  346.97  4525.3  348.31  4576.5  346.57  4588.7  344.45
  4627.4   341.9  4657.9  336.97  4688.4  334.48  4695.2  331.95  4759.5  324.56
  4830.7  319.08  4854.2  318.53  5003.5  316.34  5013.7  317.31  5190.7  316.25
  5191.5  316.19  5194.2  315.69  5197.5  316.19  5688.8  319.14    5942  318.29
#Mann= 6 ,-1 , 0
  3892.8     .12       0  4043.5     .16       0  4854.2     .12       0
  5190.7     .05       0  5191.5     .07       0  5197.5     .05       0
Bank Sta=4830.7,5942
XS Rating Curve= 0 ,0
Exp/Cntr=0.3,0.1

Chan Stop Cuts=-1
Use User Specified Reach Order=0
Composite Channel Slope=5