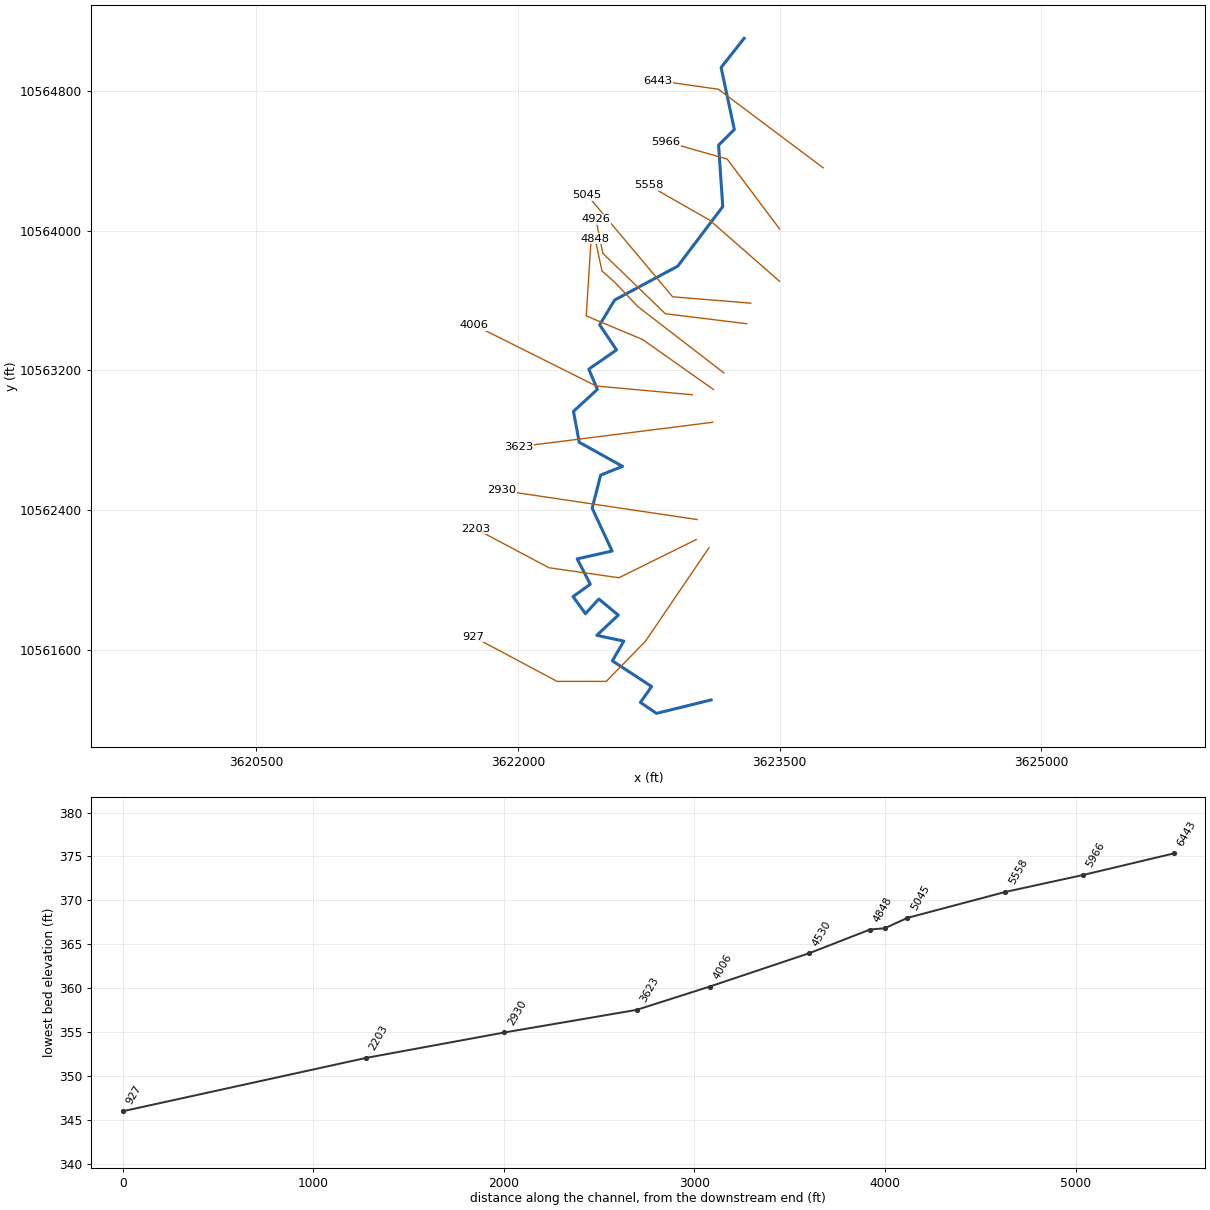
--- UNT 071 IN BUCR.prj (project) ---

Proj Title=UNT 071 IN BUCR Base Level Engineering
Current Plan=p01
Default Exp/Contr=0.3,0.1
English Units
Geom File=g01
Flow File=f01
Plan File=p01
BEGIN DESCRIPTION:
UNT 071 IN BUCR
END DESCRIPTION:

--- UNT 071 IN BUCR.p01 (plan) ---

Plan Title=Multiple Run
Short Identifier=Multiple
Geom File=g01
Flow File=f01
Subcritical Flow
K Sum by GR= 0
Std Step Tol= 0.01
Critical Tol= 0.01
Num of Std Step Trials= 20
Max Error Tol= 0.3
Flow Tol Ratio= 0.001
Split Flow NTrial= 30
Split Flow Tol= 0.02
Split Flow Ratio= 0.02
Log Output Level= 0
Friction Slope Method= 1
Unsteady Friction Slope Method= 2
Unsteady Bridges Friction Slope Method= 1
Parabolic Critical Depth
Global Vel Dist=  1 , 1 , 1
Global Log Level= 0
CheckData=True
Encroach Param= -1, 0, 0, 0
BEGIN DESCRIPTION:
Multiple Run
END DESCRIPTION:

--- UNT 071 IN BUCR.f01 (steady flow) ---

Flow Title=Multiple
Number of Profiles=7
Profile Names=10-year,25-year,50-year,1pct_min,100-year,1pct_plu,500-year
River Rch & RM= UNT 071 IN BUCR,Reach-1,6443
    1161    1602    1968    1763    2385    3225    3489
Boundary for River Rch & Prof#=UNT 071 IN BUCR,Reach-1,1
Up Type=0
Dn Type=3
Dn Slope=0.005
Boundary for River Rch & Prof#=UNT 071 IN BUCR,Reach-1,2
Up Type=0
Dn Type=3
Dn Slope=0.005
Boundary for River Rch & Prof#=UNT 071 IN BUCR,Reach-1,3
Up Type=0
Dn Type=3
Dn Slope=0.005
Boundary for River Rch & Prof#=UNT 071 IN BUCR,Reach-1,4
Up Type=0
Dn Type=3
Dn Slope=0.005
Boundary for River Rch & Prof#=UNT 071 IN BUCR,Reach-1,5
Up Type=0
Dn Type=3
Dn Slope=0.005
Boundary for River Rch & Prof#=UNT 071 IN BUCR,Reach-1,6
Up Type=0
Dn Type=3
Dn Slope=0.005
Boundary for River Rch & Prof#=UNT 071 IN BUCR,Reach-1,7
Up Type=0
Dn Type=3
Dn Slope=0.005

--- UNT 071 IN BUCR.g01 (geometry) ---

Geom Title=Existing Conditions

River Reach=UNT 071 IN BUCR,Reach-1
Reach XY= 30
      3623296.50     10565102.00      3623164.75     10564935.00
      3623240.50     10564580.00      3623150.25     10564490.00
      3623174.25     10564138.00      3622916.50     10563797.00
      3622555.00     10563603.00      3622469.00     10563461.00
      3622565.75     10563317.00      3622406.75     10563207.00
      3622456.00     10563091.00      3622319.00     10562965.00
      3622352.00     10562788.00      3622600.25     10562650.00
      3622474.75     10562600.00      3622426.25     10562410.00
      3622540.25     10562165.00      3622340.25     10562120.00
      3622415.50     10561975.00      3622316.75     10561904.00
      3622387.50     10561806.00      3622464.25     10561890.00
      3622575.75     10561798.00      3622452.75     10561682.00
      3622607.50     10561649.00      3622541.75     10561536.00
      3622766.75     10561389.00      3622702.50     10561298.00
      3622794.50     10561235.00      3623107.25     10561312.00

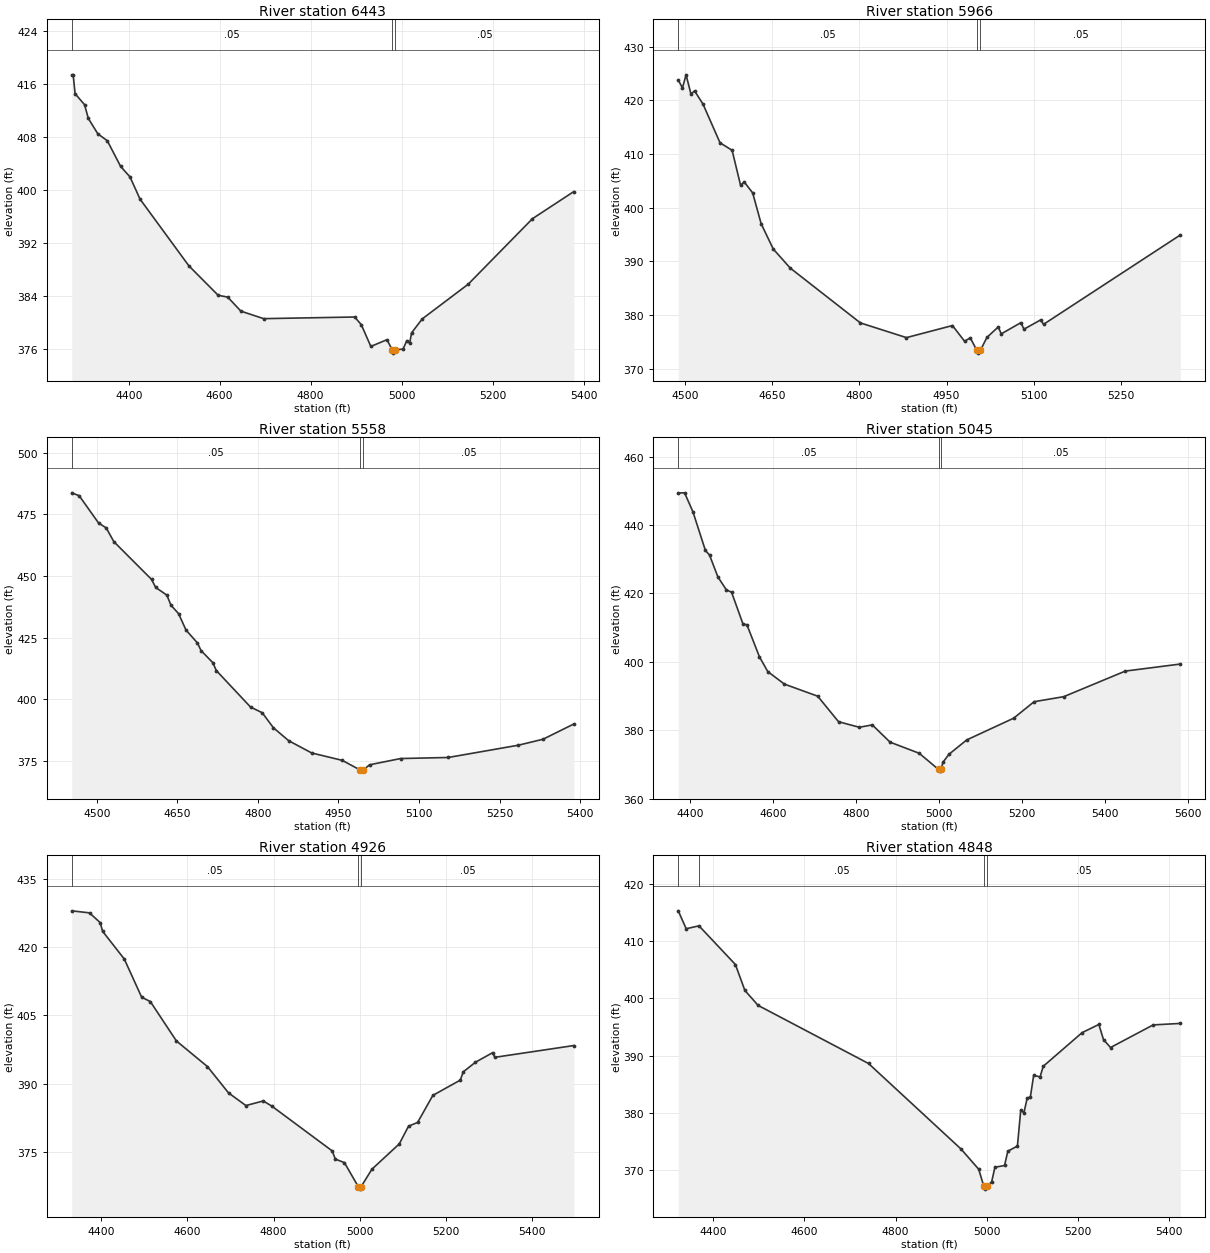
Type RM Length L Ch R = 1,6443,477,477,477
BEGIN DESCRIPTION:
UNT 071 IN BUCR 10.0
END DESCRIPTION:
XS GIS Cut Line= 3
      3623749.58     10564360.21      3623149.61     10564810.19
      3622799.63     10564860.19
#Sta/Elev= 30
  4274.9  417.41  4278.0  417.41  4282.2  414.56  4303.0  412.90  4311.3  410.82
  4332.2  408.49  4353.0  407.45  4382.2  403.58  4403.0  401.97  4424.9  398.63
  4532.2  388.55  4596.7  384.09  4617.6  383.82  4646.7  381.69  4696.7  380.56
  4896.7  380.81  4911.3  379.64  4932.2  376.36  4967.6  377.38  4979.2  375.85
  4981.9  375.35  4985.2  375.85  5003.0  375.96  5011.3  377.24  5017.6  376.86
  5021.7  378.41  5045.1  380.52  5146.1  385.76  5287.5  395.67  5378.4  399.77
#Mann=3,-1,0
  4274.9    0.05       0  4979.2    0.03       0  4985.2    0.05       0
Bank Sta=4979.2,4985.2
Exp/Cntr=0.3,0.1

Type RM Length L Ch R = 1,5966,408,408,408
BEGIN DESCRIPTION:
UNT 071 IN BUCR 9.0
END DESCRIPTION:
XS GIS Cut Line= 3
      3623499.60     10564010.20      3623199.61     10564410.19
      3622849.60     10564510.19
#Sta/Elev= 30
  4488.2  423.77  4495.5  422.31  4501.7  424.74  4510.1  421.16  4516.3  421.75
  4530.9  419.27  4560.1  412.08  4580.9  410.68  4595.5  404.15  4601.7  404.79
  4616.3  402.74  4630.9  396.99  4651.7  392.29  4680.9  388.74  4801.7  378.52
  4880.9  375.78  4960.1  378.03  4980.9  375.11  4990.8  375.73  5002.1  373.39
  5004.8  372.89  5008.1  373.39  5019.4  375.82  5038.9  377.77  5044.1  376.48
  5077.9  378.57  5083.1  377.35  5111.7  379.07  5116.9  378.26  5352.2  394.90
#Mann=3,-1,0
  4488.2    0.05       0  5002.1    0.03       0  5008.1    0.05       0
Bank Sta=5002.1,5008.1
Exp/Cntr=0.3,0.1

Type RM Length L Ch R = 1,5558,513,513,513
BEGIN DESCRIPTION:
UNT 071 IN BUCR 8.0
END DESCRIPTION:
XS GIS Cut Line= 3
      3623499.63     10563710.17      3623099.61     10564060.19
      3622749.65     10564260.16
#Sta/Elev= 30
  4453.6  483.72  4467.4  482.55  4503.5  471.48  4517.7  469.52  4531.9  463.95
  4602.2  448.62  4609.8  445.38  4630.6  442.27  4638.2  438.20  4652.5  434.73
  4666.2  428.14  4687.6  422.88  4694.2  419.82  4716.1  414.91  4722.7  411.70
  4786.3  396.94  4808.1  394.62  4829.0  388.52  4857.5  383.27  4900.2  378.32
  4957.1  375.32  4990.1  371.46  4992.8  370.96  4996.1  371.46  5008.2  373.54
  5065.8  376.06  5154.3  376.49  5284.6  381.45  5330.7  383.87  5388.2  390.06
#Mann=3,-1,0
  4453.6    0.05       0  4990.1    0.03       0  4996.1    0.05       0
Bank Sta=4990.1,4996.1
Exp/Cntr=0.3,0.1

Type RM Length L Ch R = 1,5045,119,119,119
BEGIN DESCRIPTION:
UNT 071 IN BUCR 7.0
END DESCRIPTION:
XS GIS Cut Line= 3
      3623334.89     10563584.92      3622886.99     10563621.37
      3622397.43     10564204.68
#Sta/Elev= 30
  4371.6  449.33  4386.9  449.38  4407.0  443.85  4437.1  432.54  4447.1  431.18
  4467.2  424.80  4487.3  421.08  4500.3  420.29  4527.4  411.15  4537.4  410.76
  4567.5  401.42  4587.6  397.11  4627.7  393.45  4708.0  389.92  4758.2  382.46
  4808.3  380.83  4839.6  381.53  4882.5  376.48  4952.8  373.23  4999.3  368.51
  5002.0  368.01  5005.3  368.51  5010.0  370.58  5024.3  372.91  5067.3  377.13
  5180.5  383.48  5229.9  388.31  5301.4  389.78  5449.8  397.26  5582.5  399.32
#Mann=3,-1,0
  4371.6    0.05       0  4999.3    0.03       0  5005.3    0.05       0
Bank Sta=4999.3,5005.3
Exp/Cntr=0.3,0.1

Type RM Length L Ch R = 1,4926,78,78,78
BEGIN DESCRIPTION:
Mapping XS 2e47170f
END DESCRIPTION:
XS GIS Cut Line= 4
      3623310.52     10563467.14      3622845.20     10563524.43
      3622487.57     10563869.92      3622447.63     10564064.37
#Sta/Elev= 30
  4331.9  428.00  4373.1  427.55  4398.0  425.39  4403.3  423.52  4453.7  417.41
  4494.0  409.02  4514.2  408.05  4574.6  399.40  4646.7  393.76  4695.5  387.98
  4735.8  385.20  4776.1  386.21  4796.0  385.07  4936.0  375.23  4943.2  373.44
  4964.3  372.65  4996.8  367.33  4999.5  366.83  5002.8  367.33  5028.1  371.21
  5091.6  376.77  5113.0  380.66  5134.1  381.49  5169.5  387.44  5233.1  390.79
  5240.0  392.61  5268.3  394.72  5308.0  396.82  5313.1  395.80  5496.5  398.39
#Mann=3,-1,0
  4331.9    0.05       0  4996.8    0.03       0  5002.8    0.05       0
Bank Sta=4996.8,5002.8
Exp/Cntr=0.3,0.1

Type RM Length L Ch R = 1,4848,318,318,318
BEGIN DESCRIPTION:
Mapping XS 7997aa9a
END DESCRIPTION:
XS GIS Cut Line= 5
      3623180.31     10563185.87      3622688.95     10563564.36
      3622553.54     10563706.73      3622482.36     10563769.23
      3622442.44     10563954.94
#Sta/Elev= 30
  4323.2  415.30  4340.7  412.17  4368.7  412.68  4448.6  405.92  4469.4  401.39
  4498.4  398.78  4740.6  388.63  4943.4  373.70  4982.4  370.15  4993.5  367.18
  4996.3  366.68  4999.5  367.18  5010.7  367.94  5017.9  370.50  5039.0  370.81
  5046.2  373.30  5067.3  374.21  5074.6  380.53  5081.5  380.00  5088.7  382.59
  5095.6  382.74  5102.9  386.55  5117.0  386.29  5123.9  388.14  5209.2  394.02
  5245.9  395.45  5256.1  392.80  5271.5  391.42  5365.1  395.37  5424.6  395.63
#Mann=4,-1,0
  4323.2    0.08       0  4368.7    0.05       0  4993.5    0.03       0
  4999.5    0.05       0
Bank Sta=4993.5,4999.5
Exp/Cntr=0.3,0.1

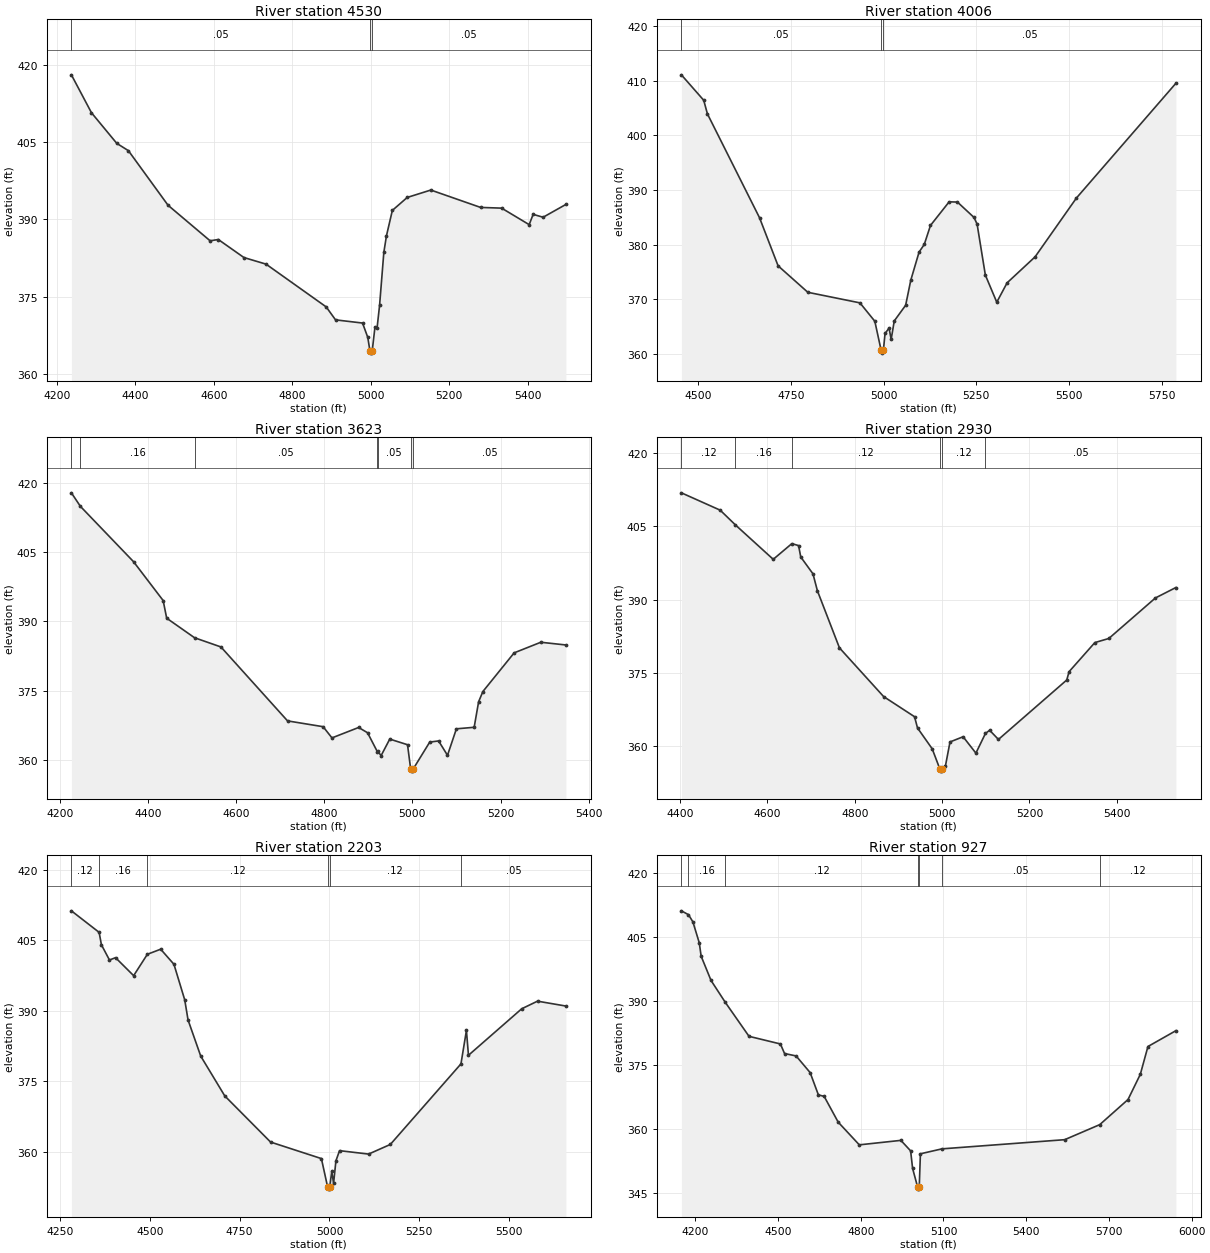
Type RM Length L Ch R = 1,4530,524,524,524
BEGIN DESCRIPTION:
UNT 071 IN BUCR 6.0
END DESCRIPTION:
XS GIS Cut Line= 4
      3623121.35     10563090.14      3622715.12     10563376.58
      3622392.20     10563512.00      3622418.24     10563923.46
#Sta/Elev= 30
  4237.3  418.12  4288.4  410.75  4352.9  404.79  4382.5  403.37  4483.5  392.75
  4590.6  385.84  4611.5  386.09  4676.8  382.58  4733.1  381.30  4886.3  372.98
  4910.1  370.46  4978.9  369.84  4992.2  367.05  4997.6  364.49  5000.3  363.99
  5003.6  364.49  5010.6  369.11  5016.0  368.96  5022.3  373.30  5033.1  383.58
  5039.8  386.81  5054.8  391.75  5092.7  394.27  5152.8  395.71  5279.5  392.33
  5333.2  392.19  5403.3  388.98  5413.4  390.98  5438.8  390.42  5496.8  392.91
#Mann=3,-1,0
  4237.3    0.05       0  4997.6    0.03       0  5003.6    0.05       0
Bank Sta=4997.6,5003.6
Exp/Cntr=0.3,0.1

Type RM Length L Ch R = 1,4006,383,383,383
BEGIN DESCRIPTION:
UNT 071 IN BUCR 5.0
END DESCRIPTION:
XS GIS Cut Line= 3
      3622999.64     10563060.19      3622449.61     10563110.19
      3621749.63     10563460.18
#Sta/Elev= 30
  4453.8  411.06  4514.1  406.41  4524.1  403.92  4664.7  384.94  4714.9  376.14
  4795.2  371.30  4935.8  369.37  4976.0  366.01  4993.1  360.68  4995.8  360.18
  4999.1  360.68  5003.6  363.77  5014.5  364.76  5020.1  362.69  5028.5  366.07
  5059.2  368.93  5073.2  373.54  5095.5  378.66  5109.5  380.05  5126.3  383.53
  5176.6  387.84  5199.0  387.80  5243.7  384.99  5252.1  383.77  5274.4  374.45
  5305.2  369.49  5333.1  373.03  5408.6  377.78  5520.4  388.55  5788.7  409.51
#Mann=3,-1,0
  4453.8    0.05       0  4993.1    0.03       0  4999.1    0.05       0
Bank Sta=4993.1,4999.1
Exp/Cntr=0.3,0.1

Type RM Length L Ch R = 1,3623,693,693,693
BEGIN DESCRIPTION:
UNT 071 IN BUCR 4.0
END DESCRIPTION:
XS GIS Cut Line= 2
      3623116.20     10562902.63      3622003.12     10562762.19
#Sta/Elev= 30
  4226.3  417.91  4246.7  414.98  4367.3  402.97  4434.5  394.54  4442.5  390.71
  4505.7  386.47  4565.6  384.47  4716.7  368.43  4797.4  367.17  4817.5  364.74
  4878.0  367.00  4898.2  365.86  4920.5  361.74  4920.9  361.81  4929.1  360.92
  4948.6  364.48  4988.9  363.26  4996.0  358.03  4998.7  357.53  5002.0  358.03
  5039.3  363.83  5059.4  364.08  5079.6  360.96  5099.8  366.71  5140.1  367.04
  5150.2  372.58  5159.9  374.80  5230.8  383.19  5291.3  385.49  5348.2  384.90
#Mann=7,-1,0
  4226.3    0.12       0  4246.7    0.16       0  4505.7    0.05       0
  4920.5    0.12       0  4920.9    0.05       0  4996.0    0.03       0
  5002.0    0.05       0
Bank Sta=4996,5002
Exp/Cntr=0.3,0.1

Type RM Length L Ch R = 1,2930,727,727,727
BEGIN DESCRIPTION:
UNT 071 IN BUCR 3.0
END DESCRIPTION:
XS GIS Cut Line= 2
      3623027.58     10562345.34      3621907.82     10562512.00
#Sta/Elev= 30
  4403.2  411.88  4492.1  408.33  4527.1  405.30  4613.5  398.28  4656.1  401.49
  4671.5  401.09  4676.5  398.76  4704.5  395.31  4714.6  391.85  4765.1  380.17
  4866.2  370.21  4937.0  366.09  4943.8  363.79  4977.4  359.53  4994.7  355.46
  4997.4  354.96  5000.7  355.46  5007.8  356.05  5018.2  360.93  5048.2  361.99
  5077.5  358.64  5099.3  362.66  5108.9  363.32  5129.1  361.44  5285.5  373.60
  5290.8  375.30  5349.8  381.25  5381.8  382.09  5488.5  390.38  5535.3  392.51
#Mann=6,-1,0
  4403.2    0.12       0  4527.1    0.16       0  4656.1    0.12       0
  4994.7    0.07       0  5000.7    0.12       0  5099.3    0.05       0
Bank Sta=4994.7,5000.7
Exp/Cntr=0.3,0.1

Type RM Length L Ch R = 1,2203,1276,1276,1276
BEGIN DESCRIPTION:
UNT 071 IN BUCR 2.0
END DESCRIPTION:
XS GIS Cut Line= 4
      3623022.45     10562230.77      3622579.70     10562012.00
      3622178.66     10562069.29      3621756.78     10562293.25
#Sta/Elev= 30
  4281.5  411.30  4358.7  406.72  4365.1  404.07  4387.5  400.83  4404.4  401.33
  4454.8  397.50  4493.0  402.05  4530.1  403.13  4567.0  399.92  4597.0  392.35
  4606.3  388.06  4641.6  380.37  4708.5  371.90  4836.0  362.08  4977.5  358.56
  4994.7  352.56  4997.4  352.06  5000.7  352.56  5006.4  355.84  5011.4  353.30
  5017.9  358.08  5028.0  360.25  5108.8  359.52  5169.4  361.57  5366.0  378.72
  5381.2  385.83  5386.9  380.55  5535.1  390.45  5579.1  392.07  5658.1  391.03
#Mann=6,-1,0
  4281.5    0.12       0  4358.7    0.16       0  4493.0    0.12       0
  4994.7    0.07       0  5000.7    0.12       0  5366.0    0.05       0
Bank Sta=4994.7,5000.7
Exp/Cntr=0.3,0.1

Type RM Length L Ch R = 1,927,0,0,0
BEGIN DESCRIPTION:
UNT 071 IN BUCR 1.0
END DESCRIPTION:
XS GIS Cut Line= 5
      3623095.34     10562183.89      3622730.74     10561647.42
      3622506.79     10561418.25      3622225.54     10561418.25
      3621746.38     10561673.45
#Sta/Elev= 30
  4149.6  411.23  4175.4  410.32  4191.4  408.64  4214.5  403.72  4221.3  400.59
  4257.2  394.90  4308.9  389.77  4394.9  381.81  4508.7  380.02  4523.7  377.78
  4565.7  377.21  4616.5  373.31  4646.4  368.09  4667.4  367.73  4718.3  361.69
  4794.8  356.37  4945.6  357.42  4980.9  354.96  4988.1  350.84  5006.2  346.49
  5009.0  345.99  5012.2  346.49  5016.4  354.27  5094.5  355.43  5539.6  357.58
  5666.8  361.11  5769.2  366.99  5813.9  372.91  5841.5  379.42  5942.8  383.13
#Mann=7,-1,0
  4149.6    0.12       0  4175.4    0.16       0  4308.9    0.12       0
  5006.2    0.07       0  5012.2    0.12       0  5094.5    0.05       0
  5666.8    0.12       0
Bank Sta=5006.2,5012.2
Exp/Cntr=0.3,0.1

Chan Stop Cuts=-1