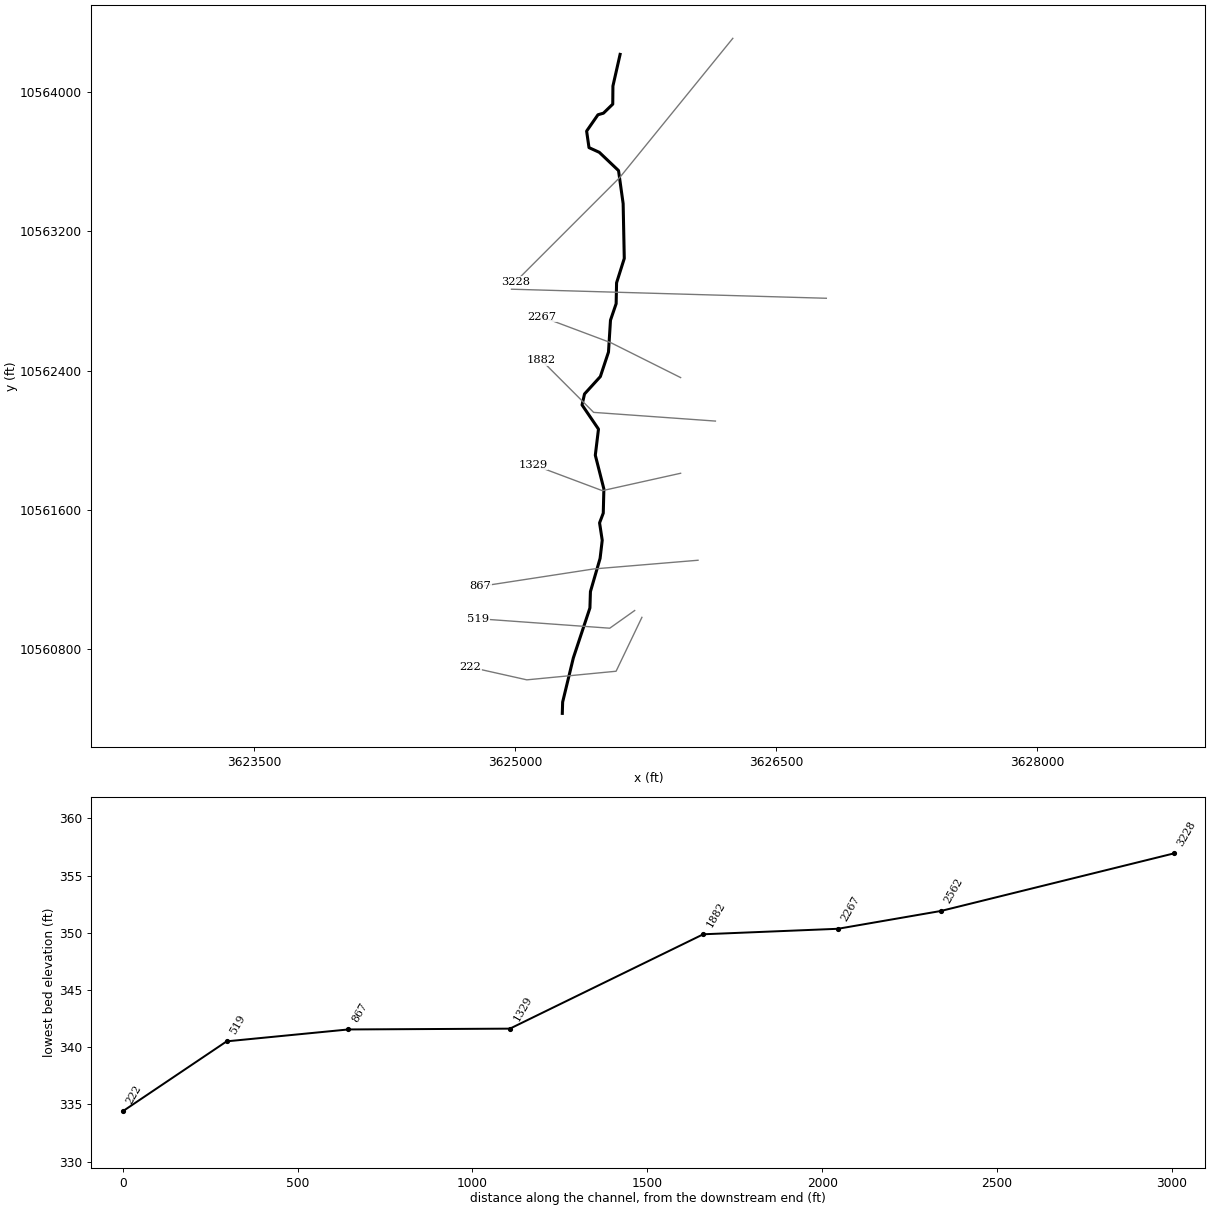
--- UNT 072 IN BUCR.prj (project) ---

Proj Title=UNT 072 IN BUCR Base Level Engineering
Current Plan=p01
Default Exp/Contr=0.3,0.1
English Units
Geom File=g01
Flow File=f01
Plan File=p01
BEGIN DESCRIPTION:
UNT 072 IN BUCR
END DESCRIPTION:

--- UNT 072 IN BUCR.p01 (plan) ---

Plan Title=Multiple Run
Short Identifier=Multiple
Geom File=g01
Flow File=f01
Subcritical Flow
K Sum by GR= 0
Std Step Tol= 0.01
Critical Tol= 0.01
Num of Std Step Trials= 20
Max Error Tol= 0.3
Flow Tol Ratio= 0.001
Split Flow NTrial= 30
Split Flow Tol= 0.02
Split Flow Ratio= 0.02
Log Output Level= 0
Friction Slope Method= 1
Unsteady Friction Slope Method= 2
Unsteady Bridges Friction Slope Method= 1
Parabolic Critical Depth
Global Vel Dist=  1 , 1 , 1
Global Log Level= 0
CheckData=True
Encroach Param= -1, 0, 0, 0
BEGIN DESCRIPTION:
Multiple Run
END DESCRIPTION:

--- UNT 072 IN BUCR.f01 (steady flow) ---

Flow Title=Multiple
Number of Profiles=7
Profile Names=10-year,25-year,50-year,1pct_min,100-year,1pct_plu,500-year
River Rch & RM= UNT 072 IN BUCR,Reach-1,3228
    1487    2098    2617    2382    3221    4356    4863
Boundary for River Rch & Prof#=UNT 072 IN BUCR,Reach-1,1
Up Type=0
Dn Type=3
Dn Slope=0.005
Boundary for River Rch & Prof#=UNT 072 IN BUCR,Reach-1,2
Up Type=0
Dn Type=3
Dn Slope=0.005
Boundary for River Rch & Prof#=UNT 072 IN BUCR,Reach-1,3
Up Type=0
Dn Type=3
Dn Slope=0.005
Boundary for River Rch & Prof#=UNT 072 IN BUCR,Reach-1,4
Up Type=0
Dn Type=3
Dn Slope=0.005
Boundary for River Rch & Prof#=UNT 072 IN BUCR,Reach-1,5
Up Type=0
Dn Type=3
Dn Slope=0.005
Boundary for River Rch & Prof#=UNT 072 IN BUCR,Reach-1,6
Up Type=0
Dn Type=3
Dn Slope=0.005
Boundary for River Rch & Prof#=UNT 072 IN BUCR,Reach-1,7
Up Type=0
Dn Type=3
Dn Slope=0.005

--- UNT 072 IN BUCR.g01 (geometry) ---

Geom Title=Existing Conditions

River Reach=UNT 072 IN BUCR,Reach-1
Reach XY= 30
      3625601.75     10564218.00      3625560.50     10564036.00
      3625559.50     10563932.00      3625506.00     10563880.00
      3625474.50     10563871.00      3625409.25     10563777.00
      3625423.00     10563682.00      3625482.25     10563655.00
      3625592.75     10563550.00      3625619.25     10563360.00
      3625625.75     10563045.00      3625581.50     10562905.00
      3625579.00     10562785.00      3625546.50     10562690.00
      3625535.00     10562507.00      3625488.25     10562366.00
      3625397.25     10562266.00      3625383.00     10562203.00
      3625477.50     10562064.00      3625459.25     10561914.00
      3625508.50     10561720.00      3625505.00     10561581.00
      3625483.75     10561525.00      3625499.00     10561425.00
      3625486.75     10561321.00      3625431.25     10561130.00
      3625428.25     10561036.00      3625333.00     10560749.00
      3625271.50     10560495.00      3625269.50     10560430.00

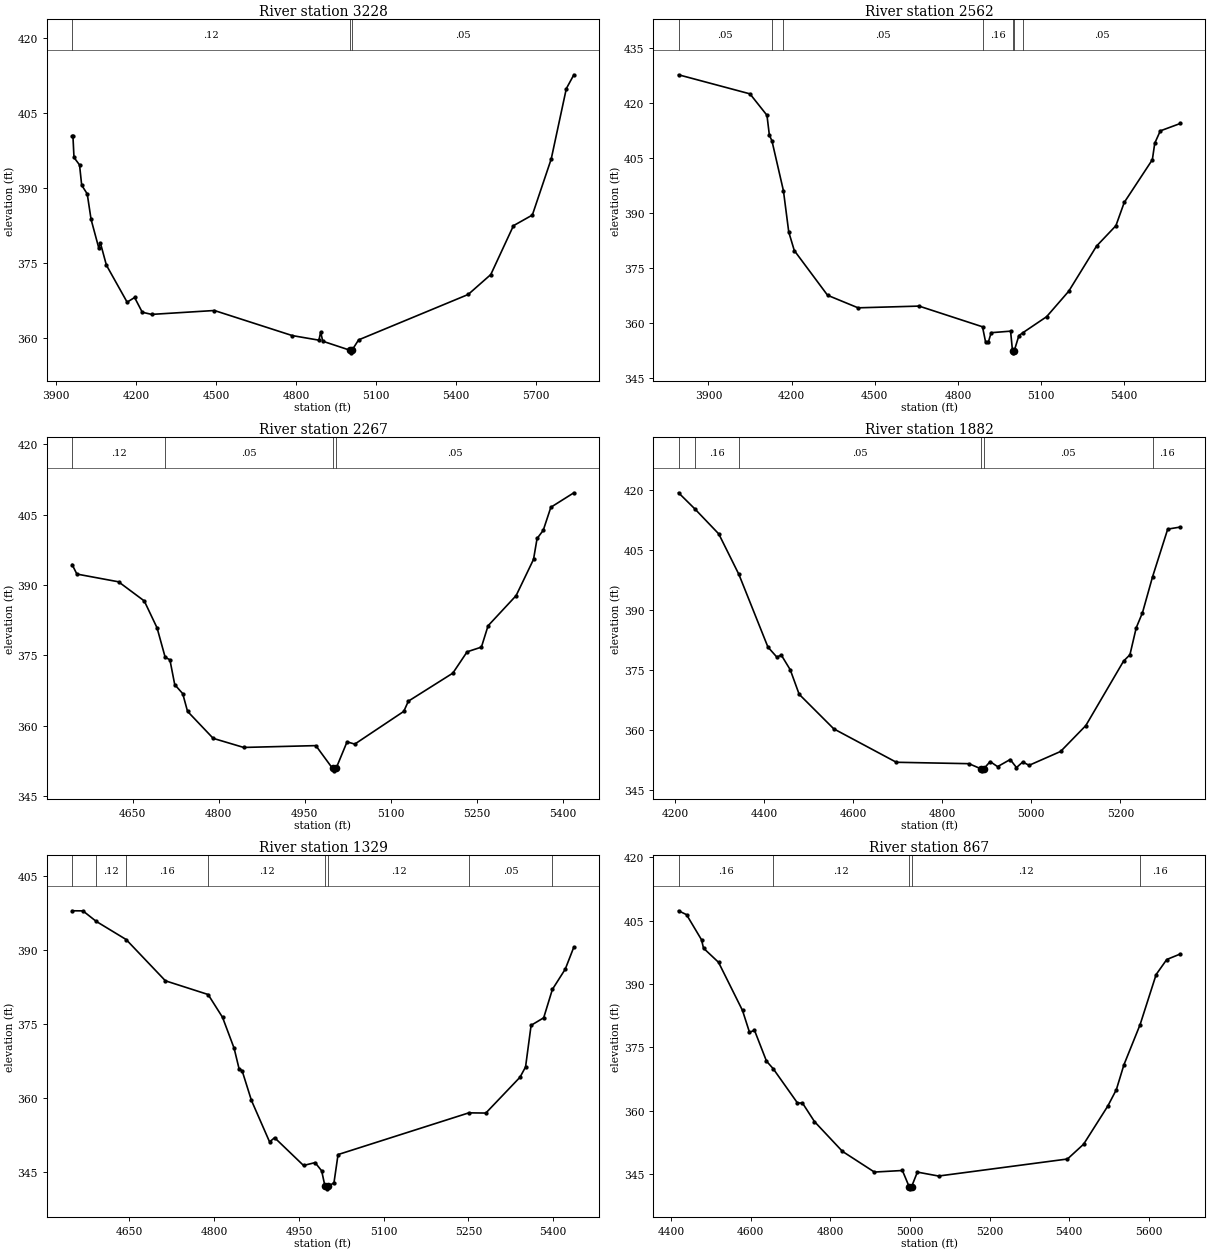
Type RM Length L Ch R = 1,3228,666,666,666
BEGIN DESCRIPTION:
UNT 072 IN BUCR 7.0
END DESCRIPTION:
XS GIS Cut Line= 3
      3626249.64     10564310.22      3625599.61     10563510.19
      3624999.64     10562910.22
#Sta/Elev= 30
  3961.1  400.35  3964.4  400.35  3968.3  396.12  3989.1  394.62  3997.1  390.56
  4017.9  388.81  4032.3  383.70  4061.0  377.99  4067.4  378.94  4089.7  374.52
  4167.3  367.10  4195.3  368.04  4224.0  365.08  4259.2  364.65  4494.1  365.43
  4785.8  360.40  4885.6  359.48  4892.1  361.11  4900.0  359.27  5003.1  357.44
  5005.8  356.94  5009.1  357.44  5034.3  359.54  5444.5  368.64  5529.3  372.64
  5614.2  382.44  5684.9  384.57  5755.6  395.81  5812.2  409.93  5840.4  412.70
#Mann=3,-1,0
  3961.1    0.12       0  5003.1    0.07       0  5009.1    0.05       0
Bank Sta=5003.1,5009.1
Exp/Cntr=0.3,0.1

Type RM Length L Ch R = 1,2562,295,295,295
BEGIN DESCRIPTION:
UNT 072 IN BUCR 6.0
END DESCRIPTION:
XS GIS Cut Line= 2
      3626787.17     10562816.11      3624977.32     10562868.19
#Sta/Elev= 30
  3791.9  427.70  4049.6  422.50  4111.0  416.66  4119.6  411.27  4129.0  409.67
  4170.4  396.09  4189.6  384.84  4209.6  379.79  4329.7  367.60  4439.7  364.18
  4659.8  364.65  4888.7  359.01  4899.9  354.83  4909.9  354.85  4919.9  357.40
  4990.0  357.82  4997.0  352.41  4999.7  351.91  5003.0  352.41  5020.0  356.61
  5033.1  357.33  5120.0  361.76  5200.0  368.72  5300.1  381.00  5370.1  386.57
  5400.1  392.90  5501.6  404.56  5510.2  409.04  5530.2  412.41  5602.5  414.43
#Mann=7,-1,0
  3791.9    0.05       0  4129.0    0.16       0  4170.4    0.05       0
  4888.7    0.16       0  4997.0    0.07       0  5003.0    0.16       0
  5033.1    0.05       0
Bank Sta=4997,5003
Exp/Cntr=0.3,0.1

Type RM Length L Ch R = 1,2267,385,385,385
BEGIN DESCRIPTION:
UNT 072 IN BUCR 5.0
END DESCRIPTION:
XS GIS Cut Line= 3
      3625949.59     10562360.20      3625549.61     10562560.19
      3625149.60     10562710.19
#Sta/Elev= 30
  4544.5  394.36  4552.9  392.32  4625.5  390.67  4670.3  386.59  4692.6  380.85
  4706.7  374.59  4715.0  374.03  4723.4  368.74  4737.3  366.82  4745.7  363.04
  4790.4  357.28  4843.6  355.34  4969.3  355.73  4998.5  350.85  5001.2  350.35
  5004.5  350.85  5023.7  356.54  5037.1  356.05  5122.5  363.03  5130.5  365.21
  5208.0  371.19  5232.9  375.74  5257.8  376.74  5269.4  381.29  5318.3  387.73
  5348.6  395.45  5354.8  399.91  5365.5  401.64  5378.8  406.57  5418.9  409.66
#Mann=4,-1,0
  4544.5    0.12       0  4706.7    0.05       0  4998.5    0.03       0
  5004.5    0.05       0
Bank Sta=4998.5,5004.5
Exp/Cntr=0.3,0.1

Type RM Length L Ch R = 1,1882,553,553,553
BEGIN DESCRIPTION:
UNT 072 IN BUCR 4.0
END DESCRIPTION:
XS GIS Cut Line= 3
      3626149.65     10562110.19      3625449.61     10562160.19
      3625149.60     10562460.20
#Sta/Elev= 30
  4208.3  419.34  4244.4  415.37  4298.6  409.06  4343.8  398.93  4408.9  380.80
  4428.9  378.29  4438.9  378.80  4459.0  375.12  4479.0  369.00  4556.7  360.36
  4697.1  352.01  4860.0  351.66  4887.1  350.37  4889.8  349.87  4893.1  350.37
  4907.6  352.18  4924.3  350.92  4952.6  352.70  4966.7  350.69  4980.8  352.08
  4995.0  351.25  5065.7  354.71  5122.3  361.18  5207.1  377.30  5221.3  378.87
  5235.4  385.60  5249.5  389.39  5272.1  398.36  5306.1  410.26  5334.4  410.78
#Mann=6,-1,0
  4208.3    0.12       0  4244.4    0.16       0  4343.8    0.05       0
  4887.1    0.03       0  4893.1    0.05       0  5272.1    0.16       0
Bank Sta=4887.1,4893.1
Exp/Cntr=0.3,0.1

Type RM Length L Ch R = 1,1329,462,462,462
BEGIN DESCRIPTION:
UNT 072 IN BUCR 3.0
END DESCRIPTION:
XS GIS Cut Line= 3
      3625949.60     10561810.19      3625499.61     10561710.19
      3625099.58     10561860.20
#Sta/Elev= 30
  4548.4  398.01  4567.6  397.99  4591.3  395.85  4644.1  392.18  4713.6  383.81
  4789.2  381.03  4814.7  376.41  4835.2  370.14  4844.2  365.88  4849.3  365.61
  4865.9  359.55  4898.0  351.14  4906.9  351.99  4958.1  346.36  4978.6  346.94
  4990.2  345.27  4996.1  342.12  4998.9  341.62  5002.1  342.12  5012.0  342.86
  5019.2  348.57  5250.7  357.03  5280.8  356.99  5341.3  364.26  5351.1  366.34
  5360.9  374.78  5383.2  376.31  5398.6  382.07  5421.4  386.18  5436.6  390.66
#Mann=8,-1,0
  4548.4    0.16       0  4591.3    0.12       0  4644.1    0.16       0
  4789.2    0.12       0  4996.1    0.07       0  5002.1    0.12       0
  5250.7    0.05       0  5398.6    0.16       0
Bank Sta=4996.1,5002.1
Exp/Cntr=0.3,0.1

Type RM Length L Ch R = 1,867,348,348,348
BEGIN DESCRIPTION:
UNT 072 IN BUCR 2.0
END DESCRIPTION:
XS GIS Cut Line= 3
      3626049.63     10561310.19      3625449.61     10561260.19
      3624799.65     10561160.20
#Sta/Elev= 30
  4419.3  407.34  4439.4  406.42  4477.0  400.48  4482.0  398.49  4519.7  395.15
  4579.9  383.75  4597.4  378.60  4610.0  379.06  4640.1  371.76  4656.9  369.98
  4717.9  361.86  4730.4  361.86  4760.5  357.47  4830.7  350.42  4911.0  345.52
  4981.3  345.89  4998.3  342.05  5001.1  341.55  5004.3  342.05  5018.9  345.51
  5072.0  344.58  5395.7  348.61  5436.2  352.11  5496.9  361.13  5518.4  365.02
  5537.4  370.90  5578.0  380.40  5618.3  392.26  5644.9  395.81  5679.0  397.12
#Mann=5,-1,0
  4419.3    0.16       0  4656.9    0.12       0  4998.3    0.07       0
  5004.3    0.12       0  5578.0    0.16       0
Bank Sta=4998.3,5004.3
Exp/Cntr=0.3,0.1

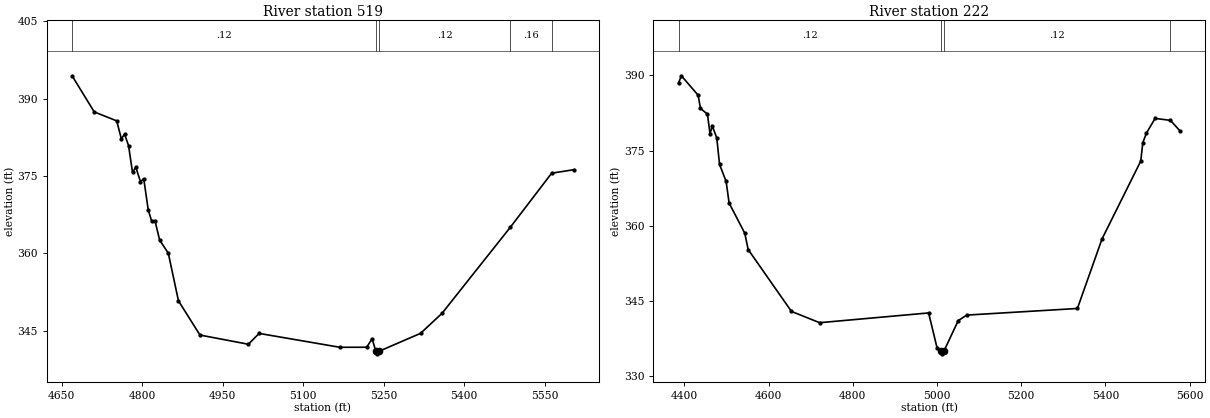
Type RM Length L Ch R = 1,519,297,297,297
BEGIN DESCRIPTION:
Mapping XS fcb15b92
END DESCRIPTION:
XS GIS Cut Line= 3
      3625685.48     10561021.15      3625542.25     10560919.59
      3624784.51     10560974.27
#Sta/Elev= 30
  4669.4  394.42  4710.8  387.41  4752.6  385.68  4761.2  382.21  4767.3  383.08
  4774.7  380.87  4782.1  375.68  4788.2  376.70  4796.9  373.89  4803.0  374.46
  4811.4  368.39  4817.8  366.23  4823.9  366.34  4832.6  362.57  4848.8  360.01
  4867.7  350.79  4907.8  344.15  4998.0  342.37  5018.1  344.47  5168.5  341.78
  5218.6  341.79  5228.6  343.44  5235.6  341.01  5238.4  340.51  5241.6  341.01
  5318.9  344.48  5359.0  348.37  5486.2  365.04  5563.3  375.53  5604.7  376.21
#Mann=5,-1,0
  4669.4    0.12       0  5235.6    0.07       0  5241.6    0.12       0
  5486.2    0.16       0  5563.3    0.05       0
Bank Sta=5235.6,5241.6
Exp/Cntr=0.3,0.1

Type RM Length L Ch R = 1,222,0,0,0
BEGIN DESCRIPTION:
UNT 072 IN BUCR 1.0
END DESCRIPTION:
XS GIS Cut Line= 4
      3625727.14     10560982.08      3625578.71     10560672.19
      3625065.69     10560622.71      3624741.14     10560695.41
#Sta/Elev= 30
  4386.1  388.50  4392.9  389.94  4432.6  386.06  4438.2  383.42  4454.7  382.28
  4460.8  378.39  4466.4  379.87  4476.9  377.53  4483.5  372.23  4499.1  368.85
  4506.2  364.52  4543.4  358.49  4551.5  355.23  4654.3  342.87  4721.2  340.62
  4980.0  342.57  5000.1  335.55  5010.1  334.90  5012.8  334.40  5016.1  334.90
  5050.3  341.04  5070.4  342.14  5333.3  343.46  5391.7  357.34  5483.6  372.88
  5488.7  376.61  5497.3  378.50  5517.8  381.43  5554.3  381.03  5577.7  378.85
#Mann=4,-1,0
  4386.1    0.12       0  5010.1    0.07       0  5016.1    0.12       0
  5554.3    0.05       0
Bank Sta=5010.1,5016.1
Exp/Cntr=0.3,0.1

Chan Stop Cuts=-1