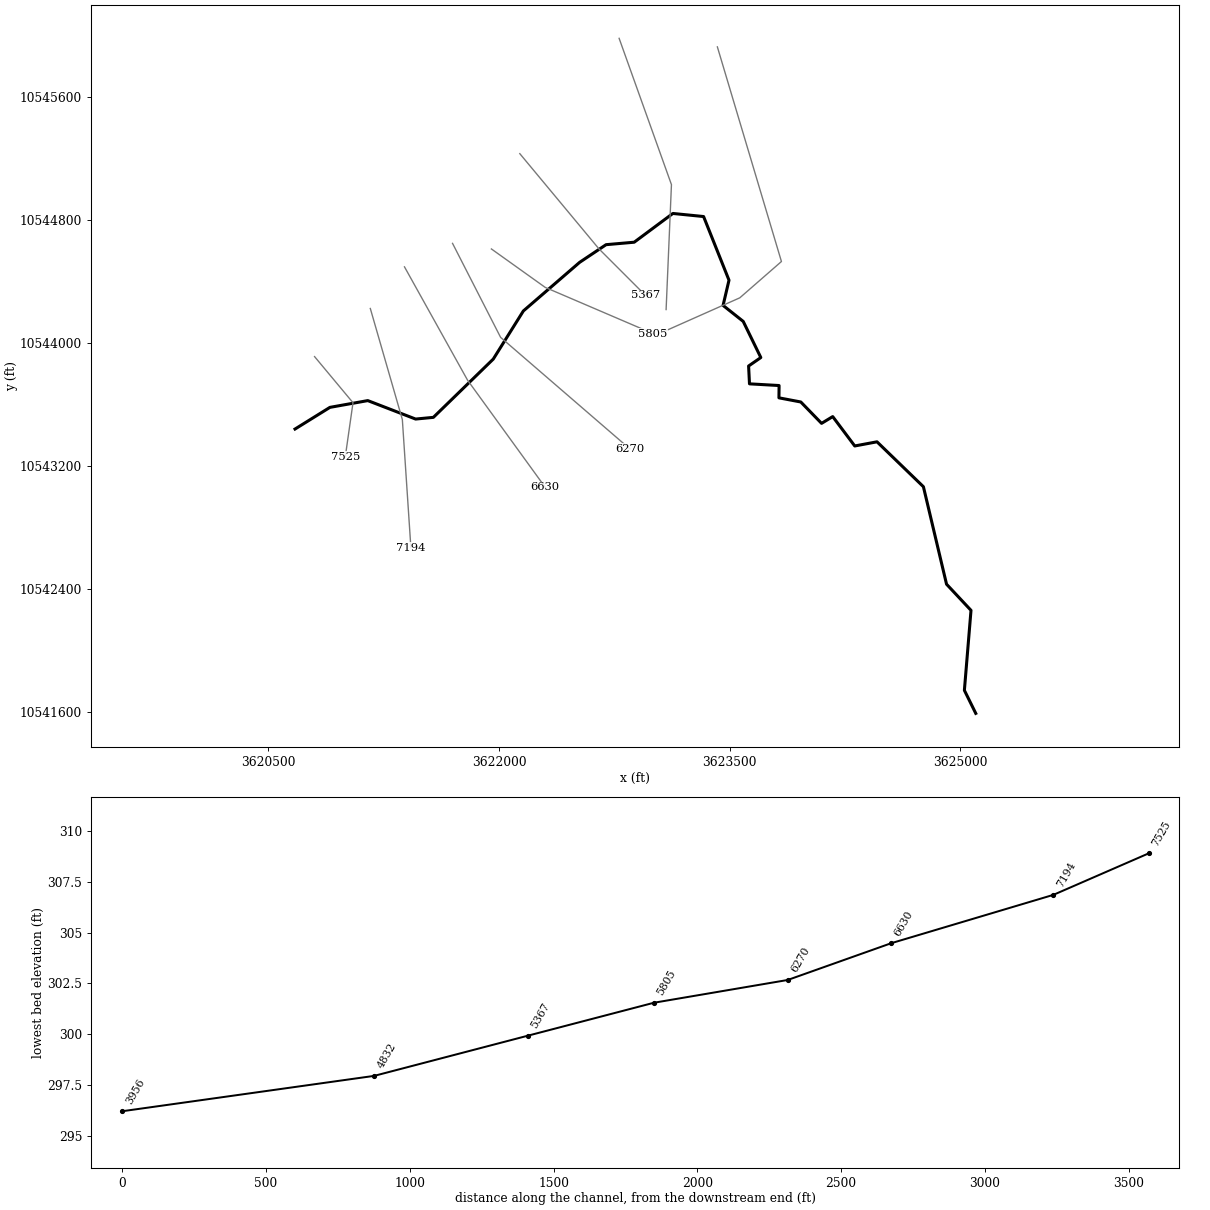
--- UNT 078 IN BUCR.prj (project) ---

Proj Title=UNT 078 IN BUCR Base Level Engineering
Current Plan=p01
Default Exp/Contr=0.3,0.1
English Units
Geom File=g01
Flow File=f01
Plan File=p01
BEGIN DESCRIPTION:
UNT 078 IN BUCR
END DESCRIPTION:

--- UNT 078 IN BUCR.p01 (plan) ---

Plan Title=Multiple Run
Short Identifier=Multiple
Geom File=g01
Flow File=f01
Subcritical Flow
K Sum by GR= 0
Std Step Tol= 0.01
Critical Tol= 0.01
Num of Std Step Trials= 20
Max Error Tol= 0.3
Flow Tol Ratio= 0.001
Split Flow NTrial= 30
Split Flow Tol= 0.02
Split Flow Ratio= 0.02
Log Output Level= 0
Friction Slope Method= 1
Unsteady Friction Slope Method= 2
Unsteady Bridges Friction Slope Method= 1
Parabolic Critical Depth
Global Vel Dist=  1 , 1 , 1
Global Log Level= 0
CheckData=True
Encroach Param= -1, 0, 0, 0
BEGIN DESCRIPTION:
Multiple Run
END DESCRIPTION:

--- UNT 078 IN BUCR.f01 (steady flow) ---

Flow Title=Multiple
Number of Profiles=7
Profile Names=10-year,25-year,50-year,1pct_min,100-year,1pct_plu,500-year
River Rch & RM= UNT 078 IN BUCR,Reach-1,7525
    1574    2220    2768    2517    3404    4604    5132
Boundary for River Rch & Prof#=UNT 078 IN BUCR,Reach-1,1
Up Type=0
Dn Type=3
Dn Slope=0.005
Boundary for River Rch & Prof#=UNT 078 IN BUCR,Reach-1,2
Up Type=0
Dn Type=3
Dn Slope=0.005
Boundary for River Rch & Prof#=UNT 078 IN BUCR,Reach-1,3
Up Type=0
Dn Type=3
Dn Slope=0.005
Boundary for River Rch & Prof#=UNT 078 IN BUCR,Reach-1,4
Up Type=0
Dn Type=3
Dn Slope=0.005
Boundary for River Rch & Prof#=UNT 078 IN BUCR,Reach-1,5
Up Type=0
Dn Type=3
Dn Slope=0.005
Boundary for River Rch & Prof#=UNT 078 IN BUCR,Reach-1,6
Up Type=0
Dn Type=3
Dn Slope=0.005
Boundary for River Rch & Prof#=UNT 078 IN BUCR,Reach-1,7
Up Type=0
Dn Type=3
Dn Slope=0.005

--- UNT 078 IN BUCR.g01 (geometry) ---

Geom Title=Existing Conditions

River Reach=UNT 078 IN BUCR,Reach-1
Reach XY= 30
      3620672.60     10543439.11      3620899.50     10543580.00
      3621145.75     10543624.00      3621456.75     10543504.00
      3621572.25     10543515.00      3621961.75     10543894.00
      3622157.50     10544207.00      3622523.25     10544523.00
      3622695.25     10544638.00      3622878.25     10544654.00
      3623129.75     10544841.00      3623329.50     10544821.00
      3623494.75     10544407.00      3623456.25     10544243.00
      3623587.25     10544139.00      3623701.75     10543904.00
      3623622.25     10543849.00      3623628.00     10543733.00
      3623820.50     10543722.00      3623819.50     10543642.00
      3623961.75     10543615.00      3624096.75     10543476.00
      3624169.25     10543520.00      3624312.50     10543329.00
      3624457.25     10543356.00      3624759.00     10543064.00
      3624909.50     10542430.00      3625068.50     10542260.00
      3625025.50     10541740.00      3625099.50     10541590.00

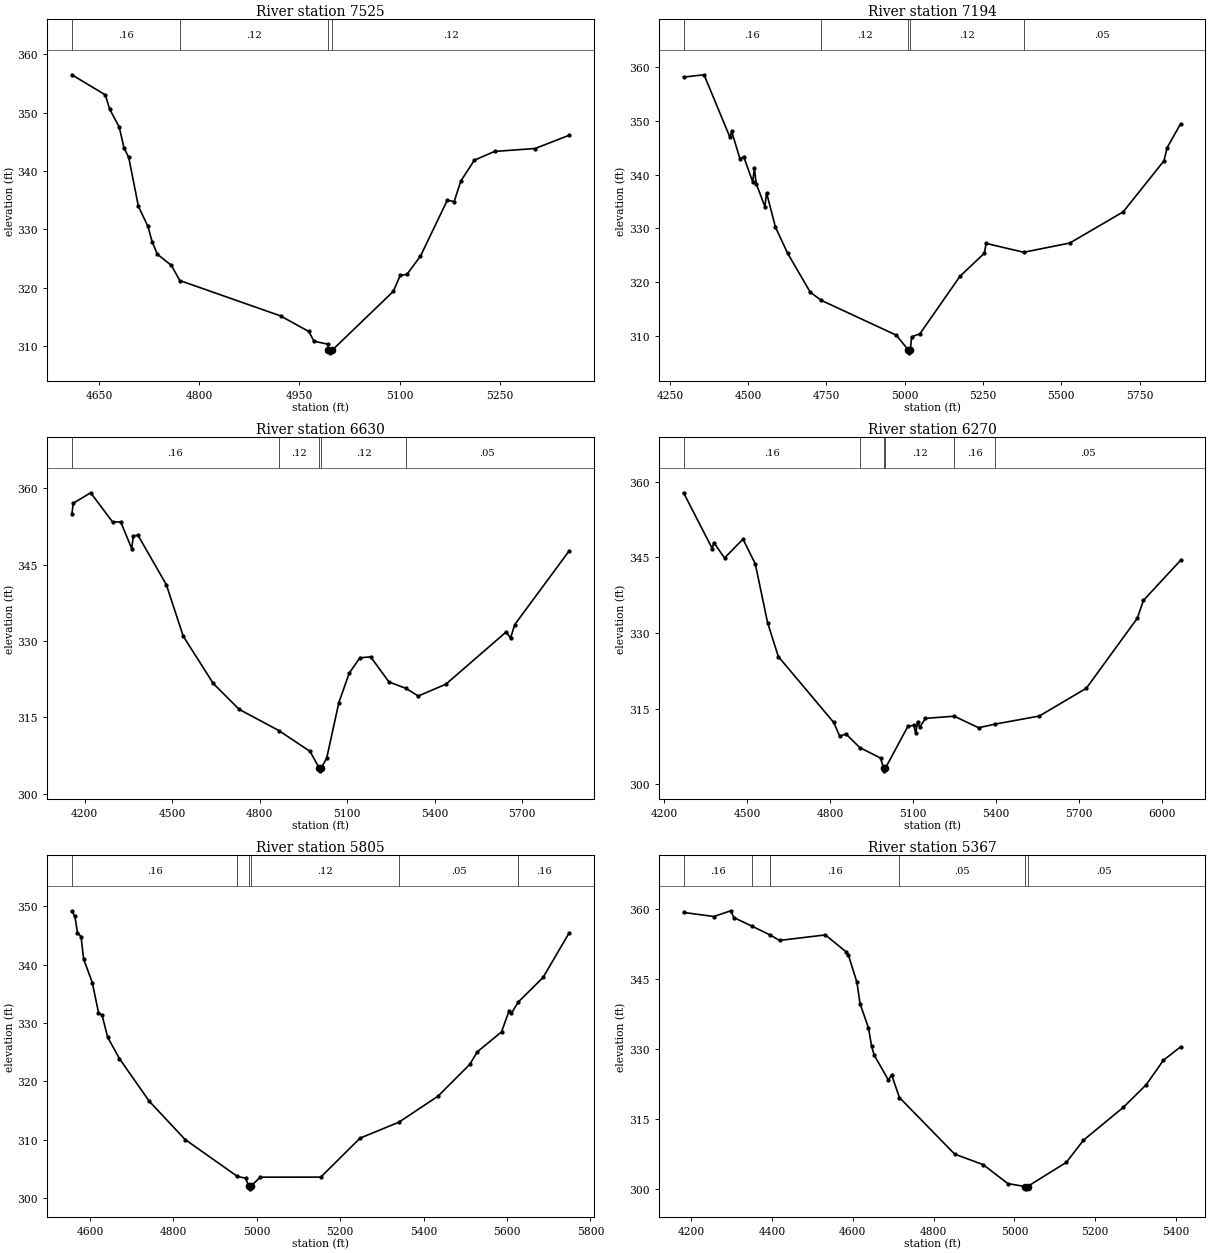
Type RM Length L Ch R = 1,7525,331,331,331
BEGIN DESCRIPTION:
UNT 078 IN BUCR 8.0
END DESCRIPTION:
XS GIS Cut Line= 3
      3620799.62     10543910.17      3621049.61     10543610.19
      3620999.62     10543260.23
#Sta/Elev= 30
  4609.3  356.46  4659.4  353.03  4665.9  350.58  4680.2  347.54  4687.4  343.96
  4694.5  342.32  4708.9  333.98  4723.2  330.53  4729.7  327.83  4737.5  325.75
  4758.3  323.86  4770.9  321.27  4921.7  315.22  4964.0  312.55  4971.8  310.89
  4992.6  310.38  4993.5  309.40  4996.3  308.90  4999.5  309.40  5090.7  319.43
  5100.8  322.13  5110.9  322.32  5131.1  325.42  5171.5  335.03  5181.6  334.76
  5191.7  338.31  5211.9  341.85  5242.2  343.35  5302.8  343.85  5353.3  346.09
#Mann=4,-1,0
  4609.3    0.16       0  4770.9    0.12       0  4993.5    0.07       0
  4999.5    0.12       0
Bank Sta=4993.5,4999.5
Exp/Cntr=0.3,0.1

Type RM Length L Ch R = 1,7194,564,564,564
BEGIN DESCRIPTION:
UNT 078 IN BUCR 7.0
END DESCRIPTION:
XS GIS Cut Line= 3
      3621162.16     10544222.98      3621370.50     10543500.72
      3621426.06     10542667.38
#Sta/Elev= 30
  4293.9  358.13  4359.3  358.56  4442.2  346.91  4447.4  348.05  4473.7  342.98
  4486.2  343.30  4514.7  338.63  4519.9  341.19  4525.8  338.34  4553.6  334.04
  4558.8  336.63  4587.2  330.24  4626.1  325.38  4698.6  318.12  4733.3  316.63
  4973.3  310.14  5011.9  307.36  5014.7  306.86  5017.9  307.36  5022.2  309.84
  5048.4  310.39  5176.4  321.09  5254.6  325.40  5259.7  327.21  5380.0  325.56
  5527.2  327.28  5697.6  333.07  5827.9  342.57  5837.9  345.01  5880.8  349.44
#Mann=5,-1,0
  4293.9    0.16       0  4733.3    0.12       0  5011.9    0.07       0
  5017.9    0.12       0  5380.0    0.05       0
Bank Sta=5011.9,5017.9
Exp/Cntr=0.3,0.1

Type RM Length L Ch R = 1,6630,360,360,360
BEGIN DESCRIPTION:
UNT 078 IN BUCR 6.0
END DESCRIPTION:
XS GIS Cut Line= 3
      3621384.38     10544493.78      3621794.11     10543757.66
      3622299.63     10543060.15
#Sta/Elev= 30
  4155.7  354.95  4160.8  357.09  4220.3  359.14  4295.8  353.37  4323.2  353.44
  4360.9  348.17  4366.7  350.69  4382.7  350.77  4479.8  341.06  4537.5  330.97
  4640.5  321.66  4729.1  316.58  4865.6  312.39  4972.4  308.30  5004.4  304.98
  5007.1  304.48  5010.4  304.98  5029.5  306.97  5071.2  317.91  5106.8  323.69
  5143.2  326.70  5180.3  326.89  5242.9  321.95  5301.1  320.69  5343.4  319.19
  5437.8  321.50  5645.0  331.79  5659.7  330.58  5674.3  333.24  5859.6  347.63
#Mann=5,-1,0
  4155.7    0.16       0  4865.6    0.12       0  5004.4    0.07       0
  5010.4    0.12       0  5301.1    0.05       0
Bank Sta=5004.4,5010.4
Exp/Cntr=0.3,0.1

Type RM Length L Ch R = 1,6270,465,465,465
BEGIN DESCRIPTION:
UNT 078 IN BUCR 5.0
END DESCRIPTION:
XS GIS Cut Line= 3
      3621696.89     10544646.55      3622009.39     10544035.44
      3622849.60     10543310.19
#Sta/Elev= 30
  4270.7  357.84  4374.4  346.76  4380.0  347.96  4418.8  344.90  4485.5  348.65
  4529.9  343.73  4574.3  332.09  4613.1  325.35  4813.1  312.29  4835.3  309.53
  4857.5  309.99  4907.6  307.28  4982.6  305.21  4993.9  303.17  4996.6  302.67
  4999.9  303.17  5081.4  311.49  5102.7  311.72  5109.9  310.09  5116.5  312.42
  5124.1  311.31  5145.0  313.08  5248.9  313.51  5337.0  311.22  5395.5  311.93
  5556.4  313.54  5726.4  319.06  5910.7  332.95  5932.6  336.47  6067.0  344.44
#Mann=6,-1,0
  4270.7    0.16       0  4907.6    0.12       0  4993.9    0.07       0
  4999.9    0.12       0  5248.9    0.16       0  5395.5    0.05       0
Bank Sta=4993.9,4999.9
Exp/Cntr=0.3,0.1

Type RM Length L Ch R = 1,5805,438,438,438
BEGIN DESCRIPTION:
UNT 078 IN BUCR 4.0
END DESCRIPTION:
XS GIS Cut Line= 3
      3621949.62     10544610.18      3622299.61     10544360.19
      3622999.62     10544060.18
#Sta/Elev= 30
  4556.4  349.24  4563.8  348.27  4569.9  345.49  4578.5  344.81  4584.7  340.95
  4605.5  336.93  4620.3  331.78  4628.9  331.34  4642.4  327.54  4670.7  323.87
  4742.0  316.58  4828.0  310.01  4953.4  303.68  4973.0  303.38  4980.4  302.05
  4983.2  301.55  4986.4  302.05  5008.3  303.55  5153.3  303.56  5247.6  310.25
  5340.6  312.98  5434.4  317.44  5510.5  322.89  5528.7  325.05  5586.7  328.47
  5604.8  332.06  5610.3  331.64  5626.7  333.58  5686.4  337.81  5748.1  345.35
#Mann=6,-1,0
  4556.4    0.16       0  4953.4    0.12       0  4980.4    0.07       0
  4986.4    0.12       0  5340.6    0.05       0  5626.7    0.16       0
Bank Sta=4980.4,4986.4
Exp/Cntr=0.3,0.1

Type RM Length L Ch R = 1,5367,535,535,535
BEGIN DESCRIPTION:
UNT 078 IN BUCR 3.0
END DESCRIPTION:
XS GIS Cut Line= 3
      3622134.36     10545229.91      3622649.61     10544610.19
      3622949.61     10544310.19
#Sta/Elev= 30
  4181.1  359.23  4256.0  358.36  4297.8  359.59  4305.5  358.14  4350.7  356.28
  4394.9  354.41  4418.7  353.23  4532.0  354.41  4582.8  350.83  4589.3  350.03
  4610.1  344.27  4617.9  339.67  4638.8  334.46  4646.6  330.49  4653.1  328.59
  4688.2  323.27  4696.0  324.40  4715.4  319.52  4852.3  307.37  4922.6  305.13
  4983.8  301.05  5026.5  300.43  5029.2  299.93  5032.5  300.43  5128.5  305.61
  5170.9  310.36  5269.9  317.44  5326.5  322.29  5368.9  327.53  5411.3  330.39
#Mann=6,-1,0
  4181.1    0.16       0  4350.7     0.1       0  4394.9    0.16       0
  4715.4    0.05       0  5026.5    0.03       0  5032.5    0.05       0
Bank Sta=5026.5,5032.5
Exp/Cntr=0.3,0.1

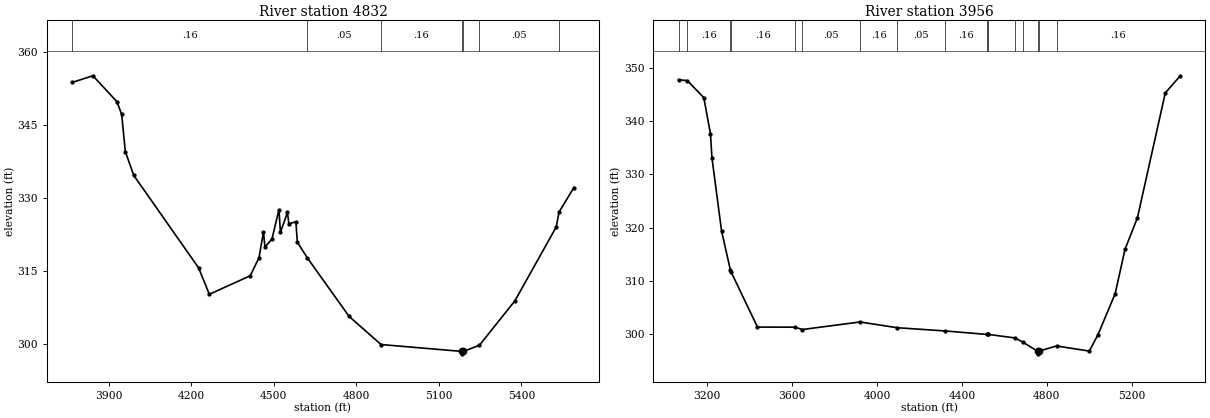
Type RM Length L Ch R = 1,4832,876,876,876
BEGIN DESCRIPTION:
UNT 078 IN BUCR 2.0
END DESCRIPTION:
XS GIS Cut Line= 3
      3622780.23     10545979.86      3623120.50     10545028.49
      3623085.78     10544216.02
#Sta/Elev= 30
  3766.9  353.69  3842.7  355.06  3929.8  349.75  3947.1  347.15  3960.5  339.48
  3991.3  334.58  4226.9  315.60  4265.7  310.18  4414.4  313.99  4446.3  317.69
  4462.5  322.99  4467.8  319.89  4493.3  321.52  4518.8  327.56  4524.1  322.90
  4549.5  326.98  4554.9  324.66  4580.3  325.08  4585.6  320.88  4621.2  317.72
  4773.7  305.64  4889.8  299.86  5183.0  298.45  5185.7  297.95  5189.0  298.45
  5247.4  299.72  5376.1  308.83  5526.3  323.99  5536.7  327.08  5590.5  332.09
#Mann=7,-1,0
  3766.9    0.16       0  4621.2    0.05       0  4889.8    0.16       0
  5183.0    0.07       0  5189.0    0.16       0  5247.4    0.05       0
  5536.7    0.16       0
Bank Sta=5183,5189
Exp/Cntr=0.3,0.1

Type RM Length L Ch R = 1,3956,0,0,0
BEGIN DESCRIPTION:
UNT 078 IN BUCR 1.0
END DESCRIPTION:
XS GIS Cut Line= 4
      3623419.13     10545924.28      3623835.78     10544528.49
      3623564.95     10544292.38      3623064.95     10544070.16
#Sta/Elev= 30
  3065.5  347.82  3107.0  347.66  3184.5  344.45  3215.9  337.64  3222.8  333.14
  3268.1  319.35  3309.4  312.04  3313.8  311.56  3437.3  301.25  3613.0  301.23
  3649.2  300.79  3920.4  302.21  4094.6  301.13  4321.4  300.52  4515.9  299.87
  4524.1  299.87  4524.7  299.87  4651.0  299.20  4686.7  298.41  4756.0  296.71
  4758.7  296.21  4762.0  296.71  4845.5  297.69  4999.9  296.73  5040.5  299.79
  5121.7  307.54  5168.2  315.91  5226.5  321.82  5357.8  345.35  5428.6  348.57
#Mann=17,-1,0
  3065.5    0.05       0  3107.0    0.16       0  3309.4    0.05       0
  3313.8    0.16       0  3613.0     0.1       0  3649.2    0.05       0
  3920.4    0.16       0  4094.6    0.05       0  4321.4    0.16       0
  4515.9    0.12       0  4524.1    0.16       0  4524.7    0.12       0
  4651.0    0.16       0  4686.7    0.12       0  4756.0    0.07       0
  4762.0    0.12       0  4845.5    0.16       0
Bank Sta=4756,4762
Exp/Cntr=0.3,0.1

Chan Stop Cuts=-1