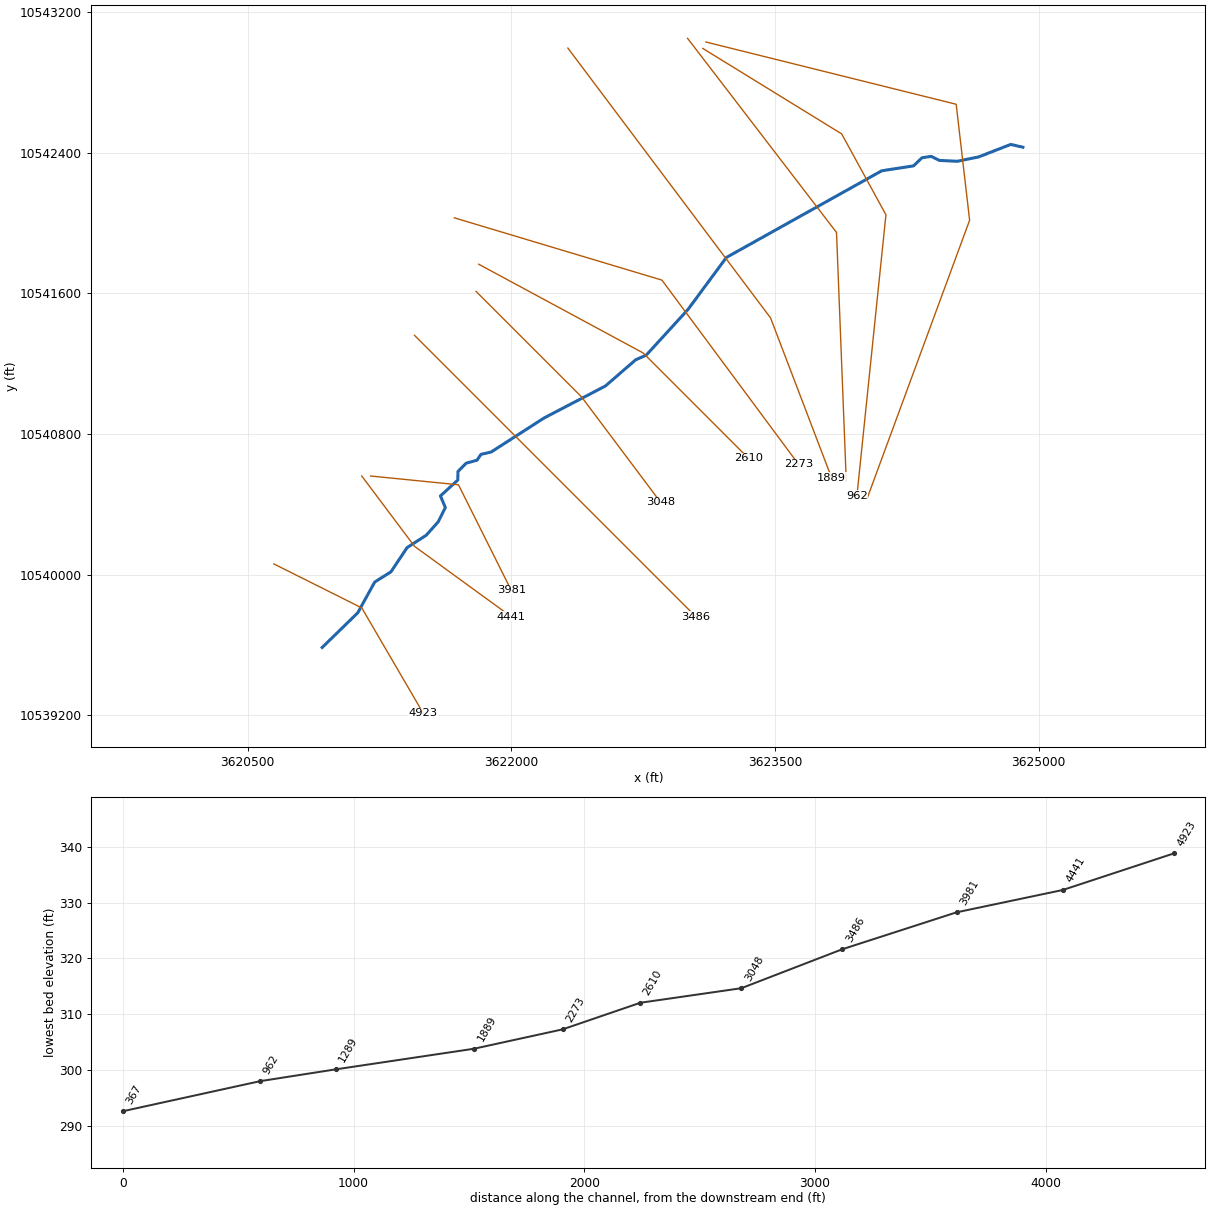
--- UNT 079 IN BUCR.prj (project) ---

Proj Title=UNT 079 IN BUCR Base Level Engineering
Current Plan=p01
Default Exp/Contr=0.3,0.1
English Units
Geom File=g01
Flow File=f01
Plan File=p01
Y Axis Title=Elevation
X Axis Title(PF)=Main Channel Distance
X Axis Title(XS)=Station
BEGIN DESCRIPTION:
UNT 079 IN BUCR
END DESCRIPTION:
DSS Export Rating Curves= 0
DSS Export Rating Curve Sorted= 0
DSS Export Volume Flow Curves= 0
DXF OffsetX= 0
DXF OffsetY= 0
DXF ScaleX= 1
DXF ScaleY= 10

--- UNT 079 IN BUCR.p01 (plan) ---

Plan Title=Multiple Run
Short Identifier=Multiple
Geom File=g01
Flow File=f01
Subcritical Flow
K Sum by GR= 0
Std Step Tol= 0.01
Critical Tol= 0.01
Num of Std Step Trials= 20
Max Error Tol= 0.3
Flow Tol Ratio= 0.001
Split Flow NTrial= 30
Split Flow Tol= 0.02
Split Flow Ratio= 0.02
Log Output Level= 0
Friction Slope Method= 1
Unsteady Friction Slope Method= 2
Unsteady Bridges Friction Slope Method= 1
Parabolic Critical Depth
Global Vel Dist=  1 , 1 , 1
Global Log Level= 0
CheckData=True
Encroach Param= -1, 0, 0, 0
BEGIN DESCRIPTION:
Multiple Run
END DESCRIPTION:

--- UNT 079 IN BUCR.f01 (steady flow) ---

Flow Title=Multiple
Number of Profiles=7
Profile Names=10-year,25-year,50-year,1pct_min,100-year,1pct_plu,500-year
River Rch & RM= UNT 079 IN BUCR,Reach-1,4923
     622     832    1001     882    1193    1614    1686
Boundary for River Rch & Prof#=UNT 079 IN BUCR,Reach-1,1
Up Type=0
Dn Type=3
Dn Slope=0.005
Boundary for River Rch & Prof#=UNT 079 IN BUCR,Reach-1,2
Up Type=0
Dn Type=3
Dn Slope=0.005
Boundary for River Rch & Prof#=UNT 079 IN BUCR,Reach-1,3
Up Type=0
Dn Type=3
Dn Slope=0.005
Boundary for River Rch & Prof#=UNT 079 IN BUCR,Reach-1,4
Up Type=0
Dn Type=3
Dn Slope=0.005
Boundary for River Rch & Prof#=UNT 079 IN BUCR,Reach-1,5
Up Type=0
Dn Type=3
Dn Slope=0.005
Boundary for River Rch & Prof#=UNT 079 IN BUCR,Reach-1,6
Up Type=0
Dn Type=3
Dn Slope=0.005
Boundary for River Rch & Prof#=UNT 079 IN BUCR,Reach-1,7
Up Type=0
Dn Type=3
Dn Slope=0.005

--- UNT 079 IN BUCR.g01 (geometry) ---

Geom Title=Existing Conditions
Program Version=4.10

River Reach=UNT 079 IN BUCR ,Reach-1
Reach XY= 30
       3620924.5       10539585.      3621126.75       10539782.
      3621223.25       10539957.       3621315.5       10540015.
       3621407.5       10540153.        3621516.       10540223.
        3621584.       10540299.        3621625.       10540381.
      3621597.25       10540447.      3621695.75       10540537.
      3621696.75       10540586.      3621743.25       10540633.
        3621805.       10540650.       3621827.5       10540683.
        3621886.       10540697.      3622186.25       10540890.
      3622535.25       10541072.      3622707.25       10541221.
        3622767.       10541247.      3623004.75       10541507.
      3623223.25       10541803.      3624106.75       10542296.
        3624288.       10542324.       3624335.5       10542370.
      3624387.75       10542378.      3624434.75       10542355.
        3624536.       10542350.       3624658.5       10542375.
       3624840.5       10542446.       3624909.5       10542430.

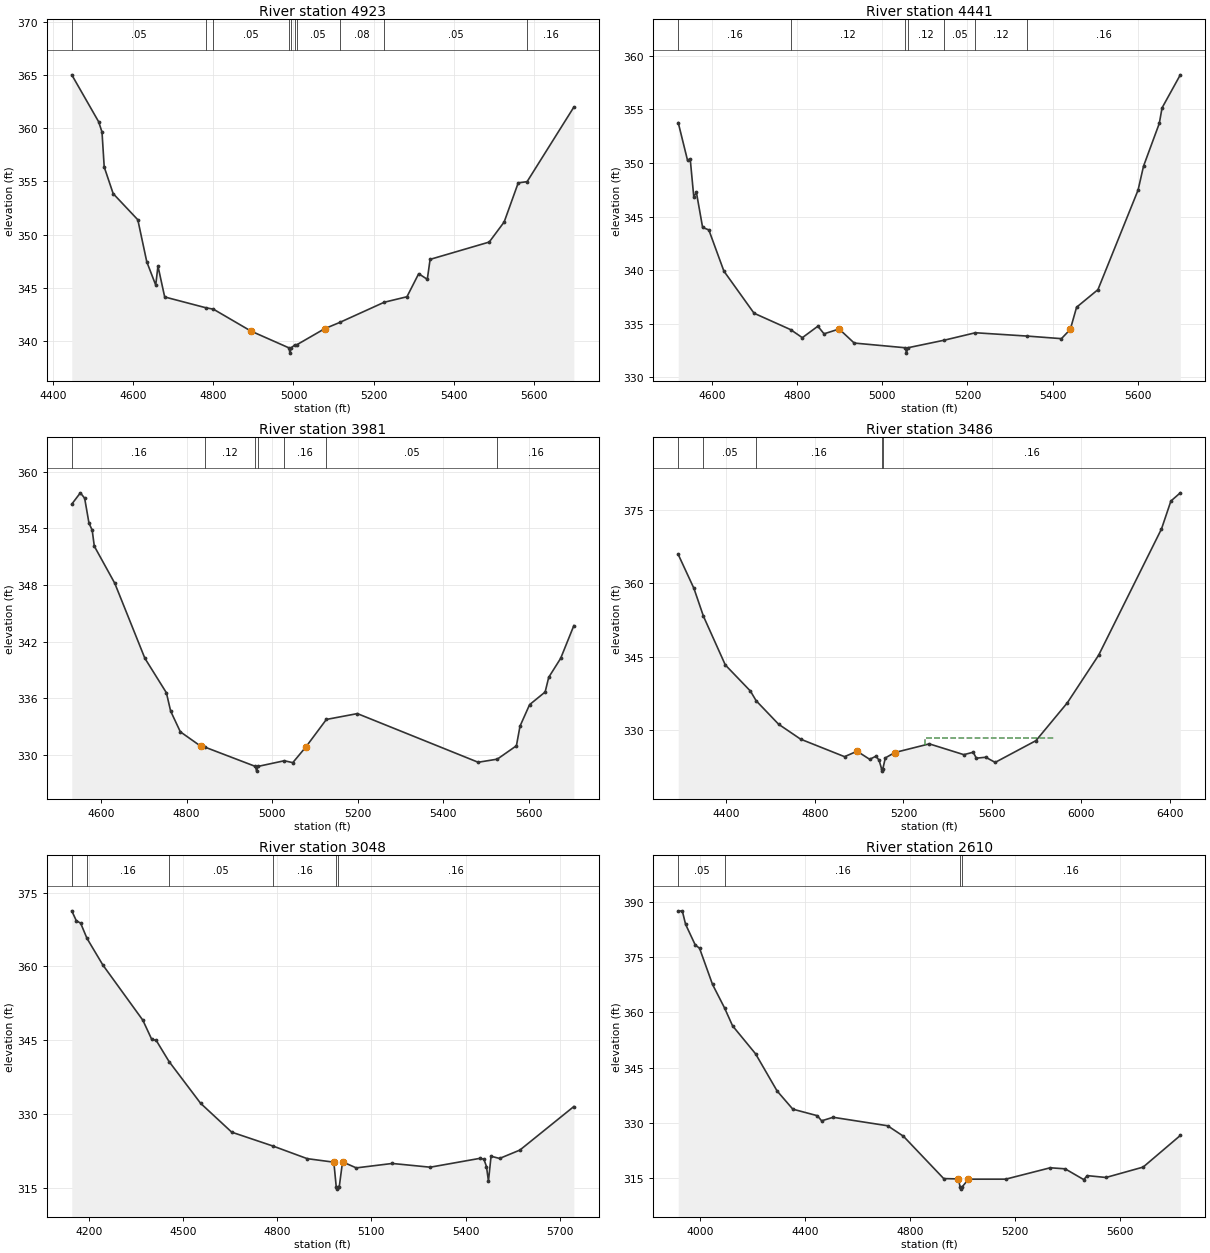
Type RM Length L Ch R = 1 ,4923    ,482,482,482
BEGIN DESCRIPTION:
UNT 079 IN BUCR 10.0
END DESCRIPTION:
XS GIS Cut Line= 3
      3620649.62     10540060.18      3621149.61     10539810.19
       3621499.6     10539210.21
#Sta/Elev= 30
  4446.4  365.04  4513.5  360.62  4521.9  359.65  4527.4  356.36  4549.8  353.85
  4611.3  351.39  4633.7  347.43    4656  345.24  4661.6  347.03  4678.4  344.12
  4781.5   343.1    4800  342.97  4893.6  340.91  4988.4  339.33  4991.2  338.83
  4994.4  339.33  5003.4  339.61  5008.4  339.62  5077.8  341.13  5115.4  341.72
  5226.4  343.62  5283.3  344.14  5312.6  346.31  5334.1  345.78  5341.1  347.66
  5488.7  349.29    5526  351.18  5561.1  354.86  5583.3  354.98    5700     362
#Mann= 10 ,-1 , 0
  4446.4     .05       0  4781.5     .08       0    4800     .05       0
  4988.4     .04       0  4994.4     .05       0  5003.4     .08       0
  5008.4     .05       0  5115.4     .08       0  5226.4     .05       0
  5583.3     .16       0
Bank Sta=4893.6,5077.8
XS Rating Curve= 0 ,0
Exp/Cntr=0.3,0.1

Type RM Length L Ch R = 1 ,4441    ,460,460,460
BEGIN DESCRIPTION:
UNT 079 IN BUCR 9.0
END DESCRIPTION:
XS GIS Cut Line= 3
      3621149.58     10540560.22      3621449.61     10540160.19
       3621999.6      10539760.2
#Sta/Elev= 30
  4520.2  353.76  4542.1  350.24  4548.4  350.36  4556.7  346.85  4562.9  347.26
  4577.5  343.99  4592.1  343.76  4627.5  339.92  4698.4  335.99  4784.4  334.46
  4811.9  333.71  4848.4  334.78  4862.9  334.07  4898.4  334.52  4933.8  333.21
  5053.9  332.77  5056.7  332.27  5059.9  332.77  5145.8  333.48  5218.7  334.17
  5340.3  333.86  5420.9  333.62  5441.8  334.49  5456.5  336.55  5506.7  338.19
    5601  347.47  5613.8   349.7  5650.9  353.69  5657.4  355.14  5700.3  358.22
#Mann= 7 ,-1 , 0
  4520.2     .16       0  4784.4     .12       0  5053.9     .07       0
  5059.9     .12       0  5145.8     .05       0  5218.7     .12       0
  5340.3     .16       0
Bank Sta=4898.4,5441.8
XS Rating Curve= 0 ,0
Exp/Cntr=0.3,0.1

Type RM Length L Ch R = 1 ,3981    ,495,495,495
BEGIN DESCRIPTION:
UNT 079 IN BUCR 8.0
END DESCRIPTION:
XS GIS Cut Line= 3
      3621199.63     10540560.19      3621699.61     10540510.19
      3621999.61     10539910.18
#Sta/Elev= 30
  4531.7  356.58  4551.8  357.78  4561.8  357.21  4571.9  354.57  4579.4  353.82
  4584.4  352.12  4632.2  348.19  4702.5  340.24  4752.8  336.58  4762.8  334.63
  4785.4  332.44  4833.2  330.91  4843.2  330.81  4960.8  328.77  4963.6  328.27
  4966.8  328.77  5028.3  329.37  5048.2  329.17  5078.9  330.84  5126.7  333.75
  5199.1  334.37  5481.4  329.21  5526.1  329.54  5570.8  330.96  5579.2  333.04
  5601.6  335.32  5637.9  336.66  5646.3  338.22  5674.2  340.23    5705   343.7
#Mann= 7 ,-1 , 0
  4531.7     .16       0  4843.2     .12       0  4960.8     .07       0
  4966.8     .12       0  5028.3     .16       0  5126.7     .05       0
  5526.1     .16       0
#XS Ineff= 1 ,-1
 5155.68 5657.61  332.93
Permanent Ineff=
       F
Bank Sta=4833.2,5078.9
XS Rating Curve= 0 ,0
Exp/Cntr=0.3,0.1

Type RM Length L Ch R = 1 ,3486    ,438,438,438
BEGIN DESCRIPTION:
UNT 079 IN BUCR 7.0
END DESCRIPTION:
XS GIS Cut Line= 3
      3621449.62     10541360.18      3622049.61     10540760.19
      3623049.59      10539760.2
#Sta/Elev= 30
  4184.9  365.85  4255.6  358.93  4298.6  353.24    4397  343.32  4510.2  337.99
  4536.1  336.01  4637.4  331.22  4736.4  328.18  4934.4  324.61    4991  325.72
  5047.6  324.07  5075.8   324.7    5090   323.9  5101.1  322.16  5103.9  321.66
  5107.1  322.16  5118.3  324.36  5160.7  325.45  5316.3  327.22  5471.8  325.02
  5514.2  325.51  5528.4   324.3  5570.8  324.49  5613.2  323.44  5797.1  327.88
  5938.5   335.6  6079.9  345.34  6362.8  371.06  6405.2  376.75  6447.6  378.42
#Mann= 5 ,-1 , 0
  4184.9     .16       0  4298.6     .05       0  4536.1     .16       0
  5101.1     .07       0  5107.1     .16       0
#XS Ineff= 1 ,-1
 5295.45  5882.1  328.41
Permanent Ineff=
       F
Bank Sta=4991,5160.7
XS Rating Curve= 0 ,0
Exp/Cntr=0.3,0.1

Type RM Length L Ch R = 1 ,3048    ,438,438,438
BEGIN DESCRIPTION:
UNT 079 IN BUCR 6.0
END DESCRIPTION:
XS GIS Cut Line= 3
      3621799.58     10541610.22      3622399.61     10541010.19
      3622849.62     10540410.17
#Sta/Elev= 30
  4146.1  371.28  4160.3   369.3  4174.4  368.76  4194.6  365.67  4245.1  360.26
  4372.4  349.03  4400.7  345.13  4414.8  344.94  4455.8  340.63  4556.3  332.13
  4655.3  326.26  4786.4  323.44  4895.7  320.87  4980.5  320.15  4988.1  315.17
  4990.9  314.67  4994.1  315.17  4997.8  315.17  5008.2  320.21    5052  318.99
  5166.5  319.89  5287.4  319.13  5444.7  320.92  5458.2  320.77  5466.5  319.27
  5472.8  316.29  5481.1  321.36  5508.2  320.91  5572.8  322.61  5744.7  331.47
#Mann= 6 ,-1 , 0
  4146.1     .05       0  4194.6     .16       0  4455.8     .05       0
  4786.4     .16       0  4988.1     .07       0  4994.1     .16       0
Bank Sta=4980.5,5008.2
XS Rating Curve= 0 ,0
Exp/Cntr=0.3,0.1

Type RM Length L Ch R = 1 ,2610    ,337,337,337
BEGIN DESCRIPTION:
UNT 079 IN BUCR 5.0
END DESCRIPTION:
XS GIS Cut Line= 3
      3621814.98     10541764.58      3622749.61     10541260.19
      3623349.63     10540660.17
#Sta/Elev= 30
  3917.5  387.47  3932.9  387.56  3945.5   383.9  3982.3  378.29  3998.5  377.42
    4048  367.59  4093.7  361.22  4124.2  356.37  4211.8  348.77  4293.6   338.7
  4353.6  333.75  4446.9  331.98  4463.1  330.59  4506.9  331.55  4714.4  329.25
  4774.4  326.41  4927.7  314.92  4983.1  314.83  4990.7  312.56  4993.4  312.06
  4996.7  312.56    5022  314.76  5163.4  314.76  5333.1  317.85  5389.7  317.57
  5460.4  314.65  5474.5  315.72  5545.2  315.22  5686.7  318.04  5828.1  326.62
#Mann= 4 ,-1 , 0
  3917.5     .05       0  4093.7     .16       0  4990.7     .07       0
  4996.7     .16       0
Bank Sta=4983.1,5022
XS Rating Curve= 0 ,0
Exp/Cntr=0.3,0.1

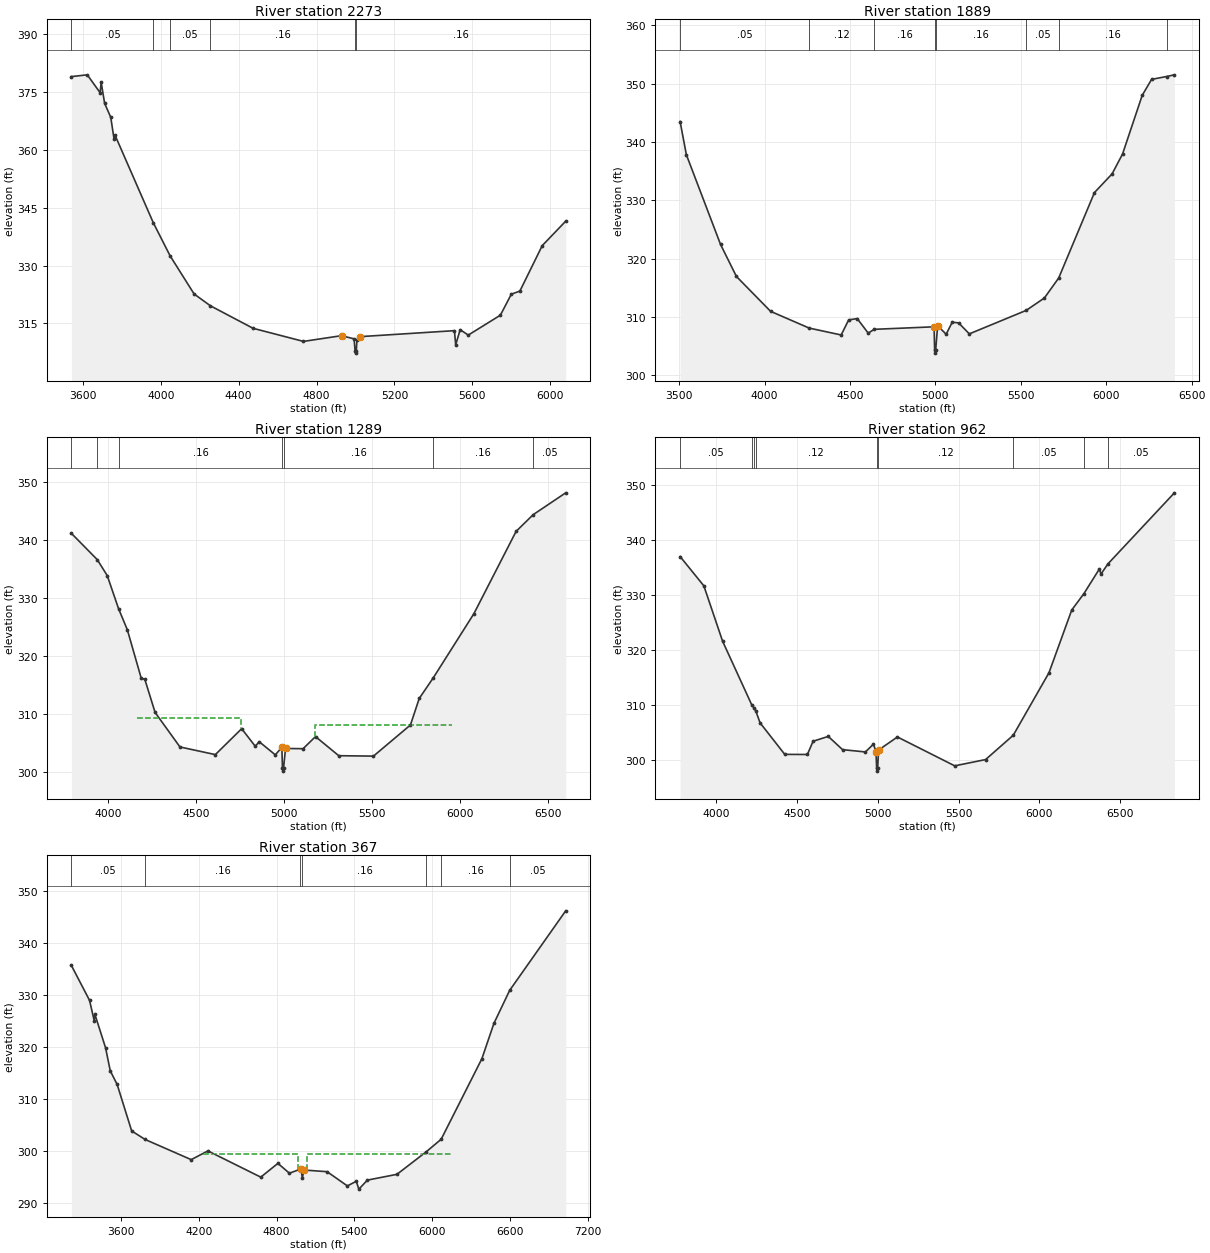
Type RM Length L Ch R = 1 ,2273    ,384,384,384
BEGIN DESCRIPTION:
UNT 079 IN BUCR 4.0
END DESCRIPTION:
XS GIS Cut Line= 3
      3621676.02      10542028.5      3622856.61     10541674.33
      3623634.36     10540625.75
#Sta/Elev= 30
    3541  379.02  3622.6  379.48  3688.7  374.83  3693.9  377.56  3711.8  372.07
  3743.1  368.47  3760.1  362.84  3765.3   363.8  3961.7   341.1  4048.3  332.49
  4171.2  322.63  4254.8  319.57  4473.9  313.73  4732.7  310.33  4928.1  311.82
  4992.5  310.99  4997.9  307.79  5000.7  307.29  5003.9  307.79  5007.1  310.79
  5021.8  311.56  5507.9  313.12  5514.2  309.43  5537.2  313.37  5578.9  311.97
  5743.7  317.13    5800  322.58  5843.9  323.39  5958.7  335.18  6079.1  341.52
#Mann= 6 ,-1 , 0
    3541     .05       0  3961.7     .16       0  4048.3     .05       0
  4254.8     .16       0  4997.9     .07       0  5003.9     .16       0
Bank Sta=4928.1,5021.8
XS Rating Curve= 0 ,0
Exp/Cntr=0.3,0.1

Type RM Length L Ch R = 1 ,1889    ,600,600,600
BEGIN DESCRIPTION:
UNT 079 IN BUCR 3.0
END DESCRIPTION:
XS GIS Cut Line= 3
      3622321.91     10542993.75      3623474.67     10541459.05
      3623821.91     10540549.28
#Sta/Elev= 30
  3505.9   343.5  3542.7  337.81  3742.6  322.45  3835.5  316.96  4035.6  310.98
  4261.7  308.11  4448.7  306.93  4492.5  309.51  4542.5  309.74    4607  307.25
  4642.2   307.9  4992.4  308.33  4995.7  304.32  4998.4  303.82  5001.7  304.32
  5013.2   308.5  5063.2  307.06  5098.7  309.12  5136.1     309  5198.8  307.12
  5531.4  311.14  5638.2  313.27  5721.9   316.7  5931.2  331.34  6034.2  334.53
  6095.6  337.94  6210.6  347.99  6265.4  350.73  6353.1  351.22  6399.1  351.51
#Mann= 8 ,-1 , 0
  3505.9     .05       0  4261.7     .12       0  4642.2     .16       0
  4995.7     .07       0  5001.7     .16       0  5531.4     .05       0
  5721.9     .16       0  6353.1     .05       0
Bank Sta=4992.4,5013.2
XS Rating Curve= 0 ,0
Exp/Cntr=0.3,0.1

Type RM Length L Ch R = 1 ,1289    ,327,327,327
BEGIN DESCRIPTION:
UNT 079 IN BUCR 2.0
END DESCRIPTION:
XS GIS Cut Line= 3
      3623002.47     10543049.29      3623849.67     10541945.16
      3623905.22     10540528.46
#Sta/Elev= 30
  3793.3  341.14  3940.3  336.61    3997  333.86  4061.4  328.15  4111.3  324.51
  4190.1  316.17    4211  315.93    4269  310.25  4410.4  304.29  4611.5  302.97
  4761.2  307.44  4838.3  304.41  4860.9  305.19  4952.4  302.93  4989.6  304.23
    4993  300.62  4995.7  300.12    4999  300.62  5010.5  304.03  5110.2  303.99
  5180.8  306.08  5313.1  302.78  5510.2  302.71  5720.4  308.08  5770.4  312.66
  5850.5  316.23  6081.2  327.29  6320.9  341.48  6417.9  344.36  6602.8  348.13
#Mann= 7 ,-1 , 0
  3793.3     .05       0  3940.3     .16       0  4061.4     .16       0
    4993     .07       0    4999     .16       0  5850.5     .16       0
  6417.9     .05       0
#XS Ineff= 2 ,-1
 4168.18 4756.82  309.26  5180.4 5953.98  308.07
Permanent Ineff=
       F       F
Bank Sta=4989.6,5010.5
XS Rating Curve= 0 ,0
Exp/Cntr=0.3,0.1

Type RM Length L Ch R = 1 ,962     ,595,595,595
BEGIN DESCRIPTION:
Mapping XS d42fbc8a
END DESCRIPTION:
XS GIS Cut Line= 4
      3623089.04     10542991.94      3623878.99     10542505.82
      3624130.72     10542045.75      3623965.79     10540448.51
#Sta/Elev= 30
  3777.4  336.96  3924.3  331.64  4040.3  321.59  4219.8  310.09  4235.3  309.46
    4245  308.98  4272.2  306.77  4424.8  301.05  4564.8  301.03    4600  303.43
  4693.9  304.31  4782.3  301.91  4923.6  301.49  4973.5  302.91  4989.1  301.56
  4993.3  298.51  4996.1  298.01  4999.3  298.51  5005.2  301.84  5121.7  304.21
  5476.2  298.97  5667.2  300.11  5838.2  304.52  6059.3  315.87  6200.1  327.26
  6274.7   330.2    6371   334.7    6381  333.79  6424.4  335.64  6835.1  348.52
#Mann= 9 ,-1 , 0
  3777.4     .05       0  4219.8      .1       0  4235.3     .05       0
    4245     .12       0  4993.3     .07       0  4999.3     .12       0
  5838.2     .05       0  6274.7     .16       0  6424.4     .05       0
Bank Sta=4989.1,5005.2
XS Rating Curve= 0 ,0
Exp/Cntr=0.3,0.1

Type RM Length L Ch R = 1 ,367     ,0,0,0
BEGIN DESCRIPTION:
UNT 079 IN BUCR 1.0
END DESCRIPTION:
XS GIS Cut Line= 4
      3623106.63     10543028.49      3624530.22     10542674.33
      3624606.61      10542014.6      3624023.93     10540433.05
#Sta/Elev= 30
    3215  335.71  3355.1  328.99  3391.2  325.09  3396.4   326.3    3479  319.84
  3515.2  315.41  3568.4  312.78  3680.5  303.83  3784.8  302.18  4140.1   298.3
  4269.3  299.98  4677.3  294.93  4809.5  297.58  4898.3  295.69    4982  296.45
  4988.2  296.45  4998.2  294.75  5010.6   296.3  5189.5  295.98  5345.8  293.24
  5414.9  294.13  5434.5  292.62    5501  294.36  5728.6  295.47  5956.2  299.84
  6070.2  302.23  6384.6  317.75  6477.6  324.56  6599.1  330.91  7031.6  346.23
#Mann= 7 ,-1 , 0
    3215     .05       0  3784.8     .16       0    4982     .08       0
  4998.2     .16       0  5956.2     .05       0  6070.2     .16       0
  6599.1     .05       0
#XS Ineff= 2 ,-1
 4232.95 4963.07299.3116 5036.93 6150.57299.3109
Permanent Ineff=
       F       F
Bank Sta=4988.2,5010.6
XS Rating Curve= 0 ,0
Exp/Cntr=0.3,0.1

Chan Stop Cuts=-1
Use User Specified Reach Order=0
Composite Channel Slope=5