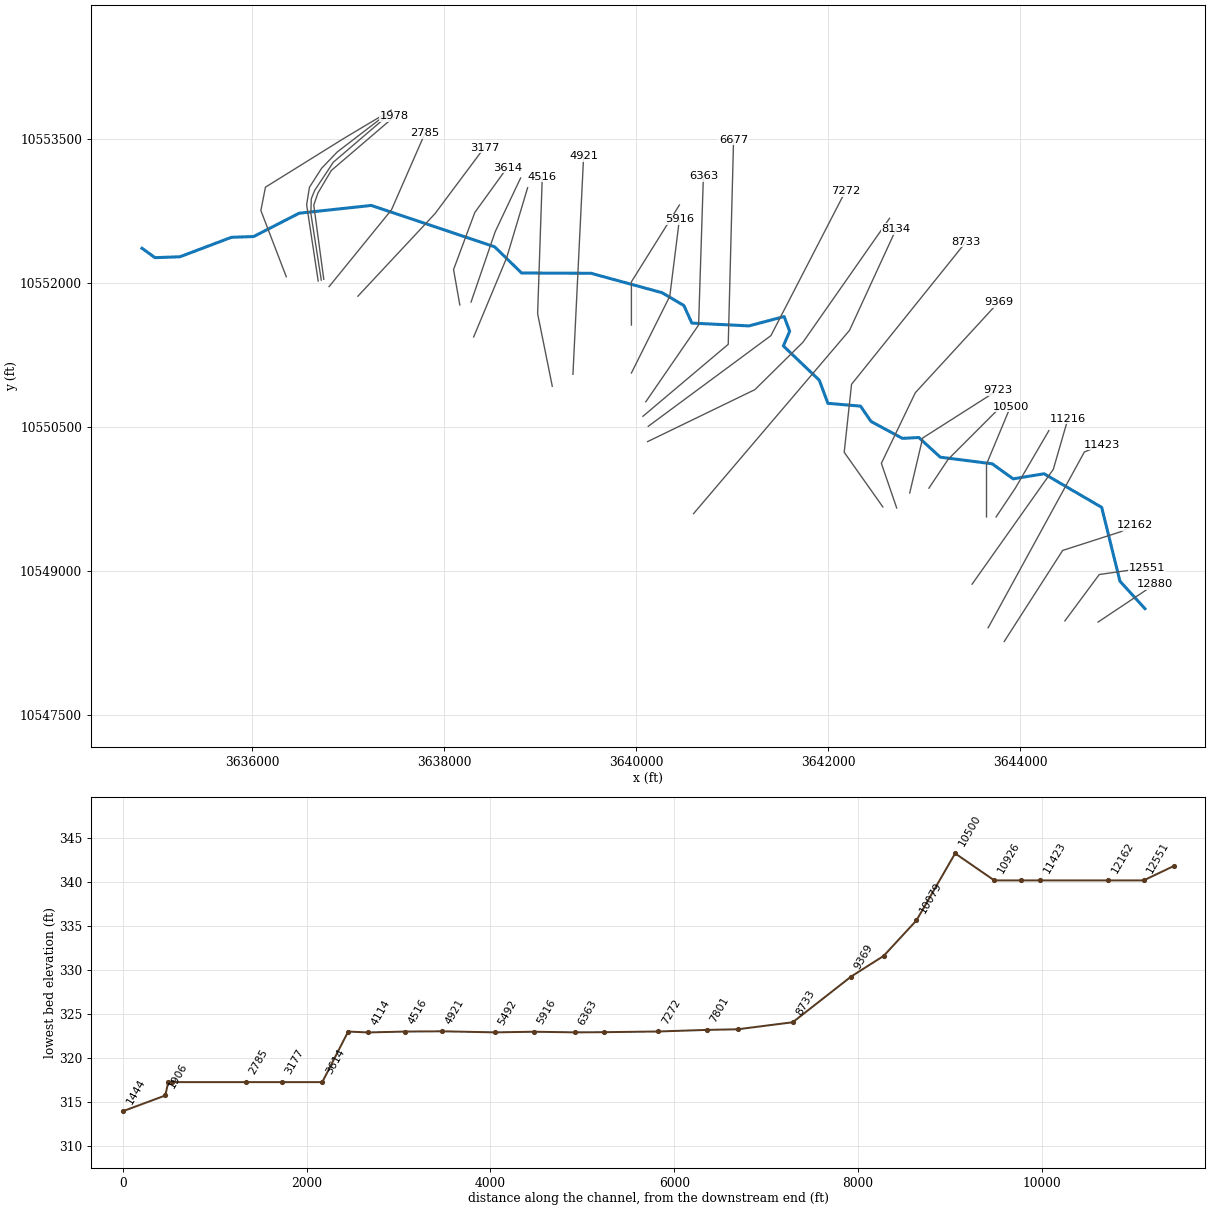
--- UNT 084 IN BUCR.prj (project) ---

Proj Title=UNT 084 IN BUCR Base Level Engineering
Current Plan=p01
Default Exp/Contr=0.3,0.1
English Units
Geom File=g01
Flow File=f01
Plan File=p01
BEGIN DESCRIPTION:
UNT 084 IN BUCR
END DESCRIPTION:

--- UNT 084 IN BUCR.p01 (plan) ---

Plan Title=Multiple Run
Short Identifier=Multiple
Geom File=g01
Flow File=f01
Subcritical Flow
K Sum by GR= 0
Std Step Tol= 0.01
Critical Tol= 0.01
Num of Std Step Trials= 20
Max Error Tol= 0.3
Flow Tol Ratio= 0.001
Split Flow NTrial= 30
Split Flow Tol= 0.02
Split Flow Ratio= 0.02
Log Output Level= 0
Friction Slope Method= 1
Unsteady Friction Slope Method= 2
Unsteady Bridges Friction Slope Method= 1
Parabolic Critical Depth
Global Vel Dist=  1 , 1 , 1
Global Log Level= 0
CheckData=True
Encroach Param= -1, 0, 0, 0
BEGIN DESCRIPTION:
Multiple Run
END DESCRIPTION:

--- UNT 084 IN BUCR.f01 (steady flow) ---

Flow Title=Multiple
Number of Profiles=7
Profile Names=10-year,25-year,50-year,1pct_min,100-year,1pct_plu,500-year
River Rch & RM= UNT 084 IN BUCR,Reach-1,12880
     803    1074    1292    1134    1533    2073    2152
River Rch & RM= UNT 084 IN BUCR,Reach-1,6677
    1317    1803    2201    1956    2646    3578    3812
Boundary for River Rch & Prof#=UNT 084 IN BUCR,Reach-1,1
Up Type=0
Dn Type=3
Dn Slope=0.005
Boundary for River Rch & Prof#=UNT 084 IN BUCR,Reach-1,2
Up Type=0
Dn Type=3
Dn Slope=0.005
Boundary for River Rch & Prof#=UNT 084 IN BUCR,Reach-1,3
Up Type=0
Dn Type=3
Dn Slope=0.005
Boundary for River Rch & Prof#=UNT 084 IN BUCR,Reach-1,4
Up Type=0
Dn Type=3
Dn Slope=0.005
Boundary for River Rch & Prof#=UNT 084 IN BUCR,Reach-1,5
Up Type=0
Dn Type=3
Dn Slope=0.005
Boundary for River Rch & Prof#=UNT 084 IN BUCR,Reach-1,6
Up Type=0
Dn Type=3
Dn Slope=0.005
Boundary for River Rch & Prof#=UNT 084 IN BUCR,Reach-1,7
Up Type=0
Dn Type=3
Dn Slope=0.005

--- UNT 084 IN BUCR.g01 (geometry) ---

Geom Title=Existing Conditions

River Reach=UNT 084 IN BUCR,Reach-1
Reach XY= 30
      3645300.48     10548604.47      3645040.06     10548890.92
      3644849.61     10549660.19      3644249.61     10550010.19
      3643927.02     10549957.17      3643709.25     10550114.00
      3643168.00     10550183.00      3642943.75     10550388.00
      3642773.00     10550379.00      3642446.75     10550555.00
      3642336.50     10550715.00      3641996.75     10550744.00
      3641907.25     10550985.00      3641533.00     10551342.00
      3641598.75     10551495.00      3641541.00     10551648.00
      3641174.50     10551551.00      3640579.50     10551580.00
      3640496.50     10551763.00      3640268.50     10551897.00
      3639529.00     10552099.00      3638805.50     10552102.00
      3638524.50     10552375.00      3637239.50     10552806.00
      3636487.50     10552725.00      3636013.75     10552482.00
      3635782.75     10552474.00      3635244.75     10552271.00
      3634985.50     10552262.00      3634849.50     10552360.00

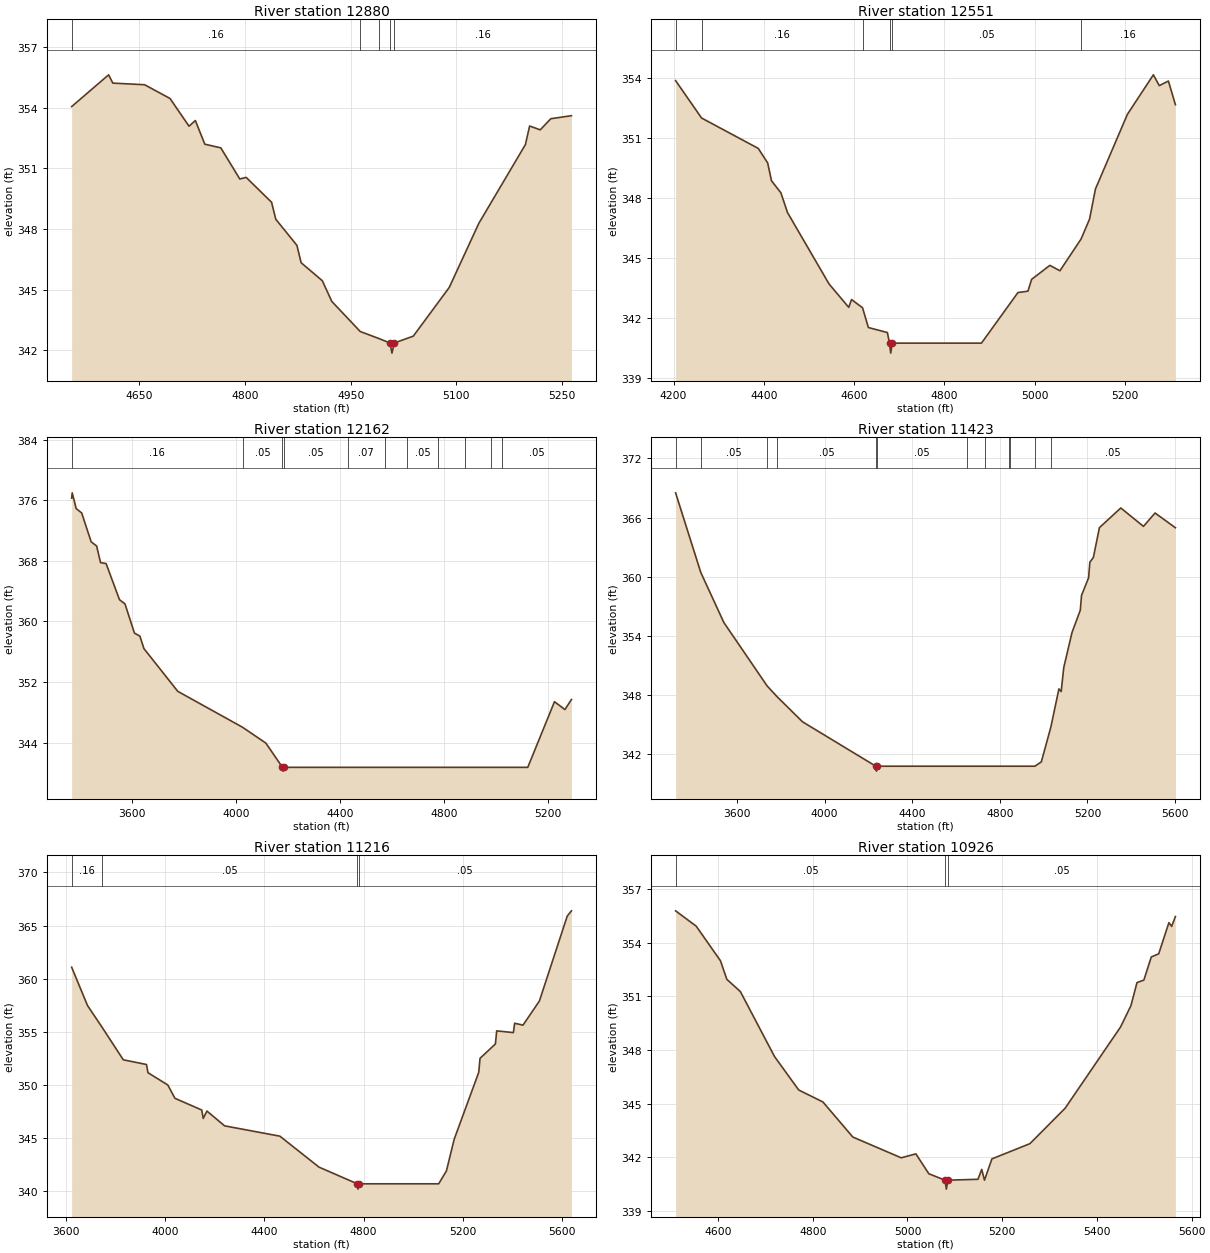
Type RM Length L Ch R = 1,12880,329,329,329
BEGIN DESCRIPTION:
UNT 084 IN BUCR 25.0
END DESCRIPTION:
XS GIS Cut Line= 2
      3644812.28     10548465.15      3645402.87     10548858.87
#Sta/Elev= 30
  4553.7  354.05  4606.2  355.62  4612.2  355.21  4657.3  355.13  4693.4  354.45
  4720.4  353.08  4729.4  353.36  4742.8  352.19  4765.5  352.01  4792.5  350.47
  4801.5  350.55  4837.6  349.32  4843.6  348.48  4873.6  347.19  4879.6  346.33
  4909.7  345.44  4923.1  344.42  4963.5  342.93  4990.2  342.58  5005.8  342.36
  5008.6  341.86  5011.8  342.36  5038.9  342.70  5090.0  345.11  5132.0  348.28
  5198.1  352.17  5204.1  353.09  5219.2  352.90  5234.2  353.45  5263.5  353.60
#Mann=5,-1,0
  4553.7    0.16       0  4963.5    0.05       0  4990.2    0.16       0
  5005.8    0.07       0  5011.8    0.16       0
Bank Sta=5005.8,5011.8
Exp/Cntr=0.3,0.1

Type RM Length L Ch R = 1,12551,389,389,389
BEGIN DESCRIPTION:
UNT 084 IN BUCR 24.0
END DESCRIPTION:
XS GIS Cut Line= 3
      3644466.30     10548477.07      3644824.22     10548960.27
      3645324.92     10549031.79
#Sta/Elev= 30
  4204.6  353.85  4262.1  351.98  4387.7  350.46  4408.6  349.73  4417.0  348.84
  4437.8  348.24  4452.5  347.25  4544.5  343.68  4588.1  342.51  4594.3  342.90
  4618.7  342.49  4631.6  341.50  4673.7  341.25  4678.4  340.72  4681.1  340.22
  4684.4  340.72  4882.1  340.72  4962.9  343.25  4985.1  343.32  4993.2  343.91
  5033.6  344.61  5055.9  344.34  5102.8  345.93  5121.5  346.92  5134.6  348.43
  5205.3  352.16  5262.9  354.14  5276.0  353.60  5296.2  353.83  5311.7  352.65
#Mann=6,-1,0
  4204.6    0.05       0  4262.1    0.16       0  4618.7    0.05       0
  4678.4    0.03       0  4684.4    0.05       0  5102.8    0.16       0
Bank Sta=4678.4,4684.4
Exp/Cntr=0.3,0.1

Type RM Length L Ch R = 1,12162,739,739,739
BEGIN DESCRIPTION:
UNT 084 IN BUCR 23.0
END DESCRIPTION:
XS GIS Cut Line= 4
      3643834.01     10548262.36      3644443.04     10549211.16
      3645043.73     10549404.60      3645191.29     10549474.04
#Sta/Elev= 30
  3368.1  376.27  3370.3  376.97  3385.5  374.89  3406.7  374.31  3443.0  370.51
  3464.1  369.95  3479.3  367.75  3500.5  367.63  3552.0  362.86  3573.2  362.30
  3609.5  358.45  3630.6  358.04  3645.8  356.41  3776.0  350.76  4025.2  346.01
  4114.9  343.92  4178.6  340.72  4181.4  340.22  4184.6  340.72  4429.7  340.72
  4571.9  340.72  4659.0  340.72  4777.1  340.72  4879.7  340.72  4982.3  340.72
  5023.1  340.72  5121.8  340.72  5224.5  349.39  5264.6  348.35  5289.7  349.68
#Mann=11,-1,0
  3368.1    0.16       0  4025.2    0.05       0  4178.6    0.07       0
  4184.6    0.05       0  4429.7    0.07       0  4571.9    0.12       0
  4659.0    0.05       0  4777.1    0.07       0  4879.7    0.05       0
  4982.3     0.1       0  5023.1    0.05       0
Bank Sta=4178.6,4184.6
Exp/Cntr=0.3,0.1

Type RM Length L Ch R = 1,11423,207,207,207
BEGIN DESCRIPTION:
UNT 084 IN BUCR 22.0
END DESCRIPTION:
XS GIS Cut Line= 3
      3643666.97     10548405.50      3644669.12     10550236.82
      3644848.42     10550311.72
#Sta/Elev= 30
  3319.7  368.51  3434.6  360.42  3539.9  355.33  3737.6  348.88  3782.4  347.80
  3899.4  345.23  4234.0  340.72  4236.8  340.22  4240.0  340.72  4648.4  340.72
  4731.2  340.72  4840.7  340.72  4845.5  340.72  4959.8  340.72  4989.4  341.16
  5033.0  344.70  5069.7  348.58  5080.1  348.31  5091.9  350.75  5129.5  354.31
  5167.4  356.58  5173.1  358.09  5205.3  359.88  5211.0  361.46  5227.1  361.94
  5254.7  364.97  5352.3  366.97  5455.8  365.10  5508.8  366.46  5601.6  364.96
#Mann=12,-1,0
  3319.7    0.16       0  3434.6    0.05       0  3737.6    0.16       0
  3782.4    0.05       0  4234.0    0.07       0  4240.0    0.05       0
  4648.4    0.12       0  4731.2    0.07       0  4840.7     0.1       0
  4845.5    0.05       0  4959.8    0.08       0  5033.0    0.05       0
Bank Sta=4234,4240
Exp/Cntr=0.3,0.1

Type RM Length L Ch R = 1,11216,290,290,290
BEGIN DESCRIPTION:
UNT 084 IN BUCR 21.0
END DESCRIPTION:
XS GIS Cut Line= 3
      3643499.62     10548860.20      3644345.70     10550056.45
      3644498.49     10550584.27
#Sta/Elev= 30
  3623.5  361.09  3687.5  357.48  3745.6  355.46  3831.7  352.38  3925.1  351.94
  3931.2  351.17  4011.2  350.01  4039.9  348.76  4147.9  347.66  4154.0  346.87
  4168.8  347.56  4240.1  346.17  4462.9  345.20  4620.5  342.29  4775.0  340.72
  4777.8  340.22  4781.0  340.72  5103.0  340.72  5134.2  341.93  5165.5  344.91
  5264.5  351.20  5269.7  352.52  5331.7  353.87  5336.9  355.10  5404.1  354.94
  5409.3  355.82  5442.9  355.64  5509.0  357.91  5621.3  365.90  5638.2  366.39
#Mann=4,-1,0
  3623.5    0.16       0  3745.6    0.05       0  4775.0    0.03       0
  4781.0    0.05       0
Bank Sta=4775,4781
Exp/Cntr=0.3,0.1

Type RM Length L Ch R = 1,10926,426,426,426
BEGIN DESCRIPTION:
UNT 084 IN BUCR 20.0
END DESCRIPTION:
XS GIS Cut Line= 3
      3643749.60     10549560.18      3643949.61     10549860.19
      3644299.61     10550460.20
#Sta/Elev= 30
  4510.5  355.77  4554.1  354.91  4605.2  352.98  4618.7  351.94  4647.2  351.26
  4719.3  347.63  4770.4  345.76  4821.5  345.09  4884.7  343.13  4986.8  341.97
  5017.8  342.19  5045.1  341.08  5079.3  340.72  5082.1  340.22  5085.3  340.72
  5148.9  340.77  5156.8  341.32  5162.6  340.72  5178.3  341.91  5258.5  342.76
  5332.9  344.74  5449.9  349.28  5471.8  350.47  5484.6  351.76  5499.1  351.90
  5514.8  353.19  5530.5  353.37  5552.0  355.11  5557.8  354.90  5565.7  355.45
#Mann=3,-1,0
  4510.5    0.05       0  5079.3    0.03       0  5085.3    0.05       0
Bank Sta=5079.3,5085.3
Exp/Cntr=0.3,0.1

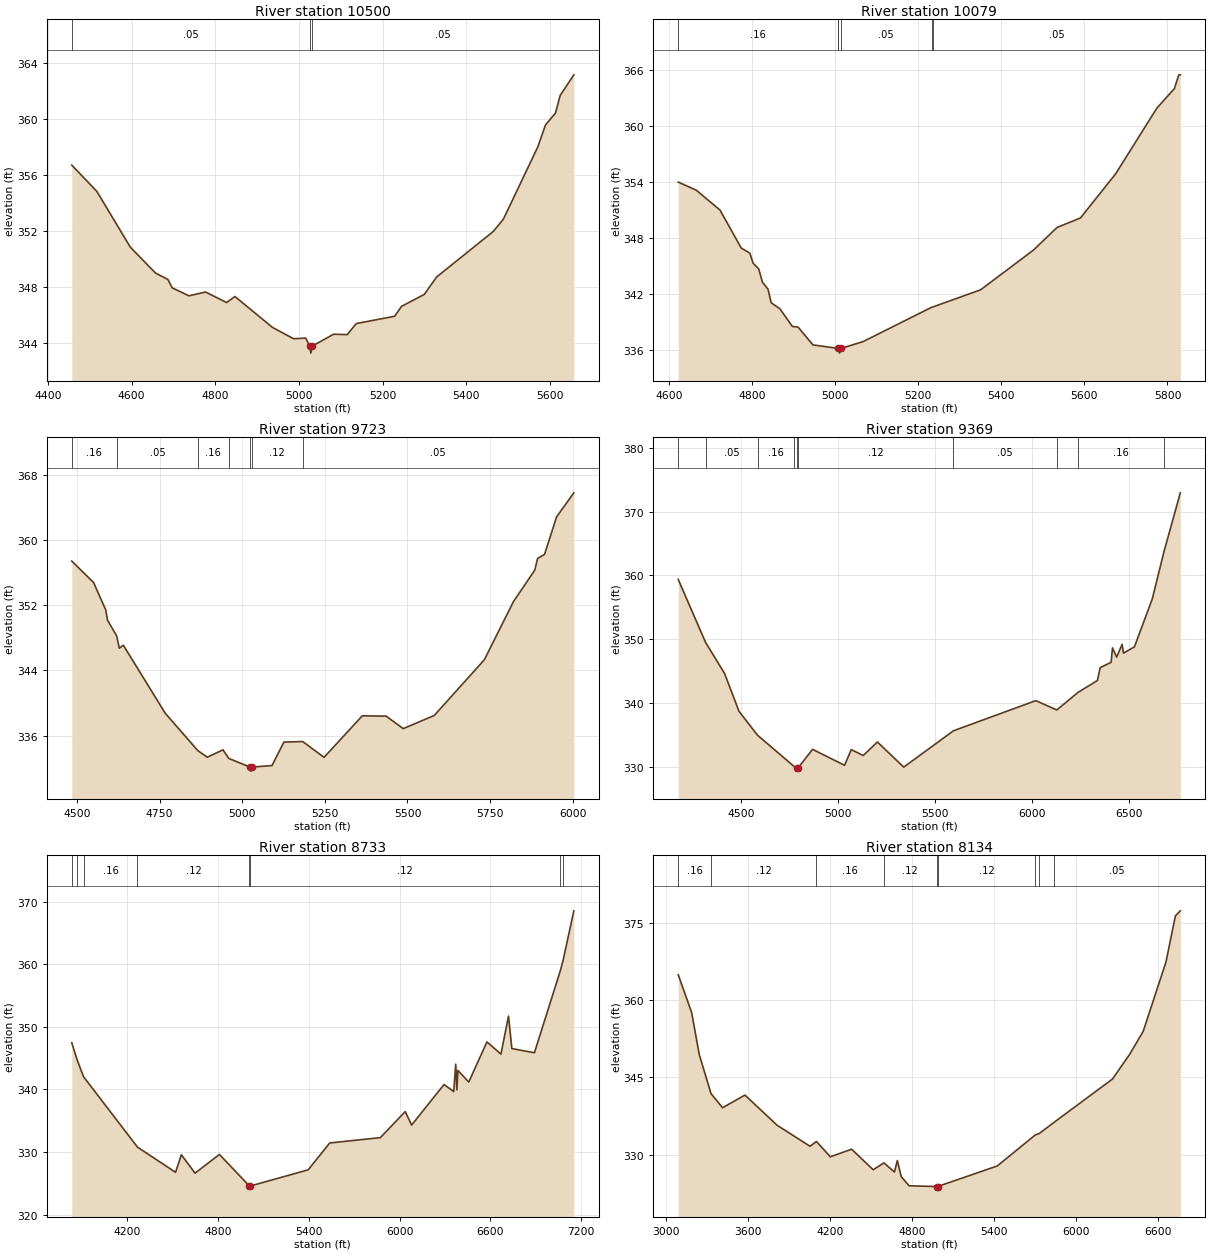
Type RM Length L Ch R = 1,10500,421,421,421
BEGIN DESCRIPTION:
UNT 084 IN BUCR 19.0
END DESCRIPTION:
XS GIS Cut Line= 3
      3643649.61     10549560.18      3643649.61     10550110.19
      3643899.60     10550710.18
#Sta/Elev= 30
  4456.9  356.71  4516.9  354.83  4596.9  350.85  4656.9  349.01  4686.9  348.54
  4696.9  347.95  4736.9  347.38  4776.9  347.65  4826.9  346.90  4846.9  347.33
  4936.9  345.12  4986.9  344.32  5016.1  344.36  5025.6  343.79  5028.3  343.29
  5031.6  343.79  5082.7  344.64  5115.2  344.61  5136.9  345.40  5228.5  345.92
  5245.2  346.63  5299.4  347.48  5329.2  348.73  5464.6  351.98  5488.5  352.85
  5570.8  358.01  5589.2  359.58  5613.0  360.42  5624.4  361.69  5656.9  363.15
#Mann=3,-1,0
  4456.9    0.05       0  5025.6    0.03       0  5031.6    0.05       0
Bank Sta=5025.6,5031.6
Exp/Cntr=0.3,0.1

Type RM Length L Ch R = 1,10079,356,356,356
BEGIN DESCRIPTION:
UNT 084 IN BUCR 18.0
END DESCRIPTION:
XS GIS Cut Line= 3
      3643049.63     10549860.22      3643249.61     10550160.19
      3643849.64     10550760.22
#Sta/Elev= 30
  4621.8  354.01  4665.3  353.14  4722.4  351.01  4773.5  346.94  4794.5  346.38
  4802.0  345.32  4815.6  344.70  4824.6  343.28  4838.1  342.52  4845.6  341.07
  4866.6  340.43  4896.7  338.53  4910.2  338.47  4946.3  336.55  5007.0  336.18
  5007.6  336.17  5010.4  335.67  5013.6  336.17  5067.2  336.91  5231.8  340.58
  5235.0  340.62  5350.0  342.46  5477.3  346.72  5533.9  349.14  5590.4  350.16
  5675.3  354.90  5774.3  361.93  5816.7  364.04  5827.3  365.51  5830.9  365.51
#Mann=6,-1,0
  4621.8    0.16       0  5007.0    0.05       0  5007.6    0.07       0
  5013.6    0.05       0  5231.8    0.16       0  5235.0    0.05       0
Bank Sta=5007.6,5013.6
Exp/Cntr=0.3,0.1

Type RM Length L Ch R = 1,9723,354,354,354
BEGIN DESCRIPTION:
UNT 084 IN BUCR 17.0
END DESCRIPTION:
XS GIS Cut Line= 3
      3642849.62     10549810.23      3642984.59     10550382.84
      3643769.32     10550882.85
#Sta/Elev= 30
  4484.5  357.39  4550.5  354.76  4587.2  351.41  4592.9  350.13  4620.5  348.21
  4628.3  346.71  4640.4  347.08  4767.4  338.73  4866.2  334.14  4894.4  333.35
  4941.9  334.25  4959.4  333.20  5023.6  332.14  5026.3  331.64  5029.6  332.14
  5090.2  332.32  5126.2  335.20  5183.1  335.27  5247.7  333.33  5363.3  338.42
  5435.6  338.38  5487.2  336.85  5581.2  338.47  5732.7  345.30  5820.7  352.43
  5885.1  356.28  5893.5  357.71  5914.7  358.22  5951.1  362.81  6003.3  365.76
#Mann=7,-1,0
  4484.5    0.16       0  4620.5    0.05       0  4866.2    0.16       0
  4959.4    0.12       0  5023.6    0.07       0  5029.6    0.12       0
  5183.1    0.05       0
Bank Sta=5023.6,5029.6
Exp/Cntr=0.3,0.1

Type RM Length L Ch R = 1,9369,636,636,636
BEGIN DESCRIPTION:
UNT 084 IN BUCR 16.0
END DESCRIPTION:
XS GIS Cut Line= 4
      3642713.74     10549653.70      3642554.03     10550118.95
      3642908.20     10550855.06      3643775.40     10551798.58
#Sta/Elev= 30
  4175.9  359.37  4317.1  349.48  4414.9  344.62  4489.4  338.68  4584.9  334.93
  4775.3  329.98  4788.2  329.79  4791.0  329.29  4794.2  329.79  4868.9  332.71
  5034.0  330.21  5068.7  332.67  5130.1  331.74  5203.5  333.86  5339.3  329.92
  5595.9  335.62  6020.4  340.35  6129.2  338.89  6238.7  341.65  6338.5  343.51
  6352.7  345.52  6409.4  346.37  6416.2  348.63  6437.8  347.18  6466.1  349.19
  6472.9  347.80  6529.6  348.80  6621.5  356.30  6681.8  363.71  6766.2  372.96
#Mann=10,-1,0
  4175.9    0.16       0  4317.1    0.05       0  4584.9    0.16       0
  4775.3    0.12       0  4788.2    0.07       0  4794.2    0.12       0
  5595.9    0.05       0  6129.2    0.12       0  6238.7    0.16       0
  6681.8    0.05       0
Bank Sta=4788.2,4794.2
Exp/Cntr=0.3,0.1

Type RM Length L Ch R = 1,8733,599,599,599
BEGIN DESCRIPTION:
UNT 084 IN BUCR 15.0
END DESCRIPTION:
XS GIS Cut Line= 4
      3642569.67     10549664.50      3642166.88     10550233.97
      3642243.27     10550942.30      3643437.72     10552428.42
#Sta/Elev= 30
  3834.6  347.46  3869.8  344.75  3912.3  342.04  4268.6  330.80  4520.1  326.78
  4558.5  329.57  4649.0  326.64  4809.9  329.63  5008.1  324.59  5010.9  324.09
  5014.1  324.59  5396.3  327.17  5538.7  331.46  5873.1  332.31  6037.3  336.47
  6079.5  334.32  6293.8  340.79  6357.8  339.67  6370.9  344.04  6378.7  339.94
  6385.1  343.04  6457.1  341.19  6577.1  347.59  6669.9  345.65  6719.5  351.72
  6741.8  346.53  6890.7  345.86  7062.0  358.96  7080.6  360.66  7151.2  368.52
#Mann=8,-1,0
  3834.6    0.16       0  3869.8    0.05       0  3912.3    0.16       0
  4268.6    0.12       0  5008.1    0.07       0  5014.1    0.12       0
  7062.0    0.16       0  7080.6    0.12       0
Bank Sta=5008.1,5014.1
Exp/Cntr=0.3,0.1

Type RM Length L Ch R = 1,8134,333,333,333
BEGIN DESCRIPTION:
UNT 084 IN BUCR 14.0
END DESCRIPTION:
XS GIS Cut Line= 3
      3640597.42     10549595.07      3642222.43     10551504.80
      3642708.53     10552560.32
#Sta/Elev= 30
  3092.7  364.96  3190.6  357.64  3246.5  349.43  3332.4  341.85  3416.8  339.11
  3580.4  341.57  3814.3  335.73  4055.9  331.62  4103.0  332.55  4204.2  329.58
  4360.1  331.05  4517.2  327.06  4595.8  328.39  4673.1  326.62  4694.0  328.85
  4722.5  325.73  4779.6  323.94  4982.0  323.79  4984.7  323.29  4988.0  323.79
  5424.2  327.79  5703.3  333.84  5730.6  334.08  5840.5  336.29  6266.7  344.69
  6393.8  349.56  6491.2  353.97  6657.4  367.42  6726.3  376.40  6762.3  377.38
#Mann=9,-1,0
  3092.7    0.16       0  3332.4    0.12       0  4103.0    0.16       0
  4595.8    0.12       0  4982.0    0.07       0  4988.0    0.12       0
  5703.3    0.05       0  5730.6    0.12       0  5840.5    0.05       0
Bank Sta=4982,4988
Exp/Cntr=0.3,0.1

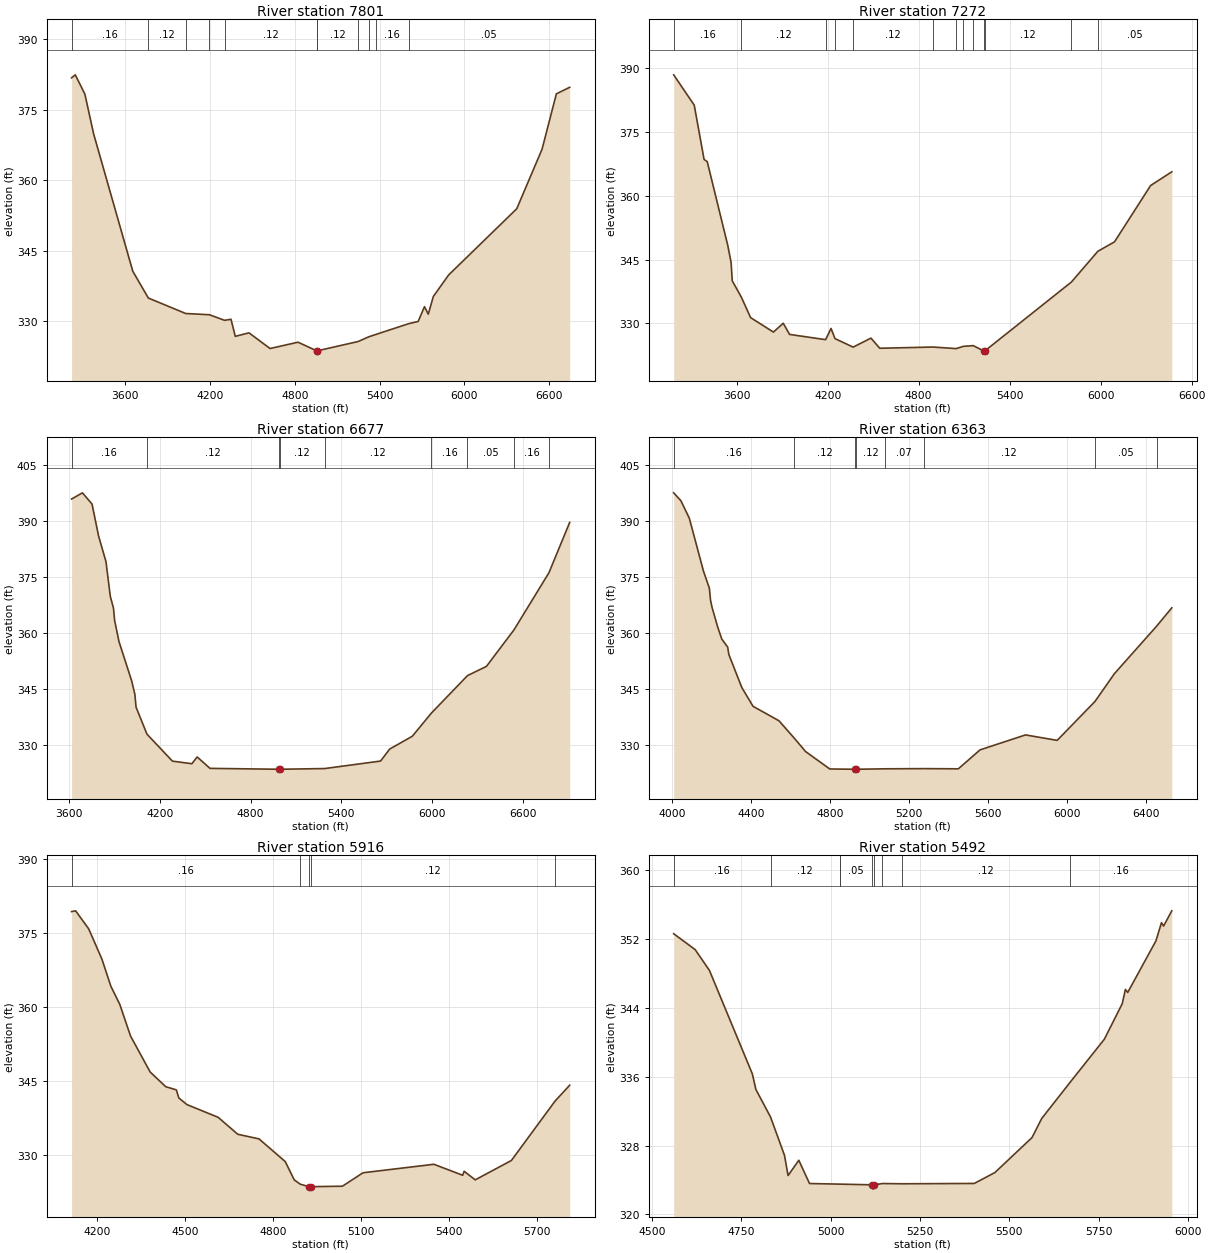
Type RM Length L Ch R = 1,7801,529,529,529
BEGIN DESCRIPTION:
UNT 084 IN BUCR 13.0
END DESCRIPTION:
XS GIS Cut Line= 4
      3640118.27     10550345.08      3641236.32     10550886.75
      3641736.32     10551379.80      3642639.13     10552671.51
#Sta/Elev= 30
  3223.1  381.73  3249.3  382.37  3317.1  378.28  3379.2  369.80  3655.8  340.62
  3765.7  334.93  4029.9  331.64  4197.0  331.38  4304.9  330.19  4349.8  330.42
  4380.2  326.79  4477.3  327.53  4625.7  324.20  4823.7  325.54  4955.2  323.72
  4957.9  323.22  4961.2  323.72  5248.9  325.69  5323.5  326.69  5373.8  327.19
  5604.6  329.47  5672.7  329.95  5717.2  333.10  5744.2  331.50  5779.9  335.26
  5888.0  339.83  6369.5  353.91  6548.3  366.56  6649.5  378.33  6743.6  379.72
#Mann=11,-1,0
  3223.1    0.16       0  3765.7    0.12       0  4029.9    0.05       0
  4197.0    0.16       0  4304.9    0.12       0  4955.2    0.07       0
  4961.2    0.12       0  5248.9    0.16       0  5323.5    0.12       0
  5373.8    0.16       0  5604.6    0.05       0
Bank Sta=4955.2,4961.2
Exp/Cntr=0.3,0.1

Type RM Length L Ch R = 1,7272,595,595,595
BEGIN DESCRIPTION:
UNT 084 IN BUCR 12.0
END DESCRIPTION:
XS GIS Cut Line= 3
      3640125.23     10550504.81      3641402.99     10551449.25
      3642180.52     10552955.72
#Sta/Elev= 30
  3184.9  388.33  3320.5  381.21  3385.3  368.47  3406.1  367.97  3541.8  348.27
  3563.4  344.33  3571.1  339.99  3630.8  336.19  3692.1  331.37  3842.4  327.98
  3907.2  330.05  3948.9  327.43  4186.4  326.20  4222.4  328.83  4248.4  326.45
  4367.9  324.45  4485.4  326.56  4543.9  324.18  4894.9  324.47  5047.1  324.10
  5095.3  324.63  5159.8  324.80  5229.9  323.54  5232.7  323.04  5235.9  323.54
  5807.5  339.73  5981.1  346.92  6091.5  349.15  6329.4  362.36  6469.1  365.58
#Mann=13,-1,0
  3184.9    0.16       0  3630.8    0.12       0  4186.4    0.16       0
  4248.4    0.05       0  4367.9    0.12       0  4894.9    0.08       0
  5047.1    0.05       0  5095.3    0.08       0  5159.8    0.12       0
  5229.9    0.07       0  5235.9    0.12       0  5807.5    0.16       0
  5981.1    0.05       0
Bank Sta=5229.9,5235.9
Exp/Cntr=0.3,0.1

Type RM Length L Ch R = 1,6677,314,314,314
BEGIN DESCRIPTION:
UNT 084 IN BUCR 11.0
END DESCRIPTION:
XS GIS Cut Line= 3
      3640069.68     10550608.99      3640958.54     10551358.97
      3641014.10     10553490.95
#Sta/Elev= 30
  3615.9  395.93  3687.7  397.60  3751.4  394.59  3794.3  386.08  3843.7  379.12
  3872.3  369.81  3893.1  366.70  3900.9  363.35  3929.5  357.72  4014.0  347.11
  4034.9  343.52  4042.6  340.13  4114.5  332.89  4283.2  325.64  4411.9  324.95
  4447.0  326.76  4531.7  323.70  4987.2  323.46  4989.9  322.96  4993.2  323.46
  5290.8  323.65  5660.4  325.66  5720.4  328.87  5870.5  332.32  5996.5  338.52
  6235.4  348.58  6360.7  351.05  6543.3  360.86  6774.6  376.19  6911.6  389.67
#Mann=9,-1,0
  3615.9    0.16       0  4114.5    0.12       0  4987.2    0.07       0
  4993.2    0.12       0  5290.8    0.12       0  5996.5    0.16       0
  6235.4    0.05       0  6543.3    0.16       0  6774.6    0.05       0
Bank Sta=4987.2,4993.2
Exp/Cntr=0.3,0.1

Type RM Length L Ch R = 1,6363,447,447,447
BEGIN DESCRIPTION:
UNT 084 IN BUCR 10.0
END DESCRIPTION:
XS GIS Cut Line= 3
      3640099.64     10550760.23      3640649.61     10551560.19
      3640699.61     10553110.20
#Sta/Elev= 30
  4009.4  397.62  4045.8  395.51  4088.5  390.81  4160.2  376.61  4190.0  372.02
  4196.1  368.75  4203.5  366.91  4231.9  361.65  4252.9  358.38  4282.7  356.23
  4288.7  354.23  4354.4  345.36  4411.2  340.33  4542.5  336.45  4619.7  331.79
  4677.1  328.20  4799.5  323.52  4927.8  323.44  4930.6  322.94  4933.8  323.44
  5078.0  323.56  5274.5  323.61  5450.4  323.56  5560.5  328.65  5790.6  332.66
  5950.7  331.19  6142.2  341.64  6240.8  349.11  6453.8  361.82  6531.0  366.76
#Mann=8,-1,0
  4009.4    0.16       0  4619.7    0.12       0  4927.8    0.07       0
  4933.8    0.12       0  5078.0    0.07       0  5274.5    0.12       0
  6142.2    0.05       0  6453.8    0.16       0
Bank Sta=4927.8,4933.8
Exp/Cntr=0.3,0.1

Type RM Length L Ch R = 1,5916,424,424,424
BEGIN DESCRIPTION:
UNT 084 IN BUCR 9.0
END DESCRIPTION:
XS GIS Cut Line= 3
      3639949.63     10551060.22      3640349.61     10551860.19
      3640449.61     10552660.17
#Sta/Elev= 30
  4111.6  379.30  4125.5  379.46  4170.3  375.78  4215.0  369.70  4245.7  364.17
  4276.5  360.45  4312.8  354.08  4379.9  346.77  4433.0  343.79  4469.3  343.14
  4477.7  341.51  4505.7  340.15  4611.9  337.58  4679.0  334.14  4751.6  333.20
  4841.1  328.60  4871.8  324.89  4892.1  324.02  4921.9  323.51  4924.7  323.01
  4927.9  323.51  5036.2  323.60  5106.8  326.33  5348.6  328.05  5446.9  325.82
  5451.9  326.63  5489.7  324.89  5613.2  328.82  5761.9  340.84  5812.2  344.09
#Mann=5,-1,0
  4111.6    0.16       0  4892.1    0.12       0  4921.9    0.07       0
  4927.9    0.12       0  5761.9    0.16       0
Bank Sta=4921.9,4927.9
Exp/Cntr=0.3,0.1

Type RM Length L Ch R = 1,5492,571,571,571
BEGIN DESCRIPTION:
UNT 084 IN BUCR 8.0
END DESCRIPTION:
XS GIS Cut Line= 3
      3639949.61     10551560.22      3639949.61     10552010.19
      3640449.63     10552810.22
#Sta/Elev= 30
  4561.3  352.60  4621.3  350.76  4661.3  348.34  4781.3  336.33  4791.3  334.51
  4832.3  331.31  4871.3  326.86  4881.3  324.52  4911.3  326.29  4941.3  323.59
  5025.9  323.52  5026.7  323.52  5116.2  323.44  5118.9  322.94  5122.2  323.44
  5145.2  323.59  5200.9  323.56  5402.2  323.60  5460.0  324.87  5563.7  328.93
  5590.9  331.15  5670.3  335.35  5766.0  340.35  5816.1  344.48  5824.9  346.13
  5831.4  345.78  5910.4  351.78  5925.8  353.89  5931.7  353.49  5954.7  355.26
#Mann=9,-1,0
  4561.3    0.16       0  4832.3    0.12       0  5025.9    0.07       0
  5026.7    0.05       0  5116.2    0.07       0  5122.2    0.05       0
  5145.2    0.16       0  5200.9    0.12       0  5670.3    0.16       0
Bank Sta=5116.2,5122.2
Exp/Cntr=0.3,0.1

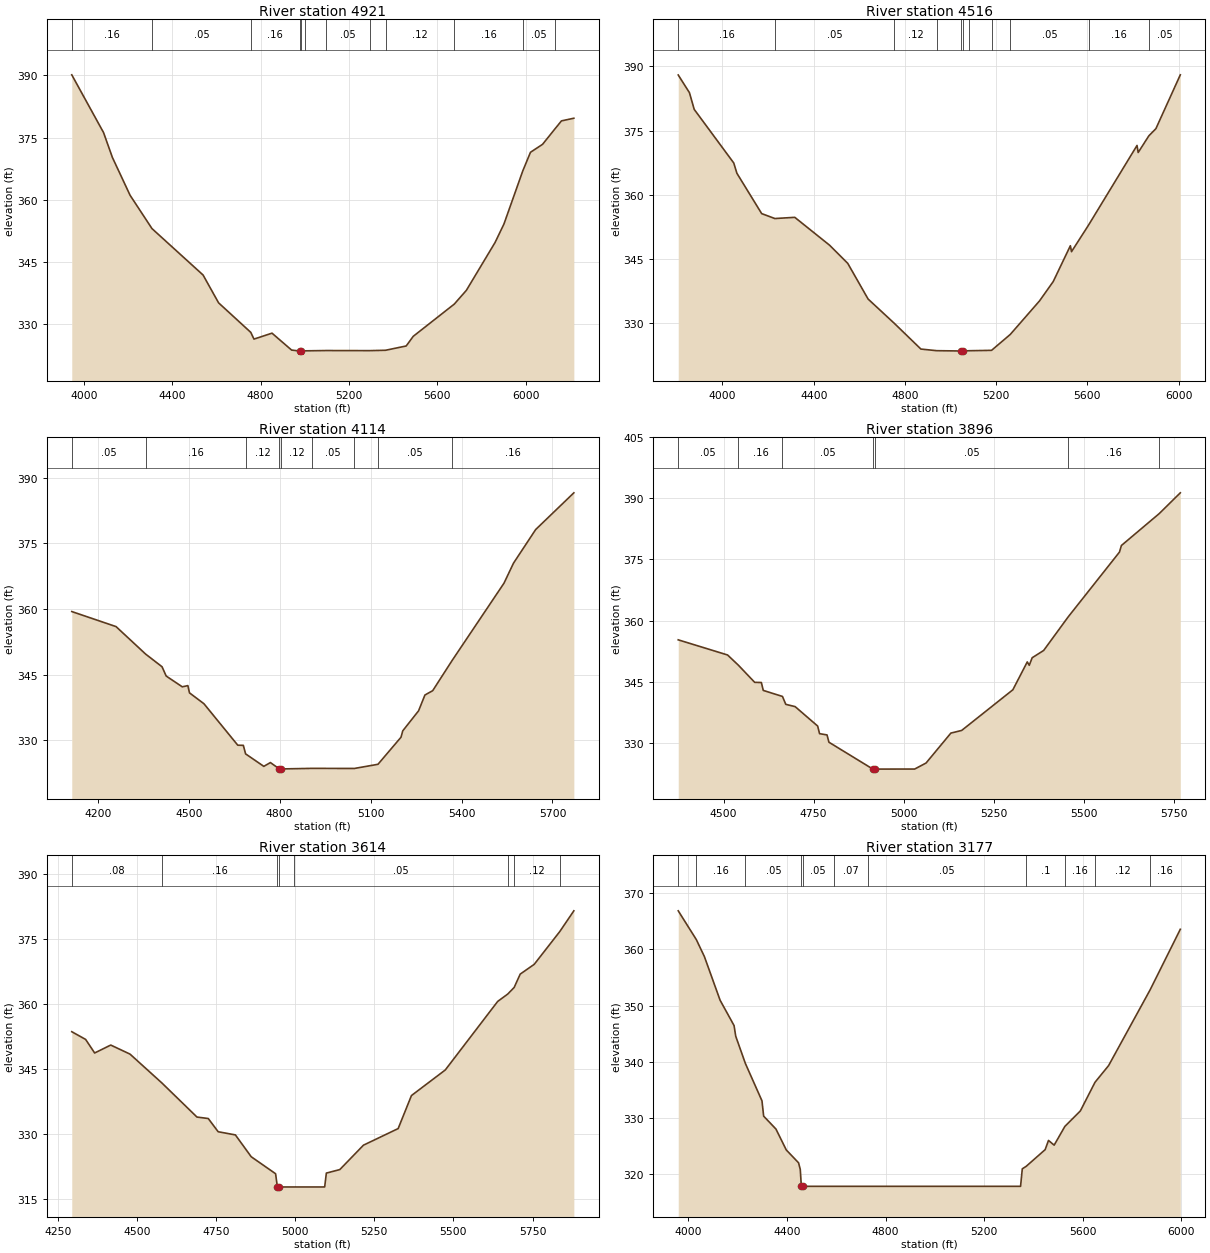
Type RM Length L Ch R = 1,4921,405,405,405
BEGIN DESCRIPTION:
UNT 084 IN BUCR 7.0
END DESCRIPTION:
XS GIS Cut Line= 2
      3639340.49     10551046.46      3639451.55     10553316.25
#Sta/Elev= 30
  3945.2  390.13  4089.1  376.21  4129.1  370.22  4209.2  361.10  4308.3  353.07
  4539.6  341.88  4609.7  335.18  4755.5  328.06  4769.9  326.44  4851.5  327.87
  4940.1  323.80  4977.2  323.56  4979.9  323.06  4983.2  323.56  4999.3  323.61
  5097.7  323.68  5294.5  323.66  5365.4  323.75  5458.8  324.78  5490.8  327.11
  5676.4  334.87  5731.1  338.18  5861.2  349.73  5901.3  354.17  5986.6  366.98
  6021.4  371.46  6076.1  373.38  6131.4  377.05  6161.6  379.03  6217.7  379.67
#Mann=12,-1,0
  3945.2    0.16       0  4308.3    0.05       0  4755.5    0.16       0
  4977.2    0.07       0  4983.2    0.16       0  4999.3    0.07       0
  5097.7    0.05       0  5294.5    0.16       0  5365.4    0.12       0
  5676.4    0.16       0  5986.6    0.05       0  6131.4    0.16       0
Bank Sta=4977.2,4983.2
Exp/Cntr=0.3,0.1

Type RM Length L Ch R = 1,4516,402,402,402
BEGIN DESCRIPTION:
UNT 084 IN BUCR 6.0
END DESCRIPTION:
XS GIS Cut Line= 3
      3639125.20     10550921.51      3638972.43     10551678.41
      3639020.98     10553107.12
#Sta/Elev= 30
  3806.0  387.98  3855.1  383.86  3876.1  379.95  4049.5  367.43  4063.3  365.03
  4171.9  355.61  4229.8  354.46  4317.1  354.74  4469.5  348.24  4549.4  343.99
  4638.6  335.66  4753.7  329.98  4870.1  323.98  4939.4  323.60  5047.2  323.53
  5050.0  323.03  5053.2  323.53  5081.7  323.59  5180.0  323.68  5262.0  327.39
  5390.4  335.23  5450.4  339.74  5525.6  348.11  5530.6  346.72  5605.1  352.91
  5817.9  371.53  5822.9  369.88  5869.7  373.77  5900.7  375.45  6007.7  388.02
#Mann=11,-1,0
  3806.0    0.16       0  4229.8    0.05       0  4753.7    0.12       0
  4939.4    0.07       0  5047.2    0.07       0  5053.2    0.07       0
  5081.7    0.05       0  5180.0    0.16       0  5262.0    0.05       0
  5605.1    0.16       0  5869.7    0.05       0
Bank Sta=5047.2,5053.2
Exp/Cntr=0.3,0.1

Type RM Length L Ch R = 1,4114,218,218,218
BEGIN DESCRIPTION:
UNT 084 IN BUCR 5.0
END DESCRIPTION:
XS GIS Cut Line= 3
      3638305.75     10551435.32      3638649.61     10552260.19
      3638868.26     10552990.90
#Sta/Elev= 30
  4114.2  359.41  4260.3  355.97  4357.8  349.69  4412.0  346.79  4425.7  344.67
  4478.8  342.20  4497.2  342.48  4502.6  340.82  4550.2  338.34  4661.8  328.86
  4680.2  328.82  4687.7  326.87  4747.9  324.02  4769.5  324.89  4799.0  323.43
  4801.8  322.93  4805.0  323.43  4906.8  323.56  5046.6  323.54  5124.4  324.49
  5200.4  330.68  5206.2  332.14  5258.4  336.72  5279.3  340.33  5304.9  341.32
  5368.9  348.21  5540.2  365.90  5571.5  370.47  5644.6  378.15  5770.6  386.55
#Mann=9,-1,0
  4114.2    0.05       0  4357.8    0.16       0  4687.7    0.12       0
  4799.0   0.035       0  4805.0    0.12       0  4906.8    0.05       0
  5046.6    0.16       0  5124.4    0.05       0  5368.9    0.16       0
Bank Sta=4799,4805
Exp/Cntr=0.3,0.1

Type RM Length L Ch R = 1,3896,282,282,282
BEGIN DESCRIPTION:
Mapping XS dcc448e1
END DESCRIPTION:
XS GIS Cut Line= 3
      3638278.83     10551799.36      3638530.58     10552532.91
      3638794.96     10553092.00
#Sta/Elev= 30
  4374.2  355.27  4511.2  351.55  4541.1  349.05  4586.5  344.83  4605.0  344.79
  4610.3  342.85  4663.6  341.37  4672.8  339.43  4698.8  338.87  4761.3  334.10
  4766.6  332.23  4787.3  331.92  4792.6  330.13  4914.6  323.53  4917.4  323.03
  4920.6  323.53  5030.6  323.54  5062.3  325.02  5131.2  332.37  5161.2  333.02
  5303.3  343.01  5343.3  349.85  5348.8  349.02  5356.9  350.87  5388.8  352.66
  5456.6  360.87  5599.2  376.81  5604.7  378.44  5709.7  386.27  5768.2  391.37
#Mann=7,-1,0
  4374.2    0.05       0  4541.1    0.16       0  4663.6    0.05       0
  4914.6    0.03       0  4920.6    0.05       0  5456.6    0.16       0
  5709.7    0.12       0
Bank Sta=4914.6,4920.6
Exp/Cntr=0.3,0.1

Type RM Length L Ch R = 1,3614,437,437,437
BEGIN DESCRIPTION:
UNT 084 IN BUCR 4.0
END DESCRIPTION:
XS GIS Cut Line= 4
      3638161.67     10551768.98      3638096.55     10552137.94
      3638317.91     10552732.56      3638655.53     10553200.04
#Sta/Elev= 30
  4294.6  353.60  4338.4  351.82  4366.9  348.69  4417.7  350.52  4478.6  348.43
  4579.3  341.77  4690.0  333.91  4725.7  333.57  4757.0  330.52  4811.4  329.79
  4861.4  324.75  4938.4  320.83  4944.0  317.78  4946.8  317.28  4950.0  317.78
  4997.5  317.78  5093.4  317.78  5098.7  320.98  5141.2  321.79  5215.9  327.42
  5325.5  331.25  5367.5  338.87  5474.3  344.77  5639.9  360.59  5671.5  362.28
  5691.9  363.81  5711.0  366.89  5755.2  369.14  5835.9  376.70  5880.4  381.49
#Mann=8,-1,0
  4294.6    0.08       0  4579.3    0.16       0  4944.0   0.035       0
  4950.0    0.16       0  4997.5    0.05       0  5671.5    0.16       0
  5691.9    0.12       0  5835.9    0.16       0
Bank Sta=4944,4950
Exp/Cntr=0.3,0.1

Type RM Length L Ch R = 1,3177,392,392,392
BEGIN DESCRIPTION:
UNT 084 IN BUCR 3.0
END DESCRIPTION:
XS GIS Cut Line= 3
      3637099.58     10551860.16      3637902.99     10552720.08
      3638417.71     10553409.62
#Sta/Elev= 30
  3958.7  366.89  4032.0  361.77  4065.0  358.72  4128.5  350.96  4185.2  346.44
  4192.0  344.54  4231.1  339.69  4298.5  333.02  4305.3  330.29  4355.2  327.99
  4397.2  324.26  4447.0  321.97  4453.9  320.78  4458.2  317.78  4460.9  317.28
  4464.2  317.78  4589.3  317.78  4728.6  317.78  5347.8  317.78  5354.8  320.90
  5370.5  321.34  5447.6  324.32  5461.1  325.96  5484.1  325.12  5527.6  328.46
  5590.4  331.22  5649.9  336.33  5705.0  339.30  5873.6  352.81  5996.0  363.60
#Mann=11,-1,0
  3958.7    0.05       0  4032.0    0.16       0  4231.1    0.05       0
  4458.2   0.033       0  4464.2    0.05       0  4589.3    0.07       0
  4728.6    0.05       0  5370.5     0.1       0  5527.6    0.16       0
  5649.9    0.12       0  5873.6    0.16       0
Bank Sta=4458.2,4464.2
Exp/Cntr=0.3,0.1

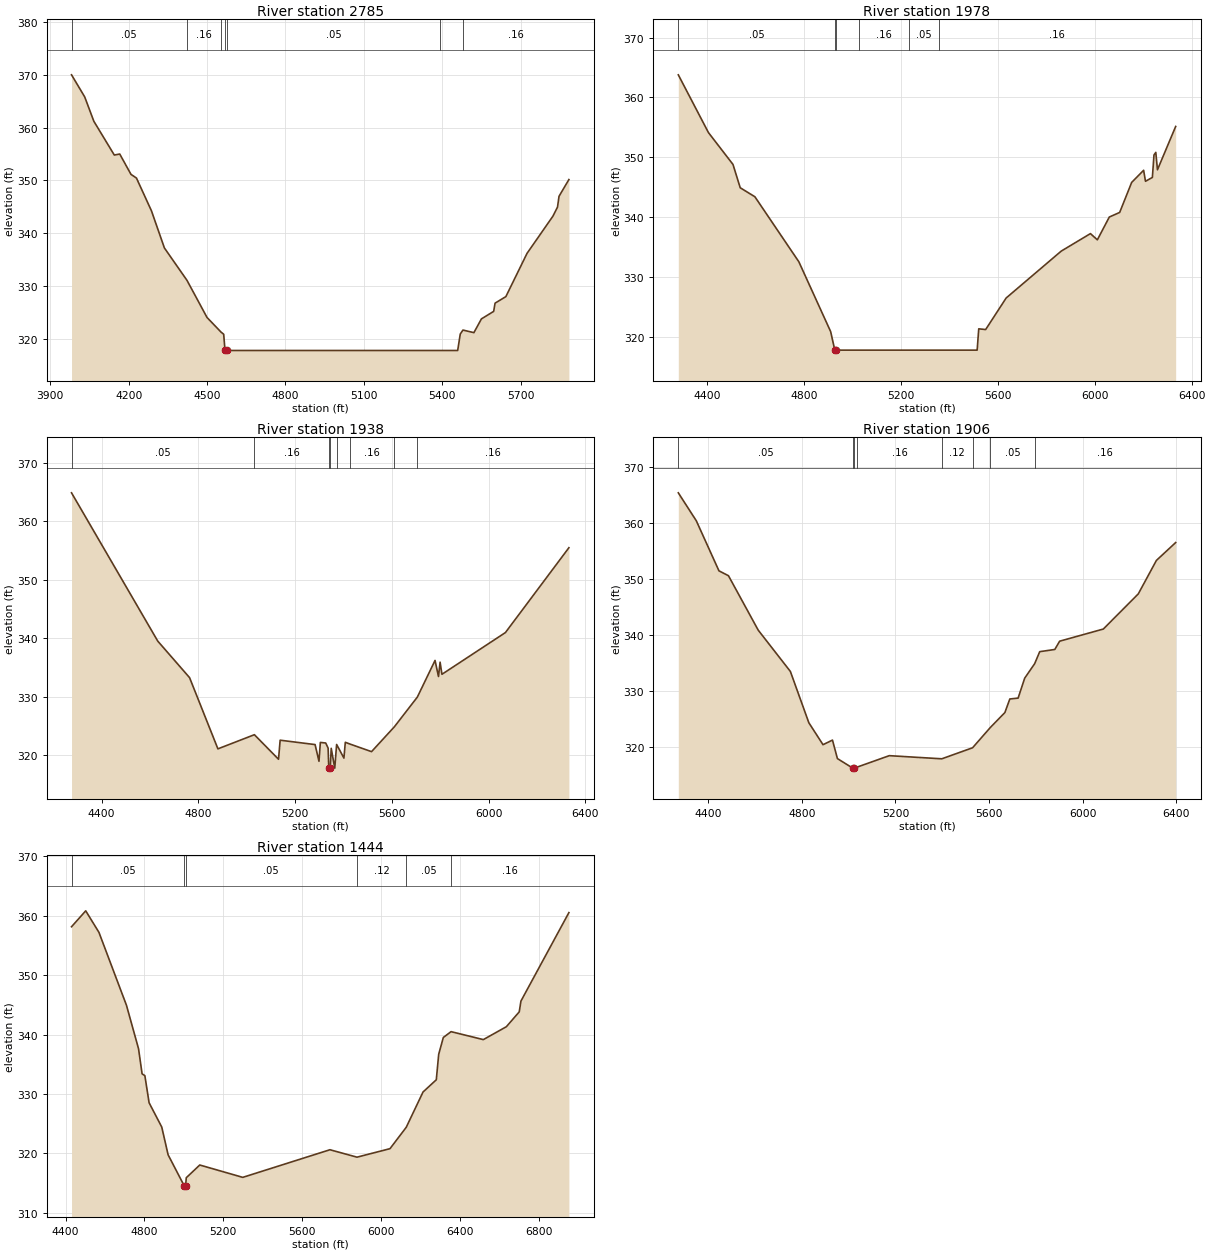
Type RM Length L Ch R = 1,2785,807,807,807
BEGIN DESCRIPTION:
UNT 084 IN BUCR 2.0
END DESCRIPTION:
XS GIS Cut Line= 3
      3636799.64     10551960.23      3637449.61     10552760.19
      3637799.59     10553560.15
#Sta/Elev= 30
  3981.1  370.02  4031.4  365.85  4066.5  361.22  4144.8  354.82  4165.6  355.01
  4208.8  351.15  4229.6  350.46  4287.1  344.24  4336.6  337.21  4423.1  331.07
  4499.7  324.04  4553.7  321.25  4563.6  320.86  4568.5  317.78  4571.3  317.28
  4574.5  317.78  5392.0  317.78  5459.3  317.78  5469.1  320.89  5479.5  321.65
  5521.3  321.16  5550.2  323.77  5597.0  325.19  5602.4  326.75  5643.7  327.99
  5724.8  336.19  5823.8  343.23  5841.4  344.95  5847.2  347.00  5885.0  350.17
#Mann=7,-1,0
  3981.1    0.05       0  4423.1    0.16       0  4553.7    0.05       0
  4568.5   0.033       0  4574.5    0.05       0  5392.0     0.1       0
  5479.5    0.16       0
Bank Sta=4568.5,4574.5
Exp/Cntr=0.3,0.1

Type RM Length L Ch R = 1,1978,40,40,40
BEGIN DESCRIPTION:
Mapping XS f95a1061
END DESCRIPTION:
XS GIS Cut Line= 5
      3636744.14     10552036.91      3636639.97     10552809.49
      3636683.37     10552935.36      3636822.26     10553169.73
      3637481.94     10553733.94
#Sta/Elev= 30
  4280.9  363.78  4405.3  354.13  4506.6  348.81  4536.5  344.91  4597.0  343.41
  4778.6  332.54  4909.8  320.88  4927.0  317.78  4929.8  317.28  4933.0  317.78
  5027.5  317.78  5232.4  317.78  5357.0  317.78  5514.6  317.78  5521.2  321.34
  5549.7  321.22  5634.3  326.49  5861.5  334.32  5982.2  337.25  6010.8  336.21
  6060.2  340.02  6103.0  340.79  6152.4  345.80  6201.8  347.83  6209.5  345.99
  6238.0  346.64  6244.6  350.39  6252.1  350.82  6258.9  347.91  6334.1  355.15
#Mann=6,-1,0
  4280.9    0.05       0  4927.0    0.03       0  4933.0    0.05       0
  5027.5    0.16       0  5232.4    0.05       0  5357.0    0.16       0
Bank Sta=4927,4933
Exp/Cntr=0.3,0.1

Type RM Length L Ch R = 1,1938,32,32,32
BEGIN DESCRIPTION:
Mapping XS 7a8848d2
END DESCRIPTION:
XS GIS Cut Line= 6
      3636718.10     10552028.20      3636609.59     10552722.68
      3636613.93     10552874.59      3636648.65     10552961.40
      3636843.96     10553256.54      3637414.67     10553745.10
#Sta/Elev= 30
  4276.1  364.88  4632.4  339.52  4763.9  333.27  4881.0  321.09  5031.8  323.51
  5131.5  319.31  5138.2  322.57  5282.6  321.82  5298.7  318.96  5304.4  322.19
  5326.5  322.09  5336.5  321.21  5339.2  317.78  5341.9  317.28  5345.2  317.78
  5349.3  321.18  5363.9  317.78  5371.6  321.84  5401.8  319.51  5407.5  322.21
  5428.2  321.89  5515.9  320.61  5610.2  324.86  5705.3  329.95  5778.3  336.21
  5792.6  333.46  5799.2  335.92  5806.8  333.84  6069.2  340.98  6331.5  355.49
#Mann=8,-1,0
  4276.1    0.05       0  5031.8    0.16       0  5339.2    0.03       0
  5345.2    0.16       0  5371.6    0.12       0  5428.2    0.16       0
  5610.2    0.05       0  5705.3    0.16       0
Bank Sta=5339.2,5345.2
Exp/Cntr=0.3,0.1

Type RM Length L Ch R = 1,1906,462,462,462
BEGIN DESCRIPTION:
Mapping XS b18095b0
END DESCRIPTION:
XS GIS Cut Line= 6
      3636686.02     10552018.25      3636565.54     10552812.73
      3636594.85     10552995.06      3636721.83     10553193.67
      3636884.63     10553362.98      3637414.98     10553769.70
#Sta/Elev= 30
  4271.1  365.45  4348.1  360.46  4445.0  351.52  4485.6  350.65  4612.9  340.93
  4750.4  333.56  4829.4  324.40  4890.0  320.48  4930.5  321.30  4951.6  318.00
  5018.5  316.26  5021.3  315.76  5024.5  316.26  5035.5  316.47  5173.4  318.52
  5398.1  317.96  5529.7  319.93  5605.6  323.55  5667.9  326.22  5689.0  328.64
  5724.5  328.80  5752.6  332.36  5795.3  334.95  5816.9  337.09  5881.3  337.48
  5902.1  338.96  6088.9  341.13  6238.5  347.41  6315.9  353.38  6398.3  356.57
#Mann=8,-1,0
  4271.1    0.05       0  5018.5    0.03       0  5024.5    0.05       0
  5035.5    0.16       0  5398.1    0.12       0  5529.7    0.16       0
  5605.6    0.05       0  5795.3    0.16       0
Bank Sta=5018.5,5024.5
Exp/Cntr=0.3,0.1

Type RM Length L Ch R = 1,1444,0,0,0
BEGIN DESCRIPTION:
UNT 084 IN BUCR 1.0
END DESCRIPTION:
XS GIS Cut Line= 5
      3636353.52     10552062.92      3636088.75     10552753.07
      3636136.50     10552996.12      3636952.47     10553503.93
      3637445.97     10553798.30
#Sta/Elev= 30
  4430.1  358.14  4502.1  360.82  4569.2  357.19  4708.6  344.93  4769.9  337.61
  4788.0  333.37  4802.0  333.08  4823.5  328.51  4887.7  324.42  4919.9  319.75
  5002.5  314.47  5005.3  313.97  5008.5  314.47  5012.1  315.89  5080.5  318.03
  5298.6  315.95  5740.8  320.60  5878.0  319.35  6045.3  320.78  6127.7  324.38
  6212.9  330.32  6280.2  332.38  6292.3  336.66  6315.8  339.50  6355.1  340.48
  6518.7  339.14  6635.5  341.31  6700.8  343.81  6709.5  345.63  6952.7  360.52
#Mann=6,-1,0
  4430.1    0.05       0  5002.5    0.03       0  5008.5    0.05       0
  5878.0    0.12       0  6127.7    0.05       0  6355.1    0.16       0
Bank Sta=5002.5,5008.5
Exp/Cntr=0.3,0.1

Chan Stop Cuts=-1