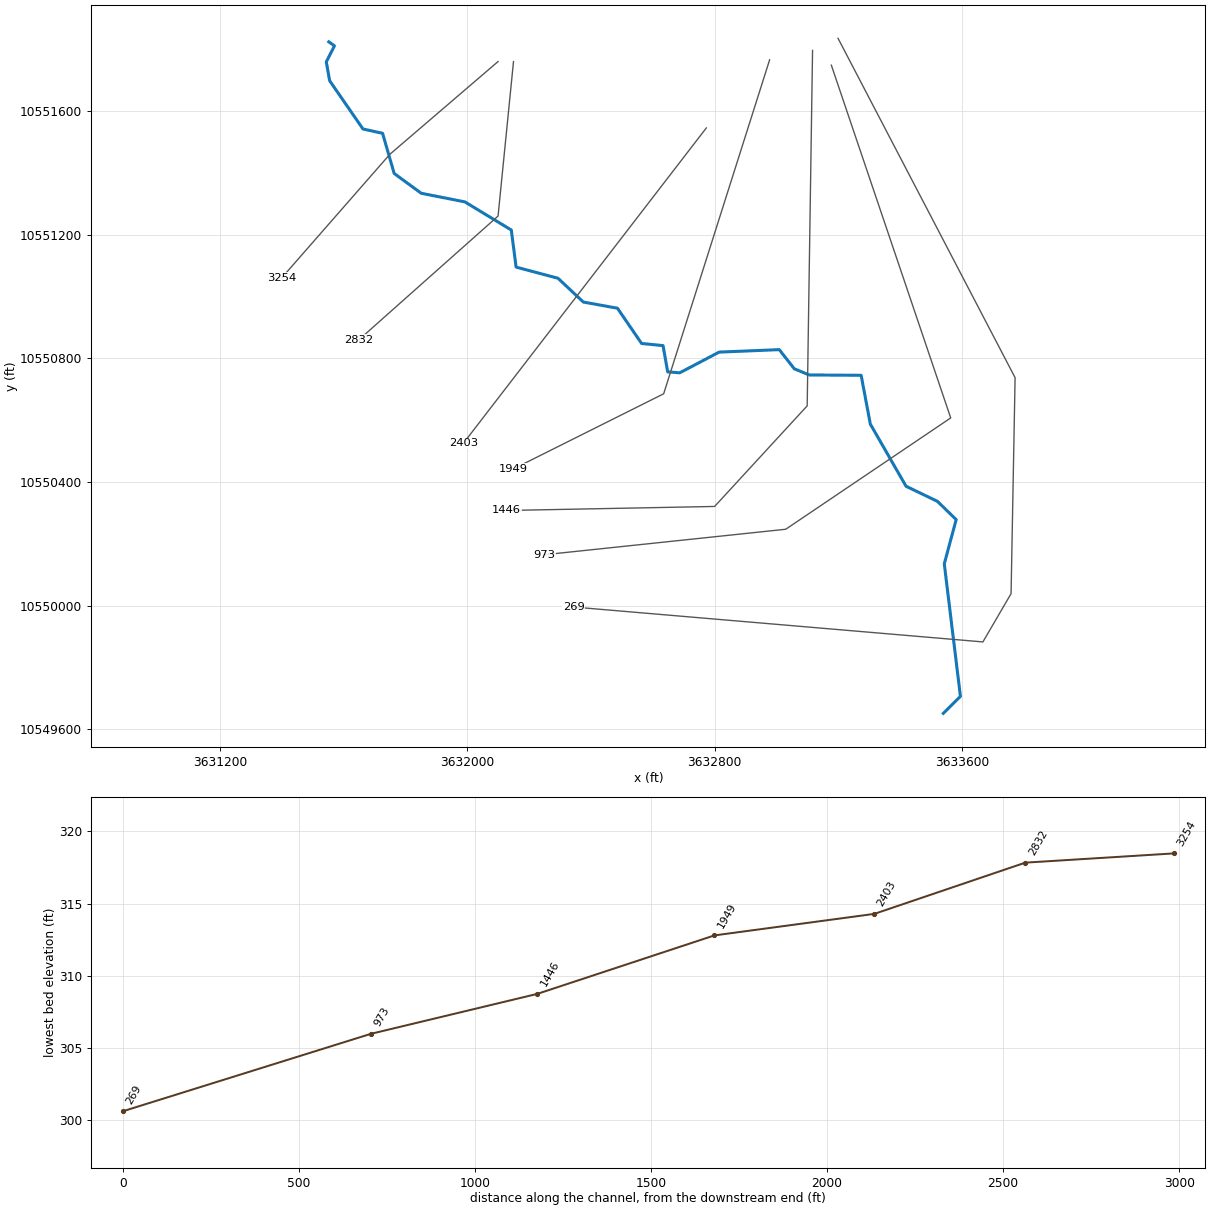
--- UNT 087 IN BUCR.prj (project) ---

Proj Title=UNT 087 IN BUCR Base Level Engineering
Current Plan=p01
Default Exp/Contr=0.3,0.1
English Units
Geom File=g01
Flow File=f01
Plan File=p01
Y Axis Title=Elevation
X Axis Title(PF)=Main Channel Distance
X Axis Title(XS)=Station
BEGIN DESCRIPTION:
UNT 087 IN BUCR
END DESCRIPTION:
DSS Export Rating Curves= 0
DSS Export Rating Curve Sorted= 0
DSS Export Volume Flow Curves= 0
DXF OffsetX= 0
DXF OffsetY= 0
DXF ScaleX= 1
DXF ScaleY= 10

--- UNT 087 IN BUCR.p01 (plan) ---

Plan Title=Multiple Run
Short Identifier=Multiple
Geom File=g01
Flow File=f01
Subcritical Flow
K Sum by GR= 0
Std Step Tol= 0.01
Critical Tol= 0.01
Num of Std Step Trials= 20
Max Error Tol= 0.3
Flow Tol Ratio= 0.001
Split Flow NTrial= 30
Split Flow Tol= 0.02
Split Flow Ratio= 0.02
Log Output Level= 0
Friction Slope Method= 1
Unsteady Friction Slope Method= 2
Unsteady Bridges Friction Slope Method= 1
Parabolic Critical Depth
Global Vel Dist=  1 , 1 , 1
Global Log Level= 0
CheckData=True
Encroach Param= -1, 0, 0, 0
BEGIN DESCRIPTION:
Multiple Run
END DESCRIPTION:

--- UNT 087 IN BUCR.f01 (steady flow) ---

Flow Title=Multiple
Number of Profiles=7
Profile Names=10-year,25-year,50-year,1pct_min,100-year,1pct_plu,500-year
River Rch & RM= UNT 087 IN BUCR,Reach-1,3254
    1049    1435    1752    1561    2111    2856    3054
Boundary for River Rch & Prof#=UNT 087 IN BUCR,Reach-1,1
Up Type=0
Dn Type=3
Dn Slope=0.005
Boundary for River Rch & Prof#=UNT 087 IN BUCR,Reach-1,2
Up Type=0
Dn Type=3
Dn Slope=0.005
Boundary for River Rch & Prof#=UNT 087 IN BUCR,Reach-1,3
Up Type=0
Dn Type=3
Dn Slope=0.005
Boundary for River Rch & Prof#=UNT 087 IN BUCR,Reach-1,4
Up Type=0
Dn Type=3
Dn Slope=0.005
Boundary for River Rch & Prof#=UNT 087 IN BUCR,Reach-1,5
Up Type=0
Dn Type=3
Dn Slope=0.005
Boundary for River Rch & Prof#=UNT 087 IN BUCR,Reach-1,6
Up Type=0
Dn Type=3
Dn Slope=0.005
Boundary for River Rch & Prof#=UNT 087 IN BUCR,Reach-1,7
Up Type=0
Dn Type=3
Dn Slope=0.005

--- UNT 087 IN BUCR.g01 (geometry) ---

Geom Title=Existing Conditions
Program Version=4.10

River Reach=UNT 087 IN BUCR ,Reach-1
Reach XY= 30
        3631552.       10551824.      3631570.25       10551811.
      3631543.75       10551759.      3631554.75       10551698.
       3631662.5       10551542.        3631726.       10551528.
       3631763.5       10551398.        3631851.       10551334.
       3631992.5       10551306.       3632142.5       10551215.
        3632158.       10551095.       3632293.5       10551059.
       3632375.5       10550982.        3632486.       10550962.
        3632564.       10550848.       3632633.5       10550841.
       3632648.5       10550756.       3632687.5       10550753.
        3632815.       10550820.       3633009.5       10550828.
      3633058.25       10550766.      3633106.75       10550746.
       3633274.5       10550745.      3633304.25       10550587.
      3633419.75       10550386.       3633521.5       10550337.
        3633582.       10550278.       3633543.5       10550135.
      3633595.75       10549706.      3633540.25       10549651.

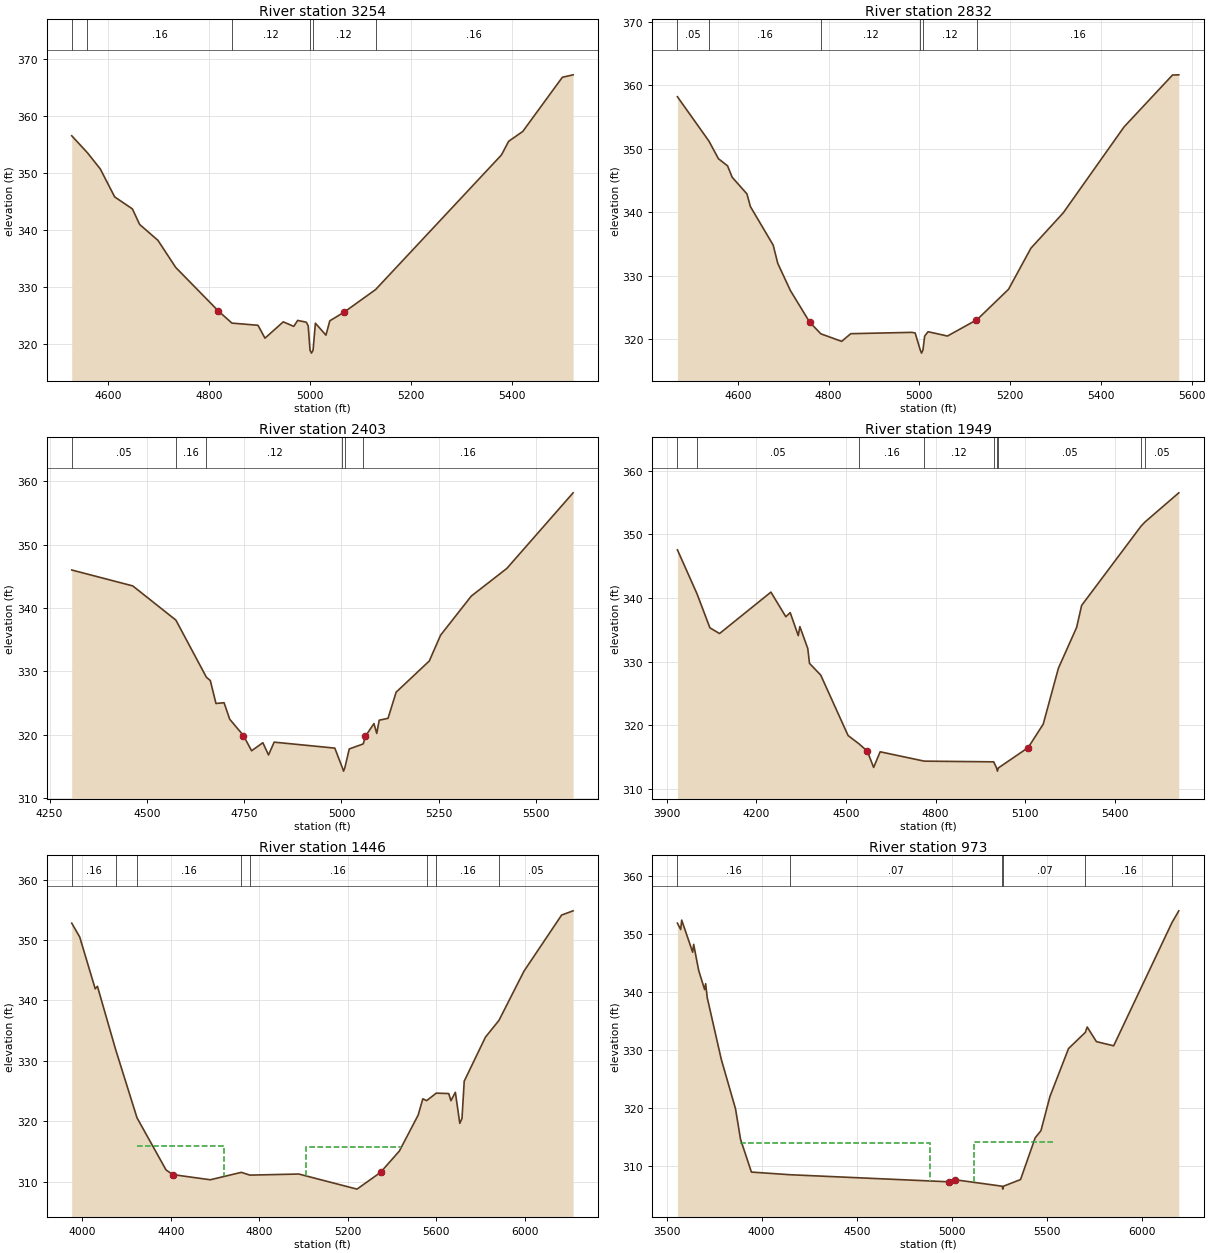
Type RM Length L Ch R = 1 ,3254    ,422,422,422
BEGIN DESCRIPTION:
UNT 087 IN BUCR 4.0
END DESCRIPTION:
XS GIS Cut Line= 3
      3632099.58     10551760.17      3631749.61     10551460.19
      3631399.64     10551060.23
#Sta/Elev= 30
    4528  356.56  4559.2  353.57  4584.5  350.75    4613  345.85  4648.1  343.74
  4662.4  341.02  4698.6  338.24  4733.8  333.49  4818.3  325.85  4845.1  323.73
  4896.7  323.35  4910.5  321.09  4946.7  323.95  4967.5  323.16  4975.2   324.2
  4992.3  323.89  4996.1  323.25  4999.7  318.97  5002.5  318.47  5005.7  318.97
  5010.3  323.71  5031.2  321.62  5038.8  324.13  5067.2  325.65  5129.5  329.61
  5378.6   353.2  5392.8  355.59  5420.8  357.32  5499.1  366.81  5520.4  367.24
#Mann= 6 ,-1 , 0
    4528     .05       0  4559.2     .16       0  4845.1     .12       0
  4999.7     .07       0  5005.7     .12       0  5129.5     .16       0
Bank Sta=4818.3,5067.2
XS Rating Curve= 0 ,0
Exp/Cntr=0.3,0.1

Type RM Length L Ch R = 1 ,2832    ,429,429,429
BEGIN DESCRIPTION:
UNT 087 IN BUCR 3.0
END DESCRIPTION:
XS GIS Cut Line= 3
      3632149.61     10551760.17      3632099.61     10551260.19
      3631649.57     10550860.16
#Sta/Elev= 30
  4467.1  358.19  4536.7  351.19  4557.5  348.43  4577.6  347.31  4587.7  345.52
  4620.3  342.89  4627.9   340.9  4678.1  334.83  4688.2  331.96  4715.8  327.71
  4758.5   322.7  4783.1  320.87  4828.9  319.68    4849  320.89  4983.4   321.1
  4990.9     321  5002.1  318.33  5004.9  317.83  5008.1  318.33  5011.8  320.51
  5019.3   321.2    5062  320.52  5125.5  323.03  5126.6  323.05  5196.6  327.88
  5245.9  334.35    5317   339.9  5451.2  353.45  5557.9  361.61  5571.7  361.64
#Mann= 6 ,-1 , 0
  4467.1     .05       0  4536.7     .16       0  4783.1     .12       0
  5002.1     .07       0  5008.1     .12       0  5126.6     .16       0
Bank Sta=4758.5,5125.5
XS Rating Curve= 0 ,0
Exp/Cntr=0.3,0.1

Type RM Length L Ch R = 1 ,2403    ,454,454,454
BEGIN DESCRIPTION:
UNT 087 IN BUCR 2.0
END DESCRIPTION:
XS GIS Cut Line= 2
      3632773.47     10551545.27      3631987.29      10550524.8
#Sta/Elev= 30
  4306.9     346  4463.7  343.49  4574.5   338.1  4652.9  329.09    4663  328.56
  4677.5  324.95  4698.3  325.07  4712.8  322.47  4748.1  319.89    4769  317.49
    4798  318.76  4812.5  316.83    4827  318.85  4982.8  317.91  5002.5  314.78
  5005.2  314.28  5008.5  314.78    5020  317.78  5055.8  318.57  5061.6  319.79
  5083.4  321.78  5090.6  320.23  5096.9  322.31  5119.6  322.61  5140.4  326.73
  5225.6  331.65  5254.6  335.72  5333.4  341.88  5424.9  346.25  5595.1  358.17
#Mann= 6 ,-1 , 0
  4306.9     .05       0  4574.5     .16       0  4652.9     .12       0
  5002.5     .07       0  5008.5     .12       0  5055.8     .16       0
Bank Sta=4748.1,5061.6
XS Rating Curve= 0 ,0
Exp/Cntr=0.3,0.1

Type RM Length L Ch R = 1 ,1949    ,503,503,503
BEGIN DESCRIPTION:
Mapping XS 8cf90f17
END DESCRIPTION:
XS GIS Cut Line= 3
      3632978.38     10551765.87       3632635.5     10550685.15
      3632149.39     10550442.09
#Sta/Elev= 30
  3936.1  347.58  4001.7  340.66  4044.8  335.32    4077  334.42  4248.9  340.93
  4298.8  337.06  4313.4  337.71  4340.4  334.09  4345.7  335.51  4372.2  332.07
    4378  329.73  4415.5  327.89    4507  318.39  4544.1  317.06  4571.5  315.92
  4592.5  313.37  4614.3  315.83  4761.8  314.36  4994.1  314.25  5003.8  313.29
  5006.6  312.79  5009.8  313.29  5109.5  316.49  5159.8  320.17  5210.7  328.97
  5271.6  335.38  5288.4  338.84  5487.6  351.33  5500.5  351.96  5613.4  356.54
#Mann= 9 ,-1 , 0
  3936.1     .16       0  4001.7     .05       0  4544.1     .16       0
  4761.8     .12       0  4994.1     .05       0  5003.8     .03       0
  5009.8     .05       0  5487.6     .16       0  5500.5     .05       0
Bank Sta=4571.5,5109.5
XS Rating Curve= 0 ,0
Exp/Cntr=0.3,0.1

Type RM Length L Ch R = 1 ,1446    ,473,473,473
BEGIN DESCRIPTION:
Mapping XS 72c112c8
END DESCRIPTION:
XS GIS Cut Line= 4
      3633117.28      10551796.3      3633099.91     10550646.09
      3632800.43     10550320.57      3632127.73     10550307.55
#Sta/Elev= 30
  3952.4   352.8  3988.5   350.5  4058.5  341.92  4068.5  342.34  4150.6  331.89
  4247.3  320.56  4378.6  311.92  4408.6  311.15  4578.6  310.29  4718.6  311.52
  4757.8  311.06  4978.6  311.24  5241.4  308.74  5347.7  311.51  5432.8  315.05
  5517.9  321.01  5538.8   323.7  5555.9   323.4  5599.8  324.64  5655.9  324.57
  5665.9  323.39  5685.9  324.78  5705.9  319.63  5715.9  320.47  5725.9  326.62
  5821.9  333.92  5882.7  336.68    5996  344.85    6166  354.14  6217.9  354.84
#Mann= 8 ,-1 , 0
  3952.4     .16       0  4150.6     .05       0  4247.3     .16       0
  4718.6     .05       0  4757.8     .16       0  5555.9     .05       0
  5599.8     .16       0  5882.7     .05       0
#XS Ineff= 2 ,-1
 4246.59 4638.64315.8182 5010.23 5444.89315.6662
Permanent Ineff=
       F       F
Bank Sta=4408.6,5347.7
XS Rating Curve= 0 ,0
Exp/Cntr=0.3,0.1

Type RM Length L Ch R = 1 ,973     ,704,704,704
BEGIN DESCRIPTION:
Mapping XS 90ba7b5c
END DESCRIPTION:
XS GIS Cut Line= 4
      3633178.05     10551748.48      3633564.32     10550607.02
      3633030.47     10550246.78      3632249.19     10550164.31
#Sta/Elev= 30
  3557.4  351.82  3574.6  350.73  3579.9  352.35  3637.5  346.82  3642.8  348.17
  3668.9   343.7  3700.4  340.37  3705.7  341.39    3714  338.99  3787.9  328.35
  3862.8  319.81    3889  314.58  3946.2  308.91  4150.1  308.45  4985.8  307.23
  5015.7  307.59  5264.5  306.47  5267.3  305.97  5270.5  306.47  5360.5  307.62
  5437.5  314.82  5467.7  316.04  5514.9  321.93  5612.8  330.21  5700.8  332.99
  5710.7  333.92  5759.3   331.4  5849.8  330.68  6155.8  351.89  6192.1  353.95
#Mann= 6 ,-1 , 0
  3557.4     .16       0  4150.1     .07       0  5264.5     .03       0
  5270.5     .07       0  5700.8     .16       0  6155.8     .05       0
#XS Ineff= 2 ,-1
 3885.23 4884.09313.8441 5117.61 5536.93314.0722
Permanent Ineff=
       F       F
Bank Sta=4985.8,5015.7
XS Rating Curve= 0 ,0
Exp/Cntr=0.3,0.1

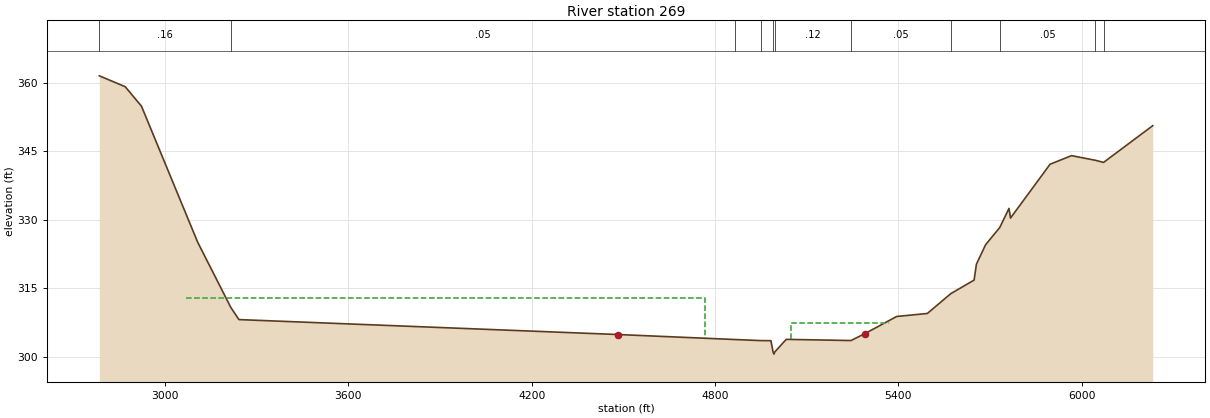
Type RM Length L Ch R = 1 ,269     ,0,0,0
BEGIN DESCRIPTION:
UNT 087 IN BUCR 1.0
END DESCRIPTION:
XS GIS Cut Line= 5
      3633199.75     10551835.31      3633772.66     10550737.23
      3633759.64     10550038.45      3633668.49      10549882.2
      3632344.73     10549995.04
#Sta/Elev= 30
  2785.3  361.46    2870  359.08  2923.2  354.82  3106.9  325.11  3215.5  310.82
  3242.2  308.16    4481   304.9    4866   303.8  4949.4  303.57  4982.8  303.55
  4989.8  301.11  4992.6  300.61  4995.8  301.11    5033  303.84  5244.8  303.58
  5290.5   305.1  5394.3  308.84  5494.7   309.5  5571.3  313.83  5647.7   316.8
  5655.2  320.27  5685.3  324.54  5731.5  328.28  5761.8  332.47  5766.8  330.36
  5896.1  342.12  5966.4  344.01  6044.5  342.99  6071.3  342.53  6232.2  350.56
#Mann= 11 ,-1 , 0
  2785.3     .16       0  3215.5     .05       0    4866     .07       0
  4949.4     .12       0  4989.8     .07       0  4995.8     .12       0
  5244.8     .05       0  5571.3     .16       0  5731.5     .05       0
  6044.5     .16       0  6071.3     .05       0
#XS Ineff= 2 ,-1
 3068.18 4768.18  312.86 5050.12 5368.71  307.32
Permanent Ineff=
       F       F
Bank Sta=4481,5290.5
XS Rating Curve= 0 ,0
Exp/Cntr=0.3,0.1

Chan Stop Cuts=-1
Use User Specified Reach Order=0
Composite Channel Slope=5