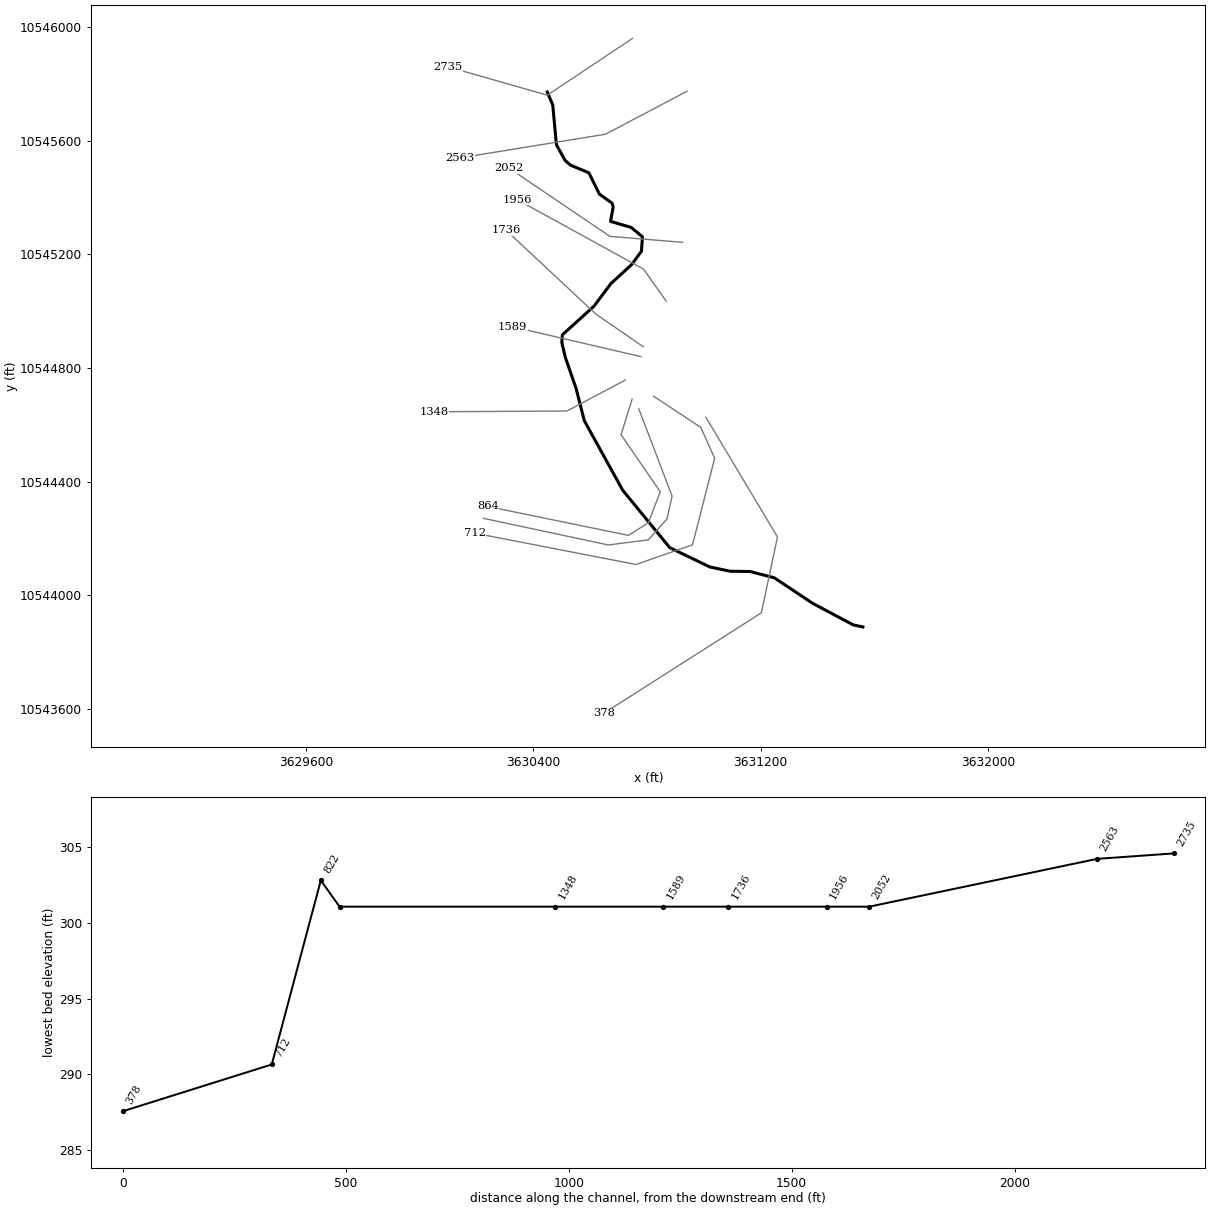
--- UNT 090 IN BUCR.prj (project) ---

Proj Title=UNT 090 IN BUCR Base Level Engineering
Current Plan=p01
Default Exp/Contr=0.3,0.1
English Units
Geom File=g01
Flow File=f01
Plan File=p01
Y Axis Title=Elevation
X Axis Title(PF)=Main Channel Distance
X Axis Title(XS)=Station
BEGIN DESCRIPTION:
UNT 090 IN BUCR
END DESCRIPTION:
DSS Export Rating Curves= 0
DSS Export Rating Curve Sorted= 0
DSS Export Volume Flow Curves= 0
DXF OffsetX= 0
DXF OffsetY= 0
DXF ScaleX= 1
DXF ScaleY= 10

--- UNT 090 IN BUCR.p01 (plan) ---

Plan Title=Multiple Run
Short Identifier=Multiple
Geom File=g01
Flow File=f01
Subcritical Flow
K Sum by GR= 0
Std Step Tol= 0.01
Critical Tol= 0.01
Num of Std Step Trials= 20
Max Error Tol= 0.3
Flow Tol Ratio= 0.001
Split Flow NTrial= 30
Split Flow Tol= 0.02
Split Flow Ratio= 0.02
Log Output Level= 0
Friction Slope Method= 1
Unsteady Friction Slope Method= 2
Unsteady Bridges Friction Slope Method= 1
Parabolic Critical Depth
Global Vel Dist=  1 , 1 , 1
Global Log Level= 0
CheckData=True
Encroach Param= -1, 0, 0, 0
BEGIN DESCRIPTION:
Multiple Run
END DESCRIPTION:

--- UNT 090 IN BUCR.f01 (steady flow) ---

Flow Title=Multiple
Program Version=4.10
Number of Profiles= 7
Profile Names=10-year,25-year,50-year,1pct_min,100-year,1pct_plu,500-year
River Rch & RM=UNT 090 IN BUCR,Reach-1         ,2735
     944    1298    1591    1425    1928    2607    2818
Boundary for River Rch & Prof#=UNT 090 IN BUCR,Reach-1         , 1
Up Type= 0
Dn Type= 3
Dn Slope=0.008
Boundary for River Rch & Prof#=UNT 090 IN BUCR,Reach-1         , 2
Up Type= 0
Dn Type= 3
Dn Slope=0.008
Boundary for River Rch & Prof#=UNT 090 IN BUCR,Reach-1         , 3
Up Type= 0
Dn Type= 3
Dn Slope=0.008
Boundary for River Rch & Prof#=UNT 090 IN BUCR,Reach-1         , 4
Up Type= 0
Dn Type= 3
Dn Slope=0.008
Boundary for River Rch & Prof#=UNT 090 IN BUCR,Reach-1         , 5
Up Type= 0
Dn Type= 3
Dn Slope=0.008
Boundary for River Rch & Prof#=UNT 090 IN BUCR,Reach-1         , 6
Up Type= 0
Dn Type= 3
Dn Slope=0.008
Boundary for River Rch & Prof#=UNT 090 IN BUCR,Reach-1         , 7
Up Type= 0
Dn Type= 3
Dn Slope=0.008
DSS Import GetInterval= 0
DSS Import GetPeak= 0
DSS Import FillOption= 0

--- UNT 090 IN BUCR.g01 (geometry) ---

Geom Title=Existing Conditions
Program Version=4.10

River Reach=UNT 090 IN BUCR ,Reach-1
Reach XY= 30
      3630449.61     10545771.02      3630468.75       10545726.
      3630481.75       10545586.        3630512.       10545531.
      3630531.25       10545514.        3630596.       10545487.
        3630633.       10545412.      3630677.75       10545380.
       3630681.5       10545367.      3630672.25       10545316.
       3630744.5       10545295.       3630784.5       10545262.
        3630781.       10545211.      3630746.25       10545164.
      3630673.25       10545097.      3630614.25       10545018.
      3630502.75       10544917.      3630500.75       10544890.
        3630513.       10544838.        3630551.       10544728.
      3630579.75       10544615.        3630715.       10544370.
       3630880.5       10544168.      3631021.75       10544100.
      3631093.25       10544085.       3631163.5       10544084.
      3631248.25       10544062.       3631383.5       10543972.
      3631526.75       10543896.      3631560.25       10543889.

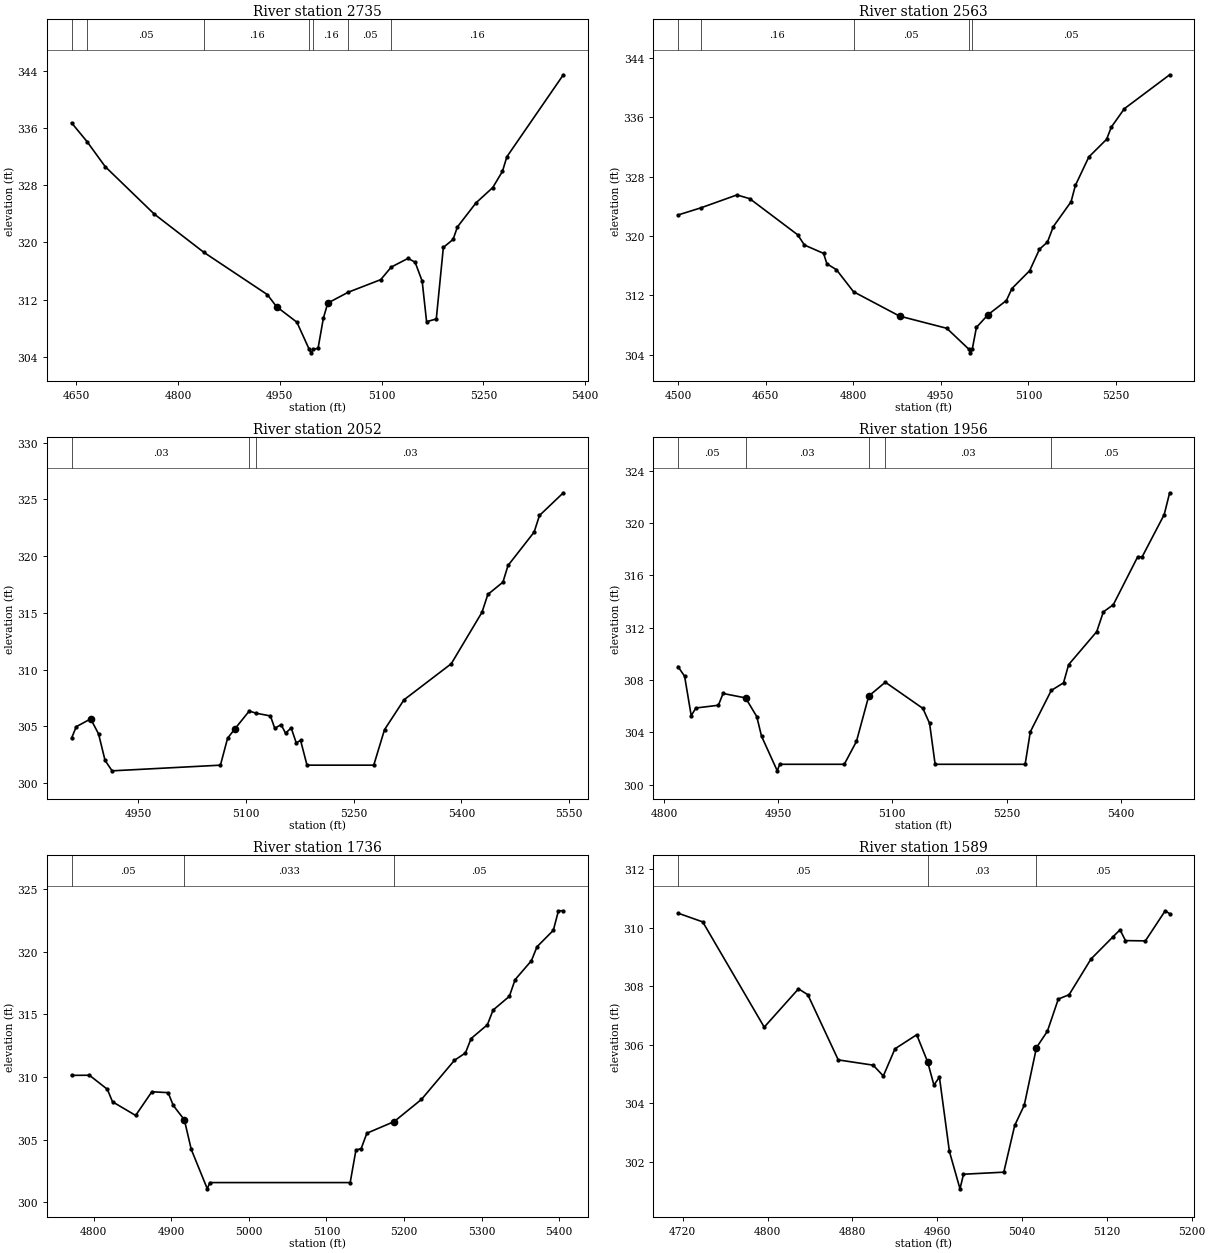
Type RM Length L Ch R = 1 ,2735    ,172,172,172
BEGIN DESCRIPTION:
UNT 090 IN BUCR 2.0
END DESCRIPTION:
XS GIS Cut Line= 3
      3630749.64     10545960.21      3630449.61     10545760.19
      3630099.61     10545860.19
#Sta/Elev= 30
  4643.3  336.71    4666   334.1  4692.9  330.59    4765  323.98  4838.3  318.62
  4931.8  312.72  4945.3  311.04  4975.3  308.87  4993.4  305.09  4996.1  304.59
  4999.4  305.09  5006.5  305.22  5014.3  309.42  5020.8  311.54  5051.1  313.06
  5098.8  314.81  5114.4  316.57  5139.1  317.78  5149.5  317.25  5159.9   314.6
  5166.4  308.94  5180.7  309.32  5191.1  319.31  5205.4  320.42  5211.9  322.18
  5239.2  325.53  5263.9  327.67  5278.2  329.94  5284.7  331.97  5367.9  343.42
#Mann= 7 ,-1 , 0
  4643.3     .16       0    4666     .05       0  4838.3     .16       0
  4993.4     .07       0  4999.4     .16       0  5051.1     .05       0
  5114.4     .16       0
Bank Sta=4945.3,5020.8
XS Rating Curve= 0 ,0
Exp/Cntr=0.3,0.1

Type RM Length L Ch R = 1 ,2563    ,511,511,511
BEGIN DESCRIPTION:
Mapping XS 9c094533
END DESCRIPTION:
XS GIS Cut Line= 3
      3630940.98     10545773.82      3630654.41     10545622.74
      3630142.97     10545539.67
#Sta/Elev= 30
  4499.7  322.83  4539.1   323.8  4600.7  325.54  4622.7  325.04  4704.7  320.17
  4716.4  318.78  4749.2  317.65  4754.8  316.25  4771.2  315.45  4800.4  312.48
  4879.2  309.19  4960.2  307.54  4997.8  304.73  5000.5  304.23  5003.8  304.73
  5010.9  307.67  5031.1   309.4  5062.2  311.29  5071.7  312.91  5102.1  315.32
  5118.8  318.21  5132.5  319.18  5142.6  321.27    5173  324.63  5180.3  326.82
  5203.4  330.67  5233.8  333.05  5241.9   334.7  5264.2  337.18  5341.8  341.76
#Mann= 5 ,-1 , 0
  4499.7     .05       0  4539.1     .16       0  4800.4     .05       0
  4997.8     .03       0  5003.8     .05       0
Bank Sta=4879.2,5031.1
XS Rating Curve= 0 ,0
Exp/Cntr=0.3,0.1

Type RM Length L Ch R = 1 ,2052    ,96,96,96
BEGIN DESCRIPTION:
Mapping XS 5293c341
END DESCRIPTION:
XS GIS Cut Line= 3
      3630926.08     10545242.45      3630670.03     10545263.37
      3630315.86     10545502.95
#Sta/Elev= 30
  4857.4  303.95  4863.9  304.96    4884  305.65    4895  304.32    4904  301.99
  4913.8  301.07  5064.6  301.57  5074.6  303.95  5084.6  304.76  5104.7  306.34
  5114.3  306.15  5134.2  305.91  5140.2  304.82  5149.1  305.14  5155.2  304.39
  5163.1  304.85  5170.1  303.54  5176.2  303.75  5185.1  301.57    5278  301.57
    5293   304.7  5320.1  307.33  5385.9  310.51  5428.7  315.05  5436.8  316.62
  5457.8   317.7  5464.9  319.17  5501.2  322.11  5508.7  323.58  5541.9  325.58
#Mann= 3 ,-1 , 0
  4857.4     .03       0  5104.7     .05       0  5114.3     .03       0
Bank Sta=4884,5084.6
XS Rating Curve= 0 ,0
Exp/Cntr=0.3,0.1

Type RM Length L Ch R = 1 ,1956    ,220,220,220
BEGIN DESCRIPTION:
Mapping XS f3a5146b
END DESCRIPTION:
XS GIS Cut Line= 3
       3630867.9      10545035.5      3630788.58     10545148.02
       3630343.3     10545392.81
#Sta/Elev= 30
  4818.4  309.04  4827.2   308.3  4835.9  305.28    4842  305.87  4871.6  306.08
  4877.7  306.98  4907.3  306.64    4922  305.21  4928.2  303.72  4948.9  301.07
  4952.1  301.57  5036.9  301.57  5052.9  303.32    5069  306.78  5090.8  307.84
  5140.1  305.84  5148.9   304.7  5156.2  301.57  5274.4  301.57  5281.2  304.05
  5308.7  307.21  5324.8  307.79  5331.5  309.18  5368.4   311.7  5377.1  313.21
  5390.2  313.76  5422.3  317.43    5428  317.41    5457  320.64  5464.2  322.31
#Mann= 5 ,-1 , 0
  4818.4     .05       0  4907.3     .03       0    5069     .05       0
  5090.8     .03       0  5308.7     .05       0
Bank Sta=4907.3,5069
XS Rating Curve= 0 ,0
Exp/Cntr=0.3,0.1

Type RM Length L Ch R = 1 ,1736    ,147,147,147
BEGIN DESCRIPTION:
Mapping XS ea803448
END DESCRIPTION:
XS GIS Cut Line= 3
      3630787.61     10544874.92      3630620.55     10544989.93
      3630305.42     10545284.23
#Sta/Elev= 30
  4771.4  310.13  4794.4  310.14  4817.5  309.02  4824.2  308.02    4854  306.93
  4874.9  308.82  4895.9  308.75  4902.5  307.73  4916.8  306.58  4925.7  304.22
  4946.4  301.07  4949.6  301.57  5130.6  301.57    5138  304.16  5144.8  304.29
  5152.1  305.51  5187.3  306.44  5222.5  308.21    5265  311.33  5279.2  311.92
  5286.5  313.07  5307.5  314.17  5314.8  315.34  5335.8  316.44  5343.2  317.77
  5364.2  319.28  5371.5   320.4  5392.5  321.71  5399.1  323.27  5405.4  323.27
#Mann= 3 , 0 , 0
  4771.4     .05       0  4916.8    .033       0  5187.3     .05       0
Bank Sta=4916.8,5187.3
XS Rating Curve= 0 ,0
Exp/Cntr=0.3,0.1

Type RM Length L Ch R = 1 ,1589    ,241,241,241
BEGIN DESCRIPTION:
Mapping XS d7802bc5
END DESCRIPTION:
XS GIS Cut Line= 2
      3630778.93     10544840.22      3630327.32     10544945.42
#Sta/Elev= 30
  4715.5   310.5  4738.9   310.2  4796.9   306.6  4829.2  307.91    4838  307.71
  4866.7  305.48  4899.6   305.3  4909.2  304.93  4920.2  305.86  4940.7  306.34
    4951  305.41  4956.9  304.62  4962.1  304.89  4971.5  302.35  4981.5  301.07
  4984.8  301.57  5022.8  301.64  5033.1  303.24  5042.1  303.93  5053.6   305.9
  5063.9  306.46  5074.2  307.56  5084.4  307.71    5105  308.93  5125.5  309.68
  5132.4  309.93  5137.5  309.56  5156.3  309.55    5175  310.58  5179.2  310.48
#Mann= 3 , 0 , 0
  4715.5     .05       0    4951     .03       0  5053.6     .05       0
Bank Sta=4951,5053.6
XS Rating Curve= 0 ,0
Exp/Cntr=0.3,0.1

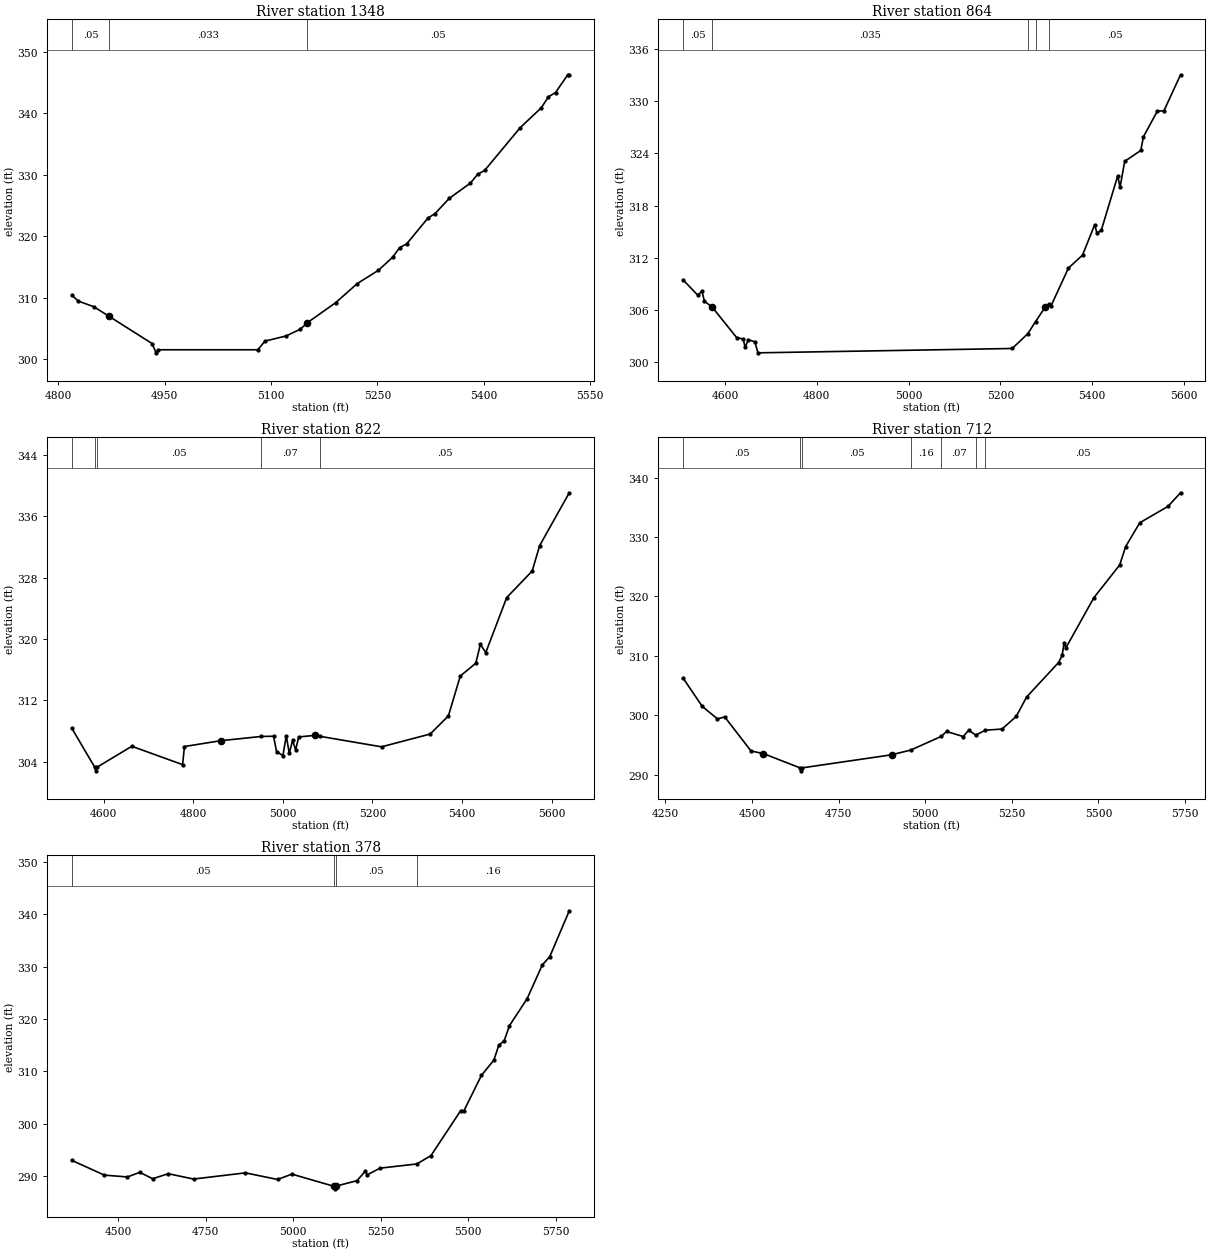
Type RM Length L Ch R = 1 ,1348    ,484,484,484
BEGIN DESCRIPTION:
Mapping XS 13fad0f6
END DESCRIPTION:
XS GIS Cut Line= 3
      3630724.76     10544758.18      3630518.99     10544648.78
      3630050.24     10544646.18
#Sta/Elev= 30
    4819  310.46  4827.9  309.49  4849.9  308.57  4871.9  306.98  4932.2  302.58
  4937.8  301.07  4941.1  301.57  5081.4  301.57  5091.4  302.97  5121.4  303.82
  5141.4  304.92  5151.4  305.98  5191.4  309.24  5221.4  312.31  5251.4  314.48
  5271.4  316.59  5281.4  318.17  5291.4  318.79  5321.4  322.98  5331.4  323.71
  5351.4  326.18  5381.4  328.68  5391.4  330.08  5401.4  330.73  5451.4  337.66
  5481.4  340.93  5491.4   342.7  5501.4  343.39  5518.6  346.28  5520.8  346.28
#Mann= 3 , 0 , 0
    4819     .05       0  4871.9    .033       0  5151.4     .05       0
Bank Sta=4871.9,5151.4
XS Rating Curve= 0 ,0
Exp/Cntr=0.3,0.1

Type RM Length L Ch R = 1 ,864     ,42,42,42
BEGIN DESCRIPTION:
Mapping XS c4d8a8fd
END DESCRIPTION:
XS GIS Cut Line= 6
      3630748.16     10544690.47      3630709.09     10544565.45
      3630847.11     10544364.93      3630805.45     10544255.55
      3630735.14     10544211.28      3630240.38     10544312.84
#Sta/Elev= 30
  4508.7  309.45  4540.4  307.71  4549.9  308.14  4555.1     307  4571.9  306.34
  4625.3  302.83  4639.7  302.66  4643.7  301.71  4650.9  302.57    4665  302.34
  4671.8  301.07  5225.8  301.57  5259.8  303.27  5276.8  304.67  5297.3  306.29
  5304.9  306.64    5310  306.42  5348.3  310.81    5379   312.3  5405.4  315.78
  5410.5  314.83  5419.8  315.14  5455.7  321.41  5460.8   320.1  5470.9  323.08
  5505.9  324.33  5511.7   325.9  5542.3  328.88  5556.2  328.87  5592.6  333.03
#Mann= 5 ,-1 , 0
  4508.7     .05       0  4571.9    .035       0  5259.8     .05       0
  5276.8     .07       0  5304.9     .05       0
Bank Sta=4571.9,5297.3
XS Rating Curve= 0 ,0
Exp/Cntr=0.3,0.1

Type RM Length L Ch R = 1 ,822     ,110,110,110
BEGIN DESCRIPTION:
Mapping XS b1d7072b
END DESCRIPTION:
XS GIS Cut Line= 6
      3630771.58     10544656.62      3630888.78      10544349.3
      3630870.55     10544268.58      3630805.45     10544195.66
      3630664.82     10544177.43      3630224.74     10544271.18
#Sta/Elev= 30
  4529.1  308.35  4579.9  303.31  4582.7  302.81  4585.9  303.31    4663  306.01
  4776.3  303.62  4780.4  305.98  4861.3  306.74  4951.7  307.29  4979.3  307.32
    4986  305.33  5000.2   304.8  5007.7  307.38  5014.4  305.09  5021.9  306.79
  5028.6  305.53  5035.5  307.23  5071.1  307.43  5081.9  307.32  5220.3  305.94
  5328.9  307.61  5369.6  309.98  5396.1  315.17  5430.7  316.84  5440.9   319.3
    5453  318.23  5499.7   325.4  5556.6  328.86  5573.3  332.18  5639.4  339.06
#Mann= 5 ,-1 , 0
  4529.1     .05       0  4579.9     .07       0  4585.9     .05       0
  4951.7     .07       0  5081.9     .05       0
Bank Sta=4861.3,5071.1
XS Rating Curve= 0 ,0
Exp/Cntr=0.3,0.1

Type RM Length L Ch R = 1 ,712     ,334,334,334
BEGIN DESCRIPTION:
Mapping XS 52de853e
END DESCRIPTION:
XS GIS Cut Line= 6
      3630823.65     10544700.89      3630989.91     10544590.95
      3631038.54     10544482.57      3630960.73     10544178.26
      3630762.02     10544108.78      3630194.06     10544218.98
#Sta/Elev= 30
  4301.2  306.25  4356.3   301.5  4400.2  299.39  4421.3  299.72  4497.3  293.98
  4532.6  293.55  4638.7  291.14  4641.5  290.64  4644.7  291.14  4902.8  293.34
  4958.9  294.15  5046.6  296.45  5061.5  297.27  5109.8  296.41  5125.4  297.49
  5145.8  296.66  5173.6  297.48  5221.9  297.68  5262.7  299.81  5292.6  303.07
  5384.9  308.88  5395.1  310.08  5401.1  312.23  5406.2  311.37  5486.8   319.8
  5561.3  325.31  5578.5   328.4  5619.2  332.41  5700.7  335.17  5736.9  337.46
#Mann= 7 ,-1 , 0
  4301.2     .05       0  4638.7     .07       0  4644.7     .05       0
  4958.9     .16       0  5046.6     .07       0  5145.8     .16       0
  5173.6     .05       0
Bank Sta=4532.6,4902.8
XS Rating Curve= 0 ,0
Exp/Cntr=0.3,0.1

Type RM Length L Ch R = 1 ,378     ,0,0,0
BEGIN DESCRIPTION:
UNT 090 IN BUCR 1.0
END DESCRIPTION:
XS GIS Cut Line= 4
      3631007.89     10544626.59      3631259.62     10544205.59
      3631203.02     10543938.71      3630647.94     10543584.86
#Sta/Elev= 30
  4367.5  292.98  4460.4  290.17  4526.4  289.82  4561.6   290.7  4598.5  289.48
  4642.9  290.44  4715.3  289.42  4863.5   290.6  4955.5  289.34  4996.4  290.36
  5115.6  288.05  5118.3  287.55  5121.6  288.05  5182.3  289.11  5205.9  290.89
  5211.9  290.24  5248.3   291.5  5353.2   292.3  5393.8  293.89  5478.8  302.49
  5487.8  302.44  5538.1  309.22  5573.7  312.15  5587.7  314.99  5602.9  315.79
  5618.1  318.71  5668.5  323.85  5712.1  330.33  5733.2  331.87  5789.1  340.65
#Mann= 4 ,-1 , 0
  4367.5     .05       0  5115.6     .03       0  5121.6     .05       0
  5353.2     .16       0
Bank Sta=5115.6,5121.6
XS Rating Curve= 0 ,0
Exp/Cntr=0.3,0.1

Chan Stop Cuts=-1
Use User Specified Reach Order=0
Composite Channel Slope=5