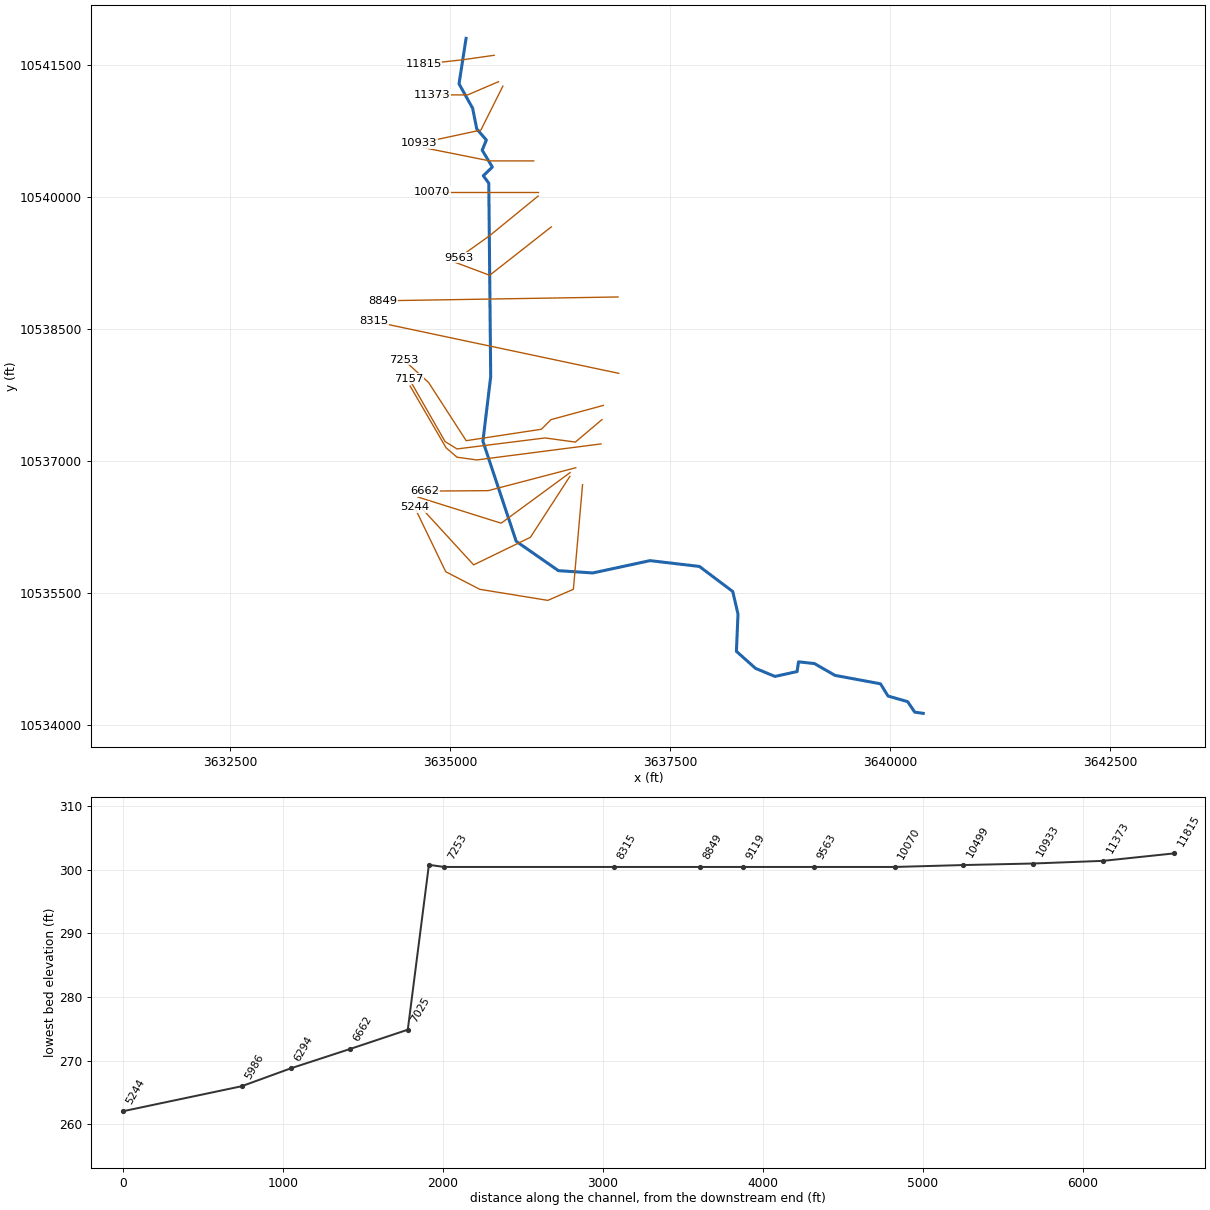
--- UNT 091 IN BUCR.prj (project) ---

Proj Title=UNT 091 IN BUCR Base Level Engineering
Current Plan=p01
Default Exp/Contr=0.3,0.1
English Units
Geom File=g01
Flow File=f01
Plan File=p01
BEGIN DESCRIPTION:
UNT 091 IN BUCR
END DESCRIPTION:

--- UNT 091 IN BUCR.p01 (plan) ---

Plan Title=Multiple Run
Short Identifier=Multiple
Geom File=g01
Flow File=f01
Subcritical Flow
K Sum by GR= 0
Std Step Tol= 0.01
Critical Tol= 0.01
Num of Std Step Trials= 20
Max Error Tol= 0.3
Flow Tol Ratio= 0.001
Split Flow NTrial= 30
Split Flow Tol= 0.02
Split Flow Ratio= 0.02
Log Output Level= 0
Friction Slope Method= 1
Unsteady Friction Slope Method= 2
Unsteady Bridges Friction Slope Method= 1
Parabolic Critical Depth
Global Vel Dist=  1 , 1 , 1
Global Log Level= 0
CheckData=True
Encroach Param= -1, 0, 0, 0
BEGIN DESCRIPTION:
Multiple Run
END DESCRIPTION:

--- UNT 091 IN BUCR.f01 (steady flow) ---

Flow Title=Multiple
Number of Profiles=7
Profile Names=10-year,25-year,50-year,1pct_min,100-year,1pct_plu,500-year
River Rch & RM= UNT 091 IN BUCR,Reach-1,11815
    1306    1835    2283    2075    2806    3794    4221
River Rch & RM= UNT 091 IN BUCR,Reach-1,10499
    1506    2120    2640    2399    3244    4387    4880
River Rch & RM= UNT 091 IN BUCR,Reach-1,7025
    2173    3116    3927    3605    4875    6593    7494
Boundary for River Rch & Prof#=UNT 091 IN BUCR,Reach-1,1
Up Type=0
Dn Type=3
Dn Slope=0.005
Boundary for River Rch & Prof#=UNT 091 IN BUCR,Reach-1,2
Up Type=0
Dn Type=3
Dn Slope=0.005
Boundary for River Rch & Prof#=UNT 091 IN BUCR,Reach-1,3
Up Type=0
Dn Type=3
Dn Slope=0.005
Boundary for River Rch & Prof#=UNT 091 IN BUCR,Reach-1,4
Up Type=0
Dn Type=3
Dn Slope=0.005
Boundary for River Rch & Prof#=UNT 091 IN BUCR,Reach-1,5
Up Type=0
Dn Type=3
Dn Slope=0.005
Boundary for River Rch & Prof#=UNT 091 IN BUCR,Reach-1,6
Up Type=0
Dn Type=3
Dn Slope=0.005
Boundary for River Rch & Prof#=UNT 091 IN BUCR,Reach-1,7
Up Type=0
Dn Type=3
Dn Slope=0.005

--- UNT 091 IN BUCR.g01 (geometry) ---

Geom Title=Existing Conditions

River Reach=UNT 091 IN BUCR,Reach-1
Reach XY= 30
      3635181.50     10541803.00      3635101.50     10541286.00
      3635255.75     10541009.00      3635303.25     10540772.00
      3635412.25     10540647.00      3635364.50     10540532.00
      3635479.75     10540340.00      3635377.25     10540241.00
      3635439.50     10540157.00      3635461.25     10537959.00
      3635372.75     10537224.00      3635750.50     10536087.00
      3636230.00     10535753.00      3636620.75     10535727.00
      3637270.75     10535867.00      3637831.50     10535801.00
      3638210.00     10535516.00      3638269.75     10535260.00
      3638251.75     10534836.00      3638469.75     10534642.00
      3638689.25     10534551.00      3638941.00     10534606.00
      3638957.00     10534717.00      3639138.25     10534697.00
      3639370.75     10534563.00      3639888.25     10534467.00
      3639973.50     10534328.00      3640196.75     10534264.00
      3640276.75     10534145.00      3640373.75     10534131.00

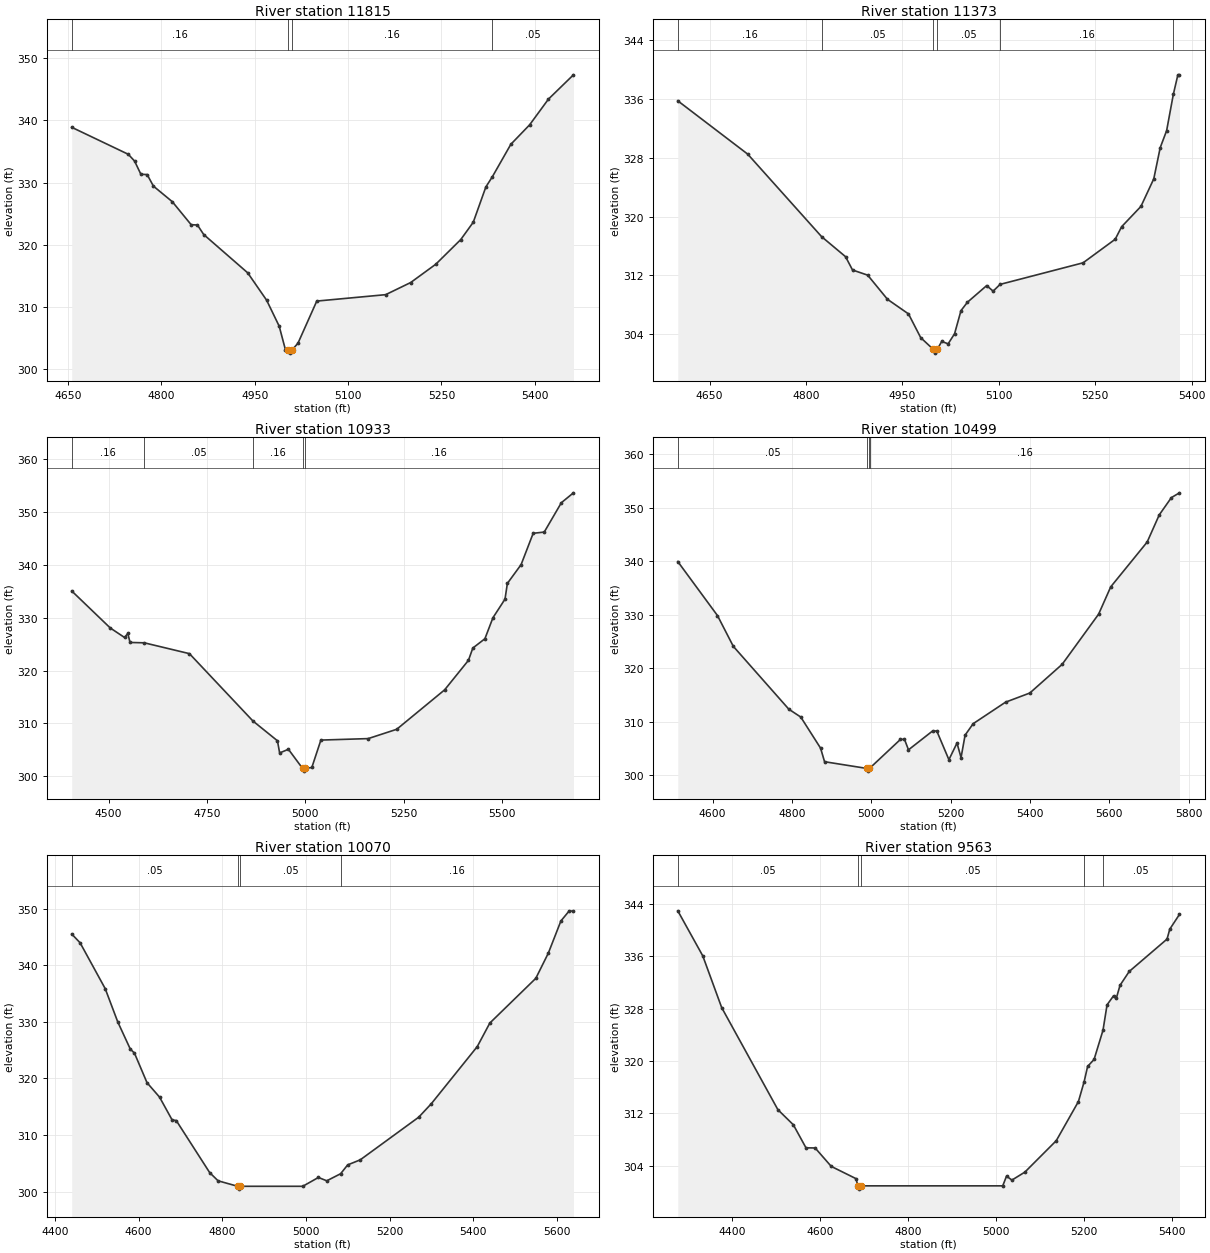
Type RM Length L Ch R = 1,11815,442,442,442
BEGIN DESCRIPTION:
UNT 091 IN BUCR 13.0
END DESCRIPTION:
XS GIS Cut Line= 3
      3635499.62     10541610.19      3635149.61     10541560.19
      3634699.64     10541510.19
#Sta/Elev= 30
  4655.9  338.89  4746.8  334.55  4756.9  333.46  4767.0  331.34  4777.1  331.29
  4787.2  329.43  4817.5  326.93  4847.8  323.23  4857.9  323.18  4868.0  321.65
  4938.7  315.49  4969.1  311.09  4989.3  306.91  4999.4  303.09  5003.9  303.08
  5006.7  302.58  5009.9  303.08  5019.5  304.18  5049.7  310.95  5160.4  311.98
  5200.6  313.93  5240.9  316.87  5281.1  320.84  5301.2  323.63  5321.4  329.29
  5332.1  330.98  5361.6  336.16  5391.8  339.29  5422.0  343.42  5462.2  347.33
#Mann=4,-1,0
  4655.9    0.16       0  5003.9    0.07       0  5009.9    0.16       0
  5332.1    0.05       0
Bank Sta=5003.9,5009.9
Exp/Cntr=0.3,0.1

Type RM Length L Ch R = 1,11373,440,440,440
BEGIN DESCRIPTION:
UNT 091 IN BUCR 12.0
END DESCRIPTION:
XS GIS Cut Line= 3
      3635549.57     10541310.17      3635199.61     10541160.19
      3634799.65     10541160.19
#Sta/Elev= 30
  4600.4  335.77  4709.2  328.51  4824.2  317.27  4861.5  314.54  4872.3  312.73
  4895.9  312.03  4926.7  308.74  4959.4  306.75  4978.4  303.52  4998.1  301.91
  5000.9  301.41  5004.1  301.91  5011.1  303.00  5021.1  302.68  5031.1  304.05
  5041.1  307.20  5051.1  308.34  5081.1  310.61  5091.1  309.85  5101.9  310.77
  5231.1  313.71  5281.1  316.92  5291.1  318.63  5321.1  321.39  5341.1  325.15
  5351.1  329.39  5361.1  331.71  5371.5  336.64  5378.6  339.31  5381.1  339.31
#Mann=6,-1,0
  4600.4    0.16       0  4824.2    0.05       0  4998.1   0.035       0
  5004.1    0.05       0  5101.9    0.16       0  5371.5    0.05       0
Bank Sta=4998.1,5004.1
Exp/Cntr=0.3,0.1

Type RM Length L Ch R = 1,10933,434,434,434
BEGIN DESCRIPTION:
UNT 091 IN BUCR 11.0
END DESCRIPTION:
XS GIS Cut Line= 3
      3635599.60     10541260.17      3635349.61     10540760.19
      3634649.60     10540610.19
#Sta/Elev= 30
  4406.5  335.05  4504.3  328.06  4540.6  326.26  4549.0  327.02  4554.6  325.32
  4590.9  325.25  4705.6  323.20  4866.9  310.47  4929.2  306.73  4934.8  304.43
  4957.1  305.12  4993.2  301.49  4995.9  300.99  4999.2  301.49  5016.6  301.68
  5039.6  306.86  5159.8  307.14  5232.3  308.90  5354.1  316.36  5414.6  321.94
  5425.7  324.26  5456.4  326.02  5476.8  329.99  5507.5  333.51  5513.5  336.48
  5548.4  340.04  5579.1  345.96  5607.2  346.19  5650.7  351.74  5681.4  353.61
#Mann=5,-1,0
  4406.5    0.16       0  4590.9    0.05       0  4866.9    0.16       0
  4993.2    0.07       0  4999.2    0.16       0
Bank Sta=4993.2,4999.2
Exp/Cntr=0.3,0.1

Type RM Length L Ch R = 1,10499,429,429,429
BEGIN DESCRIPTION:
UNT 091 IN BUCR 10.0
END DESCRIPTION:
XS GIS Cut Line= 3
      3635949.59     10540410.19      3635449.61     10540410.19
      3634699.65     10540560.18
#Sta/Elev= 30
  4512.4  339.92  4612.4  329.83  4652.4  324.07  4792.4  312.32  4822.4  310.86
  4872.4  305.04  4882.4  302.51  4989.4  301.25  4992.1  300.75  4995.4  301.25
  4996.2  301.29  5073.6  306.67  5083.8  306.71  5094.0  304.73  5155.2  308.28
  5165.4  308.24  5195.9  302.89  5216.3  306.00  5226.5  303.28  5236.7  307.48
  5257.1  309.62  5338.7  313.64  5399.9  315.35  5481.5  320.72  5573.3  330.09
  5603.9  335.20  5695.7  343.57  5726.2  348.65  5756.8  351.88  5777.2  352.77
#Mann=4,-1,0
  4512.4    0.05       0  4989.4    0.07       0  4995.4    0.05       0
  4996.2    0.16       0
Bank Sta=4989.4,4995.4
Exp/Cntr=0.3,0.1

Type RM Length L Ch R = 1,10070,507,507,507
BEGIN DESCRIPTION:
UNT 091 IN BUCR 9.0
END DESCRIPTION:
XS GIS Cut Line= 3
      3635999.60     10540060.19      3635449.61     10540060.19
      3634799.60     10540060.19
#Sta/Elev= 30
  4439.9  345.50  4459.9  343.95  4519.9  335.86  4549.9  329.99  4579.9  325.19
  4589.9  324.47  4619.9  319.25  4649.9  316.70  4679.9  312.68  4689.9  312.56
  4769.9  303.36  4789.9  301.92  4836.9  300.95  4839.6  300.45  4842.9  300.95
  4992.4  300.95  5029.9  302.51  5049.9  301.92  5083.0  303.17  5099.9  304.73
  5129.9  305.62  5269.9  313.16  5299.9  315.53  5409.9  325.63  5439.9  329.78
  5549.9  337.68  5579.9  342.14  5609.9  347.81  5629.9  349.60  5639.9  349.52
#Mann=4,-1,0
  4439.9    0.05       0  4836.9   0.033       0  4842.9    0.05       0
  5083.0    0.16       0
Bank Sta=4836.9,4842.9
Exp/Cntr=0.3,0.1

Type RM Length L Ch R = 1,9563,444,444,444
BEGIN DESCRIPTION:
UNT 091 IN BUCR 8.0
END DESCRIPTION:
XS GIS Cut Line= 3
      3635999.64     10540010.22      3635449.61     10539560.19
      3635099.60     10539310.18
#Sta/Elev= 30
  4276.9  342.90  4333.7  336.03  4376.7  328.14  4504.5  312.57  4539.7  310.26
  4568.4  306.75  4589.2  306.73  4625.8  303.92  4681.8  302.06  4686.7  300.95
  4689.4  300.45  4692.7  300.95  5015.8  300.95  5024.4  302.43  5036.7  301.83
  5066.2  303.05  5137.5  307.84  5187.9  313.81  5200.9  316.84  5208.8  319.17
  5223.5  320.23  5243.8  324.69  5253.0  328.56  5267.8  329.94  5273.9  329.53
  5282.5  331.54  5303.4  333.65  5389.4  338.59  5395.6  340.10  5417.7  342.36
#Mann=5,-1,0
  4276.9    0.05       0  4686.7   0.033       0  4692.7    0.05       0
  5200.9    0.16       0  5243.8    0.05       0
Bank Sta=4686.7,4692.7
Exp/Cntr=0.3,0.1

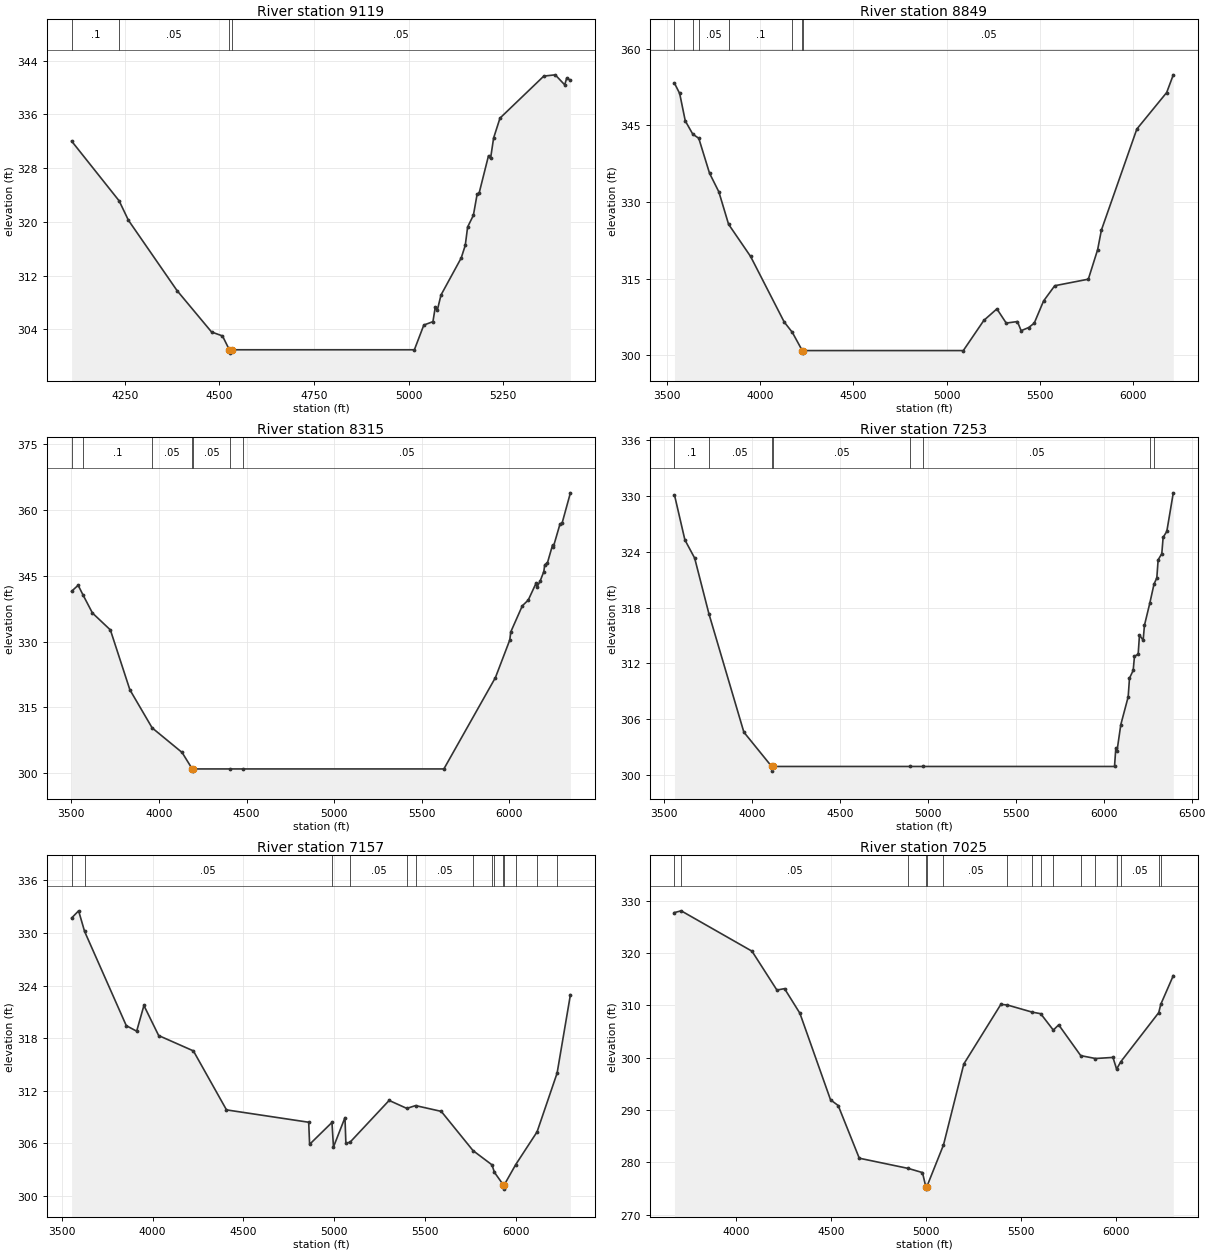
Type RM Length L Ch R = 1,9119,270,270,270
BEGIN DESCRIPTION:
UNT 091 IN BUCR 7.0
END DESCRIPTION:
XS GIS Cut Line= 3
      3636149.58     10539660.16      3635449.61     10539110.19
      3635049.59     10539260.19
#Sta/Elev= 30
  4109.7  332.04  4235.3  323.13  4259.7  320.25  4388.0  309.78  4479.3  303.60
  4508.2  303.01  4526.3  300.95  4529.1  300.45  4532.3  300.95  5015.0  300.95
  5039.9  304.63  5064.0  305.14  5070.2  307.31  5075.5  306.83  5085.3  309.11
  5138.7  314.63  5149.4  316.51  5155.6  319.24  5170.8  320.98  5180.6  324.09
  5185.9  324.27  5210.8  329.87  5216.2  329.45  5224.2  332.49  5241.1  335.46
  5356.8  341.72  5387.0  341.91  5412.0  340.42  5417.3  341.42  5427.1  341.11
#Mann=4,-1,0
  4109.7     0.1       0  4235.3    0.05       0  4526.3   0.033       0
  4532.3    0.05       0
Bank Sta=4526.3,4532.3
Exp/Cntr=0.3,0.1

Type RM Length L Ch R = 1,8849,534,534,534
BEGIN DESCRIPTION:
UNT 091 IN BUCR 6.0
END DESCRIPTION:
XS GIS Cut Line= 2
      3636907.41     10538863.54      3634234.26     10538820.15
#Sta/Elev= 30
  3541.9  353.27  3569.7  351.26  3599.7  345.90  3640.1  343.29  3672.0  342.50
  3729.7  335.66  3779.7  332.01  3831.9  325.66  3949.8  319.37  4129.8  306.55
  4173.6  304.51  4226.8  300.95  4229.5  300.45  4232.8  300.95  5089.9  300.95
  5199.9  306.85  5269.9  309.11  5319.9  306.33  5379.9  306.63  5399.9  304.84
  5439.9  305.45  5470.0  306.31  5520.0  310.65  5580.0  313.64  5760.0  314.92
  5810.0  320.71  5830.0  324.52  6020.0  344.30  6180.0  351.45  6215.4  354.91
#Mann=7,-1,0
  3541.9    0.05       0  3640.1    0.08       0  3672.0    0.05       0
  3831.9     0.1       0  4173.6    0.05       0  4226.8   0.033       0
  4232.8    0.05       0
Bank Sta=4226.8,4232.8
Exp/Cntr=0.3,0.1

Type RM Length L Ch R = 1,8315,1062,1062,1062
BEGIN DESCRIPTION:
Mapping XS ff5b79a4
END DESCRIPTION:
XS GIS Cut Line= 2
      3636916.12     10537995.49      3634131.02     10538585.48
#Sta/Elev= 30
  3501.3  341.46  3538.6  342.83  3566.1  340.64  3620.4  336.49  3722.6  332.64
  3833.8  319.00  3961.0  310.31  4131.9  304.70  4189.8  300.95  4192.6  300.45
  4195.8  300.95  4402.9  300.95  4480.8  300.95  5626.0  300.95  5920.3  321.79
  6002.1  330.35  6008.1  332.22  6073.7  338.14  6107.5  339.45  6152.1  343.29
  6157.2  342.39  6175.9  343.83  6196.3  345.94  6201.7  347.51  6216.8  347.91
  6246.3  352.00  6251.4  351.66  6288.3  356.73  6301.1  357.05  6348.2  363.90
#Mann=7,-1,0
  3501.3    0.05       0  3566.1     0.1       0  3961.0    0.05       0
  4189.8   0.033       0  4195.8    0.05       0  4402.9    0.08       0
  4480.8    0.05       0
Bank Sta=4189.8,4195.8
Exp/Cntr=0.3,0.1

Type RM Length L Ch R = 1,7253,96,96,96
BEGIN DESCRIPTION:
UNT 091 IN BUCR 5.0
END DESCRIPTION:
XS GIS Cut Line= 6
      3636740.28     10537631.11      3636146.51     10537469.65
      3636037.13     10537360.27      3635182.97     10537230.06
      3634755.88     10537891.52      3634469.43     10538151.94
#Sta/Elev= 30
  3559.4  330.07  3618.6  325.25  3674.1  323.30  3755.3  317.32  3953.9  304.63
  4112.0  300.95  4114.8  300.45  4118.0  300.95  4898.0  300.95  4974.6  300.95
  6061.4  300.95  6068.8  302.92  6075.6  302.62  6097.2  305.44  6139.1  308.42
  6146.5  310.42  6167.5  311.25  6174.9  312.76  6195.9  313.00  6203.3  315.05
  6224.2  314.49  6231.7  316.10  6261.6  318.43  6286.1  320.52  6301.9  321.17
  6309.4  323.11  6330.3  323.78  6337.8  325.53  6358.7  326.16  6395.6  330.30
#Mann=8,-1,0
  3559.4     0.1       0  3755.3    0.05       0  4112.0   0.033       0
  4118.0    0.05       0  4898.0    0.08       0  4974.6    0.05       0
  6261.6    0.08       0  6286.1    0.05       0
Bank Sta=4112,4118
Exp/Cntr=0.3,0.1

Type RM Length L Ch R = 1,7157,132,132,132
BEGIN DESCRIPTION:
UNT 091 IN BUCR 4.0
END DESCRIPTION:
XS GIS Cut Line= 6
      3636724.65     10537469.66      3636422.55     10537214.44
      3636078.80     10537261.31      3635078.80     10537136.31
      3634943.38     10537219.65      3634533.06     10537936.81
#Sta/Elev= 30
  3553.8  331.71  3592.4  332.53  3625.3  330.18  3855.0  319.43  3912.2  318.80
  3952.1  321.73  4033.4  318.30  4224.7  316.55  4407.0  309.82  4859.8  308.41
  4864.8  305.89  4988.0  308.39  4996.3  305.59  5059.6  308.94  5064.6  306.02
  5087.5  306.13  5302.9  310.90  5400.3  309.99  5448.6  310.31  5590.0  309.65
  5765.3  305.17  5869.4  303.55  5882.8  302.70  5931.4  301.28  5934.2  300.78
  5937.4  301.28  6000.2  303.58  6117.7  307.31  6228.2  314.02  6301.5  322.96
#Mann=14,-1,0
  3553.8     0.1       0  3625.3    0.05       0  4988.0     0.1       0
  5087.5    0.05       0  5400.3    0.08       0  5448.6    0.05       0
  5765.3    0.08       0  5869.4    0.05       0  5882.8    0.08       0
  5931.4    0.07       0  5937.4    0.08       0  6000.2    0.05       0
  6117.7    0.08       0  6228.2    0.05       0
Bank Sta=5931.4,5937.4
Exp/Cntr=0.3,0.1

Type RM Length L Ch R = 1,7025,363,363,363
BEGIN DESCRIPTION:
UNT 091 IN BUCR 3.0
END DESCRIPTION:
XS GIS Cut Line= 5
      3636714.18     10537193.60      3635302.76     10537011.31
      3635078.80     10537042.56      3634954.50     10537149.48
      3634545.99     10537851.43
#Sta/Elev= 30
  3677.6  327.71  3712.9  328.04  4085.5  320.33  4216.7  312.90  4256.9  313.17
  4337.6  308.47  4498.9  291.93  4539.3  290.83  4650.2  280.77  4908.8  278.81
  4982.9  278.02  5000.1  275.36  5002.8  274.86  5006.1  275.36  5093.4  283.29
  5200.5  298.78  5395.3  310.16  5429.1  310.05  5560.5  308.68  5605.1  308.38
  5671.5  305.25  5699.9  306.25  5815.8  300.37  5893.5  299.82  5985.5  300.03
  6004.5  297.80  6026.6  299.20  6226.4  308.59  6237.3  310.19  6303.0  315.66
#Mann=16,-1,0
  3677.6    0.16       0  3712.9    0.05       0  4908.8    0.12       0
  5000.1    0.07       0  5006.1    0.12       0  5093.4    0.05       0
  5429.1    0.08       0  5560.5    0.05       0  5605.1    0.16       0
  5671.5    0.05       0  5815.8    0.16       0  5893.5    0.05       0
  6004.5    0.08       0  6026.6    0.05       0  6226.4    0.08       0
  6237.3    0.05       0
Bank Sta=5000.1,5006.1
Exp/Cntr=0.3,0.1

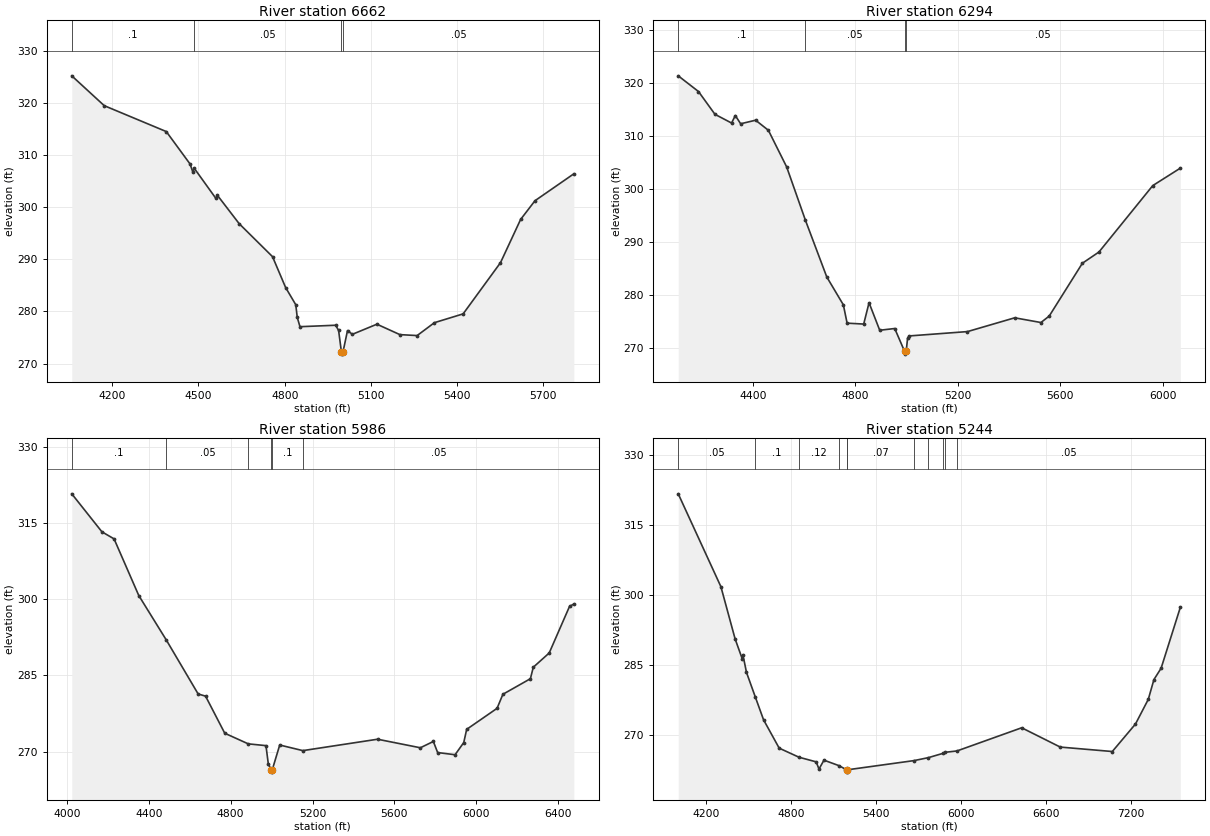
Type RM Length L Ch R = 1,6662,368,368,368
BEGIN DESCRIPTION:
UNT 091 IN BUCR 2.0
END DESCRIPTION:
XS GIS Cut Line= 3
      3636427.75     10536922.77      3635432.97     10536662.35
      3634714.39     10536657.15
#Sta/Elev= 30
  4059.1  325.18  4172.0  319.46  4388.0  314.49  4470.7  308.27  4479.9  306.80
  4485.4  307.44  4560.7  301.66  4565.9  302.26  4641.5  296.83  4757.6  290.50
  4803.2  284.58  4838.5  281.28  4843.6  278.86  4853.1  277.07  4977.2  277.35
  4987.5  276.36  4997.1  272.31  4999.9  271.81  5003.1  272.31  5018.5  276.33
  5035.4  275.61  5120.8  277.55  5200.8  275.55  5260.8  275.37  5320.8  277.84
  5420.8  279.53  5550.8  289.35  5620.8  297.64  5670.8  301.23  5806.0  306.39
#Mann=4,-1,0
  4059.1     0.1       0  4485.4    0.05       0  4997.1   0.035       0
  5003.1    0.05       0
Bank Sta=4997.1,5003.1
Exp/Cntr=0.3,0.1

Type RM Length L Ch R = 1,6294,308,308,308
BEGIN DESCRIPTION:
Mapping XS 1138091e
END DESCRIPTION:
XS GIS Cut Line= 3
      3636363.35     10536867.82      3635580.06     10536292.22
      3634636.55     10536588.92
#Sta/Elev= 30
  4107.8  321.27  4186.9  318.31  4251.3  314.01  4316.1  312.37  4330.7  313.78
  4351.6  312.23  4410.1  312.90  4459.9  311.00  4531.3  304.09  4604.8  294.01
  4688.0  283.34  4752.8  278.08  4767.4  274.63  4832.2  274.46  4853.1  278.48
  4894.8  273.29  4953.4  273.62  4992.1  269.29  4994.8  268.79  4998.1  269.29
  5003.5  271.74  5009.7  272.22  5237.6  273.04  5422.1  275.64  5524.5  274.75
  5556.9  275.97  5686.4  285.93  5751.2  288.05  5961.3  300.57  6068.9  303.86
#Mann=4,-1,0
  4107.8     0.1       0  4604.8    0.05       0  4992.1   0.035       0
  4998.1    0.05       0
Bank Sta=4992.1,4998.1
Exp/Cntr=0.3,0.1

Type RM Length L Ch R = 1,5986,742,742,742
BEGIN DESCRIPTION:
Mapping XS fa9b756d
END DESCRIPTION:
XS GIS Cut Line= 4
      3636360.08     10536823.85      3635911.77     10536131.62
      3635267.43     10535818.88      3634651.13     10536491.60
#Sta/Elev= 30
  4023.5  320.70  4170.8  313.23  4230.2  311.84  4350.9  300.70  4485.8  291.93
  4641.0  281.34  4677.3  280.91  4771.0  273.62  4885.8  271.53  4972.4  271.18
  4984.0  267.54  4997.5  266.47  5000.3  265.97  5003.5  266.47  5039.6  271.30
  5152.6  270.20  5517.6  272.44  5726.8  270.76  5790.3  272.00  5811.3  269.82
  5896.4  269.39  5938.9  271.79  5953.1  274.38  6101.7  278.52  6130.1  281.28
  6264.5  284.34  6278.7  286.60  6356.4  289.40  6455.7  298.56  6476.8  299.03
#Mann=6,-1,0
  4023.5     0.1       0  4485.8    0.05       0  4885.8     0.1       0
  4997.5    0.07       0  5003.5     0.1       0  5152.6    0.05       0
Bank Sta=4997.5,5003.5
Exp/Cntr=0.3,0.1

Type RM Length L Ch R = 1,5244,0,0,0
BEGIN DESCRIPTION:
UNT 091 IN BUCR 1.0
END DESCRIPTION:
XS GIS Cut Line= 6
      3636504.41     10536730.37      3636400.24     10535541.10
      3636109.44     10535415.23      3635336.87     10535541.10
      3634950.59     10535740.75      3634595.50     10536476.91
#Sta/Elev= 30
  4003.8  321.59  4305.1  301.72  4405.5  290.54  4455.3  286.33  4460.3  287.17
  4485.8  283.38  4546.9  278.22  4606.3  273.24  4716.7  267.17  4856.4  265.23
  4977.7  264.24  4997.8  262.70  5032.9  264.60  5138.6  263.43  5192.6  262.54
  5195.3  262.04  5198.6  262.54  5669.5  264.51  5770.4  265.14  5873.6  266.06
  5891.1  266.29  5972.0  266.57  6429.2  271.53  6701.6  267.40  7069.1  266.45
  7232.9  272.34  7323.4  277.62  7363.0  281.84  7413.8  284.27  7549.4  297.29
#Mann=11,-1,0
  4003.8    0.05       0  4546.9     0.1       0  4856.4    0.12       0
  5138.6    0.07       0  5192.6    0.07       0  5198.6    0.07       0
  5669.5     0.1       0  5770.4    0.12       0  5873.6    0.05       0
  5891.1     0.1       0  5972.0    0.05       0
Bank Sta=5192.6,5198.6
Exp/Cntr=0.3,0.1

Chan Stop Cuts=-1