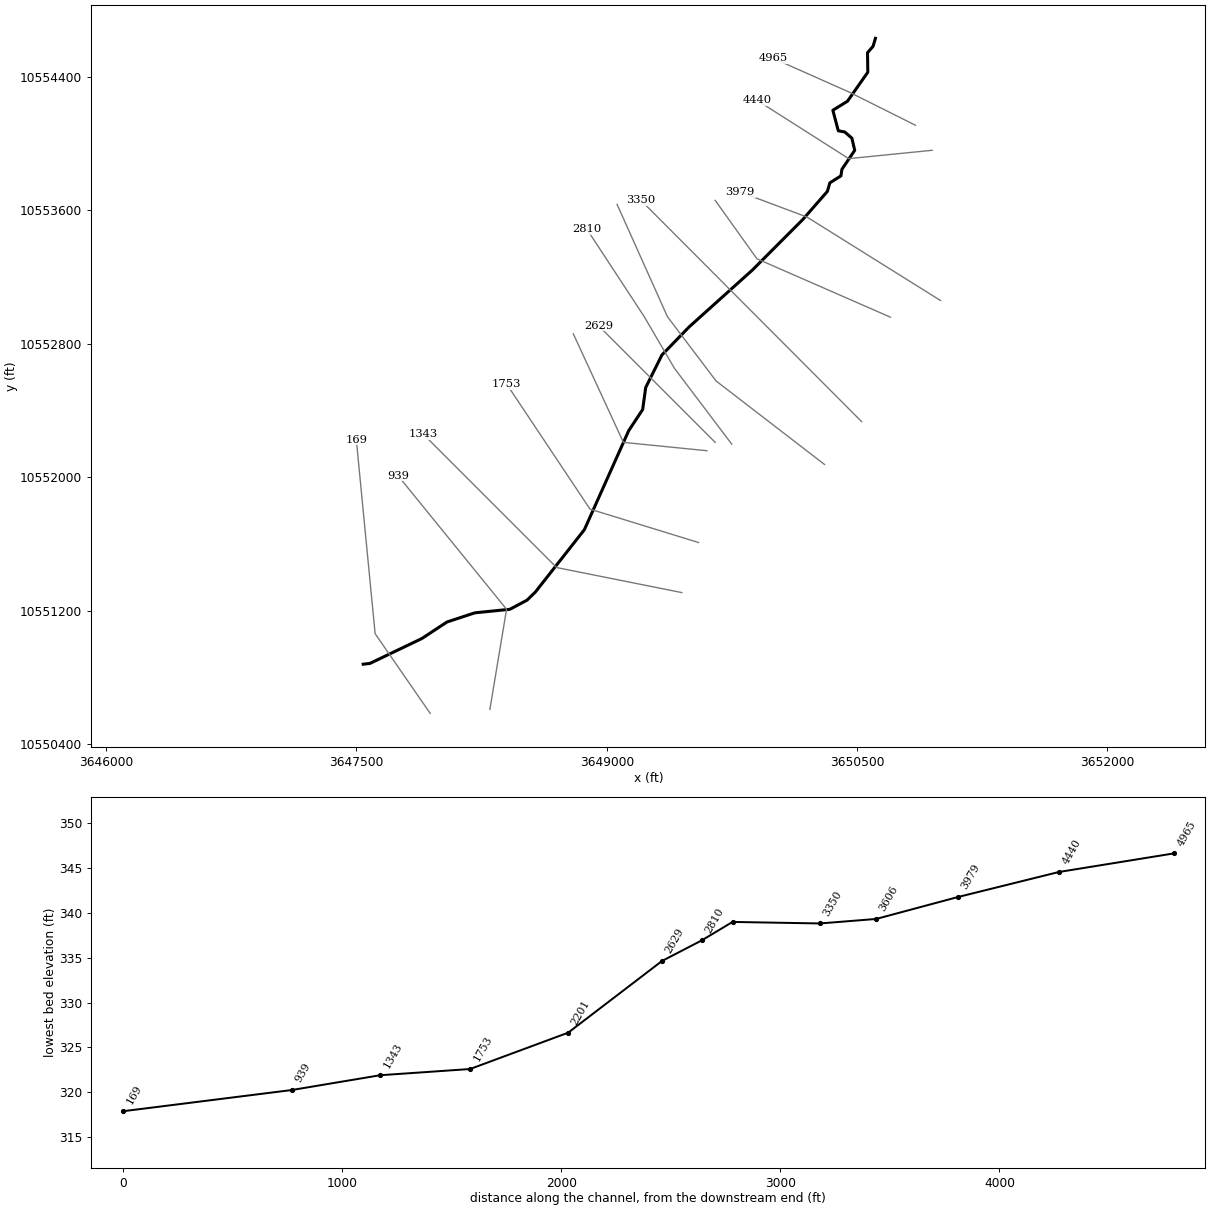
--- UNT 094 IN BUCR.prj (project) ---

Proj Title=UNT 094 IN BUCR Base Level Engineering
Current Plan=p01
Default Exp/Contr=0.3,0.1
English Units
Geom File=g01
Flow File=f01
Plan File=p01
BEGIN DESCRIPTION:
UNT 094 IN BUCR
END DESCRIPTION:

--- UNT 094 IN BUCR.p01 (plan) ---

Plan Title=Multiple Run
Short Identifier=Multiple
Geom File=g01
Flow File=f01
Subcritical Flow
K Sum by GR= 0
Std Step Tol= 0.01
Critical Tol= 0.01
Num of Std Step Trials= 20
Max Error Tol= 0.3
Flow Tol Ratio= 0.001
Split Flow NTrial= 30
Split Flow Tol= 0.02
Split Flow Ratio= 0.02
Log Output Level= 0
Friction Slope Method= 1
Unsteady Friction Slope Method= 2
Unsteady Bridges Friction Slope Method= 1
Parabolic Critical Depth
Global Vel Dist=  1 , 1 , 1
Global Log Level= 0
CheckData=True
Encroach Param= -1, 0, 0, 0
BEGIN DESCRIPTION:
Multiple Run
END DESCRIPTION:

--- UNT 094 IN BUCR.f01 (steady flow) ---

Flow Title=Multiple
Number of Profiles=7
Profile Names=10-year,25-year,50-year,1pct_min,100-year,1pct_plu,500-year
River Rch & RM= UNT 094 IN BUCR,Reach-1,4965
     517     701     852     762    1030    1394    1513
River Rch & RM= UNT 094 IN BUCR,Reach-1,3350
     659     903    1106     995    1346    1820    2002
Boundary for River Rch & Prof#=UNT 094 IN BUCR,Reach-1,1
Up Type=0
Dn Type=3
Dn Slope=0.005
Boundary for River Rch & Prof#=UNT 094 IN BUCR,Reach-1,2
Up Type=0
Dn Type=3
Dn Slope=0.005
Boundary for River Rch & Prof#=UNT 094 IN BUCR,Reach-1,3
Up Type=0
Dn Type=3
Dn Slope=0.005
Boundary for River Rch & Prof#=UNT 094 IN BUCR,Reach-1,4
Up Type=0
Dn Type=3
Dn Slope=0.005
Boundary for River Rch & Prof#=UNT 094 IN BUCR,Reach-1,5
Up Type=0
Dn Type=3
Dn Slope=0.005
Boundary for River Rch & Prof#=UNT 094 IN BUCR,Reach-1,6
Up Type=0
Dn Type=3
Dn Slope=0.005
Boundary for River Rch & Prof#=UNT 094 IN BUCR,Reach-1,7
Up Type=0
Dn Type=3
Dn Slope=0.005

--- UNT 094 IN BUCR.g01 (geometry) ---

Geom Title=Existing Conditions

River Reach=UNT 094 IN BUCR,Reach-1
Reach XY= 30
      3650609.75     10554631.00      3650595.25     10554583.00
      3650562.25     10554545.00      3650564.00     10554428.00
      3650442.00     10554254.00      3650354.50     10554200.00
      3650387.25     10554077.00      3650425.75     10554070.00
      3650468.50     10554033.00      3650485.50     10553960.00
      3650408.75     10553846.00      3650403.00     10553807.00
      3650336.50     10553765.00      3650321.75     10553714.00
      3650175.00     10553546.00      3649872.75     10553243.00
      3649493.50     10552902.00      3649330.50     10552734.00
      3649233.25     10552539.00      3649215.00     10552407.00
      3649131.25     10552280.00      3648865.75     10551687.00
      3648571.75     10551313.00      3648522.50     10551265.00
      3648419.50     10551210.00      3648210.00     10551189.00
      3648042.75     10551134.00      3647892.25     10551035.00
      3647581.50     10550886.00      3647540.50     10550881.00

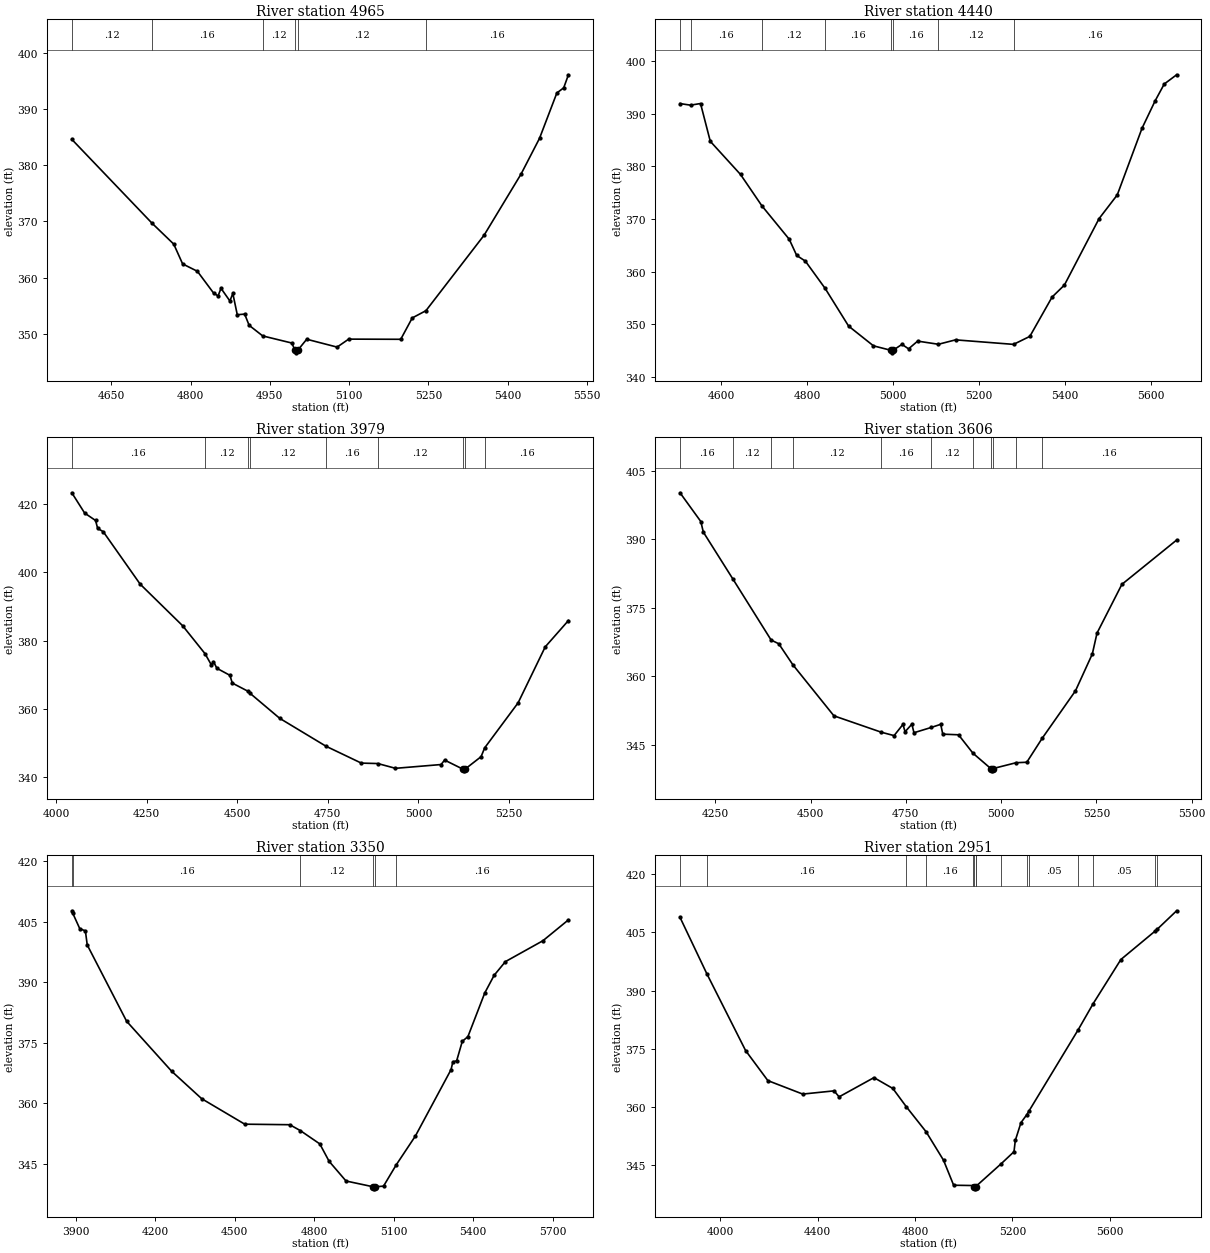
Type RM Length L Ch R = 1,4965,525,525,525
BEGIN DESCRIPTION:
UNT 094 IN BUCR 11.0
END DESCRIPTION:
XS GIS Cut Line= 3
      3650849.65     10554110.17      3650449.61     10554310.19
      3649999.61     10554510.19
#Sta/Elev= 30
  4575.3  384.59  4726.8  369.70  4768.2  365.95  4785.0  362.43  4812.9  361.12
  4843.7  357.23  4852.1  356.74  4857.6  358.09  4874.4  355.84  4880.0  357.17
  4888.4  353.39  4902.4  353.50  4910.8  351.51  4936.5  349.62  4991.8  348.35
  4997.2  347.11  4999.9  346.61  5003.2  347.11  5019.8  349.03  5077.3  347.63
  5099.2  349.05  5197.7  349.02  5219.5  352.82  5245.4  354.11  5355.6  367.56
  5425.4  378.42  5460.3  384.77  5493.1  392.84  5506.1  393.76  5515.0  396.08
#Mann=6,-1,0
  4575.3    0.12       0  4726.8    0.16       0  4936.5    0.12       0
  4997.2    0.07       0  5003.2    0.12       0  5245.4    0.16       0
Bank Sta=4997.2,5003.2
Exp/Cntr=0.3,0.1

Type RM Length L Ch R = 1,4440,461,461,461
BEGIN DESCRIPTION:
UNT 094 IN BUCR 10.0
END DESCRIPTION:
XS GIS Cut Line= 3
      3650949.61     10553960.19      3650449.61     10553910.19
      3649899.62     10554260.18
#Sta/Elev= 30
  4504.9  391.96  4529.3  391.66  4552.6  391.97  4575.3  384.78  4645.6  378.47
  4695.3  372.50  4758.7  366.16  4776.2  363.06  4796.3  361.99  4842.3  356.79
  4896.8  349.63  4954.6  345.87  4994.3  345.04  4997.1  344.54  5000.3  345.04
  5020.9  346.15  5036.2  345.30  5057.3  346.77  5105.6  346.17  5145.4  347.01
  5280.2  346.15  5318.1  347.67  5369.8  355.15  5398.5  357.44  5479.0  370.07
  5521.3  374.58  5578.9  387.27  5609.4  392.49  5630.5  395.68  5659.3  397.44
#Mann=8,-1,0
  4504.9    0.05       0  4529.3    0.16       0  4695.3    0.12       0
  4842.3    0.16       0  4994.3    0.07       0  5000.3    0.16       0
  5105.6    0.12       0  5280.2    0.16       0
Bank Sta=4994.3,5000.3
Exp/Cntr=0.3,0.1

Type RM Length L Ch R = 1,3979,373,373,373
BEGIN DESCRIPTION:
UNT 094 IN BUCR 9.0
END DESCRIPTION:
XS GIS Cut Line= 3
      3650999.65     10553060.16      3650199.61     10553560.19
      3649799.65     10553710.17
#Sta/Elev= 30
  4043.5  423.36  4078.9  417.41  4109.0  415.23  4114.9  412.89  4130.2  411.95
  4232.2  396.54  4349.6  384.31  4411.1  376.14  4428.6  372.85  4434.5  373.80
  4443.9  371.85  4479.9  369.78  4486.4  367.51  4530.6  365.06  4534.3  364.61
  4617.3  357.16  4745.1  348.97  4842.5  344.02  4888.1  343.89  4936.8  342.49
  5062.6  343.60  5072.4  344.91  5122.8  342.25  5125.5  341.75  5128.8  342.25
  5173.0  345.90  5183.0  348.50  5275.3  361.72  5350.1  378.14  5414.1  385.86
#Mann=9,-1,0
  4043.5    0.16       0  4411.1    0.12       0  4530.6    0.16       0
  4534.3    0.12       0  4745.1    0.16       0  4888.1    0.12       0
  5122.8    0.07       0  5128.8    0.12       0  5183.0    0.16       0
Bank Sta=5122.8,5128.8
Exp/Cntr=0.3,0.1

Type RM Length L Ch R = 1,3606,256,256,256
BEGIN DESCRIPTION:
UNT 094 IN BUCR 8.0
END DESCRIPTION:
XS GIS Cut Line= 3
      3650699.62     10552960.18      3649899.61     10553310.19
      3649649.63     10553660.16
#Sta/Elev= 30
  4157.3  400.17  4211.9  393.88  4218.5  391.56  4296.4  381.25  4396.4  367.94
  4416.5  367.12  4453.5  362.52  4561.2  351.35  4685.7  347.76  4719.1  347.02
  4742.4  349.47  4747.9  347.87  4765.8  349.52  4771.3  347.65  4816.4  348.80
  4841.5  349.49  4846.9  347.34  4888.2  347.20  4926.2  343.16  4972.9  339.81
  4975.7  339.31  4978.9  339.81  5039.5  341.09  5067.4  341.19  5107.4  346.39
  5195.2  356.83  5239.4  364.90  5251.7  369.46  5316.9  380.12  5460.6  389.82
#Mann=11,-1,0
  4157.3    0.16       0  4296.4    0.12       0  4396.4    0.16       0
  4453.5    0.12       0  4685.7    0.16       0  4816.4    0.12       0
  4926.2    0.16       0  4972.9    0.07       0  4978.9    0.16       0
  5039.5    0.12       0  5107.4    0.16       0
Bank Sta=4972.9,4978.9
Exp/Cntr=0.3,0.1

Type RM Length L Ch R = 1,3350,399,399,399
BEGIN DESCRIPTION:
UNT 094 IN BUCR 7.0
END DESCRIPTION:
XS GIS Cut Line= 2
      3650526.63     10552334.84      3649204.17     10553660.77
#Sta/Elev= 30
  3886.0  407.67  3888.7  407.19  3916.0  403.24  3937.2  402.69  3944.2  399.20
  4092.7  380.31  4262.4  367.94  4375.6  361.14  4538.2  354.82  4707.9  354.69
  4748.3  353.21  4821.1  349.94  4856.4  345.62  4920.1  340.75  5023.1  339.31
  5025.9  338.81  5029.1  339.31  5061.5  339.48  5109.3  344.74  5181.7  351.90
  5316.0  368.32  5323.1  370.28  5337.2  370.50  5358.5  375.34  5379.7  376.51
  5443.3  387.33  5478.7  391.70  5521.1  395.08  5662.5  400.25  5758.7  405.42
#Mann=6,-1,0
  3886.0    0.05       0  3888.7    0.16       0  4748.3    0.12       0
  5023.1    0.07       0  5029.1    0.12       0  5109.3    0.16       0
Bank Sta=5023.1,5029.1
Exp/Cntr=0.3,0.1

Type RM Length L Ch R = 1,2951,141,141,141
BEGIN DESCRIPTION:
Mapping XS 44a4c0c2
END DESCRIPTION:
XS GIS Cut Line= 4
      3650304.39     10552077.91      3649655.09     10552577.91
      3649363.42     10552963.32      3649061.74     10553636.03
#Sta/Elev= 30
  3834.8  408.88  3944.7  394.40  4104.3  374.58  4195.7  366.85  4338.9  363.38
  4467.6  364.21  4488.4  362.67  4631.6  367.62  4709.2  364.82  4764.2  360.14
  4845.7  353.68  4917.3  346.35  4958.9  339.91  5038.2  339.83  5042.9  339.48
  5045.7  338.98  5048.9  339.48  5049.7  339.57  5153.9  345.43  5206.8  348.54
  5212.2  351.43  5235.4  356.01  5259.6  358.10  5267.6  358.94  5470.9  379.98
  5532.3  386.69  5645.9  398.03  5787.9  405.42  5794.3  405.77  5874.9  410.58
#Mann=15,-1,0
  3834.8    0.05       0  3944.7    0.16       0  4764.2    0.08       0
  4845.7    0.16       0  5038.2    0.12       0  5042.9    0.07       0
  5048.9    0.12       0  5049.7    0.05       0  5153.9    0.16       0
  5259.6    0.12       0  5267.6    0.05       0  5470.9    0.16       0
  5532.3    0.05       0  5787.9    0.16       0  5794.3    0.05       0
Bank Sta=5042.9,5048.9
Exp/Cntr=0.3,0.1

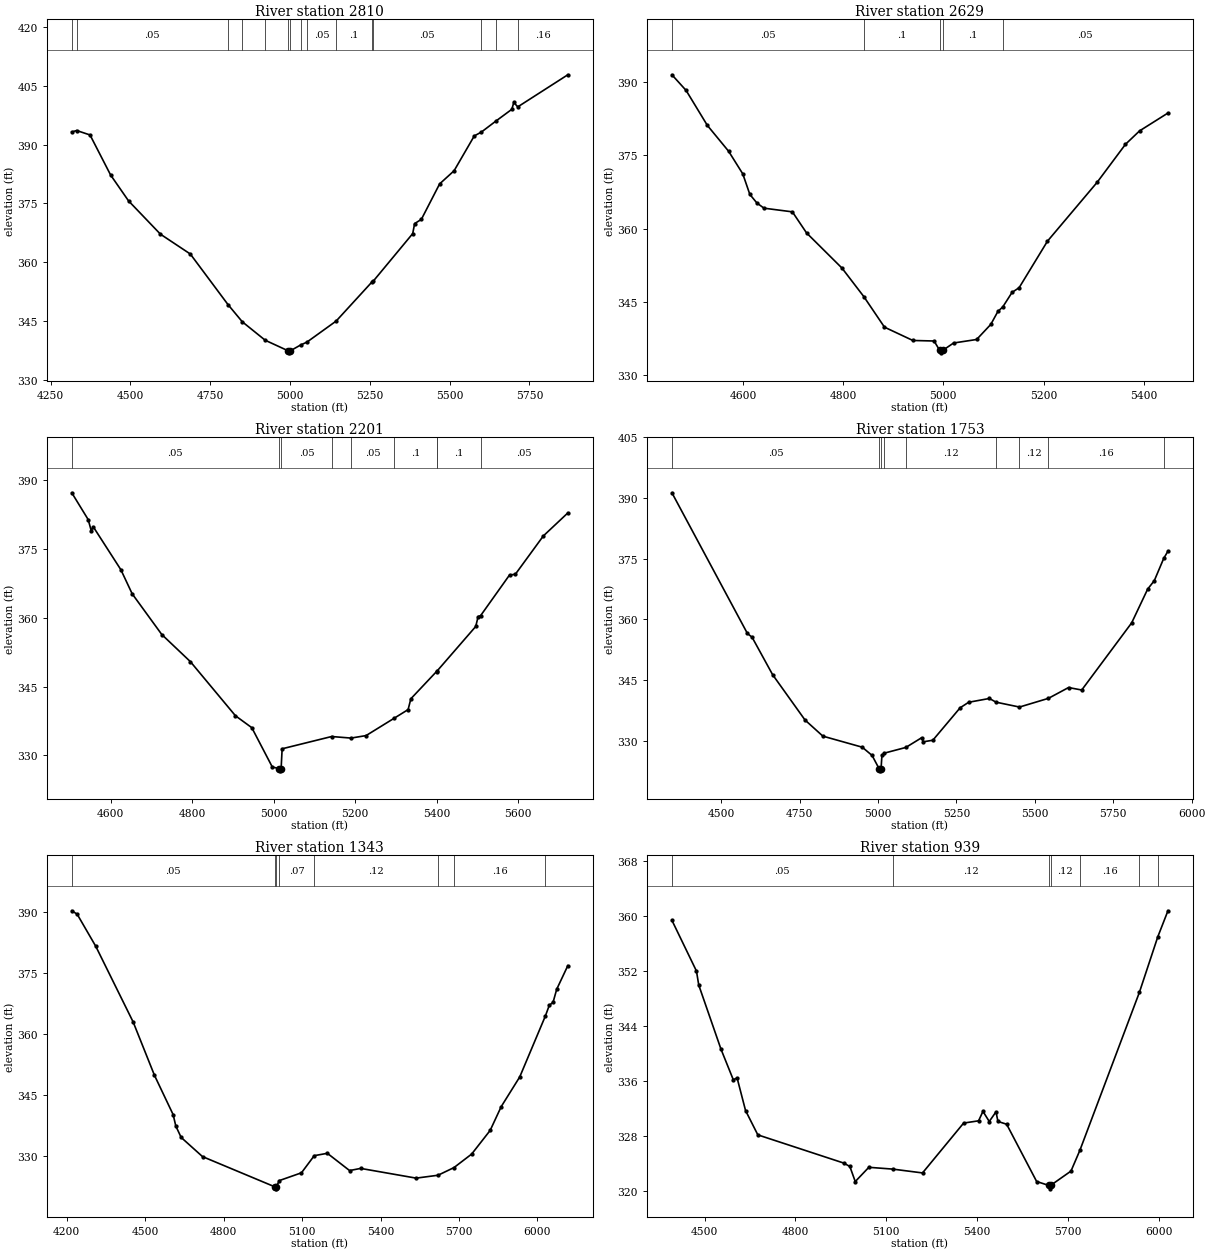
Type RM Length L Ch R = 1,2810,181,181,181
BEGIN DESCRIPTION:
Mapping XS eb81985f
END DESCRIPTION:
XS GIS Cut Line= 4
      3649748.85     10552199.42      3649405.09     10552654.30
      3649224.53     10552963.32      3648881.56     10553486.44
#Sta/Elev= 30
  4316.6  393.23  4331.8  393.60  4373.7  392.47  4438.2  382.26  4494.4  375.66
  4594.3  367.17  4687.9  362.11  4805.7  349.24  4850.6  344.84  4922.4  340.13
  4994.8  337.42  4997.6  336.92  5000.8  337.42  5033.5  338.93  5052.8  339.64
  5144.6  345.02  5256.0  354.92  5261.3  355.24  5384.4  367.32  5390.4  369.87
  5411.5  370.95  5468.7  379.99  5514.0  383.34  5577.3  392.23  5599.1  393.18
  5644.8  396.00  5694.9  399.01  5700.9  400.75  5713.5  399.63  5870.2  407.81
#Mann=15,-1,0
  4316.6    0.08       0  4331.8    0.05       0  4805.7    0.08       0
  4850.6     0.1       0  4922.4    0.05       0  4994.8    0.04       0
  5000.8    0.05       0  5033.5    0.08       0  5052.8    0.05       0
  5144.6     0.1       0  5256.0    0.08       0  5261.3    0.05       0
  5599.1    0.16       0  5644.8    0.05       0  5713.5    0.16       0
Bank Sta=4994.8,5000.8
Exp/Cntr=0.3,0.1

Type RM Length L Ch R = 1,2629,428,428,428
BEGIN DESCRIPTION:
UNT 094 IN BUCR 6.0
END DESCRIPTION:
XS GIS Cut Line= 3
      3649649.59     10552210.21      3649249.61     10552610.19
      3648949.62     10552910.18
#Sta/Elev= 30
  4458.3  391.49  4486.6  388.29  4529.0  381.14  4571.4  375.86  4599.7  371.23
  4613.8  367.03  4628.0  365.26  4642.1  364.21  4698.7  363.46  4727.0  359.15
  4797.7  351.96  4841.4  346.11  4882.5  339.88  4939.1  337.16  4981.5  337.05
  4992.7  335.13  4995.4  334.63  4998.7  335.13  5020.4  336.64  5066.4  337.36
  5094.7  340.45  5108.8  343.09  5118.6  344.02  5137.1  346.99  5151.2  347.95
  5207.8  357.47  5306.8  369.49  5363.4  377.27  5391.6  380.02  5448.2  383.67
#Mann=5,-1,0
  4458.3    0.05       0  4841.4     0.1       0  4992.7    0.07       0
  4998.7     0.1       0  5118.6    0.05       0
Bank Sta=4992.7,4998.7
Exp/Cntr=0.3,0.1

Type RM Length L Ch R = 1,2201,448,448,448
BEGIN DESCRIPTION:
UNT 094 IN BUCR 5.0
END DESCRIPTION:
XS GIS Cut Line= 3
      3649599.64     10552160.19      3649099.61     10552210.19
      3648799.61     10552860.18
#Sta/Elev= 30
  4504.1  387.17  4544.3  381.35  4551.9  378.92  4556.9  379.76  4624.7  370.42
  4652.4  365.19  4725.2  356.32  4795.6  350.40  4906.1  338.64  4946.3  336.04
  4996.6  327.49  5012.3  327.15  5015.1  326.65  5018.3  327.15  5020.8  331.45
  5142.4  334.12  5189.9  333.78  5226.9  334.32  5296.0  338.10  5330.2  339.98
  5337.0  342.34  5400.1  348.27  5402.2  348.46  5496.3  358.07  5502.2  360.22
  5508.3  360.43  5579.3  369.27  5593.6  369.43  5662.4  377.78  5722.5  382.78
#Mann=9,-1,0
  4504.1    0.05       0  5012.3    0.03       0  5018.3    0.05       0
  5142.4     0.1       0  5189.9    0.05       0  5296.0     0.1       0
  5400.1    0.12       0  5402.2     0.1       0  5508.3    0.05       0
Bank Sta=5012.3,5018.3
Exp/Cntr=0.3,0.1

Type RM Length L Ch R = 1,1753,410,410,410
BEGIN DESCRIPTION:
UNT 094 IN BUCR 4.0
END DESCRIPTION:
XS GIS Cut Line= 3
      3649549.59     10551610.19      3648899.61     10551810.19
      3648399.63     10552560.15
#Sta/Elev= 30
  4343.0  391.30  4583.6  356.55  4598.7  355.59  4664.1  346.35  4767.4  335.15
  4824.3  331.17  4949.8  328.44  4981.2  326.40  5003.7  323.10  5006.5  322.60
  5009.7  323.10  5012.6  326.45  5020.5  326.98  5088.7  328.38  5138.7  330.76
  5144.7  329.78  5174.8  330.16  5261.9  338.18  5289.0  339.54  5355.1  340.48
  5376.5  339.56  5451.1  338.36  5543.3  340.51  5607.5  343.18  5649.5  342.57
  5808.8  359.17  5859.8  367.51  5880.9  369.59  5910.8  375.07  5924.4  376.88
#Mann=9,-1,0
  4343.0    0.05       0  5003.7    0.03       0  5009.7    0.05       0
  5020.5    0.07       0  5088.7    0.12       0  5376.5    0.16       0
  5451.1    0.12       0  5543.3    0.16       0  5910.8    0.05       0
Bank Sta=5003.7,5009.7
Exp/Cntr=0.3,0.1

Type RM Length L Ch R = 1,1343,404,404,404
BEGIN DESCRIPTION:
UNT 094 IN BUCR 3.0
END DESCRIPTION:
XS GIS Cut Line= 3
      3649449.63     10551310.18      3648699.61     10551460.19
      3647899.64     10552260.15
#Sta/Elev= 30
  4219.8  390.22  4240.2  389.40  4311.6  381.48  4454.4  362.90  4536.0  349.78
  4607.3  340.14  4617.5  337.33  4637.9  334.54  4719.5  329.83  4995.8  322.41
  4998.6  321.91  5001.8  322.41  5013.2  323.94  5097.8  325.85  5146.7  330.06
  5196.8  330.64  5281.7  326.40  5324.1  326.93  5536.2  324.54  5619.8  325.25
  5680.8  327.13  5748.4  330.45  5819.1  336.26  5861.5  342.12  5932.2  349.40
  6030.4  364.40  6045.3  367.02  6059.5  367.72  6073.6  370.95  6116.0  376.73
#Mann=8,-1,0
  4219.8    0.05       0  4995.8    0.03       0  5001.8    0.05       0
  5013.2    0.07       0  5146.7    0.12       0  5619.8    0.07       0
  5680.8    0.16       0  6030.4    0.05       0
Bank Sta=4995.8,5001.8
Exp/Cntr=0.3,0.1

Type RM Length L Ch R = 1,939,770,770,770
BEGIN DESCRIPTION:
UNT 094 IN BUCR 2.0
END DESCRIPTION:
XS GIS Cut Line= 3
      3648299.61     10550610.17      3648399.61     10551210.19
      3647749.59     10552010.21
#Sta/Elev= 30
  4391.9  359.42  4473.0  352.02  4480.6  349.97  4554.1  340.62  4594.7  336.17
  4607.3  336.43  4635.2  331.68  4675.8  328.13  4959.6  324.02  4979.9  323.52
  4997.7  321.32  5042.6  323.40  5121.1  323.14  5220.0  322.58  5355.8  329.85
  5405.3  330.18  5419.7  331.56  5440.5  330.08  5462.8  331.49  5469.2  330.09
  5498.0  329.68  5597.1  321.33  5637.2  320.76  5640.0  320.26  5643.2  320.76
  5710.6  322.85  5740.2  325.90  5936.6  348.91  5997.4  357.01  6031.0  360.81
#Mann=7,-1,0
  4391.9    0.05       0  5121.1    0.12       0  5637.2   0.035       0
  5643.2    0.12       0  5740.2    0.16       0  5936.6    0.12       0
  5997.4    0.05       0
Bank Sta=5637.2,5643.2
Exp/Cntr=0.3,0.1

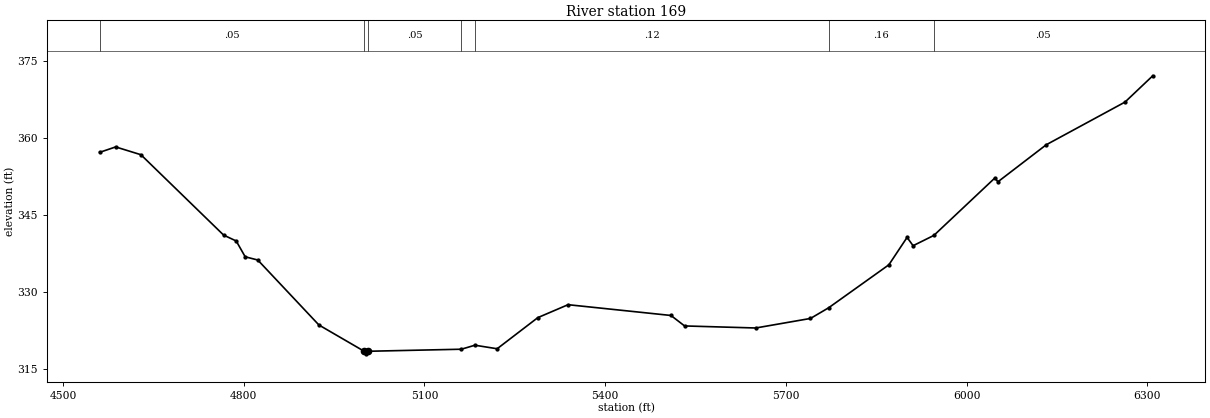
Type RM Length L Ch R = 1,169,0,0,0
BEGIN DESCRIPTION:
UNT 094 IN BUCR 1.0
END DESCRIPTION:
XS GIS Cut Line= 3
      3647941.96     10550586.45      3647612.07     10551063.92
      3647499.32     10552226.12
#Sta/Elev= 30
  4560.9  357.18  4587.5  358.24  4629.4  356.72  4766.7  341.05  4787.6  339.90
  4802.5  336.82  4823.4  336.19  4924.8  323.53  5000.0  318.40  5002.8  317.90
  5006.0  318.40  5161.2  318.80  5183.8  319.58  5220.7  318.89  5288.2  324.96
  5338.4  327.48  5509.2  325.38  5531.8  323.34  5649.9  322.94  5740.8  324.80
  5770.8  326.87  5870.9  335.26  5901.1  340.60  5911.1  338.98  5945.6  340.99
  6046.9  352.19  6051.9  351.44  6132.1  358.66  6262.8  366.98  6308.9  372.11
#Mann=7,-1,0
  4560.9    0.05       0  5000.0   0.035       0  5006.0    0.05       0
  5161.2    0.16       0  5183.8    0.12       0  5770.8    0.16       0
  5945.6    0.05       0
Bank Sta=5000,5006
Exp/Cntr=0.3,0.1

Chan Stop Cuts=-1