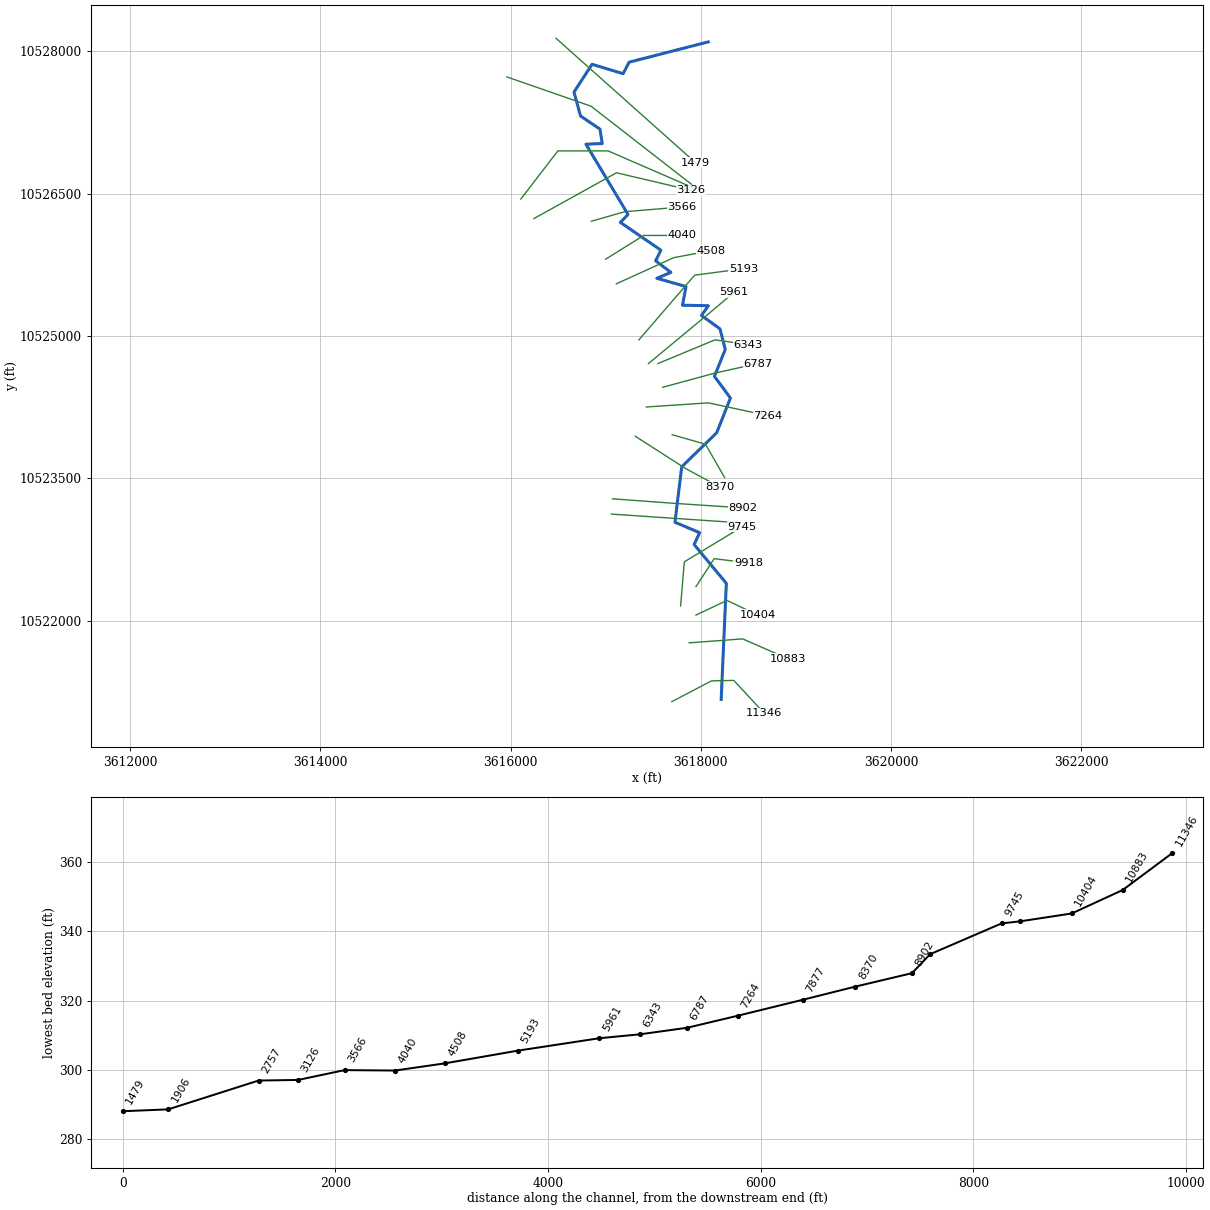
--- UNT 1 TO ALLIGATOR CR.prj (project) ---

Proj Title=UNT 1 TO ALLIGATOR CR Base Level Engineering
Current Plan=p01
Default Exp/Contr=0.3,0.1
English Units
Geom File=g01
Flow File=f01
Plan File=p01
BEGIN DESCRIPTION:
UNT 1 TO ALLIGATOR CR
END DESCRIPTION:

--- UNT 1 TO ALLIGATOR CR.p01 (plan) ---

Plan Title=Multiple Run
Short Identifier=Multiple
Geom File=g01
Flow File=f01
Subcritical Flow
K Sum by GR= 0
Std Step Tol= 0.01
Critical Tol= 0.01
Num of Std Step Trials= 20
Max Error Tol= 0.3
Flow Tol Ratio= 0.001
Split Flow NTrial= 30
Split Flow Tol= 0.02
Split Flow Ratio= 0.02
Log Output Level= 0
Friction Slope Method= 1
Unsteady Friction Slope Method= 2
Unsteady Bridges Friction Slope Method= 1
Parabolic Critical Depth
Global Vel Dist=  1 , 1 , 1
Global Log Level= 0
CheckData=True
Encroach Param= -1, 0, 0, 0
BEGIN DESCRIPTION:
Multiple Run
END DESCRIPTION:

--- UNT 1 TO ALLIGATOR CR.f01 (steady flow) ---

Flow Title=Multiple
Number of Profiles=7
Profile Names=10-year,25-year,50-year,1pct_min,100-year,1pct_plu,500-year
River Rch & RM= UNT 1 TO ALLIGAT,Reach-1,11346
     852    1166    1426    1275    1725    2332    2512
River Rch & RM= UNT 1 TO ALLIGAT,Reach-1,7264
    1125    1559    1921    1729    2338    3163    3451
Boundary for River Rch & Prof#=UNT 1 TO ALLIGAT,Reach-1,1
Up Type=0
Dn Type=3
Dn Slope=0.005
Boundary for River Rch & Prof#=UNT 1 TO ALLIGAT,Reach-1,2
Up Type=0
Dn Type=3
Dn Slope=0.005
Boundary for River Rch & Prof#=UNT 1 TO ALLIGAT,Reach-1,3
Up Type=0
Dn Type=3
Dn Slope=0.005
Boundary for River Rch & Prof#=UNT 1 TO ALLIGAT,Reach-1,4
Up Type=0
Dn Type=3
Dn Slope=0.005
Boundary for River Rch & Prof#=UNT 1 TO ALLIGAT,Reach-1,5
Up Type=0
Dn Type=3
Dn Slope=0.005
Boundary for River Rch & Prof#=UNT 1 TO ALLIGAT,Reach-1,6
Up Type=0
Dn Type=3
Dn Slope=0.005
Boundary for River Rch & Prof#=UNT 1 TO ALLIGAT,Reach-1,7
Up Type=0
Dn Type=3
Dn Slope=0.005

--- UNT 1 TO ALLIGATOR CR.g01 (geometry) ---

Geom Title=Existing Conditions

River Reach=UNT 1 TO ALLIGAT,Reach-1
Reach XY= 30
      3618214.25     10521171.00      3618268.50     10522394.00
      3617930.00     10522803.00      3617987.75     10522928.00
      3617728.25     10523038.00      3617799.25     10523622.00
      3618167.00     10523981.00      3618311.75     10524347.00
      3618143.00     10524575.00      3618257.25     10524859.00
      3618201.50     10525076.00      3618007.00     10525217.00
      3618079.50     10525320.00      3617807.50     10525325.00
      3617844.75     10525522.00      3617538.00     10525609.00
      3617686.00     10525671.00      3617525.25     10525793.00
      3617580.50     10525905.00      3617154.75     10526198.00
      3617234.75     10526282.00      3616792.50     10527022.00
      3616964.00     10527029.00      3616940.00     10527181.00
      3616735.75     10527319.00      3616666.75     10527571.00
      3616856.75     10527864.00      3617183.25     10527765.00
      3617246.25     10527886.00      3618078.00     10528100.00

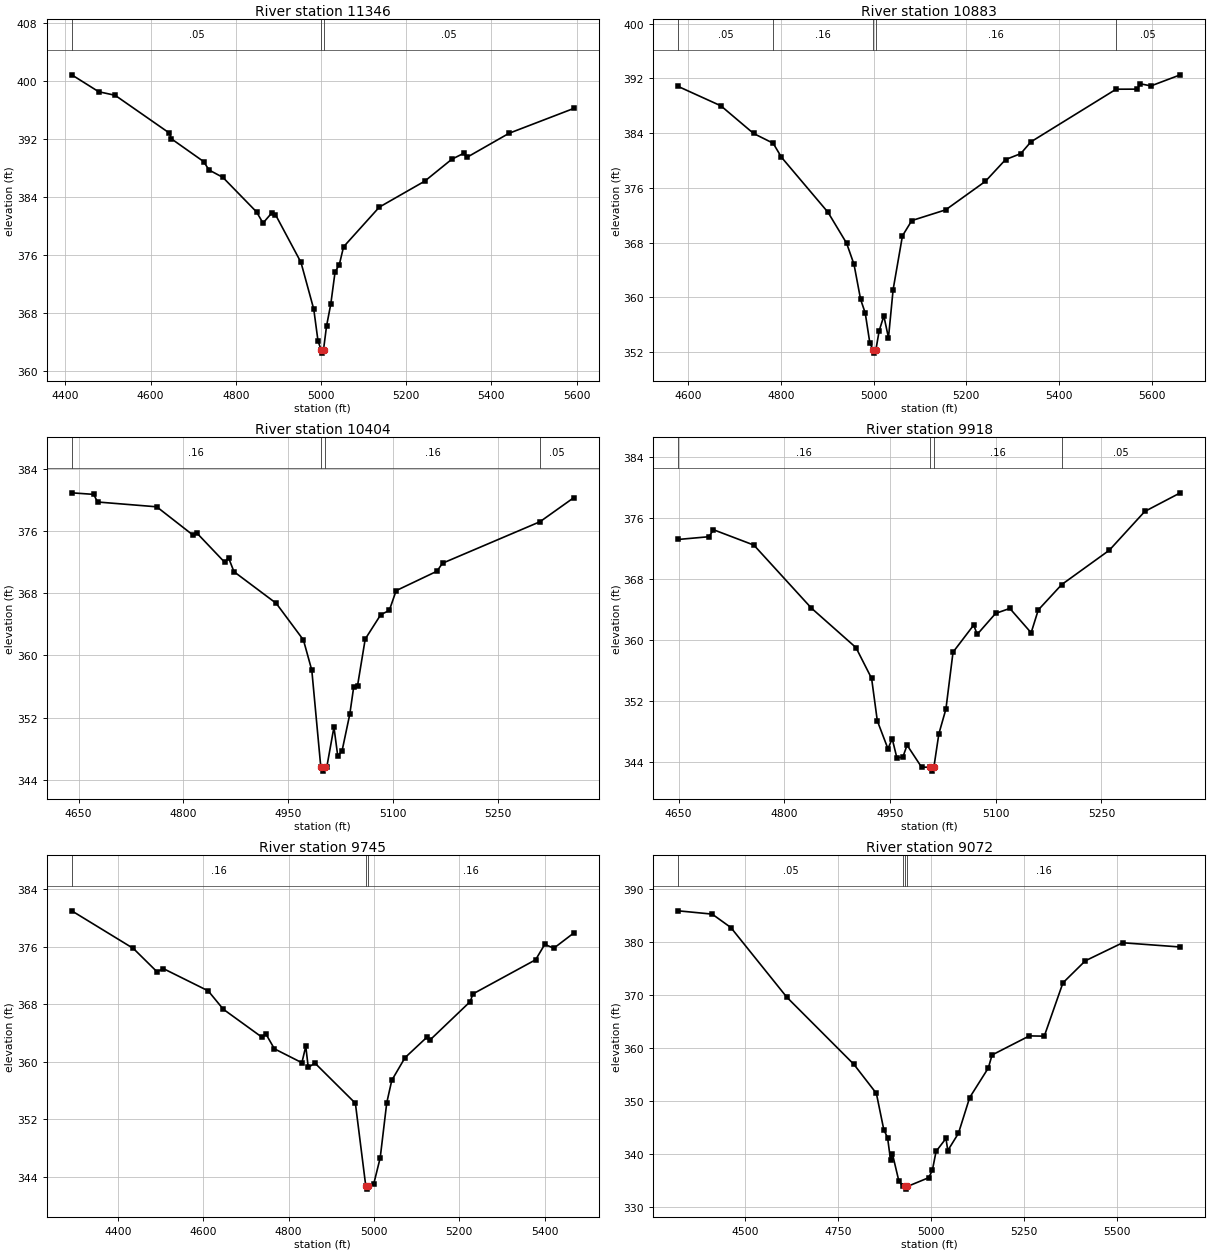
Type RM Length L Ch R = 1,11346,463,463,463
BEGIN DESCRIPTION:
UNT 1 TO ALLIGATOR CR 17.0
END DESCRIPTION:
XS GIS Cut Line= 4
      3617695.58     10521147.38      3618112.20     10521366.11
      3618346.58     10521371.32      3618668.18     10521023.78
#Sta/Elev= 30
  4415.1  400.81  4478.3  398.48  4516.8  397.99  4643.5  392.81  4649.1  391.98
  4724.6  388.85  4737.3  387.69  4769.8  386.67  4848.8  381.91  4864.0  380.37
  4884.7  381.78  4893.1  381.55  4953.1  374.95  4983.1  368.50  4993.1  364.11
  5000.1  362.94  5002.8  362.44  5006.1  362.94  5013.1  366.17  5023.1  369.21
  5033.1  373.62  5043.1  374.65  5053.1  377.10  5137.0  382.57  5243.6  386.15
  5307.1  389.17  5335.4  390.00  5342.2  389.42  5441.5  392.75  5593.6  396.18
#Mann=3,-1,0
  4415.1    0.05       0  5000.1    0.03       0  5006.1    0.05       0
Bank Sta=5000.1,5006.1
Exp/Cntr=0.3,0.1

Type RM Length L Ch R = 1,10883,479,479,479
BEGIN DESCRIPTION:
UNT 1 TO ALLIGATOR CR 16.0
END DESCRIPTION:
XS GIS Cut Line= 3
      3617877.83     10521767.15      3618440.33     10521808.82
      3618914.32     10521600.47
#Sta/Elev= 30
  4579.2  390.82  4671.2  387.99  4741.4  383.96  4783.7  382.53  4801.6  380.48
  4901.9  372.44  4942.0  367.92  4957.9  364.84  4972.1  359.73  4982.1  357.73
  4992.1  353.33  4999.1  352.37  5001.9  351.87  5005.1  352.37  5012.2  355.15
  5022.2  357.30  5032.2  354.12  5042.2  361.15  5062.3  369.00  5082.4  371.23
  5155.5  372.80  5240.8  376.95  5284.5  380.14  5317.2  381.01  5339.1  382.73
  5522.7  390.42  5568.5  390.43  5574.3  391.22  5597.7  390.90  5661.0  392.52
#Mann=5,-1,0
  4579.2    0.05       0  4783.7    0.16       0  4999.1    0.07       0
  5005.1    0.16       0  5522.7    0.05       0
Bank Sta=4999.1,5005.1
Exp/Cntr=0.3,0.1

Type RM Length L Ch R = 1,10404,486,486,486
BEGIN DESCRIPTION:
UNT 1 TO ALLIGATOR CR 15.0
END DESCRIPTION:
XS GIS Cut Line= 3
      3617949.62     10522060.19      3618275.00     10522214.00
      3618599.60     10522060.19
#Sta/Elev= 30
  4640.1  380.93  4671.5  380.73  4677.0  379.75  4761.8  379.13  4813.6  375.50
  4819.1  375.77  4859.1  371.99  4864.6  372.58  4872.4  370.78  4932.9  366.71
  4971.9  361.99  4983.9  358.09  4996.8  345.61  4999.5  345.11  5002.8  345.61
  5005.3  345.61  5015.6  350.77  5021.1  347.03  5027.2  347.71  5038.3  352.44
  5043.9  355.94  5049.4  356.11  5060.4  362.11  5082.6  365.24  5094.9  365.80
  5104.7  368.34  5163.1  370.84  5171.1  371.87  5310.7  377.21  5359.2  380.31
#Mann=4,-1,0
  4640.1    0.16       0  4996.8    0.07       0  5002.8    0.16       0
  5310.7    0.05       0
Bank Sta=4996.8,5002.8
Exp/Cntr=0.3,0.1

Type RM Length L Ch R = 1,9918,173,173,173
BEGIN DESCRIPTION:
UNT 1 TO ALLIGATOR CR 14.0
END DESCRIPTION:
XS GIS Cut Line= 3
      3617949.60     10522360.17      3618140.50     10522654.00
      3618499.64     10522610.19
#Sta/Elev= 30
  4649.6  373.20  4693.4  373.56  4699.4  374.48  4756.9  372.46  4838.4  364.21
  4901.7  359.03  4923.9  354.99  4932.0  349.43  4947.1  345.77  4953.1  347.09
  4959.7  344.60  4968.2  344.67  4974.2  346.25  4994.7  343.37  5006.2  343.34
  5008.9  342.84  5012.2  343.34  5019.3  347.73  5029.3  350.97  5039.4  358.43
  5068.7  361.98  5073.7  360.76  5099.8  363.51  5120.0  364.16  5150.2  360.97
  5160.3  363.96  5193.6  367.29  5261.0  371.78  5311.4  376.87  5361.8  379.31
#Mann=4,-1,0
  4649.6    0.16       0  5006.2    0.07       0  5012.2    0.16       0
  5193.6    0.05       0
Bank Sta=5006.2,5012.2
Exp/Cntr=0.3,0.1

Type RM Length L Ch R = 1,9745,673,673,673
BEGIN DESCRIPTION:
UNT 1 TO ALLIGATOR CR 13.0
END DESCRIPTION:
XS GIS Cut Line= 3
      3617787.82     10522156.31      3617826.89     10522620.73
      3618434.50     10522989.64
#Sta/Elev= 30
  4291.6  380.98  4436.0  375.74  4491.5  372.49  4506.2  372.94  4611.4  369.84
  4646.7  367.29  4737.0  363.41  4747.1  363.80  4766.5  361.78  4831.0  359.84
  4840.1  362.12  4846.0  359.18  4861.4  359.80  4956.4  354.20  4980.6  342.75
  4983.3  342.25  4986.6  342.75  4999.1  342.90  5014.6  346.61  5029.9  354.25
  5041.7  357.39  5072.7  360.54  5123.5  363.36  5130.9  362.98  5225.8  368.36
  5231.7  369.41  5378.9  374.17  5400.3  376.31  5421.6  375.78  5468.5  377.90
#Mann=3,-1,0
  4291.6    0.16       0  4980.6    0.07       0  4986.6    0.16       0
Bank Sta=4980.6,4986.6
Exp/Cntr=0.3,0.1

Type RM Length L Ch R = 1,9072,170,170,170
BEGIN DESCRIPTION:
Mapping XS 8e9c15cb
END DESCRIPTION:
XS GIS Cut Line= 3
      3617058.65     10523124.21      3618013.52     10523059.10
      3618404.17     10523033.06
#Sta/Elev= 30
  4320.5  385.83  4411.7  385.21  4461.8  382.68  4612.1  369.55  4792.5  356.87
  4852.7  351.41  4872.7  344.55  4882.8  343.06  4890.9  338.77  4895.9  339.99
  4912.8  334.97  4923.0  333.96  4929.9  333.86  4932.6  333.36  4935.9  333.86
  4993.0  335.51  5003.0  336.88  5013.1  340.48  5039.6  342.91  5044.6  340.64
  5073.2  343.89  5103.3  350.62  5153.4  356.20  5163.4  358.65  5263.6  362.25
  5303.7  362.20  5353.8  372.25  5414.0  376.41  5514.2  379.81  5669.1  379.01
#Mann=4,-1,0
  4320.5    0.05       0  4923.0    0.16       0  4929.9    0.07       0
  4935.9    0.16       0
Bank Sta=4929.9,4935.9
Exp/Cntr=0.3,0.1

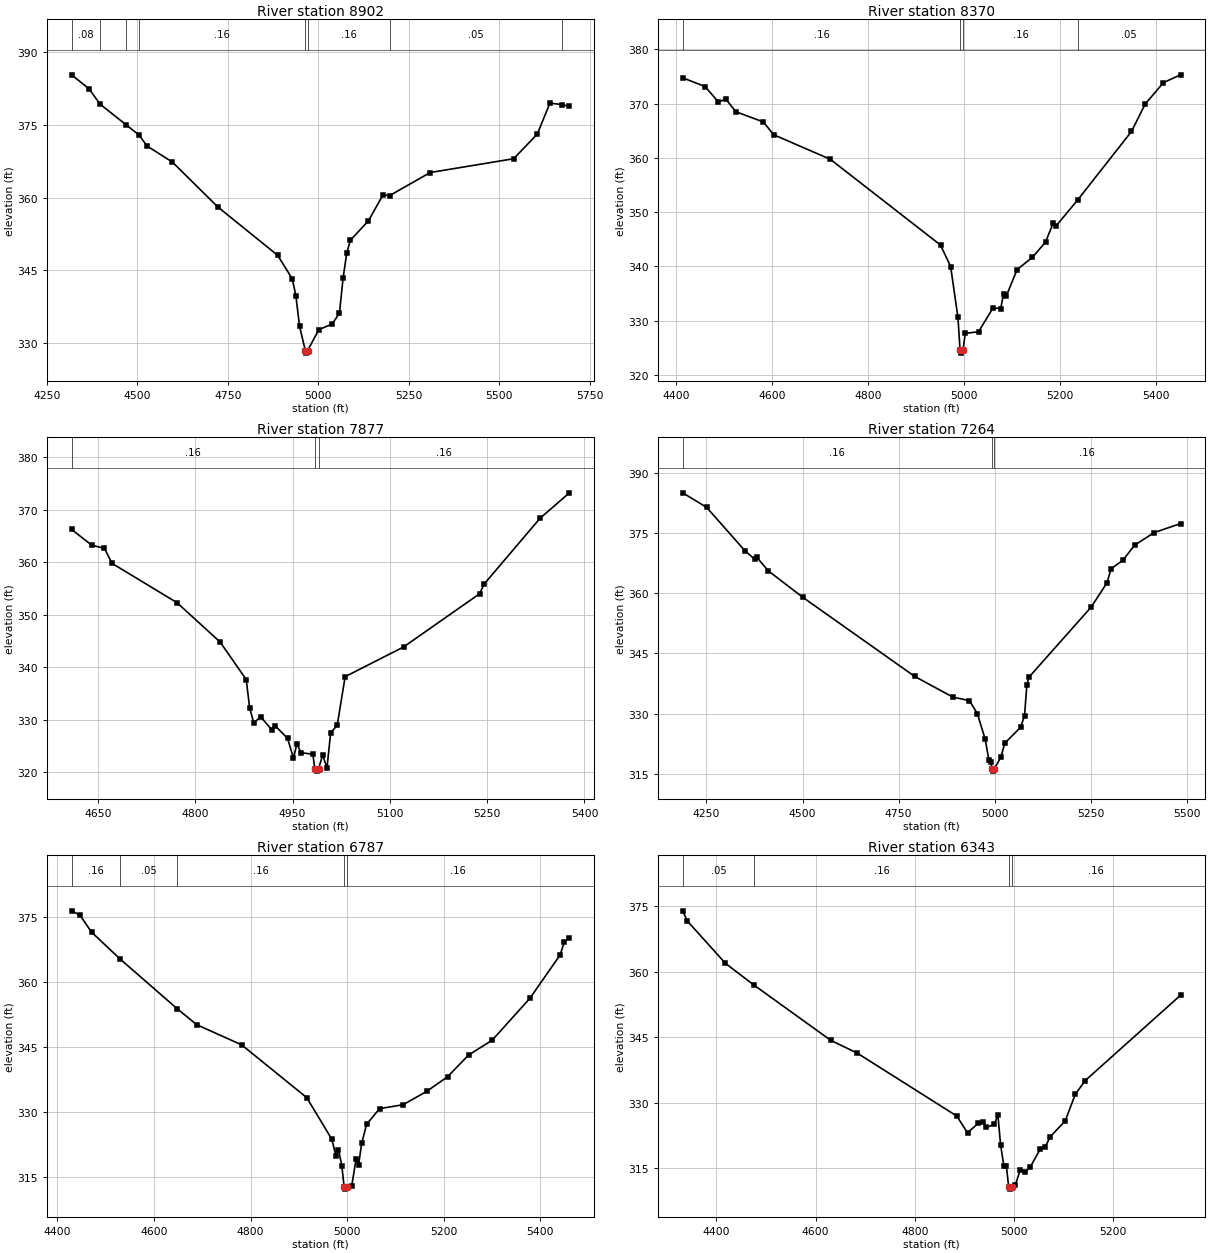
Type RM Length L Ch R = 1,8902,532,532,532
BEGIN DESCRIPTION:
UNT 1 TO ALLIGATOR CR 12.0
END DESCRIPTION:
XS GIS Cut Line= 3
      3617071.73     10523284.79      3617722.72     10523237.05
      3618443.20     10523189.31
#Sta/Elev= 30
  4318.6  385.37  4366.6  382.50  4397.4  379.31  4468.3  375.10  4505.3  372.91
  4527.0  370.67  4597.2  367.34  4723.0  358.05  4888.0  348.08  4928.1  343.24
  4938.1  339.73  4948.2  333.44  4964.3  328.39  4967.0  327.89  4970.3  328.39
  5001.4  332.74  5038.4  333.90  5058.4  336.16  5068.4  343.35  5078.5  348.51
  5088.5  351.20  5138.6  355.23  5178.7  360.58  5197.3  360.44  5309.0  365.19
  5539.5  368.04  5604.6  373.11  5639.7  379.52  5672.2  379.24  5693.4  378.84
#Mann=8,-1,0
  4318.6    0.08       0  4397.4    0.05       0  4468.3    0.08       0
  4505.3    0.16       0  4964.3    0.07       0  4970.3    0.16       0
  5197.3    0.05       0  5672.2    0.16       0
Bank Sta=4964.3,4970.3
Exp/Cntr=0.3,0.1

Type RM Length L Ch R = 1,8370,493,493,493
BEGIN DESCRIPTION:
UNT 1 TO ALLIGATOR CR 11.0
END DESCRIPTION:
XS GIS Cut Line= 3
      3617310.36     10523944.54      3617844.25     10523601.64
      3618199.63     10523410.18
#Sta/Elev= 30
  4413.7  374.75  4460.3  373.14  4488.3  370.29  4503.5  370.84  4524.6  368.50
  4582.1  366.61  4603.2  364.27  4721.5  359.74  4951.4  343.93  4972.5  339.97
  4987.7  330.59  4992.2  324.52  4994.9  324.02  4998.2  324.52  5002.9  327.65
  5030.8  327.97  5060.9  332.36  5077.0  332.23  5082.8  334.99  5088.5  334.53
  5111.1  339.42  5142.8  341.65  5170.4  344.48  5186.6  348.05  5192.3  347.44
  5237.8  352.29  5349.6  364.86  5378.1  369.90  5416.2  373.86  5451.9  375.30
#Mann=4,-1,0
  4413.7    0.16       0  4992.2    0.07       0  4998.2    0.16       0
  5237.8    0.05       0
Bank Sta=4992.2,4998.2
Exp/Cntr=0.3,0.1

Type RM Length L Ch R = 1,7877,613,613,613
BEGIN DESCRIPTION:
UNT 1 TO ALLIGATOR CR 10.0
END DESCRIPTION:
XS GIS Cut Line= 3
      3617699.56     10523960.20      3618049.61     10523860.19
      3618249.63     10523510.16
#Sta/Elev= 30
  4609.5  366.24  4640.7  363.24  4660.2  362.64  4671.9  359.78  4772.1  352.29
  4838.4  344.81  4878.7  337.67  4883.9  332.31  4890.4  329.37  4900.8  330.60
  4917.7  328.15  4922.9  328.91  4942.4  326.47  4951.5  322.68  4956.7  325.41
  4963.2  323.74  4981.5  323.44  4984.2  320.73  4987.0  320.23  4990.2  320.73
  4996.6  323.33  5003.1  320.77  5008.8  327.54  5018.9  328.94  5031.1  338.21
  5121.1  343.86  5238.5  354.01  5244.9  355.78  5331.3  368.34  5376.7  373.21
#Mann=3,-1,0
  4609.5    0.16       0  4984.2    0.07       0  4990.2    0.16       0
Bank Sta=4984.2,4990.2
Exp/Cntr=0.3,0.1

Type RM Length L Ch R = 1,7264,477,477,477
BEGIN DESCRIPTION:
UNT 1 TO ALLIGATOR CR 9.0
END DESCRIPTION:
XS GIS Cut Line= 3
      3617427.60     10524252.68      3618078.62     10524296.08
      3618706.27     10524161.90
#Sta/Elev= 30
  4188.5  385.13  4250.7  381.50  4350.9  370.60  4376.2  368.52  4381.2  369.02
  4411.0  365.65  4501.2  359.00  4791.9  339.26  4890.5  334.13  4934.0  333.22
  4954.5  330.00  4974.9  323.60  4984.4  318.49  4989.5  317.95  4992.4  316.12
  4995.1  315.62  4998.4  316.12  5015.8  319.13  5026.0  322.61  5067.0  326.57
  5077.2  329.47  5083.3  337.15  5088.5  339.06  5251.0  356.65  5291.9  362.71
  5302.2  366.17  5332.8  368.27  5363.5  372.07  5414.4  375.21  5482.8  377.44
#Mann=3,-1,0
  4188.5    0.16       0  4992.4    0.07       0  4998.4    0.16       0
Bank Sta=4992.4,4998.4
Exp/Cntr=0.3,0.1

Type RM Length L Ch R = 1,6787,444,444,444
BEGIN DESCRIPTION:
UNT 1 TO ALLIGATOR CR 8.0
END DESCRIPTION:
XS GIS Cut Line= 3
      3617599.64     10524460.20      3618149.61     10524610.19
      3618599.58     10524710.18
#Sta/Elev= 30
  4429.2  376.43  4446.4  375.45  4470.6  371.51  4529.0  365.37  4648.6  353.75
  4688.3  350.13  4781.6  345.46  4916.3  333.27  4968.2  323.67  4976.8  319.77
  4982.0  321.26  4988.9  317.56  4993.7  312.64  4996.4  312.14  4999.7  312.64
  5009.5  312.91  5018.5  319.12  5023.6  317.70  5030.0  322.70  5040.2  327.10
  5067.1  330.73  5115.8  331.64  5164.4  334.70  5208.0  338.11  5251.5  343.12
  5300.2  346.53  5378.3  356.20  5441.0  366.24  5450.0  369.33  5460.2  370.21
#Mann=5,-1,0
  4429.2    0.16       0  4529.0    0.05       0  4648.6    0.16       0
  4993.7    0.07       0  4999.7    0.16       0
Bank Sta=4993.7,4999.7
Exp/Cntr=0.3,0.1

Type RM Length L Ch R = 1,6343,382,382,382
BEGIN DESCRIPTION:
UNT 1 TO ALLIGATOR CR 7.0
END DESCRIPTION:
XS GIS Cut Line= 3
      3617549.59     10524710.18      3618149.61     10524960.19
      3618499.64     10524910.18
#Sta/Elev= 30
  4332.2  373.87  4341.4  371.56  4418.3  361.87  4476.4  356.85  4630.7  344.26
  4683.8  341.36  4884.7  326.96  4906.4  323.12  4928.1  325.32  4938.3  325.50
  4943.8  324.34  4960.6  325.06  4967.6  327.24  4973.0  320.45  4979.5  315.63
  4984.7  315.63  4989.3  310.75  4992.1  310.25  4995.3  310.75  5002.4  311.11
  5012.5  314.54  5022.6  314.14  5032.7  315.26  5052.9  319.38  5063.0  319.89
  5073.1  322.20  5103.4  325.87  5123.6  331.92  5143.8  335.08  5335.8  354.57
#Mann=4,-1,0
  4332.2    0.05       0  4476.4    0.16       0  4989.3    0.07       0
  4995.3    0.16       0
Bank Sta=4989.3,4995.3
Exp/Cntr=0.3,0.1

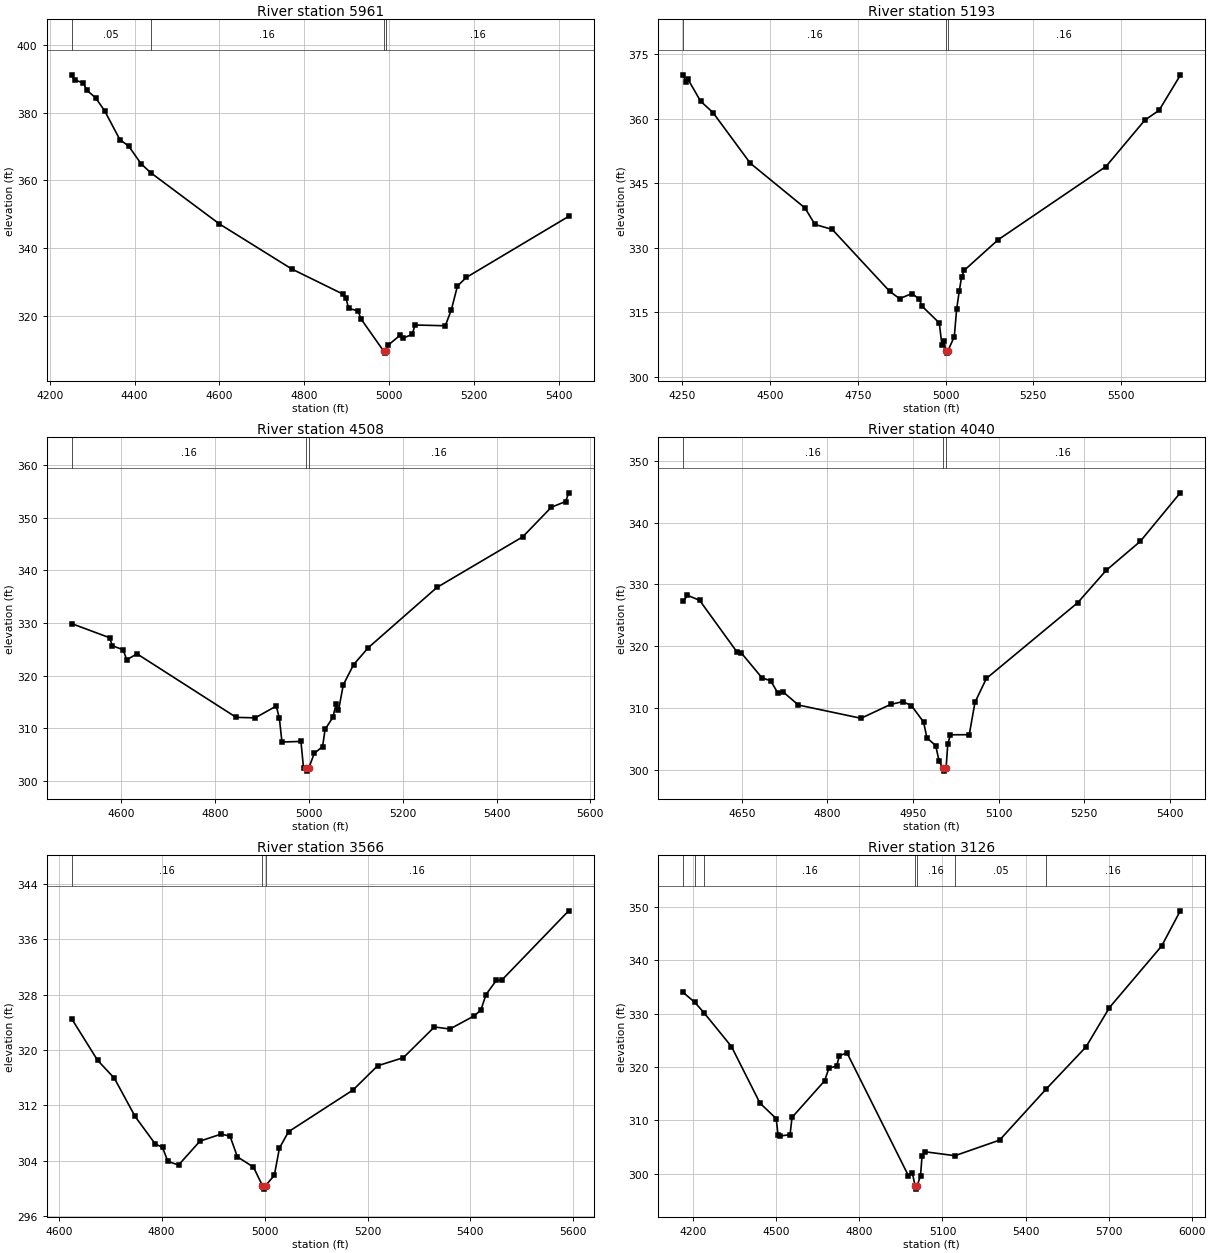
Type RM Length L Ch R = 1,5961,768,768,768
BEGIN DESCRIPTION:
UNT 1 TO ALLIGATOR CR 6.0
END DESCRIPTION:
XS GIS Cut Line= 3
      3617449.57     10524710.16      3618095.98     10525246.60
      3618349.61     10525460.19
#Sta/Elev= 30
  4251.4  391.11  4258.6  389.63  4279.4  388.69  4287.3  386.59  4308.1  384.35
  4329.4  380.52  4365.4  372.01  4386.2  370.11  4414.9  364.97  4437.6  362.31
  4599.8  347.19  4770.4  333.91  4890.2  326.56  4898.0  325.42  4904.5  322.28
  4926.7  321.58  4933.1  319.29  4987.5  309.62  4990.2  309.12  4993.5  309.62
  4997.0  311.40  5025.6  314.38  5032.1  313.49  5054.3  314.66  5060.8  317.41
  5132.3  317.18  5146.6  321.93  5160.9  328.89  5181.7  331.41  5423.0  349.41
#Mann=4,-1,0
  4251.4    0.05       0  4437.6    0.16       0  4987.5    0.07       0
  4993.5    0.16       0
Bank Sta=4987.5,4993.5
Exp/Cntr=0.3,0.1

Type RM Length L Ch R = 1,5193,685,685,685
BEGIN DESCRIPTION:
UNT 1 TO ALLIGATOR CR 5.0
END DESCRIPTION:
XS GIS Cut Line= 3
      3617349.61     10524960.19      3617935.39     10525641.57
      3618449.57     10525710.18
#Sta/Elev= 30
  4251.8  370.22  4258.9  368.63  4265.5  369.20  4301.7  364.08  4336.8  361.46
  4443.3  349.67  4599.1  339.28  4627.6  335.44  4677.0  334.28  4840.5  319.91
  4869.0  318.18  4904.2  319.39  4925.0  318.09  4932.7  316.46  4982.1  312.55
  4989.7  307.34  4996.3  308.24  5000.5  306.03  5003.2  305.53  5006.5  306.03
  5024.9  309.37  5031.5  315.73  5039.1  319.98  5045.7  323.29  5053.4  324.79
  5149.8  331.88  5457.3  348.91  5568.3  359.71  5608.6  361.96  5669.1  370.11
#Mann=3,-1,0
  4251.8    0.16       0  5000.5    0.07       0  5006.5    0.16       0
Bank Sta=5000.5,5006.5
Exp/Cntr=0.3,0.1

Type RM Length L Ch R = 1,4508,468,468,468
BEGIN DESCRIPTION:
UNT 1 TO ALLIGATOR CR 4.0
END DESCRIPTION:
XS GIS Cut Line= 3
      3617112.44     10525550.51      3617716.59     10525826.55
      3618105.94     10525899.22
#Sta/Elev= 30
  4493.5  329.90  4574.9  327.20  4580.4  325.70  4603.4  324.92  4611.3  323.04
  4633.3  324.14  4844.7  312.08  4885.2  311.99  4930.2  314.23  4936.8  311.91
  4942.3  307.40  4982.8  307.51  4988.3  302.47  4993.1  302.37  4995.9  301.87
  4999.1  302.37  5011.3  305.25  5028.9  306.53  5034.4  309.82  5051.1  312.11
  5057.4  314.53  5062.9  313.39  5073.1  318.25  5095.1  322.10  5126.5  325.32
  5272.7  336.75  5455.8  346.37  5516.8  351.99  5547.4  353.08  5553.8  354.73
#Mann=3,-1,0
  4493.5    0.16       0  4993.1    0.07       0  4999.1    0.16       0
Bank Sta=4993.1,4999.1
Exp/Cntr=0.3,0.1

Type RM Length L Ch R = 1,4040,474,474,474
BEGIN DESCRIPTION:
UNT 1 TO ALLIGATOR CR 3.0
END DESCRIPTION:
XS GIS Cut Line= 3
      3616999.63     10525810.20      3617399.61     10526060.19
      3617799.64     10526060.19
#Sta/Elev= 30
  4547.0  327.25  4554.6  328.24  4575.9  327.43  4641.3  319.09  4649.0  318.92
  4685.5  314.87  4700.3  314.43  4712.7  312.51  4722.1  312.63  4749.2  310.49
  4858.9  308.35  4910.8  310.59  4932.0  311.04  4947.3  310.41  4968.6  307.74
  4974.5  305.17  4989.8  303.94  4995.7  301.49  5002.1  300.30  5004.9  299.80
  5008.1  300.30  5011.0  304.18  5015.7  305.68  5048.7  305.69  5058.7  310.92
  5078.7  314.79  5238.7  327.03  5288.7  332.27  5348.7  336.98  5418.7  344.82
#Mann=3,-1,0
  4547.0    0.16       0  5002.1    0.07       0  5008.1    0.16       0
Bank Sta=5002.1,5008.1
Exp/Cntr=0.3,0.1

Type RM Length L Ch R = 1,3566,440,440,440
BEGIN DESCRIPTION:
UNT 1 TO ALLIGATOR CR 2.0
END DESCRIPTION:
XS GIS Cut Line= 3
      3616849.63     10526210.20      3617199.61     10526310.19
      3617799.65     10526360.19
#Sta/Elev= 30
  4624.8  324.56  4675.5  318.52  4708.0  315.94  4748.3  310.42  4787.3  306.46
  4801.6  305.94  4812.0  303.93  4832.8  303.40  4874.4  306.85  4916.0  307.88
  4932.9  307.55  4947.2  304.58  4978.4  303.10  4995.8  300.42  4998.6  299.92
  5001.8  300.42  5018.9  301.91  5028.9  305.86  5046.5  308.21  5171.9  314.24
  5219.6  317.73  5269.8  318.91  5330.0  323.34  5360.1  323.04  5407.7  324.96
  5420.3  325.78  5430.3  328.02  5450.4  330.07  5460.4  330.06  5590.9  340.11
#Mann=3,-1,0
  4624.8    0.16       0  4995.8    0.07       0  5001.8    0.16       0
Bank Sta=4995.8,5001.8
Exp/Cntr=0.3,0.1

Type RM Length L Ch R = 1,3126,369,369,369
BEGIN DESCRIPTION:
Mapping XS ea57cdce
END DESCRIPTION:
XS GIS Cut Line= 3
      3616245.85     10526238.20      3617113.92     10526720.85
      3617894.92     10526536.88
#Sta/Elev= 30
  4163.4  333.97  4205.2  332.14  4238.7  330.17  4338.0  323.82  4440.9  313.22
  4499.5  310.31  4506.1  307.31  4511.9  307.03  4549.6  307.30  4556.7  310.53
  4674.3  317.39  4690.3  319.81  4717.7  320.14  4728.0  322.13  4755.5  322.62
  4977.4  299.57  4991.5  300.04  5001.8  297.58  5004.6  297.08  5007.8  297.58
  5020.8  299.58  5026.5  303.37  5036.8  304.09  5145.1  303.35  5306.3  306.27
  5473.1  315.77  5618.6  323.76  5703.3  331.14  5891.9  342.69  5959.0  349.28
#Mann=7,-1,0
  4163.4    0.16       0  4205.2    0.05       0  4238.7    0.16       0
  5001.8    0.07       0  5007.8    0.16       0  5145.1    0.05       0
  5473.1    0.16       0
Bank Sta=5001.8,5007.8
Exp/Cntr=0.3,0.1

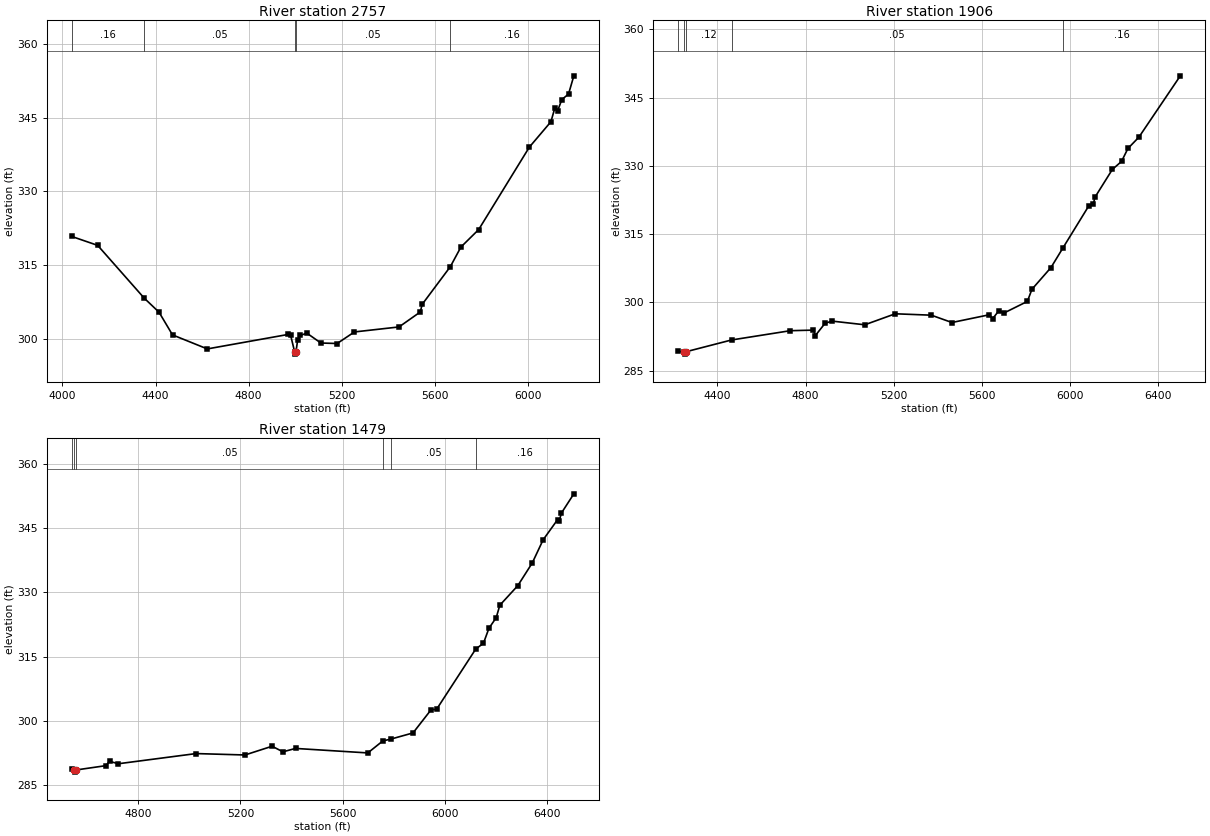
Type RM Length L Ch R = 1,2757,851,851,851
BEGIN DESCRIPTION:
Mapping XS 1ef265b7
END DESCRIPTION:
XS GIS Cut Line= 4
      3616108.60     10526444.57      3616497.48     10526951.50
      3617025.25     10526951.50      3617934.81     10526555.74
#Sta/Elev= 30
  4039.9  320.85  4151.2  319.04  4351.5  308.30  4415.0  305.45  4473.1  300.83
  4622.6  297.98  4970.9  300.93  4980.9  300.74  4997.9  297.42  5000.7  296.92
  5003.9  297.42  5010.9  299.73  5020.9  300.71  5050.9  301.18  5110.9  299.18
  5180.9  299.08  5255.0  301.43  5446.9  302.45  5538.5  305.50  5546.1  307.02
  5667.5  314.71  5713.0  318.70  5789.3  322.25  6007.4  339.03  6099.9  344.18
  6116.5  346.93  6128.8  346.41  6146.8  348.69  6175.6  349.81  6198.5  353.52
#Mann=5,-1,0
  4039.9    0.16       0  4351.5    0.05       0  4997.9    0.03       0
  5003.9    0.05       0  5667.5    0.16       0
Bank Sta=4997.9,5003.9
Exp/Cntr=0.3,0.1

Type RM Length L Ch R = 1,1906,427,427,427
BEGIN DESCRIPTION:
Mapping XS e913523d
END DESCRIPTION:
XS GIS Cut Line= 3
      3615961.15     10527731.26      3616846.56     10527422.24
      3617902.10     10526599.33
#Sta/Elev= 30
  4222.9  289.20  4250.0  289.10  4252.8  288.60  4256.0  289.10  4464.4  291.71
  4730.9  293.75  4835.6  293.88  4844.6  292.68  4888.5  295.38  4920.3  295.86
  5068.6  295.05  5206.8  297.47  5370.5  297.16  5463.7  295.55  5633.8  297.26
  5648.3  296.40  5677.2  298.18  5698.0  297.60  5805.7  300.19  5826.5  302.86
  5912.7  307.63  5967.0  311.95  6083.4  321.13  6104.2  321.50  6112.3  323.10
  6191.0  329.20  6232.7  330.97  6261.6  333.81  6311.4  336.30  6499.1  349.78
#Mann=5,-1,0
  4222.9    0.12       0  4250.0    0.03       0  4256.0    0.12       0
  4464.4    0.05       0  5967.0    0.16       0
Bank Sta=4250,4256
Exp/Cntr=0.3,0.1

Type RM Length L Ch R = 1,1479,0,0,0
BEGIN DESCRIPTION:
UNT 1 TO ALLIGATOR CR 1.0
END DESCRIPTION:
XS GIS Cut Line= 2
      3616478.51     10528137.52      3617945.81     10526826.31
#Sta/Elev= 30
  4538.8  288.71  4549.1  288.56  4551.9  288.06  4555.1  288.56  4672.5  289.57
  4686.7  290.57  4721.9  290.02  5026.2  292.39  5217.6  292.06  5323.8  294.10
  5366.4  292.80  5415.7  293.59  5699.1  292.54  5757.9  295.34  5790.1  295.78
  5876.3  297.21  5947.4  302.64  5968.3  302.69  6122.3  316.80  6152.2  318.11
  6173.9  321.64  6202.3  324.10  6216.5  327.01  6286.8  331.56  6343.6  336.87
  6386.3  342.28  6443.1  346.99  6449.8  346.69  6457.3  348.46  6506.6  353.00
#Mann=6,-1,0
  4538.8    0.05       0  4549.1    0.03       0  4555.1    0.05       0
  5757.9    0.16       0  5790.1    0.05       0  6122.3    0.16       0
Bank Sta=4549.1,4555.1
Exp/Cntr=0.3,0.1

Chan Stop Cuts=-1