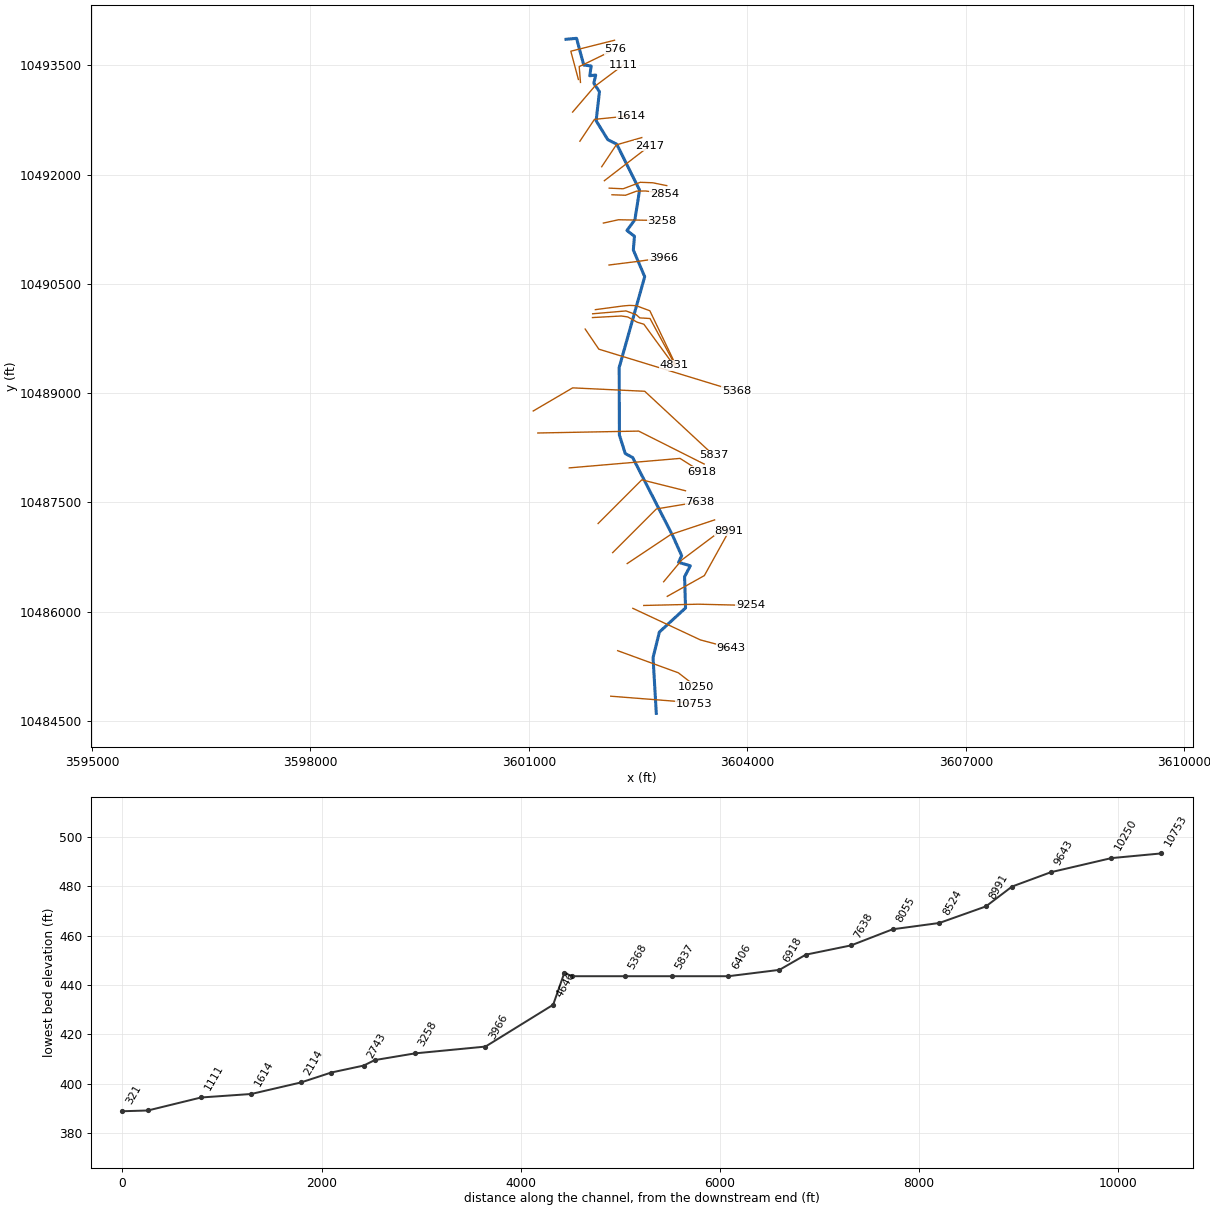
--- UNT 1 TO WEST FORK PANTHER CR.prj (project) ---

Proj Title=UNT 1 TO WEST FORK PANTHER CR Base Level Engineering
Current Plan=p01
Default Exp/Contr=0.3,0.1
English Units
Geom File=g01
Flow File=f01
Plan File=p01
BEGIN DESCRIPTION:
UNT 1 TO WEST FORK PANTHER CR
END DESCRIPTION:

--- UNT 1 TO WEST FORK PANTHER CR.p01 (plan) ---

Plan Title=Multiple Run
Short Identifier=Multiple
Geom File=g01
Flow File=f01
Subcritical Flow
K Sum by GR= 0
Std Step Tol= 0.01
Critical Tol= 0.01
Num of Std Step Trials= 20
Max Error Tol= 0.3
Flow Tol Ratio= 0.001
Split Flow NTrial= 30
Split Flow Tol= 0.02
Split Flow Ratio= 0.02
Log Output Level= 0
Friction Slope Method= 1
Unsteady Friction Slope Method= 2
Unsteady Bridges Friction Slope Method= 1
Parabolic Critical Depth
Global Vel Dist=  1 , 1 , 1
Global Log Level= 0
CheckData=True
Encroach Param= -1, 0, 0, 0
BEGIN DESCRIPTION:
Multiple Run
END DESCRIPTION:

--- UNT 1 TO WEST FORK PANTHER CR.f01 (steady flow) ---

Flow Title=Multiple
Number of Profiles=7
Profile Names=10-year,25-year,50-year,1pct_min,100-year,1pct_plu,500-year
River Rch & RM= UNT 1 TO WEST FO,Reach-1,10753
     866    1186    1449    1293    1749    2365    2539
Boundary for River Rch & Prof#=UNT 1 TO WEST FO,Reach-1,1
Up Type=0
Dn Type=3
Dn Slope=0.005
Boundary for River Rch & Prof#=UNT 1 TO WEST FO,Reach-1,2
Up Type=0
Dn Type=3
Dn Slope=0.005
Boundary for River Rch & Prof#=UNT 1 TO WEST FO,Reach-1,3
Up Type=0
Dn Type=3
Dn Slope=0.005
Boundary for River Rch & Prof#=UNT 1 TO WEST FO,Reach-1,4
Up Type=0
Dn Type=3
Dn Slope=0.005
Boundary for River Rch & Prof#=UNT 1 TO WEST FO,Reach-1,5
Up Type=0
Dn Type=3
Dn Slope=0.005
Boundary for River Rch & Prof#=UNT 1 TO WEST FO,Reach-1,6
Up Type=0
Dn Type=3
Dn Slope=0.005
Boundary for River Rch & Prof#=UNT 1 TO WEST FO,Reach-1,7
Up Type=0
Dn Type=3
Dn Slope=0.005

--- UNT 1 TO WEST FORK PANTHER CR.g01 (geometry) ---

Geom Title=Existing Conditions

River Reach=UNT 1 TO WEST FO,Reach-1
Reach XY= 30
      3602748.92     10484603.08      3602704.36     10485368.41
      3602791.17     10485719.80      3603150.40     10486050.56
      3603137.38     10486480.25      3603216.35     10486629.61
      3603055.50     10486677.00      3603097.00     10486769.00
      3602976.25     10487039.00      3602424.75     10488116.00
      3602322.75     10488171.00      3602242.00     10488426.00
      3602239.50     10489353.00      3602589.75     10490600.00
      3602433.50     10490966.00      3602449.00     10491155.00
      3602345.50     10491234.00      3602455.25     10491383.00
      3602519.25     10491789.00      3602206.00     10492419.00
      3602082.50     10492482.00      3601922.75     10492742.00
      3601968.50     10493140.00      3601891.50     10493256.00
      3601916.75     10493369.00      3601835.50     10493359.00
      3601854.50     10493493.00      3601752.25     10493507.00
      3601654.00     10493873.00      3601509.50     10493860.00

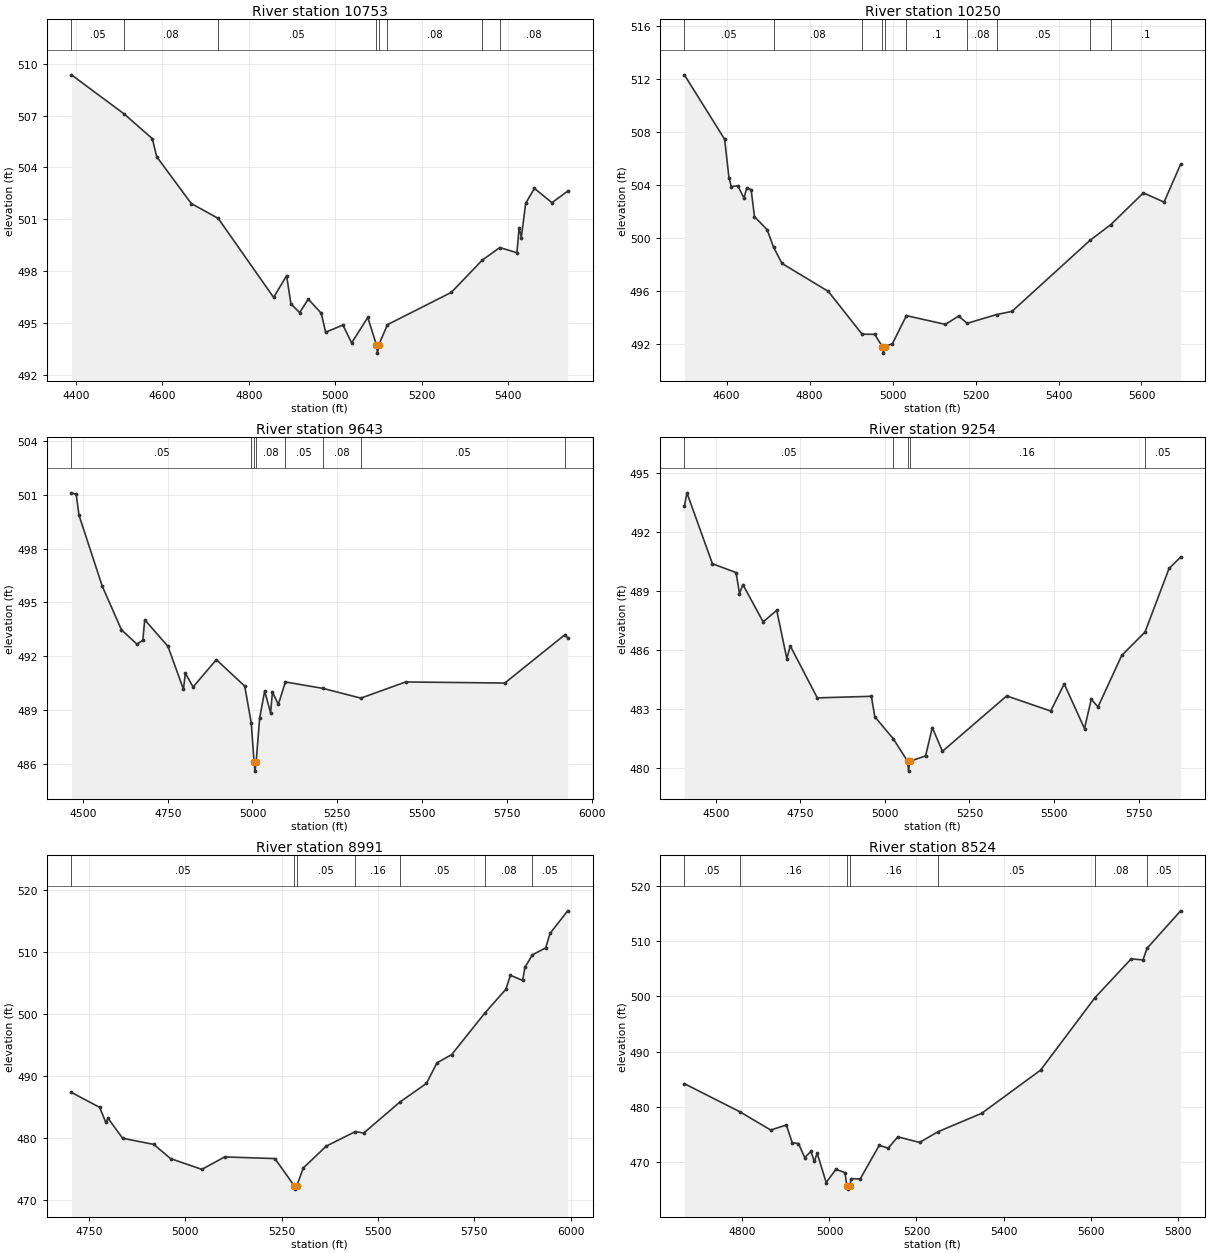
Type RM Length L Ch R = 1,10753,503,503,503
BEGIN DESCRIPTION:
UNT 1 TO WEST FORK PANTHER CR 22.0
END DESCRIPTION:
XS GIS Cut Line= 3
      3602123.02     10484839.02      3603008.39     10484769.57
      3603265.65     10484726.70
#Sta/Elev= 30
  4389.4  509.37  4511.5  507.10  4576.6  505.67  4586.6  504.63  4666.8  501.91
  4729.1  501.05  4857.4  496.47  4887.5  497.73  4897.5  496.09  4917.6  495.59
  4937.7  496.37  4967.8  495.55  4977.8  494.45  5017.9  494.87  5038.0  493.83
  5075.4  495.31  5095.2  493.74  5097.9  493.24  5101.2  493.74  5121.0  494.89
  5268.7  496.76  5340.5  498.63  5381.0  499.36  5420.7  499.06  5425.8  500.51
  5430.9  499.94  5440.9  501.92  5461.2  502.79  5501.8  501.96  5538.3  502.63
#Mann=8,-1,0
  4389.4    0.05       0  4511.5    0.08       0  4729.1    0.05       0
  5095.2    0.04       0  5101.2    0.05       0  5121.0    0.08       0
  5340.5     0.1       0  5381.0    0.08       0
Bank Sta=5095.2,5101.2
Exp/Cntr=0.3,0.1

Type RM Length L Ch R = 1,10250,607,607,607
BEGIN DESCRIPTION:
UNT 1 TO WEST FORK PANTHER CR 21.0
END DESCRIPTION:
XS GIS Cut Line= 3
      3602218.48     10485464.01      3603051.80     10485160.20
      3603295.91     10484970.55
#Sta/Elev= 30
  4498.2  512.34  4595.2  507.48  4605.8  504.55  4611.4  503.90  4627.1  503.97
  4641.9  503.03  4648.4  503.79  4659.1  503.68  4667.2  501.63  4697.7  500.65
  4713.1  499.33  4733.6  498.10  4845.2  495.99  4926.6  492.76  4956.8  492.75
  4975.4  491.83  4978.1  491.33  4981.4  491.83  4999.7  492.04  5033.4  494.16
  5127.4  493.50  5159.3  494.13  5179.8  493.58  5250.6  494.24  5287.7  494.48
  5476.1  499.85  5526.3  501.04  5604.6  503.43  5654.4  502.73  5694.3  505.59
#Mann=10,-1,0
  4498.2    0.05       0  4713.1    0.08       0  4926.6    0.05       0
  4975.4    0.04       0  4981.4    0.05       0  5033.4     0.1       0
  5179.8    0.08       0  5250.6    0.05       0  5476.1    0.08       0
  5526.3     0.1       0
Bank Sta=4975.4,4981.4
Exp/Cntr=0.3,0.1

Type RM Length L Ch R = 1,9643,389,389,389
BEGIN DESCRIPTION:
UNT 1 TO WEST FORK PANTHER CR 20.0
END DESCRIPTION:
XS GIS Cut Line= 3
      3602426.81     10486045.61      3603355.62     10485611.59
      3603778.91     10485499.09
#Sta/Elev= 30
  4466.3  501.10  4480.4  501.01  4488.4  499.86  4557.0  495.91  4613.7  493.48
  4659.4  492.68  4676.7  492.90  4682.3  494.04  4750.8  492.56  4796.5  490.17
  4802.0  491.07  4824.9  490.30  4893.4  491.82  4977.1  490.35  4996.4  488.30
  5004.7  486.12  5007.4  485.62  5010.7  486.12  5021.3  488.59  5036.0  490.08
  5053.4  488.86  5058.9  490.02  5076.2  489.33  5097.1  490.58  5208.3  490.22
  5319.5  489.68  5451.8  490.58  5744.0  490.52  5920.1  493.19  5929.5  493.04
#Mann=8,-1,0
  4466.3    0.05       0  4996.4    0.08       0  5004.7    0.07       0
  5010.7    0.08       0  5097.1    0.05       0  5208.3    0.08       0
  5319.5    0.05       0  5920.1    0.08       0
Bank Sta=5004.7,5010.7
Exp/Cntr=0.3,0.1

Type RM Length L Ch R = 1,9254,263,263,263
BEGIN DESCRIPTION:
Mapping XS b25b9f0d
END DESCRIPTION:
XS GIS Cut Line= 3
      3602576.63     10486085.02      3603327.54     10486102.38
      3604043.72     10486085.02
#Sta/Elev= 30
  4406.8  493.31  4414.4  494.00  4489.8  490.39  4559.8  489.94  4569.8  488.87
  4579.8  489.33  4639.8  487.43  4679.9  488.02  4709.9  485.55  4719.9  486.21
  4799.9  483.56  4959.9  483.64  4969.9  482.60  5025.0  481.47  5067.0  480.33
  5069.7  479.83  5073.0  480.33  5120.0  480.60  5140.0  482.05  5170.0  480.84
  5360.0  483.66  5490.1  482.89  5530.1  484.27  5590.1  482.00  5610.1  483.49
  5630.1  483.10  5700.1  485.72  5769.0  486.91  5840.2  490.15  5874.3  490.73
#Mann=5,-1,0
  4406.8    0.05       0  5025.0    0.16       0  5067.0    0.03       0
  5073.0    0.16       0  5769.0    0.05       0
Bank Sta=5067,5073
Exp/Cntr=0.3,0.1

Type RM Length L Ch R = 1,8991,467,467,467
BEGIN DESCRIPTION:
UNT 1 TO WEST FORK PANTHER CR 19.0
END DESCRIPTION:
XS GIS Cut Line= 3
      3602899.61     10486210.19      3603408.80     10486495.09
      3603749.62     10487110.20
#Sta/Elev= 30
  4705.3  487.36  4778.4  484.95  4794.4  482.52  4800.1  483.20  4837.8  479.98
  4918.8  478.98  4962.2  476.70  5043.3  474.96  5102.6  476.97  5232.8  476.70
  5283.4  472.28  5286.1  471.78  5289.4  472.28  5306.3  475.19  5365.8  478.70
  5441.6  481.06  5463.1  480.81  5556.3  485.78  5625.7  488.81  5653.1  492.13
  5690.9  493.44  5777.2  500.15  5831.7  503.98  5843.4  506.23  5875.2  505.39
  5880.9  507.50  5900.3  509.52  5934.8  510.64  5946.3  512.99  5992.0  516.61
#Mann=7,-1,0
  4705.3    0.05       0  5283.4    0.03       0  5289.4    0.05       0
  5441.6    0.16       0  5556.3    0.05       0  5777.2    0.08       0
  5900.3    0.05       0
Bank Sta=5283.4,5289.4
Exp/Cntr=0.3,0.1

Type RM Length L Ch R = 1,8524,469,469,469
BEGIN DESCRIPTION:
UNT 1 TO WEST FORK PANTHER CR 18.0
END DESCRIPTION:
XS GIS Cut Line= 3
      3602849.63     10486410.21      3603099.61     10486710.19
      3603699.63     10487160.20
#Sta/Elev= 30
  4666.5  484.20  4793.9  479.11  4865.0  475.79  4900.8  476.71  4914.4  473.51
  4928.8  473.34  4943.1  470.80  4957.4  471.92  4965.2  470.10  4971.7  471.59
  4992.5  466.27  5014.7  468.67  5035.5  468.08  5040.3  465.58  5043.1  465.08
  5046.3  465.58  5049.8  466.98  5070.5  466.91  5114.3  473.01  5135.1  472.51
  5157.0  474.56  5207.0  473.55  5249.8  475.50  5349.7  478.82  5485.1  486.65
  5609.9  499.76  5693.4  506.82  5720.5  506.63  5729.9  508.74  5807.0  515.53
#Mann=7,-1,0
  4666.5    0.05       0  4793.9    0.16       0  5040.3    0.07       0
  5046.3    0.16       0  5249.8    0.05       0  5609.9    0.08       0
  5729.9    0.05       0
Bank Sta=5040.3,5046.3
Exp/Cntr=0.3,0.1

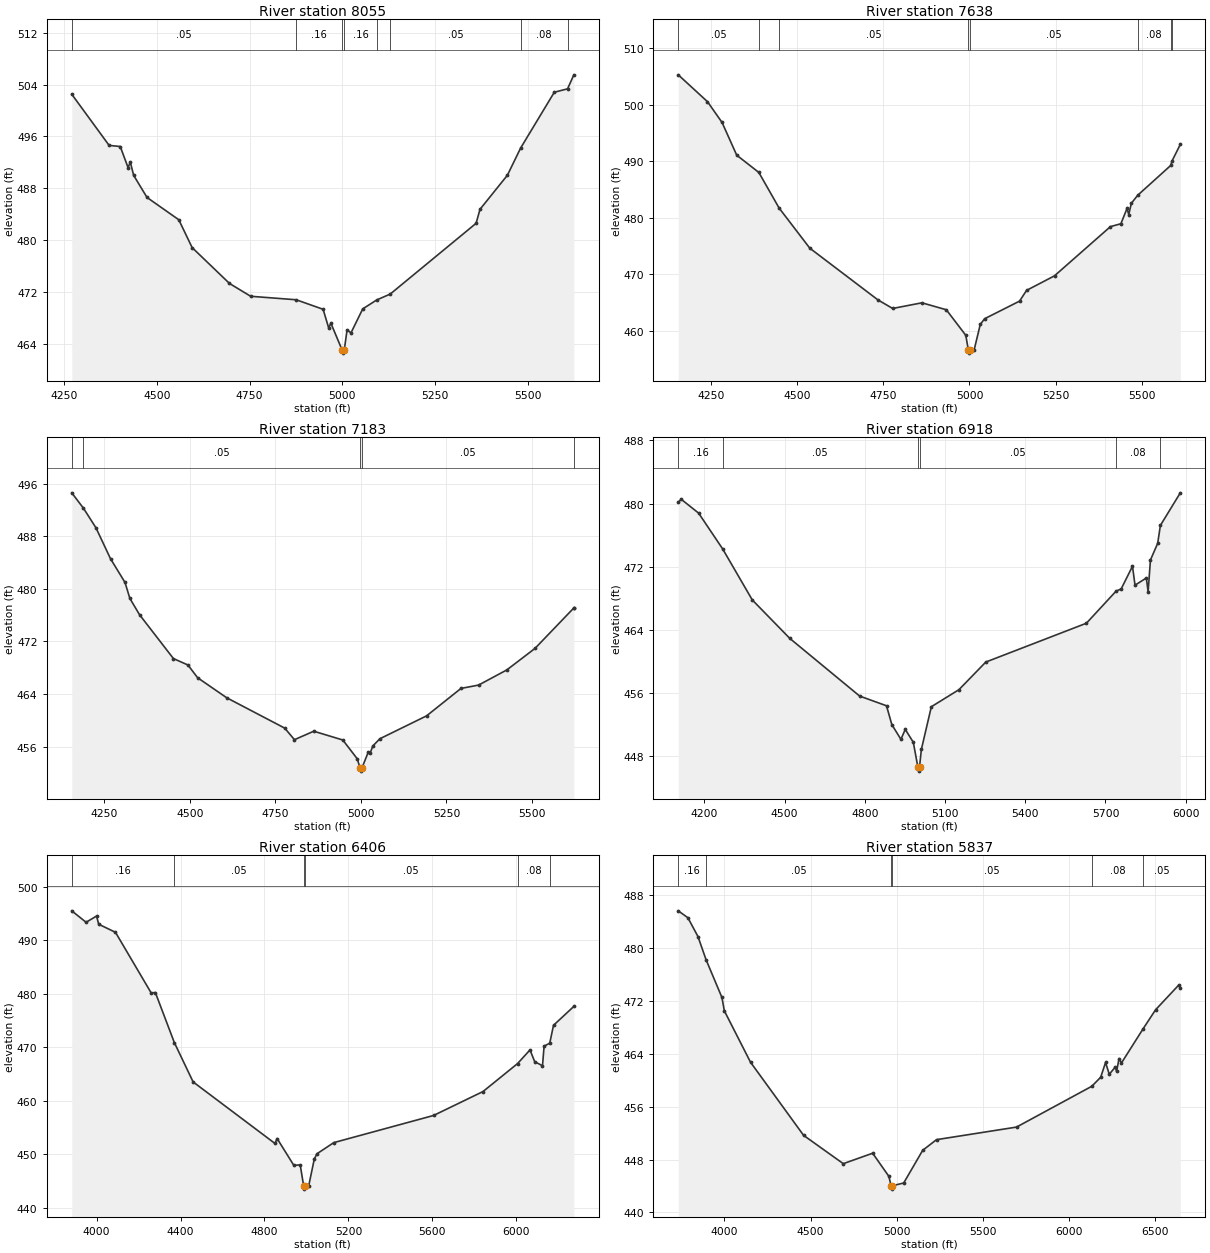
Type RM Length L Ch R = 1,8055,417,417,417
BEGIN DESCRIPTION:
UNT 1 TO WEST FORK PANTHER CR 17.0
END DESCRIPTION:
XS GIS Cut Line= 3
      3602349.57     10486660.16      3602949.61     10487060.19
      3603549.60     10487260.19
#Sta/Elev= 30
  4270.4  502.51  4371.1  494.61  4401.1  494.44  4422.2  491.18  4428.2  492.04
  4437.2  489.99  4473.3  486.57  4558.9  483.13  4594.9  478.83  4695.6  473.29
  4752.7  471.31  4875.5  470.77  4948.0  469.30  4963.0  466.43  4969.0  467.15
  4999.1  463.03  5001.8  462.53  5005.1  463.03  5012.6  466.11  5023.2  465.66
  5054.8  469.36  5092.8  470.75  5128.9  471.65  5360.5  482.58  5371.0  484.74
  5444.8  490.00  5480.5  494.20  5571.3  502.82  5607.1  503.35  5624.0  505.51
#Mann=8,-1,0
  4270.4    0.05       0  4875.5    0.16       0  4999.1    0.07       0
  5005.1    0.16       0  5092.8    0.08       0  5128.9    0.05       0
  5480.5    0.08       0  5607.1    0.05       0
Bank Sta=4999.1,5005.1
Exp/Cntr=0.3,0.1

Type RM Length L Ch R = 1,7638,455,455,455
BEGIN DESCRIPTION:
UNT 1 TO WEST FORK PANTHER CR 16.0
END DESCRIPTION:
XS GIS Cut Line= 3
      3602149.64     10486810.22      3602749.61     10487410.19
      3603349.64     10487510.19
#Sta/Elev= 30
  4155.0  505.29  4239.8  500.54  4282.2  496.85  4324.7  491.06  4388.8  488.01
  4447.7  481.70  4536.8  474.59  4734.8  465.42  4777.2  463.92  4862.1  464.92
  4932.8  463.69  4989.3  459.17  4997.0  456.51  4999.7  456.01  5003.0  456.51
  5013.6  456.58  5031.4  461.10  5044.0  462.10  5145.4  465.22  5165.7  467.12
  5246.8  469.70  5409.0  478.41  5439.4  478.92  5457.2  481.63  5462.2  480.55
  5469.8  482.55  5488.3  483.97  5583.9  489.24  5587.9  490.05  5611.8  492.97
#Mann=8,-1,0
  4155.0    0.05       0  4388.8     0.1       0  4447.7    0.05       0
  4997.0    0.03       0  5003.0    0.05       0  5488.3    0.08       0
  5583.9     0.1       0  5587.9    0.05       0
Bank Sta=4997,5003
Exp/Cntr=0.3,0.1

Type RM Length L Ch R = 1,7183,265,265,265
BEGIN DESCRIPTION:
UNT 1 TO WEST FORK PANTHER CR 15.0
END DESCRIPTION:
XS GIS Cut Line= 3
      3601949.60     10487210.18      3602549.61     10487810.19
      3603149.60     10487660.19
#Sta/Elev= 30
  4155.4  494.65  4189.6  492.30  4226.1  489.32  4268.6  484.61  4311.0  480.99
  4325.1  478.57  4353.4  476.08  4452.4  469.40  4494.8  468.42  4523.1  466.48
  4608.0  463.43  4777.7  458.80  4806.0  457.04  4862.5  458.33  4947.4  456.99
  4989.8  454.11  4997.4  452.75  5000.2  452.25  5003.4  452.75  5022.0  455.18
  5027.1  454.96  5034.9  456.07  5055.5  457.18  5192.1  460.67  5292.6  464.85
  5344.1  465.36  5426.6  467.67  5509.0  470.95  5621.8  477.08  5622.4  477.08
#Mann=5,-1,0
  4155.4    0.16       0  4189.6    0.05       0  4997.4    0.03       0
  5003.4    0.05       0  5621.8    0.08       0
Bank Sta=4997.4,5003.4
Exp/Cntr=0.3,0.1

Type RM Length L Ch R = 1,6918,512,512,512
BEGIN DESCRIPTION:
UNT 1 TO WEST FORK PANTHER CR 14.0
END DESCRIPTION:
XS GIS Cut Line= 3
      3601553.69     10487974.26      3603074.48     10488104.47
      3603371.37     10487916.96
#Sta/Elev= 30
  4102.4  480.14  4113.3  480.55  4178.6  478.79  4268.4  474.26  4379.3  467.79
  4519.8  462.91  4780.8  455.61  4881.2  454.38  4901.2  451.99  4935.1  450.13
  4951.4  451.39  4981.5  449.75  4998.6  446.60  5001.3  446.10  5004.6  446.60
  5011.6  448.85  5048.9  454.26  5152.1  456.42  5252.5  459.92  5628.8  464.84
  5739.6  468.90  5758.8  469.19  5801.1  472.06  5810.5  469.66  5852.9  470.57
  5859.5  468.82  5868.2  472.85  5895.3  474.96  5905.4  477.23  5979.9  481.36
#Mann=6,-1,0
  4102.4    0.16       0  4268.4    0.05       0  4998.6    0.03       0
  5004.6    0.05       0  5739.6    0.08       0  5905.4    0.05       0
Bank Sta=4998.6,5004.6
Exp/Cntr=0.3,0.1

Type RM Length L Ch R = 1,6406,569,569,569
BEGIN DESCRIPTION:
UNT 1 TO WEST FORK PANTHER CR 13.0
END DESCRIPTION:
XS GIS Cut Line= 3
      3601121.39     10488453.43      3602506.78     10488479.47
      3603406.22     10488027.15
#Sta/Elev= 30
  3881.9  495.48  3950.1  493.34  4000.1  494.51  4010.1  492.98  4090.2  491.47
  4260.2  480.16  4280.2  480.23  4370.5  470.90  4460.2  463.54  4850.3  452.05
  4860.3  452.98  4940.3  447.95  4970.3  448.07  4987.3  444.03  4990.1  443.53
  4993.3  444.03  5010.3  444.03  5037.5  449.14  5050.3  450.13  5130.3  452.21
  5605.9  457.28  5841.6  461.75  6006.2  466.97  6065.4  469.52  6087.8  467.32
  6124.9  466.56  6132.6  470.22  6159.4  470.77  6177.4  474.11  6274.3  477.64
#Mann=6,-1,0
  3881.9    0.16       0  4370.5    0.05       0  4987.3    0.03       0
  4993.3    0.05       0  6006.2    0.08       0  6159.4    0.05       0
Bank Sta=4987.3,4993.3
Exp/Cntr=0.3,0.1

Type RM Length L Ch R = 1,5837,469,469,469
BEGIN DESCRIPTION:
UNT 1 TO WEST FORK PANTHER CR 12.0
END DESCRIPTION:
XS GIS Cut Line= 4
      3601058.82     10488755.49      3601600.53     10489073.22
      3602590.11     10489026.34      3603538.05     10488146.11
#Sta/Elev= 30
  3732.3  485.61  3788.2  484.57  3846.8  481.72  3893.4  478.24  3985.6  472.52
  3999.9  470.48  4151.6  462.72  4459.5  451.66  4689.8  447.38  4860.0  448.96
  4953.9  445.47  4967.1  444.03  4969.8  443.53  4973.1  444.03  5040.2  444.46
  5150.3  449.40  5230.4  451.01  5694.5  452.91  6131.1  459.08  6182.8  460.45
  6211.0  462.68  6232.5  460.90  6267.7  461.99  6275.0  461.33  6289.2  463.28
  6303.3  462.61  6428.9  467.78  6501.2  470.65  6635.6  474.39  6644.6  473.89
#Mann=6,-1,0
  3732.3    0.16       0  3893.4    0.05       0  4967.1    0.03       0
  4973.1    0.05       0  6131.1    0.08       0  6428.9    0.05       0
Bank Sta=4967.1,4973.1
Exp/Cntr=0.3,0.1

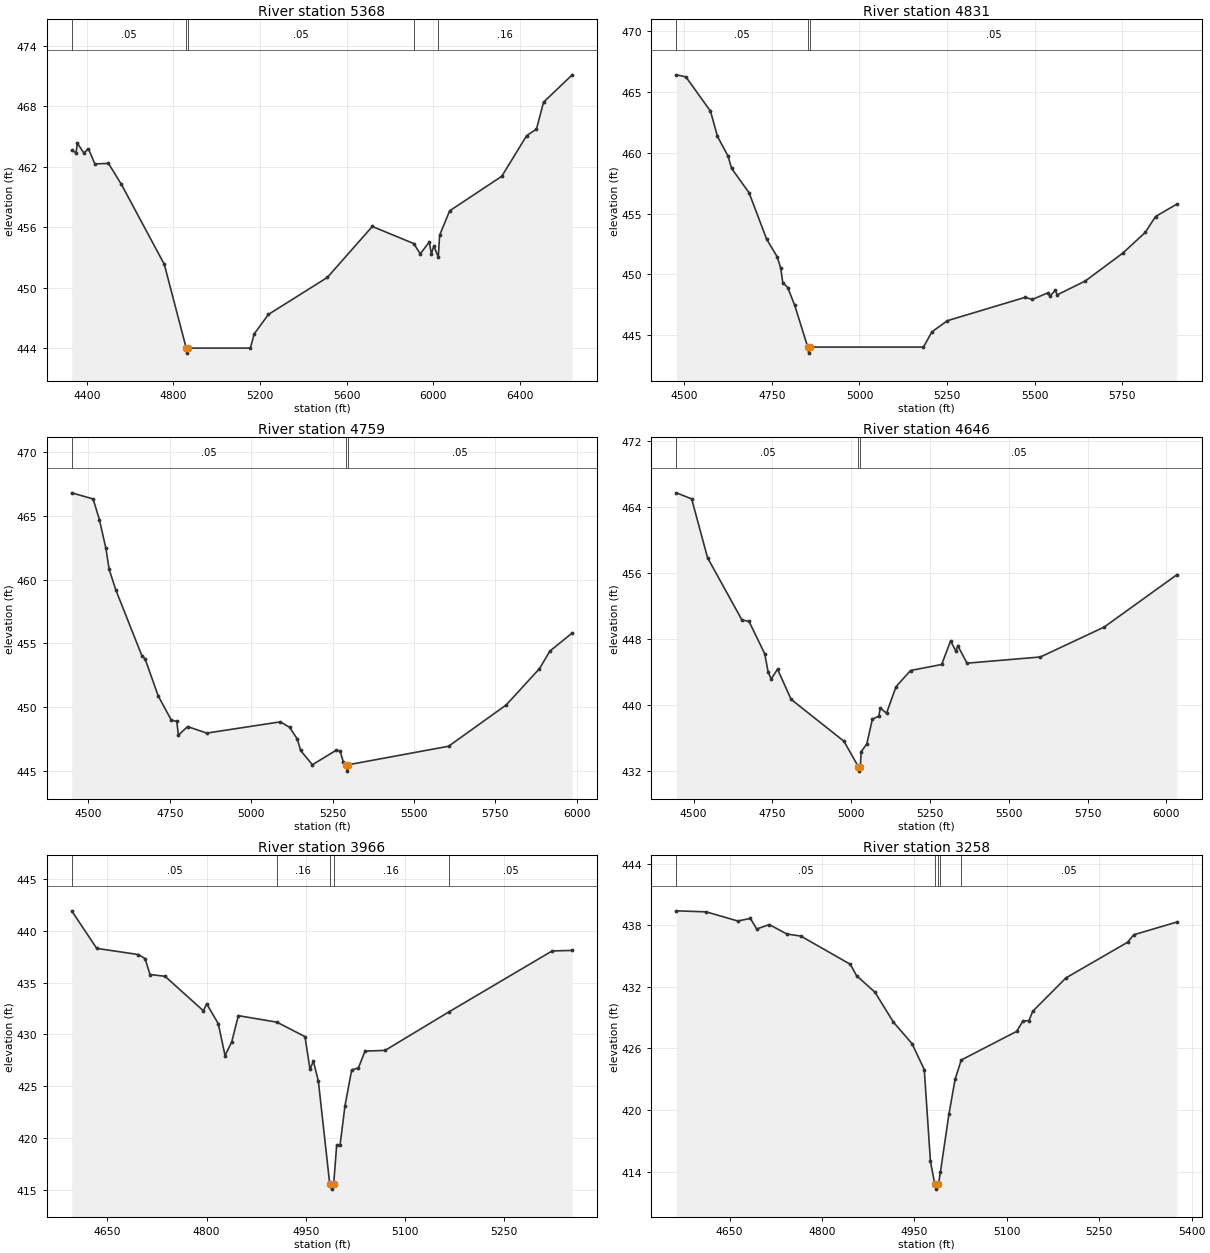
Type RM Length L Ch R = 1,5368,537,537,537
BEGIN DESCRIPTION:
UNT 1 TO WEST FORK PANTHER CR 11.0
END DESCRIPTION:
XS GIS Cut Line= 3
      3601772.38     10489880.54      3601959.90     10489604.47
      3603850.55     10489026.34
#Sta/Elev= 30
  4330.2  463.61  4350.4  463.39  4356.4  464.33  4386.3  463.35  4407.3  463.78
  4437.2  462.28  4500.1  462.32  4559.9  460.24  4757.7  452.33  4858.9  444.03
  4861.6  443.53  4864.9  444.03  5155.1  444.03  5172.6  445.43  5238.2  447.36
  5510.6  451.03  5718.1  456.08  5909.7  454.38  5939.4  453.36  5981.2  454.54
  5990.8  453.35  6002.1  454.15  6022.8  453.04  6028.8  455.21  6075.3  457.63
  6315.8  461.05  6430.9  465.08  6475.9  465.72  6508.7  468.39  6641.0  471.10
#Mann=5,-1,0
  4330.2    0.05       0  4858.9    0.03       0  4864.9    0.05       0
  5909.7    0.08       0  6022.8    0.16       0
Bank Sta=4858.9,4864.9
Exp/Cntr=0.3,0.1

Type RM Length L Ch R = 1,4831,72,72,72
BEGIN DESCRIPTION:
UNT 1 TO WEST FORK PANTHER CR 10.0
END DESCRIPTION:
XS GIS Cut Line= 6
      3601872.63     10490038.50      3602267.63     10490060.20
      3602356.60     10490047.18      3602484.64     10489975.56
      3602577.96     10489947.35      3602989.51     10489384.17
#Sta/Elev= 30
  4477.8  466.43  4504.8  466.26  4574.9  463.44  4594.9  461.36  4625.0  459.74
  4635.0  458.74  4685.1  456.72  4735.2  452.90  4765.2  451.46  4775.2  450.54
  4781.2  449.34  4795.3  448.93  4815.3  447.46  4852.4  444.03  4855.1  443.53
  4858.4  444.03  5182.6  444.03  5206.6  445.28  5250.9  446.20  5472.5  448.12
  5493.4  447.95  5537.4  448.49  5543.6  448.20  5558.2  448.70  5564.4  448.33
  5644.0  449.46  5750.5  451.74  5815.4  453.46  5844.7  454.77  5905.9  455.80
#Mann=3,-1,0
  4477.8    0.05       0  4852.4    0.03       0  4858.4    0.05       0
Bank Sta=4852.4,4858.4
Exp/Cntr=0.3,0.1

Type RM Length L Ch R = 1,4759,113,113,113
BEGIN DESCRIPTION:
UNT 1 TO WEST FORK PANTHER CR 9.0
END DESCRIPTION:
XS GIS Cut Line= 6
      3601874.83     10490090.58      3602332.73     10490129.64
      3602473.79     10490077.56      3602521.53     10490034.16
      3602662.59     10490025.48      3603005.45     10489391.84
#Sta/Elev= 30
  4449.1  466.79  4514.8  466.31  4534.1  464.70  4554.2  462.43  4564.2  460.79
  4584.3  459.20  4664.5  454.04  4674.5  453.78  4714.6  450.89  4754.7  449.00
  4771.8  448.88  4776.8  447.81  4805.0  448.48  4863.7  447.97  5089.8  448.85
  5118.2  448.42  5141.9  447.50  5151.9  446.61  5188.0  445.49  5261.5  446.63
  5273.4  446.57  5282.8  445.72  5292.3  445.49  5295.0  444.99  5298.3  445.49
  5606.4  446.94  5783.1  450.17  5885.4  453.02  5917.5  454.40  5985.9  455.81
#Mann=3,-1,0
  4449.1    0.05       0  5292.3    0.03       0  5298.3    0.05       0
Bank Sta=5292.3,5298.3
Exp/Cntr=0.3,0.1

Type RM Length L Ch R = 1,4646,680,680,680
BEGIN DESCRIPTION:
Mapping XS a75f9a5c
END DESCRIPTION:
XS GIS Cut Line= 6
      3601911.77     10490147.01      3602282.82     10490196.92
      3602378.30     10490205.60      3602473.79     10490201.26
      3602660.42     10490131.81      3603015.48     10489389.22
#Sta/Elev= 30
  4445.8  465.75  4494.1  465.01  4544.5  457.87  4653.8  450.31  4675.7  450.17
  4726.1  446.21  4736.7  444.00  4746.3  443.16  4766.5  444.35  4809.6  440.69
  4977.4  435.60  5023.4  432.48  5026.1  431.98  5029.4  432.48  5031.7  434.33
  5049.7  435.28  5067.5  438.28  5087.4  438.65  5092.8  439.63  5112.3  439.01
  5142.5  442.23  5188.6  444.19  5287.3  444.92  5315.6  447.78  5332.7  446.52
  5338.2  447.21  5367.8  445.08  5600.5  445.83  5802.8  449.46  6033.9  455.82
#Mann=3,-1,0
  4445.8    0.05       0  5023.4    0.03       0  5029.4    0.05       0
Bank Sta=5023.4,5029.4
Exp/Cntr=0.3,0.1

Type RM Length L Ch R = 1,3966,708,708,708
BEGIN DESCRIPTION:
UNT 1 TO WEST FORK PANTHER CR 8.0
END DESCRIPTION:
XS GIS Cut Line= 3
      3602099.59     10490760.19      3602499.61     10490810.19
      3602849.62     10490860.19
#Sta/Elev= 30
  4596.0  441.96  4633.8  438.33  4696.8  437.73  4706.9  437.34  4714.4  435.80
  4737.1  435.63  4795.1  432.29  4800.1  432.96  4817.7  431.03  4827.8  427.96
  4837.9  429.28  4848.0  431.82  4906.3  431.19  4948.7  429.79  4956.3  426.62
  4961.3  427.43  4968.9  425.50  4986.1  415.54  4988.8  415.04  4992.1  415.54
  4996.6  419.29  5001.7  419.29  5009.2  423.12  5019.3  426.57  5029.4  426.76
  5039.5  428.39  5069.8  428.46  5165.9  432.17  5322.4  438.08  5352.7  438.13
#Mann=5,-1,0
  4596.0    0.05       0  4906.3    0.16       0  4986.1    0.07       0
  4992.1    0.16       0  5165.9    0.05       0
Bank Sta=4986.1,4992.1
Exp/Cntr=0.3,0.1

Type RM Length L Ch R = 1,3258,404,404,404
BEGIN DESCRIPTION:
UNT 1 TO WEST FORK PANTHER CR 7.0
END DESCRIPTION:
XS GIS Cut Line= 3
      3602022.39     10491336.24      3602230.73     10491381.81
      3602829.67     10491370.96
#Sta/Elev= 30
  4563.9  439.40  4612.2  439.30  4663.4  438.41  4683.9  438.66  4694.1  437.63
  4714.6  438.06  4743.2  437.14  4765.8  436.94  4846.1  434.19  4856.1  433.09
  4886.1  431.47  4916.1  428.55  4946.1  426.47  4966.1  423.94  4976.1  414.99
  4983.1  412.79  4985.8  412.29  4989.1  412.79  4992.2  413.91  5006.1  419.59
  5016.1  422.99  5026.1  424.87  5116.1  427.66  5126.1  428.66  5136.1  428.71
  5142.0  429.61  5196.1  432.87  5296.1  436.34  5306.1  437.07  5376.2  438.31
#Mann=5,-1,0
  4563.9    0.05       0  4983.1    0.07       0  4989.1    0.05       0
  4992.2    0.16       0  5026.1    0.05       0
Bank Sta=4983.1,4989.1
Exp/Cntr=0.3,0.1

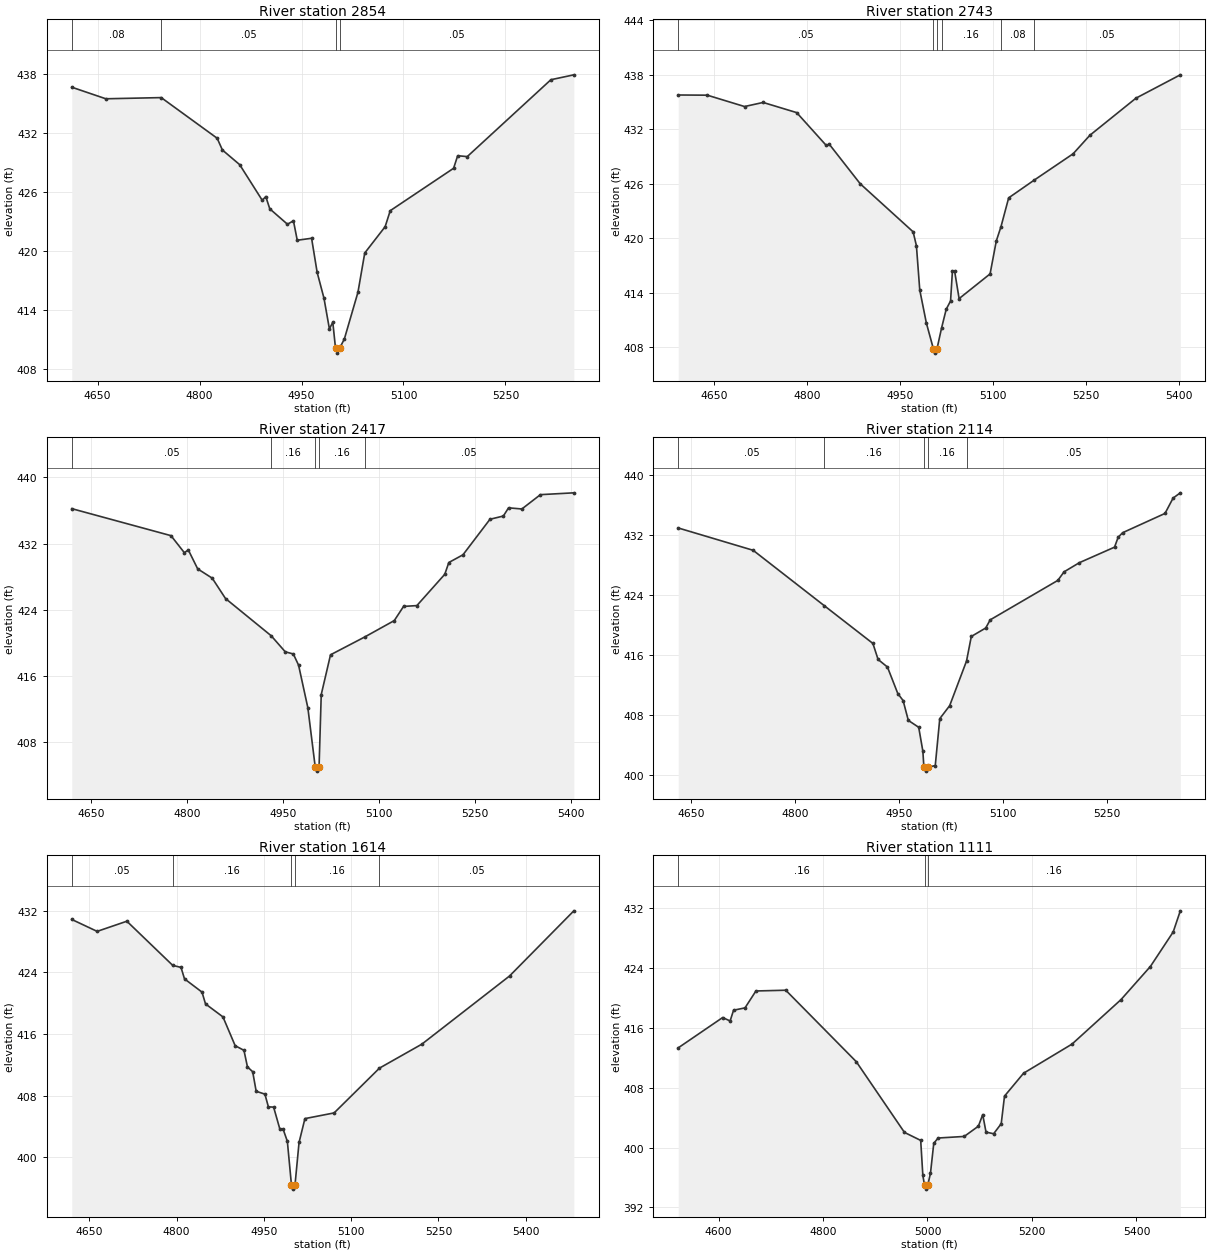
Type RM Length L Ch R = 1,2854,111,111,111
BEGIN DESCRIPTION:
UNT 1 TO WEST FORK PANTHER CR 6.0
END DESCRIPTION:
XS GIS Cut Line= 6
      3602139.54     10491724.70      3602326.22     10491718.18
      3602478.13     10491774.61      3602599.66     10491776.78
      3602745.06     10491759.42      3602862.29     10491729.02
#Sta/Elev= 30
  4612.0  436.66  4662.1  435.48  4743.6  435.60  4825.9  431.46  4833.6  430.26
  4859.0  428.77  4892.2  425.14  4897.4  425.52  4903.3  424.27  4929.3  422.70
  4938.1  423.05  4943.7  421.07  4964.8  421.27  4973.0  417.79  4983.0  415.17
  4991.0  412.04  4996.0  412.72  5000.0  410.07  5002.7  409.57  5006.0  410.07
  5013.0  411.01  5033.0  415.77  5043.0  419.77  5073.0  422.45  5080.5  424.08
  5173.7  428.40  5179.7  429.68  5193.8  429.59  5316.8  437.42  5350.6  437.92
#Mann=4,-1,0
  4612.0    0.08       0  4743.6    0.05       0  5000.0    0.03       0
  5006.0    0.05       0
Bank Sta=5000,5006
Exp/Cntr=0.3,0.1

Type RM Length L Ch R = 1,2743,326,326,326
BEGIN DESCRIPTION:
UNT 1 TO WEST FORK PANTHER CR 5.0
END DESCRIPTION:
XS GIS Cut Line= 5
      3602102.71     10491815.84      3602293.67     10491807.16
      3602530.21     10491896.14      3602699.48     10491889.63
      3602892.60     10491850.57
#Sta/Elev= 30
  4591.6  435.76  4638.5  435.74  4698.6  434.49  4728.6  434.94  4782.8  433.82
  4830.2  430.23  4835.6  430.32  4885.3  425.99  4970.7  420.70  4976.0  419.17
  4981.4  414.29  4992.1  410.65  5003.3  407.85  5006.0  407.35  5009.3  407.85
  5016.5  410.09  5024.1  412.18  5031.1  413.09  5034.1  416.36  5037.7  416.36
  5044.9  413.35  5094.9  416.07  5104.9  419.69  5112.5  421.27  5124.9  424.44
  5165.2  426.35  5228.9  429.29  5256.0  431.33  5330.3  435.41  5401.9  437.98
#Mann=6,-1,0
  4591.6    0.05       0  5003.3    0.04       0  5009.3    0.05       0
  5016.5    0.16       0  5112.5    0.08       0  5165.2    0.05       0
Bank Sta=5003.3,5009.3
Exp/Cntr=0.3,0.1

Type RM Length L Ch R = 1,2417,303,303,303
BEGIN DESCRIPTION:
Mapping XS 0ab920f6
END DESCRIPTION:
XS GIS Cut Line= 2
      3602035.40     10491917.82      3602656.82     10492396.33
#Sta/Elev= 30
  4619.7  436.21  4774.7  432.95  4795.5  430.90  4801.8  431.22  4816.4  428.94
  4839.1  427.82  4859.9  425.36  4931.2  420.87  4953.2  418.93  4965.8  418.67
  4974.0  417.32  4988.5  412.17  5000.0  405.03  5002.8  404.53  5006.0  405.03
  5009.4  413.77  5023.9  418.57  5077.3  420.72  5123.5  422.70  5138.0  424.41
  5158.8  424.51  5202.4  428.29  5208.7  429.71  5230.8  430.64  5273.0  434.93
  5293.9  435.32  5302.0  436.31  5322.8  436.17  5351.8  437.90  5404.0  438.12
#Mann=5,-1,0
  4619.7    0.05       0  4931.2    0.16       0  5000.0    0.07       0
  5006.0    0.16       0  5077.3    0.05       0
Bank Sta=5000,5006
Exp/Cntr=0.3,0.1

Type RM Length L Ch R = 1,2114,500,500,500
BEGIN DESCRIPTION:
UNT 1 TO WEST FORK PANTHER CR 4.0
END DESCRIPTION:
XS GIS Cut Line= 3
      3601999.63     10492110.22      3602199.61     10492410.19
      3602549.59     10492510.18
#Sta/Elev= 30
  4630.9  432.98  4739.0  430.00  4841.9  422.59  4911.8  417.57  4919.3  415.43
  4932.8  414.42  4947.8  410.87  4955.4  409.95  4962.9  407.30  4977.9  406.38
  4983.9  403.19  4985.4  401.03  4988.2  400.53  4991.4  401.03  5001.8  401.28
  5008.3  407.53  5022.6  409.27  5046.9  415.22  5053.8  418.50  5074.6  419.63
  5081.1  420.72  5178.6  425.98  5187.7  427.13  5209.8  428.35  5260.5  430.42
  5265.7  431.74  5272.2  432.35  5333.3  434.92  5345.0  436.97  5355.4  437.67
#Mann=5,-1,0
  4630.9    0.05       0  4841.9    0.16       0  4985.4    0.07       0
  4991.4    0.16       0  5046.9    0.05       0
Bank Sta=4985.4,4991.4
Exp/Cntr=0.3,0.1

Type RM Length L Ch R = 1,1614,503,503,503
BEGIN DESCRIPTION:
UNT 1 TO WEST FORK PANTHER CR 3.0
END DESCRIPTION:
XS GIS Cut Line= 3
      3601699.61     10492460.18      3601899.61     10492760.19
      3602399.65     10492810.19
#Sta/Elev= 30
  4619.7  430.88  4663.3  429.33  4714.4  430.65  4793.3  424.91  4807.5  424.65
  4813.5  423.16  4843.6  421.44  4849.6  419.91  4879.6  418.22  4900.6  414.48
  4915.7  413.88  4921.7  411.73  4930.7  411.10  4936.7  408.56  4951.7  408.19
  4957.7  406.54  4966.7  406.50  4977.3  403.68  4982.8  403.68  4990.3  402.06
  4997.4  396.35  5000.1  395.85  5003.4  396.35  5010.4  401.91  5020.5  405.01
  5070.7  405.75  5148.7  411.57  5221.5  414.68  5372.2  423.53  5482.8  432.00
#Mann=5,-1,0
  4619.7    0.05       0  4793.3    0.16       0  4997.4    0.07       0
  5003.4    0.16       0  5148.7    0.05       0
Bank Sta=4997.4,5003.4
Exp/Cntr=0.3,0.1

Type RM Length L Ch R = 1,1111,535,535,535
BEGIN DESCRIPTION:
UNT 1 TO WEST FORK PANTHER CR 2.0
END DESCRIPTION:
XS GIS Cut Line= 3
      3601599.63     10492860.21      3601899.61     10493210.19
      3602299.65     10493510.22
#Sta/Elev= 30
  4522.9  413.32  4607.9  417.37  4622.2  416.91  4628.8  418.35  4650.7  418.66
  4671.6  420.92  4728.7  421.02  4863.7  411.47  4955.9  402.02  4987.0  400.95
  4991.1  396.27  4994.4  394.94  4997.1  394.44  5000.4  394.94  5005.7  396.56
  5012.0  400.56  5020.3  401.27  5070.3  401.48  5097.4  402.85  5105.7  404.40
  5112.0  402.06  5126.6  401.84  5141.1  403.18  5147.4  406.87  5183.9  409.93
  5276.6  413.82  5370.3  419.76  5426.6  424.19  5470.3  428.81  5483.9  431.63
#Mann=3,-1,0
  4522.9    0.16       0  4994.4    0.07       0  5000.4    0.16       0
Bank Sta=4994.4,5000.4
Exp/Cntr=0.3,0.1

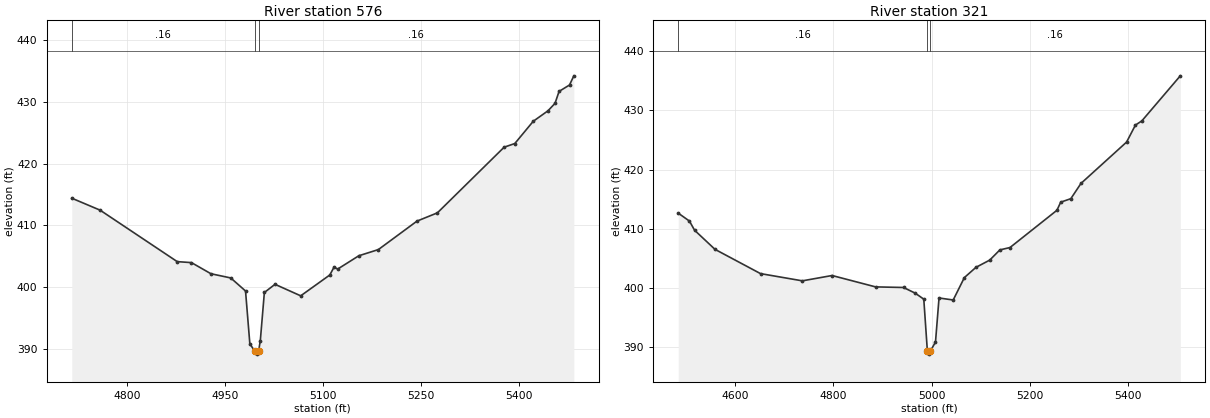
Type RM Length L Ch R = 1,576,255,255,255
BEGIN DESCRIPTION:
Mapping XS 3102fd0d
END DESCRIPTION:
XS GIS Cut Line= 3
      3601707.73     10493267.67      3601690.37     10493484.68
      3602185.56     10493724.71
#Sta/Elev= 30
  4715.9  414.39  4759.3  412.45  4877.2  404.13  4899.0  403.97  4928.8  402.17
  4959.1  401.49  4981.7  399.38  4988.3  390.84  4995.7  389.67  4998.5  389.17
  5001.7  389.67  5004.3  391.34  5010.5  399.14  5026.8  400.46  5066.1  398.60
  5110.6  401.97  5117.1  403.24  5122.7  402.93  5155.0  405.08  5184.9  406.08
  5243.9  410.68  5275.2  412.02  5377.3  422.64  5393.6  423.23  5421.8  426.83
  5444.3  428.52  5455.1  429.73  5461.3  431.66  5477.3  432.70  5483.9  434.18
#Mann=3,-1,0
  4715.9    0.16       0  4995.7    0.07       0  5001.7    0.16       0
Bank Sta=4995.7,5001.7
Exp/Cntr=0.3,0.1

Type RM Length L Ch R = 1,321,0,0,0
BEGIN DESCRIPTION:
UNT 1 TO WEST FORK PANTHER CR 1.0
END DESCRIPTION:
XS GIS Cut Line= 3
      3601679.18     10493308.13      3601575.00     10493696.18
      3602175.50     10493846.84
#Sta/Elev= 30
  4484.7  412.65  4507.5  411.31  4517.9  409.77  4559.3  406.55  4652.0  402.45
  4737.1  401.23  4797.5  402.13  4886.0  400.21  4942.8  400.11  4966.6  399.15
  4984.0  398.14  4991.3  389.37  4994.1  388.87  4997.3  389.37  5007.8  390.91
  5015.0  398.34  5043.8  398.00  5066.5  401.78  5090.1  403.51  5118.1  404.73
  5138.7  406.45  5159.3  406.85  5254.7  413.13  5262.4  414.50  5283.0  415.09
  5303.6  417.66  5396.4  424.64  5414.3  427.50  5427.4  428.21  5505.6  435.81
#Mann=3,-1,0
  4484.7    0.16       0  4991.3    0.07       0  4997.3    0.16       0
Bank Sta=4991.3,4997.3
Exp/Cntr=0.3,0.1

Chan Stop Cuts=-1