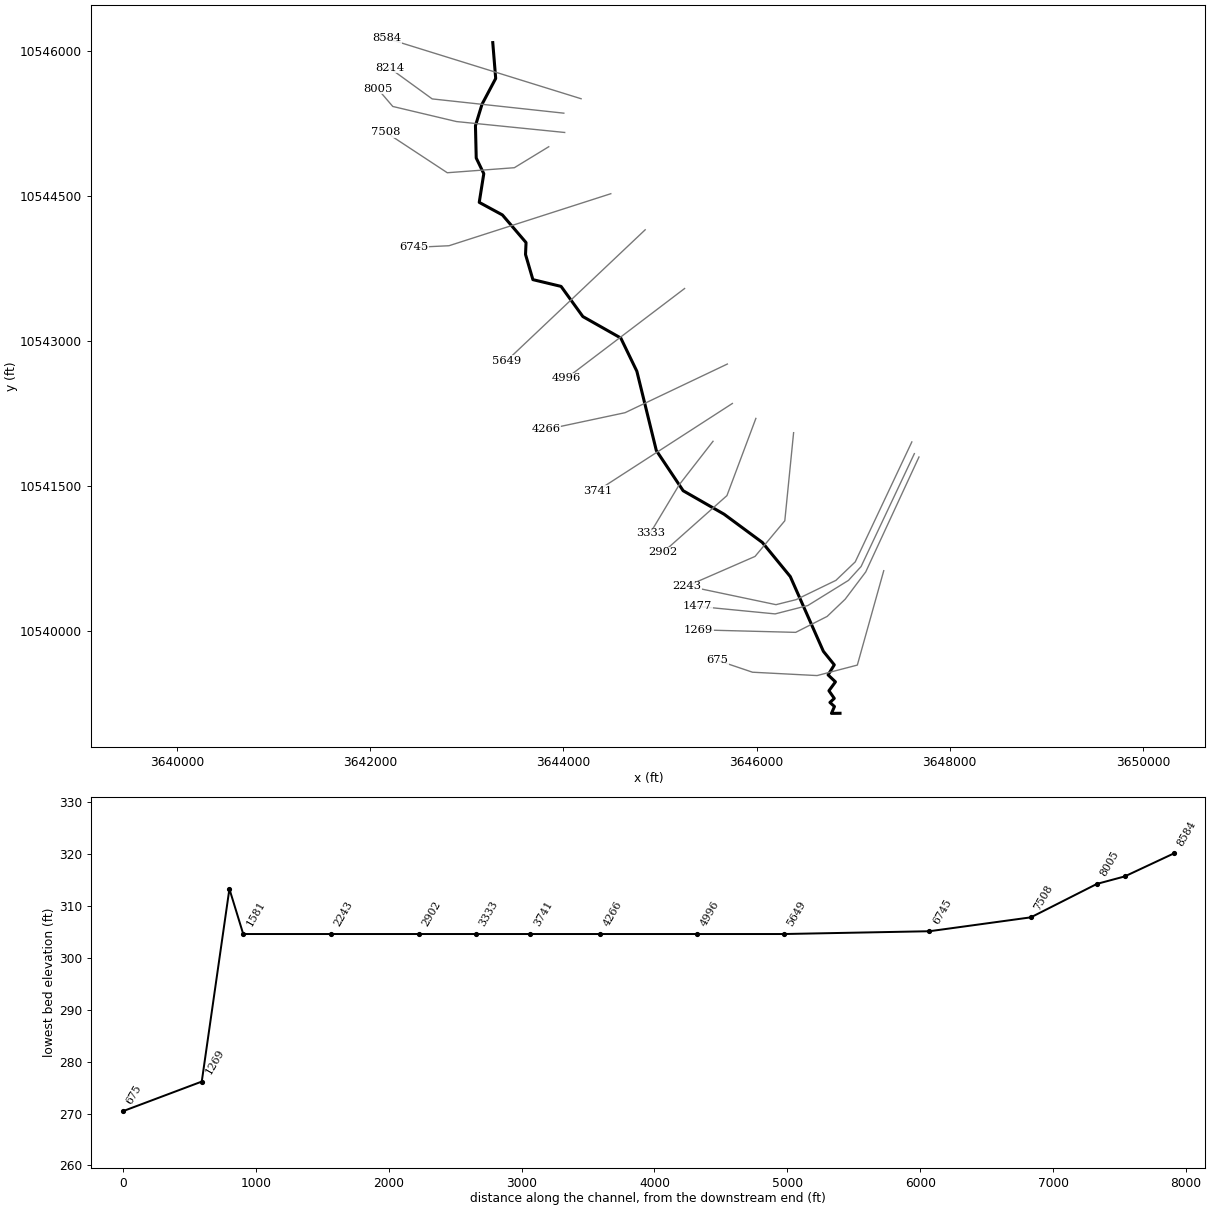
--- UNT 103 IN BUCR.prj (project) ---

Proj Title=UNT 103 IN BUCR Base Level Engineering
Current Plan=p01
Default Exp/Contr=0.3,0.1
English Units
Geom File=g01
Flow File=f01
Plan File=p01
BEGIN DESCRIPTION:
UNT 103 IN BUCR
END DESCRIPTION:

--- UNT 103 IN BUCR.p01 (plan) ---

Plan Title=Multiple Run
Short Identifier=Multiple
Geom File=g01
Flow File=f01
Subcritical Flow
K Sum by GR= 0
Std Step Tol= 0.01
Critical Tol= 0.01
Num of Std Step Trials= 20
Max Error Tol= 0.3
Flow Tol Ratio= 0.001
Split Flow NTrial= 30
Split Flow Tol= 0.02
Split Flow Ratio= 0.02
Log Output Level= 0
Friction Slope Method= 1
Unsteady Friction Slope Method= 2
Unsteady Bridges Friction Slope Method= 1
Parabolic Critical Depth
Global Vel Dist=  1 , 1 , 1
Global Log Level= 0
CheckData=True
Encroach Param= -1, 0, 0, 0
BEGIN DESCRIPTION:
Multiple Run
END DESCRIPTION:

--- UNT 103 IN BUCR.f01 (steady flow) ---

Flow Title=Multiple
Number of Profiles=7
Profile Names=10-year,25-year,50-year,1pct_min,100-year,1pct_plu,500-year
River Rch & RM= UNT 103 IN BUCR,Reach-1,8584
    1294    1811    2248    2036    2754    3724    4119
River Rch & RM= UNT 103 IN BUCR,Reach-1,2243
    1408    1988    2482    2263    3060    4139    4643
Boundary for River Rch & Prof#=UNT 103 IN BUCR,Reach-1,1
Up Type=0
Dn Type=3
Dn Slope=0.005
Boundary for River Rch & Prof#=UNT 103 IN BUCR,Reach-1,2
Up Type=0
Dn Type=3
Dn Slope=0.005
Boundary for River Rch & Prof#=UNT 103 IN BUCR,Reach-1,3
Up Type=0
Dn Type=3
Dn Slope=0.005
Boundary for River Rch & Prof#=UNT 103 IN BUCR,Reach-1,4
Up Type=0
Dn Type=3
Dn Slope=0.005
Boundary for River Rch & Prof#=UNT 103 IN BUCR,Reach-1,5
Up Type=0
Dn Type=3
Dn Slope=0.005
Boundary for River Rch & Prof#=UNT 103 IN BUCR,Reach-1,6
Up Type=0
Dn Type=3
Dn Slope=0.005
Boundary for River Rch & Prof#=UNT 103 IN BUCR,Reach-1,7
Up Type=0
Dn Type=3
Dn Slope=0.005

--- UNT 103 IN BUCR.g01 (geometry) ---

Geom Title=Existing Conditions

River Reach=UNT 103 IN BUCR,Reach-1
Reach XY= 30
      3643269.50     10546085.00      3643299.75     10545714.00
      3643158.25     10545447.00      3643090.25     10545225.00
      3643098.25     10544891.00      3643176.50     10544729.00
      3643129.50     10544432.00      3643369.25     10544302.00
      3643614.00     10544016.00      3643608.58     10543893.09
      3643684.90     10543632.61      3643976.65     10543562.61
      3644202.15     10543250.61      3644594.65     10543028.61
      3644761.15     10542684.61      3644962.65     10541864.61
      3645240.40     10541448.61      3645664.15     10541205.61
      3646059.90     10540913.61      3646349.61     10540560.19
      3646692.00     10539787.00      3646805.00     10539647.00
      3646740.75     10539543.00      3646817.00     10539471.00
      3646749.50     10539379.00      3646805.00     10539300.00
      3646759.75     10539258.00      3646806.75     10539216.00
      3646775.50     10539145.00      3646864.25     10539146.00

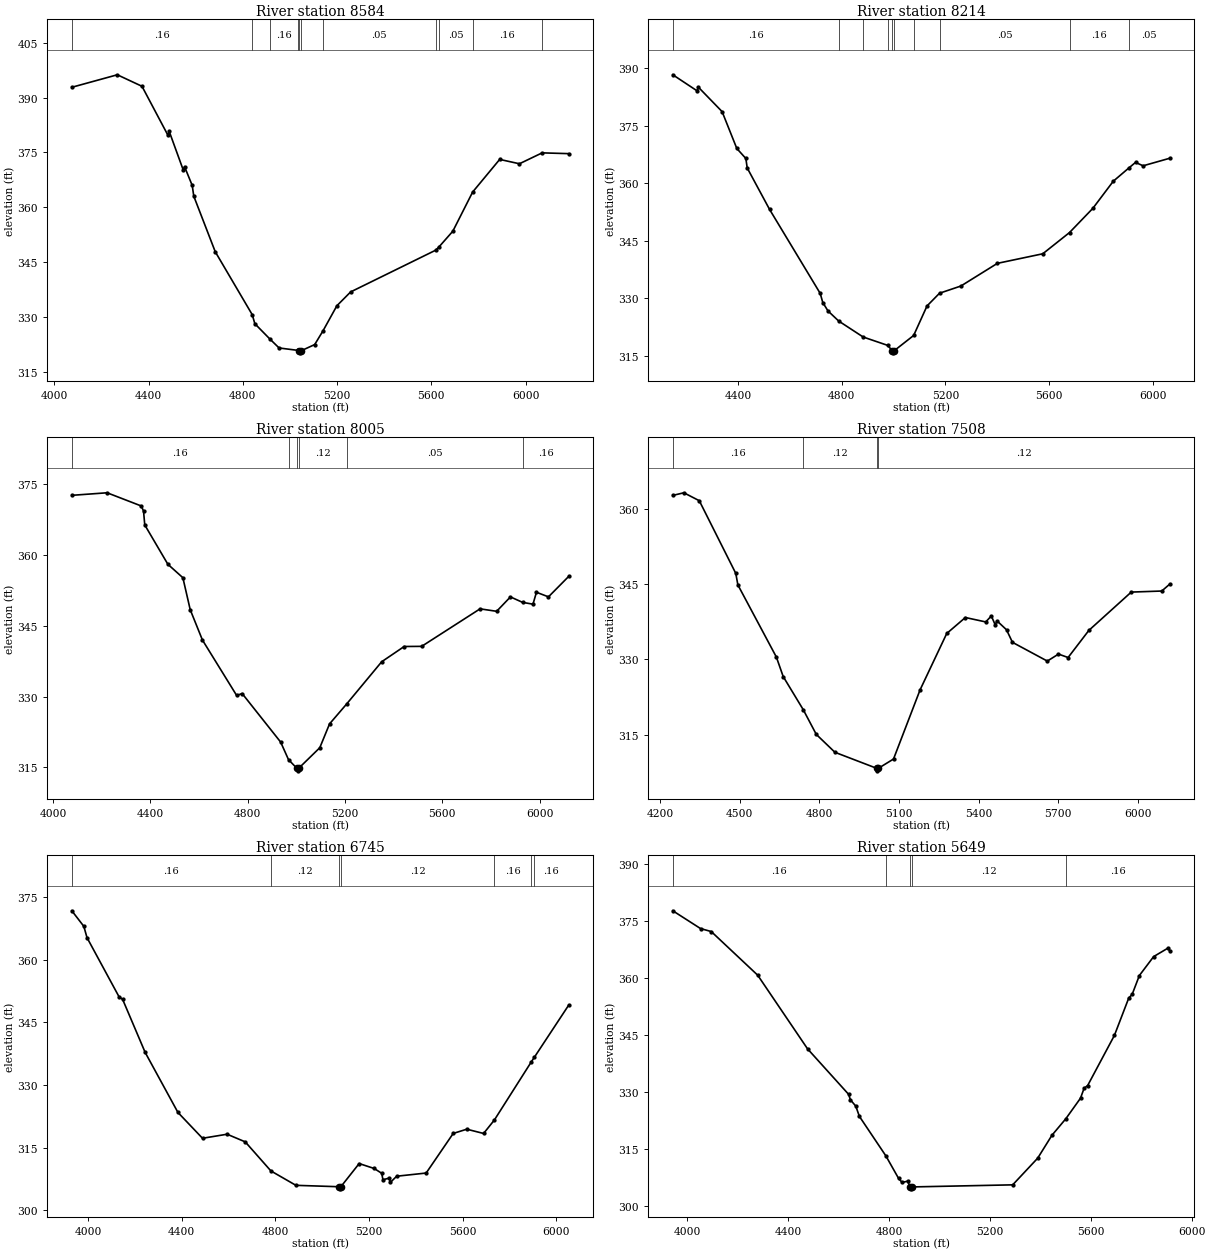
Type RM Length L Ch R = 1,8584,370,370,370
BEGIN DESCRIPTION:
UNT 103 IN BUCR 6.0
END DESCRIPTION:
XS GIS Cut Line= 2
      3644184.04     10545504.17      3642170.20     10546129.16
#Sta/Elev= 30
  4074.1  392.81  4267.2  396.23  4371.9  393.08  4482.1  379.68  4487.4  380.76
  4547.3  370.13  4552.5  371.11  4585.1  365.96  4591.8  363.01  4682.8  347.83
  4840.0  330.59  4850.9  328.14  4914.1  323.99  4953.9  321.50  5035.7  320.83
  5039.0  320.67  5041.8  320.17  5045.0  320.67  5104.9  322.43  5140.5  326.22
  5199.1  333.05  5257.5  336.83  5617.9  348.23  5630.5  349.00  5691.2  353.44
  5775.3  364.15  5890.1  373.08  5973.9  371.89  6070.3  374.87  6182.7  374.66
#Mann=11,-1,0
  4074.1    0.16       0  4840.0    0.12       0  4914.1    0.16       0
  5035.7    0.12       0  5039.0    0.07       0  5045.0    0.12       0
  5140.5    0.05       0  5617.9    0.16       0  5630.5    0.05       0
  5775.3    0.16       0  6070.3    0.05       0
Bank Sta=5039,5045
Exp/Cntr=0.3,0.1

Type RM Length L Ch R = 1,8214,209,209,209
BEGIN DESCRIPTION:
Mapping XS adb05d62
END DESCRIPTION:
XS GIS Cut Line= 3
      3644005.26     10545354.86      3642642.38     10545502.43
      3642199.66     10545823.62
#Sta/Elev= 30
  4147.9  388.35  4241.5  384.16  4246.5  385.12  4338.2  378.73  4395.0  369.10
  4429.9  366.49  4435.2  364.01  4521.6  353.17  4716.9  331.26  4726.9  328.87
  4747.0  326.67  4788.4  324.03  4882.9  319.86  4977.8  317.67  4995.5  316.23
  4998.2  315.73  5001.5  316.23  5077.7  320.27  5129.3  327.98  5177.6  331.30
  5260.0  333.18  5400.8  339.10  5576.1  341.60  5679.4  347.15  5769.3  353.46
  5848.3  360.55  5908.7  364.03  5934.1  365.46  5963.5  364.58  6065.7  366.54
#Mann=10,-1,0
  4147.9    0.16       0  4788.4    0.12       0  4882.9    0.16       0
  4977.8    0.12       0  4995.5    0.07       0  5001.5    0.12       0
  5077.7    0.16       0  5177.6    0.05       0  5679.4    0.16       0
  5908.7    0.05       0
Bank Sta=4995.5,5001.5
Exp/Cntr=0.3,0.1

Type RM Length L Ch R = 1,8005,497,497,497
BEGIN DESCRIPTION:
Mapping XS 028f3ea2
END DESCRIPTION:
XS GIS Cut Line= 4
      3644013.94     10545155.21      3642894.12     10545268.06
      3642234.40     10545424.31      3642078.77     10545605.87
#Sta/Elev= 30
  4076.8  372.61  4221.9  373.15  4362.6  370.35  4371.7  369.27  4376.7  366.34
  4471.8  358.01  4533.4  355.17  4563.6  348.40  4613.8  341.98  4754.5  330.25
  4777.2  330.65  4935.5  320.37  4967.7  316.66  5002.8  314.79  5005.6  314.29
  5008.8  314.79  5096.3  319.18  5136.5  324.23  5206.2  328.41  5350.8  337.38
  5443.3  340.61  5515.2  340.64  5755.3  348.58  5823.5  348.06  5880.2  351.11
  5930.1  349.95  5972.9  349.57  5987.1  352.09  6036.5  351.12  6119.4  355.43
#Mann=6,-1,0
  4076.8    0.16       0  4967.7    0.12       0  5002.8    0.07       0
  5008.8    0.12       0  5206.2    0.05       0  5930.1    0.16       0
Bank Sta=5002.8,5008.8
Exp/Cntr=0.3,0.1

Type RM Length L Ch R = 1,7508,763,763,763
BEGIN DESCRIPTION:
Mapping XS 98056c29
END DESCRIPTION:
XS GIS Cut Line= 4
      3643848.96     10545007.63      3643493.08     10544790.63
      3642798.63     10544738.55      3642164.96     10545155.20
#Sta/Elev= 30
  4248.0  362.65  4289.7  363.17  4347.8  361.59  4485.3  347.13  4493.2  344.83
  4638.2  330.48  4663.9  326.60  4739.4  320.01  4788.6  315.09  4858.8  311.53
  5016.3  308.34  5019.0  307.84  5022.3  308.34  5079.5  310.19  5179.7  323.97
  5280.0  335.17  5350.2  338.35  5426.9  337.47  5448.0  338.66  5463.0  336.84
  5469.0  337.70  5505.2  335.91  5527.6  333.41  5658.9  329.68  5701.0  331.07
  5737.2  330.39  5815.5  335.79  5975.2  343.41  6090.1  343.62  6119.6  344.97
#Mann=4,-1,0
  4248.0    0.16       0  4739.4    0.12       0  5016.3    0.07       0
  5022.3    0.12       0
Bank Sta=5016.3,5022.3
Exp/Cntr=0.3,0.1

Type RM Length L Ch R = 1,6745,1096,1096,1096
BEGIN DESCRIPTION:
Mapping XS 35d21ac7
END DESCRIPTION:
XS GIS Cut Line= 3
      3644491.38     10544521.55      3642815.99     10543983.34
      3642453.02     10543966.05
#Sta/Elev= 30
  3930.2  371.70  3981.5  367.98  3995.1  365.27  4131.6  351.16  4147.3  350.50
  4243.6  337.81  4383.7  323.44  4488.7  317.26  4593.8  318.23  4671.4  316.40
  4781.1  309.44  4887.9  306.00  5073.9  305.66  5076.7  305.16  5079.9  305.66
  5158.2  311.21  5222.4  310.03  5254.5  308.88  5259.8  307.34  5286.6  307.73
  5291.9  306.72  5318.5  308.18  5444.5  308.94  5560.1  318.42  5618.2  319.43
  5689.9  318.41  5736.1  321.64  5892.8  335.45  5906.3  336.60  6053.3  349.09
#Mann=7,-1,0
  3930.2    0.16       0  4781.1    0.12       0  5073.9    0.07       0
  5079.9    0.12       0  5736.1    0.16       0  5892.8    0.12       0
  5906.3    0.16       0
Bank Sta=5073.9,5079.9
Exp/Cntr=0.3,0.1

Type RM Length L Ch R = 1,5649,653,653,653
BEGIN DESCRIPTION:
Mapping XS 046c30e3
END DESCRIPTION:
XS GIS Cut Line= 2
      3644847.25     10544148.27      3643415.54     10542794.65
#Sta/Elev= 30
  3942.2  377.73  4052.3  373.05  4094.7  372.27  4278.8  360.80  4476.6  341.43
  4639.6  329.46  4646.5  328.04  4668.0  326.36  4682.1  323.68  4787.2  313.29
  4837.5  307.38  4851.6  306.29  4873.1  306.63  4884.2  305.12  4887.0  304.62
  4890.2  305.12  5290.2  305.67  5389.3  312.68  5445.9  318.71  5500.8  323.04
  5559.2  328.46  5573.3  331.05  5587.5  331.78  5693.5  344.95  5750.1  354.72
  5764.3  355.80  5792.6  360.71  5849.2  365.68  5905.9  367.91  5912.5  367.23
#Mann=5,-1,0
  3942.2    0.16       0  4787.2    0.12       0  4884.2    0.07       0
  4890.2    0.12       0  5500.8    0.16       0
Bank Sta=4884.2,4890.2
Exp/Cntr=0.3,0.1

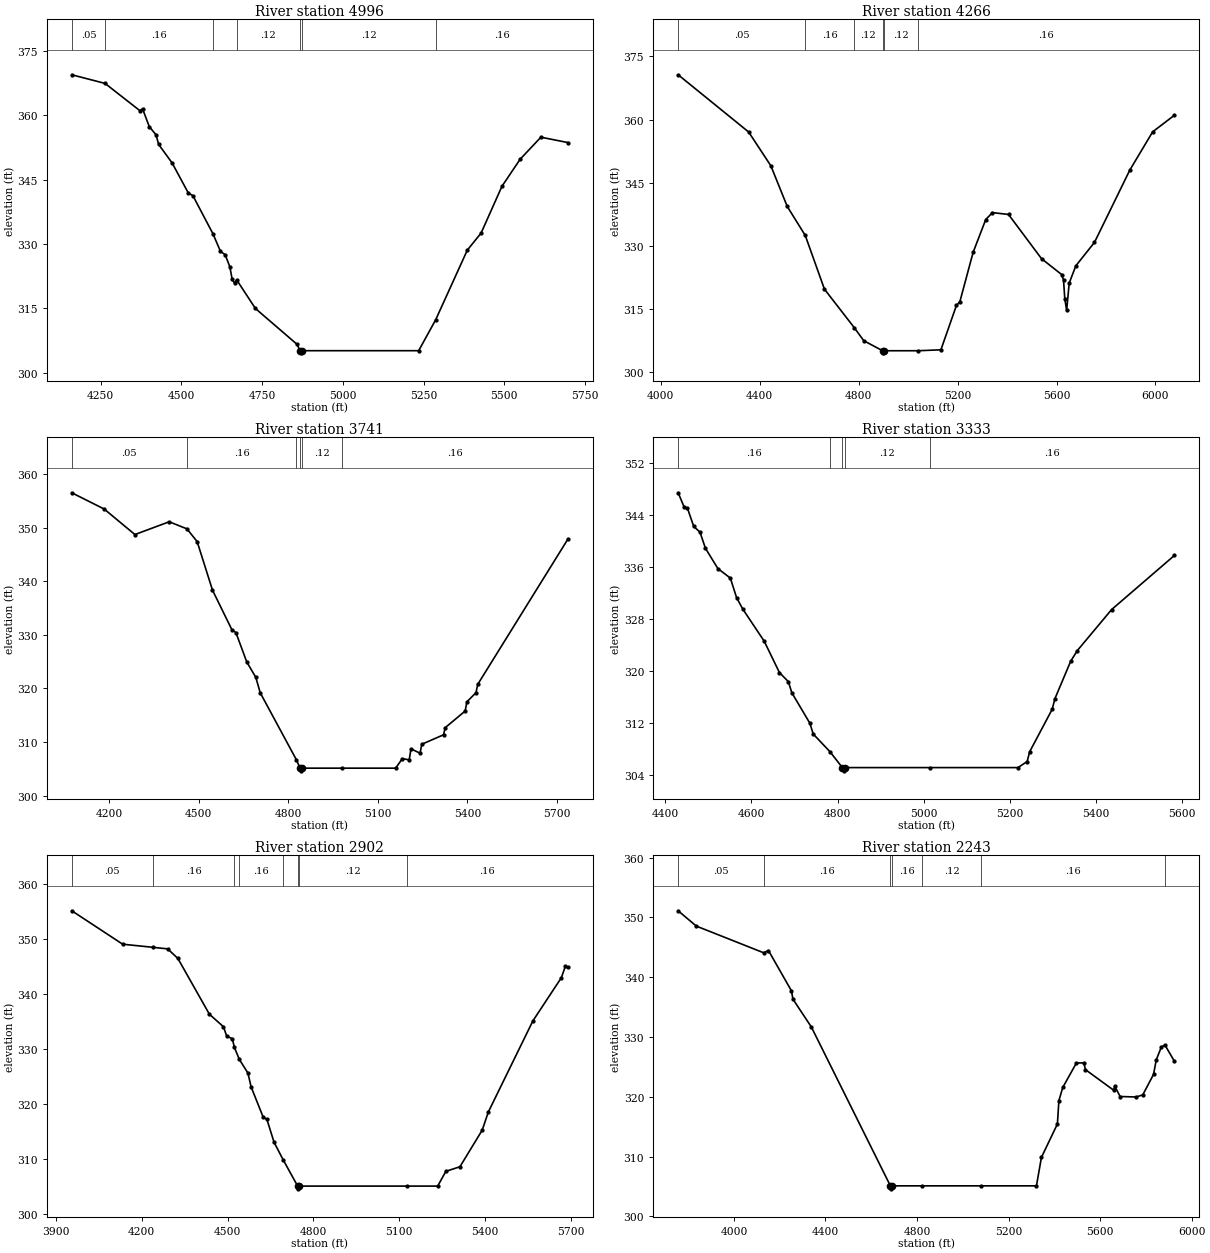
Type RM Length L Ch R = 1,4996,730,730,730
BEGIN DESCRIPTION:
Mapping XS 9417bdd0
END DESCRIPTION:
XS GIS Cut Line= 2
      3645255.22     10543540.62      3644031.24     10542611.79
#Sta/Elev= 30
  4160.6  369.41  4263.6  367.40  4371.4  361.05  4379.7  361.49  4400.5  357.33
  4421.4  355.43  4429.6  353.18  4471.3  348.86  4521.2  341.89  4535.7  341.23
  4597.7  332.36  4621.0  328.26  4635.6  327.48  4650.1  324.65  4657.2  321.76
  4664.7  320.84  4671.0  321.64  4729.1  314.96  4858.1  306.60  4867.6  305.12
  4870.4  304.62  4873.6  305.12  5234.7  305.12  5287.3  312.31  5385.3  328.55
  5428.0  332.52  5492.5  343.41  5548.7  349.71  5613.2  354.87  5697.1  353.61
#Mann=7,-1,0
  4160.6    0.05       0  4263.6    0.16       0  4597.7     0.1       0
  4671.0    0.12       0  4867.6    0.07       0  4873.6    0.12       0
  5287.3    0.16       0
Bank Sta=4867.6,4873.6
Exp/Cntr=0.3,0.1

Type RM Length L Ch R = 1,4266,525,525,525
BEGIN DESCRIPTION:
Mapping XS 3661fc20
END DESCRIPTION:
XS GIS Cut Line= 3
      3645697.93     10542759.38      3644638.91     10542255.91
      3643823.76     10542082.47
#Sta/Elev= 30
  4070.4  370.63  4355.3  357.05  4445.0  349.04  4511.4  339.37  4584.3  332.48
  4661.7  319.74  4782.2  310.61  4820.7  307.50  4896.9  305.12  4899.7  304.62
  4902.9  305.12  5040.7  305.12  5132.6  305.34  5195.3  315.86  5209.0  316.71
  5262.7  328.45  5313.9  336.27  5341.0  337.91  5405.9  337.47  5539.3  326.98
  5620.6  323.21  5628.3  321.92  5633.4  317.47  5641.0  314.70  5651.2  321.16
  5677.9  325.26  5753.5  330.85  5896.6  348.04  5988.6  357.08  6076.4  361.02
#Mann=6,-1,0
  4070.4    0.05       0  4584.3    0.16       0  4782.2    0.12       0
  4896.9    0.07       0  4902.9    0.12       0  5040.7    0.16       0
Bank Sta=4896.9,4902.9
Exp/Cntr=0.3,0.1

Type RM Length L Ch R = 1,3741,408,408,408
BEGIN DESCRIPTION:
Mapping XS cd3ce1dd
END DESCRIPTION:
XS GIS Cut Line= 2
      3645749.99     10542351.37      3644353.51     10541449.30
#Sta/Elev= 30
  4074.8  356.48  4183.3  353.45  4286.3  348.69  4401.1  351.07  4460.6  349.75
  4494.8  347.38  4546.2  338.32  4611.0  330.96  4624.7  330.40  4661.0  324.93
  4691.4  322.05  4706.2  319.17  4827.6  306.65  4839.5  305.12  4842.2  304.62
  4845.5  305.12  4978.8  305.12  5159.8  305.12  5182.4  306.90  5205.3  306.67
  5211.3  308.72  5241.6  307.91  5247.6  309.58  5320.2  311.34  5326.1  312.68
  5392.7  315.77  5398.7  317.51  5429.0  319.19  5435.0  320.76  5737.3  347.87
#Mann=6,-1,0
  4074.8    0.05       0  4460.6    0.16       0  4827.6    0.12       0
  4839.5    0.07       0  4845.5    0.12       0  4978.8    0.16       0
Bank Sta=4839.5,4845.5
Exp/Cntr=0.3,0.1

Type RM Length L Ch R = 1,3333,431,431,431
BEGIN DESCRIPTION:
UNT 103 IN BUCR 5.0
END DESCRIPTION:
XS GIS Cut Line= 3
      3645549.62     10541960.20      3645199.61     10541510.19
      3644899.61     10541010.19
#Sta/Elev= 30
  4429.6  347.41  4443.2  345.27  4451.3  345.01  4465.8  342.23  4480.3  341.35
  4493.0  338.87  4521.9  335.75  4550.9  334.28  4565.3  331.29  4579.8  329.51
  4629.6  324.57  4664.9  319.75  4685.7  318.35  4693.8  316.63  4735.5  311.97
  4743.6  310.28  4782.6  307.55  4811.2  305.12  4813.9  304.62  4817.2  305.12
  5014.2  305.12  5219.3  305.12  5240.7  306.05  5246.5  307.56  5299.0  314.11
  5304.9  315.68  5341.8  321.48  5357.3  323.13  5437.0  329.44  5582.8  337.76
#Mann=5,-1,0
  4429.6    0.16       0  4782.6    0.12       0  4811.2    0.07       0
  4817.2    0.12       0  5014.2    0.16       0
Bank Sta=4811.2,4817.2
Exp/Cntr=0.3,0.1

Type RM Length L Ch R = 1,2902,659,659,659
BEGIN DESCRIPTION:
Mapping XS 8179e59a
END DESCRIPTION:
XS GIS Cut Line= 3
      3645993.15     10542196.77      3645693.66     10541398.13
      3645034.25     10540812.46
#Sta/Elev= 30
  3955.4  355.19  4133.3  349.11  4238.4  348.55  4290.6  348.26  4326.2  346.53
  4436.6  336.37  4485.7  334.10  4497.1  332.37  4516.7  331.93  4523.9  330.34
  4541.2  328.16  4571.2  325.68  4582.5  323.14  4624.6  317.66  4637.7  317.24
  4662.6  313.09  4694.1  309.93  4745.1  305.12  4747.8  304.62  4751.1  305.12
  5126.7  305.12  5234.7  305.12  5263.2  307.80  5312.5  308.64  5390.3  315.29
  5412.0  318.62  5567.6  335.17  5667.1  343.02  5681.3  345.13  5690.3  344.94
#Mann=8,-1,0
  3955.4    0.05       0  4238.4    0.16       0  4523.9    0.12       0
  4541.2    0.16       0  4694.1    0.12       0  4745.1    0.07       0
  4751.1    0.12       0  5126.7    0.16       0
Bank Sta=4745.1,4751.1
Exp/Cntr=0.3,0.1

Type RM Length L Ch R = 1,2243,662,662,662
BEGIN DESCRIPTION:
UNT 103 IN BUCR 4.0
END DESCRIPTION:
XS GIS Cut Line= 4
      3646383.76     10542049.12      3646292.62     10541137.71
      3645984.46     10540768.79      3645277.02     10540460.63
#Sta/Elev= 30
  3756.2  351.12  3835.5  348.56  4129.6  344.10  4150.9  344.47  4251.4  337.72
  4257.6  336.35  4338.0  331.70  4683.6  305.12  4686.3  304.62  4689.6  305.12
  4822.7  305.12  5078.9  305.12  5321.8  305.12  5343.6  309.88  5413.4  315.46
  5419.9  319.37  5436.8  321.57  5496.3  325.66  5529.0  325.69  5536.0  324.55
  5658.6  321.13  5664.0  321.81  5687.4  320.06  5757.7  319.98  5786.6  320.34
  5833.5  323.76  5845.3  326.18  5867.8  328.35  5883.6  328.65  5924.5  325.97
#Mann=7,-1,0
  3756.2    0.05       0  4129.6    0.16       0  4683.6    0.07       0
  4689.6    0.16       0  4822.7    0.12       0  5078.9    0.16       0
  5883.6    0.05       0
Bank Sta=4683.6,4689.6
Exp/Cntr=0.3,0.1

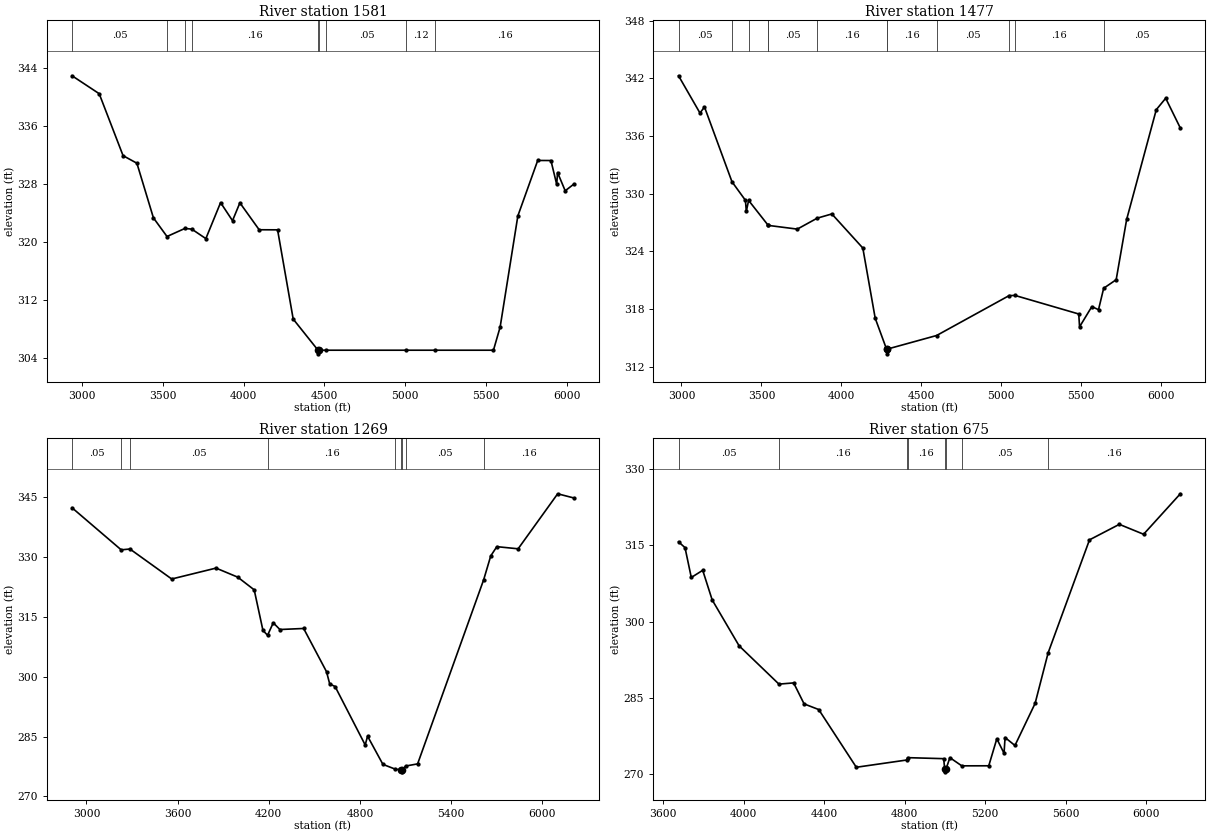
Type RM Length L Ch R = 1,1581,104,104,104
BEGIN DESCRIPTION:
Mapping XS edb37934
END DESCRIPTION:
XS GIS Cut Line= 6
      3647607.74     10541953.71      3647021.79     10540712.36
      3646822.14     10540521.39      3646409.81     10540321.74
      3646201.48     10540269.65      3645437.63     10540430.23
#Sta/Elev= 30
  2939.2  342.94  3107.0  340.47  3254.7  331.93  3340.2  330.89  3442.4  323.36
  3526.4  320.79  3636.9  321.90  3679.5  321.81  3766.7  320.50  3857.8  325.46
  3931.6  322.97  3977.2  325.43  4096.5  321.72  4210.4  321.71  4307.0  309.41
  4460.6  305.12  4463.3  304.62  4466.6  305.12  4512.6  305.12  5007.6  305.12
  5185.4  305.12  5545.7  305.12  5587.0  308.31  5696.6  323.63  5819.4  331.27
  5901.2  331.26  5937.0  327.96  5942.1  329.61  5989.4  327.09  6043.0  328.01
#Mann=9,-1,0
  2939.2    0.05       0  3526.4    0.16       0  3636.9    0.05       0
  3679.5    0.16       0  4460.6    0.03       0  4466.6    0.16       0
  4512.6    0.05       0  5007.6    0.12       0  5185.4    0.16       0
Bank Sta=4460.6,4466.6
Exp/Cntr=0.3,0.1

Type RM Length L Ch R = 1,1477,208,208,208
BEGIN DESCRIPTION:
UNT 103 IN BUCR 3.0
END DESCRIPTION:
XS GIS Cut Line= 6
      3647633.77     10541832.16      3647082.55     10540664.62
      3646952.34     10540521.39      3646531.34     10540260.97
      3646192.80     10540174.17      3645389.83     10540252.29
#Sta/Elev= 30
  2981.8  342.28  3115.8  338.40  3144.1  339.03  3316.0  331.24  3400.1  329.31
  3405.6  328.15  3419.9  329.30  3541.1  326.73  3541.5  326.70  3724.4  326.31
  3848.8  327.45  3940.4  327.89  4134.1  324.34  4211.5  317.03  4282.2  313.82
  4284.9  313.32  4288.2  313.82  4595.6  315.23  5049.5  319.39  5086.3  319.40
  5484.3  317.47  5489.3  316.13  5566.0  318.24  5607.8  317.92  5640.1  320.15
  5718.3  321.04  5783.8  327.32  5969.1  338.75  6027.9  339.94  6119.4  336.84
#Mann=12,-1,0
  2981.8    0.05       0  3316.0    0.16       0  3419.9    0.05       0
  3541.1    0.16       0  3541.5    0.05       0  3848.8    0.16       0
  4282.2    0.03       0  4288.2    0.16       0  4595.6    0.05       0
  5049.5    0.12       0  5086.3    0.16       0  5640.1    0.05       0
Bank Sta=4282.2,4288.2
Exp/Cntr=0.3,0.1

Type RM Length L Ch R = 1,1269,594,594,594
BEGIN DESCRIPTION:
UNT 103 IN BUCR 2.0
END DESCRIPTION:
XS GIS Cut Line= 6
      3647681.50     10541797.42      3647130.30     10540608.19
      3646917.62     10540326.08      3646730.99     10540148.13
      3646405.47     10539983.19      3645398.52     10540009.23
#Sta/Elev= 30
  2905.8  342.28  3229.0  331.75  3286.5  331.96  3561.4  324.45  3852.9  327.18
  3995.9  324.91  4104.1  321.73  4161.7  311.56  4192.1  310.36  4229.4  313.48
  4273.1  311.80  4429.3  312.06  4579.8  301.24  4600.9  298.16  4636.2  297.53
  4834.3  282.89  4849.9  285.09  4950.9  278.03  5032.9  276.82  5072.1  276.66
  5074.8  276.16  5078.1  276.66  5100.0  277.61  5179.1  278.15  5613.9  324.28
  5660.3  330.23  5700.3  332.55  5840.4  332.01  6100.6  345.79  6207.1  344.74
#Mann=9,-1,0
  2905.8    0.05       0  3229.0    0.16       0  3286.5    0.05       0
  4192.1    0.16       0  5032.9    0.12       0  5072.1    0.07       0
  5078.1    0.12       0  5100.0    0.05       0  5613.9    0.16       0
Bank Sta=5072.1,5078.1
Exp/Cntr=0.3,0.1

Type RM Length L Ch R = 1,675,0,0,0
BEGIN DESCRIPTION:
UNT 103 IN BUCR 1.0
END DESCRIPTION:
XS GIS Cut Line= 5
      3647316.92     10540621.19      3647043.49     10539644.65
      3646626.82     10539536.15      3645958.42     10539570.87
      3645598.14     10539692.41
#Sta/Elev= 30
  3675.9  315.67  3708.1  314.53  3739.3  308.66  3796.1  310.07  3843.1  304.25
  3977.0  295.22  4175.0  287.69  4248.1  287.93  4300.0  283.80  4372.7  282.69
  4559.6  271.34  4810.8  272.77  4814.0  273.23  4993.7  273.03  4999.1  270.94
  5001.8  270.44  5005.1  270.94  5024.7  273.23  5083.8  271.62  5217.9  271.63
  5258.0  276.94  5293.9  274.09  5298.9  277.19  5348.1  275.62  5448.2  283.89
  5513.1  293.85  5718.6  316.06  5866.9  319.11  5987.5  317.16  6170.1  325.12
#Mann=8,-1,0
  3675.9    0.05       0  4175.0    0.16       0  4810.8    0.05       0
  4814.0    0.16       0  4999.1    0.07       0  5005.1    0.16       0
  5083.8    0.05       0  5513.1    0.16       0
Bank Sta=4999.1,5005.1
Exp/Cntr=0.3,0.1

Chan Stop Cuts=-1