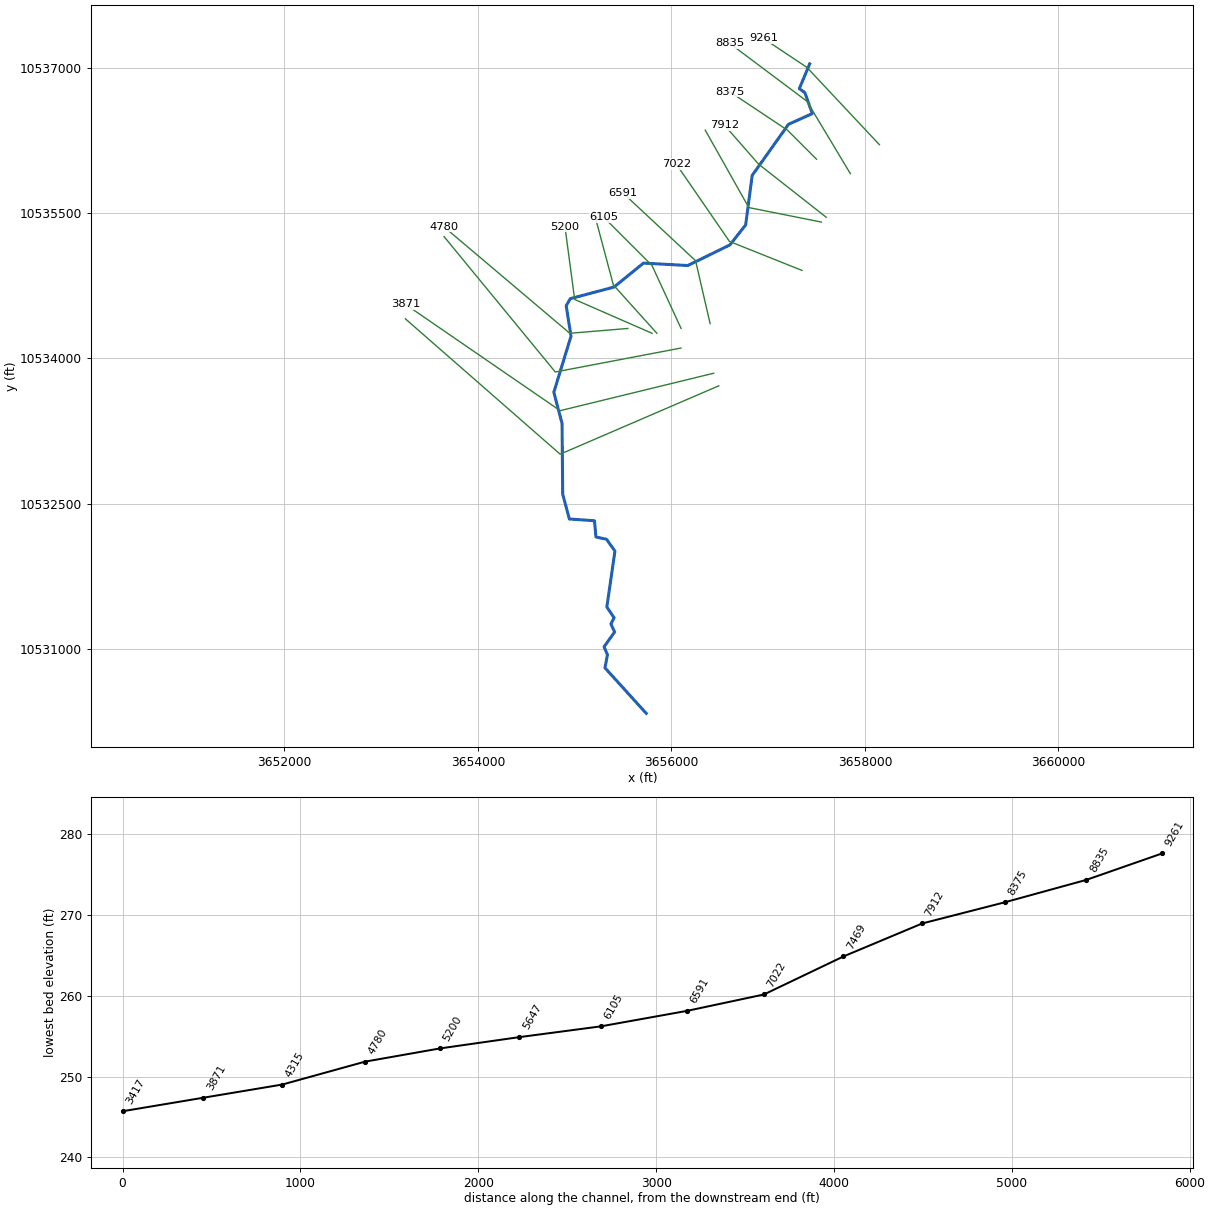
--- UNT 107 IN BUCR.prj (project) ---

Proj Title=UNT 107 IN BUCR Base Level Engineering
Current Plan=p01
Default Exp/Contr=0.3,0.1
English Units
Geom File=g01
Flow File=f01
Plan File=p01
BEGIN DESCRIPTION:
UNT 107 IN BUCR
END DESCRIPTION:

--- UNT 107 IN BUCR.p01 (plan) ---

Plan Title=Multiple Run
Short Identifier=Multiple
Geom File=g01
Flow File=f01
Subcritical Flow
K Sum by GR= 0
Std Step Tol= 0.01
Critical Tol= 0.01
Num of Std Step Trials= 20
Max Error Tol= 0.3
Flow Tol Ratio= 0.001
Split Flow NTrial= 30
Split Flow Tol= 0.02
Split Flow Ratio= 0.02
Log Output Level= 0
Friction Slope Method= 1
Unsteady Friction Slope Method= 2
Unsteady Bridges Friction Slope Method= 1
Parabolic Critical Depth
Global Vel Dist=  1 , 1 , 1
Global Log Level= 0
CheckData=True
Encroach Param= -1, 0, 0, 0
BEGIN DESCRIPTION:
Multiple Run
END DESCRIPTION:

--- UNT 107 IN BUCR.f01 (steady flow) ---

Flow Title=Multiple
Number of Profiles=7
Profile Names=10-year,25-year,50-year,1pct_min,100-year,1pct_plu,500-year
River Rch & RM= UNT 107 IN BUCR,Reach-1,9261
    1032    1461    1830    1683    2276    3078    3538
River Rch & RM= UNT 107 IN BUCR,Reach-1,3871
    1128    1598    2001    1838    2486    3362    3858
Boundary for River Rch & Prof#=UNT 107 IN BUCR,Reach-1,1
Up Type=0
Dn Type=3
Dn Slope=0.005
Boundary for River Rch & Prof#=UNT 107 IN BUCR,Reach-1,2
Up Type=0
Dn Type=3
Dn Slope=0.005
Boundary for River Rch & Prof#=UNT 107 IN BUCR,Reach-1,3
Up Type=0
Dn Type=3
Dn Slope=0.005
Boundary for River Rch & Prof#=UNT 107 IN BUCR,Reach-1,4
Up Type=0
Dn Type=3
Dn Slope=0.005
Boundary for River Rch & Prof#=UNT 107 IN BUCR,Reach-1,5
Up Type=0
Dn Type=3
Dn Slope=0.005
Boundary for River Rch & Prof#=UNT 107 IN BUCR,Reach-1,6
Up Type=0
Dn Type=3
Dn Slope=0.005
Boundary for River Rch & Prof#=UNT 107 IN BUCR,Reach-1,7
Up Type=0
Dn Type=3
Dn Slope=0.005

--- UNT 107 IN BUCR.g01 (geometry) ---

Geom Title=Existing Conditions

River Reach=UNT 107 IN BUCR,Reach-1
Reach XY= 30
      3657428.75     10537046.00      3657321.50     10536790.00
      3657378.75     10536749.00      3657455.75     10536532.00
      3657209.50     10536421.00      3656834.50     10535893.00
      3656767.00     10535381.00      3656604.00     10535174.00
      3656169.00     10534961.00      3655711.00     10534986.00
      3655405.75     10534738.00      3654954.50     10534618.00
      3654912.00     10534545.00      3654962.00     10534230.00
      3654784.25     10533650.00      3654869.25     10533328.00
      3654876.25     10532596.00      3654944.75     10532340.00
      3655204.75     10532322.00      3655219.25     10532154.00
      3655329.25     10532130.00      3655416.00     10532008.00
      3655332.25     10531430.00      3655407.25     10531319.00
      3655374.75     10531255.00      3655412.50     10531171.00
      3655303.75     10531019.00      3655338.50     10530935.00
      3655312.75     10530801.00      3655739.50     10530330.00

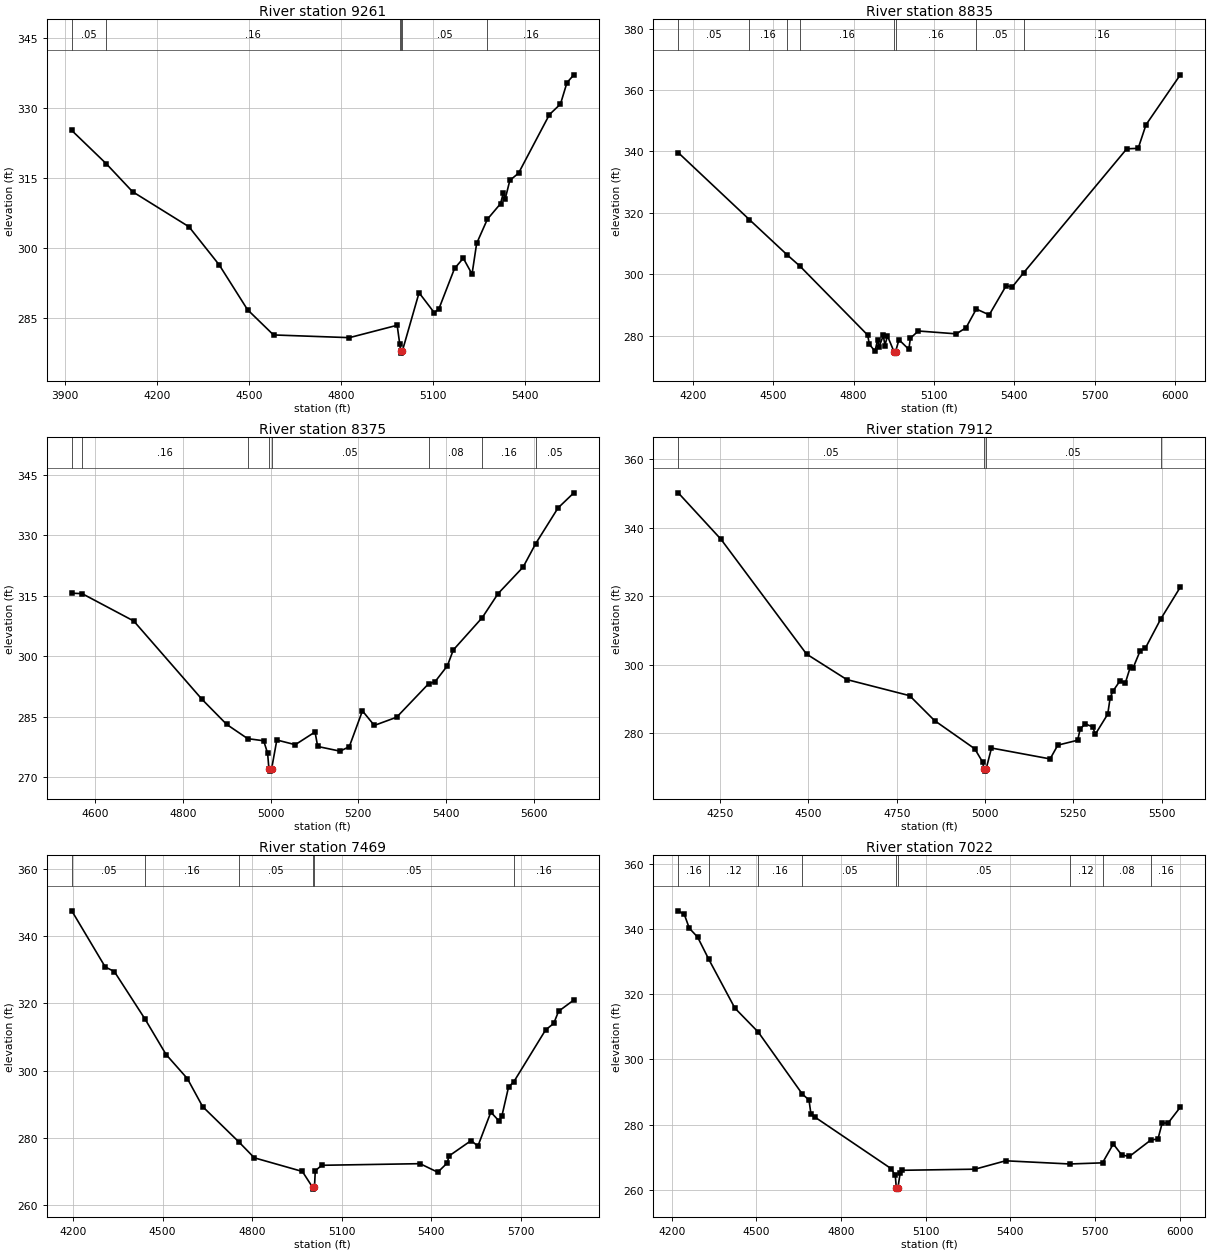
Type RM Length L Ch R = 1,9261,426,426,426
BEGIN DESCRIPTION:
UNT 107 IN BUCR 14.0
END DESCRIPTION:
XS GIS Cut Line= 3
      3658149.61     10536210.19      3657399.61     10537010.19
      3656949.62     10537310.18
#Sta/Elev= 30
  3922.4  325.21  4035.1  318.08  4120.5  312.12  4304.6  304.61  4403.3  296.45
  4495.6  286.87  4580.3  281.47  4827.8  280.89  4983.6  283.54  4992.1  279.48
  4994.7  278.08  4997.5  277.58  5000.7  278.08  5055.0  290.50  5104.6  286.23
  5119.6  287.03  5170.7  295.69  5199.3  297.88  5227.8  294.48  5242.8  301.04
  5277.8  306.22  5320.9  309.56  5330.0  311.93  5336.0  310.59  5351.0  314.52
  5379.5  316.08  5480.2  328.61  5516.2  330.86  5537.3  335.43  5559.8  337.11
#Mann=6,-1,0
  3922.4    0.05       0  4035.1    0.16       0  4992.1    0.05       0
  4994.7    0.03       0  5000.7    0.05       0  5277.8    0.16       0
Bank Sta=4994.7,5000.7
Exp/Cntr=0.3,0.1

Type RM Length L Ch R = 1,8835,460,460,460
BEGIN DESCRIPTION:
UNT 107 IN BUCR 13.0
END DESCRIPTION:
XS GIS Cut Line= 3
      3657849.59     10535910.21      3657399.61     10536660.19
      3656599.62     10537260.18
#Sta/Elev= 30
  4145.6  339.61  4410.9  317.82  4552.0  306.34  4600.2  302.63  4853.1  280.17
  4858.9  277.24  4880.3  274.90  4890.0  278.73  4895.8  276.39  4911.4  280.10
  4917.2  276.79  4926.9  279.89  4951.1  274.81  4953.9  274.31  4957.1  274.81
  4969.7  278.68  5006.6  275.54  5012.4  279.18  5042.1  281.52  5183.8  280.59
  5220.2  282.58  5258.5  288.68  5306.7  286.77  5370.2  296.31  5392.1  295.79
  5435.9  300.55  5820.2  340.85  5862.9  341.01  5892.1  348.69  6020.2  364.95
#Mann=8,-1,0
  4145.6    0.05       0  4410.9    0.16       0  4552.0    0.12       0
  4600.2    0.16       0  4951.1    0.07       0  4957.1    0.16       0
  5258.5    0.05       0  5435.9    0.16       0
Bank Sta=4951.1,4957.1
Exp/Cntr=0.3,0.1

Type RM Length L Ch R = 1,8375,463,463,463
BEGIN DESCRIPTION:
UNT 107 IN BUCR 12.0
END DESCRIPTION:
XS GIS Cut Line= 3
      3657499.60     10536060.20      3657199.61     10536360.19
      3656599.58     10536760.21
#Sta/Elev= 30
  4546.6  315.62  4570.3  315.50  4688.0  308.72  4843.6  289.33  4900.1  283.10
  4947.8  279.58  4984.4  279.05  4993.4  275.95  4996.4  272.03  4999.1  271.53
  5002.4  272.03  5014.4  279.24  5056.5  278.08  5101.6  281.23  5107.6  277.64
  5158.6  276.48  5179.7  277.58  5209.7  286.46  5236.8  282.85  5287.8  284.89
  5361.1  293.23  5375.0  293.63  5403.5  297.63  5417.0  301.55  5483.1  309.57
  5519.2  315.52  5576.3  322.09  5605.1  327.92  5655.9  336.73  5692.0  340.48
#Mann=8,-1,0
  4546.6    0.05       0  4570.3    0.16       0  4947.8    0.05       0
  4996.4    0.03       0  5002.4    0.05       0  5361.1    0.08       0
  5483.1    0.16       0  5605.1    0.05       0
Bank Sta=4996.4,5002.4
Exp/Cntr=0.3,0.1

Type RM Length L Ch R = 1,7912,443,443,443
BEGIN DESCRIPTION:
UNT 107 IN BUCR 11.0
END DESCRIPTION:
XS GIS Cut Line= 3
      3657599.61     10535460.19      3656899.61     10536010.19
      3656549.63     10536410.17
#Sta/Elev= 30
  4131.2  350.24  4252.3  336.66  4494.5  303.13  4608.4  295.68  4786.4  290.97
  4857.0  283.69  4970.8  275.45  4993.4  271.52  4996.7  269.42  4999.5  268.92
  5002.7  269.42  5018.2  275.67  5184.2  272.49  5206.0  276.51  5262.0  277.94
  5269.6  281.27  5283.9  282.73  5304.7  281.84  5312.3  279.70  5347.4  285.57
  5354.1  290.27  5361.7  292.24  5382.6  295.36  5396.8  294.54  5411.0  299.24
  5418.6  298.94  5439.5  304.15  5453.7  304.81  5497.1  313.30  5552.9  322.68
#Mann=4,-1,0
  4131.2    0.05       0  4996.7    0.03       0  5002.7    0.05       0
  5497.1    0.16       0
Bank Sta=4996.7,5002.7
Exp/Cntr=0.3,0.1

Type RM Length L Ch R = 1,7469,447,447,447
BEGIN DESCRIPTION:
UNT 107 IN BUCR 10.0
END DESCRIPTION:
XS GIS Cut Line= 3
      3657549.56     10535410.20      3656799.61     10535560.19
      3656349.60     10536360.20
#Sta/Elev= 30
  4195.9  347.50  4308.0  330.83  4338.6  329.46  4442.0  315.27  4512.0  304.82
  4583.4  297.66  4634.4  289.36  4756.2  278.83  4807.7  274.14  4968.7  270.09
  5003.3  265.34  5006.0  264.84  5009.3  265.34  5012.0  270.30  5033.7  271.92
  5363.2  272.40  5422.5  269.86  5454.1  272.59  5460.1  274.68  5534.4  279.26
  5557.0  277.61  5600.4  287.70  5627.8  285.09  5637.6  286.62  5659.6  295.12
  5677.5  296.74  5783.9  312.12  5811.3  314.07  5827.3  317.66  5878.6  321.01
#Mann=6,-1,0
  4195.9    0.05       0  4442.0    0.16       0  4756.2    0.05       0
  5003.3    0.03       0  5009.3    0.05       0  5677.5    0.16       0
Bank Sta=5003.3,5009.3
Exp/Cntr=0.3,0.1

Type RM Length L Ch R = 1,7022,431,431,431
BEGIN DESCRIPTION:
UNT 107 IN BUCR 9.0
END DESCRIPTION:
XS GIS Cut Line= 3
      3657349.64     10534910.17      3656599.61     10535210.19
      3656049.63     10536010.16
#Sta/Elev= 30
  4223.3  345.69  4244.9  344.58  4262.4  340.36  4292.0  337.60  4331.7  330.75
  4423.9  315.79  4506.9  308.40  4663.0  289.35  4686.5  287.54  4693.2  283.37
  4708.0  282.25  4977.3  266.45  4992.1  264.36  4995.8  260.64  4998.6  260.14
  5001.8  260.64  5009.6  265.20  5016.3  265.93  5274.6  266.27  5383.0  268.85
  5610.4  267.87  5726.3  268.22  5764.5  274.02  5794.3  270.65  5821.3  270.17
  5896.6  275.18  5922.8  275.59  5937.7  280.45  5958.6  280.45  6001.9  285.33
#Mann=9,-1,0
  4223.3    0.16       0  4331.7    0.12       0  4506.9    0.16       0
  4663.0    0.05       0  4995.8    0.03       0  5001.8    0.05       0
  5610.4    0.12       0  5726.3    0.08       0  5896.6    0.16       0
Bank Sta=4995.8,5001.8
Exp/Cntr=0.3,0.1

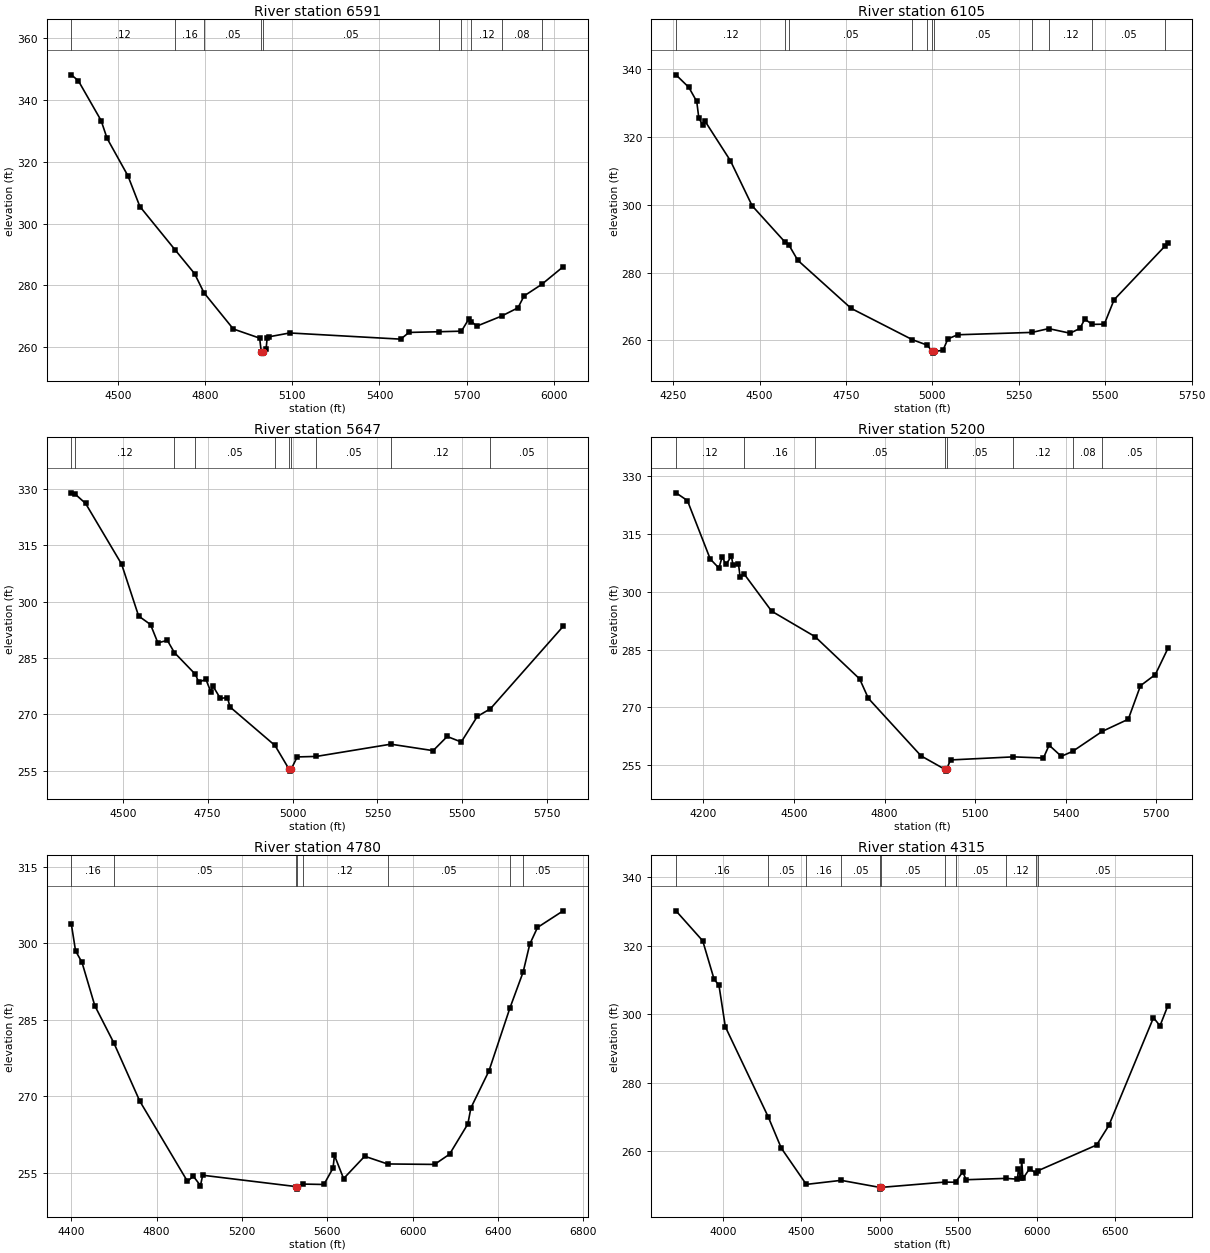
Type RM Length L Ch R = 1,6591,486,486,486
BEGIN DESCRIPTION:
UNT 107 IN BUCR 8.0
END DESCRIPTION:
XS GIS Cut Line= 3
      3656399.62     10534360.15      3656249.61     10535010.19
      3655499.64     10535710.16
#Sta/Elev= 30
  4339.3  348.11  4363.3  346.25  4442.0  333.33  4462.5  327.58  4534.3  315.46
  4575.4  305.53  4696.6  291.52  4763.5  283.85  4796.4  277.60  4897.0  265.93
  4987.6  262.97  4993.2  258.62  4995.9  258.12  4999.2  258.62  5009.8  259.45
  5013.5  262.93  5020.3  263.41  5091.2  264.64  5473.2  262.64  5501.6  264.81
  5606.3  265.04  5682.1  265.22  5706.7  269.03  5716.6  268.32  5735.1  266.85
  5820.1  270.09  5876.7  272.77  5897.7  276.61  5958.2  280.33  6032.3  286.05
#Mann=10,-1,0
  4339.3    0.12       0  4696.6    0.16       0  4796.4    0.05       0
  4993.2    0.03       0  4999.2    0.05       0  5606.3    0.12       0
  5682.1    0.07       0  5716.6    0.12       0  5820.1    0.08       0
  5958.2    0.16       0
Bank Sta=4993.2,4999.2
Exp/Cntr=0.3,0.1

Type RM Length L Ch R = 1,6105,458,458,458
BEGIN DESCRIPTION:
UNT 107 IN BUCR 7.0
END DESCRIPTION:
XS GIS Cut Line= 3
      3656099.60     10534310.20      3655799.61     10534960.19
      3655299.60     10535460.20
#Sta/Elev= 30
  4258.2  338.35  4295.4  334.65  4318.3  330.48  4324.3  325.60  4335.3  323.58
  4341.2  324.84  4415.6  313.01  4478.5  299.70  4573.6  288.98  4584.7  288.15
  4610.6  283.60  4764.8  269.42  4942.2  260.16  4985.2  258.55  4999.4  256.70
  5002.1  256.20  5005.4  256.70  5030.6  257.04  5044.8  260.40  5073.1  261.62
  5288.5  262.32  5336.2  263.44  5398.3  262.08  5426.6  263.49  5440.8  266.22
  5462.6  264.69  5497.3  264.74  5525.6  271.96  5672.0  287.71  5681.2  288.58
#Mann=11,-1,0
  4258.2    0.12       0  4573.6    0.16       0  4584.7    0.05       0
  4942.2    0.12       0  4985.2    0.05       0  4999.4    0.03       0
  5005.4    0.05       0  5288.5    0.16       0  5336.2    0.12       0
  5462.6    0.05       0  5672.0    0.08       0
Bank Sta=4999.4,5005.4
Exp/Cntr=0.3,0.1

Type RM Length L Ch R = 1,5647,447,447,447
BEGIN DESCRIPTION:
UNT 107 IN BUCR 6.0
END DESCRIPTION:
XS GIS Cut Line= 3
      3655849.59     10534260.21      3655399.61     10534760.19
      3655199.60     10535510.23
#Sta/Elev= 30
  4348.2  328.92  4358.1  328.70  4390.4  326.10  4496.5  309.94  4546.6  296.14
  4581.7  293.87  4603.4  288.98  4631.1  289.68  4651.9  286.42  4714.1  280.60
  4723.7  278.51  4744.7  279.32  4758.9  276.05  4765.6  277.50  4787.3  274.22
  4808.2  274.45  4815.7  271.95  4948.3  261.69  4989.8  255.37  4992.6  254.87
  4995.8  255.37  5013.7  258.65  5069.9  258.78  5289.4  262.04  5414.1  260.32
  5455.5  264.09  5496.9  262.62  5544.1  269.41  5583.0  271.48  5797.1  293.39
#Mann=10,-1,0
  4348.2    0.16       0  4358.1    0.12       0  4651.9    0.16       0
  4714.1    0.05       0  4948.3    0.12       0  4989.8    0.07       0
  4995.8    0.12       0  5069.9    0.05       0  5289.4    0.12       0
  5583.0    0.05       0
Bank Sta=4989.8,4995.8
Exp/Cntr=0.3,0.1

Type RM Length L Ch R = 1,5200,420,420,420
BEGIN DESCRIPTION:
UNT 107 IN BUCR 5.0
END DESCRIPTION:
XS GIS Cut Line= 3
      3655799.65     10534260.17      3654999.61     10534610.19
      3654899.61     10535360.19
#Sta/Elev= 30
  4109.0  325.64  4146.9  323.63  4222.5  308.48  4251.3  306.12  4261.9  309.01
  4274.7  307.08  4292.7  309.20  4298.1  306.86  4316.0  307.28  4321.5  303.82
  4333.8  304.70  4426.0  294.95  4569.7  288.35  4717.6  277.38  4746.4  272.35
  4921.1  257.42  4999.4  253.97  5002.2  253.47  5005.4  253.97  5018.8  256.37
  5227.3  257.17  5326.5  256.87  5345.4  260.20  5385.8  257.31  5423.0  258.58
  5521.5  263.78  5607.7  266.93  5648.1  275.62  5697.3  278.51  5738.9  285.28
#Mann=8,-1,0
  4109.0    0.12       0  4333.8    0.16       0  4569.7    0.05       0
  4999.4    0.03       0  5005.4    0.05       0  5227.3    0.12       0
  5423.0    0.08       0  5521.5    0.05       0
Bank Sta=4999.4,5005.4
Exp/Cntr=0.3,0.1

Type RM Length L Ch R = 1,4780,465,465,465
BEGIN DESCRIPTION:
UNT 107 IN BUCR 4.0
END DESCRIPTION:
XS GIS Cut Line= 3
      3655549.66     10534310.19      3654949.61     10534260.19
      3653649.58     10535360.21
#Sta/Elev= 30
  4399.9  303.85  4420.0  298.51  4450.1  296.26  4510.3  287.76  4599.3  280.49
  4721.1  269.07  4944.3  253.37  4971.9  254.37  5005.3  252.53  5015.7  254.56
  5453.3  252.34  5456.1  251.84  5459.3  252.34  5486.5  252.83  5583.8  252.75
  5626.6  255.96  5633.2  258.46  5676.1  253.90  5774.9  258.28  5881.9  256.77
  6102.4  256.68  6172.6  258.68  6258.4  264.61  6272.7  267.76  6357.2  274.99
  6455.0  287.26  6517.5  294.37  6548.4  299.81  6584.7  303.09  6705.0  306.35
#Mann=8,-1,0
  4399.9    0.16       0  4599.3    0.05       0  5453.3    0.03       0
  5459.3    0.05       0  5486.5    0.12       0  5881.9    0.05       0
  6455.0    0.16       0  6517.5    0.05       0
Bank Sta=5453.3,5459.3
Exp/Cntr=0.3,0.1

Type RM Length L Ch R = 1,4315,444,444,444
BEGIN DESCRIPTION:
UNT 107 IN BUCR 3.0
END DESCRIPTION:
XS GIS Cut Line= 3
      3656098.50     10534107.75      3654799.61     10533860.19
      3653649.63     10535260.16
#Sta/Elev= 30
  3700.6  330.16  3871.0  321.41  3943.8  310.16  3974.3  308.50  4015.1  296.34
  4288.6  270.05  4371.4  260.98  4530.9  250.39  4753.2  251.57  4999.5  249.51
  5002.3  249.01  5005.5  249.51  5412.3  251.06  5482.5  251.02  5527.6  254.09
  5548.8  251.75  5801.8  252.14  5876.0  251.92  5882.5  254.82  5896.8  252.19
  5903.3  257.32  5911.2  252.11  5954.2  255.00  5994.7  253.59  6008.3  254.40
  6380.4  261.87  6458.6  267.59  6742.8  299.00  6784.4  296.63  6834.6  302.51
#Mann=11,-1,0
  3700.6    0.16       0  4288.6    0.05       0  4530.9    0.16       0
  4753.2    0.05       0  4999.5    0.03       0  5005.5    0.05       0
  5412.3    0.08       0  5482.5    0.05       0  5801.8    0.12       0
  5994.7    0.07       0  6008.3    0.05       0
Bank Sta=4999.5,5005.5
Exp/Cntr=0.3,0.1

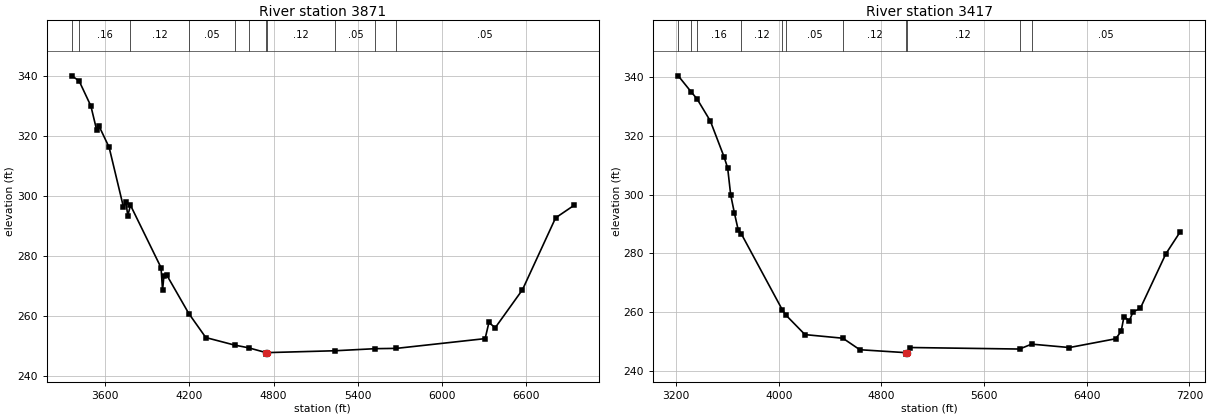
Type RM Length L Ch R = 1,3871,454,454,454
BEGIN DESCRIPTION:
UNT 107 IN BUCR 2.0
END DESCRIPTION:
XS GIS Cut Line= 3
      3656437.08     10533847.34      3654849.61     10533460.19
      3653249.65     10534560.16
#Sta/Elev= 30
  3363.2  340.16  3415.2  338.49  3499.2  330.11  3540.9  322.00  3556.2  323.52
  3629.4  316.30  3731.1  296.43  3749.4  297.96  3762.0  293.54  3781.4  297.01
  3998.8  276.22  4009.8  268.70  4019.4  273.45  4039.9  273.71  4196.7  260.91
  4317.9  252.90  4522.4  250.40  4623.2  249.48  4747.2  247.88  4749.9  247.38
  4753.2  247.88  5240.4  248.51  5526.2  249.20  5675.6  249.30  6307.0  252.55
  6334.0  257.93  6378.7  256.17  6572.9  268.85  6808.9  292.81  6938.8  296.94
#Mann=11,-1,0
  3363.2    0.05       0  3415.2    0.16       0  3781.4    0.12       0
  4196.7    0.05       0  4522.4    0.16       0  4623.2    0.12       0
  4747.2    0.07       0  4753.2    0.12       0  5240.4    0.05       0
  5526.2    0.16       0  5675.6    0.05       0
Bank Sta=4747.2,4753.2
Exp/Cntr=0.3,0.1

Type RM Length L Ch R = 1,3417,0,0,0
BEGIN DESCRIPTION:
UNT 107 IN BUCR 1.0
END DESCRIPTION:
XS GIS Cut Line= 3
      3656489.19     10533717.14      3654849.61     10533010.19
      3653249.63     10534410.17
#Sta/Elev= 30
  3217.1  340.40  3320.2  334.81  3363.4  332.56  3467.1  325.04  3573.1  312.94
  3602.1  309.07  3625.6  299.92  3654.5  293.76  3684.9  287.84  3707.8  286.69
  4029.2  260.68  4057.2  258.93  4204.6  252.35  4499.8  251.12  4631.6  247.21
  4990.6  246.21  4993.3  245.71  4996.6  246.21  5024.0  247.96  5875.8  247.44
  5970.2  249.11  6264.5  247.95  6625.1  250.94  6667.8  253.48  6689.7  258.47
  6731.4  257.01  6759.9  260.09  6816.8  261.27  7015.2  279.78  7128.6  287.38
#Mann=11,-1,0
  3217.1    0.05       0  3320.2    0.12       0  3363.4    0.16       0
  3707.8    0.12       0  4029.2    0.16       0  4057.2    0.05       0
  4499.8    0.12       0  4990.6    0.07       0  4996.6    0.12       0
  5875.8    0.16       0  5970.2    0.05       0
Bank Sta=4990.6,4996.6
Exp/Cntr=0.3,0.1

Chan Stop Cuts=-1