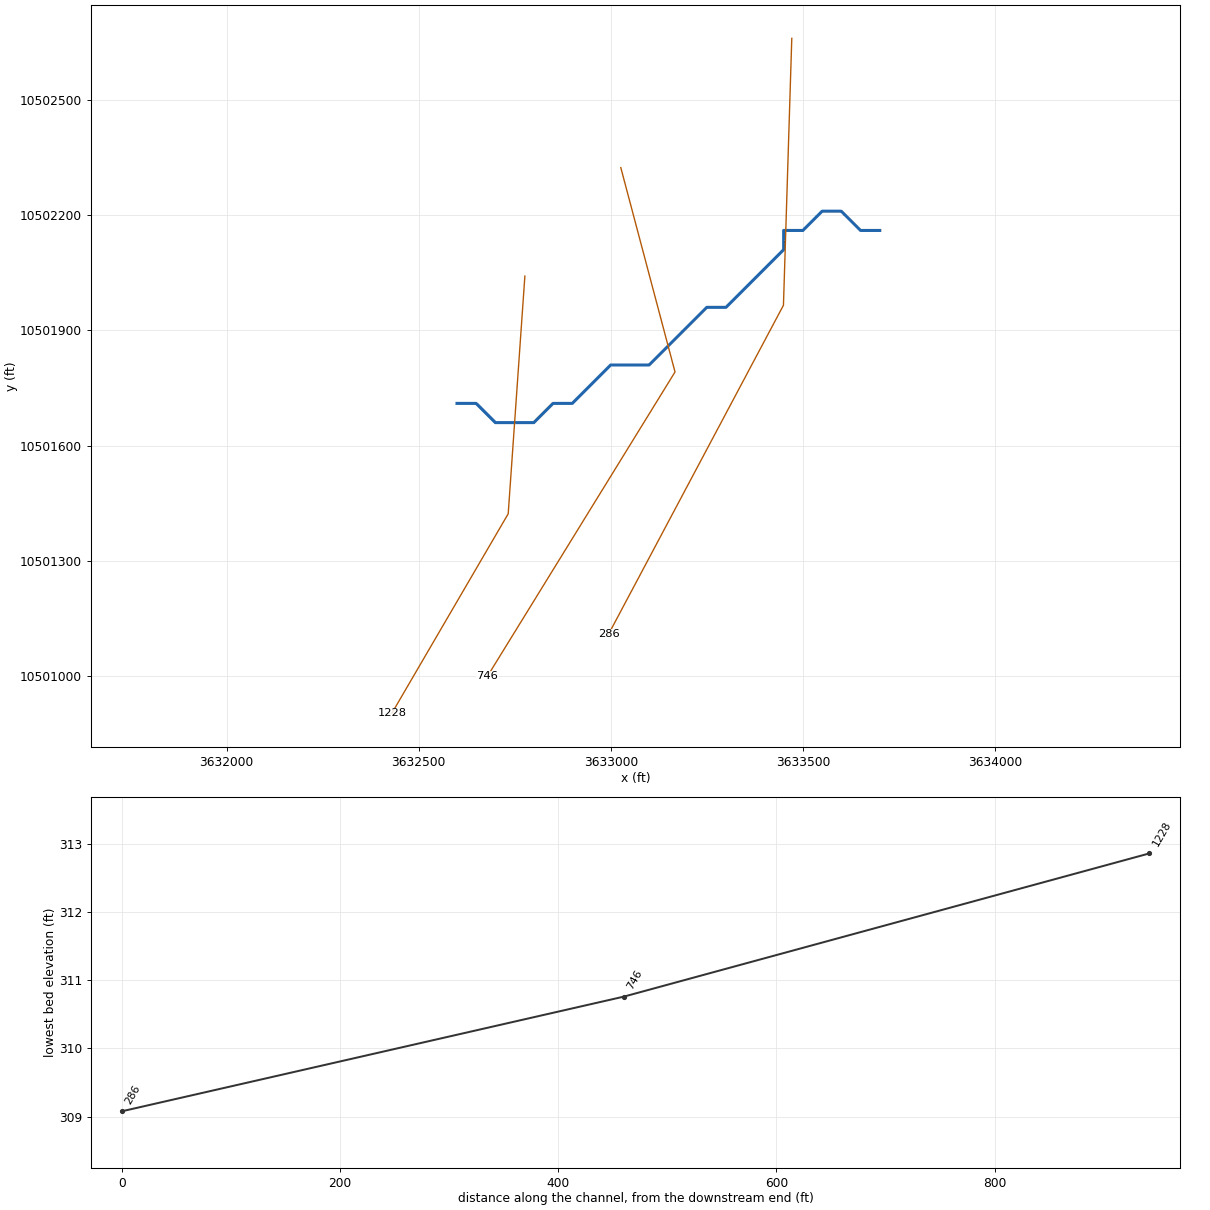
--- UNT 110 IN BUCR.prj (project) ---

Proj Title=UNT 110 IN BUCR Base Level Engineering
Current Plan=p01
Default Exp/Contr=0.3,0.1
English Units
Geom File=g01
Flow File=f01
Plan File=p01
BEGIN DESCRIPTION:
UNT 110 IN BUCR
END DESCRIPTION:

--- UNT 110 IN BUCR.p01 (plan) ---

Plan Title=Multiple Run
Short Identifier=Multiple
Geom File=g01
Flow File=f01
Subcritical Flow
K Sum by GR= 0
Std Step Tol= 0.01
Critical Tol= 0.01
Num of Std Step Trials= 20
Max Error Tol= 0.3
Flow Tol Ratio= 0.001
Split Flow NTrial= 30
Split Flow Tol= 0.02
Split Flow Ratio= 0.02
Log Output Level= 0
Friction Slope Method= 1
Unsteady Friction Slope Method= 2
Unsteady Bridges Friction Slope Method= 1
Parabolic Critical Depth
Global Vel Dist=  1 , 1 , 1
Global Log Level= 0
CheckData=True
Encroach Param= -1, 0, 0, 0
BEGIN DESCRIPTION:
Multiple Run
END DESCRIPTION:

--- UNT 110 IN BUCR.f01 (steady flow) ---

Flow Title=Multiple
Number of Profiles=7
Profile Names=10-year,25-year,50-year,1pct_min,100-year,1pct_plu,500-year
River Rch & RM= UNT 110 IN BUCR,Reach-1,1228
     472     615     724     494     838    1182    1112
Boundary for River Rch & Prof#=UNT 110 IN BUCR,Reach-1,1
Up Type=0
Dn Type=3
Dn Slope=0.005
Boundary for River Rch & Prof#=UNT 110 IN BUCR,Reach-1,2
Up Type=0
Dn Type=3
Dn Slope=0.005
Boundary for River Rch & Prof#=UNT 110 IN BUCR,Reach-1,3
Up Type=0
Dn Type=3
Dn Slope=0.005
Boundary for River Rch & Prof#=UNT 110 IN BUCR,Reach-1,4
Up Type=0
Dn Type=3
Dn Slope=0.005
Boundary for River Rch & Prof#=UNT 110 IN BUCR,Reach-1,5
Up Type=0
Dn Type=3
Dn Slope=0.005
Boundary for River Rch & Prof#=UNT 110 IN BUCR,Reach-1,6
Up Type=0
Dn Type=3
Dn Slope=0.005
Boundary for River Rch & Prof#=UNT 110 IN BUCR,Reach-1,7
Up Type=0
Dn Type=3
Dn Slope=0.005

--- UNT 110 IN BUCR.g01 (geometry) ---

Geom Title=Existing Conditions

River Reach=UNT 110 IN BUCR,Reach-1
Reach XY= 24
      3632599.61     10501710.19      3632649.61     10501710.19
      3632699.61     10501660.19      3632749.61     10501660.19
      3632799.61     10501660.19      3632849.61     10501710.19
      3632899.61     10501710.19      3632949.61     10501760.19
      3632999.61     10501810.19      3633049.61     10501810.19
      3633099.61     10501810.19      3633149.61     10501860.19
      3633199.61     10501910.19      3633249.61     10501960.19
      3633299.61     10501960.19      3633349.61     10502010.19
      3633399.61     10502060.19      3633449.61     10502110.19
      3633449.61     10502160.19      3633499.61     10502160.19
      3633549.61     10502210.19      3633599.61     10502210.19
      3633649.61     10502160.19      3633699.61     10502160.19

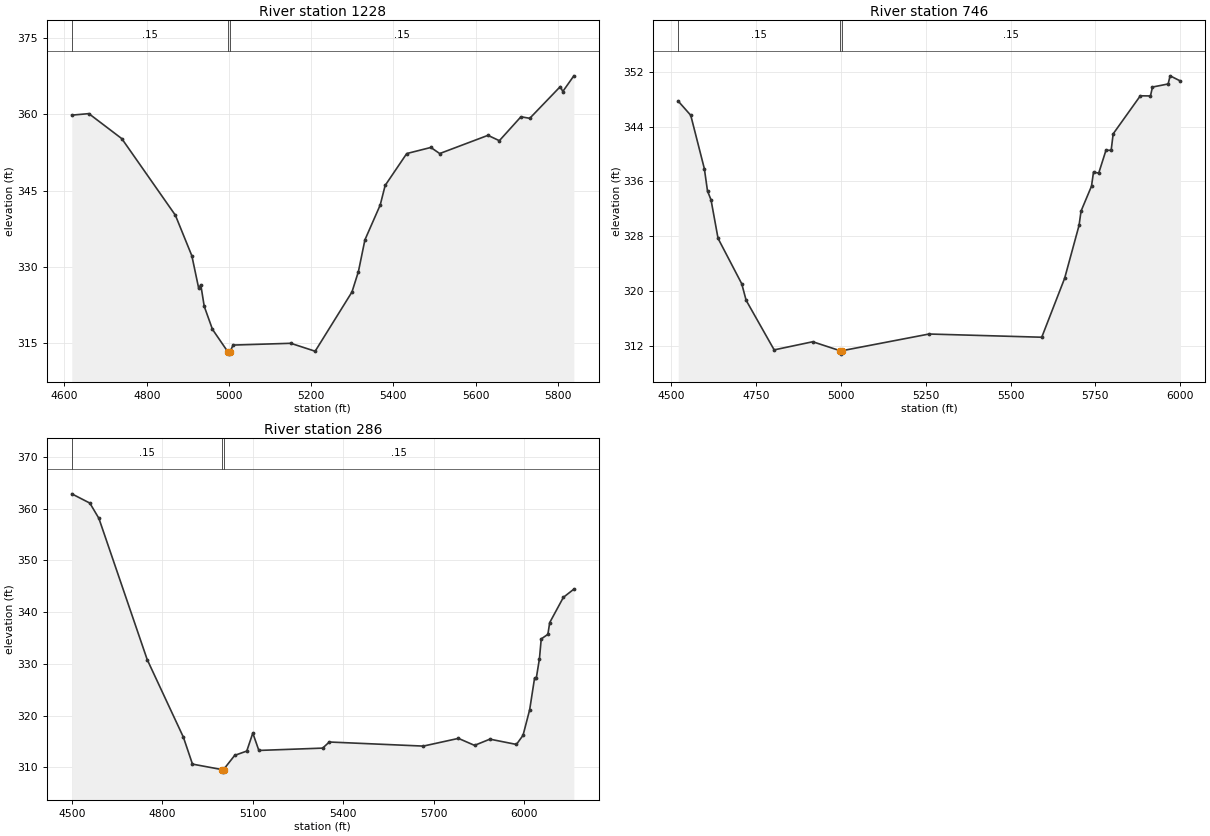
Type RM Length L Ch R = 1,1228,482,482,482
BEGIN DESCRIPTION:
UNT 110 IN BUCR 2.0
END DESCRIPTION:
XS GIS Cut Line= 3
      3632776.34     10502041.55      3632732.94     10501423.04
      3632429.98     10500903.68
#Sta/Elev= 30
  4617.7  359.84  4659.2  360.14  4739.4  355.22  4869.7  340.17  4909.8  332.19
  4926.5  325.78  4931.5  326.51  4939.9  322.26  4959.9  317.74  4997.0  313.36
  4999.8  312.86  5003.0  313.36  5010.0  314.64  5150.4  314.99  5209.7  313.43
  5299.3  325.08  5315.0  329.10  5330.8  335.33  5368.0  342.18  5380.0  346.02
  5432.5  352.29  5491.2  353.49  5512.7  352.29  5630.1  355.87  5657.8  354.82
  5710.3  359.52  5731.8  359.22  5806.2  365.47  5812.0  364.48  5839.0  367.57
#Mann=3,-1,0
  4617.7    0.15       0  4997.0    0.05       0  5003.0    0.15       0
Bank Sta=4997,5003
Exp/Cntr=0.3,0.1

Type RM Length L Ch R = 1,746,460,460,460
BEGIN DESCRIPTION:
Mapping XS 1ab8eadb
END DESCRIPTION:
XS GIS Cut Line= 3
      3633025.91     10502323.65      3633166.97     10501791.96
      3632678.68     10500999.85
#Sta/Elev= 30
  4519.9  347.74  4556.8  345.67  4596.9  337.87  4606.2  334.61  4616.6  333.31
  4637.3  327.68  4707.2  321.04  4720.1  318.63  4802.8  311.38  4916.6  312.57
  4997.0  311.26  4999.8  310.76  5003.0  311.26  5259.6  313.70  5591.9  313.23
  5659.4  321.85  5701.9  329.58  5707.8  331.67  5738.6  335.31  5744.5  337.37
  5759.9  337.22  5781.2  340.55  5796.6  340.56  5802.5  342.96  5882.6  348.52
  5912.5  348.50  5918.4  349.80  5964.6  350.25  5970.4  351.44  6000.5  350.69
#Mann=3,-1,0
  4519.9    0.15       0  4997.0    0.05       0  5003.0    0.15       0
Bank Sta=4997,5003
Exp/Cntr=0.3,0.1

Type RM Length L Ch R = 1,286,0,0,0
BEGIN DESCRIPTION:
UNT 110 IN BUCR 1.0
END DESCRIPTION:
XS GIS Cut Line= 3
      3633470.79     10502660.04      3633449.09     10501965.57
      3632993.98     10501109.54
#Sta/Elev= 30
  4499.9  362.85  4559.8  361.06  4589.8  358.11  4749.9  330.83  4869.9  315.83
  4900.0  310.63  4997.0  309.58  4999.8  309.08  5003.0  309.58  5040.0  312.32
  5080.0  313.15  5100.0  316.62  5120.1  313.27  5331.6  313.72  5353.5  314.90
  5665.2  314.11  5781.7  315.60  5835.0  314.25  5886.0  315.45  5973.9  314.43
  5995.8  316.20  6017.8  321.14  6034.1  327.28  6039.8  327.27  6050.2  331.01
  6056.1  334.82  6078.1  335.70  6084.2  337.97  6129.5  342.85  6164.2  344.43
#Mann=3,-1,0
  4499.9    0.15       0  4997.0    0.05       0  5003.0    0.15       0
Bank Sta=4997,5003
Exp/Cntr=0.3,0.1

Chan Stop Cuts=-1