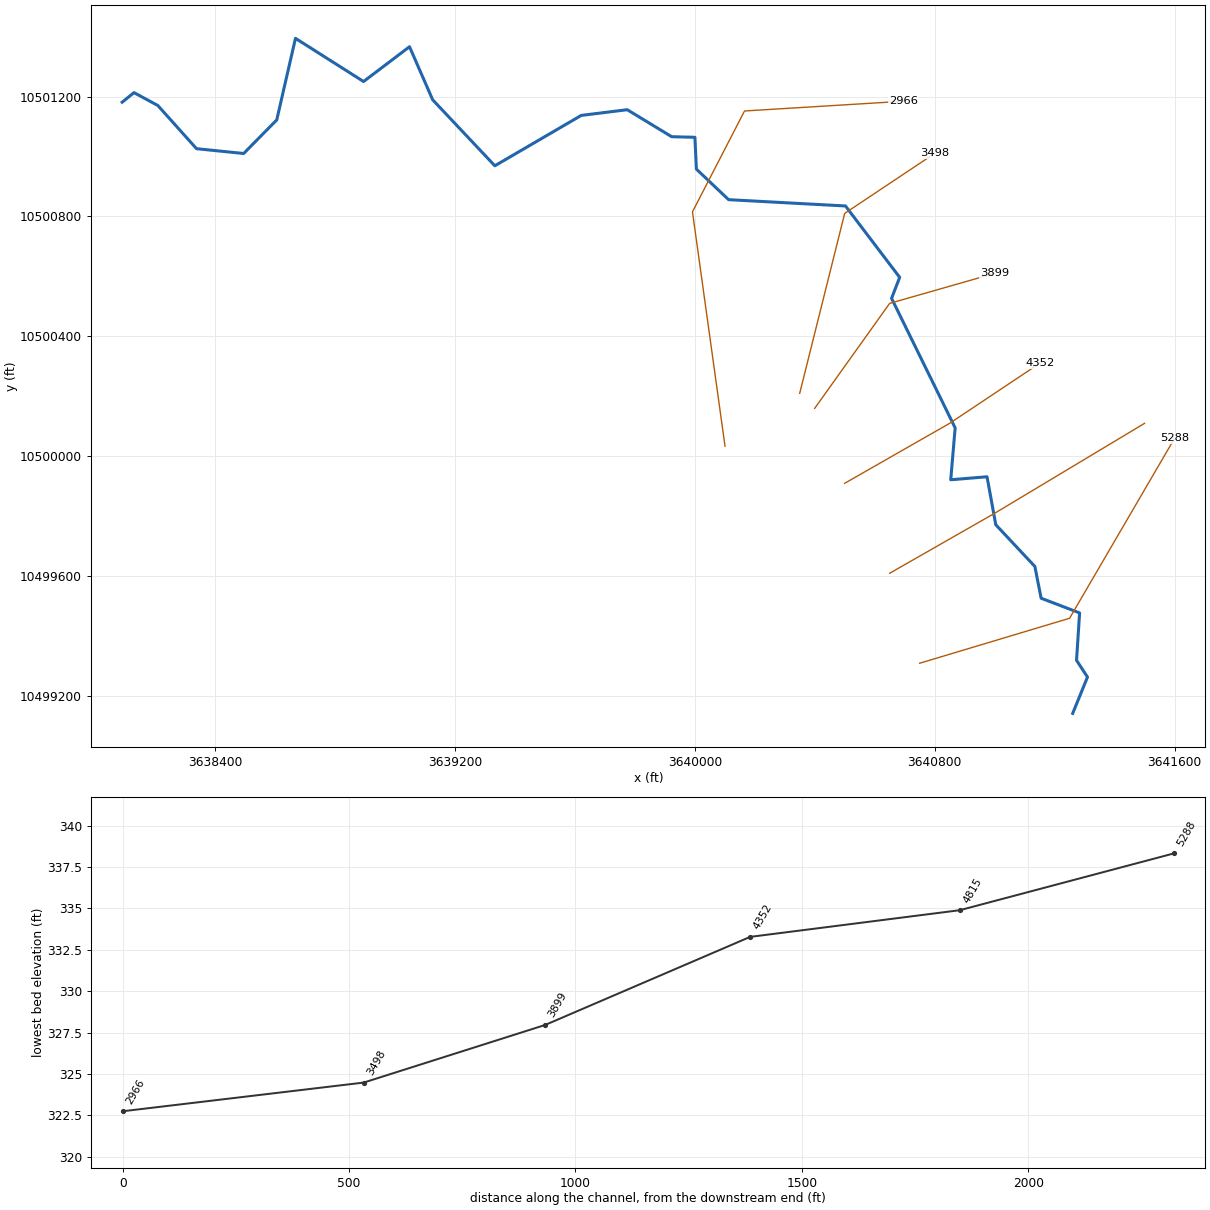
--- UNT 112 IN BUCR.prj (project) ---

Proj Title=UNT 112 IN BUCR Base Level Engineering
Current Plan=p01
Default Exp/Contr=0.3,0.1
English Units
Geom File=g01
Flow File=f01
Plan File=p01
BEGIN DESCRIPTION:
UNT 112 IN BUCR
END DESCRIPTION:

--- UNT 112 IN BUCR.p01 (plan) ---

Plan Title=Multiple Run
Short Identifier=Multiple
Geom File=g01
Flow File=f01
Subcritical Flow
K Sum by GR= 0
Std Step Tol= 0.01
Critical Tol= 0.01
Num of Std Step Trials= 20
Max Error Tol= 0.3
Flow Tol Ratio= 0.001
Split Flow NTrial= 30
Split Flow Tol= 0.02
Split Flow Ratio= 0.02
Log Output Level= 0
Friction Slope Method= 1
Unsteady Friction Slope Method= 2
Unsteady Bridges Friction Slope Method= 1
Parabolic Critical Depth
Global Vel Dist=  1 , 1 , 1
Global Log Level= 0
CheckData=True
Encroach Param= -1, 0, 0, 0
BEGIN DESCRIPTION:
Multiple Run
END DESCRIPTION:

--- UNT 112 IN BUCR.f01 (steady flow) ---

Flow Title=Multiple
Number of Profiles=7
Profile Names=10-year,25-year,50-year,1pct_min,100-year,1pct_plu,500-year
River Rch & RM= UNT 112 IN BUCR,Reach-1,5288
    1032    1415    1730    1544    2088    2824    3030
Boundary for River Rch & Prof#=UNT 112 IN BUCR,Reach-1,1
Up Type=0
Dn Type=3
Dn Slope=0.005
Boundary for River Rch & Prof#=UNT 112 IN BUCR,Reach-1,2
Up Type=0
Dn Type=3
Dn Slope=0.005
Boundary for River Rch & Prof#=UNT 112 IN BUCR,Reach-1,3
Up Type=0
Dn Type=3
Dn Slope=0.005
Boundary for River Rch & Prof#=UNT 112 IN BUCR,Reach-1,4
Up Type=0
Dn Type=3
Dn Slope=0.005
Boundary for River Rch & Prof#=UNT 112 IN BUCR,Reach-1,5
Up Type=0
Dn Type=3
Dn Slope=0.005
Boundary for River Rch & Prof#=UNT 112 IN BUCR,Reach-1,6
Up Type=0
Dn Type=3
Dn Slope=0.005
Boundary for River Rch & Prof#=UNT 112 IN BUCR,Reach-1,7
Up Type=0
Dn Type=3
Dn Slope=0.005

--- UNT 112 IN BUCR.g01 (geometry) ---

Geom Title=Existing Conditions

River Reach=UNT 112 IN BUCR,Reach-1
Reach XY= 30
      3641260.00     10499143.00      3641309.25     10499264.00
      3641272.75     10499320.00      3641283.00     10499478.00
      3641154.75     10499527.00      3641133.75     10499633.00
      3641003.50     10499772.00      3640974.25     10499932.00
      3640853.25     10499922.00      3640868.00     10500095.00
      3640656.00     10500527.00      3640683.00     10500597.00
      3640502.25     10500835.00      3640112.50     10500856.00
      3640005.00     10500958.00      3640000.25     10501064.00
      3639922.75     10501066.00      3639774.50     10501156.00
      3639621.25     10501137.00      3639333.00     10500969.00
      3639125.75     10501189.00      3639048.50     10501366.00
      3638895.25     10501250.00      3638668.25     10501394.00
      3638605.75     10501122.00      3638495.50     10501010.00
      3638338.25     10501026.00      3638209.25     10501170.00
      3638129.75     10501213.00      3638090.25     10501181.00

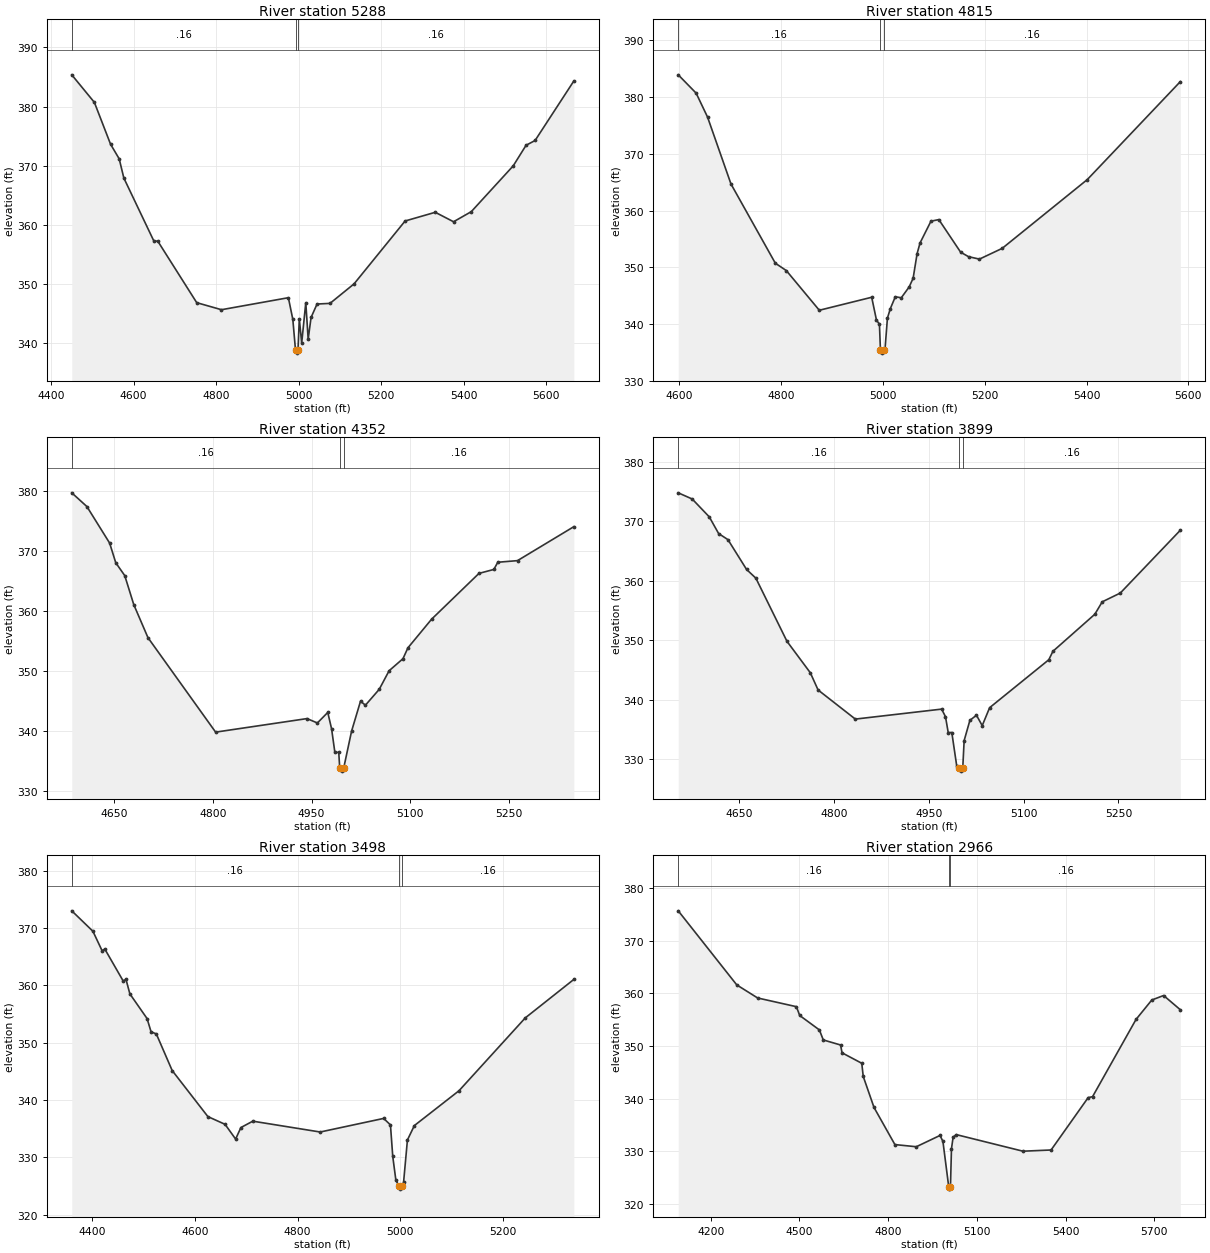
Type RM Length L Ch R = 1,5288,473,473,473
BEGIN DESCRIPTION:
UNT 112 IN BUCR 6.0
END DESCRIPTION:
XS GIS Cut Line= 3
      3640749.57     10499310.18      3641249.61     10499460.19
      3641599.62     10500060.21
#Sta/Elev= 30
  4450.4  385.37  4505.2  380.71  4544.4  373.64  4565.3  371.17  4576.6  367.92
  4648.8  357.35  4659.2  357.21  4753.2  346.85  4813.2  345.66  4975.3  347.69
  4986.1  344.02  4992.6  338.82  4995.4  338.32  4998.6  338.82  5001.8  344.10
  5007.6  340.04  5017.5  346.85  5023.3  340.68  5030.3  344.35  5044.8  346.62
  5076.2  346.73  5134.5  350.03  5258.2  360.66  5331.3  362.13  5375.6  360.53
  5418.6  362.24  5520.3  369.99  5551.3  373.46  5573.2  374.27  5667.1  384.33
#Mann=3,-1,0
  4450.4    0.16       0  4992.6    0.07       0  4998.6    0.16       0
Bank Sta=4992.6,4998.6
Exp/Cntr=0.3,0.1

Type RM Length L Ch R = 1,4815,463,463,463
BEGIN DESCRIPTION:
UNT 112 IN BUCR 5.0
END DESCRIPTION:
XS GIS Cut Line= 3
      3640649.64     10499610.21      3640999.61     10499810.19
      3641499.63     10500110.20
#Sta/Elev= 30
  4597.9  383.91  4633.1  380.68  4655.5  376.46  4701.5  364.68  4788.6  350.73
  4810.2  349.43  4875.0  342.44  4977.9  344.73  4987.3  340.70  4993.1  339.99
  4995.1  335.39  4997.8  334.89  5001.1  335.39  5003.9  335.39  5008.8  341.06
  5014.6  342.75  5024.3  344.82  5036.0  344.64  5051.5  346.55  5059.3  348.08
  5067.1  352.42  5072.9  354.30  5094.3  358.13  5109.8  358.41  5152.6  352.67
  5168.1  351.88  5189.5  351.45  5234.2  353.34  5401.4  365.46  5584.1  382.71
#Mann=3,-1,0
  4597.9    0.16       0  4995.1    0.07       0  5001.1    0.16       0
Bank Sta=4995.1,5001.1
Exp/Cntr=0.3,0.1

Type RM Length L Ch R = 1,4352,453,453,453
BEGIN DESCRIPTION:
UNT 112 IN BUCR 4.0
END DESCRIPTION:
XS GIS Cut Line= 3
      3640499.61     10499910.19      3640849.61     10500110.19
      3641149.63     10500310.21
#Sta/Elev= 30
  4585.2  379.74  4608.2  377.45  4642.8  371.35  4652.1  368.07  4665.8  365.92
  4679.5  361.08  4701.1  355.56  4804.0  339.79  4943.0  342.05  4958.8  341.32
  4974.6  343.08  4980.4  340.34  4985.4  336.41  4991.3  336.41  4992.8  333.78
  4995.6  333.28  4998.8  333.78  5010.8  339.95  5024.4  344.95  5031.9  344.29
  5052.9  346.94  5067.9  350.04  5089.0  352.05  5096.5  353.86  5132.5  358.64
  5204.6  366.29  5227.2  366.95  5233.2  368.15  5263.2  368.42  5348.9  374.09
#Mann=3,-1,0
  4585.2    0.16       0  4992.8    0.07       0  4998.8    0.16       0
Bank Sta=4992.8,4998.8
Exp/Cntr=0.3,0.1

Type RM Length L Ch R = 1,3899,401,401,401
BEGIN DESCRIPTION:
UNT 112 IN BUCR 3.0
END DESCRIPTION:
XS GIS Cut Line= 3
      3640399.64     10500160.23      3640649.61     10500510.19
      3640999.63     10500610.20
#Sta/Elev= 30
  4553.7  374.81  4575.8  373.77  4602.8  370.76  4617.6  367.95  4632.3  366.93
  4661.8  361.91  4676.5  360.44  4725.7  349.81  4762.6  344.52  4774.9  341.62
  4833.8  336.72  4970.3  338.40  4976.4  337.12  4980.7  334.46  4986.4  334.46
  4994.2  328.81  4997.7  328.46  5000.4  327.96  5003.7  328.46  5005.9  333.10
  5015.0  336.51  5025.4  337.37  5034.5  335.62  5046.2  338.64  5139.8  346.71
  5146.3  348.13  5212.6  354.37  5224.3  356.46  5252.9  357.94  5347.8  368.51
#Mann=3,-1,0
  4553.7    0.16       0  4997.7    0.07       0  5003.7    0.16       0
Bank Sta=4997.7,5003.7
Exp/Cntr=0.3,0.1

Type RM Length L Ch R = 1,3498,532,532,532
BEGIN DESCRIPTION:
UNT 112 IN BUCR 2.0
END DESCRIPTION:
XS GIS Cut Line= 3
      3640349.62     10500210.23      3640499.61     10500810.19
      3640799.63     10501010.20
#Sta/Elev= 30
  4359.6  373.01  4400.8  369.45  4418.8  366.04  4424.0  366.35  4460.1  360.74
  4465.2  361.10  4472.9  358.53  4506.4  354.23  4514.2  351.92  4524.5  351.54
  4555.4  345.16  4625.0  337.13  4658.5  335.78  4679.1  333.21  4689.4  335.22
  4712.6  336.33  4844.0  334.44  4967.7  336.81  4981.0  335.68  4985.5  330.17
  4991.5  326.09  4997.6  324.98  5000.3  324.48  5003.6  324.98  5006.6  325.67
  5014.1  333.05  5027.6  335.56  5114.7  341.64  5243.9  354.34  5338.6  361.05
#Mann=3,-1,0
  4359.6    0.16       0  4997.6    0.07       0  5003.6    0.16       0
Bank Sta=4997.6,5003.6
Exp/Cntr=0.3,0.1

Type RM Length L Ch R = 1,2966,0,0,0
BEGIN DESCRIPTION:
UNT 112 IN BUCR 1.0
END DESCRIPTION:
XS GIS Cut Line= 4
      3640100.57     10500034.12      3639992.05     10500815.40
      3640165.67     10501151.77      3640695.96     10501184.24
#Sta/Elev= 30
  4089.8  375.73  4287.8  361.63  4358.4  359.14  4489.7  357.48  4500.7  355.81
  4567.3  353.06  4580.5  351.15  4639.0  350.19  4644.0  348.70  4710.7  346.71
  4715.7  344.20  4752.2  338.29  4822.8  331.23  4895.2  330.82  4975.5  332.97
  4985.3  331.83  5004.8  323.25  5007.5  322.75  5010.8  323.25  5014.2  330.45
  5019.8  332.64  5030.3  333.13  5256.0  329.97  5351.2  330.20  5476.6  340.17
  5491.5  340.35  5638.5  355.05  5691.9  358.75  5731.9  359.61  5788.4  356.90
#Mann=3,-1,0
  4089.8    0.16       0  5004.8    0.07       0  5010.8    0.16       0
Bank Sta=5004.8,5010.8
Exp/Cntr=0.3,0.1

Chan Stop Cuts=-1