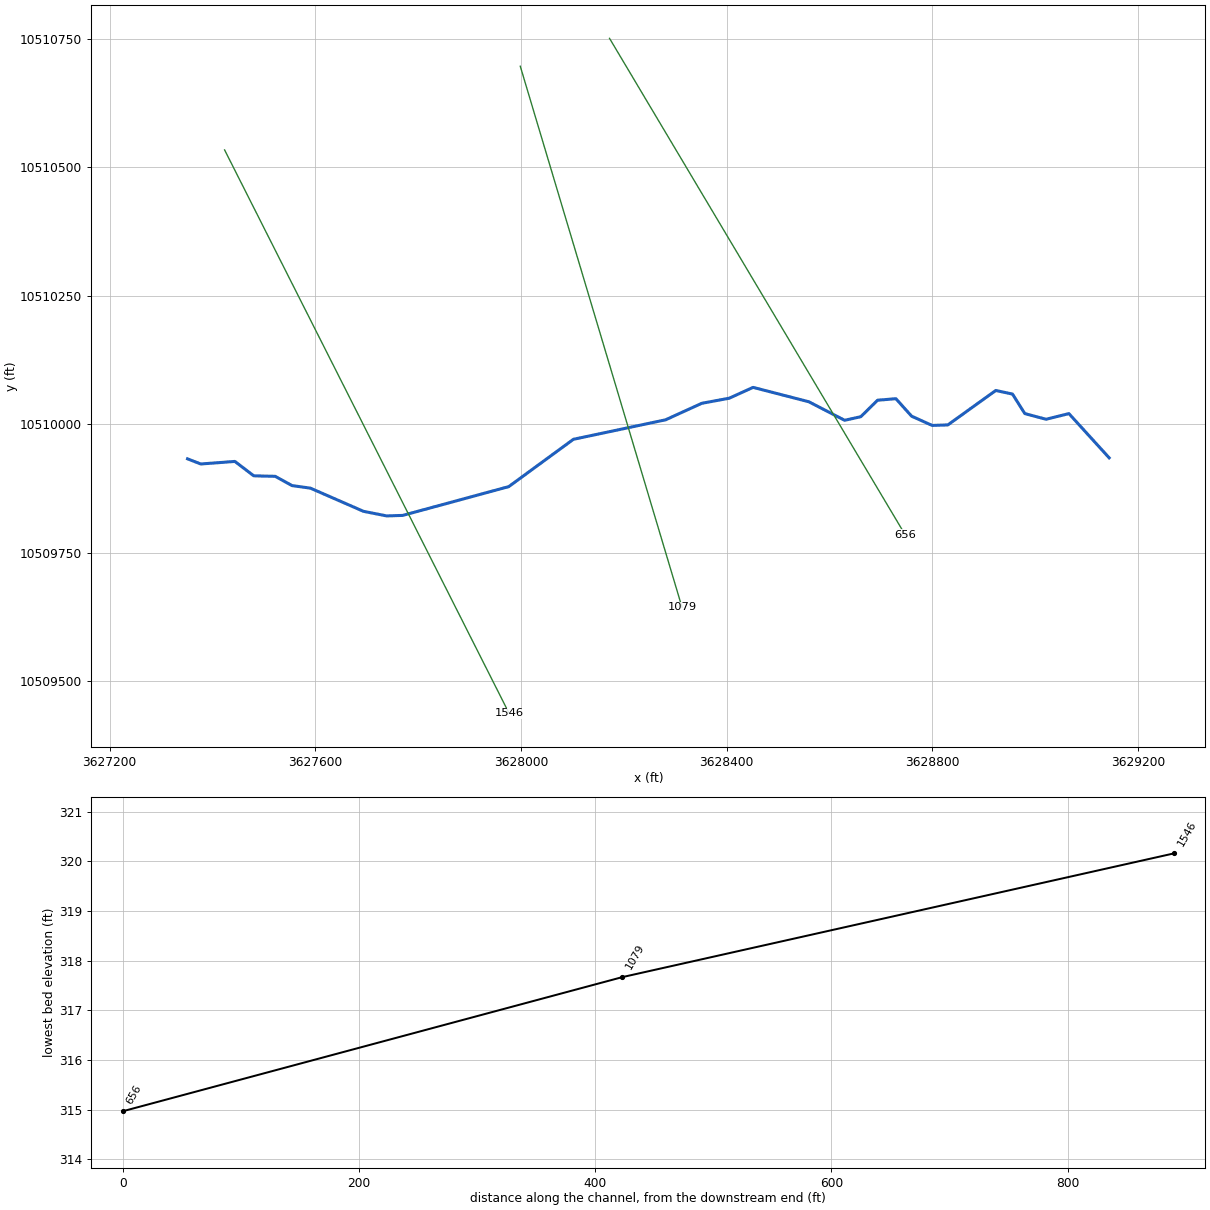
--- UNT 115 IN BUCR.prj (project) ---

Proj Title=UNT 115 IN BUCR Base Level Engineering
Current Plan=p01
Default Exp/Contr=0.3,0.1
English Units
Geom File=g01
Flow File=f01
Plan File=p01
BEGIN DESCRIPTION:
UNT 115 IN BUCR
END DESCRIPTION:

--- UNT 115 IN BUCR.p01 (plan) ---

Plan Title=Multiple Run
Short Identifier=Multiple
Geom File=g01
Flow File=f01
Subcritical Flow
K Sum by GR= 0
Std Step Tol= 0.01
Critical Tol= 0.01
Num of Std Step Trials= 20
Max Error Tol= 0.3
Flow Tol Ratio= 0.001
Split Flow NTrial= 30
Split Flow Tol= 0.02
Split Flow Ratio= 0.02
Log Output Level= 0
Friction Slope Method= 1
Unsteady Friction Slope Method= 2
Unsteady Bridges Friction Slope Method= 1
Parabolic Critical Depth
Global Vel Dist=  1 , 1 , 1
Global Log Level= 0
CheckData=True
Encroach Param= -1, 0, 0, 0
BEGIN DESCRIPTION:
Multiple Run
END DESCRIPTION:

--- UNT 115 IN BUCR.f01 (steady flow) ---

Flow Title=Multiple
Number of Profiles=7
Profile Names=10-year,25-year,50-year,1pct_min,100-year,1pct_plu,500-year
River Rch & RM= UNT 115 IN BUCR,Reach-1,1546
    1309    1829    2267    2051    2774    3751    4136
Boundary for River Rch & Prof#=UNT 115 IN BUCR,Reach-1,1
Up Type=0
Dn Type=3
Dn Slope=0.005
Boundary for River Rch & Prof#=UNT 115 IN BUCR,Reach-1,2
Up Type=0
Dn Type=3
Dn Slope=0.005
Boundary for River Rch & Prof#=UNT 115 IN BUCR,Reach-1,3
Up Type=0
Dn Type=3
Dn Slope=0.005
Boundary for River Rch & Prof#=UNT 115 IN BUCR,Reach-1,4
Up Type=0
Dn Type=3
Dn Slope=0.005
Boundary for River Rch & Prof#=UNT 115 IN BUCR,Reach-1,5
Up Type=0
Dn Type=3
Dn Slope=0.005
Boundary for River Rch & Prof#=UNT 115 IN BUCR,Reach-1,6
Up Type=0
Dn Type=3
Dn Slope=0.005
Boundary for River Rch & Prof#=UNT 115 IN BUCR,Reach-1,7
Up Type=0
Dn Type=3
Dn Slope=0.005

--- UNT 115 IN BUCR.g01 (geometry) ---

Geom Title=Existing Conditions

River Reach=UNT 115 IN BUCR,Reach-1
Reach XY= 30
      3627351.75     10509933.00      3627377.50     10509923.00
      3627443.75     10509928.00      3627480.50     10509900.00
      3627522.25     10509899.00      3627555.00     10509881.00
      3627590.75     10509876.00      3627693.75     10509831.00
      3627739.00     10509822.00      3627770.25     10509823.00
      3627976.50     10509879.00      3628102.25     10509971.00
      3628281.75     10510009.00      3628351.75     10510041.00
      3628405.50     10510051.00      3628451.75     10510072.00
      3628560.25     10510044.00      3628629.75     10510008.00
      3628661.25     10510015.00      3628693.75     10510047.00
      3628729.50     10510050.00      3628760.00     10510016.00
      3628800.00     10509998.00      3628830.50     10509999.00
      3628923.75     10510066.00      3628956.25     10510059.00
      3628980.25     10510021.00      3629021.50     10510010.00
      3629066.00     10510021.00      3629144.25     10509935.00

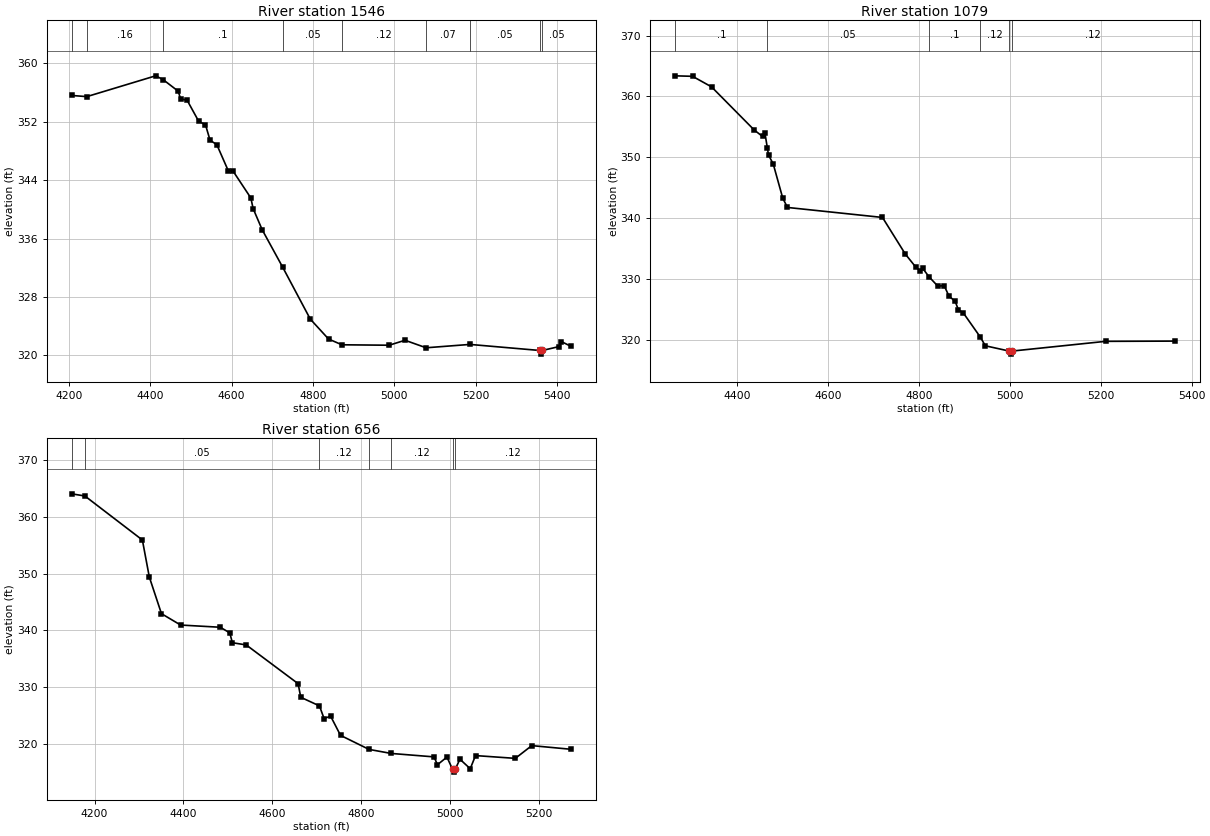
Type RM Length L Ch R = 1,1546,467,467,467
BEGIN DESCRIPTION:
UNT 115 IN BUCR 2.0
END DESCRIPTION:
XS GIS Cut Line= 2
      3627423.80     10510533.86      3627977.18     10509437.95
#Sta/Elev= 30
  4207.0  355.61  4244.3  355.45  4413.4  358.30  4431.6  357.79  4468.8  356.20
  4474.7  355.17  4491.2  354.92  4519.3  352.07  4536.0  351.59  4547.2  349.48
  4563.9  348.86  4592.0  345.29  4602.9  345.32  4647.5  341.56  4653.1  340.11
  4675.4  337.20  4726.0  332.05  4793.6  324.96  4838.5  322.23  4871.4  321.44
  4987.5  321.38  5026.5  322.06  5078.3  321.03  5186.1  321.49  5357.9  320.66
  5360.7  320.16  5363.9  320.66  5405.5  321.20  5411.1  321.87  5434.7  321.22
#Mann=9,-1,0
  4207.0     0.1       0  4244.3    0.16       0  4431.6     0.1       0
  4726.0    0.05       0  4871.4    0.12       0  5078.3    0.07       0
  5186.1    0.05       0  5357.9    0.07       0  5363.9    0.05       0
Bank Sta=5357.9,5363.9
Exp/Cntr=0.3,0.1

Type RM Length L Ch R = 1,1079,423,423,423
BEGIN DESCRIPTION:
UNT 115 IN BUCR 1.5
END DESCRIPTION:
XS GIS Cut Line= 2
      3627998.86     10510696.68      3628313.37     10509644.69
#Sta/Elev= 30
  4264.7  363.38  4302.8  363.30  4344.5  361.57  4438.5  354.47  4456.7  353.42
  4461.9  353.97  4467.4  351.46  4469.8  350.37  4480.2  348.89  4501.1  343.28
  4511.5  341.76  4720.3  340.12  4770.4  334.12  4793.3  331.98  4803.5  331.35
  4808.7  331.76  4822.9  330.35  4841.8  328.85  4856.0  328.91  4866.4  327.22
  4880.2  326.32  4887.3  324.93  4897.7  324.47  4935.5  320.46  4946.4  319.04
  4999.1  318.17  5001.8  317.67  5005.1  318.17  5210.8  319.77  5362.7  319.81
#Mann=6,-1,0
  4264.7     0.1       0  4467.4    0.05       0  4822.9     0.1       0
  4935.5    0.12       0  4999.1    0.07       0  5005.1    0.12       0
Bank Sta=4999.1,5005.1
Exp/Cntr=0.3,0.1

Type RM Length L Ch R = 1,656,0,0,0
BEGIN DESCRIPTION:
UNT 115 IN BUCR 1.0
END DESCRIPTION:
XS GIS Cut Line= 2
      3628172.47     10510750.91      3628747.57     10509785.18
#Sta/Elev= 30
  4148.3  364.09  4178.1  363.71  4307.5  355.94  4323.1  349.41  4350.4  342.94
  4393.6  340.93  4482.8  340.54  4504.2  339.55  4510.0  337.81  4541.2  337.42
  4658.0  330.58  4663.9  328.18  4706.0  326.66  4716.4  324.42  4731.1  324.85
  4753.4  321.46  4817.6  318.98  4867.2  318.27  4963.9  317.66  4971.5  316.27
  4992.9  317.63  5005.5  315.47  5008.3  314.97  5011.5  315.47  5022.1  317.25
  5045.3  315.57  5057.2  317.89  5146.8  317.40  5183.8  319.65  5272.3  319.00
#Mann=7,-1,0
  4148.3     0.1       0  4178.1    0.05       0  4706.0    0.12       0
  4817.6    0.16       0  4867.2    0.12       0  5005.5    0.07       0
  5011.5    0.12       0
Bank Sta=5005.5,5011.5
Exp/Cntr=0.3,0.1

Chan Stop Cuts=-1