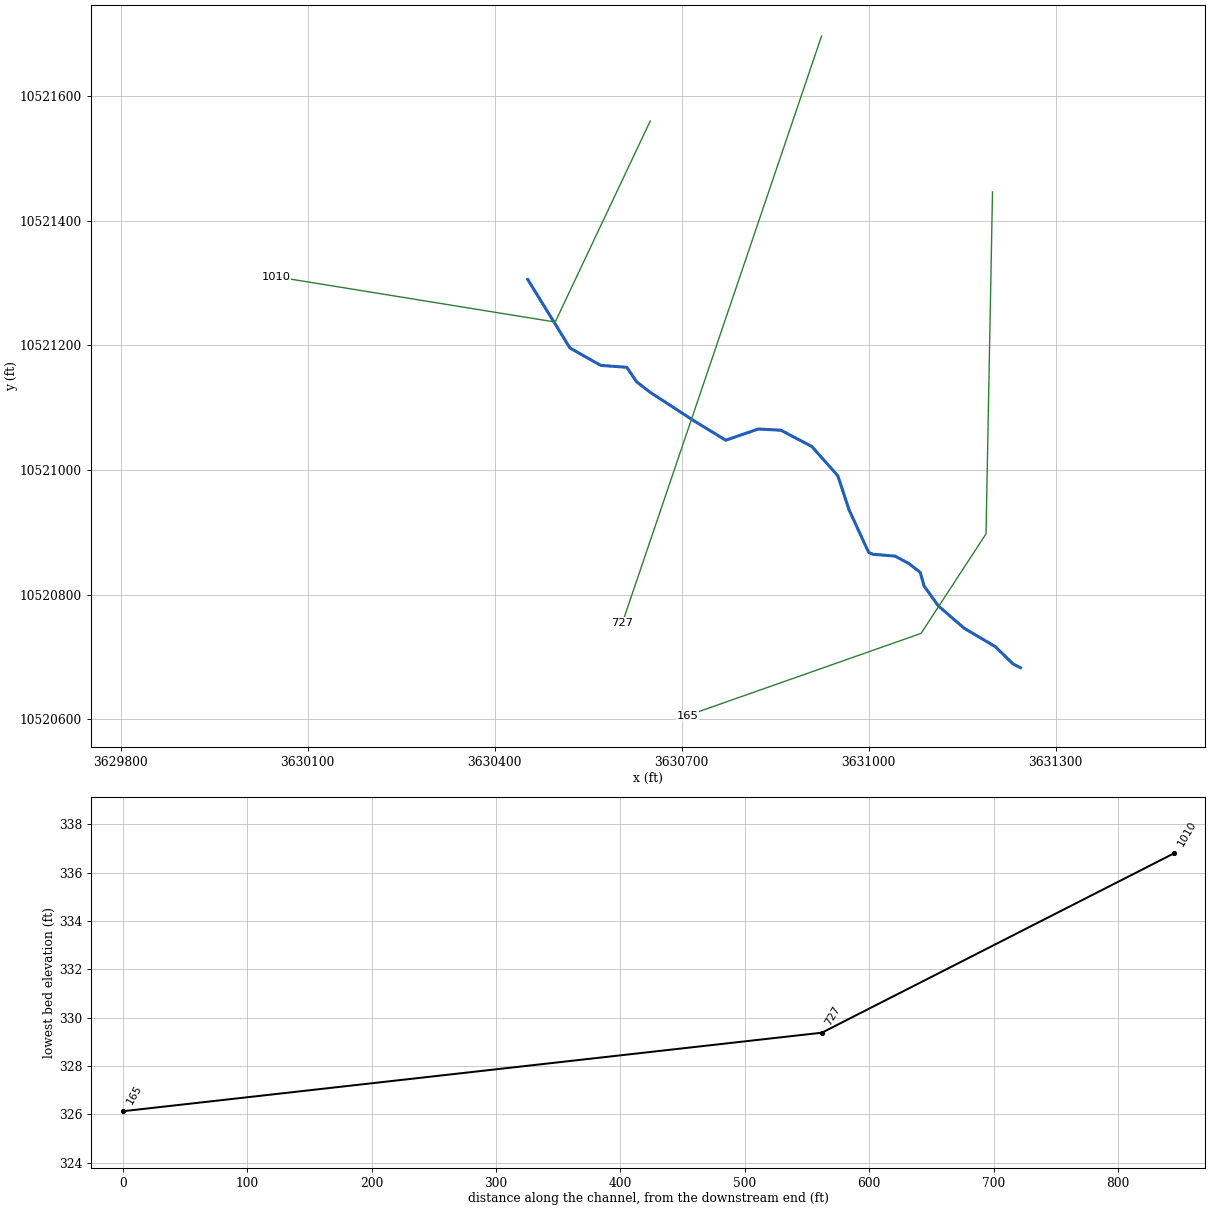
--- UNT 120 IN BUCR.prj (project) ---

Proj Title=UNT 120 IN BUCR Base Level Engineering
Current Plan=p01
Default Exp/Contr=0.3,0.1
English Units
Geom File=g01
Flow File=f01
Plan File=p01
BEGIN DESCRIPTION:
UNT 120 IN BUCR
END DESCRIPTION:

--- UNT 120 IN BUCR.p01 (plan) ---

Plan Title=Multiple Run
Short Identifier=Multiple
Geom File=g01
Flow File=f01
Subcritical Flow
K Sum by GR= 0
Std Step Tol= 0.01
Critical Tol= 0.01
Num of Std Step Trials= 20
Max Error Tol= 0.3
Flow Tol Ratio= 0.001
Split Flow NTrial= 30
Split Flow Tol= 0.02
Split Flow Ratio= 0.02
Log Output Level= 0
Friction Slope Method= 1
Unsteady Friction Slope Method= 2
Unsteady Bridges Friction Slope Method= 1
Parabolic Critical Depth
Global Vel Dist=  1 , 1 , 1
Global Log Level= 0
CheckData=True
Encroach Param= -1, 0, 0, 0
BEGIN DESCRIPTION:
Multiple Run
END DESCRIPTION:

--- UNT 120 IN BUCR.f01 (steady flow) ---

Flow Title=Multiple
Number of Profiles=7
Profile Names=10-year,25-year,50-year,1pct_min,100-year,1pct_plu,500-year
River Rch & RM= UNT 120 IN BUCR,Reach-1,1010
     227     283     326     276     373     504     483
Boundary for River Rch & Prof#=UNT 120 IN BUCR,Reach-1,1
Up Type=0
Dn Type=3
Dn Slope=0.005
Boundary for River Rch & Prof#=UNT 120 IN BUCR,Reach-1,2
Up Type=0
Dn Type=3
Dn Slope=0.005
Boundary for River Rch & Prof#=UNT 120 IN BUCR,Reach-1,3
Up Type=0
Dn Type=3
Dn Slope=0.005
Boundary for River Rch & Prof#=UNT 120 IN BUCR,Reach-1,4
Up Type=0
Dn Type=3
Dn Slope=0.005
Boundary for River Rch & Prof#=UNT 120 IN BUCR,Reach-1,5
Up Type=0
Dn Type=3
Dn Slope=0.005
Boundary for River Rch & Prof#=UNT 120 IN BUCR,Reach-1,6
Up Type=0
Dn Type=3
Dn Slope=0.005
Boundary for River Rch & Prof#=UNT 120 IN BUCR,Reach-1,7
Up Type=0
Dn Type=3
Dn Slope=0.005

--- UNT 120 IN BUCR.g01 (geometry) ---

Geom Title=Existing Conditions

River Reach=UNT 120 IN BUCR,Reach-1
Reach XY= 24
      3630453.00     10521306.00      3630520.75     10521196.00
      3630570.25     10521168.00      3630612.00     10521165.00
      3630627.50     10521142.00      3630649.25     10521125.00
      3630720.00     10521079.00      3630770.75     10521048.00
      3630823.00     10521066.00      3630859.25     10521064.00
      3630908.75     10521038.00      3630950.50     10520991.00
      3630968.75     10520936.00      3631000.00     10520868.00
      3631007.00     10520865.00      3631042.50     10520862.00
      3631064.75     10520850.00      3631082.75     10520836.00
      3631089.00     10520814.00      3631112.00     10520782.00
      3631153.75     10520746.00      3631203.00     10520717.00
      3631231.75     10520689.00      3631243.50     10520683.00

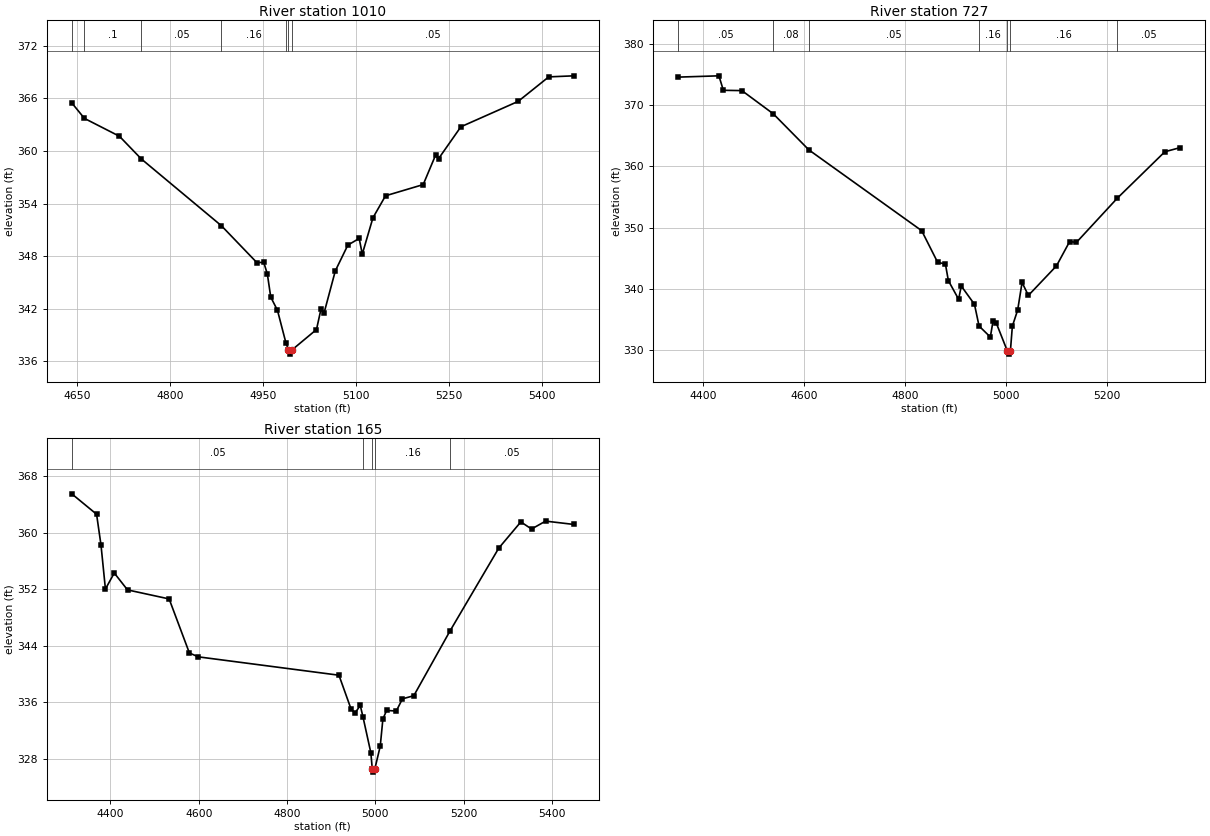
Type RM Length L Ch R = 1,1010,283,283,283
BEGIN DESCRIPTION:
UNT 120 IN BUCR 2.0
END DESCRIPTION:
XS GIS Cut Line= 3
      3630649.63     10521560.23      3630497.11     10521237.59
      3630049.64     10521310.18
#Sta/Elev= 30
  4640.9  365.49  4661.3  363.72  4717.8  361.68  4753.1  359.09  4882.4  351.46
  4939.6  347.25  4950.7  347.28  4956.5  345.95  4962.0  343.31  4972.8  341.81
  4986.6  338.05  4990.6  337.30  4993.3  336.80  4996.6  337.30  5035.8  339.61
  5043.0  341.92  5048.1  341.52  5066.2  346.31  5086.4  349.25  5104.7  350.01
  5109.7  348.22  5126.9  352.37  5147.2  354.88  5208.0  356.16  5227.9  359.51
  5232.9  359.13  5268.8  362.76  5361.2  365.66  5410.6  368.46  5451.1  368.58
#Mann=7,-1,0
  4640.9    0.08       0  4661.3     0.1       0  4753.1    0.05       0
  4882.4    0.16       0  4986.6    0.05       0  4990.6    0.03       0
  4996.6    0.05       0
Bank Sta=4990.6,4996.6
Exp/Cntr=0.3,0.1

Type RM Length L Ch R = 1,727,562,562,562
BEGIN DESCRIPTION:
Mapping XS 3413b5ec
END DESCRIPTION:
XS GIS Cut Line= 2
      3630924.47     10521696.38      3630605.03     10520755.42
#Sta/Elev= 30
  4350.9  374.55  4431.4  374.76  4440.2  372.40  4476.9  372.35  4539.1  368.56
  4609.5  362.68  4832.7  349.51  4864.3  344.35  4879.7  344.07  4885.5  341.37
  4905.8  338.33  4911.1  340.48  4937.2  337.50  4946.3  333.96  4968.6  332.17
  4973.9  334.74  4980.5  334.42  5002.3  329.88  5005.1  329.38  5008.3  329.88
  5012.2  333.94  5022.7  336.57  5031.4  341.06  5043.9  338.95  5099.5  343.77
  5125.6  347.74  5138.9  347.59  5219.7  354.79  5314.0  362.38  5344.6  363.06
#Mann=7,-1,0
  4350.9    0.05       0  4539.1    0.08       0  4609.5    0.05       0
  4946.3    0.16       0  5002.3    0.07       0  5008.3    0.16       0
  5219.7    0.05       0
Bank Sta=5002.3,5008.3
Exp/Cntr=0.3,0.1

Type RM Length L Ch R = 1,165,0,0,0
BEGIN DESCRIPTION:
UNT 120 IN BUCR 1.0
END DESCRIPTION:
XS GIS Cut Line= 4
      3631198.78     10521446.39      3631188.37     10520897.79
      3631084.20     10520738.07      3630709.22     10520606.13
#Sta/Elev= 30
  4312.5  365.50  4368.7  362.61  4378.7  358.25  4388.7  352.03  4408.7  354.30
  4438.7  351.91  4533.0  350.63  4578.8  342.99  4598.8  342.44  4917.5  339.84
  4944.6  335.11  4953.7  334.48  4965.8  335.56  4972.1  333.89  4989.7  328.88
  4992.9  326.63  4995.7  326.13  4998.9  326.63  5011.0  329.80  5017.0  333.65
  5025.5  334.86  5047.3  334.77  5061.3  336.50  5087.0  336.94  5168.8  346.08
  5279.4  357.82  5329.4  361.53  5353.6  360.52  5385.4  361.64  5449.4  361.17
#Mann=5,-1,0
  4312.5    0.05       0  4972.1    0.16       0  4992.9    0.07       0
  4998.9    0.16       0  5168.8    0.05       0
Bank Sta=4992.9,4998.9
Exp/Cntr=0.3,0.1

Chan Stop Cuts=-1