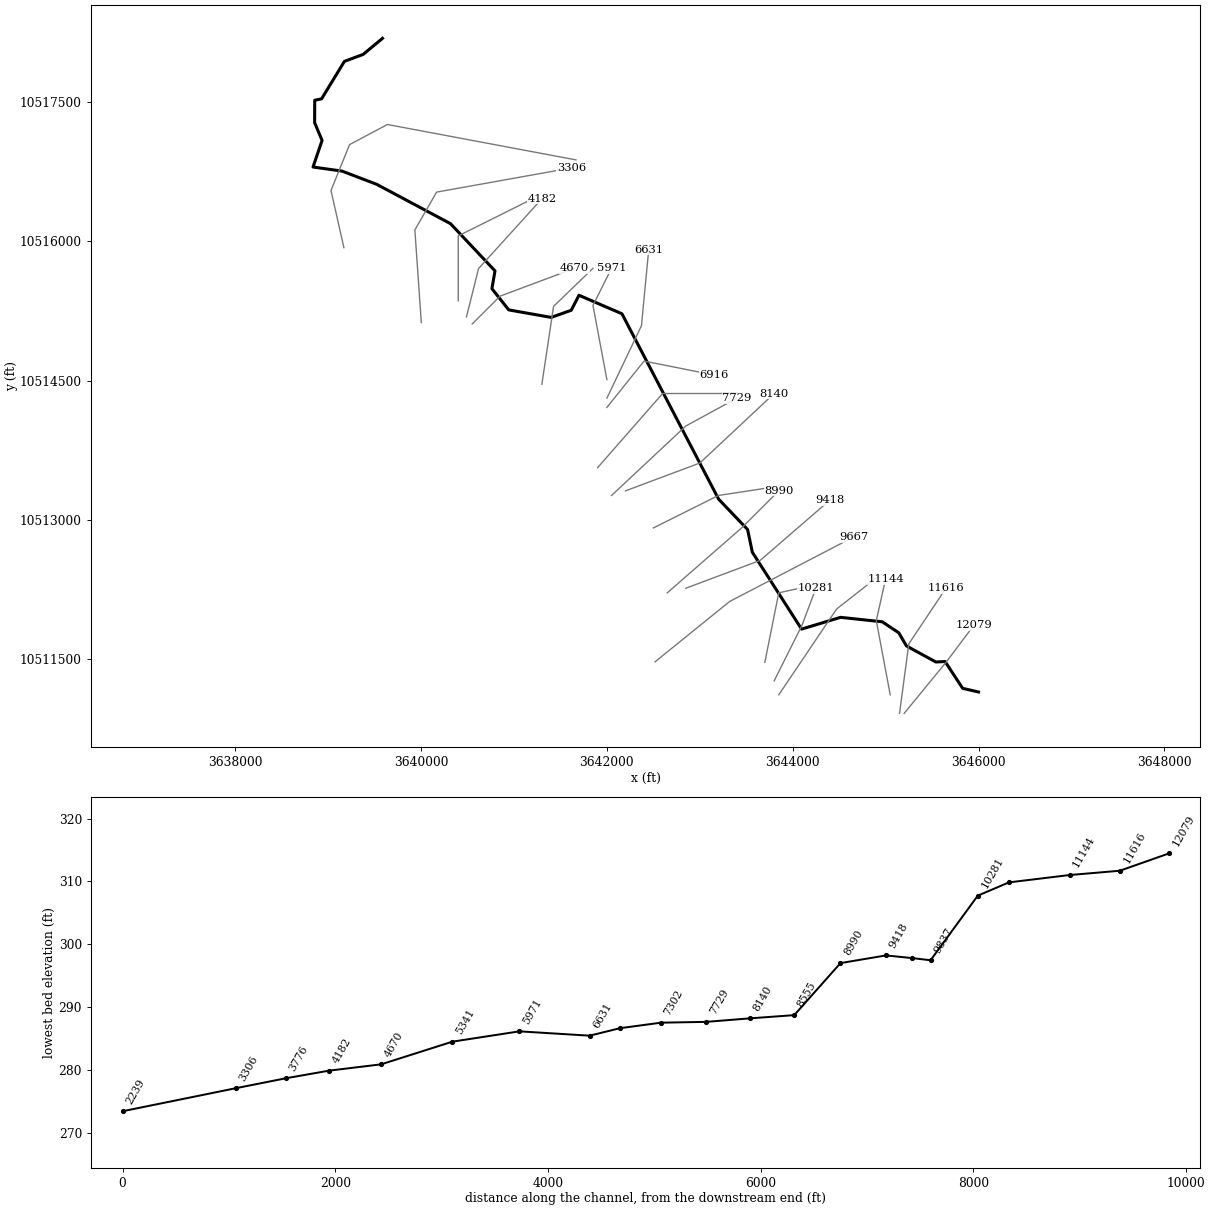
--- UNT 123 IN BUCR.prj (project) ---

Proj Title=UNT 123 IN BUCR Base Level Engineering
Current Plan=p01
Default Exp/Contr=0.3,0.1
English Units
Geom File=g01
Flow File=f01
Plan File=p01
Y Axis Title=Elevation
X Axis Title(PF)=Main Channel Distance
X Axis Title(XS)=Station
BEGIN DESCRIPTION:
UNT 123 IN BUCR
END DESCRIPTION:
DSS Export Rating Curves= 0
DSS Export Rating Curve Sorted= 0
DSS Export Volume Flow Curves= 0
DXF OffsetX= 0
DXF OffsetY= 0
DXF ScaleX= 1
DXF ScaleY= 10

--- UNT 123 IN BUCR.p01 (plan) ---

Plan Title=Multiple Run
Short Identifier=Multiple
Geom File=g01
Flow File=f01
Subcritical Flow
K Sum by GR= 0
Std Step Tol= 0.01
Critical Tol= 0.01
Num of Std Step Trials= 20
Max Error Tol= 0.3
Flow Tol Ratio= 0.001
Split Flow NTrial= 30
Split Flow Tol= 0.02
Split Flow Ratio= 0.02
Log Output Level= 0
Friction Slope Method= 1
Unsteady Friction Slope Method= 2
Unsteady Bridges Friction Slope Method= 1
Parabolic Critical Depth
Global Vel Dist=  1 , 1 , 1
Global Log Level= 0
CheckData=True
Encroach Param= -1, 0, 0, 0
BEGIN DESCRIPTION:
Multiple Run
END DESCRIPTION:

--- UNT 123 IN BUCR.f01 (steady flow) ---

Flow Title=Multiple
Number of Profiles=7
Profile Names=10-year,25-year,50-year,1pct_min,100-year,1pct_plu,500-year
River Rch & RM= UNT 123 IN BUCR,Reach-1,12079
    1668    2376    2984    2736    3700    5003    5686
River Rch & RM= UNT 123 IN BUCR,Reach-1,9667
    2066    2951    3710    3400    4598    6219    7056
Boundary for River Rch & Prof#=UNT 123 IN BUCR,Reach-1,1
Up Type=0
Dn Type=3
Dn Slope=0.005
Boundary for River Rch & Prof#=UNT 123 IN BUCR,Reach-1,2
Up Type=0
Dn Type=3
Dn Slope=0.005
Boundary for River Rch & Prof#=UNT 123 IN BUCR,Reach-1,3
Up Type=0
Dn Type=3
Dn Slope=0.005
Boundary for River Rch & Prof#=UNT 123 IN BUCR,Reach-1,4
Up Type=0
Dn Type=3
Dn Slope=0.005
Boundary for River Rch & Prof#=UNT 123 IN BUCR,Reach-1,5
Up Type=0
Dn Type=3
Dn Slope=0.005
Boundary for River Rch & Prof#=UNT 123 IN BUCR,Reach-1,6
Up Type=0
Dn Type=3
Dn Slope=0.005
Boundary for River Rch & Prof#=UNT 123 IN BUCR,Reach-1,7
Up Type=0
Dn Type=3
Dn Slope=0.005

--- UNT 123 IN BUCR.g01 (geometry) ---

Geom Title=Existing Conditions
Program Version=4.10

River Reach=UNT 123 IN BUCR ,Reach-1
Reach XY= 30
        3646000.       10511141.       3645829.5       10511180.
       3645639.5       10511470.      3645541.25       10511464.
      3645223.75       10511638.      3645141.75       10511779.
       3644963.5       10511898.      3644514.75       10511946.
        3644095.       10511819.      3643565.25       10512648.
      3643514.25       10512893.        3643202.       10513221.
      3642161.75       10515220.        3641699.       10515420.
      3641615.75       10515258.       3641399.5       10515181.
        3640943.       10515262.        3640762.       10515491.
        3640795.       10515683.      3640316.25       10516192.
       3639522.5       10516616.      3639148.75       10516759.
      3638836.25       10516803.      3638933.75       10517090.
       3638853.5       10517281.       3638854.5       10517523.
      3638928.75       10517539.      3639173.75       10517942.
      3639376.25       10518018.      3639584.25       10518191.

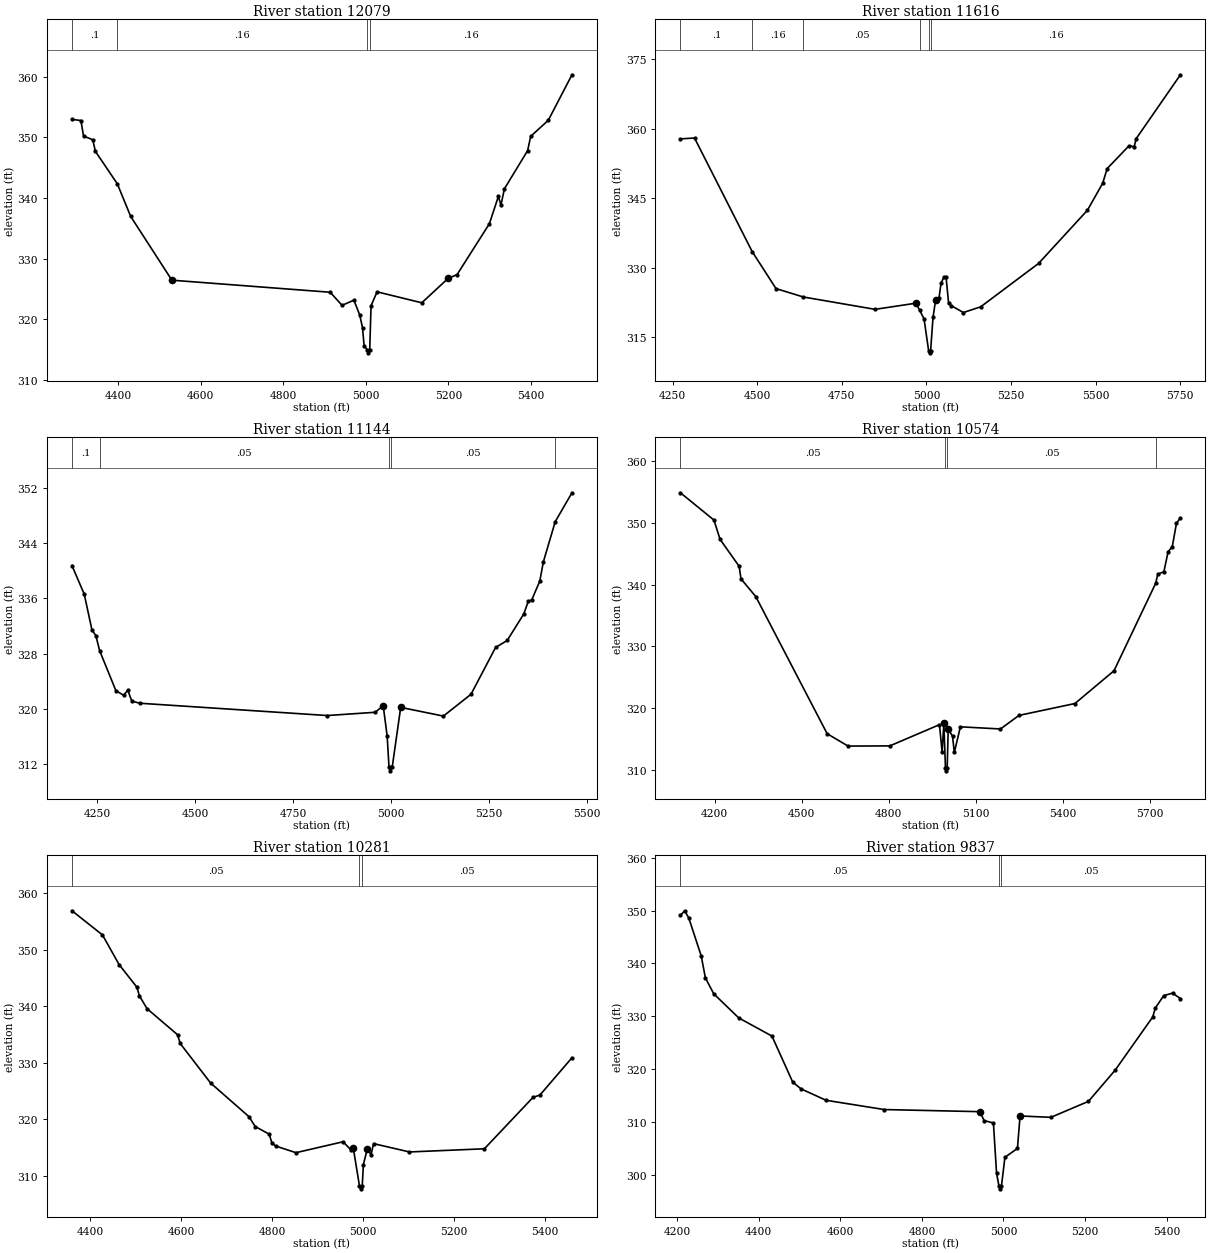
Type RM Length L Ch R = 1 ,12079   ,463,463,463
BEGIN DESCRIPTION:
UNT 123 IN BUCR 20.0
END DESCRIPTION:
XS GIS Cut Line= 3
      3645199.59     10510910.17      3645649.61     10511460.19
      3645949.63     10511860.22
#Sta/Elev= 30
  4288.7  352.98  4310.3  352.79  4316.7  350.24    4339  349.61  4345.4   347.7
  4398.4  342.36  4430.9  336.96  4530.6  326.44  4913.9  324.45  4942.7  322.29
  4971.4  323.14  4985.7  320.65  4992.2   318.6  4996.1  315.62  5003.7  314.95
  5006.4  314.45  5009.7  314.95  5012.9  322.22  5027.5  324.52  5135.8  322.71
  5199.4  326.73  5221.2  327.36  5299.4  335.75  5321.2  340.26  5327.5  338.85
  5335.8  341.52  5392.1  347.83  5399.4  350.17  5442.1  352.83  5499.4  360.34
#Mann= 4 ,-1 , 0
  4288.7      .1       0  4398.4     .16       0  5003.7     .07       0
  5009.7     .16       0
Bank Sta=4530.6,5199.4
XS Rating Curve= 0 ,0
Exp/Cntr=0.3,0.1

Type RM Length L Ch R = 1 ,11616   ,472,472,472
BEGIN DESCRIPTION:
UNT 123 IN BUCR 19.0
END DESCRIPTION:
XS GIS Cut Line= 3
       3645149.6     10510910.16      3645249.61     10511660.19
      3645649.62      10512260.2
#Sta/Elev= 30
  4272.9  357.82  4314.5  358.01    4485  333.51  4555.4  325.54  4636.2  323.73
    4848  321.07    4969  322.39  4979.7   320.9    4993     319  5006.4  312.19
  5009.1  311.69  5012.4  312.19  5019.5  319.35    5027     323  5037.1  323.46
  5043.1  326.68  5052.1  328.08  5058.1  327.98  5065.6  322.34  5073.1  321.88
  5109.2  320.38  5160.3  321.61  5331.5  330.97  5475.8  342.43  5520.8  348.23
  5534.3  351.43  5598.9  356.34    5614  356.13    5620  357.88  5750.7  371.64
#Mann= 6 ,-1 , 0
  4272.9      .1       0    4485     .16       0  4636.2     .05       0
  4979.7     .16       0  5006.4     .07       0  5012.4     .16       0
Bank Sta=4969,5027
XS Rating Curve= 0 ,0
Exp/Cntr=0.3,0.1

Type RM Length L Ch R = 1 ,11144   ,570,570,570
BEGIN DESCRIPTION:
UNT 123 IN BUCR 18.0
END DESCRIPTION:
XS GIS Cut Line= 3
       3645049.6     10511110.23      3644899.61     10511910.19
      3644999.61     10512360.21
#Sta/Elev= 30
  4186.3  340.74  4217.6  336.59  4237.1  331.45  4247.3  330.57  4256.9   328.4
  4298.2  322.63  4317.7  321.96  4328.7  322.67  4338.9  321.11  4359.2   320.8
  4837.4  319.02  4959.5  319.49  4979.9  320.44    4990  316.05  4994.7  311.51
  4997.4  311.01  5000.7  311.51  5002.8  311.51  5024.5   320.2  5133.4  318.94
  5203.8   322.1  5266.5  328.88    5296  329.89  5338.3  333.72  5349.8  335.56
  5358.7  335.77  5379.2  338.49  5388.2  341.26  5418.5  347.09  5461.2  351.28
#Mann= 5 ,-1 , 0
  4186.3      .1       0  4256.9     .05       0  4994.7     .03       0
  5000.7     .05       0  5418.5     .16       0
Bank Sta=4979.9,5024.5
XS Rating Curve= 0 ,0
Exp/Cntr=0.3,0.1

Type RM Length L Ch R = 1 ,10574   ,293,293,293
BEGIN DESCRIPTION:
UNT 123 IN BUCR 17.0
END DESCRIPTION:
XS GIS Cut Line= 3
      3643849.62      10511110.2      3644472.34      10512035.9
      3644949.61     10512410.19
#Sta/Elev= 30
  4082.4  354.87  4197.9  350.45  4218.9  347.33  4284.8  342.96  4290.9  340.93
  4341.8  338.07  4587.8  315.85  4659.8  313.85  4803.7  313.88  4974.7  317.32
  4983.7  312.88  4989.7  317.53  4995.3  310.34  4998.1  309.84  5001.3  310.34
  5004.7   316.6  5019.7  315.45  5025.7  312.81  5046.7  316.97  5184.7  316.62
  5248.7  318.82  5441.2  320.74  5575.9  326.05  5719.3   340.2  5726.8   341.7
  5747.6  342.08  5762.1   345.3  5776.6  346.16    5791  349.93  5804.6  350.81
#Mann= 4 ,-1 , 0
  4082.4     .05       0  4995.3     .03       0  5001.3     .05       0
  5719.3     .16       0
Bank Sta=4989.7,5004.7
XS Rating Curve= 0 ,0
Exp/Cntr=0.3,0.1

Type RM Length L Ch R = 1 ,10281   ,444,444,444
BEGIN DESCRIPTION:
UNT 123 IN BUCR 16.0
END DESCRIPTION:
XS GIS Cut Line= 3
      3643799.62     10511260.22      3644099.61     10511860.19
      3644249.61      10512260.2
#Sta/Elev= 30
  4360.7  356.88  4427.7  352.61  4464.1  347.38  4503.2  343.38  4508.8  341.84
  4525.6  339.57  4592.7  334.96  4598.2  333.44  4665.3  326.42  4749.2   320.5
  4763.2  318.74  4793.9  317.39  4799.5  315.89  4807.9   315.3  4852.6  314.12
    4956  316.05  4972.8  314.66  4978.4  314.97  4992.1  308.23  4994.9  307.73
  4998.1  308.23  5000.7  312.02  5009.1  314.77  5017.5  313.77  5023.1  315.72
  5101.8  314.25  5266.4  314.81  5373.2   323.9  5388.4  324.31  5458.7   330.9
#Mann= 3 ,-1 , 0
  4360.7     .05       0  4992.1     .03       0  4998.1     .05       0
Bank Sta=4978.4,5009.1
XS Rating Curve= 0 ,0
Exp/Cntr=0.3,0.1

Type RM Length L Ch R = 1 ,9837    ,170,170,170
BEGIN DESCRIPTION:
UNT 123 IN BUCR 15.0
END DESCRIPTION:
XS GIS Cut Line= 3
       3643699.6     10511460.16      3643849.61     10512210.19
      3644299.65      10512310.2
#Sta/Elev= 30
    4208  349.07  4218.2  349.95  4228.4  348.61    4259  341.41  4269.2  337.28
  4289.6  334.28  4350.8  329.73  4432.4  326.29  4483.4  317.59  4503.8  316.32
    4565  314.17  4707.7  312.42  4942.3  312.02  4952.5  310.34  4975.4  309.88
  4983.1  300.37  4989.1  297.95  4991.8  297.45  4995.1  297.95  5003.6   303.4
  5034.3  305.08  5040.7  311.21  5116.3  310.95  5208.5  313.97  5273.8  319.85
    5366   329.9  5372.4  331.59  5392.9  333.93  5414.6   334.4  5433.9  333.38
#Mann= 3 ,-1 , 0
    4208     .05       0  4989.1     .03       0  4995.1     .05       0
Bank Sta=4942.3,5040.7
XS Rating Curve= 0 ,0
Exp/Cntr=0.3,0.1

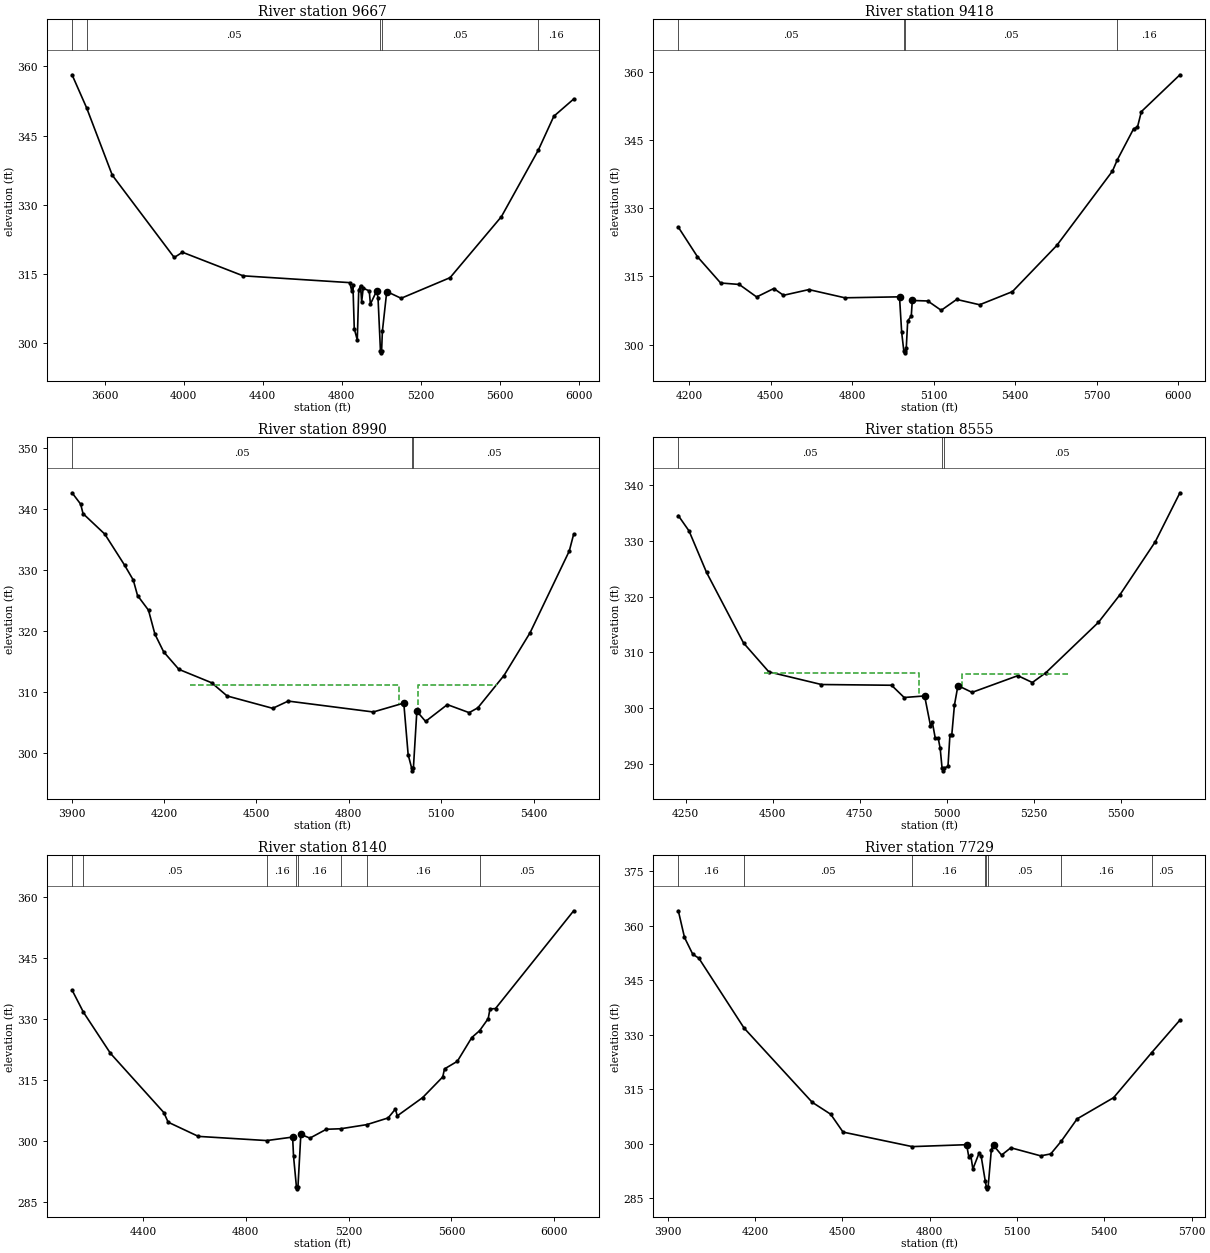
Type RM Length L Ch R = 1 ,9667    ,249,249,249
BEGIN DESCRIPTION:
Mapping XS 66487e2d
END DESCRIPTION:
XS GIS Cut Line= 3
      3642517.93     10511466.16      3643320.87      10512117.2
      3644653.35     10512811.65
#Sta/Elev= 30
  3435.9  358.19  3509.3  351.03  3639.2  336.39  3952.5   318.5  3994.1  319.64
  4300.6  314.52  4840.3  313.04  4850.3  311.16    4856  312.61  4862.9  303.01
  4878.1   300.6  4885.4  311.37  4894.5  312.39  4900.2  308.88    4908  311.84
  4938.7  311.24  4944.4  308.37  4975.6  311.21  4982.9   309.8  4995.2  298.29
  4997.9  297.79  5001.2  298.29    5005  302.48  5027.1  311.11  5099.7  309.64
  5347.3  314.12  5606.8  327.37  5793.6  341.84  5871.9  349.18  5972.2  352.92
#Mann= 5 ,-1 , 0
  3435.9     .16       0  3509.3     .05       0  4995.2     .03       0
  5001.2     .05       0  5793.6     .16       0
Bank Sta=4975.6,5027.1
XS Rating Curve= 0 ,0
Exp/Cntr=0.3,0.1

Type RM Length L Ch R = 1 ,9418    ,428,428,428
BEGIN DESCRIPTION:
UNT 123 IN BUCR 14.0
END DESCRIPTION:
XS GIS Cut Line= 3
      3642849.59     10512260.18      3643649.61     10512560.19
      3644399.62      10513210.2
#Sta/Elev= 30
  4160.2  325.82  4230.5  319.34    4316  313.56  4384.5  313.24  4448.6  310.49
  4511.8  312.35  4547.4  310.86  4640.8  312.11  4773.4  310.31  4974.6  310.52
  4982.6   302.7  4990.3  298.72    4993  298.22  4996.3  298.72  4999.5  299.33
  5004.8  305.26  5017.9  306.28  5021.7  309.72  5078.7  309.61  5128.1  307.56
  5185.1  309.95  5269.6  308.78  5390.2  311.66  5553.6   321.8  5758.7  338.14
  5776.5   340.6  5836.6  347.43  5850.8   347.8  5865.1   351.2  6007.1  359.29
#Mann= 4 ,-1 , 0
  4160.2     .05       0  4990.3     .03       0  4996.3     .05       0
  5776.5     .16       0
Bank Sta=4974.6,5021.7
XS Rating Curve= 0 ,0
Exp/Cntr=0.3,0.1

Type RM Length L Ch R = 1 ,8990    ,435,435,435
BEGIN DESCRIPTION:
UNT 123 IN BUCR 13.0
END DESCRIPTION:
XS GIS Cut Line= 3
      3642649.64     10512210.21      3643449.61     10512910.19
      3643849.63     10513310.21
#Sta/Elev= 30
  3901.7  342.68  3929.7  340.81  3937.3  339.26    4008  335.89    4072  330.81
  4100.5  328.34  4114.3   325.8  4149.9  323.39  4170.7  319.46  4199.2  316.54
  4248.6  313.67  4354.9  311.47  4405.2   309.3  4553.2  307.27  4603.5  308.46
  4879.7  306.67  4978.8  308.13    4993  299.65  5004.1   297.5  5006.9     297
  5010.1   297.5  5021.2  306.79  5049.5  305.12  5120.2  307.88    5191  306.56
  5219.2  307.35  5304.1  312.66  5388.9  319.69  5516.2  333.12  5530.4  335.88
#Mann= 3 ,-1 , 0
  3901.7     .05       0  5004.1     .03       0  5010.1     .05       0
#XS Ineff= 2 ,-1
 4283.75 4963.86311.0961 5025.23 5279.89311.0961
Permanent Ineff=
       F       F
Bank Sta=4978.8,5021.2
XS Rating Curve= 0 ,0
Exp/Cntr=0.3,0.1

Type RM Length L Ch R = 1 ,8555    ,415,415,415
BEGIN DESCRIPTION:
UNT 123 IN BUCR 12.0
END DESCRIPTION:
XS GIS Cut Line= 3
      3642499.58     10512910.17      3643199.61     10513260.19
      3643849.61     10513360.19
#Sta/Elev= 30
  4228.8  334.52  4259.6  331.77  4309.9  324.32  4416.1  311.66  4488.8  306.48
  4639.7  304.21    4841  304.08  4877.3  301.88    4936  302.16  4952.8  296.84
  4958.3   297.4  4966.7  294.54  4975.1  294.56  4980.7  292.75  4986.1  289.22
  4988.8  288.72  4992.1  289.22  5003.1  289.52  5008.7  295.15    5014  295.15
  5021.6   300.5  5031.7  304.02  5072.2   302.8  5203.7   305.8  5245.4  304.57
  5284.6  306.36  5435.1  315.37  5497.1  320.34  5598.3  329.83  5669.1  338.62
#Mann= 3 ,-1 , 0
  4228.8     .05       0  4986.1     .03       0  4992.1     .05       0
#XS Ineff= 2 ,-1
 4473.64 4919.09  306.28 5042.73    5350  306.13
Permanent Ineff=
       F       F
Bank Sta=4936,5031.7
XS Rating Curve= 0 ,0
Exp/Cntr=0.3,0.1

Type RM Length L Ch R = 1 ,8140    ,411,411,411
BEGIN DESCRIPTION:
UNT 123 IN BUCR 11.0
END DESCRIPTION:
XS GIS Cut Line= 3
      3642199.65      10513310.2      3642999.61     10513610.19
      3643799.58     10514360.16
#Sta/Elev= 30
  4124.6  337.13  4168.8  331.68  4274.1  321.54  4481.4  306.99  4498.4  304.61
  4615.8  301.12  4881.8  300.09  4982.4  300.95    4986  296.24  4997.2  288.71
    5000  288.21  5003.2  288.71  5014.4  301.62  5049.6  300.69  5113.5  302.87
    5170     303  5270.8  304.01  5353.9  305.66  5382.2  307.84  5389.5  306.17
  5488.2  310.67  5566.3  315.75  5573.2  317.73    5623  319.59  5679.2  325.44
  5709.8  327.14  5743.1   330.1    5750  332.47  5771.5  332.58  6075.5  356.64
#Mann= 8 ,-1 , 0
  4124.6     .16       0  4168.8     .05       0  4881.8     .16       0
  4997.2     .07       0  5003.2     .16       0    5170     .05       0
  5270.8     .16       0  5709.8     .05       0
Bank Sta=4982.4,5014.4
XS Rating Curve= 0 ,0
Exp/Cntr=0.3,0.1

Type RM Length L Ch R = 1 ,7729    ,427,427,427
BEGIN DESCRIPTION:
UNT 123 IN BUCR 10.0
END DESCRIPTION:
XS GIS Cut Line= 3
      3642049.61     10513260.19      3642849.61     10514010.19
      3643399.62      10514310.2
#Sta/Elev= 30
  3936.7   364.1  3957.9  356.77  3986.3  352.15  4007.3  351.05  4162.5  331.86
  4396.6  311.45  4460.1  308.16  4502.6  303.25  4740.3  299.26  4927.1  299.79
  4934.4  296.49  4941.2  296.95  4948.5  293.09  4969.5  297.41  4976.9  296.69
  4990.8  289.91  4994.9  288.15  4997.6  287.65  5000.9  288.15    5012  298.42
  5019.4  299.61  5047.1  296.93  5078.9  298.94  5181.4  296.72    5216  297.25
  5252.1  300.74  5306.7  306.89    5432  312.72  5562.3  325.06  5659.8  334.05
#Mann= 8 ,-1 , 0
  3936.7     .16       0  4162.5     .05       0  4740.3     .16       0
  4990.8     .05       0  4994.9     .03       0  5000.9     .05       0
  5252.1     .16       0  5562.3     .05       0
Bank Sta=4927.1,5019.4
XS Rating Curve= 0 ,0
Exp/Cntr=0.3,0.1

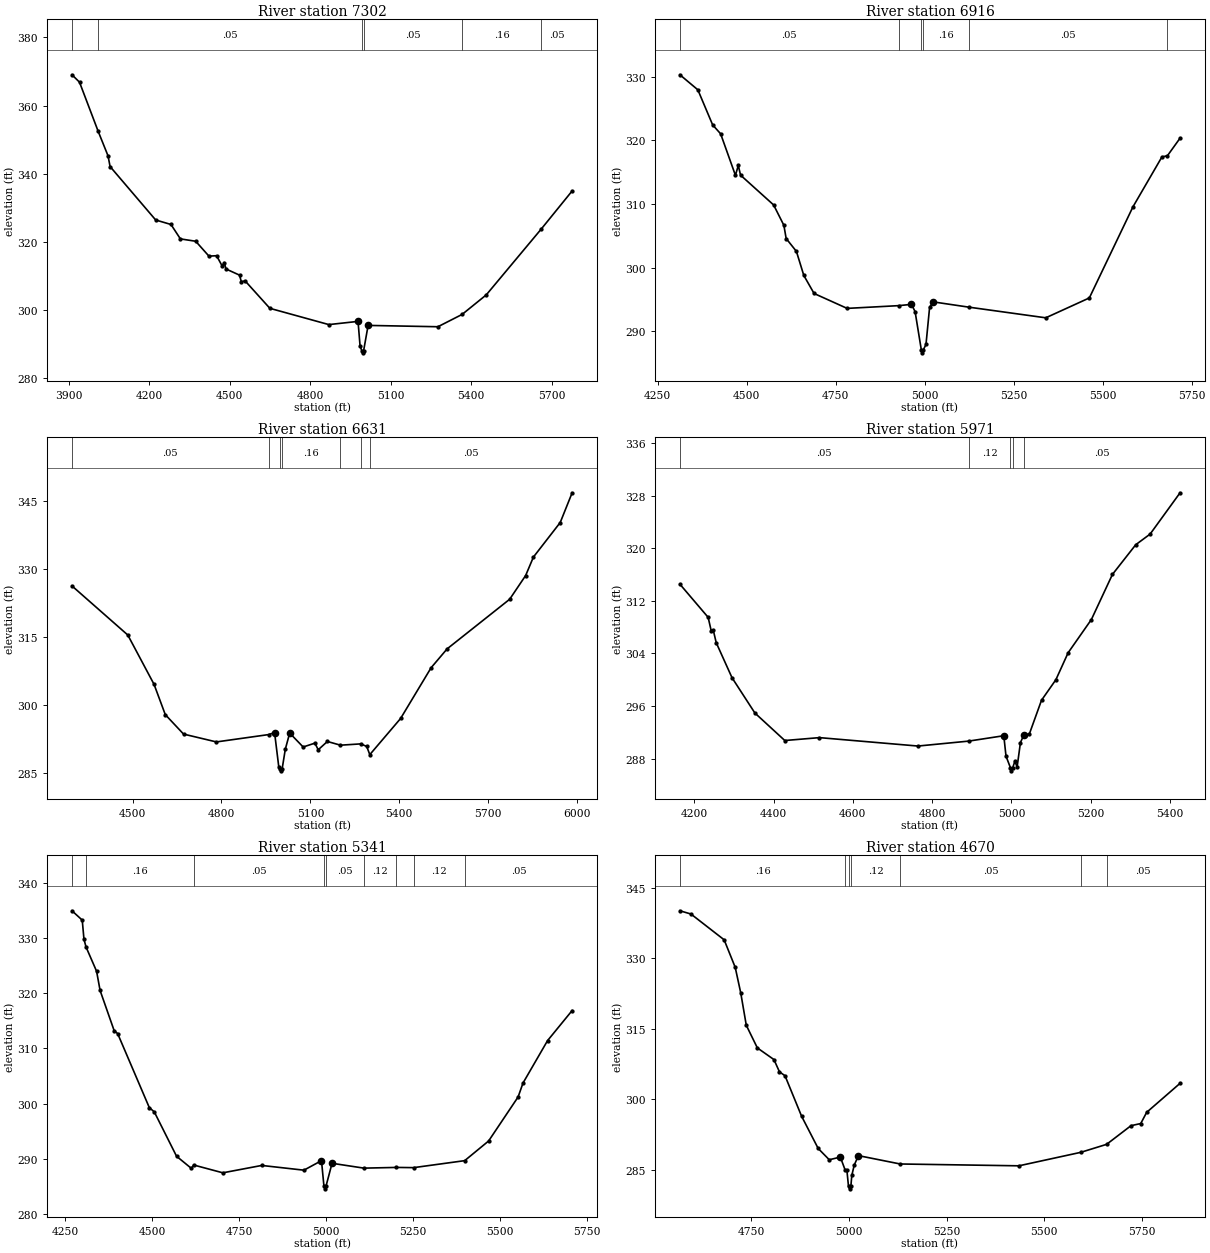
Type RM Length L Ch R = 1 ,7302    ,386,386,386
BEGIN DESCRIPTION:
UNT 123 IN BUCR 9.0
END DESCRIPTION:
XS GIS Cut Line= 3
      3641899.62      10513560.2      3642599.61     10514360.19
      3643399.61     10514360.19
#Sta/Elev= 30
  3912.7  369.03  3940.7  366.86  4010.4  352.42    4047  345.26  4054.6  342.13
  4224.5  326.46  4281.4  325.15  4316.5  320.92  4373.5  320.23  4422.8  315.87
  4451.3  315.99  4472.2  312.96  4479.8     314  4486.4   312.1  4536.7   310.3
  4543.4  308.39  4557.6  308.61  4649.7  300.57  4869.4   295.8  4978.2  296.74
  4985.7  289.58  4992.7  288.02  4995.5  287.52  4998.7  288.02  5015.7  295.56
  5275.7  295.17  5365.8  298.78  5455.7   304.5  5661.1  323.86  5775.7  334.98
#Mann= 6 ,-1 , 0
  3912.7     .16       0  4010.4     .05       0  4992.7     .03       0
  4998.7     .05       0  5365.8     .16       0  5661.1     .05       0
Bank Sta=4978.2,5015.7
XS Rating Curve= 0 ,0
Exp/Cntr=0.3,0.1

Type RM Length L Ch R = 1 ,6916    ,285,285,285
BEGIN DESCRIPTION:
UNT 123 IN BUCR 8.0
END DESCRIPTION:
XS GIS Cut Line= 3
      3641999.63     10514210.22      3642399.61     10514710.19
      3643149.58     10514560.19
#Sta/Elev= 30
  4312.5   330.3  4362.9  327.94  4404.5  322.43  4426.9  321.03  4468.5  314.51
  4476.5  316.06  4482.9  314.54  4575.8  309.86  4604.6  306.66    4611  304.59
  4639.8  302.57  4660.6  298.79  4689.4  295.96  4782.3  293.62  4927.1  294.05
    4963  294.25  4973.2  293.12  4990.6  287.14  4993.3  286.64  4996.6  287.14
  5003.8  287.96    5014  293.79  5024.2  294.64  5124.6  293.81  5340.3  292.14
  5462.7  295.26  5585.1  309.55  5666.6   317.4  5682.1  317.59  5717.6  320.35
#Mann= 6 ,-1 , 0
  4312.5     .05       0  4927.1     .16       0  4990.6     .07       0
  4996.6     .16       0  5124.6     .05       0  5682.1     .16       0
Bank Sta=4963,5024.2
XS Rating Curve= 0 ,0
Exp/Cntr=0.3,0.1

Type RM Length L Ch R = 1 ,6631    ,660,660,660
BEGIN DESCRIPTION:
UNT 123 IN BUCR 7.0
END DESCRIPTION:
XS GIS Cut Line= 3
      3641999.62     10514310.22      3642371.64     10515091.46
      3642449.61     10515910.16
#Sta/Elev= 30
  4295.5  326.32  4483.8  315.47  4572.4  304.57  4610.3  297.88    4672  293.57
  4782.8  291.84  4958.6  293.46  4979.1   293.9  4993.2  286.36  4998.8  285.95
  5001.6  285.45  5004.8  285.95  5015.4  290.25  5030.1   293.8  5075.5  290.72
  5115.1  291.57  5126.4  290.11  5157.3  291.94  5201.5  291.12  5270.2  291.41
  5290.1  290.83  5300.4  289.03  5404.3  297.02  5507.3  308.24  5561.3  312.41
  5772.3  323.37  5826.3  328.62  5852.6  332.71    5943  340.34  5983.2  346.91
#Mann= 7 ,-1 , 0
  4295.5     .05       0  4958.6     .16       0  4998.8     .07       0
  5004.8     .16       0  5201.5     .05       0  5270.2     .16       0
  5300.4     .05       0
Bank Sta=4979.1,5030.1
XS Rating Curve= 0 ,0
Exp/Cntr=0.3,0.1

Type RM Length L Ch R = 1 ,5971    ,630,630,630
BEGIN DESCRIPTION:
UNT 123 IN BUCR 6.0
END DESCRIPTION:
XS GIS Cut Line= 3
      3641999.61     10514510.18      3641849.61     10515310.19
      3642049.63     10515710.22
#Sta/Elev= 30
  4163.9  314.52  4235.1  309.48  4242.8  307.44  4247.8  307.59  4255.5  305.62
  4295.3   300.3    4353  294.93  4428.4  290.75  4515.8  291.19  4764.2  289.91
    4892  290.66  4980.6  291.48  4986.2  288.37  4997.2  286.64    5000  286.14
  5003.2  286.64  5008.6   287.6  5014.2  286.72  5022.6  290.44    5031  291.57
  5031.7  291.56  5044.9  291.72  5075.7  296.87    5112     300  5142.8  304.09
  5201.5  309.15  5254.6  316.01  5313.3  320.52  5349.6  322.14  5425.1  328.42
#Mann= 5 ,-1 , 0
  4163.9     .05       0    4892     .12       0  4997.2     .07       0
  5003.2     .12       0  5031.7     .05       0
Bank Sta=4980.6,5031
XS Rating Curve= 0 ,0
Exp/Cntr=0.3,0.1

Type RM Length L Ch R = 1 ,5341    ,671,671,671
BEGIN DESCRIPTION:
UNT 123 IN BUCR 5.0
END DESCRIPTION:
XS GIS Cut Line= 3
      3641299.61      10514460.2      3641425.46     10515299.79
      3641849.64     10515710.22
#Sta/Elev= 30
  4269.2  335.01  4298.7  333.31  4303.7  329.82  4309.7  328.42    4340  324.02
  4350.1  320.53  4390.5  313.24  4400.6   312.7  4491.6  299.27  4506.1  298.47
  4570.1  290.42    4613   288.2  4619.3  288.83  4703.3  287.41  4815.2  288.75
  4936.6  287.89  4987.1  289.62  4994.2     285    4997   284.5  5000.2     285
  5017.5  289.14  5109.3  288.26  5202.4  288.39  5252.2  288.35  5399.2  289.62
    5468  293.19  5552.9  301.19    5567  303.72  5637.7  311.43  5708.4  316.89
#Mann= 9 ,-1 , 0
  4269.2     .05       0  4309.7     .16       0  4619.3     .05       0
  4994.2     .03       0  5000.2     .05       0  5109.3     .12       0
  5202.4     .05       0  5252.2     .12       0  5399.2     .05       0
Bank Sta=4987.1,5017.5
XS Rating Curve= 0 ,0
Exp/Cntr=0.3,0.1

Type RM Length L Ch R = 1 ,4670    ,488,488,488
BEGIN DESCRIPTION:
UNT 123 IN BUCR 4.0
END DESCRIPTION:
XS GIS Cut Line= 3
      3640549.63     10515110.21      3640849.61     10515410.19
      3641649.58     10515710.18
#Sta/Elev= 30
  4568.4  340.07  4596.6  339.38  4681.5  333.89  4709.8  328.03  4723.9   322.6
  4738.1   315.7  4766.4  310.88  4808.8   308.4  4822.9  305.79  4837.1  304.96
  4879.5  296.34  4921.9  289.48  4950.2  287.08  4978.5  287.65  4991.1  284.83
  4995.3  284.83  4999.4  281.39  5002.2  280.89  5005.4  281.39  5007.8  283.73
    5014  285.93  5024.7  287.96  5131.5  286.18    5435  285.79  5593.2  288.66
  5659.2  290.36  5721.5  294.33  5746.5  294.79  5761.6  297.17    5847  303.35
#Mann= 7 ,-1 , 0
  4568.4     .16       0  4991.1     .12       0  4999.4     .07       0
  5005.4     .12       0  5131.5     .05       0  5593.2     .16       0
  5659.2     .05       0
Bank Sta=4978.5,5024.7
XS Rating Curve= 0 ,0
Exp/Cntr=0.3,0.1

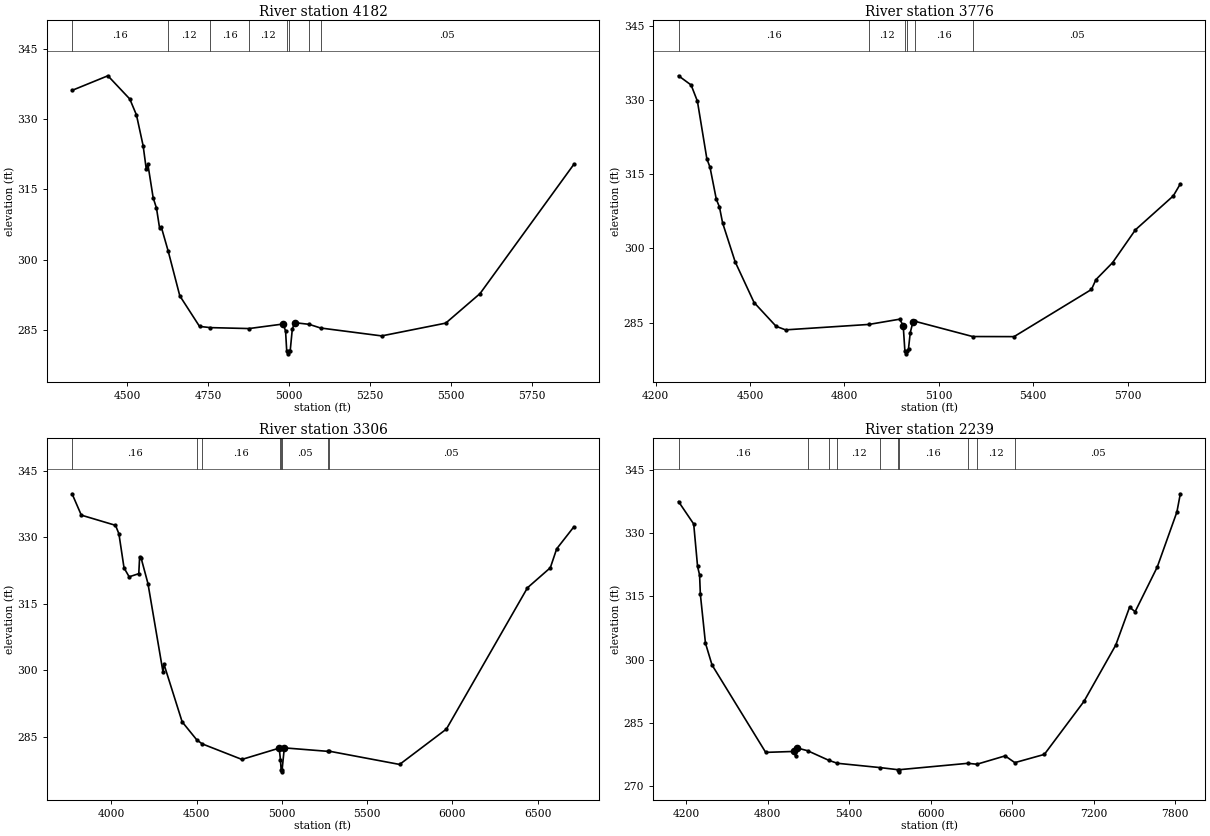
Type RM Length L Ch R = 1 ,4182    ,406,406,406
BEGIN DESCRIPTION:
UNT 123 IN BUCR 3.0
END DESCRIPTION:
XS GIS Cut Line= 3
      3640487.95      10515186.9      3640618.17     10515707.78
      3641299.58     10516460.16
#Sta/Elev= 30
  4328.9  336.16  4439.7  339.28  4507.5  334.31  4528.1   330.9  4548.8   324.3
  4558.2  319.42  4563.4  320.37  4579.7  313.23    4590  311.01  4599.4  306.83
  4604.6  307.04  4626.4  301.78  4662.1  292.28  4723.1  285.75  4756.5  285.49
  4876.1  285.29  4981.7  286.26  4989.2  284.79  4992.9  280.39  4995.7  279.89
  4998.9  280.39  5003.4  280.44  5010.1  285.18  5017.5  286.55  5062.3  286.19
  5097.3  285.41  5286.5  283.72  5484.6  286.45  5590.7  292.76  5880.9  320.37
#Mann= 8 ,-1 , 0
  4328.9     .16       0  4626.4     .12       0  4756.5     .16       0
  4876.1     .12       0  4992.9     .07       0  4998.9     .12       0
  5062.3     .16       0  5097.3     .05       0
Bank Sta=4981.7,5017.5
XS Rating Curve= 0 ,0
Exp/Cntr=0.3,0.1

Type RM Length L Ch R = 1 ,3776    ,470,470,470
BEGIN DESCRIPTION:
UNT 123 IN BUCR 2.0
END DESCRIPTION:
XS GIS Cut Line= 3
      3640399.61     10515360.22      3640399.61     10516060.19
      3641199.62     10516460.19
#Sta/Elev= 30
  4272.9  334.92  4312.9  333.05  4332.9  329.77  4362.9  318.13  4372.9  316.42
  4392.9  309.95  4402.9  308.38  4412.9  305.17  4452.9  297.28  4512.9  289.06
  4582.9  284.25  4612.9  283.53    4878  284.63  4975.7  285.69  4986.8  284.37
  4992.2  279.18    4995  278.68  4998.2  279.18  5003.6  279.74  5009.2  282.98
  5017.6  285.09  5025.6  285.24  5207.4  282.18    5339  282.16    5585   291.7
    5599  293.68  5652.1  297.13  5724.7  303.77  5844.9  310.62  5867.3  313.05
#Mann= 6 ,-1 , 0
  4272.9     .16       0    4878     .12       0  4992.2     .07       0
  4998.2     .12       0  5025.6     .16       0  5207.4     .05       0
Bank Sta=4986.8,5017.6
XS Rating Curve= 0 ,0
Exp/Cntr=0.3,0.1

Type RM Length L Ch R = 1 ,3306    ,1067,1067,1067
BEGIN DESCRIPTION:
Mapping XS 03e1bd79
END DESCRIPTION:
XS GIS Cut Line= 4
      3640001.85     10515126.14       3639932.4     10516124.44
      3640166.78     10516532.43      3641615.56     10516792.69
#Sta/Elev= 30
    3770  339.86  3824.2  335.04  4024.7  332.74  4044.7  330.84  4074.8  323.13
  4104.9  321.12  4161.3  321.83  4166.3  325.65    4175  325.35  4215.1   319.6
  4303.5   299.6  4308.5  301.46  4415.6  288.39  4501.8   284.3  4533.4  283.41
  4766.1   279.9  4984.9  282.45  4992.1  279.87  4996.1   277.6  4998.8   277.1
  5002.1   277.6  5014.9  282.51  5269.1  281.73  5275.5  281.78  5691.1  278.77
  5965.5  286.75  6441.2  318.65  6575.1  323.16  6612.4  327.43  6713.2   332.4
#Mann= 8 ,-1 , 0
    3770     .16       0  4501.8     .05       0  4533.4     .16       0
  4992.1     .05       0  4996.1     .03       0  5002.1     .05       0
  5269.1     .12       0  5275.5     .05       0
Bank Sta=4984.9,5014.9
XS Rating Curve= 0 ,0
Exp/Cntr=0.3,0.1

Type RM Length L Ch R = 1 ,2239    ,0,0,0
BEGIN DESCRIPTION:
UNT 123 IN BUCR 1.0
END DESCRIPTION:
XS GIS Cut Line= 5
      3639168.51     10515933.48      3639029.63     10516549.79
      3639229.28     10517044.58      3639637.27     10517261.59
      3641666.57     10516880.02
#Sta/Elev= 30
  4144.3  337.45  4255.9  332.14  4284.4  322.08  4299.2  320.07  4304.9  315.47
  4342.4  303.91  4390.8  298.74  4785.6  278.04  4992.2  278.26  5005.8  277.07
  5013.7  279.11  5094.2  278.43  5248.5  276.18  5312.5  275.46  5626.3  274.44
  5760.4  273.93  5763.2  273.43  5766.4  273.93  6273.2  275.45  6339.7  275.23
  6547.4  277.21  6618.9  275.61    6836  277.56  7127.4  290.11  7361.5  303.46
  7463.2  312.44  7503.9  311.36  7666.7  321.94  7811.4  334.99  7836.6   339.3
#Mann= 10 ,-1 , 0
  4144.3     .16       0  5094.2     .12       0  5248.5     .07       0
  5312.5     .12       0  5626.3     .16       0  5760.4     .07       0
  5766.4     .16       0  6273.2     .05       0  6339.7     .12       0
  6618.9     .05       0
Bank Sta=4992.2,5013.7
XS Rating Curve= 0 ,0
Exp/Cntr=0.3,0.1

Chan Stop Cuts=-1
Use User Specified Reach Order=0
Composite Channel Slope=5