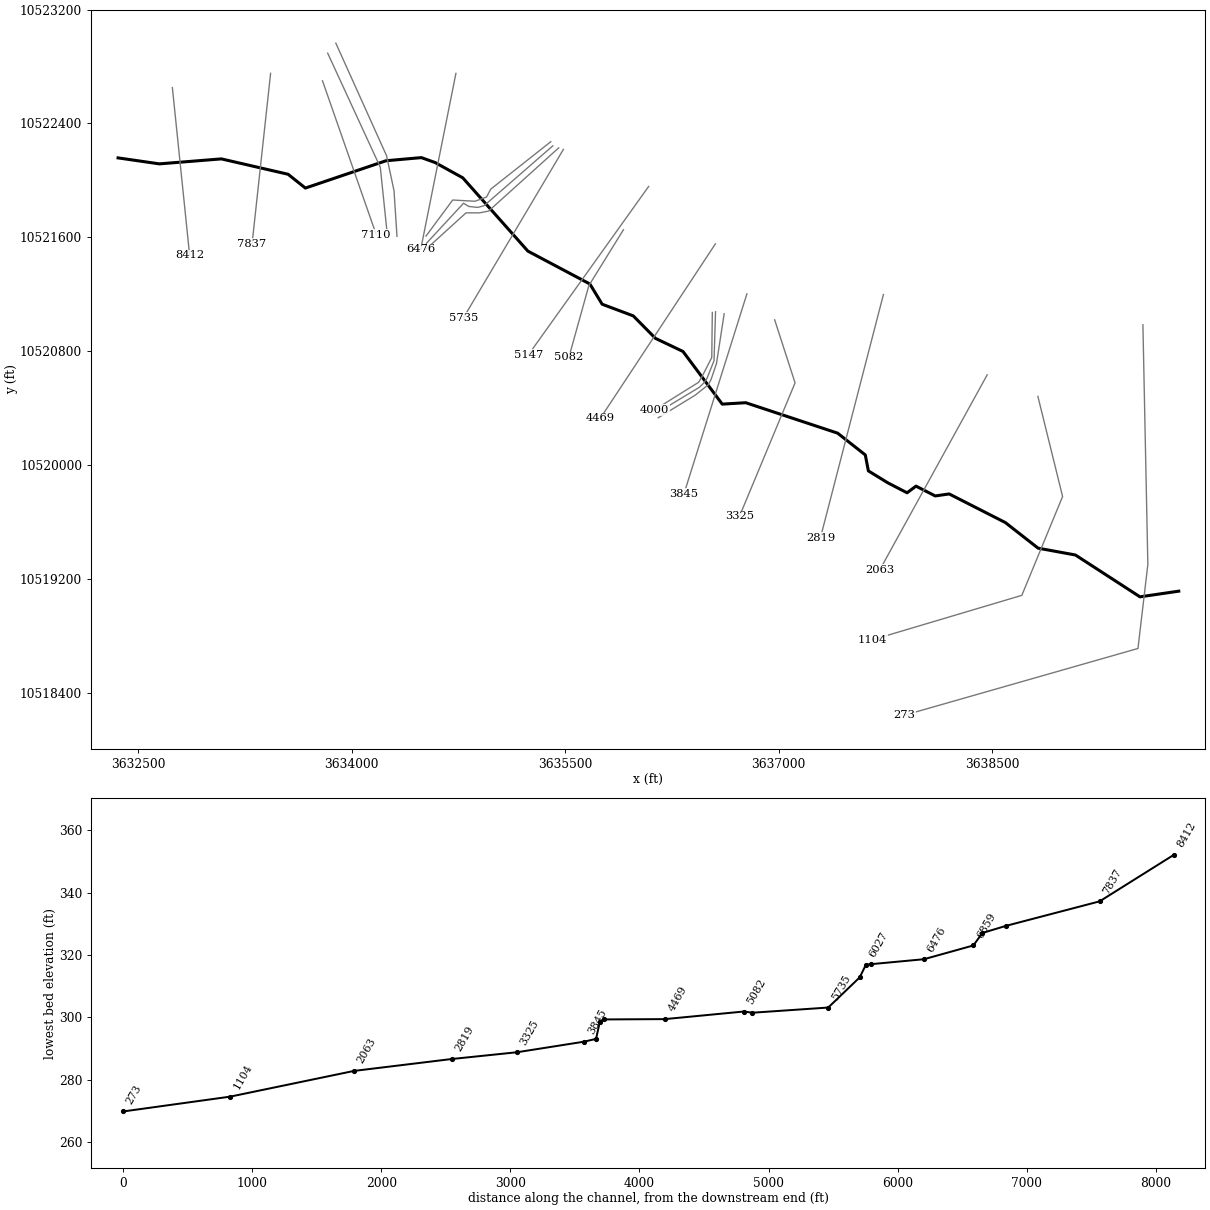
--- UNT 124 IN BUCR.prj (project) ---

Proj Title=UNT 124 IN BUCR Base Level Engineering
Current Plan=p01
Default Exp/Contr=0.3,0.1
English Units
Geom File=g01
Flow File=f01
Plan File=p01
Y Axis Title=Elevation
X Axis Title(PF)=Main Channel Distance
X Axis Title(XS)=Station
BEGIN DESCRIPTION:
UNT 124 IN BUCR
END DESCRIPTION:
DSS Export Rating Curves= 0
DSS Export Rating Curve Sorted= 0
DSS Export Volume Flow Curves= 0
DXF OffsetX= 0
DXF OffsetY= 0
DXF ScaleX= 1
DXF ScaleY= 10

--- UNT 124 IN BUCR.p01 (plan) ---

Plan Title=Multiple Run
Short Identifier=Multiple
Geom File=g01
Flow File=f01
Subcritical Flow
K Sum by GR= 0
Std Step Tol= 0.01
Critical Tol= 0.01
Num of Std Step Trials= 20
Max Error Tol= 0.3
Flow Tol Ratio= 0.001
Split Flow NTrial= 30
Split Flow Tol= 0.02
Split Flow Ratio= 0.02
Log Output Level= 0
Friction Slope Method= 1
Unsteady Friction Slope Method= 2
Unsteady Bridges Friction Slope Method= 1
Parabolic Critical Depth
Global Vel Dist=  1 , 1 , 1
Global Log Level= 0
CheckData=True
Encroach Param= -1, 0, 0, 0
BEGIN DESCRIPTION:
Multiple Run
END DESCRIPTION:

--- UNT 124 IN BUCR.f01 (steady flow) ---

Flow Title=Multiple
Number of Profiles=7
Profile Names=10-year,25-year,50-year,1pct_min,100-year,1pct_plu,500-year
River Rch & RM= UNT 124 IN BUCR,Reach-1,8412
    1120    1552    1912    1720    2326    3146    3431
Boundary for River Rch & Prof#=UNT 124 IN BUCR,Reach-1,1
Up Type=0
Dn Type=3
Dn Slope=0.005
Boundary for River Rch & Prof#=UNT 124 IN BUCR,Reach-1,2
Up Type=0
Dn Type=3
Dn Slope=0.005
Boundary for River Rch & Prof#=UNT 124 IN BUCR,Reach-1,3
Up Type=0
Dn Type=3
Dn Slope=0.005
Boundary for River Rch & Prof#=UNT 124 IN BUCR,Reach-1,4
Up Type=0
Dn Type=3
Dn Slope=0.005
Boundary for River Rch & Prof#=UNT 124 IN BUCR,Reach-1,5
Up Type=0
Dn Type=3
Dn Slope=0.005
Boundary for River Rch & Prof#=UNT 124 IN BUCR,Reach-1,6
Up Type=0
Dn Type=3
Dn Slope=0.005
Boundary for River Rch & Prof#=UNT 124 IN BUCR,Reach-1,7
Up Type=0
Dn Type=3
Dn Slope=0.005

--- UNT 124 IN BUCR.g01 (geometry) ---

Geom Title=Existing Conditions
Program Version=4.10

River Reach=UNT 124 IN BUCR ,Reach-1
Reach XY= 30
      3632358.75       10522158.      3632648.75       10522116.
       3633084.5       10522151.      3633553.25       10522043.
      3633674.75       10521946.       3634241.5       10522138.
      3634489.75       10522160.        3634587.       10522125.
       3634780.5       10522018.        3635238.       10521503.
      3635673.75       10521272.      3635759.75       10521130.
       3635978.5       10521048.       3636134.5       10520890.
      3636327.75       10520798.       3636603.5       10520428.
       3636768.5       10520438.      3637414.25       10520224.
      3637608.75       10520071.      3637630.25       10519959.
        3637767.       10519875.      3637902.25       10519805.
      3637964.75       10519852.      3638099.75       10519783.
        3638198.       10519797.       3638592.5       10519596.
      3638822.75       10519416.        3639085.       10519368.
       3639538.5       10519074.        3639811.       10519114.

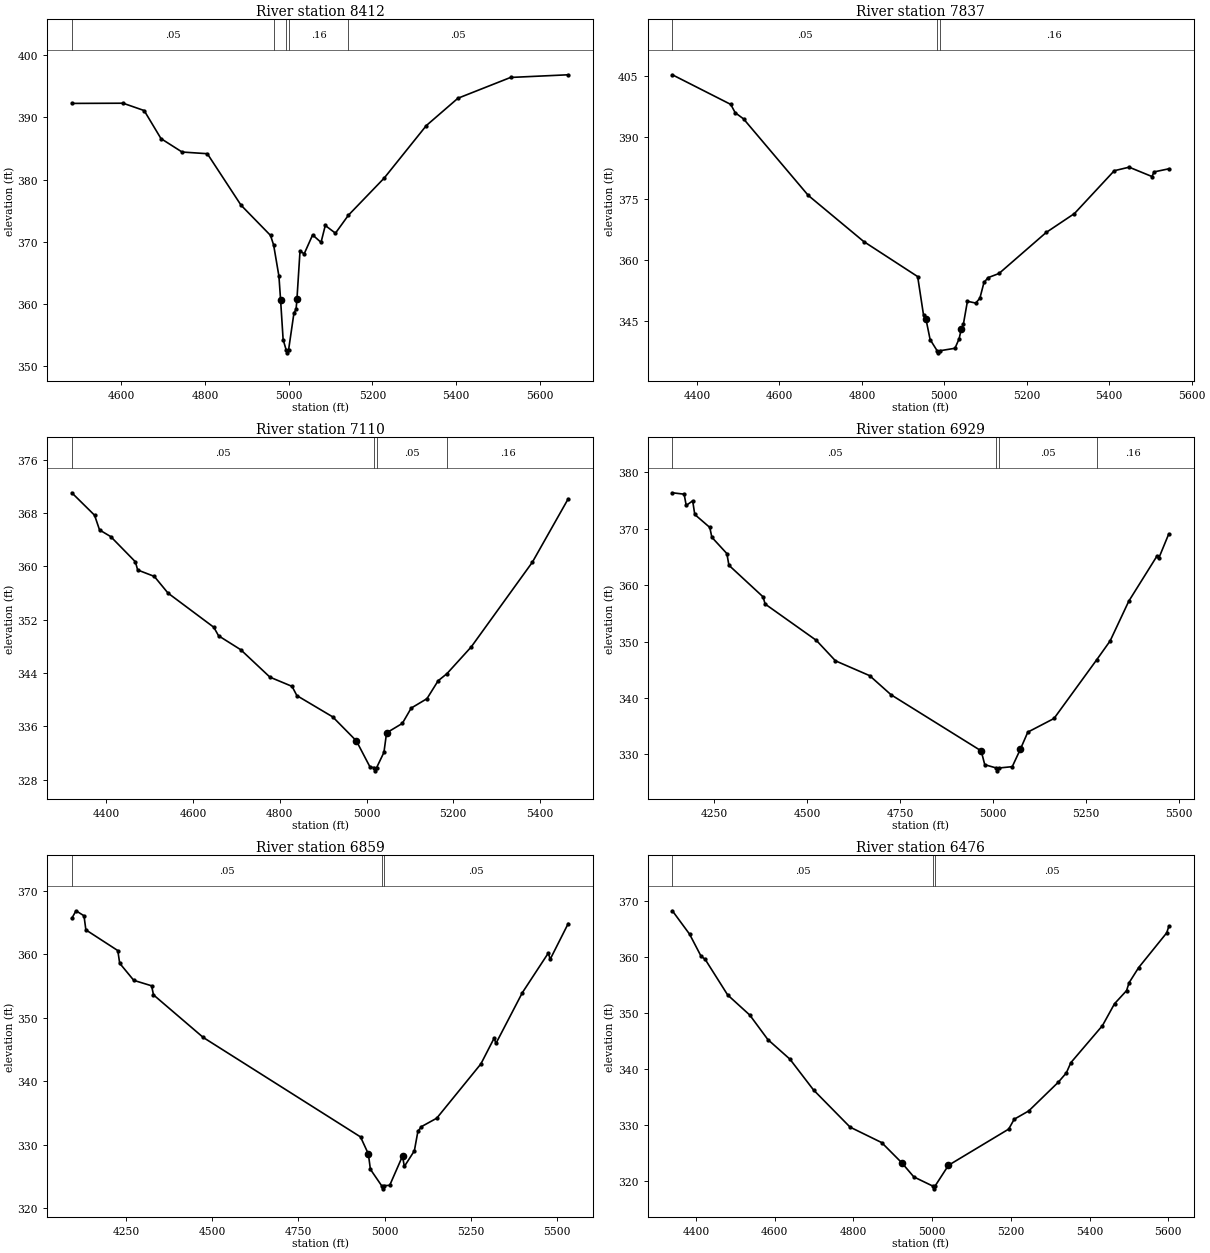
Type RM Length L Ch R = 1 ,8412    ,575,575,575
BEGIN DESCRIPTION:
UNT 124 IN BUCR 3.0
END DESCRIPTION:
XS GIS Cut Line= 2
      3632740.24     10522651.98      3632861.58     10521473.31
#Sta/Elev= 30
  4482.3  392.26  4604.7  392.29    4655  391.11  4695.2  386.59  4745.5  384.43
  4805.8  384.16  4886.2  375.87  4956.6     371  4964.1  369.44  4976.7  364.43
 4980.68  360.58  4986.7  354.23  4993.8  352.59  4996.5  352.09  4999.8  352.59
  5012.6  358.53  5017.6  359.08 5019.66   360.7    5027  368.48    5037  368.04
  5057.1  371.08  5077.2  369.88  5087.3   372.6  5111.6  371.36  5142.6  374.26
    5228  380.24  5328.5  388.69  5403.9  393.09  5529.6  396.44  5667.2  396.87
#Mann= 5 ,-1 , 0
  4482.3     .05       0  4964.1     .16       0  4993.8     .07       0
  4999.8     .16       0  5142.6     .05       0
Bank Sta=4980.68,5019.66
XS Rating Curve= 0 ,0
Exp/Cntr=0.3,0.1

Type RM Length L Ch R = 1 ,7837    ,727,727,727
BEGIN DESCRIPTION:
Mapping XS 30fe1c91
END DESCRIPTION:
XS GIS Cut Line= 2
      3633430.35     10522751.81      3633300.22     10521554.56
#Sta/Elev= 30
  4340.2  405.34  4481.8  398.08  4492.7  396.03  4512.8  394.54  4669.9  375.77
  4804.5  364.46  4935.3  355.87  4949.5  346.45  4955.4  345.45  4965.5  340.44
  4982.6  337.68  4985.4  337.18  4988.6  337.68  5025.8   338.3  5035.9  340.64
    5041  342.98  5046.1  344.14    5056  349.82  5076.1  349.38  5086.2  350.56
  5096.2  354.45  5106.3  355.62  5132.6  356.63  5247.1  366.69  5315.6  371.32
  5412.2  381.82  5448.3  382.69  5503.7   380.4  5508.8  381.53  5544.5  382.29
#Mann= 3 ,-1 , 0
  4340.2     .05       0  4982.6     .07       0  4988.6     .16       0
Bank Sta=4955.4,5041
XS Rating Curve= 0 ,0
Exp/Cntr=0.3,0.1

Type RM Length L Ch R = 1 ,7110    ,181,181,181
BEGIN DESCRIPTION:
Mapping XS 080b69f4
END DESCRIPTION:
XS GIS Cut Line= 2
      3633794.93     10522699.71      3634172.53     10521618.98
#Sta/Elev= 30
  4320.2  371.05  4372.7  367.68  4384.2  365.47    4410  364.47  4466.8  360.69
  4472.1  359.46  4510.4   358.5  4542.1  355.99  4647.7  350.86  4658.7  349.58
  4709.8  347.49  4777.2  343.37  4828.1  341.99  4839.3   340.6  4921.9  337.41
  4976.4  333.81  5008.2  329.85  5017.3  329.81  5020.1  329.31  5023.3  329.81
    5040  332.08  5046.1  335.01  5082.4  336.43  5102.9  338.73  5139.2  340.14
    5165  342.83  5185.2  343.89  5241.3  347.91  5382.3  360.63    5465  370.15
#Mann= 4 ,-1 , 0
  4320.2     .05       0  5017.3     .03       0  5023.3     .05       0
  5185.2     .16       0
Bank Sta=4976.4,5046.1
XS Rating Curve= 0 ,0
Exp/Cntr=0.3,0.1

Type RM Length L Ch R = 1 ,6929    ,70,70,70
BEGIN DESCRIPTION:
Mapping XS 92f0c8aa
END DESCRIPTION:
XS GIS Cut Line= 3
      3633831.33     10522893.94      3634201.13     10522091.85
      3634247.79      10521643.3
#Sta/Elev= 30
  4137.9  376.39  4169.6  376.14  4175.1  374.14  4192.5  374.96  4198.1  372.54
  4238.5  370.24    4244   368.5  4284.4   365.6  4289.9  363.53  4381.7  357.92
  4387.2  356.65  4524.9   350.2  4576.3  346.57  4668.1  343.94  4725.6  340.55
  4967.9  330.59  4977.5  328.14    5009  327.55  5011.7  327.05    5015  327.55
  5051.4  327.79  5073.1  330.87  5093.2  333.92  5163.6  336.34  5278.3  346.75
  5314.4   350.1  5364.6  357.16  5440.7   365.2  5445.7  364.86  5472.1   369.1
#Mann= 4 ,-1 , 0
  4137.9     .05       0    5009     .03       0    5015     .05       0
  5278.3     .16       0
Bank Sta=4967.9,5073.1
XS Rating Curve= 0 ,0
Exp/Cntr=0.3,0.1

Type RM Length L Ch R = 1 ,6859    ,383,383,383
BEGIN DESCRIPTION:
Mapping XS 3720371b
END DESCRIPTION:
XS GIS Cut Line= 4
      3633888.64     10522964.21       3634245.4     10522172.58
      3634297.48     10521927.79      3634318.31     10521607.44
#Sta/Elev= 30
  4092.9  365.67  4105.1  366.86  4128.3  366.07  4133.7  363.85  4226.3  360.59
  4231.8  358.59  4272.6   355.9  4324.3  355.04  4329.8  353.61  4474.1   346.9
  4930.2  331.23  4952.9  328.55  4958.8  326.13  4991.3  323.55  4994.1  323.05
  4997.3  323.55  5014.8   323.6    5052  328.22  5057.2  326.57  5086.3  329.04
  5096.5  332.09  5106.8  332.85  5151.2  334.18  5279.2  342.73  5317.8  346.81
  5322.8  345.95  5399.5  353.96    5475  360.22    5480   359.2  5532.5  364.85
#Mann= 3 ,-1 , 0
  4092.9     .05       0  4991.3     .03       0  4997.3     .05       0
Bank Sta=4952.9,5052
XS Rating Curve= 0 ,0
Exp/Cntr=0.3,0.1

Type RM Length L Ch R = 1 ,6476    ,408,408,408
BEGIN DESCRIPTION:
Mapping XS ef10a115
END DESCRIPTION:
XS GIS Cut Line= 2
      3634732.43     10522751.79      3634485.07     10521514.98
#Sta/Elev= 30
  4339.8  368.26  4383.5  364.09  4412.8  360.14    4423  359.61  4480.4  353.23
  4536.5  349.65  4582.4  345.28  4638.5  341.78  4698.4  336.29  4791.4  329.65
  4871.7  326.89  4922.7  323.29  4953.3  320.77  5001.3  319.14  5004.1  318.64
  5007.3  319.14  5041.3  322.84  5194.3   329.3  5208.3  331.06  5245.2  332.54
  5320.4  337.67  5340.8  339.33  5352.3  341.16  5432.6  347.77  5463.2  351.67
  5493.8  354.01  5500.2  355.42  5524.4  358.11  5595.8  364.32  5601.1  365.46
#Mann= 3 ,-1 , 0
  4339.8     .05       0  5001.3     .03       0  5007.3     .05       0
Bank Sta=4922.7,5041.3
XS Rating Curve= 0 ,0
Exp/Cntr=0.3,0.1

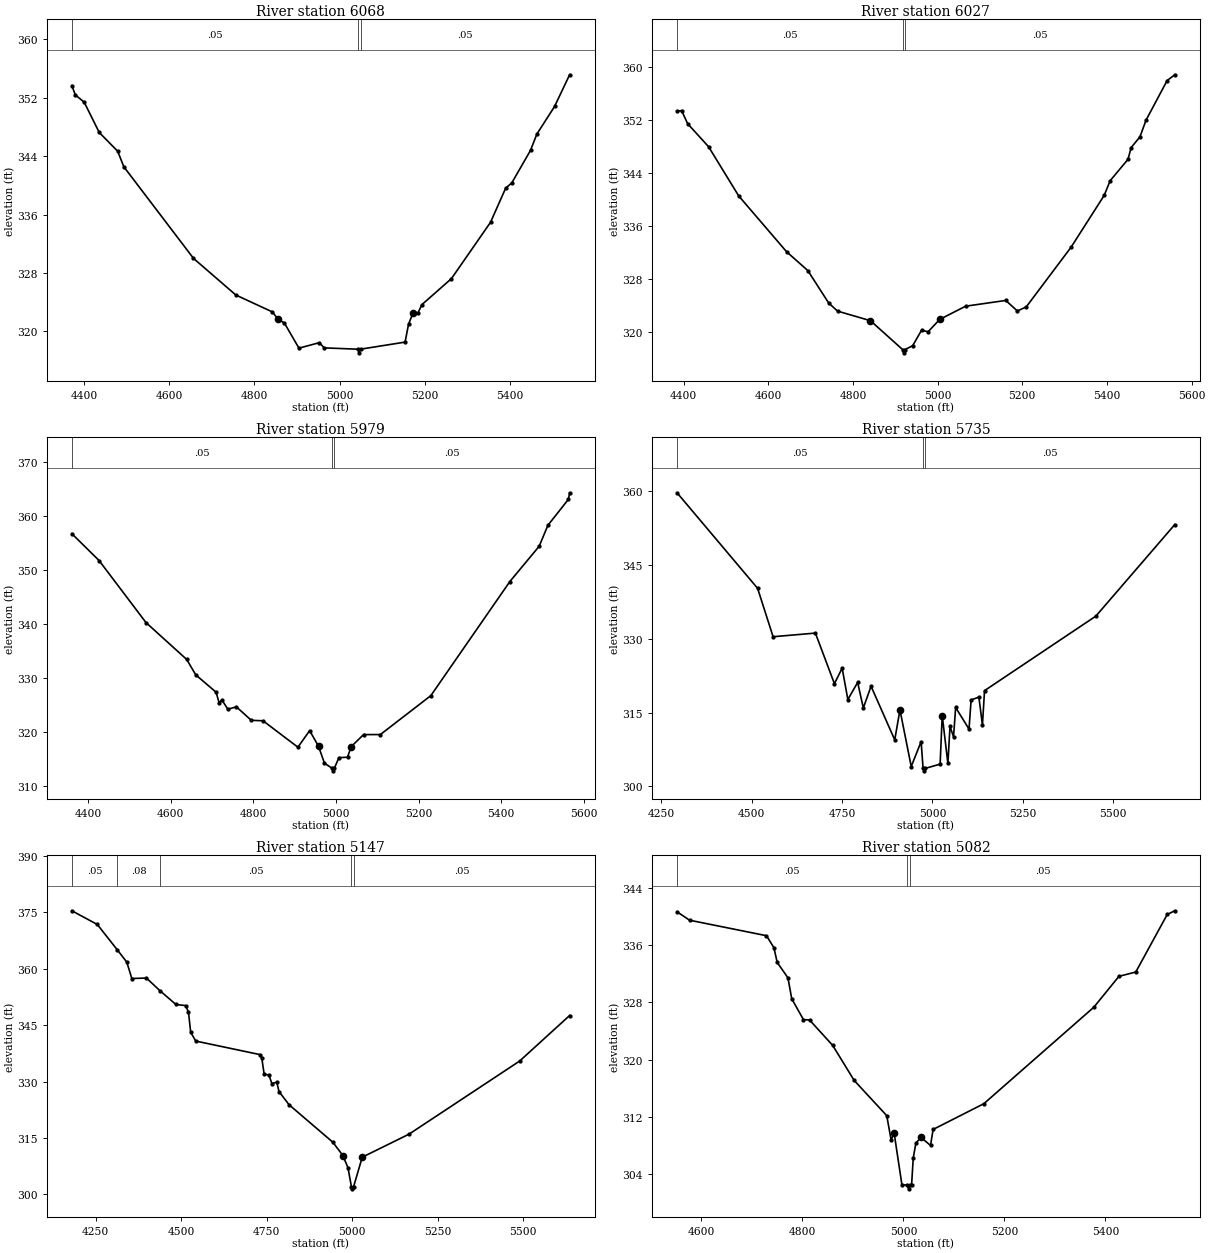
Type RM Length L Ch R = 1 ,6068    ,41,41,41
BEGIN DESCRIPTION:
Mapping XS ab85a471
END DESCRIPTION:
XS GIS Cut Line= 6
      3635398.96      10522271.8      3634977.08     10521938.46
      3634947.57     10521882.91      3634865.97     10521853.39
      3634709.72     10521862.07      3634522.23     10521608.62
#Sta/Elev= 30
  4371.5  353.67  4379.6  352.39  4400.4   351.4  4435.7  347.25    4479  344.68
  4493.4  342.55  4656.9     330  4756.3  324.98  4842.2  322.66  4855.6  321.64
  4870.1  321.15  4904.4   317.7    4952  318.45  4963.8  317.74  5042.8  317.56
  5045.5  317.06  5048.8  317.56  5153.4  318.53  5161.6     321    5172   322.5
  5183.7  322.54    5193  323.67  5262.1  327.22  5353.9  334.94  5389.3   339.6
    5404  340.36  5447.8   344.8  5462.5  347.01  5504.2  350.81  5539.5  355.15
#Mann= 3 ,-1 , 0
  4371.5     .05       0  5042.8     .03       0  5048.8     .05       0
Bank Sta=4855.6,5172
XS Rating Curve= 0 ,0
Exp/Cntr=0.3,0.1

Type RM Length L Ch R = 1 ,6027    ,48,48,48
BEGIN DESCRIPTION:
Mapping XS ed65f598
END DESCRIPTION:
XS GIS Cut Line= 6
      3635412.82     10522242.26      3634930.21     10521822.14
      3634885.07     10521809.99      3634822.57     10521816.94
      3634786.11      10521839.5      3634525.69     10521558.25
#Sta/Elev= 30
  4384.5  353.36  4395.3  353.45  4409.6  351.47  4458.9  348.01  4530.1  340.58
  4643.1  332.16  4693.4  329.31  4742.7  324.41  4763.6  323.19  4841.4  321.74
  4917.2  317.39  4919.9  316.89  4923.2  317.39  4941.1  317.97    4962   320.3
  4977.5  320.07  5004.8  321.93  5066.2  323.93    5161   324.8  5188.3  323.21
  5209.3  323.82  5315.3  332.84  5393.5  340.66  5407.6  342.88  5449.7   346.1
  5457.1  347.87    5478   349.5  5492.2     352  5542.1  357.99  5560.2  358.86
#Mann= 3 ,-1 , 0
  4384.5     .05       0  4917.2     .03       0  4923.2     .05       0
Bank Sta=4841.4,5004.8
XS Rating Curve= 0 ,0
Exp/Cntr=0.3,0.1

Type RM Length L Ch R = 1 ,5979    ,244,244,244
BEGIN DESCRIPTION:
Mapping XS c8128708
END DESCRIPTION:
XS GIS Cut Line= 5
      3635454.52      10522228.4      3634961.46     10521783.95
      3634897.22      10521771.8      3634803.47      10521771.8
      3634520.69     10521515.04
#Sta/Elev= 30
  4360.6  356.68  4426.5  351.72  4540.1  340.24  4638.7  333.42  4660.4  330.59
  4709.7  327.37  4717.2  325.37  4723.9  325.94  4738.1  324.23    4759  324.66
  4794.9  322.17  4823.3  322.09  4907.8   317.2  4936.2  320.27  4957.8  317.35
    4972  314.25    4990  313.33  4992.7  312.83    4996  313.33  5007.2  315.27
  5027.9  315.35  5036.5  317.29  5066.7  319.53  5107.4  319.54  5229.6  326.74
  5420.8  347.83  5491.8  354.36  5512.9  358.23  5562.7  363.05  5565.5  364.25
#Mann= 3 ,-1 , 0
  4360.6     .05       0    4990     .03       0    4996     .05       0
Bank Sta=4957.8,5036.5
XS Rating Curve= 0 ,0
Exp/Cntr=0.3,0.1

Type RM Length L Ch R = 1 ,5735    ,588,588,588
BEGIN DESCRIPTION:
Mapping XS 978e78b2
END DESCRIPTION:
XS GIS Cut Line= 2
      3635487.63     10522217.91      3634785.23     10521034.23
#Sta/Elev= 30
  4293.9  359.64  4516.7  340.23  4559.5   330.4  4676.5  331.14  4729.1  320.86
  4750.5  324.02  4766.2  317.65  4793.4  321.12    4809  315.93  4830.4  320.34
  4895.9  309.45  4910.3  315.54  4941.5  304.04  4968.8  309.08  4974.3  303.66
  4977.1  303.16  4980.3  303.66  5021.4  304.52  5027.2   314.4  5042.9  304.66
  5048.7  312.18  5058.5  310.07  5064.3  316.03  5101.3  311.64  5107.1  317.57
  5128.6  318.13  5138.4  312.47  5144.2  319.45  5452.1  334.59  5670.3  353.18
#Mann= 3 ,-1 , 0
  4293.9     .05       0  4974.3     .03       0  4980.3     .05       0
Bank Sta=4910.3,5027.2
XS Rating Curve= 0 ,0
Exp/Cntr=0.3,0.1

Type RM Length L Ch R = 1 ,5147    ,65,65,65
BEGIN DESCRIPTION:
Mapping XS 8564f25c
END DESCRIPTION:
XS GIS Cut Line= 2
      3636086.61     10521957.52      3635241.14     10520773.87
#Sta/Elev= 30
  4180.6  375.35    4255  371.71  4313.3  364.98  4341.1  361.72  4355.8  357.36
  4398.5  357.49  4437.4  354.17  4484.6  350.47  4513.1  350.17  4521.4  348.42
  4527.8  343.09  4542.6  340.75  4729.4  337.17  4735.5  336.31  4742.6  331.91
  4756.4  331.76    4765  329.46  4779.5  329.82  4785.9  327.33  4815.4  323.83
  4943.2  313.89  4972.7  310.33  4987.5  307.09  4997.7     302  5000.4   301.5
  5003.7     302  5029.2  309.91  5165.7  316.01  5488.9  335.42  5635.2  347.53
#Mann= 5 ,-1 , 0
  4180.6     .05       0  4313.3     .08       0  4437.4     .05       0
  4997.7     .03       0  5003.7     .05       0
Bank Sta=4972.7,5029.2
XS Rating Curve= 0 ,0
Exp/Cntr=0.3,0.1

Type RM Length L Ch R = 1 ,5082    ,613,613,613
BEGIN DESCRIPTION:
Mapping XS 893f776f
END DESCRIPTION:
XS GIS Cut Line= 3
      3635909.47     10521653.31       3635666.4     10521260.91
      3635525.77      10520755.7
#Sta/Elev= 30
  4551.6  340.69  4576.4  339.51  4728.8  337.34  4743.5  335.66    4750   333.6
  4771.3  331.44  4778.8  328.51  4802.1  325.58  4814.1  325.54    4860  321.97
  4902.5  317.07    4967  312.14  4975.7  308.73  4981.6  309.73    4997  302.49
  5007.7  302.39  5010.4  301.89  5013.7  302.39  5016.2  302.39  5019.5  306.21
  5024.7  308.29  5034.7   309.1  5053.7  307.97  5058.9  310.21  5159.3  313.81
  5377.2  327.32    5427  331.65  5460.3  332.25  5522.6  340.31  5537.6  340.83
#Mann= 3 ,-1 , 0
  4551.6     .05       0  5007.7     .03       0  5013.7     .05       0
Bank Sta=4981.6,5034.7
XS Rating Curve= 0 ,0
Exp/Cntr=0.3,0.1

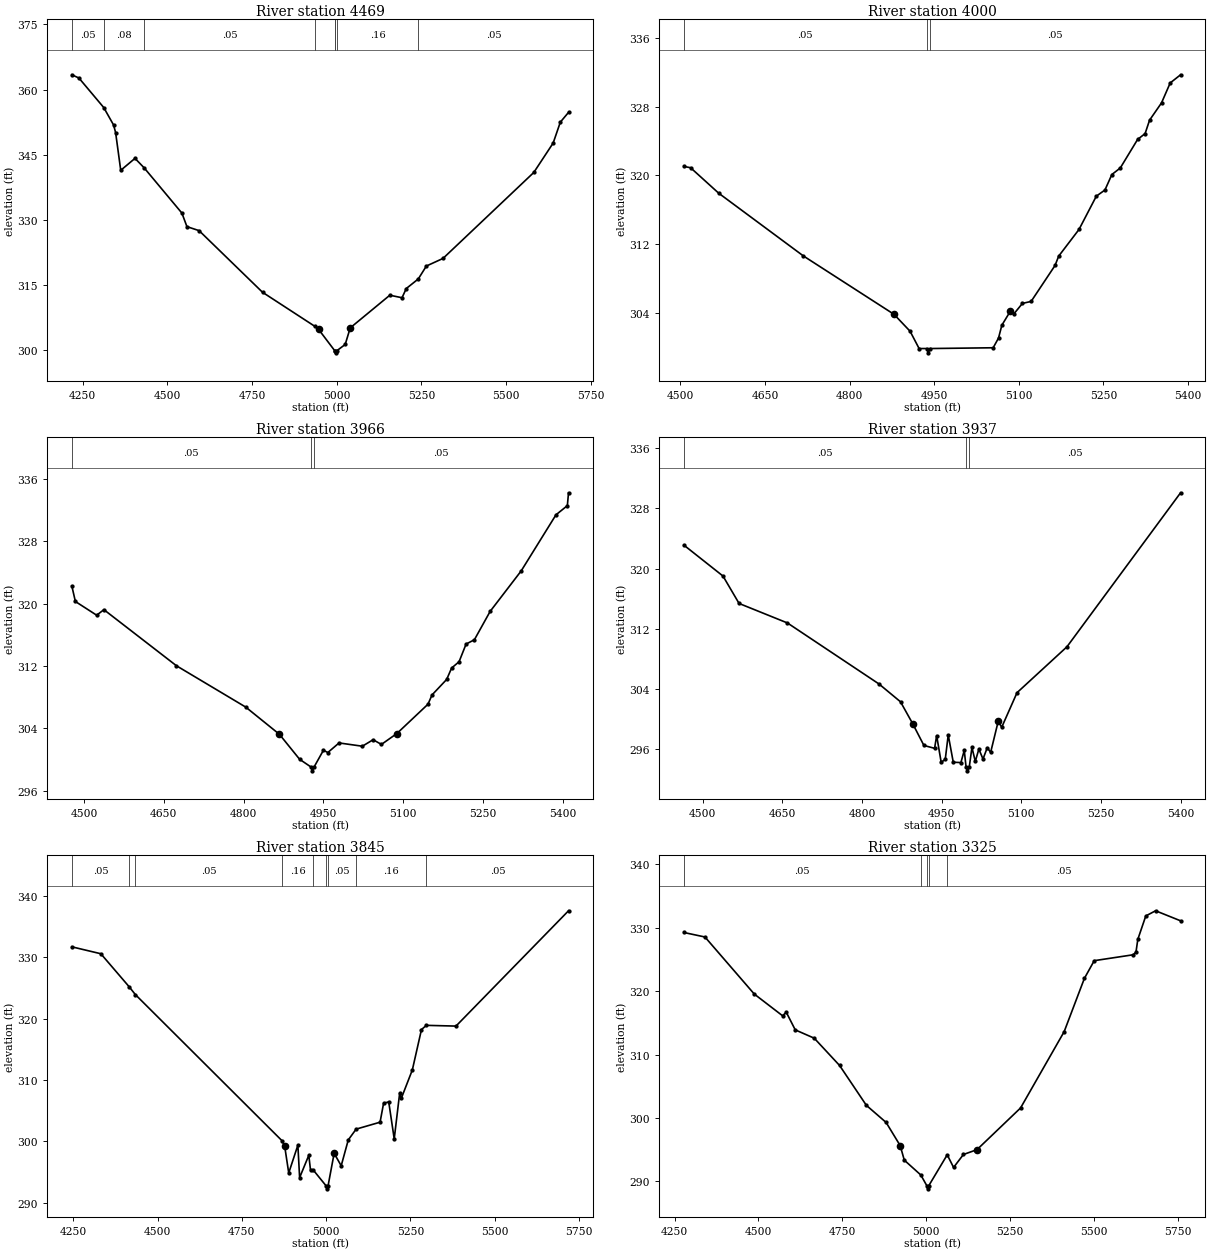
Type RM Length L Ch R = 1 ,4469    ,469,469,469
BEGIN DESCRIPTION:
Mapping XS 6551430a
END DESCRIPTION:
XS GIS Cut Line= 2
      3636555.32     10521553.82      3635748.04     10520329.88
#Sta/Elev= 30
  4218.1  363.39    4239  362.65  4312.4  355.85  4341.4  351.84  4347.4   350.1
  4362.5  341.42  4404.6  344.17  4431.5     342  4543.1  331.58  4557.9  328.47
  4593.8  327.55    4781  313.38  4935.2  305.56  4946.5  304.85  4993.9  299.97
  4994.7  299.95  4997.5  299.45  5000.7  299.95  5025.1  301.38  5039.9  305.19
  5156.8   312.7  5192.8  312.12  5205.4  314.24  5240.7  316.43  5264.7  319.41
  5313.8  321.16  5581.8  340.93    5639   347.7  5660.1   352.5  5684.3  354.74
#Mann= 8 ,-1 , 0
  4218.1     .05       0  4312.4     .08       0  4431.5     .05       0
  4935.2      .1       0  4993.9     .16       0  4994.7     .07       0
  5000.7     .16       0  5240.7     .05       0
Bank Sta=4946.5,5039.9
XS Rating Curve= 0 ,0
Exp/Cntr=0.3,0.1

Type RM Length L Ch R = 1 ,4000    ,34,34,34
BEGIN DESCRIPTION:
Mapping XS f1a94eb9
END DESCRIPTION:
XS GIS Cut Line= 5
      3636533.82     10521072.04      3636529.92     10520755.67
      3636462.21     10520622.85      3636437.47     10520581.19
      3636126.23     10520387.15
#Sta/Elev= 30
  4506.1  321.03    4518  320.88    4568  317.91    4718  310.62  4878.7  303.83
  4907.2  301.86  4923.2  299.85  4936.8  299.85  4939.5  299.35  4942.8  299.85
  5054.5  299.94    5064  301.07  5069.9  302.56  5085.2  304.22  5091.1  303.87
  5106.4   305.1  5121.8  305.33  5164.2  309.51  5170.7   310.6  5206.7   313.7
  5237.4  317.57  5252.7  318.29    5265  320.09  5279.9  320.85  5310.6  324.17
  5323.9  324.85  5331.8  326.41    5353  328.42  5368.4  330.74  5386.8  331.69
#Mann= 3 ,-1 , 0
  4506.1     .05       0  4936.8     .03       0  4942.8     .05       0
Bank Sta=4878.7,5085.2
XS Rating Curve= 0 ,0
Exp/Cntr=0.3,0.1

Type RM Length L Ch R = 1 ,3966    ,29,29,29
BEGIN DESCRIPTION:
Mapping XS 29f09f39
END DESCRIPTION:
XS GIS Cut Line= 6
      3636556.39     10521076.84      3636545.98      10520733.1
      3636497.37     10520611.57       3636474.8     10520576.85
      3636441.81      10520545.6      3636123.49     10520353.56
#Sta/Elev= 30
  4477.3  322.29    4484  320.29    4524  318.53  4537.6  319.24    4674  312.04
  4804.1  306.74  4867.4  303.25  4905.4  300.04  4926.6  299.06  4929.4  298.56
  4932.6  299.06  4950.1   301.2  4958.4  300.91  4979.5  302.14  5023.2  301.72
  5043.5  302.55  5059.1  301.95  5088.2  303.35  5146.6  307.11  5154.2   308.3
  5181.7  310.29    5191  311.75    5205  312.56  5218.2  314.83  5233.8  315.38
  5263.4  319.02  5321.8  324.22  5387.1  331.41  5408.5  332.59  5410.7  334.24
#Mann= 3 ,-1 , 0
  4477.3     .05       0  4926.6     .03       0  4932.6     .05       0
Bank Sta=4867.4,5088.2
XS Rating Curve= 0 ,0
Exp/Cntr=0.3,0.1

Type RM Length L Ch R = 1 ,3937    ,92,92,92
BEGIN DESCRIPTION:
Mapping XS 8d618602
END DESCRIPTION:
XS GIS Cut Line= 6
      3636617.16       10521063.      3636563.34       10520714.
      3636525.14     10520601.15      3636504.31     10520562.96
       3636412.3     10520490.04      3636154.11     10520332.36
#Sta/Elev= 30
  4464.4  323.11  4538.1     319  4568.4  315.36  4659.5  312.77  4832.1  304.66
  4872.5   302.3  4895.4   299.4  4916.6   296.5  4936.7  296.12  4940.6  297.81
  4949.1  294.27  4956.8  294.65  4962.4   297.9  4971.9  294.27  4986.3  294.23
  4992.6  295.84    4996  293.63  4998.7  293.13    5002  293.63  5007.1  296.23
  5013.4  294.38  5020.1  296.02  5027.9   294.7  5035.9   296.2  5042.3  295.58
  5056.7  299.75  5063.1  298.91    5092  303.51  5186.1  309.61  5400.1  330.06
#Mann= 3 ,-1 , 0
  4464.4     .05       0    4996     .03       0    5002     .05       0
Bank Sta=4895.4,5056.7
XS Rating Curve= 0 ,0
Exp/Cntr=0.3,0.1

Type RM Length L Ch R = 1 ,3845    ,520,520,520
BEGIN DESCRIPTION:
Mapping XS b00f071c
END DESCRIPTION:
XS GIS Cut Line= 2
      3636776.71     10521202.33       3636334.3     10519797.03
#Sta/Elev= 30
  4245.7  331.71  4331.8  330.58  4415.7   325.2    4434  323.93  4869.5  300.06
    4877  299.22  4889.1  294.82  4916.2  299.35  4921.4  294.06  4948.6   297.7
  4953.8  295.24  4962.4  295.26  4999.8  292.73  5002.5  292.23  5005.8  292.73
  5023.8  298.03  5044.7  295.99  5065.7  300.21    5089  301.97    5160   303.1
  5170.5   306.2  5185.7  306.41    5202  300.38  5218.1  307.83  5223.3  307.04
  5255.7  311.62  5282.8  318.21  5297.3   318.9  5385.2  318.78    5719  337.59
#Mann= 9 ,-1 , 0
  4245.7     .05       0  4415.7      .1       0    4434     .05       0
  4869.5     .16       0  4962.4     .05       0  4999.8     .03       0
  5005.8     .05       0    5089     .16       0  5297.3     .05       0
Bank Sta=4877,5023.8
XS Rating Curve= 0 ,0
Exp/Cntr=0.3,0.1

Type RM Length L Ch R = 1 ,3325    ,506,506,506
BEGIN DESCRIPTION:
Mapping XS 5f7a3c9e
END DESCRIPTION:
XS GIS Cut Line= 3
      3636972.01     10521020.03      3637115.24      10520577.3
       3636724.6     10519639.75
#Sta/Elev= 30
  4277.6  329.22  4340.5  328.51  4487.6  319.52  4571.7  316.11    4583  316.65
  4609.7  313.88  4666.3  312.57  4741.9  308.27  4821.8  301.99  4880.6   299.3
  4922.6  295.65  4934.8  293.36  4984.1  291.02  5001.9  289.34  5004.6  288.84
  5007.9  289.34  5062.8   294.2  5081.8  292.21  5111.1  294.25  5151.5  295.01
  5281.5  301.58  5411.5   313.6  5471.8  321.99  5501.1  324.78  5617.3  325.71
  5625.6  326.12  5631.1  328.14  5654.9  331.83  5684.1  332.64  5758.6  331.06
#Mann= 5 ,-1 , 0
  4277.6     .05       0  4984.1      .1       0  5001.9     .07       0
  5007.9      .1       0  5062.8     .05       0
Bank Sta=4922.6,5151.5
XS Rating Curve= 0 ,0
Exp/Cntr=0.3,0.1

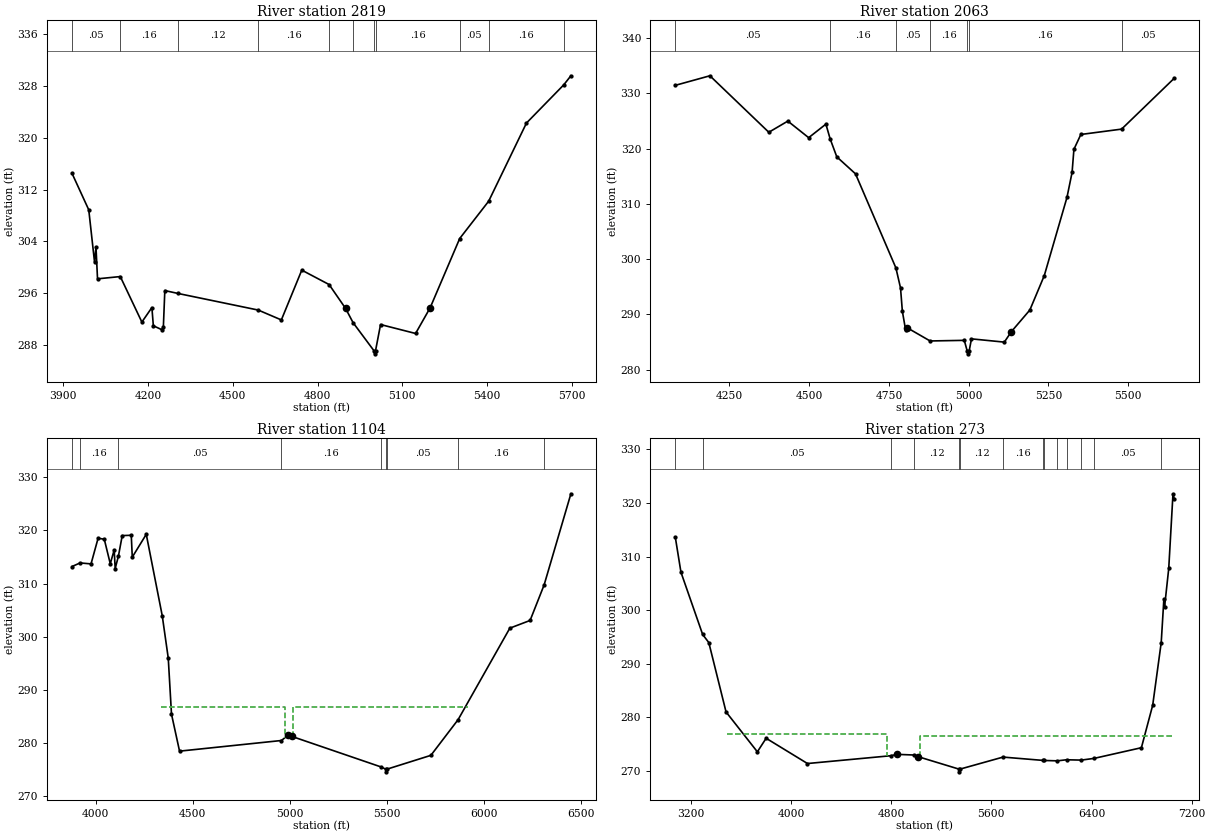
Type RM Length L Ch R = 1 ,2819    ,756,756,756
BEGIN DESCRIPTION:
Mapping XS 7212bf04
END DESCRIPTION:
XS GIS Cut Line= 2
       3637735.9     10521197.93       3637293.2      10519487.9
#Sta/Elev= 30
  3930.4  314.54    3990  308.88  4010.4  300.85  4015.6  303.11    4021  298.24
  4101.6  298.59    4178  291.57  4213.5  293.81  4218.6     291  4248.3   290.4
  4254.1  290.83  4259.3  296.43  4306.3  295.98  4590.1  293.42  4671.8   291.9
  4744.1  299.58  4840.8  297.36  4899.1  293.68  4925.7  291.48  4999.3  287.17
  5002.1  286.67  5005.3  287.17    5023  291.19    5147  289.81  5198.6  293.78
  5303.2  304.46  5405.8  310.22  5539.5  322.27  5671.3  328.15  5696.8  329.56
#Mann= 11 ,-1 , 0
  3930.4     .05       0  4101.6     .16       0  4306.3     .12       0
  4590.1     .16       0  4840.8     .05       0  4925.7     .16       0
  4999.3     .07       0  5005.3     .16       0  5303.2     .05       0
  5405.8     .16       0  5671.3     .05       0
#XS Ineff= 1 ,-1
 4012.78 4751.42   297.9
Permanent Ineff=
       F
Bank Sta=4899.1,5198.6
XS Rating Curve= 0 ,0
Exp/Cntr=0.3,0.1

Type RM Length L Ch R = 1 ,2063    ,959,959,959
BEGIN DESCRIPTION:
Mapping XS 15727b06
END DESCRIPTION:
XS GIS Cut Line= 2
      3638465.07     10520633.72      3637710.68     10519263.68
#Sta/Elev= 30
  4080.3  331.44  4188.8  333.17  4373.5  322.95  4433.1  324.97  4498.4  321.97
  4552.4  324.42  4565.8  321.74  4586.6   318.5  4645.2  315.43  4771.8  298.41
  4786.3  294.79  4792.1  290.55  4802.3  287.17    4808  287.55    4879  285.19
  4986.2   285.3  4995.4  283.36  4998.1  282.86  5001.4  283.36  5008.7  285.57
  5111.7  284.98  5133.7  286.87  5191.7  290.79  5236.9  297.01    5308  311.15
  5324.1   315.7  5329.8  319.86  5351.5  322.55  5479.3  323.52  5644.3  332.72
#Mann= 7 ,-1 , 0
  4080.3     .05       0  4565.8     .16       0  4771.8     .05       0
    4879     .16       0  4995.4     .07       0  5001.4     .16       0
  5479.3     .05       0
Bank Sta=4808,5133.7
XS Rating Curve= 0 ,0
Exp/Cntr=0.3,0.1

Type RM Length L Ch R = 1 ,1104    ,831,831,831
BEGIN DESCRIPTION:
UNT 124 IN BUCR 2.0
END DESCRIPTION:
XS GIS Cut Line= 4
       3638821.3     10520482.07       3638994.9     10519778.96
      3638708.45     10519084.51      3637658.09     10518772.01
#Sta/Elev= 30
  3876.9  313.21    3919  313.89  3975.4  313.71  4011.7  318.53  4043.6  318.35
  4074.5  313.74  4094.7  316.33  4099.8  312.84  4116.6  315.19  4136.1  319.03
  4182.7  319.09  4187.9  314.98    4260  319.27  4342.4  303.95  4373.3     296
    4390  285.46  4431.5  278.51  4956.5  280.51  4989.2  281.47  5010.9  281.27
  5469.1  275.55  5494.2  275.12  5496.9  274.62  5500.2  275.12  5726.7  277.72
    5867  284.43  6133.6  301.63    6238  303.08  6310.3  309.76  6448.2  326.89
#Mann= 9 ,-1 , 0
  3876.9     .05       0    3919     .16       0  4116.6     .05       0
  4956.5     .16       0  5469.1     .05       0  5494.2     .07       0
  5500.2     .05       0    5867     .16       0  6310.3     .05       0
#XS Ineff= 2 ,-1
 4336.93 4974.43286.8248 5017.69 5919.42286.7925
Permanent Ineff=
       F       F
Bank Sta=4989.2,5010.9
XS Rating Curve= 0 ,0
Exp/Cntr=0.3,0.1

Type RM Length L Ch R = 1 ,273     ,0,0,0
BEGIN DESCRIPTION:
UNT 124 IN BUCR 1.0
END DESCRIPTION:
XS GIS Cut Line= 4
      3639559.14     10520985.52      3639593.86     10519301.53
      3639524.42     10518711.25      3637884.16      10518242.6
#Sta/Elev= 30
    3076  313.64  3121.3  307.08  3294.5  295.48  3343.8  293.96  3481.4  281.03
  3731.5  273.59  3801.5  276.12  4131.6  271.41    4800  272.87  4843.4  273.12
  4981.4     273  5014.6  272.69  5342.7  270.36  5345.5  269.86  5348.7  270.36
  5693.3  272.61    6014  271.99  6022.8  271.98  6125.6  271.91  6200.4  272.11
  6319.1  272.05  6420.8  272.37  6798.3  274.36  6888.5  282.28  6956.5  293.95
  6977.7  302.04  6982.9  300.51  7016.7  307.81  7050.5  321.71  7060.6  320.72
#Mann= 14 ,-1 , 0
    3076     .16       0  3294.5     .05       0    4800     .16       0
  4981.4     .12       0  5342.7     .07       0  5348.7     .12       0
  5693.3     .16       0    6014     .07       0  6022.8     .05       0
  6125.6     .07       0  6200.4     .05       0  6319.1     .07       0
  6420.8     .05       0  6956.5     .16       0
#XS Ineff= 2 ,-1
  3485.8 4767.05  276.91 5028.41  7048.3276.5573
Permanent Ineff=
       F       F
Bank Sta=4843.4,5014.6
XS Rating Curve= 0 ,0
Exp/Cntr=0.3,0.1

Chan Stop Cuts=-1
Use User Specified Reach Order=0
Composite Channel Slope=5