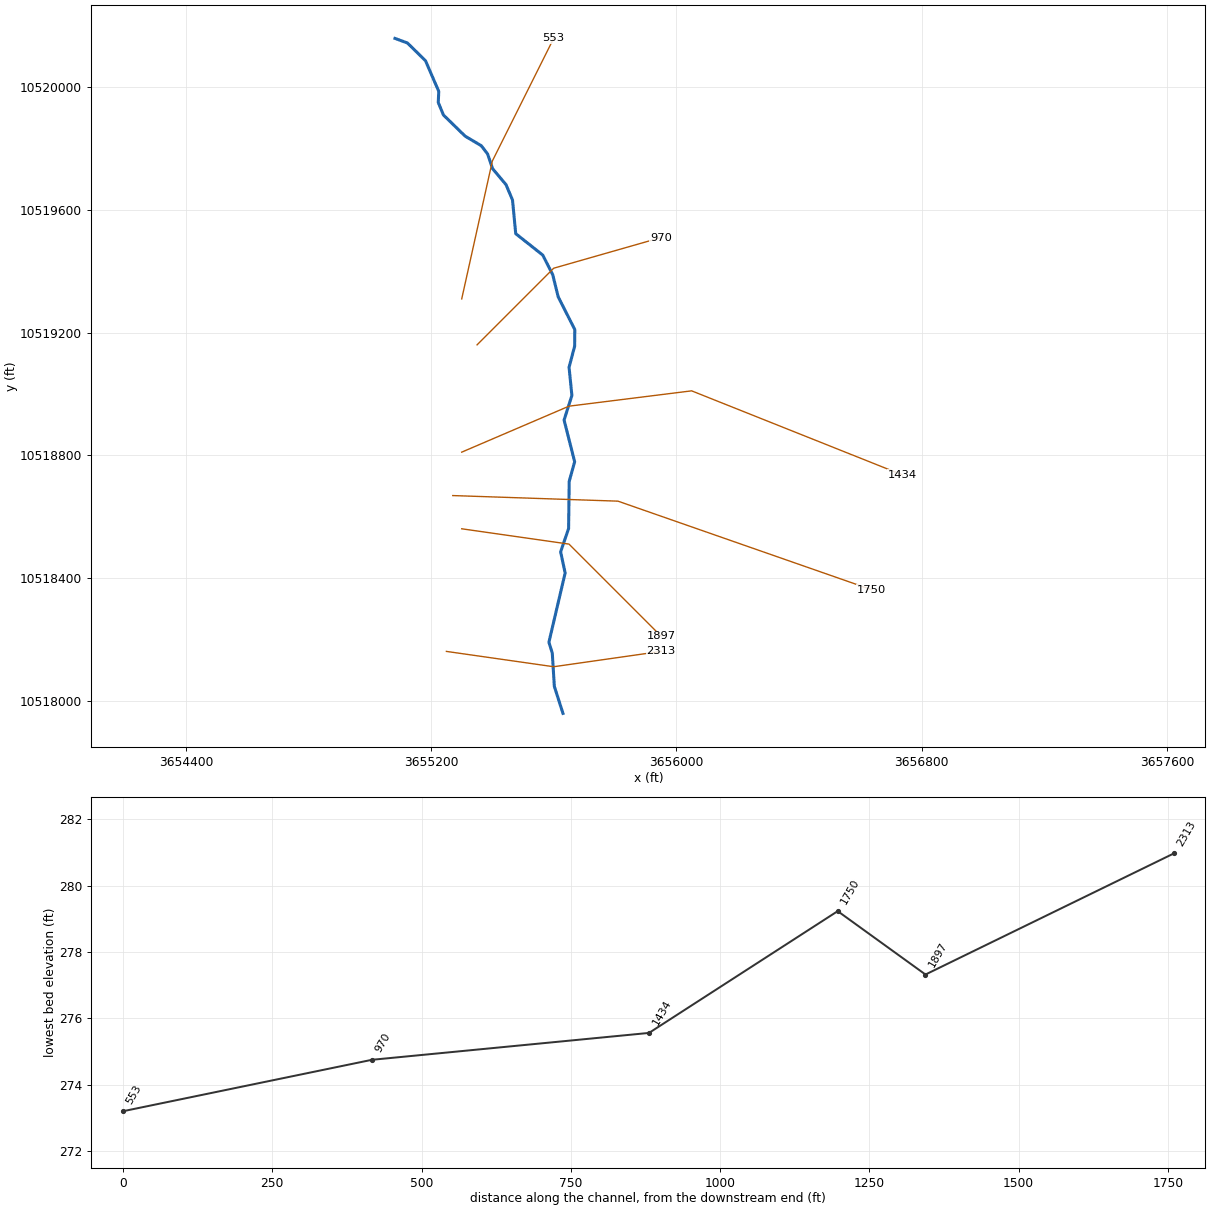
--- UNT 128 IN BUCR.prj (project) ---

Proj Title=UNT 128 IN BUCR Base Level Engineering
Current Plan=p01
Default Exp/Contr=0.3,0.1
English Units
Geom File=g01
Flow File=f01
Plan File=p01
Y Axis Title=Elevation
X Axis Title(PF)=Main Channel Distance
X Axis Title(XS)=Station
BEGIN DESCRIPTION:
UNT 128 IN BUCR
END DESCRIPTION:
DSS Export Rating Curves= 0
DSS Export Rating Curve Sorted= 0
DSS Export Volume Flow Curves= 0
DXF OffsetX= 0
DXF OffsetY= 0
DXF ScaleX= 1
DXF ScaleY= 10

--- UNT 128 IN BUCR.p01 (plan) ---

Plan Title=Multiple Run
Short Identifier=Multiple
Geom File=g01
Flow File=f01
Subcritical Flow
K Sum by GR= 0
Std Step Tol= 0.01
Critical Tol= 0.01
Num of Std Step Trials= 20
Max Error Tol= 0.3
Flow Tol Ratio= 0.001
Split Flow NTrial= 30
Split Flow Tol= 0.02
Split Flow Ratio= 0.02
Log Output Level= 0
Friction Slope Method= 1
Unsteady Friction Slope Method= 2
Unsteady Bridges Friction Slope Method= 1
Parabolic Critical Depth
Global Vel Dist=  1 , 1 , 1
Global Log Level= 0
CheckData=True
Encroach Param= -1, 0, 0, 0
BEGIN DESCRIPTION:
Multiple Run
END DESCRIPTION:

--- UNT 128 IN BUCR.f01 (steady flow) ---

Flow Title=Multiple
Number of Profiles=7
Profile Names=10-year,25-year,50-year,1pct_min,100-year,1pct_plu,500-year
River Rch & RM= UNT 128 IN BUCR,Reach-1,2313
     480     647     784     699     945    1278    1378
Boundary for River Rch & Prof#=UNT 128 IN BUCR,Reach-1,1
Up Type=0
Dn Type=3
Dn Slope=0.005
Boundary for River Rch & Prof#=UNT 128 IN BUCR,Reach-1,2
Up Type=0
Dn Type=3
Dn Slope=0.005
Boundary for River Rch & Prof#=UNT 128 IN BUCR,Reach-1,3
Up Type=0
Dn Type=3
Dn Slope=0.005
Boundary for River Rch & Prof#=UNT 128 IN BUCR,Reach-1,4
Up Type=0
Dn Type=3
Dn Slope=0.005
Boundary for River Rch & Prof#=UNT 128 IN BUCR,Reach-1,5
Up Type=0
Dn Type=3
Dn Slope=0.005
Boundary for River Rch & Prof#=UNT 128 IN BUCR,Reach-1,6
Up Type=0
Dn Type=3
Dn Slope=0.005
Boundary for River Rch & Prof#=UNT 128 IN BUCR,Reach-1,7
Up Type=0
Dn Type=3
Dn Slope=0.005

--- UNT 128 IN BUCR.g01 (geometry) ---

Geom Title=Existing Conditions
Program Version=4.10

River Reach=UNT 128 IN BUCR ,Reach-1
Reach XY= 30
      3655629.87     10517958.03      3655601.75       10518046.
        3655595.       10518155.        3655584.       10518190.
        3655637.       10518416.      3655622.25       10518485.
      3655648.25       10518561.      3655650.25       10518715.
        3655668.       10518779.       3655633.5       10518915.
        3655659.       10518995.      3655649.75       10519087.
        3655668.       10519156.       3655668.5       10519210.
      3655614.25       10519317.       3655596.5       10519389.
        3655564.       10519453.      3655475.75       10519523.
      3655465.25       10519633.        3655444.       10519683.
      3655400.25       10519735.        3655384.       10519783.
      3655363.25       10519810.      3655310.75       10519841.
        3655240.       10519910.        3655223.       10519951.
      3655224.75       10519987.       3655181.5       10520087.
       3655122.5       10520145.      3655081.75       10520160.

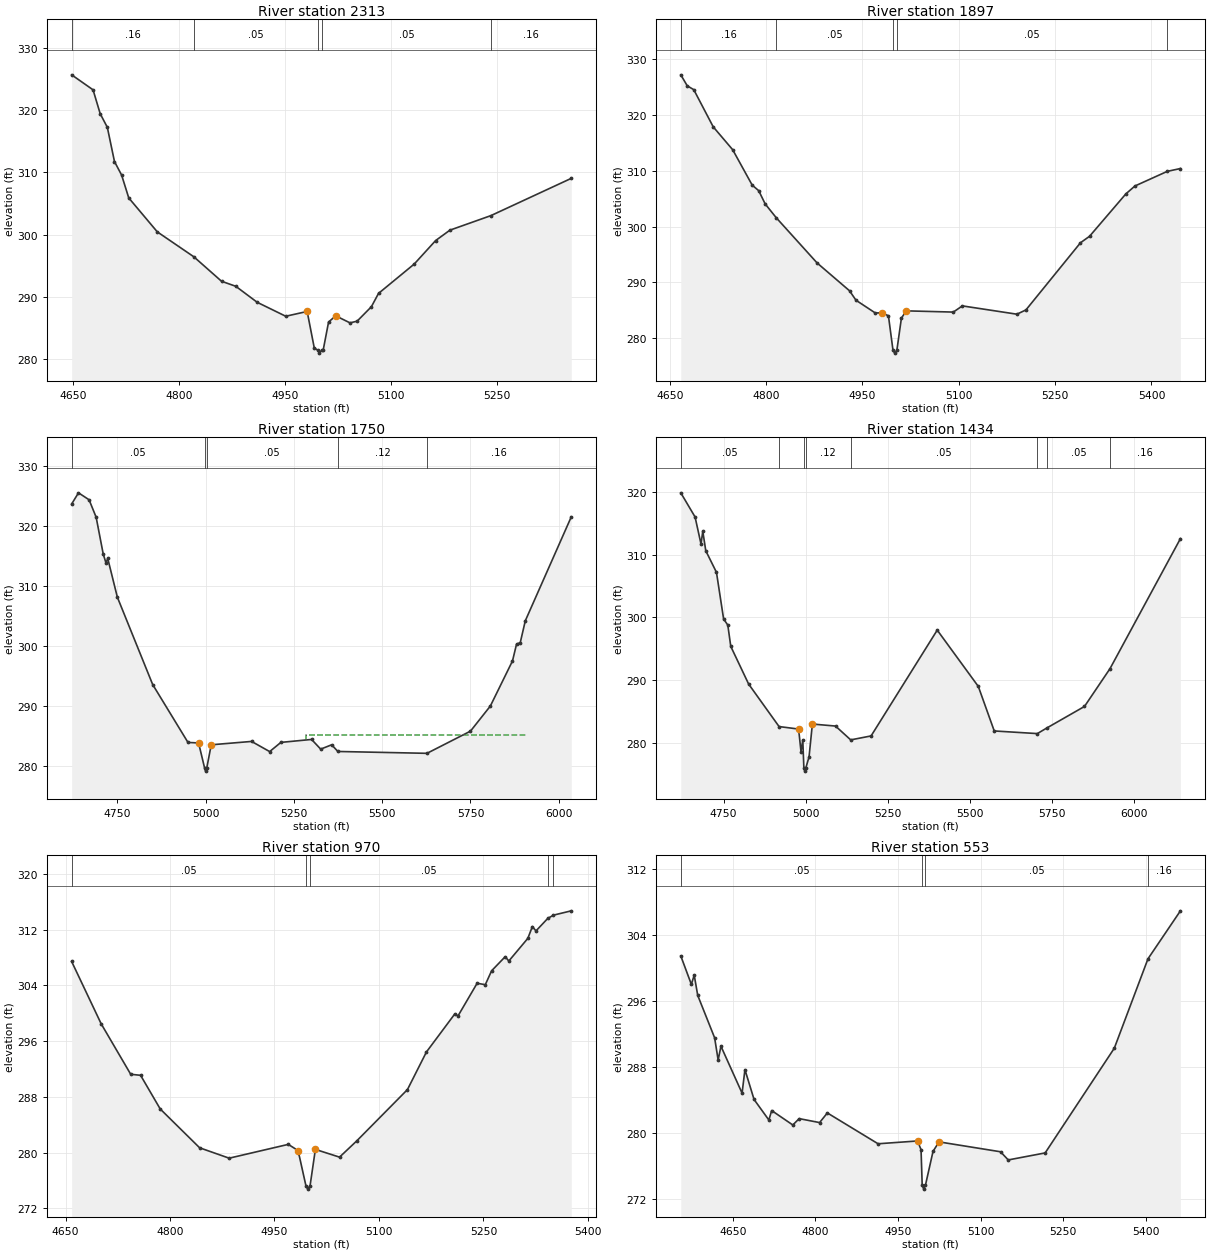
Type RM Length L Ch R = 1 ,2313    ,416,416,416
BEGIN DESCRIPTION:
UNT 128 IN BUCR 5.0
END DESCRIPTION:
XS GIS Cut Line= 3
      3655249.65     10518160.18      3655599.61     10518110.19
      3655949.64     10518160.19
#Sta/Elev= 30
  4647.9  325.65  4678.2  323.24  4688.3  319.41  4698.4  317.22  4708.5  311.73
  4718.6  309.56  4728.7  305.89  4769.1  300.44  4820.9  296.43    4860  292.51
  4880.2   291.7  4910.5  289.13  4950.9  286.89  4981.2  287.66  4991.3  281.78
  4995.9  281.47  4998.6  280.97  5001.9  281.47  5003.9  281.47  5011.5  285.96
  5021.6  286.96  5041.8  285.83  5051.9   286.1  5072.1  288.42  5082.2  290.56
  5132.7  295.27    5163  299.04  5183.2  300.71  5241.3  303.05    5355  309.03
#Mann= 5 ,-1 , 0
  4647.9     .16       0  4820.9     .05       0  4995.9     .03       0
  5001.9     .05       0  5241.3     .16       0
Bank Sta=4981.2,5021.6
XS Rating Curve= 0 ,0
Exp/Cntr=0.3,0.1

Type RM Length L Ch R = 1 ,1897    ,147,147,147
BEGIN DESCRIPTION:
UNT 128 IN BUCR 4.0
END DESCRIPTION:
XS GIS Cut Line= 3
      3655299.57     10518560.19      3655649.61     10518510.19
      3655949.64     10518210.16
#Sta/Elev= 30
  4667.2  327.22  4677.3  325.24  4687.4  324.56  4717.7  317.89    4748  313.79
  4778.4  307.44  4788.5  306.45  4798.6  304.07  4815.7  301.61  4879.4  293.49
  4929.9   288.5    4940   286.8  4970.3   284.5  4980.4  284.59  4990.5     284
  4997.6  277.82  5000.3  277.32  5003.6  277.82  5010.7   283.6  5018.3   284.9
  5091.5  284.68  5105.6  285.79  5190.5   284.3  5204.6  285.07  5289.5  297.11
  5303.6  298.27  5360.2  305.88  5374.3  307.29  5424.6  309.91  5445.1  310.42
#Mann= 5 ,-1 , 0
  4667.2     .16       0  4815.7     .05       0  4997.6     .03       0
  5003.6     .05       0  5424.6     .16       0
Bank Sta=4980.4,5018.3
XS Rating Curve= 0 ,0
Exp/Cntr=0.3,0.1

Type RM Length L Ch R = 1 ,1750    ,316,316,316
BEGIN DESCRIPTION:
Mapping XS 6d3f1111
END DESCRIPTION:
XS GIS Cut Line= 3
      3655270.27     10518668.57      3655809.36     10518650.34
      3656636.05     10518361.78
#Sta/Elev= 30
  4620.5  323.66  4639.9  325.52  4669.9  324.36  4689.9  321.46  4709.9  315.35
  4717.7  313.86  4722.7  314.61  4749.9  308.17    4850  293.63    4950     284
    4980  283.92  4997.1  279.73  4999.8  279.23  5003.1  279.73  5015.8  283.61
  5130.1  284.17  5181.3  282.48  5213.1  284.01    5300   284.5  5325.8  282.89
  5356.9  283.61  5374.4   282.5  5626.8  282.19    5750  285.88  5806.3  290.06
    5869  297.56  5880.4  300.34    5891  300.61  5905.3  304.24  6035.5  321.53
#Mann= 5 ,-1 , 0
  4620.5     .05       0  4997.1     .03       0  5003.1     .05       0
  5374.4     .12       0  5626.8     .16       0
#XS Ineff= 1 ,-1
 5283.64    5910  285.17
Permanent Ineff=
       F
Bank Sta=4980,5015.8
XS Rating Curve= 0 ,0
Exp/Cntr=0.3,0.1

Type RM Length L Ch R = 1 ,1434    ,464,464,464
BEGIN DESCRIPTION:
UNT 128 IN BUCR 3.0
END DESCRIPTION:
XS GIS Cut Line= 4
      3655299.65     10518810.21      3655649.61     10518960.19
      3656049.61     10519010.19      3656735.52     10518736.65
#Sta/Elev= 30
  4619.5  319.83    4663  315.99  4681.1  311.69  4686.5  313.72  4695.6  310.62
  4728.2  307.18    4750  299.75  4762.7   298.8  4771.8   295.4  4826.2  289.41
  4918.9  282.65  4978.5  282.25  4985.7  278.68  4991.2   280.5  4994.5  276.06
  4997.3  275.56  5000.5  276.06  5010.3  277.84  5020.4  283.05  5090.9  282.73
  5137.2  280.53  5199.3  281.16  5400.8  297.99    5526  289.03  5574.5  281.95
  5705.9  281.53  5734.3  282.41  5849.5  285.85  5927.3  291.87  6141.8  312.55
#Mann= 8 ,-1 , 0
  4619.5     .05       0  4918.9     .12       0  4994.5     .07       0
  5000.5     .12       0  5137.2     .05       0  5705.9     .12       0
  5734.3     .05       0  5927.3     .16       0
#XS Ineff= 1 ,-1
 5465.45 5982.73  288.21
Permanent Ineff=
       F
Bank Sta=4978.5,5020.4
XS Rating Curve= 0 ,0
Exp/Cntr=0.3,0.1

Type RM Length L Ch R = 1 ,970     ,417,417,417
BEGIN DESCRIPTION:
UNT 128 IN BUCR 2.0
END DESCRIPTION:
XS GIS Cut Line= 3
      3655349.64     10519160.22      3655599.61     10519410.19
      3655949.59     10519510.18
#Sta/Elev= 30
  4658.7  307.41  4701.1  298.47  4743.5  291.23  4757.7  291.08  4785.9  286.25
  4842.5  280.68  4884.9  279.19  4969.8  281.17  4983.9  280.28  4995.1  275.25
  4997.8  274.75  5001.1  275.25  5008.7  280.45  5043.4  279.34  5068.1  281.67
  5140.9  289.03  5168.2  294.43  5208.5  299.83  5213.7  299.63    5241  304.29
  5252.7  304.08  5261.8  306.08  5281.3   308.1  5286.5  307.48  5313.8  310.73
  5320.3  312.42  5325.5   311.8  5342.4  313.59  5350.6  314.06  5376.2  314.68
#Mann= 5 ,-1 , 0
  4658.7     .05       0  4995.1     .03       0  5001.1     .05       0
  5342.4     .16       0  5350.6     .05       0
Bank Sta=4983.9,5008.7
XS Rating Curve= 0 ,0
Exp/Cntr=0.3,0.1

Type RM Length L Ch R = 1 ,553     ,0,0,0
BEGIN DESCRIPTION:
UNT 128 IN BUCR 1.0
END DESCRIPTION:
XS GIS Cut Line= 3
       3655299.6     10519310.15      3655399.61     10519760.19
       3655599.6     10520160.16
#Sta/Elev= 30
  4555.2  301.48  4574.4  298.03  4579.6  299.15    4586  296.69  4616.7  291.55
  4623.1  288.86  4628.2  290.53  4666.6  284.84  4671.8  287.69  4688.4  284.07
  4715.3  281.58  4720.4  282.73  4758.8  280.98  4770.4  281.75  4807.5  281.27
  4821.6  282.44  4913.8   278.7  4985.5  279.04  4991.9  277.99    4994   273.7
  4996.8   273.2    5000   273.7  5013.7  277.78  5024.6  278.93  5136.4  277.73
  5150.4  276.74  5217.5  277.59  5343.2  290.29  5404.4  301.13  5463.4  306.95
#Mann= 4 ,-1 , 0
  4555.2     .05       0    4994     .03       0    5000     .05       0
  5404.4     .16       0
Bank Sta=4985.5,5024.6
XS Rating Curve= 0 ,0
Exp/Cntr=0.3,0.1

Chan Stop Cuts=-1
Use User Specified Reach Order=0
Composite Channel Slope=5