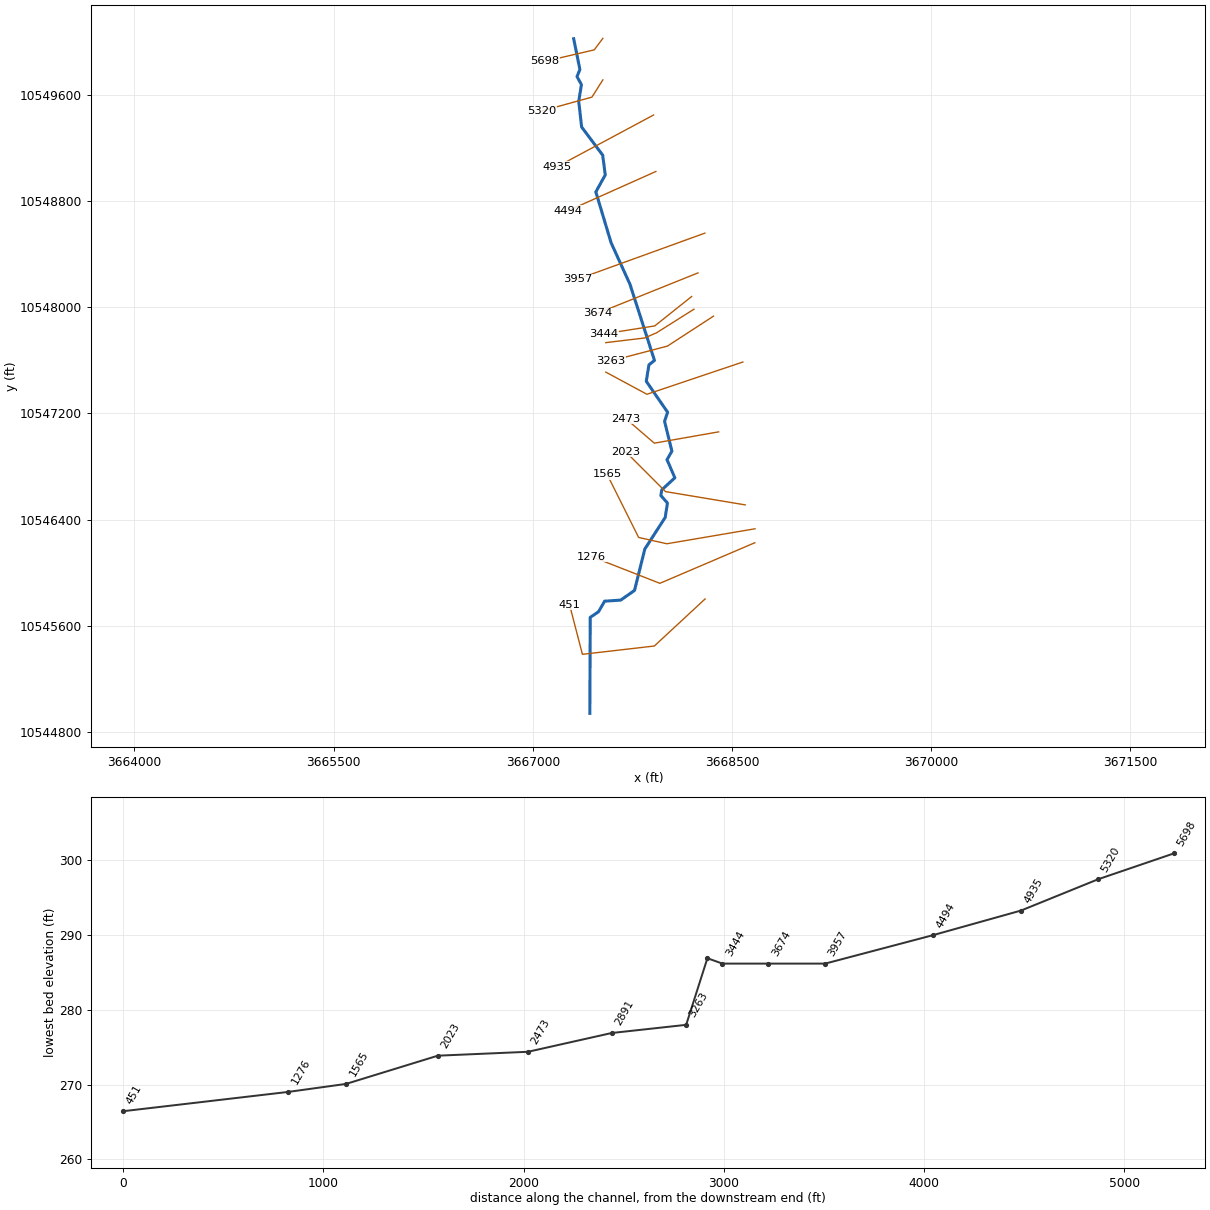
--- UNT 137 IN BUCR.prj (project) ---

Proj Title=UNT 137 IN BUCR Base Level Engineering
Current Plan=p01
Default Exp/Contr=0.3,0.1
English Units
Geom File=g01
Flow File=f01
Plan File=p01
BEGIN DESCRIPTION:
UNT 137 IN BUCR
END DESCRIPTION:

--- UNT 137 IN BUCR.p01 (plan) ---

Plan Title=Multiple Run
Short Identifier=Multiple
Geom File=g01
Flow File=f01
Subcritical Flow
K Sum by GR= 0
Std Step Tol= 0.01
Critical Tol= 0.01
Num of Std Step Trials= 20
Max Error Tol= 0.3
Flow Tol Ratio= 0.001
Split Flow NTrial= 30
Split Flow Tol= 0.02
Split Flow Ratio= 0.02
Log Output Level= 0
Friction Slope Method= 1
Unsteady Friction Slope Method= 2
Unsteady Bridges Friction Slope Method= 1
Parabolic Critical Depth
Global Vel Dist=  1 , 1 , 1
Global Log Level= 0
CheckData=True
Encroach Param= -1, 0, 0, 0
BEGIN DESCRIPTION:
Multiple Run
END DESCRIPTION:

--- UNT 137 IN BUCR.f01 (steady flow) ---

Flow Title=Multiple
Number of Profiles=7
Profile Names=10-year,25-year,50-year,1pct_min,100-year,1pct_plu,500-year
River Rch & RM= UNT 137 IN BUCR,Reach-1,5698
     617     843    1031     927    1253    1695    1859
Boundary for River Rch & Prof#=UNT 137 IN BUCR,Reach-1,1
Up Type=0
Dn Type=3
Dn Slope=0.005
Boundary for River Rch & Prof#=UNT 137 IN BUCR,Reach-1,2
Up Type=0
Dn Type=3
Dn Slope=0.005
Boundary for River Rch & Prof#=UNT 137 IN BUCR,Reach-1,3
Up Type=0
Dn Type=3
Dn Slope=0.005
Boundary for River Rch & Prof#=UNT 137 IN BUCR,Reach-1,4
Up Type=0
Dn Type=3
Dn Slope=0.005
Boundary for River Rch & Prof#=UNT 137 IN BUCR,Reach-1,5
Up Type=0
Dn Type=3
Dn Slope=0.005
Boundary for River Rch & Prof#=UNT 137 IN BUCR,Reach-1,6
Up Type=0
Dn Type=3
Dn Slope=0.005
Boundary for River Rch & Prof#=UNT 137 IN BUCR,Reach-1,7
Up Type=0
Dn Type=3
Dn Slope=0.005

--- UNT 137 IN BUCR.g01 (geometry) ---

Geom Title=Existing Conditions

River Reach=UNT 137 IN BUCR,Reach-1
Reach XY= 30
      3667307.75     10550021.00      3667354.75     10549789.00
      3667332.75     10549736.00      3667366.25     10549675.00
      3667345.75     10549550.00      3667367.75     10549356.00
      3667526.25     10549144.00      3667545.50     10548995.00
      3667474.75     10548867.00      3667589.75     10548484.00
      3667732.00     10548171.00      3667916.50     10547598.00
      3667874.50     10547565.00      3667854.50     10547441.00
      3668015.25     10547208.00      3667992.25     10547140.00
      3668047.50     10546915.00      3668010.75     10546851.00
      3668069.75     10546714.00      3667971.00     10546623.00
      3667964.25     10546581.00      3668014.00     10546524.00
      3667997.25     10546416.00      3667843.75     10546178.00
      3667766.00     10545866.00      3667662.00     10545793.00
      3667541.00     10545785.00      3667494.50     10545705.00
      3667432.50     10545663.00      3667429.50     10544940.00

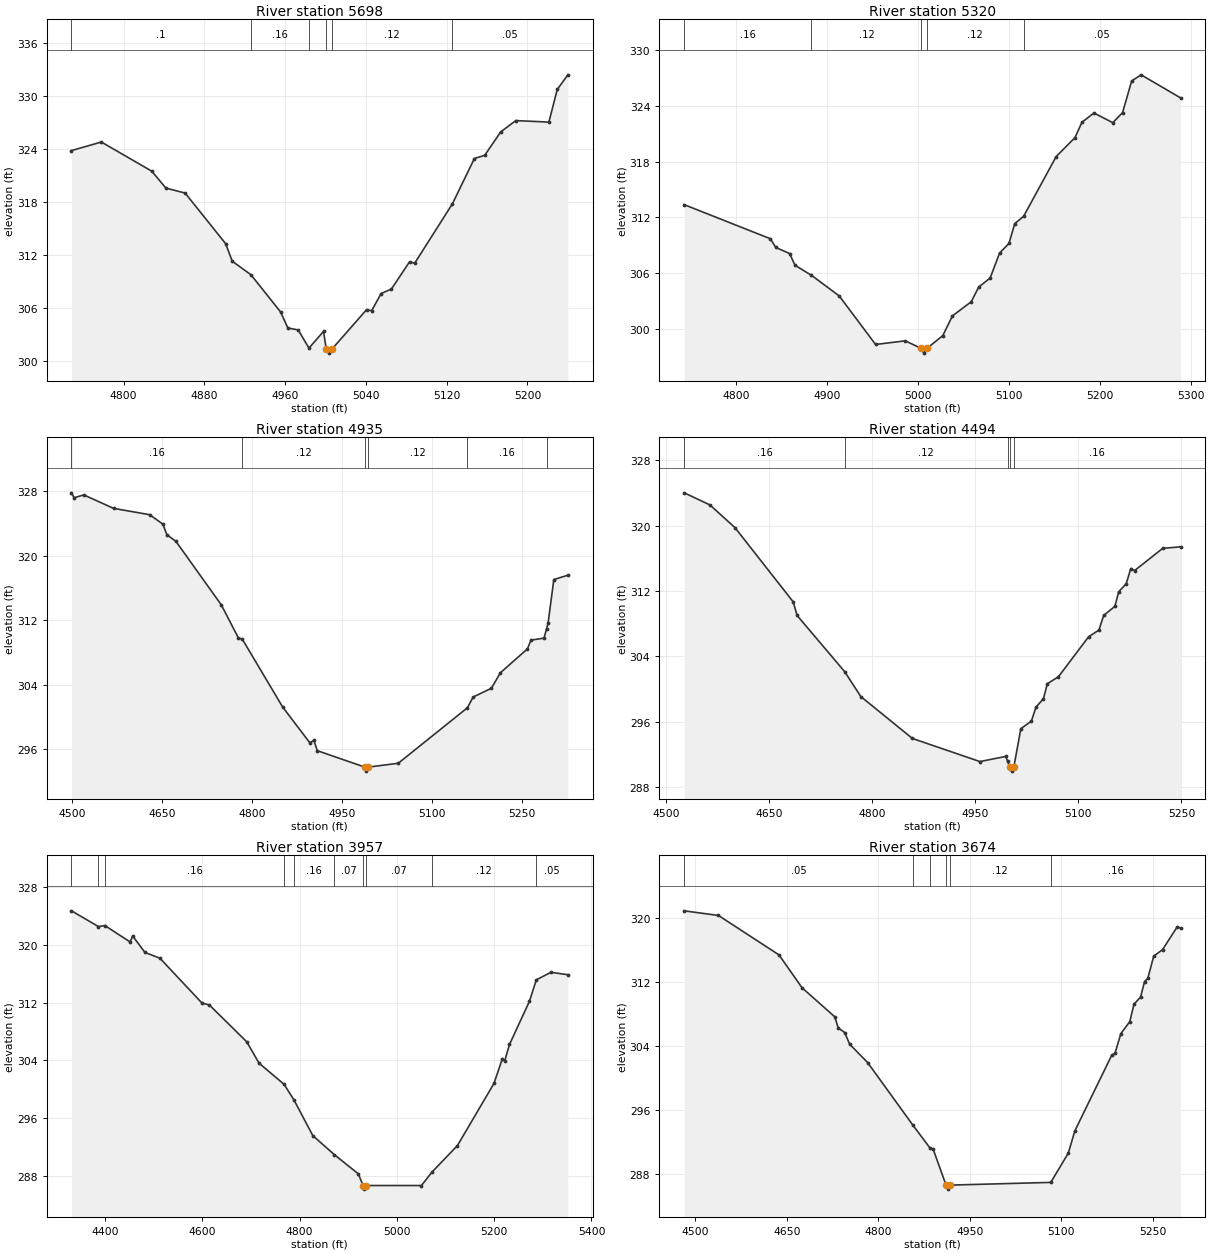
Type RM Length L Ch R = 1,5698,378,378,378
BEGIN DESCRIPTION:
UNT 137 IN BUCR 6.0
END DESCRIPTION:
XS GIS Cut Line= 3
      3667527.79     10550023.87      3667462.65     10549937.02
      3667089.37     10549850.21
#Sta/Elev= 30
  4748.3  323.84  4777.9  324.81  4827.9  321.50  4841.8  319.59  4860.9  319.02
  4901.0  313.29  4907.6  311.29  4926.1  309.76  4955.4  305.55  4962.7  303.72
  4972.9  303.50  4983.6  301.44  4998.0  303.33  5000.7  301.37  5003.5  300.87
  5006.7  301.37  5040.6  305.79  5045.7  305.68  5055.1  307.63  5065.3  308.14
  5083.2  311.22  5088.3  311.06  5125.7  317.80  5147.5  322.94  5157.7  323.30
  5173.6  325.96  5188.5  327.24  5221.3  327.07  5229.6  330.77  5240.1  332.43
#Mann=6,-1,0
  4748.3     0.1       0  4926.1    0.16       0  4983.6    0.12       0
  5000.7    0.07       0  5006.7    0.12       0  5125.7    0.05       0
Bank Sta=5000.7,5006.7
Exp/Cntr=0.3,0.1

Type RM Length L Ch R = 1,5320,385,385,385
BEGIN DESCRIPTION:
Mapping XS c648ee34
END DESCRIPTION:
XS GIS Cut Line= 3
      3667527.76     10549711.33      3667445.29     10549581.12
      3667067.73     10549476.97
#Sta/Elev= 30
  4743.1  313.37  4837.8  309.71  4843.8  308.77  4859.0  308.12  4864.9  306.86
  4883.0  305.78  4913.5  303.57  4953.5  298.35  4986.1  298.74  5003.9  297.92
  5006.6  297.42  5009.9  297.92  5027.4  299.30  5038.0  301.42  5058.7  302.94
  5066.9  304.52  5079.5  305.49  5089.9  308.18  5100.2  309.20  5106.5  311.33
  5116.3  312.12  5152.1  318.54  5172.8  320.58  5180.4  322.22  5193.6  323.22
  5214.3  322.18  5225.1  323.26  5235.1  326.66  5245.5  327.32  5288.9  324.84
#Mann=5,-1,0
  4743.1    0.16       0  4883.0    0.12       0  5003.9    0.07       0
  5009.9    0.12       0  5116.3    0.05       0
Bank Sta=5003.9,5009.9
Exp/Cntr=0.3,0.1

Type RM Length L Ch R = 1,4935,441,441,441
BEGIN DESCRIPTION:
Mapping XS 7c61b2f2
END DESCRIPTION:
XS GIS Cut Line= 2
      3667909.69     10549446.56      3667180.53     10549055.94
#Sta/Elev= 30
  4499.3  327.83  4503.6  327.22  4519.9  327.57  4569.4  325.90  4629.6  325.11
  4651.5  323.94  4658.2  322.64  4673.4  321.79  4749.0  313.90  4777.4  309.80
  4783.9  309.65  4851.1  301.22  4896.4  296.77  4903.3  297.05  4909.0  295.78
  4988.1  293.74  4990.8  293.24  4994.1  293.74  5043.9  294.22  5159.0  301.11
  5168.7  302.45  5199.1  303.54  5214.1  305.47  5259.2  308.44  5264.9  309.52
  5286.8  309.77  5291.1  310.96  5293.5  311.62  5303.1  317.05  5326.5  317.59
#Mann=6,-1,0
  4499.3    0.16       0  4783.9    0.12       0  4988.1    0.07       0
  4994.1    0.12       0  5159.0    0.16       0  5291.1    0.05       0
Bank Sta=4988.1,4994.1
Exp/Cntr=0.3,0.1

Type RM Length L Ch R = 1,4494,537,537,537
BEGIN DESCRIPTION:
Mapping XS e836f159
END DESCRIPTION:
XS GIS Cut Line= 2
      3667927.02     10549021.21      3667267.33     10548726.08
#Sta/Elev= 30
  4526.1  324.01  4563.5  322.53  4600.0  319.75  4684.9  310.65  4690.4  309.00
  4759.8  302.11  4783.2  299.07  4858.3  293.94  4956.6  291.11  4994.3  291.74
  4996.9  291.15  5000.0  290.44  5002.7  289.94  5006.0  290.44  5016.2  295.14
  5031.6  296.06  5038.2  297.77  5049.1  298.81  5054.8  300.64  5071.0  301.50
  5114.8  306.38  5129.9  307.21  5136.8  309.00  5153.1  310.11  5158.7  311.90
  5169.6  312.88  5176.3  314.74  5181.8  314.49  5222.7  317.21  5248.8  317.40
#Mann=5,-1,0
  4526.1    0.16       0  4759.8    0.12       0  4996.9    0.16       0
  5000.0    0.07       0  5006.0    0.16       0
Bank Sta=5000,5006
Exp/Cntr=0.3,0.1

Type RM Length L Ch R = 1,3957,283,283,283
BEGIN DESCRIPTION:
Mapping XS 2c203672
END DESCRIPTION:
XS GIS Cut Line= 2
      3668295.99     10548556.82      3667336.80     10548209.60
#Sta/Elev= 30
  4331.4  324.71  4386.8  322.53  4400.0  322.67  4451.8  320.40  4457.1  321.23
  4482.4  318.94  4513.1  318.15  4599.7  311.92  4614.7  311.67  4691.6  306.56
  4716.9  303.60  4768.2  300.68  4788.5  298.52  4827.4  293.56  4871.9  290.91
  4920.8  288.27  4930.7  286.65  4933.5  286.15  4936.7  286.65  5050.7  286.65
  5072.5  288.53  5124.6  292.19  5199.6  300.79  5216.6  304.15  5221.9  303.96
  5231.5  306.19  5272.5  312.17  5286.7  315.15  5316.6  316.19  5351.5  315.86
#Mann=10,-1,0
  4331.4    0.16       0  4386.8    0.05       0  4400.0    0.16       0
  4768.2    0.12       0  4788.5    0.16       0  4871.9    0.07       0
  4930.7    0.07       0  4936.7    0.07       0  5072.5    0.12       0
  5286.7    0.05       0
Bank Sta=4930.7,4936.7
Exp/Cntr=0.3,0.1

Type RM Length L Ch R = 1,3674,230,230,230
BEGIN DESCRIPTION:
Mapping XS fb7218d5
END DESCRIPTION:
XS GIS Cut Line= 2
      3668243.91     10548257.34      3667488.73     10547953.53
#Sta/Elev= 30
  4481.9  320.85  4538.1  320.27  4637.4  315.35  4675.2  311.25  4728.9  307.63
  4734.4  306.25  4745.2  305.67  4753.1  304.23  4782.7  301.93  4856.3  294.19
  4884.4  291.33  4890.2  291.11  4911.3  286.65  4914.1  286.15  4917.3  286.65
  5083.0  286.99  5111.7  290.63  5122.5  293.42  5183.0  302.85  5188.4  303.10
  5197.9  305.54  5212.6  307.04  5219.5  309.21  5230.3  310.11  5236.8  312.03
  5242.2  312.44  5251.8  315.20  5266.3  316.01  5290.5  318.87  5295.9  318.69
#Mann=6,-1,0
  4481.9    0.05       0  4856.3    0.16       0  4884.4    0.12       0
  4911.3    0.07       0  4917.3    0.12       0  5083.0    0.16       0
Bank Sta=4911.3,4917.3
Exp/Cntr=0.3,0.1

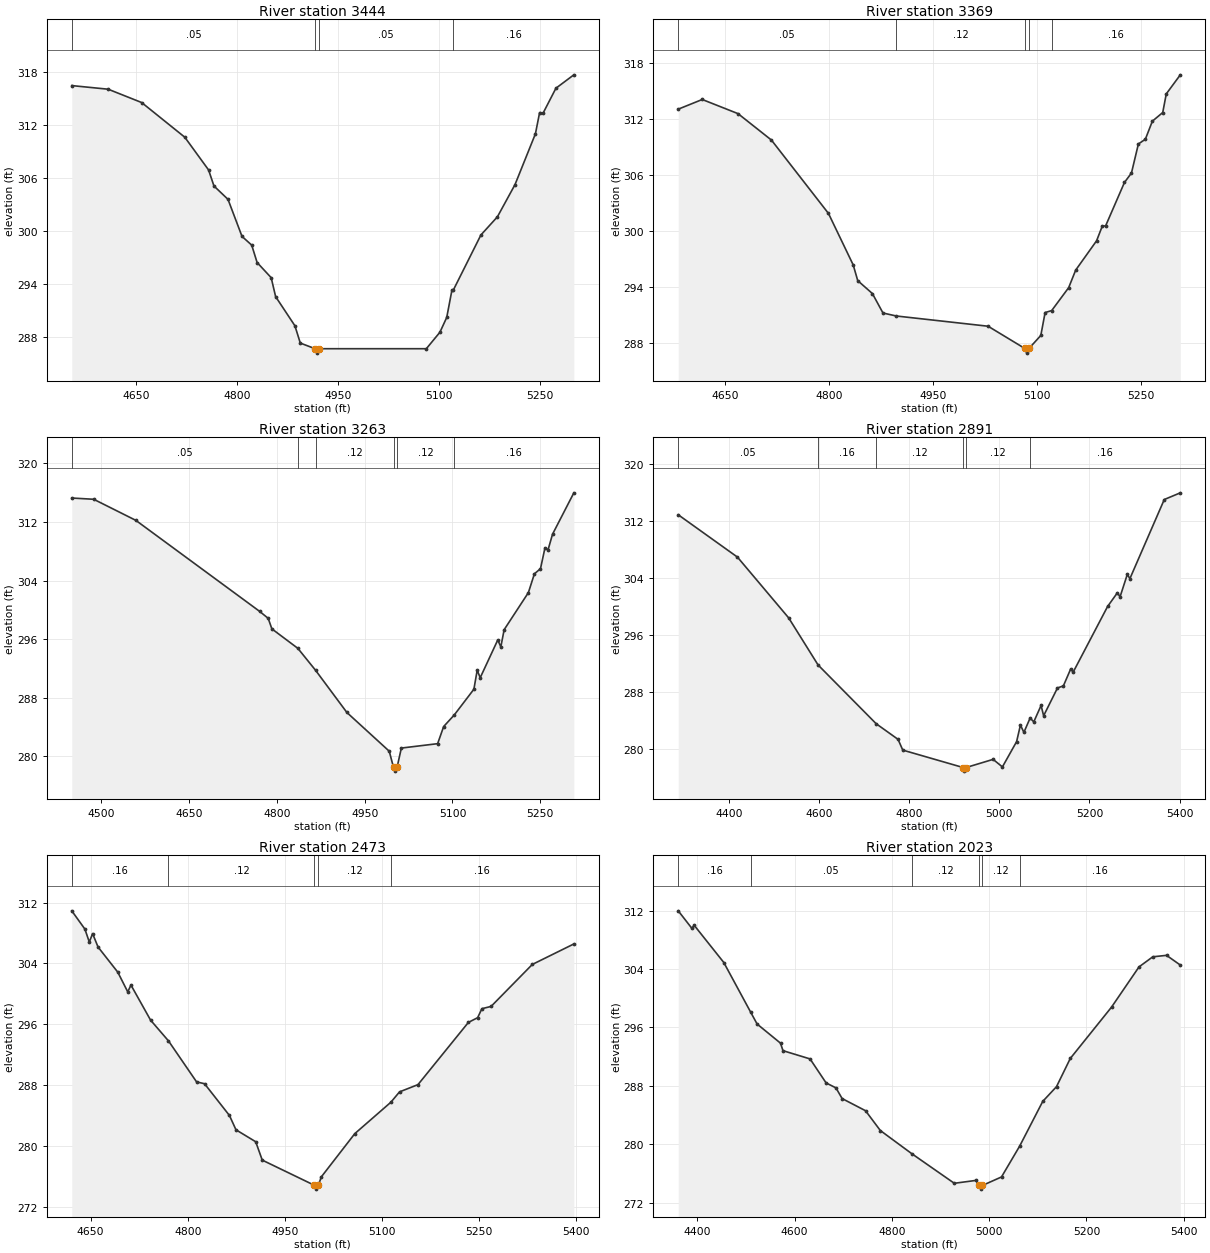
Type RM Length L Ch R = 1,3444,75,75,75
BEGIN DESCRIPTION:
Mapping XS 52d4e12e
END DESCRIPTION:
XS GIS Cut Line= 3
      3668196.19     10548079.41      3667918.38     10547858.03
      3667533.34     10547797.46
#Sta/Elev= 30
  4554.9  316.47  4608.9  316.06  4658.6  314.55  4722.6  310.62  4757.9  306.91
  4765.9  305.09  4786.7  303.58  4807.5  299.38  4821.9  298.39  4829.9  296.42
  4850.8  294.70  4857.4  292.55  4886.0  289.25  4894.0  287.29  4916.0  286.65
  4918.8  286.15  4922.0  286.65  5081.0  286.65  5101.2  288.52  5111.3  290.20
  5118.9  293.25  5120.9  293.27  5162.0  299.54  5186.5  301.60  5212.6  305.25
  5242.9  311.01  5249.1  313.41  5254.2  313.34  5273.3  316.17  5299.9  317.69
#Mann=4,-1,0
  4554.9    0.05       0  4916.0    0.07       0  4922.0    0.05       0
  5120.9    0.16       0
Bank Sta=4916,4922
Exp/Cntr=0.3,0.1

Type RM Length L Ch R = 1,3369,106,106,106
BEGIN DESCRIPTION:
Mapping XS 80b03615
END DESCRIPTION:
XS GIS Cut Line= 4
      3668213.55     10547983.92      3667931.40     10547805.95
      3667840.26     10547766.89      3667549.47     10547732.17
#Sta/Elev= 30
  4581.7  313.08  4616.4  314.12  4668.1  312.60  4716.4  309.76  4798.8  301.88
  4834.6  296.34  4841.1  294.66  4862.3  293.27  4877.6  291.18  4896.8  290.86
  5029.5  289.76  5082.6  287.37  5085.4  286.87  5088.6  287.37  5105.7  288.77
  5111.9  291.23  5121.4  291.44  5146.0  293.91  5156.1  295.79  5186.3  298.94
  5194.4  300.49  5199.4  300.55  5226.6  305.21  5236.7  306.22  5246.7  309.34
  5256.8  309.85  5266.9  311.79  5281.9  312.72  5287.0  314.72  5307.3  316.77
#Mann=5,-1,0
  4581.7    0.05       0  4896.8    0.12       0  5082.6    0.07       0
  5088.6    0.12       0  5121.4    0.16       0
Bank Sta=5082.6,5088.6
Exp/Cntr=0.3,0.1

Type RM Length L Ch R = 1,3263,372,372,372
BEGIN DESCRIPTION:
Mapping XS 0b33f69a
END DESCRIPTION:
XS GIS Cut Line= 3
      3668361.07     10547931.80      3668013.87     10547706.12
      3667584.43     10547593.34
#Sta/Elev= 30
  4449.3  315.27  4486.8  315.10  4558.8  312.22  4770.2  299.80  4785.0  298.84
  4791.3  297.40  4835.7  294.74  4865.9  291.75  4919.5  285.98  4991.9  280.69
  4999.2  278.47  5002.0  277.97  5005.2  278.47  5012.6  281.12  5074.6  281.72
  5084.9  284.06  5102.9  285.63  5136.6  289.16  5142.2  291.75  5147.4  290.73
  5177.4  295.89  5182.6  294.94  5188.3  297.29  5229.7  302.35  5240.0  304.92
  5250.4  305.62  5258.1  308.48  5263.3  308.19  5271.0  310.33  5307.4  315.98
#Mann=6,-1,0
  4449.3    0.05       0  4835.7    0.16       0  4865.9    0.12       0
  4999.2    0.07       0  5005.2    0.12       0  5102.9    0.16       0
Bank Sta=4999.2,5005.2
Exp/Cntr=0.3,0.1

Type RM Length L Ch R = 1,2891,418,418,418
BEGIN DESCRIPTION:
UNT 137 IN BUCR 5.0
END DESCRIPTION:
XS GIS Cut Line= 3
      3668581.91     10547586.17      3667859.69     10547343.12
      3667549.65     10547510.17
#Sta/Elev= 30
  4287.6  312.85  4419.0  306.91  4532.7  298.38  4598.0  291.77  4726.9  283.53
  4775.4  281.34  4785.9  279.83  4920.1  277.38  4922.8  276.88  4926.1  277.38
  4986.4  278.53  5007.0  277.47  5038.5  281.02  5047.0  283.34  5054.7  282.32
  5068.5  284.33  5076.6  283.79  5092.8  286.09  5098.5  284.65  5129.2  288.55
  5142.3  288.84  5158.5  291.21  5164.2  290.79  5240.4  299.98  5262.3  301.92
  5268.0  301.32  5284.2  304.49  5289.9  303.89  5366.2  314.99  5401.8  315.93
#Mann=6,-1,0
  4287.6    0.05       0  4598.0    0.16       0  4726.9    0.12       0
  4920.1    0.07       0  4926.1    0.12       0  5068.5    0.16       0
Bank Sta=4920.1,4926.1
Exp/Cntr=0.3,0.1

Type RM Length L Ch R = 1,2473,450,450,450
BEGIN DESCRIPTION:
UNT 137 IN BUCR 4.0
END DESCRIPTION:
XS GIS Cut Line= 3
      3668399.59     10547060.19      3667915.24     10546975.06
      3667699.59     10547160.21
#Sta/Elev= 30
  4620.8  310.91  4641.1  308.51  4647.9  306.81  4653.0  307.92  4661.4  306.16
  4691.9  302.86  4707.3  300.27  4712.3  301.16  4742.6  296.56  4770.3  293.83
  4813.7  288.45  4826.0  288.21  4864.5  284.04  4874.6  282.16  4905.1  280.59
  4915.2  278.18  4995.9  274.87  4998.7  274.37  5001.9  274.87  5006.6  275.99
  5058.3  281.66  5114.0  285.78  5127.4  287.14  5155.9  288.09  5233.8  296.26
  5248.1  296.88  5254.7  298.06  5268.9  298.36  5332.6  303.87  5396.8  306.56
#Mann=5,-1,0
  4620.8    0.16       0  4770.3    0.12       0  4995.9    0.07       0
  5001.9    0.12       0  5114.0    0.16       0
Bank Sta=4995.9,5001.9
Exp/Cntr=0.3,0.1

Type RM Length L Ch R = 1,2023,458,458,458
BEGIN DESCRIPTION:
UNT 137 IN BUCR 3.0
END DESCRIPTION:
XS GIS Cut Line= 3
      3668599.56     10546510.20      3667999.61     10546610.19
      3667699.60     10546910.19
#Sta/Elev= 30
  4360.6  311.98  4388.4  309.60  4393.5  309.99  4454.3  304.90  4509.6  298.09
  4522.8  296.47  4570.9  293.85  4576.0  292.82  4631.7  291.69  4664.7  288.40
  4685.0  287.72  4697.6  286.26  4745.8  284.59  4776.2  281.88  4840.6  278.72
  4928.3  274.65  4972.4  275.04  4980.0  274.35  4982.7  273.85  4986.0  274.35
  5025.4  275.52  5062.7  279.74  5110.2  285.87  5138.5  287.89  5166.8  291.75
  5251.7  298.79  5308.2  304.30  5336.5  305.68  5364.8  305.88  5393.1  304.55
#Mann=6,-1,0
  4360.6    0.16       0  4509.6    0.05       0  4840.6    0.12       0
  4980.0    0.07       0  4986.0    0.12       0  5062.7    0.16       0
Bank Sta=4980,4986
Exp/Cntr=0.3,0.1

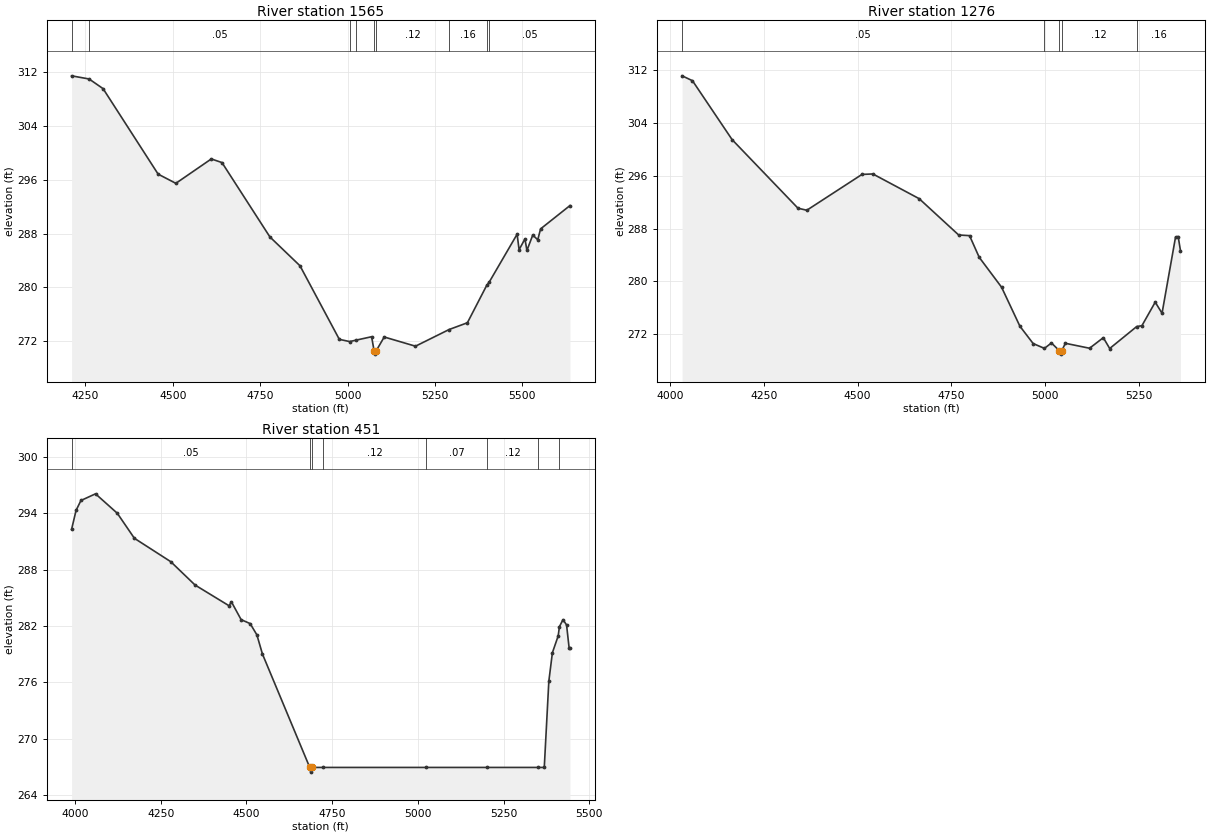
Type RM Length L Ch R = 1,1565,289,289,289
BEGIN DESCRIPTION:
UNT 137 IN BUCR 2.0
END DESCRIPTION:
XS GIS Cut Line= 4
      3668673.60     10546330.26      3668009.53     10546217.41
      3667796.86     10546265.15      3667558.16     10546742.54
#Sta/Elev= 30
  4210.8  311.50  4260.9  311.03  4300.9  309.59  4458.3  296.87  4509.0  295.50
  4610.4  299.13  4640.9  298.59  4778.0  287.52  4864.0  283.23  4976.5  272.28
  5005.9  271.95  5024.5  272.16  5068.8  272.67  5076.0  270.58  5078.8  270.08
  5082.0  270.58  5104.9  272.63  5194.3  271.26  5290.4  273.74  5342.8  274.75
  5397.9  280.30  5405.2  280.80  5485.0  287.93  5490.6  285.62  5507.4  287.23
  5513.0  285.51  5529.7  287.80  5544.0  287.10  5552.1  288.72  5636.1  292.19
#Mann=9,-1,0
  4210.8    0.16       0  4260.9    0.05       0  5005.9     0.1       0
  5024.5    0.12       0  5076.0    0.03       0  5082.0    0.12       0
  5290.4    0.16       0  5397.9    0.12       0  5405.2    0.05       0
Bank Sta=5076,5082
Exp/Cntr=0.3,0.1

Type RM Length L Ch R = 1,1276,825,825,825
BEGIN DESCRIPTION:
Mapping XS db43152e
END DESCRIPTION:
XS GIS Cut Line= 3
      3668672.19     10546225.07      3667956.91     10545919.51
      3667443.82     10546120.59
#Sta/Elev= 30
  4032.2  311.10  4059.8  310.36  4165.5  301.45  4341.1  291.08  4364.7  290.77
  4511.8  296.19  4540.8  296.26  4664.3  292.52  4769.6  287.03  4798.6  286.93
  4824.4  283.65  4884.0  279.13  4932.9  273.23  4968.2  270.61  4998.3  269.88
  5017.0  270.70  5038.4  269.51  5041.2  269.01  5044.4  269.51  5054.1  270.65
  5118.6  269.90  5155.3  271.50  5172.3  269.86  5244.3  273.18  5258.2  273.31
  5293.7  276.87  5311.9  275.19  5347.9  286.72  5354.9  286.79  5361.1  284.64
#Mann=5,-1,0
  4032.2    0.05       0  4998.3    0.12       0  5038.4    0.07       0
  5044.4    0.12       0  5244.3    0.16       0
Bank Sta=5038.4,5044.4
Exp/Cntr=0.3,0.1

Type RM Length L Ch R = 1,451,0,0,0
BEGIN DESCRIPTION:
UNT 137 IN BUCR 1.0
END DESCRIPTION:
XS GIS Cut Line= 4
      3668297.15     10545801.42      3667915.24     10545447.29
      3667373.58     10545384.79      3667276.35     10545759.79
#Sta/Elev= 30
  3990.2  292.30  4003.3  294.33  4017.5  295.38  4060.0  296.09  4123.5  294.02
  4173.4  291.35  4279.4  288.86  4350.3  286.37  4449.5  284.16  4456.3  284.58
  4484.7  282.68  4511.0  282.26  4530.6  281.06  4546.9  279.01  4684.8  266.93
  4687.6  266.43  4690.8  266.93  4723.0  266.93  5025.3  266.93  5200.3  266.93
  5351.5  266.93  5368.8  266.93  5382.1  276.12  5392.5  279.16  5409.4  280.95
  5412.9  281.93  5423.4  282.68  5433.8  282.12  5441.3  279.65  5443.7  279.65
#Mann=8,-1,0
  3990.2    0.05       0  4684.8    0.07       0  4690.8    0.05       0
  4723.0    0.12       0  5025.3    0.07       0  5200.3    0.12       0
  5351.5    0.07       0  5412.9    0.05       0
Bank Sta=4684.8,4690.8
Exp/Cntr=0.3,0.1

Chan Stop Cuts=-1