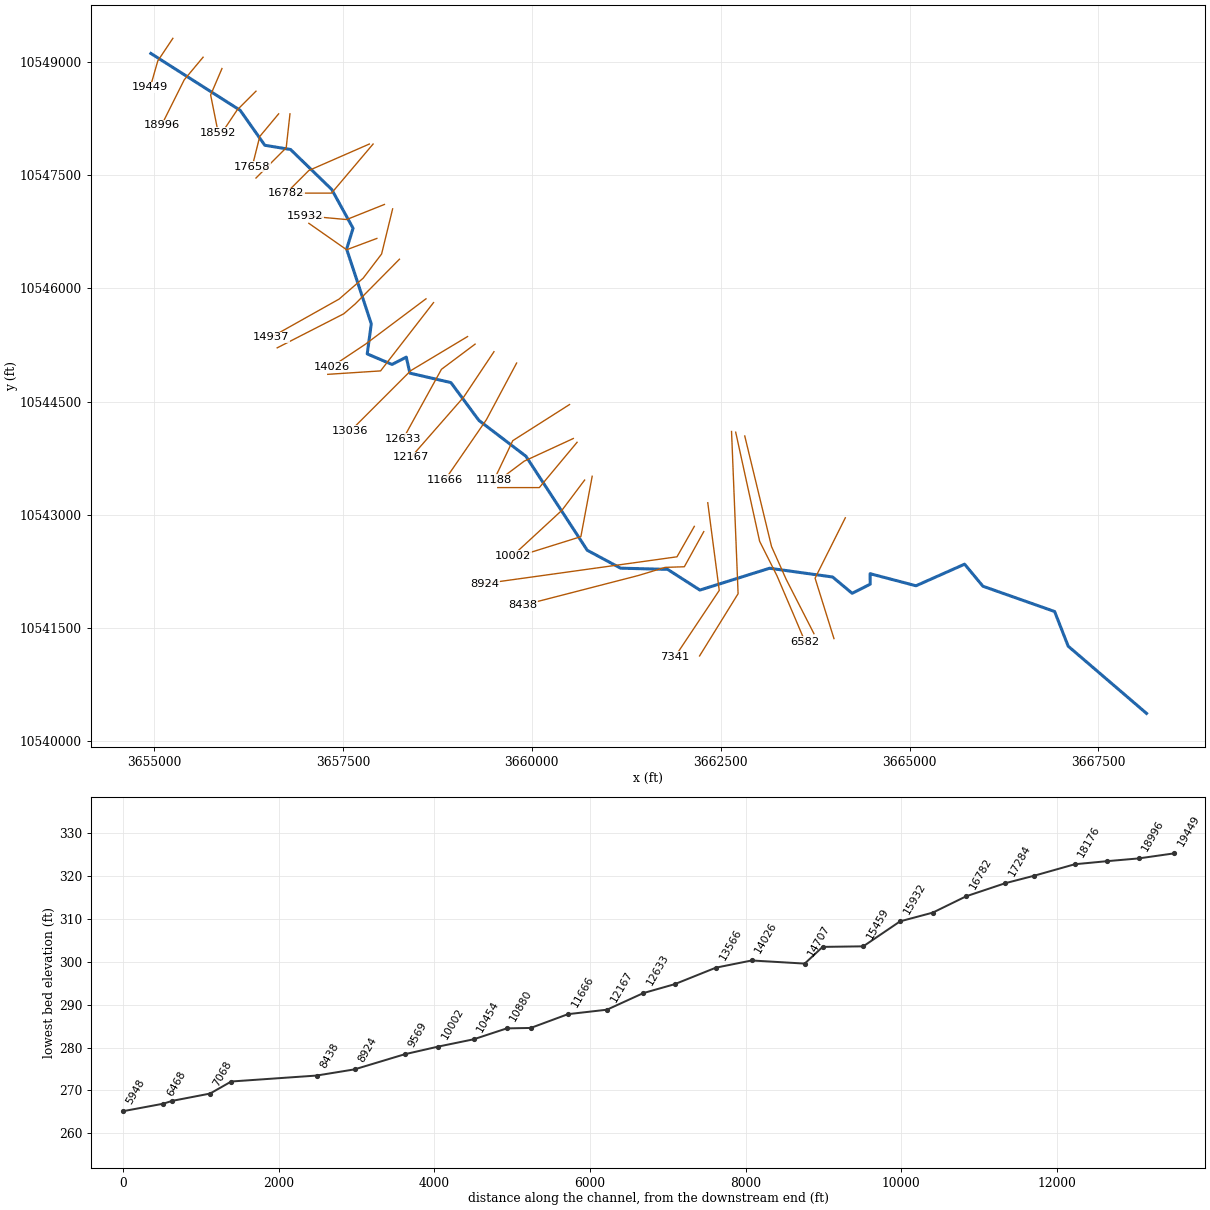
--- UNT 146 IN BUCR.prj (project) ---

Proj Title=UNT 146 IN BUCR Base Level Engineering
Current Plan=p01
Default Exp/Contr=0.3,0.1
English Units
Geom File=g01
Flow File=f01
Plan File=p01
BEGIN DESCRIPTION:
UNT 146 IN BUCR
END DESCRIPTION:

--- UNT 146 IN BUCR.p01 (plan) ---

Plan Title=Multiple Run
Short Identifier=Multiple
Geom File=g01
Flow File=f01
Subcritical Flow
K Sum by GR= 0
Std Step Tol= 0.01
Critical Tol= 0.01
Num of Std Step Trials= 20
Max Error Tol= 0.3
Flow Tol Ratio= 0.001
Split Flow NTrial= 30
Split Flow Tol= 0.02
Split Flow Ratio= 0.02
Log Output Level= 0
Friction Slope Method= 1
Unsteady Friction Slope Method= 2
Unsteady Bridges Friction Slope Method= 1
Parabolic Critical Depth
Global Vel Dist=  1 , 1 , 1
Global Log Level= 0
CheckData=True
Encroach Param= -1, 0, 0, 0
BEGIN DESCRIPTION:
Multiple Run
END DESCRIPTION:

--- UNT 146 IN BUCR.f01 (steady flow) ---

Flow Title=Multiple
Number of Profiles=7
Profile Names=10-year,25-year,50-year,1pct_min,100-year,1pct_plu,500-year
River Rch & RM= UNT 146 IN BUCR,Reach-1,19449
     837    1169    1451    1322    1788    2418    2729
River Rch & RM= UNT 146 IN BUCR,Reach-1,14707
    1177    1673    2101    1936    2618    3540    4084
River Rch & RM= UNT 146 IN BUCR,Reach-1,12167
    1240    1762    2212    2035    2753    3723    4288
River Rch & RM= UNT 146 IN BUCR,Reach-1,8924
    1467    2089    2626    2418    3270    4422    5098
Boundary for River Rch & Prof#=UNT 146 IN BUCR,Reach-1,1
Up Type=0
Dn Type=3
Dn Slope=0.005
Boundary for River Rch & Prof#=UNT 146 IN BUCR,Reach-1,2
Up Type=0
Dn Type=3
Dn Slope=0.005
Boundary for River Rch & Prof#=UNT 146 IN BUCR,Reach-1,3
Up Type=0
Dn Type=3
Dn Slope=0.005
Boundary for River Rch & Prof#=UNT 146 IN BUCR,Reach-1,4
Up Type=0
Dn Type=3
Dn Slope=0.005
Boundary for River Rch & Prof#=UNT 146 IN BUCR,Reach-1,5
Up Type=0
Dn Type=3
Dn Slope=0.005
Boundary for River Rch & Prof#=UNT 146 IN BUCR,Reach-1,6
Up Type=0
Dn Type=3
Dn Slope=0.005
Boundary for River Rch & Prof#=UNT 146 IN BUCR,Reach-1,7
Up Type=0
Dn Type=3
Dn Slope=0.005

--- UNT 146 IN BUCR.g01 (geometry) ---

Geom Title=Existing Conditions

River Reach=UNT 146 IN BUCR,Reach-1
Reach XY= 30
      3654958.75     10549110.00      3656140.50     10548357.00
      3656466.50     10547894.00      3656807.50     10547838.00
      3657352.00     10547309.00      3657634.50     10546795.00
      3657549.50     10546519.00      3657875.75     10545529.00
      3657822.00     10545131.00      3658150.25     10544991.00
      3658338.75     10545088.00      3658387.00     10544876.00
      3658929.75     10544751.00      3659299.25     10544251.00
      3659923.00     10543775.00      3660734.50     10542530.00
      3661176.00     10542293.00      3661798.25     10542277.00
      3662225.25     10542003.00      3663147.25     10542292.00
      3663982.25     10542176.00      3664240.25     10541960.00
      3664479.25     10542081.00      3664477.75     10542220.00
      3665085.50     10542060.00      3665728.50     10542346.00
      3665971.00     10542054.00      3666920.00     10541719.00
      3667099.50     10541260.00      3668136.25     10540370.00

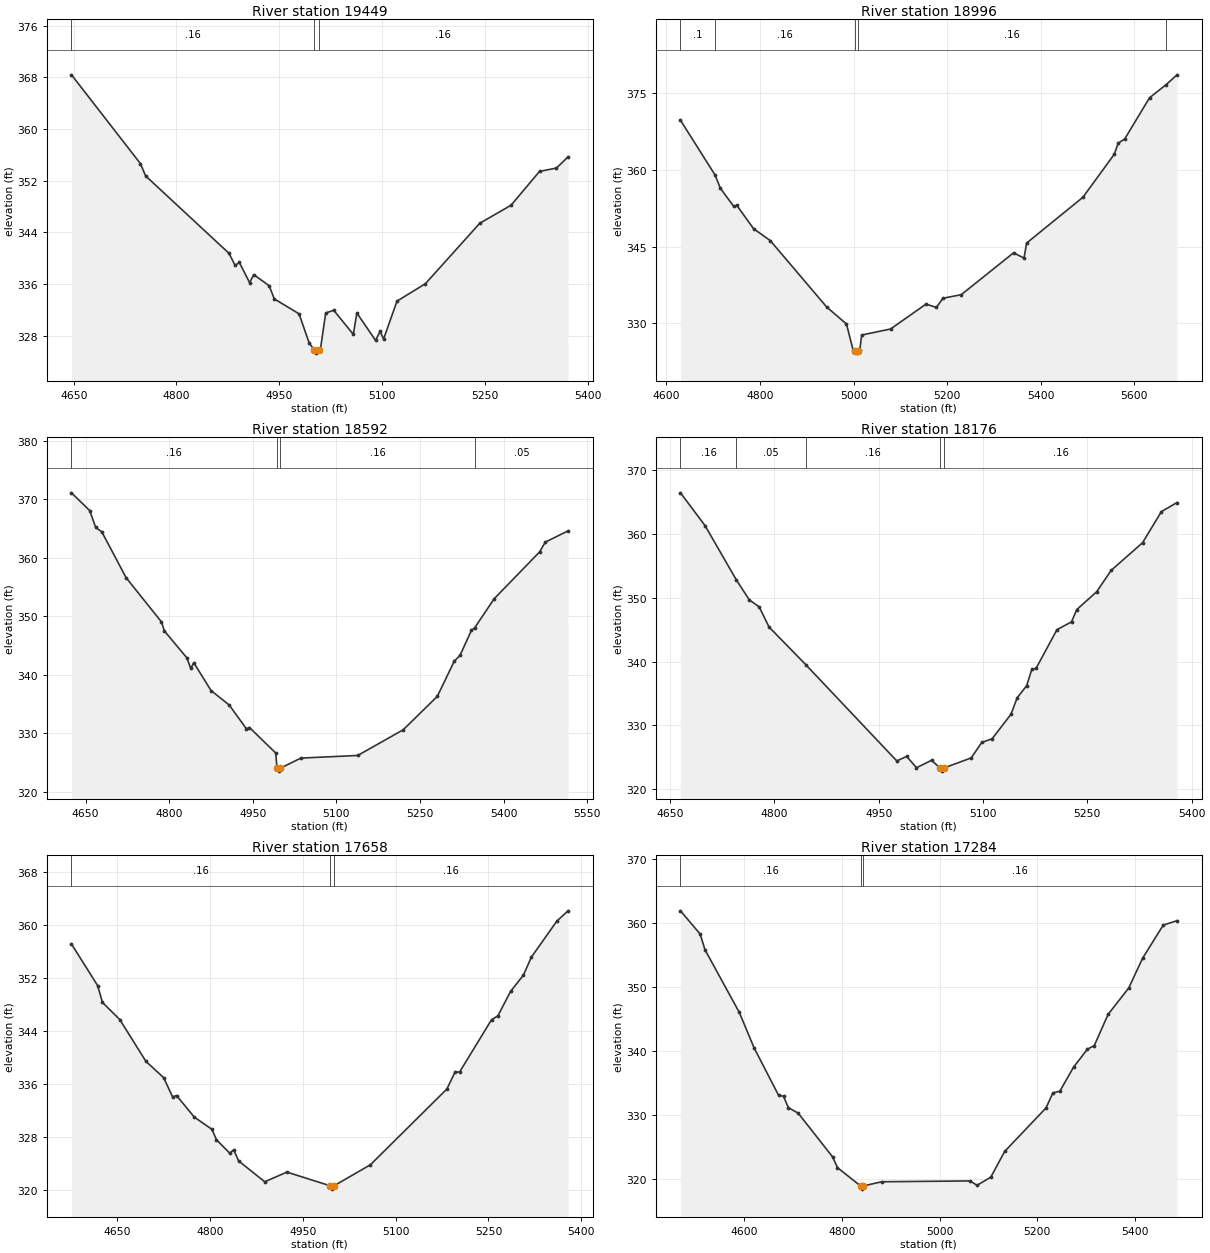
Type RM Length L Ch R = 1,19449,453,453,453
BEGIN DESCRIPTION:
UNT 146 IN BUCR 42.0
END DESCRIPTION:
XS GIS Cut Line= 3
      3655249.60     10549310.17      3655049.61     10549010.19
      3654949.62     10548660.22
#Sta/Elev= 30
  4646.8  368.39  4747.4  354.65  4754.9  352.76  4876.6  340.78  4885.6  338.90
  4891.7  339.37  4906.7  336.24  4912.7  337.48  4935.2  335.77  4942.7  333.73
  4978.8  331.42  4993.8  326.85  5001.3  325.84  5004.1  325.34  5007.3  325.84
  5009.9  325.84  5017.7  331.55  5029.4  331.97  5058.0  328.25  5063.2  331.54
  5090.5  327.30  5097.0  328.71  5102.2  327.52  5121.7  333.38  5163.3  336.09
  5242.6  345.44  5288.1  348.21  5329.7  353.45  5354.4  353.97  5371.3  355.70
#Mann=3,-1,0
  4646.8    0.16       0  5001.3    0.07       0  5007.3    0.16       0
Bank Sta=5001.3,5007.3
Exp/Cntr=0.3,0.1

Type RM Length L Ch R = 1,18996,404,404,404
BEGIN DESCRIPTION:
UNT 146 IN BUCR 41.0
END DESCRIPTION:
XS GIS Cut Line= 3
      3655649.63     10549060.22      3655399.61     10548760.19
      3655099.60     10548160.16
#Sta/Elev= 30
  4629.9  369.70  4704.1  358.95  4715.2  356.39  4743.8  352.85  4750.3  353.06
  4786.1  348.50  4821.9  346.16  4942.3  333.20  4984.7  329.86  4999.0  324.74
  5003.8  324.67  5006.5  324.17  5009.8  324.67  5013.3  324.86  5017.2  327.71
  5079.1  328.89  5154.6  333.75  5177.0  333.11  5191.0  334.90  5230.1  335.60
  5341.9  343.78  5364.2  342.75  5369.8  345.69  5490.0  354.63  5557.1  363.04
  5565.5  365.21  5579.5  366.05  5632.6  374.10  5668.1  376.67  5691.3  378.58
#Mann=5,-1,0
  4629.9     0.1       0  4704.1    0.16       0  5003.8    0.07       0
  5009.8    0.16       0  5668.1    0.05       0
Bank Sta=5003.8,5009.8
Exp/Cntr=0.3,0.1

Type RM Length L Ch R = 1,18592,416,416,416
BEGIN DESCRIPTION:
UNT 146 IN BUCR 40.0
END DESCRIPTION:
XS GIS Cut Line= 3
      3655899.62     10548910.21      3655749.61     10548560.19
      3655849.61     10548060.20
#Sta/Elev= 30
  4624.8  371.14  4657.5  368.10  4668.3  365.21  4679.2  364.46  4722.7  356.63
  4786.2  349.06  4791.6  347.49  4831.5  342.94  4838.8  341.10  4844.2  342.07
  4875.1  337.32  4907.7  334.84  4938.5  330.78  4944.0  330.99  4991.1  326.64
  4993.5  324.03  4996.3  323.53  4999.5  324.03  5036.2  325.76  5138.2  326.21
  5219.8  330.60  5281.0  336.32  5311.6  342.37  5321.7  343.32  5342.1  347.59
  5348.2  348.07  5382.9  353.01  5464.5  361.03  5474.7  362.71  5515.5  364.63
#Mann=4,-1,0
  4624.8    0.16       0  4993.5    0.07       0  4999.5    0.16       0
  5348.2    0.05       0
Bank Sta=4993.5,4999.5
Exp/Cntr=0.3,0.1

Type RM Length L Ch R = 1,18176,518,518,518
BEGIN DESCRIPTION:
UNT 146 IN BUCR 39.0
END DESCRIPTION:
XS GIS Cut Line= 3
      3656349.62     10548610.20      3656099.61     10548360.19
      3655899.62     10548060.21
#Sta/Elev= 30
  4664.9  366.47  4700.3  361.31  4745.4  352.78  4763.9  349.67  4778.1  348.58
  4792.2  345.43  4844.9  339.53  4976.0  324.41  4990.2  325.12  5004.3  323.34
  5026.0  324.51  5038.0  323.31  5040.8  322.81  5044.0  323.31  5083.1  324.89
  5098.1  327.31  5113.1  327.89  5140.2  331.73  5149.2  334.34  5162.7  336.20
  5170.2  338.79  5176.2  338.92  5206.3  345.00  5227.3  346.23  5234.8  348.15
  5263.3  350.94  5284.4  354.32  5329.4  358.64  5356.5  363.52  5379.0  364.95
#Mann=5,-1,0
  4664.9    0.16       0  4745.4    0.05       0  4844.9    0.16       0
  5038.0    0.07       0  5044.0    0.16       0
Bank Sta=5038,5044
Exp/Cntr=0.3,0.1

Type RM Length L Ch R = 1,17658,374,374,374
BEGIN DESCRIPTION:
UNT 146 IN BUCR 38.0
END DESCRIPTION:
XS GIS Cut Line= 3
      3656649.60     10548310.18      3656399.61     10548010.19
      3656299.61     10547610.20
#Sta/Elev= 30
  4576.0  357.15  4618.3  350.87  4626.1  348.33  4654.1  345.74  4696.4  339.43
  4725.0  336.98  4739.4  334.08  4745.9  334.27  4774.5  331.03  4803.1  329.17
  4810.3  327.62  4831.8  325.58  4838.3  326.08  4846.1  324.42  4888.4  321.26
  4924.2  322.72  4994.4  320.65  4997.2  320.15  5000.4  320.65  5059.3  323.83
  5183.0  335.27  5195.9  337.79  5203.6  337.85  5255.1  345.72  5265.4  346.31
  5286.0  350.01  5306.7  352.46  5319.5  355.17  5360.8  360.62  5378.8  362.16
#Mann=3,-1,0
  4576.0    0.16       0  4994.4    0.07       0  5000.4    0.16       0
Bank Sta=4994.4,5000.4
Exp/Cntr=0.3,0.1

Type RM Length L Ch R = 1,17284,502,502,502
BEGIN DESCRIPTION:
UNT 146 IN BUCR 37.0
END DESCRIPTION:
XS GIS Cut Line= 3
      3656799.61     10548310.20      3656749.61     10547860.19
      3656349.58     10547460.16
#Sta/Elev= 30
  4468.7  361.84  4509.0  358.22  4519.0  355.76  4589.4  345.97  4619.6  340.46
  4669.9  333.04  4680.0  332.88  4690.1  331.11  4710.2  330.25  4780.6  323.43
  4790.7  321.75  4838.0  318.89  4840.7  318.39  4844.0  318.89  4881.2  319.54
  5062.9  319.67  5077.0  318.98  5105.3  320.27  5133.6  324.27  5218.5  331.07
  5232.6  333.43  5246.7  333.66  5275.0  337.44  5303.3  340.23  5317.5  340.81
  5345.7  345.66  5388.2  349.80  5416.5  354.43  5458.9  359.61  5487.2  360.30
#Mann=3,-1,0
  4468.7    0.16       0  4838.0    0.07       0  4844.0    0.16       0
Bank Sta=4838,4844
Exp/Cntr=0.3,0.1

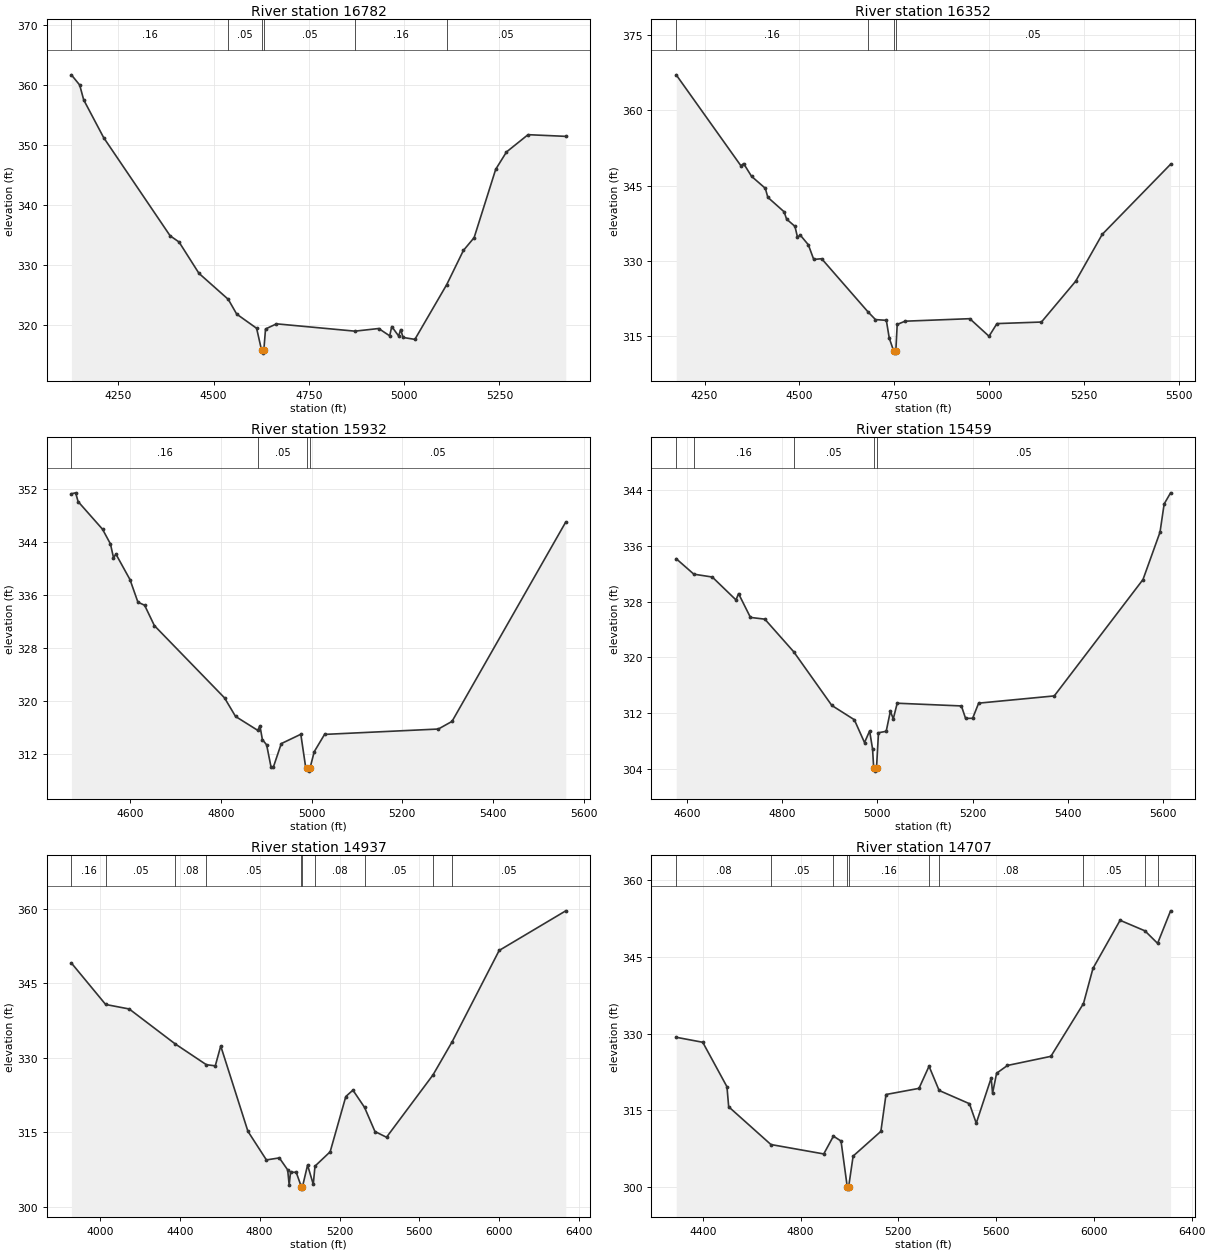
Type RM Length L Ch R = 1,16782,430,430,430
BEGIN DESCRIPTION:
UNT 146 IN BUCR 36.0
END DESCRIPTION:
XS GIS Cut Line= 3
      3657849.59     10547910.18      3657049.61     10547560.19
      3656749.58     10547260.16
#Sta/Elev= 30
  4126.6  361.70  4148.4  360.00  4158.9  357.53  4211.2  351.25  4385.8  334.88
  4409.2  333.85  4461.4  328.63  4538.3  324.30  4560.5  321.84  4612.7  319.48
  4625.7  315.84  4628.4  315.34  4631.7  315.84  4636.1  319.36  4664.9  320.22
  4870.8  319.00  4933.1  319.44  4962.0  318.22  4967.4  319.77  4985.4  318.20
  4990.8  319.26  4997.1  317.95  5028.1  317.63  5111.8  326.77  5155.4  332.44
  5183.6  334.58  5240.2  345.96  5268.5  348.85  5325.1  351.73  5424.1  351.45
#Mann=6,-1,0
  4126.6    0.16       0  4538.3    0.05       0  4625.7    0.07       0
  4631.7    0.05       0  4870.8    0.16       0  5111.8    0.05       0
Bank Sta=4625.7,4631.7
Exp/Cntr=0.3,0.1

Type RM Length L Ch R = 1,16352,420,420,420
BEGIN DESCRIPTION:
UNT 146 IN BUCR 35.0
END DESCRIPTION:
XS GIS Cut Line= 3
      3657899.64     10547910.22      3657349.61     10547260.19
      3656899.62     10547260.19
#Sta/Elev= 30
  4175.5  367.11  4345.8  348.95  4353.0  349.38  4373.8  346.84  4410.1  344.44
  4416.7  342.64  4459.6  339.75  4466.1  338.29  4488.1  336.84  4494.7  334.72
  4502.4  335.07  4523.3  333.17  4537.6  330.23  4558.4  330.38  4680.3  319.77
  4700.1  318.22  4728.7  318.07  4736.4  314.51  4747.7  312.02  4750.5  311.52
  4753.7  312.02  4757.3  317.25  4778.1  317.90  4948.4  318.40  4999.0  314.89
  5019.9  317.42  5137.0  317.73  5227.0  325.87  5297.0  335.24  5477.0  349.25
#Mann=4,-1,0
  4175.5    0.16       0  4680.3    0.05       0  4747.7    0.03       0
  4753.7    0.05       0
Bank Sta=4747.7,4753.7
Exp/Cntr=0.3,0.1

Type RM Length L Ch R = 1,15932,473,473,473
BEGIN DESCRIPTION:
UNT 146 IN BUCR 34.0
END DESCRIPTION:
XS GIS Cut Line= 3
      3658049.63     10547110.20      3657549.61     10546910.19
      3656999.61     10546960.19
#Sta/Elev= 30
  4470.0  351.32  4479.4  351.46  4484.8  350.14  4538.7  345.97  4556.2  343.75
  4562.9  341.68  4568.3  342.21  4599.3  338.37  4616.8  334.97  4631.6  334.50
  4653.1  331.43  4807.9  320.53  4832.2  317.73  4881.2  315.63  4886.0  316.32
  4891.4  314.24  4900.8  313.44  4910.3  310.17  4915.6  310.08  4933.1  313.63
  4976.2  315.04  4987.0  310.03  4990.7  309.98  4993.5  309.48  4996.7  309.98
  5005.8  312.41  5028.6  315.02  5279.6  315.83  5309.8  316.98  5560.8  347.06
#Mann=4,-1,0
  4470.0    0.16       0  4881.2    0.05       0  4990.7    0.03       0
  4996.7    0.05       0
Bank Sta=4990.7,4996.7
Exp/Cntr=0.3,0.1

Type RM Length L Ch R = 1,15459,522,522,522
BEGIN DESCRIPTION:
UNT 146 IN BUCR 33.0
END DESCRIPTION:
XS GIS Cut Line= 3
      3657949.62     10546660.19      3657549.61     10546510.19
      3657049.64     10546860.16
#Sta/Elev= 30
  4577.7  334.15  4614.7  331.93  4653.4  331.52  4703.2  328.23  4708.5  329.14
  4733.5  325.72  4763.7  325.47  4824.3  320.79  4904.3  313.08  4951.5  311.03
  4972.9  307.75  4983.6  309.42  4989.8  306.82  4992.1  304.15  4994.9  303.65
  4998.1  304.15  5002.2  309.16  5018.4  309.37  5027.1  312.24  5033.3  311.17
  5041.5  313.40  5176.2  313.01  5185.0  311.22  5199.8  311.24  5212.4  313.41
  5371.1  314.45  5557.3  331.16  5593.0  337.96  5601.7  342.01  5615.2  343.61
#Mann=5,-1,0
  4577.7    0.05       0  4614.7    0.16       0  4824.3    0.05       0
  4992.1    0.03       0  4998.1    0.05       0
Bank Sta=4992.1,4998.1
Exp/Cntr=0.3,0.1

Type RM Length L Ch R = 1,14937,230,230,230
BEGIN DESCRIPTION:
UNT 146 IN BUCR 32.0
END DESCRIPTION:
XS GIS Cut Line= 5
      3658158.31     10547051.50      3658012.46     10546454.23
      3657769.41     10546134.79      3657449.96     10545857.01
      3656547.20     10545350.07
#Sta/Elev= 30
  3857.7  349.06  4029.2  340.71  4147.3  339.80  4376.6  332.79  4533.3  328.58
  4578.1  328.35  4605.3  332.35  4741.5  315.16  4834.0  309.40  4898.7  309.81
  4940.4  307.40  4948.0  304.35  4954.6  306.90  4983.1  306.92  5008.6  304.02
  5011.4  303.52  5014.6  304.02  5040.1  308.36  5068.6  304.48  5077.2  308.15
  5153.1  311.04  5231.5  322.17  5267.1  323.46  5325.3  319.98  5377.4  315.12
  5435.3  313.97  5668.2  326.54  5763.9  333.21  5999.2  351.59  6332.6  359.57
#Mann=10,-1,0
  3857.7    0.16       0  4029.2    0.05       0  4376.6    0.08       0
  4533.3    0.05       0  5008.6    0.03       0  5014.6    0.05       0
  5077.2    0.08       0  5325.3    0.05       0  5668.2    0.08       0
  5763.9    0.05       0
Bank Sta=5008.6,5014.6
Exp/Cntr=0.3,0.1

Type RM Length L Ch R = 1,14707,681,681,681
BEGIN DESCRIPTION:
UNT 146 IN BUCR 31.0
END DESCRIPTION:
XS GIS Cut Line= 4
      3658248.58     10546384.79      3657665.24     10545794.51
      3657512.46     10545662.56      3656630.53     10545211.18
#Sta/Elev= 30
  4291.3  329.31  4399.9  328.33  4498.9  319.64  4506.0  315.72  4678.7  308.34
  4894.9  306.50  4934.5  309.98  4965.6  309.02  4990.9  300.12  4993.6  299.62
  4996.9  300.12  5015.1  306.08  5128.6  310.91  5149.6  318.12  5284.5  319.32
  5325.6  323.65  5366.9  318.91  5491.0  316.32  5518.8  312.51  5579.9  321.35
  5585.5  318.37  5602.1  322.28  5646.5  323.80  5824.1  325.58  5957.5  335.91
  5996.2  342.77  6107.2  352.18  6208.8  350.12  6260.7  347.67  6313.8  354.03
#Mann=10,-1,0
  4291.3    0.08       0  4678.7    0.05       0  4934.5    0.16       0
  4990.9    0.07       0  4996.9    0.16       0  5325.6     0.1       0
  5366.9    0.08       0  5957.5    0.05       0  6208.8    0.08       0
  6260.7    0.05       0
Bank Sta=4990.9,4996.9
Exp/Cntr=0.3,0.1

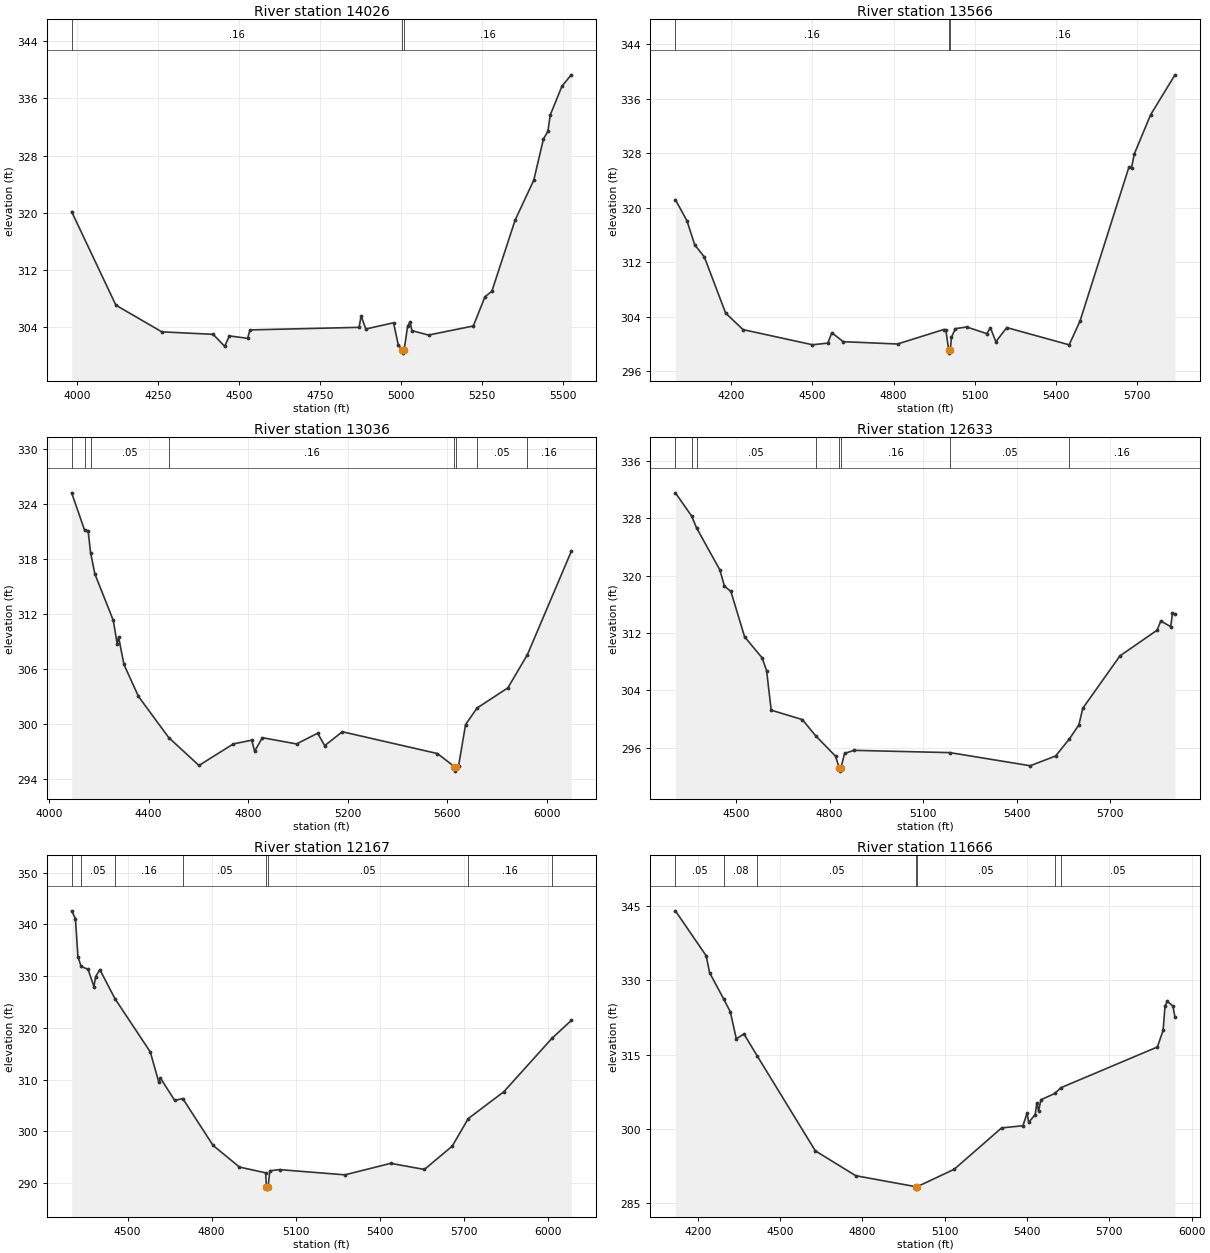
Type RM Length L Ch R = 1,14026,460,460,460
BEGIN DESCRIPTION:
UNT 146 IN BUCR 30.0
END DESCRIPTION:
XS GIS Cut Line= 3
      3658599.65     10545860.22      3657799.61     10545260.19
      3657349.59     10544960.18
#Sta/Elev= 30
  3984.0  320.15  4120.5  307.06  4262.2  303.33  4420.5  302.98  4455.9  301.30
  4470.5  302.76  4526.8  302.42  4534.0  303.60  4870.5  303.96  4876.8  305.56
  4891.3  303.73  4976.8  304.60  4991.6  301.47  5003.6  300.85  5006.3  300.35
  5009.6  300.85  5020.1  304.08  5027.6  304.72  5033.6  303.50  5084.7  302.88
  5222.9  304.15  5259.0  308.26  5280.0  309.01  5352.1  319.01  5409.2  324.55
  5439.2  330.34  5452.8  331.39  5460.3  333.71  5496.3  337.73  5524.9  339.31
#Mann=3,-1,0
  3984.0    0.16       0  5003.6    0.07       0  5009.6    0.16       0
Bank Sta=5003.6,5009.6
Exp/Cntr=0.3,0.1

Type RM Length L Ch R = 1,13566,530,530,530
BEGIN DESCRIPTION:
UNT 146 IN BUCR 29.0
END DESCRIPTION:
XS GIS Cut Line= 3
      3658699.58     10545810.15      3657998.58     10544905.62
      3657299.62     10544860.19
#Sta/Elev= 30
  3994.3  321.19  4036.8  318.11  4065.8  314.56  4101.1  312.79  4179.8  304.55
  4244.1  302.12  4500.3  299.90  4557.4  300.14  4571.8  301.67  4614.2  300.35
  4814.5  300.01  4984.7  302.13  4992.8  302.09  5003.4  299.17  5006.1  298.67
  5009.4  299.17  5013.6  300.99  5028.1  302.26  5069.7  302.51  5144.0  301.53
  5157.7  302.38  5177.7  300.34  5217.8  302.42  5448.3  299.89  5488.4  303.38
  5668.8  325.94  5678.8  325.91  5688.8  327.89  5748.9  333.64  5839.1  339.51
#Mann=3,-1,0
  3994.3    0.16       0  5003.4    0.07       0  5009.4    0.16       0
Bank Sta=5003.4,5009.4
Exp/Cntr=0.3,0.1

Type RM Length L Ch R = 1,13036,403,403,403
BEGIN DESCRIPTION:
UNT 146 IN BUCR 28.0
END DESCRIPTION:
XS GIS Cut Line= 3
      3659149.65     10545360.21      3658399.61     10544910.19
      3657599.58     10544110.16
#Sta/Elev= 30
  4091.1  325.20  4143.0  321.13  4157.2  321.07  4167.1  318.67  4184.4  316.34
  4258.3  311.27  4273.9  308.73  4279.7  309.44  4301.1  306.46  4359.4  302.97
  4481.1  298.47  4602.3  295.43  4740.3  297.78  4814.2  298.19  4825.8  296.99
  4856.9  298.46  4994.1  297.78  5078.9  298.95  5107.2  297.59  5177.9  299.11
  5559.8  296.73  5627.5  295.31  5630.2  294.81  5633.5  295.31  5644.6  295.36
  5672.9  299.90  5719.0  301.70  5842.6  303.90  5921.2  307.53  6097.2  318.80
#Mann=8,-1,0
  4091.1    0.05       0  4143.0    0.16       0  4167.1    0.05       0
  4481.1    0.16       0  5627.5    0.07       0  5633.5    0.16       0
  5719.0    0.05       0  5921.2    0.16       0
Bank Sta=5627.5,5633.5
Exp/Cntr=0.3,0.1

Type RM Length L Ch R = 1,12633,466,466,466
BEGIN DESCRIPTION:
UNT 146 IN BUCR 27.0
END DESCRIPTION:
XS GIS Cut Line= 3
      3659249.57     10545260.16      3658804.13     10544926.45
      3658299.59     10544010.16
#Sta/Elev= 30
  4305.5  331.54  4357.4  328.32  4374.0  326.60  4448.2  320.79  4462.8  318.53
  4483.6  317.78  4527.4  311.47  4583.6  308.53  4598.2  306.72  4612.8  301.23
  4712.8  299.92  4755.0  297.68  4819.1  294.82  4830.7  293.23  4833.4  292.73
  4836.7  293.23  4848.3  295.20  4878.4  295.63  5186.5  295.31  5443.7  293.48
  5525.1  294.84  5569.6  297.24  5599.8  299.18  5612.2  301.49  5731.5  308.80
  5850.8  312.39  5862.4  313.67  5894.3  312.88  5900.0  314.73  5908.1  314.68
#Mann=8,-1,0
  4305.5    0.12       0  4357.4    0.16       0  4374.0    0.05       0
  4755.0    0.16       0  4830.7    0.07       0  4836.7    0.16       0
  5186.5    0.05       0  5569.6    0.16       0
Bank Sta=4830.7,4836.7
Exp/Cntr=0.3,0.1

Type RM Length L Ch R = 1,12167,501,501,501
BEGIN DESCRIPTION:
UNT 146 IN BUCR 26.0
END DESCRIPTION:
XS GIS Cut Line= 3
      3659499.60     10545160.18      3659099.61     10544560.19
      3658399.62     10543760.20
#Sta/Elev= 30
  4300.4  342.62  4313.9  341.11  4322.9  333.78  4334.1  331.89  4359.0  331.32
  4380.0  327.99  4386.0  329.90  4401.0  331.27  4455.2  325.64  4581.3  315.36
  4611.4  309.56  4617.4  310.32  4668.5  305.99  4697.2  306.36  4805.2  297.32
  4899.8  293.12  4993.0  292.01  4996.0  289.36  4998.7  288.86  5002.0  289.36
  5008.0  292.40  5042.9  292.63  5276.3  291.62  5439.6  293.84  5560.1  292.66
  5659.3  297.16  5716.9  302.50  5843.9  307.68  6015.9  318.01  6084.5  321.44
#Mann=8,-1,0
  4300.4    0.08       0  4334.1    0.05       0  4455.2    0.16       0
  4697.2    0.05       0  4996.0    0.03       0  5002.0    0.05       0
  5716.9    0.16       0  6015.9    0.05       0
Bank Sta=4996,5002
Exp/Cntr=0.3,0.1

Type RM Length L Ch R = 1,11666,478,478,478
BEGIN DESCRIPTION:
UNT 146 IN BUCR 25.0
END DESCRIPTION:
XS GIS Cut Line= 3
      3659799.61     10545010.20      3659399.61     10544260.19
      3658849.63     10543460.22
#Sta/Elev= 30
  4118.5  344.01  4230.8  334.93  4243.2  331.50  4294.0  326.27  4318.6  323.64
  4340.6  318.16  4368.2  319.16  4417.2  314.67  4628.5  295.55  4775.8  290.53
  4993.9  288.32  4996.7  287.82  4999.9  288.32  5134.3  291.82  5307.5  300.18
  5385.2  300.62  5400.1  303.18  5406.2  301.30  5429.7  302.88  5436.0  305.29
  5442.1  303.59  5450.9  305.87  5501.5  307.14  5522.8  308.28  5875.1  316.52
  5896.0  319.87  5902.9  324.75  5910.9  325.75  5931.9  324.77  5939.3  322.50
#Mann=7,-1,0
  4118.5    0.05       0  4294.0    0.08       0  4417.2    0.05       0
  4993.9    0.03       0  4999.9    0.05       0  5501.5    0.16       0
  5522.8    0.05       0
Bank Sta=4993.9,4999.9
Exp/Cntr=0.3,0.1

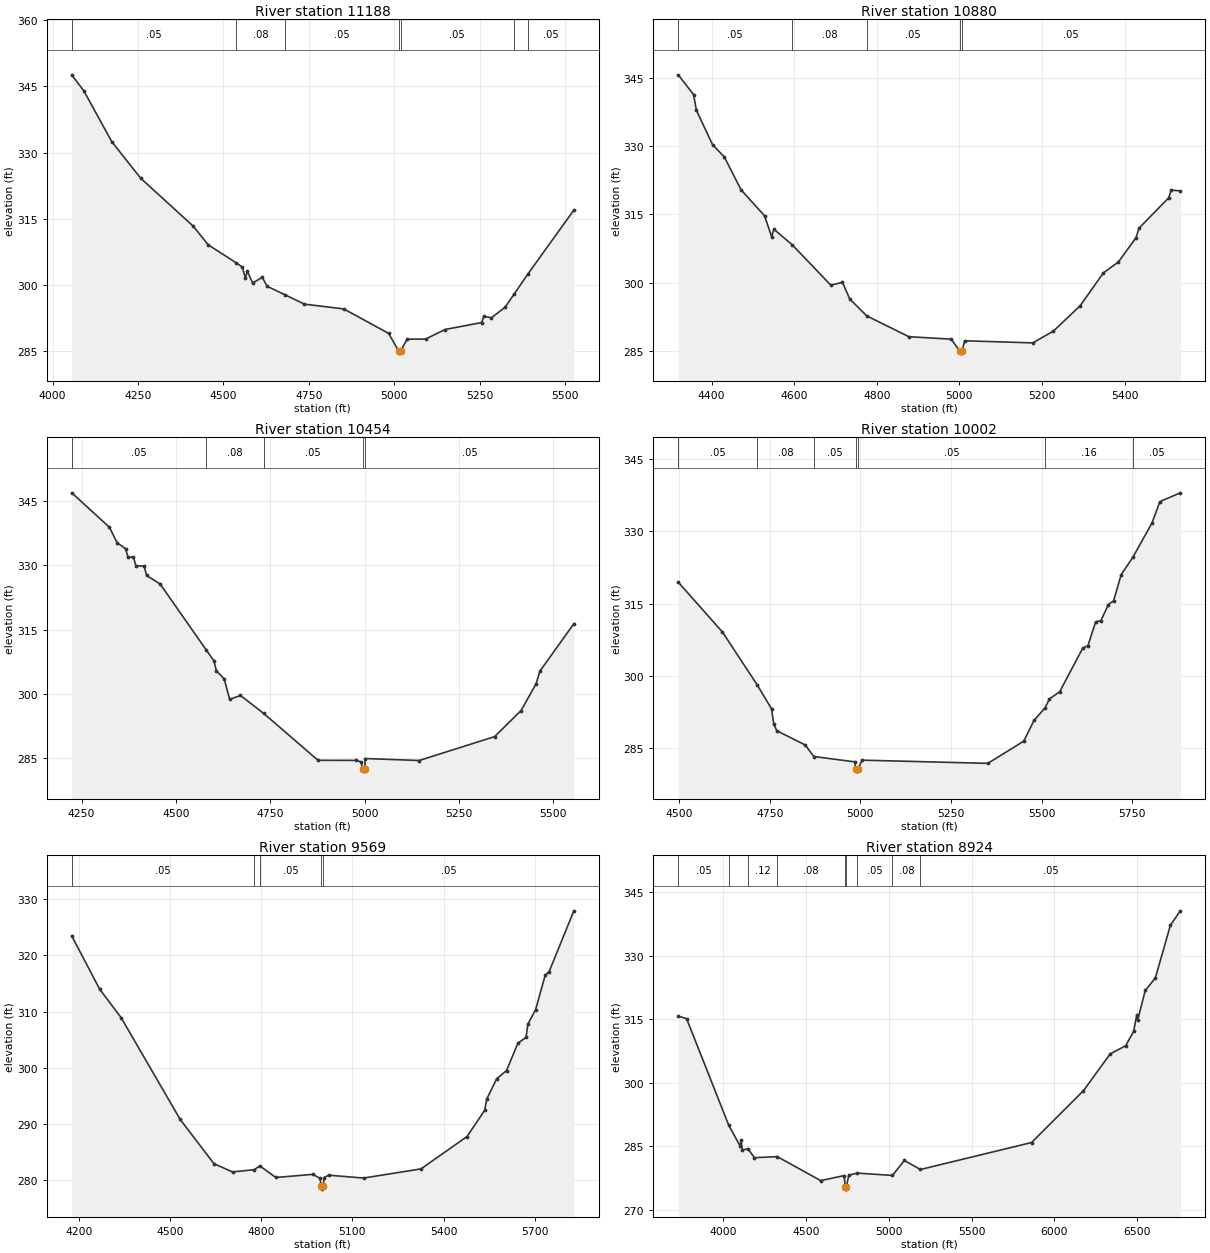
Type RM Length L Ch R = 1,11188,308,308,308
BEGIN DESCRIPTION:
UNT 146 IN BUCR 24.0
END DESCRIPTION:
XS GIS Cut Line= 3
      3660499.64     10544460.21      3659748.58     10543982.01
      3659499.59     10543460.14
#Sta/Elev= 30
  4056.2  347.62  4091.8  343.95  4173.1  332.50  4257.8  324.21  4411.9  313.32
  4455.0  309.14  4537.1  305.06  4554.9  304.08  4564.2  301.66  4570.1  303.10
  4585.3  300.47  4613.4  301.77  4627.7  299.74  4681.1  297.77  4736.9  295.69
  4852.0  294.61  4983.2  289.06  5012.1  285.10  5014.8  284.60  5018.1  285.10
  5037.2  287.77  5091.1  287.78  5148.0  289.95  5255.5  291.53  5261.0  292.92
  5283.7  292.61  5323.6  294.98  5349.7  297.92  5389.5  302.41  5524.8  317.00
#Mann=7,-1,0
  4056.2    0.05       0  4537.1    0.08       0  4681.1    0.05       0
  5012.1    0.03       0  5018.1    0.05       0  5349.7    0.16       0
  5389.5    0.05       0
Bank Sta=5012.1,5018.1
Exp/Cntr=0.3,0.1

Type RM Length L Ch R = 1,10880,426,426,426
BEGIN DESCRIPTION:
UNT 146 IN BUCR 23.0
END DESCRIPTION:
XS GIS Cut Line= 3
      3660549.59     10544010.18      3659899.61     10543710.19
      3659499.58     10543410.17
#Sta/Elev= 30
  4319.1  345.62  4356.3  341.28  4363.1  337.83  4402.1  330.30  4430.6  327.61
  4471.0  320.39  4528.3  314.65  4545.3  310.05  4550.8  311.72  4594.9  308.31
  4688.5  299.44  4716.9  300.03  4734.4  296.40  4775.5  292.69  4877.6  288.11
  4980.4  287.57  5000.3  285.00  5003.1  284.50  5006.3  285.00  5012.9  287.21
  5177.7  286.75  5227.7  289.34  5292.3  294.89  5348.5  302.10  5385.0  304.51
  5427.7  309.85  5435.0  311.95  5506.8  318.61  5513.1  320.32  5535.0  320.11
#Mann=5,-1,0
  4319.1    0.05       0  4594.9    0.08       0  4775.5    0.05       0
  5000.3    0.03       0  5006.3    0.05       0
Bank Sta=5000.3,5006.3
Exp/Cntr=0.3,0.1

Type RM Length L Ch R = 1,10454,452,452,452
BEGIN DESCRIPTION:
UNT 146 IN BUCR 22.0
END DESCRIPTION:
XS GIS Cut Line= 3
      3660599.61     10543960.19      3660099.61     10543360.19
      3659549.64     10543360.19
#Sta/Elev= 30
  4223.9  346.93  4323.5  338.91  4344.3  335.26  4366.4  333.90  4373.0  331.90
  4387.3  331.91  4393.8  329.93  4415.9  329.77  4422.4  327.63  4458.2  325.64
  4581.0  310.16  4600.7  307.71  4607.3  305.36  4628.1  303.50  4642.4  298.70
  4671.0  299.63  4732.8  295.42  4876.7  284.48  4976.9  284.46  4991.3  284.12
  4994.8  282.45  4997.5  281.95  5000.8  282.45  5001.7  284.89  5144.9  284.43
  5344.9  290.01  5414.9  296.09  5454.9  302.36  5464.9  305.29  5554.9  316.37
#Mann=5,-1,0
  4223.9    0.05       0  4581.0    0.08       0  4732.8    0.05       0
  4994.8    0.03       0  5000.8    0.05       0
Bank Sta=4994.8,5000.8
Exp/Cntr=0.3,0.1

Type RM Length L Ch R = 1,10002,433,433,433
BEGIN DESCRIPTION:
UNT 146 IN BUCR 21.0
END DESCRIPTION:
XS GIS Cut Line= 3
      3660699.61     10543460.19      3660399.61     10543060.19
      3659749.61     10542460.19
#Sta/Elev= 30
  4497.7  319.46  4619.6  309.12  4715.1  298.19  4755.0  293.18  4761.2  290.04
  4769.6  288.63  4847.7  285.70  4871.8  283.29  4984.2  282.19  4987.4  280.76
  4990.2  280.26  4993.4  280.76  5004.8  282.54  5351.5  281.87  5450.5  286.47
  5478.8  290.77  5509.5  293.41  5521.4  295.24  5549.7  296.73  5613.2  305.78
  5627.4  306.28  5649.0  311.23  5663.1  311.47  5684.1  314.82  5698.3  315.60
  5719.3  321.02  5751.3  324.62  5804.3  331.75  5825.9  336.16  5882.3  337.99
#Mann=7,-1,0
  4497.7    0.05       0  4715.1    0.08       0  4871.8    0.05       0
  4987.4    0.03       0  4993.4    0.05       0  5509.5    0.16       0
  5751.3    0.05       0
Bank Sta=4987.4,4993.4
Exp/Cntr=0.3,0.1

Type RM Length L Ch R = 1,9569,645,645,645
BEGIN DESCRIPTION:
UNT 146 IN BUCR 20.0
END DESCRIPTION:
XS GIS Cut Line= 3
      3660799.60     10543510.15      3660649.61     10542710.19
      3659849.57     10542460.18
#Sta/Elev= 30
  4176.8  323.48  4268.3  314.04  4339.6  308.91  4533.7  290.84  4644.8  282.98
  4705.8  281.52  4777.7  281.92  4795.4  282.60  4848.3  280.53  4970.4  281.09
  4993.3  280.38  4998.2  278.96  5000.9  278.46  5004.2  278.96  5006.9  280.51
  5022.1  280.94  5136.9  280.43  5326.0  282.06  5477.4  287.81  5535.5  292.48
  5542.3  294.47  5574.8  298.07  5607.3  299.54  5645.0  304.42  5671.7  305.44
  5677.5  307.79  5703.1  310.37  5734.6  316.47  5747.7  317.15  5828.9  327.94
#Mann=5,-1,0
  4176.8    0.05       0  4777.7    0.08       0  4795.4    0.05       0
  4998.2    0.03       0  5004.2    0.05       0
Bank Sta=4998.2,5004.2
Exp/Cntr=0.3,0.1

Type RM Length L Ch R = 1,8924,486,486,486
BEGIN DESCRIPTION:
UNT 146 IN BUCR 18.0
END DESCRIPTION:
XS GIS Cut Line= 3
      3662151.16     10542846.45      3661921.99     10542443.67
      3659380.36     10542089.51
#Sta/Elev= 30
  3730.1  315.74  3780.7  315.12  4035.0  289.98  4103.5  285.12  4109.3  286.43
  4117.0  284.14  4150.4  284.46  4190.0  282.34  4327.5  282.60  4589.7  276.94
  4731.0  278.12  4738.1  275.43  4740.9  274.93  4744.1  275.43  4759.2  278.22
  4811.5  278.71  5022.6  278.16  5094.5  281.69  5191.5  279.56  5861.9  285.92
  6174.9  298.13  6336.4  306.81  6430.5  308.76  6477.8  312.12  6497.0  316.01
  6502.1  314.79  6548.4  321.80  6609.0  324.72  6699.9  337.15  6759.7  340.56
#Mann=9,-1,0
  3730.1    0.05       0  4035.0    0.08       0  4150.4    0.12       0
  4327.5    0.08       0  4738.1    0.04       0  4744.1    0.08       0
  4811.5    0.05       0  5022.6    0.08       0  5191.5    0.05       0
Bank Sta=4738.1,4744.1
Exp/Cntr=0.3,0.1

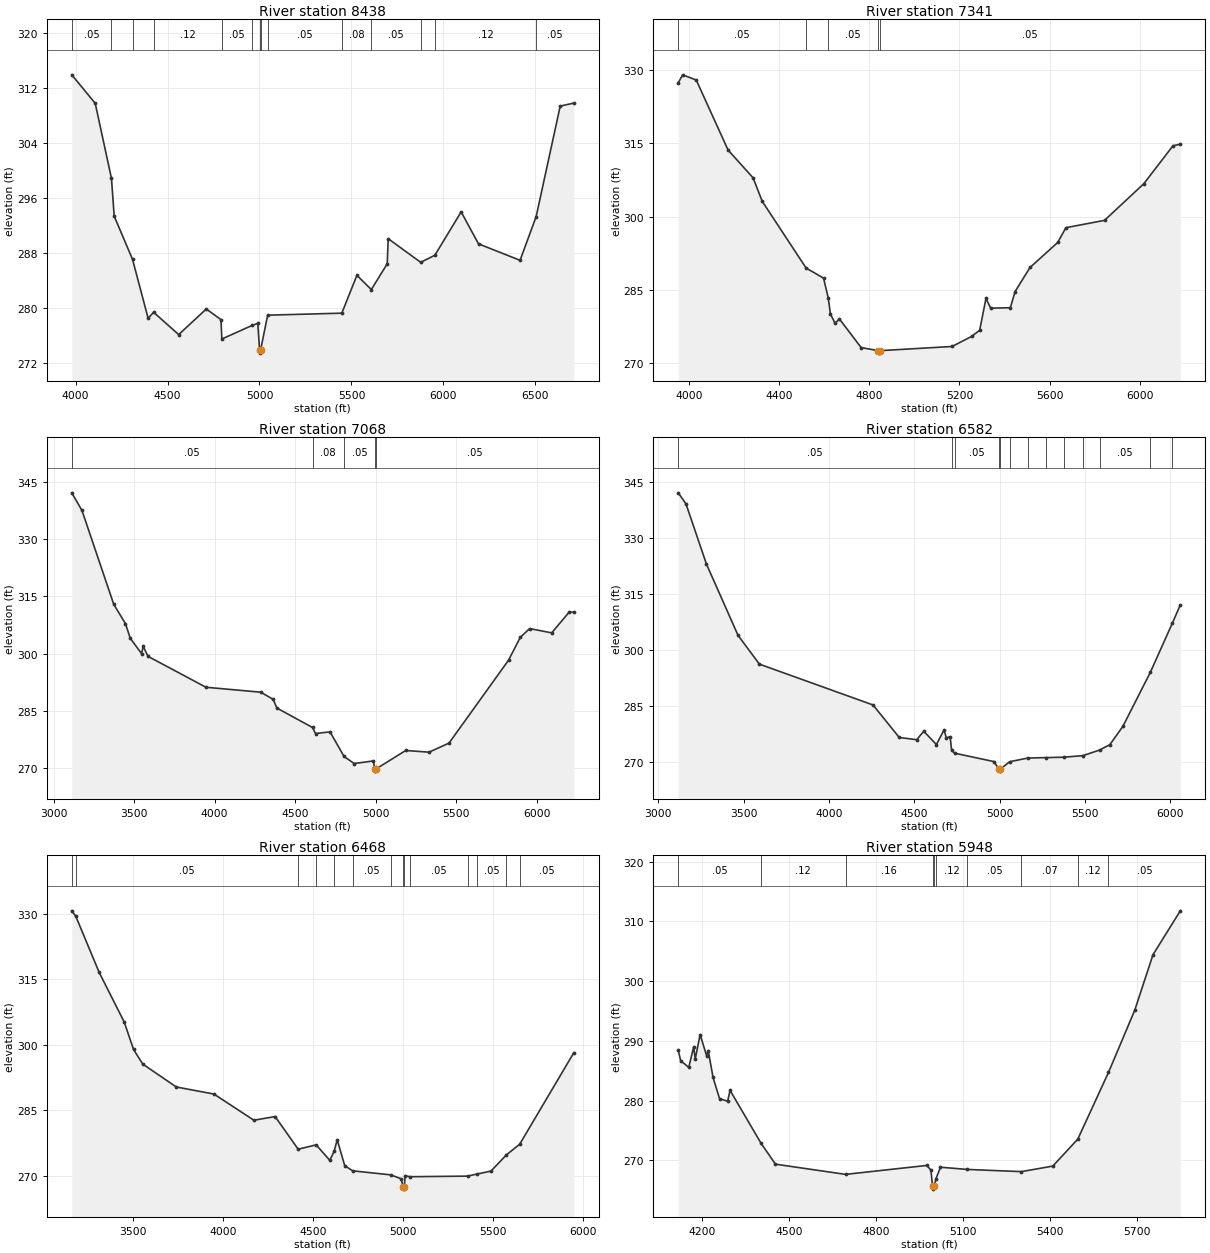
Type RM Length L Ch R = 1,8438,1097,1097,1097
BEGIN DESCRIPTION:
UNT 146 IN BUCR 19.0
END DESCRIPTION:
XS GIS Cut Line= 5
      3662276.15     10542776.99      3662019.21     10542311.72
      3661765.39     10542303.62      3661411.23     10542195.98
      3659887.86     10541803.18
#Sta/Elev= 30
  3979.7  313.88  4107.2  309.74  4195.5  298.84  4210.3  293.37  4310.0  287.09
  4394.8  278.54  4424.5  279.42  4560.8  276.18  4710.9  279.90  4790.5  278.35
  4795.5  275.54  4961.5  277.53  4990.7  277.81  5000.4  273.99  5003.2  273.49
  5006.4  273.99  5044.3  279.00  5447.4  279.29  5529.4  284.78  5607.8  282.72
  5694.3  286.46  5699.5  290.10  5876.1  286.67  5952.9  287.69  6096.0  293.99
  6190.3  289.35  6416.2  286.96  6503.6  293.30  6634.4  309.34  6708.5  309.78
#Mann=14,-1,0
  3979.7    0.05       0  4195.5    0.08       0  4310.0    0.05       0
  4424.5    0.12       0  4795.5    0.05       0  4961.5    0.07       0
  5000.4    0.07       0  5006.4    0.07       0  5044.3    0.05       0
  5447.4    0.08       0  5607.8    0.05       0  5876.1    0.07       0
  5952.9    0.12       0  6503.6    0.05       0
Bank Sta=5000.4,5006.4
Exp/Cntr=0.3,0.1

Type RM Length L Ch R = 1,7341,273,273,273
BEGIN DESCRIPTION:
UNT 146 IN BUCR 16.0
END DESCRIPTION:
XS GIS Cut Line= 3
      3662329.31     10543159.48      3662481.21     10541998.50
      3661895.27     10541119.58
#Sta/Elev= 30
  3952.8  327.39  3972.3  329.04  4032.8  327.97  4174.0  313.64  4284.9  307.96
  4325.2  303.17  4520.0  289.51  4597.5  287.44  4618.4  283.34  4627.8  280.13
  4648.0  278.22  4668.1  279.07  4764.2  273.24  4840.1  272.60  4842.8  272.10
  4846.1  272.60  5167.7  273.46  5253.8  275.51  5289.9  276.77  5317.9  283.29
  5338.9  281.30  5426.1  281.39  5447.1  284.70  5513.2  289.62  5636.4  294.75
  5672.5  297.77  5843.7  299.26  6018.0  306.76  6147.2  314.51  6180.0  314.86
#Mann=5,-1,0
  3952.8    0.05       0  4520.0    0.08       0  4618.4    0.05       0
  4840.1    0.03       0  4846.1    0.05       0
Bank Sta=4840.1,4846.1
Exp/Cntr=0.3,0.1

Type RM Length L Ch R = 1,7068,486,486,486
BEGIN DESCRIPTION:
UNT 146 IN BUCR 15.0
END DESCRIPTION:
XS GIS Cut Line= 3
      3662643.98     10544103.49      3662730.78     10541955.10
      3662220.82     10541130.49
#Sta/Elev= 30
  3112.1  342.12  3175.5  337.50  3373.0  312.93  3445.7  307.89  3475.7  304.05
  3545.8  300.04  3555.8  301.96  3585.8  299.32  3946.1  291.23  4286.4  289.94
  4363.8  288.06  4386.4  285.79  4608.0  280.70  4626.6  279.12  4716.7  279.56
  4804.0  273.11  4866.8  271.27  4986.9  271.95  4993.9  269.78  4996.7  269.28
  4999.9  269.78  5187.1  274.68  5331.8  274.24  5456.1  276.61  5825.9  298.31
  5899.2  304.30  5957.1  306.59  6094.2  305.47  6204.2  310.97  6231.8  310.85
#Mann=5,-1,0
  3112.1    0.05       0  4608.0    0.08       0  4804.0    0.05       0
  4993.9    0.03       0  4999.9    0.05       0
Bank Sta=4993.9,4999.9
Exp/Cntr=0.3,0.1

Type RM Length L Ch R = 1,6582,114,114,114
BEGIN DESCRIPTION:
UNT 146 IN BUCR 14.0
END DESCRIPTION:
XS GIS Cut Line= 5
      3662698.94     10544094.35      3663015.77     10542649.06
      3663245.81     10542191.16      3663467.16     10541672.50
      3663616.91     10541318.75
#Sta/Elev= 30
  3117.7  342.15  3162.9  339.21  3282.5  323.10  3468.0  303.95  3592.9  296.25
  4258.3  285.31  4411.9  276.60  4514.3  276.00  4555.2  278.27  4629.6  274.71
  4674.4  278.63  4687.5  276.48  4709.8  276.81  4718.7  273.15  4735.9  272.39
  4965.3  270.15  4997.1  268.08  4999.9  267.58  5003.1  268.08  5058.9  270.10
  5165.1  271.09  5270.0  271.20  5375.0  271.31  5487.3  271.73  5584.8  273.22
  5645.3  274.68  5721.7  279.59  5882.8  294.11  6010.6  307.16  6057.8  312.12
#Mann=13,-1,0
  3117.7    0.05       0  4718.7    0.12       0  4735.9    0.05       0
  4997.1    0.04       0  5003.1    0.05       0  5058.9    0.08       0
  5165.1    0.05       0  5270.0    0.08       0  5375.0    0.05       0
  5487.3    0.08       0  5584.8    0.05       0  5882.8    0.16       0
  6010.6    0.05       0
Bank Sta=4997.1,5003.1
Exp/Cntr=0.3,0.1

Type RM Length L Ch R = 1,6468,520,520,520
BEGIN DESCRIPTION:
UNT 146 IN BUCR 13.0
END DESCRIPTION:
XS GIS Cut Line= 4
      3662818.91     10544043.63      3663173.06     10542580.14
      3663367.33     10542144.72      3663734.50     10541426.00
#Sta/Elev= 30
  3159.1  330.65  3181.8  329.37  3311.4  316.54  3450.7  305.17  3502.2  298.91
  3553.6  295.55  3740.0  290.31  3949.2  288.69  4170.9  282.70  4289.0  283.54
  4417.0  276.06  4517.0  277.06  4592.8  273.51  4617.0  275.62  4634.0  278.23
  4675.7  272.29  4719.9  271.11  4931.1  270.19  4987.7  269.31  5001.2  267.42
  5004.0  266.92  5007.2  267.42  5011.0  270.03  5036.7  269.76  5358.3  269.90
  5412.5  270.39  5488.3  271.05  5574.4  274.78  5647.8  277.20  5948.7  298.17
#Mann=14,-1,0
  3159.1    0.16       0  3181.8    0.05       0  4417.0    0.08       0
  4517.0    0.05       0  4617.0    0.12       0  4719.9    0.05       0
  4931.1    0.16       0  5001.2    0.07       0  5007.2    0.16       0
  5036.7    0.05       0  5358.3    0.08       0  5412.5    0.05       0
  5574.4    0.08       0  5647.8    0.05       0
Bank Sta=5001.2,5007.2
Exp/Cntr=0.3,0.1

Type RM Length L Ch R = 1,5948,393,393,393
BEGIN DESCRIPTION:
UNT 146 IN BUCR 12.0
END DESCRIPTION:
XS GIS Cut Line= 3
      3664149.63     10542960.23      3663749.61     10542160.19
      3663999.60     10541360.21
#Sta/Elev= 30
  4116.5  288.45  4124.9  286.66  4152.9  285.56  4169.6  288.96  4175.2  286.97
  4192.0  291.04  4214.4  287.50  4220.0  288.36  4236.7  283.86  4259.1  280.31
  4287.0  279.88  4295.4  281.69  4402.4  272.83  4452.0  269.34  4693.8  267.63
  4974.6  269.13  4988.6  268.33  4994.0  265.66  4996.7  265.16  5000.0  265.66
  5005.8  266.89  5021.4  268.83  5113.8  268.46  5300.7  268.09  5409.1  269.02
  5495.4  273.54  5601.2  284.70  5692.0  295.14  5754.8  304.42  5849.1  311.77
#Mann=10,-1,0
  4116.5    0.05       0  4402.4    0.12       0  4693.8    0.16       0
  4994.0    0.07       0  5000.0    0.16       0  5005.8    0.12       0
  5113.8    0.05       0  5300.7    0.07       0  5495.4    0.12       0
  5601.2    0.05       0
Bank Sta=4994,5000
Exp/Cntr=0.3,0.1