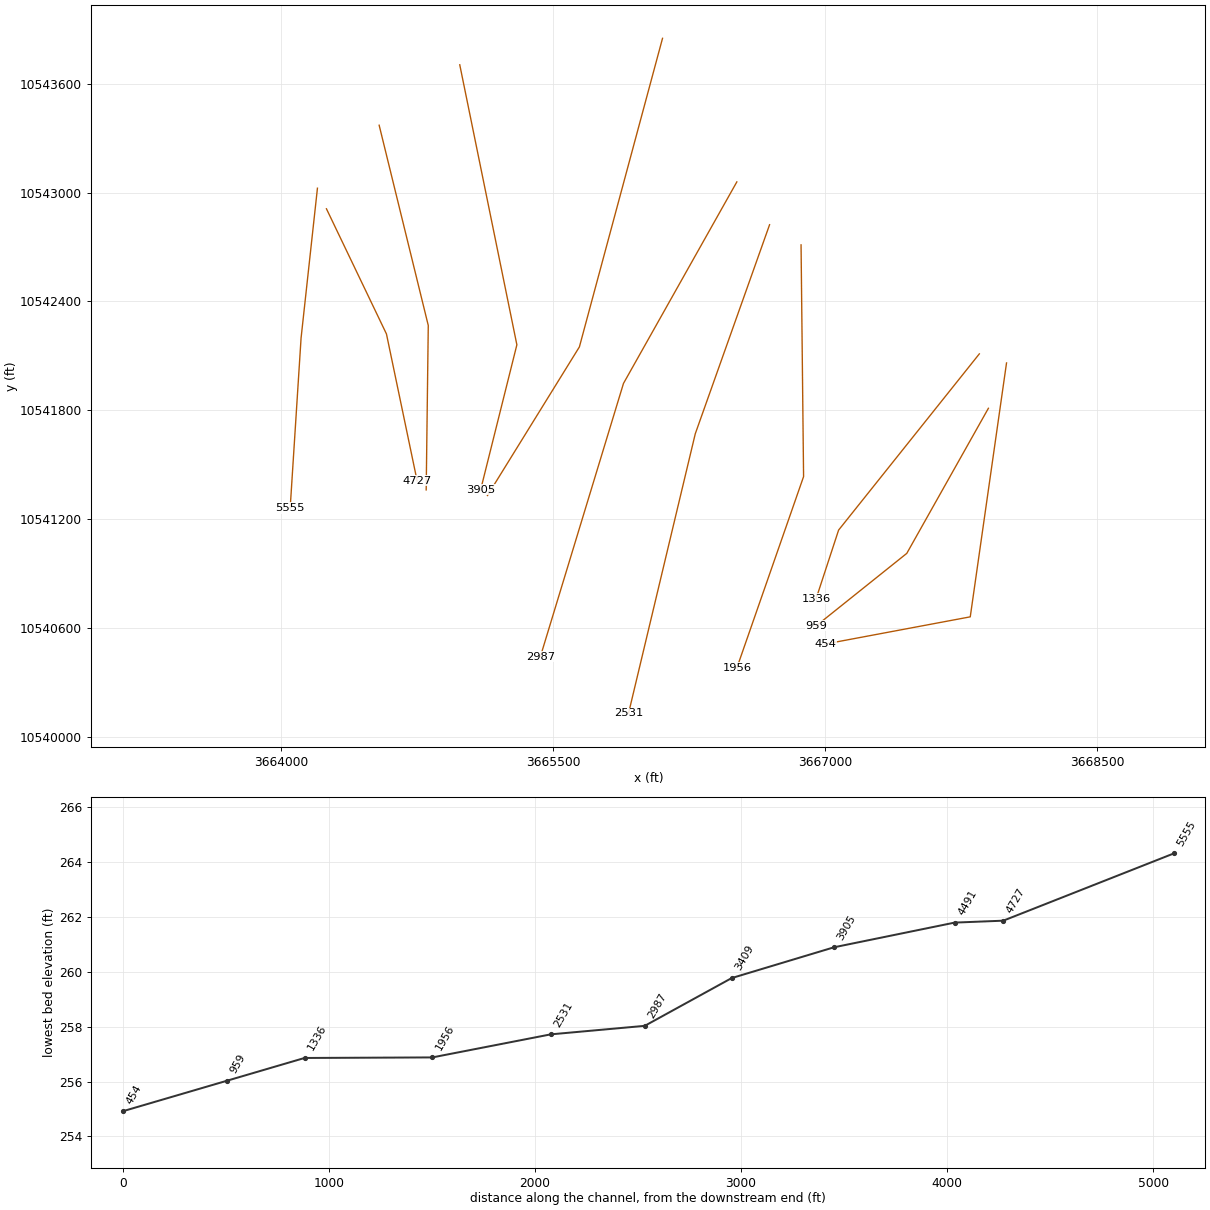
HEC-RAS study UNT 146 IN BUCR.prj: UNT 146 IN BUCR Base Level Engineering

--- UNT 146 IN BUCR.g01 (geometry) --- (continued)

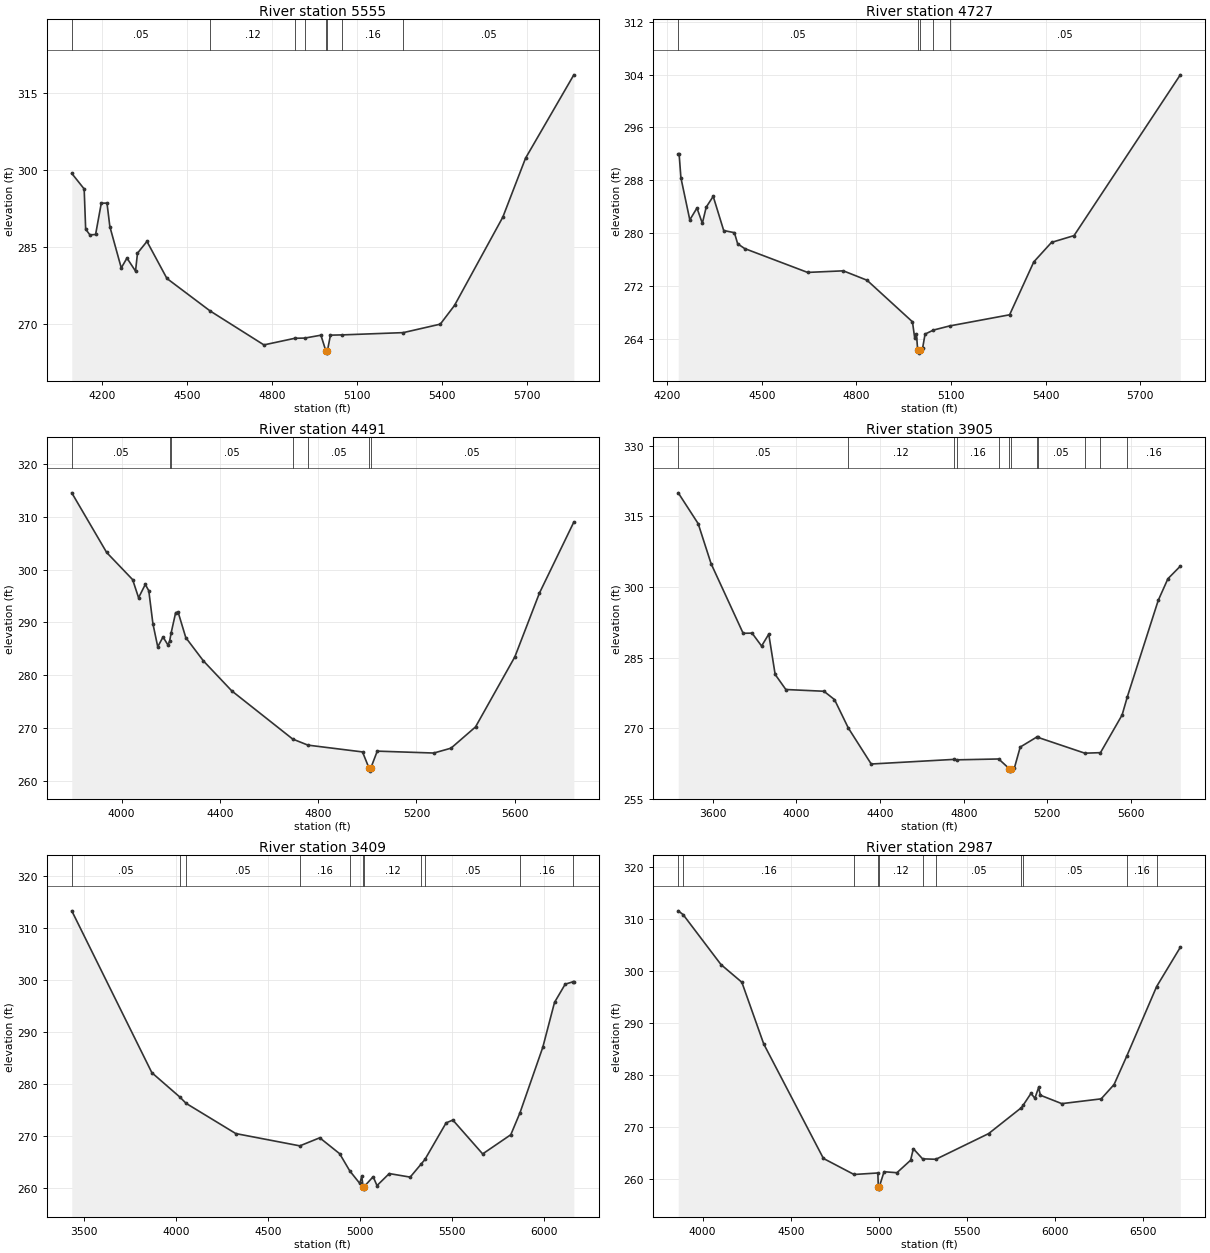
Type RM Length L Ch R = 1,5555,828,828,828
BEGIN DESCRIPTION:
UNT 146 IN BUCR 11.0
END DESCRIPTION:
XS GIS Cut Line= 3
      3664199.96     10543023.68      3664109.69     10542197.29
      3664049.61     10541260.22
#Sta/Elev= 30
  4094.0  299.29  4137.7  296.26  4143.0  288.44  4157.9  287.32  4178.0  287.40
  4198.1  293.49  4218.2  293.51  4228.3  288.93  4268.5  280.89  4288.6  282.81
  4318.8  280.27  4325.7  283.76  4359.1  286.05  4429.5  278.84  4581.8  272.52
  4771.5  265.91  4880.6  267.20  4915.8  267.24  4972.5  267.80  4989.5  264.81
  4992.3  264.31  4995.5  264.81  5006.1  267.81  5048.3  267.86  5262.9  268.30
  5393.4  269.95  5443.5  273.59  5613.8  290.77  5694.0  302.25  5864.3  318.47
#Mann=8,-1,0
  4094.0    0.05       0  4581.8    0.12       0  4880.6    0.16       0
  4915.8    0.12       0  4989.5    0.07       0  4995.5    0.12       0
  5048.3    0.16       0  5262.9    0.05       0
Bank Sta=4989.5,4995.5
Exp/Cntr=0.3,0.1

Type RM Length L Ch R = 1,4727,236,236,236
BEGIN DESCRIPTION:
UNT 146 IN BUCR 10.0
END DESCRIPTION:
XS GIS Cut Line= 3
      3664249.61     10542910.18      3664580.50     10542220.00
      3664749.61     10541410.17
#Sta/Elev= 30
  4234.6  292.00  4237.4  292.00  4243.1  288.38  4271.3  282.02  4294.0  283.81
  4311.1  281.50  4323.3  283.94  4345.5  285.58  4378.8  280.41  4412.8  280.08
  4423.1  278.40  4445.3  277.68  4644.9  274.07  4758.2  274.31  4833.4  272.89
  4977.6  266.60  4984.8  264.12  4990.3  264.75  4994.1  262.36  4996.9  261.86
  5000.1  262.36  5010.0  262.66  5017.6  264.74  5044.3  265.35  5095.2  265.97
  5285.8  267.66  5362.5  275.66  5418.7  278.61  5490.2  279.64  5827.3  303.96
#Mann=5,-1,0
  4234.6    0.05       0  4994.1    0.03       0  5000.1    0.05       0
  5044.3    0.12       0  5095.2    0.05       0
Bank Sta=4994.1,5000.1
Exp/Cntr=0.3,0.1

Type RM Length L Ch R = 1,4491,586,586,586
BEGIN DESCRIPTION:
UNT 146 IN BUCR 9.0
END DESCRIPTION:
XS GIS Cut Line= 3
      3664540.24     10543370.89      3664811.08     10542266.73
      3664799.61     10541360.19
#Sta/Elev= 30
  3797.1  314.55  3939.1  303.24  4044.9  298.09  4069.0  294.66  4096.4  297.19
  4110.6  295.98  4127.3  289.76  4147.0  285.36  4168.5  287.22  4188.6  285.70
  4195.5  286.44  4201.3  287.94  4220.0  291.85  4230.2  291.89  4261.2  287.10
  4333.2  282.67  4448.4  277.00  4696.3  267.87  4758.2  266.72  4980.5  265.43
  5007.5  262.29  5010.3  261.79  5013.5  262.29  5040.5  265.58  5270.6  265.22
  5340.6  266.14  5440.4  270.17  5600.6  283.47  5700.6  295.55  5840.6  309.01
#Mann=7,-1,0
  3797.1    0.05       0  4195.5    0.12       0  4201.3    0.05       0
  4696.3    0.16       0  4758.2    0.05       0  5007.5    0.03       0
  5013.5    0.05       0
Bank Sta=5007.5,5013.5
Exp/Cntr=0.3,0.1

Type RM Length L Ch R = 1,3905,496,496,496
BEGIN DESCRIPTION:
UNT 146 IN BUCR 8.0
END DESCRIPTION:
XS GIS Cut Line= 3
      3664984.68     10543704.25      3665299.61     10542160.19
      3665099.60     10541360.16
#Sta/Elev= 30
  3435.2  319.98  3530.5  313.44  3592.4  304.92  3745.5  290.16  3788.3  290.19
  3833.7  287.45  3868.0  289.97  3898.6  281.42  3949.6  278.22  4131.8  277.85
  4182.3  276.08  4248.6  270.03  4357.9  262.40  4752.6  263.38  4769.2  263.29
  4967.3  263.47  5018.4  261.39  5021.1  260.89  5024.4  261.39  5042.0  261.49
  5070.3  266.00  5150.6  268.16  5153.3  268.08  5379.3  264.70  5454.0  264.81
  5557.4  272.81  5582.6  276.70  5730.0  297.13  5776.4  301.74  5835.7  304.41
#Mann=12,-1,0
  3435.2    0.05       0  4248.6    0.12       0  4752.6    0.05       0
  4769.2    0.16       0  4967.3    0.12       0  5018.4    0.07       0
  5024.4    0.12       0  5150.6    0.16       0  5153.3    0.05       0
  5379.3    0.07       0  5454.0    0.05       0  5582.6    0.16       0
Bank Sta=5018.4,5024.4
Exp/Cntr=0.3,0.1

Type RM Length L Ch R = 1,3409,422,422,422
BEGIN DESCRIPTION:
UNT 146 IN BUCR 7.0
END DESCRIPTION:
XS GIS Cut Line= 3
      3666102.74     10543850.07      3665644.41     10542148.68
      3665137.48     10541329.25
#Sta/Elev= 30
  3435.3  313.28  3870.2  282.15  4022.5  277.46  4056.0  276.26  4325.8  270.45
  4673.4  268.09  4781.5  269.64  4889.6  266.58  4944.6  263.27  4999.0  260.86
  5009.5  262.25  5016.7  260.27  5019.5  259.77  5022.7  260.27  5071.5  262.16
  5092.2  260.45  5158.8  262.76  5272.5  262.08  5332.6  264.62  5352.6  265.48
  5467.5  272.51  5504.1  273.05  5665.9  266.54  5818.6  270.23  5868.5  274.45
  5992.3  287.04  6056.1  295.68  6114.0  299.18  6157.6  299.65  6160.9  299.65
#Mann=11,-1,0
  3435.3    0.05       0  4022.5    0.16       0  4056.0    0.05       0
  4673.4    0.16       0  4944.6    0.12       0  5016.7    0.07       0
  5022.7    0.12       0  5332.6    0.16       0  5352.6    0.05       0
  5868.5    0.16       0  6157.6    0.05       0
Bank Sta=5016.7,5022.7
Exp/Cntr=0.3,0.1

Type RM Length L Ch R = 1,2987,456,456,456
BEGIN DESCRIPTION:
UNT 146 IN BUCR 6.0
END DESCRIPTION:
XS GIS Cut Line= 3
      3666512.47     10543058.41      3665887.46     10541947.29
      3665429.15     10540440.39
#Sta/Elev= 30
  3861.6  311.61  3889.7  310.87  4104.1  301.27  4222.7  297.86  4347.0  285.97
  4685.6  263.94  4859.3  260.85  4994.6  261.14  4997.3  258.53  5000.1  258.03
  5003.3  258.53  5029.9  261.38  5103.0  261.19  5180.5  263.59  5196.1  265.81
  5248.6  263.86  5324.2  263.78  5623.4  268.72  5809.8  273.72  5820.1  274.22
  5863.9  276.46  5886.0  275.53  5907.2  277.60  5917.3  276.11  6038.7  274.49
  6262.3  275.41  6335.4  278.16  6406.6  283.57  6577.2  297.04  6711.5  304.59
#Mann=11,-1,0
  3861.6    0.05       0  3889.7    0.16       0  4859.3    0.12       0
  4997.3    0.07       0  5003.3    0.12       0  5248.6    0.16       0
  5324.2    0.05       0  5809.8    0.16       0  5820.1    0.05       0
  6406.6    0.16       0  6577.2    0.05       0
Bank Sta=4997.3,5003.3
Exp/Cntr=0.3,0.1

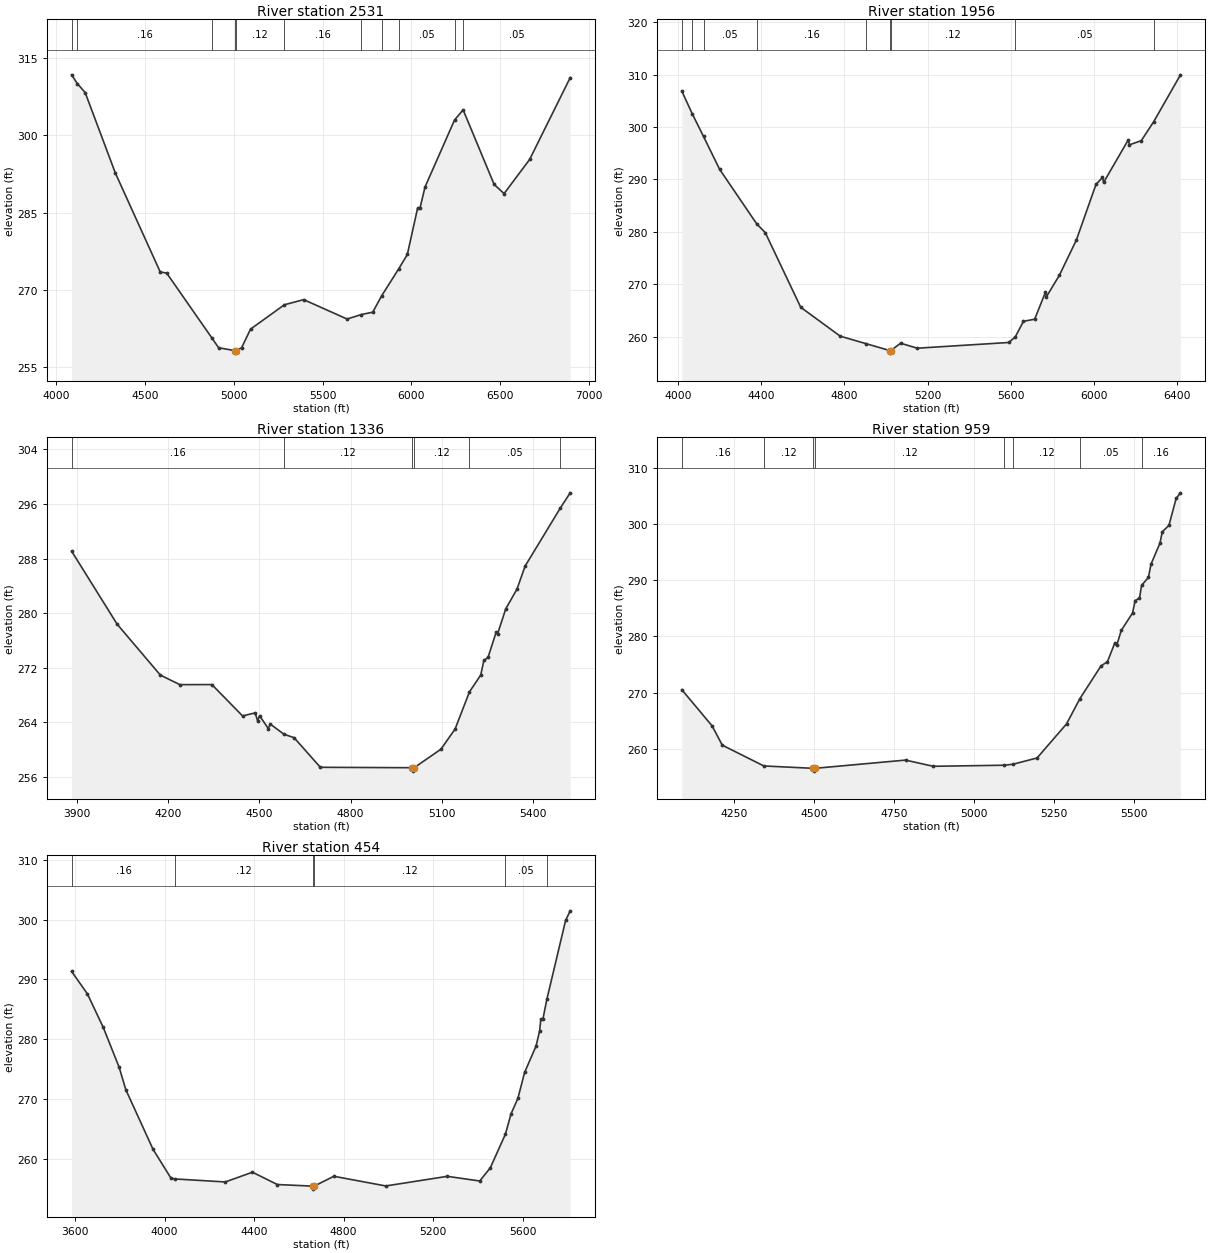
Type RM Length L Ch R = 1,2531,575,575,575
BEGIN DESCRIPTION:
UNT 146 IN BUCR 5.0
END DESCRIPTION:
XS GIS Cut Line= 3
      3666693.03     10542822.31      3666283.30     10541669.51
      3665915.25     10540127.89
#Sta/Elev= 30
  4085.9  311.77  4118.2  310.07  4162.4  308.32  4332.3  292.70  4585.2  273.48
  4621.4  273.27  4875.1  260.71  4914.0  258.76  5003.5  258.22  5006.3  257.72
  5009.5  258.22  5043.3  258.75  5093.7  262.38  5284.3  267.11  5392.9  268.11
  5637.6  264.34  5717.2  265.21  5782.1  265.67  5832.0  268.84  5928.5  274.10
  5976.9  276.88  6034.6  285.86  6048.9  285.99  6076.7  290.00  6242.8  303.00
  6291.1  304.97  6465.9  290.48  6521.8  288.70  6665.8  295.34  6894.3  311.23
#Mann=11,-1,0
  4085.9    0.05       0  4118.2    0.16       0  4875.1    0.12       0
  5003.5    0.07       0  5009.5    0.12       0  5284.3    0.16       0
  5717.2    0.05       0  5832.0     0.1       0  5928.5    0.05       0
  6242.8    0.16       0  6291.1    0.05       0
Bank Sta=5003.5,5009.5
Exp/Cntr=0.3,0.1

Type RM Length L Ch R = 1,1956,620,620,620
BEGIN DESCRIPTION:
UNT 146 IN BUCR 4.0
END DESCRIPTION:
XS GIS Cut Line= 3
      3666866.63     10542711.14      3666880.52     10541433.40
      3666512.47     10540377.84
#Sta/Elev= 30
  4018.8  306.84  4068.7  302.52  4122.9  298.20  4199.8  291.96  4378.6  281.52
  4419.8  279.84  4589.8  265.63  4779.8  260.11  4904.1  258.68  5016.8  257.38
  5019.6  256.88  5022.8  257.38  5069.8  258.77  5149.8  257.82  5589.6  258.91
  5621.0  259.99  5660.1  262.95  5713.9  263.35  5765.4  268.46  5770.7  267.65
  5832.9  271.75  5914.3  278.45  6008.7  289.07  6039.8  290.38  6045.1  289.43
  6164.1  297.57  6169.4  296.60  6226.2  297.40  6285.5  300.99  6414.5  309.95
#Mann=9,-1,0
  4018.8    0.05       0  4068.7    0.16       0  4122.9    0.05       0
  4378.6    0.16       0  4904.1    0.12       0  5016.8    0.07       0
  5022.8    0.12       0  5621.0    0.05       0  6285.5    0.16       0
Bank Sta=5016.8,5022.8
Exp/Cntr=0.3,0.1

Type RM Length L Ch R = 1,1336,377,377,377
BEGIN DESCRIPTION:
UNT 146 IN BUCR 3.0
END DESCRIPTION:
XS GIS Cut Line= 3
      3667849.61     10542110.20      3667073.62     10541138.52
      3666949.59     10540760.14
#Sta/Elev= 30
  3881.5  289.09  4031.2  278.40  4173.7  270.93  4237.8  269.53  4343.4  269.54
  4444.3  264.95  4485.9  265.39  4493.9  264.23  4500.3  264.98  4529.1  263.10
  4535.5  263.76  4580.7  262.26  4614.0  261.76  4700.5  257.42  5003.3  257.36
  5006.0  256.86  5009.3  257.36  5097.5  260.07  5144.3  263.04  5191.4  268.47
  5228.5  270.93  5239.0  273.09  5252.5  273.51  5279.1  277.18  5284.4  277.01
  5310.9  280.63  5348.0  283.53  5374.6  286.89  5490.7  295.41  5523.2  297.63
#Mann=6,-1,0
  3881.5    0.16       0  4580.7    0.12       0  5003.3    0.07       0
  5009.3    0.12       0  5191.4    0.05       0  5490.7    0.16       0
Bank Sta=5003.3,5009.3
Exp/Cntr=0.3,0.1

Type RM Length L Ch R = 1,959,505,505,505
BEGIN DESCRIPTION:
UNT 146 IN BUCR 2.0
END DESCRIPTION:
XS GIS Cut Line= 3
      3667899.60     10541810.17      3667449.61     10541010.19
      3666949.59     10540610.17
#Sta/Elev= 30
  4086.7  270.50  4181.3  264.07  4212.9  260.65  4343.0  256.95  4496.4  256.53
  4499.2  256.03  4502.4  256.53  4785.6  257.99  4872.3  256.89  5094.8  257.08
  5121.6  257.26  5196.7  258.37  5288.7  264.42  5330.7  268.93  5396.0  274.70
  5416.8  275.51  5439.2  278.75  5445.6  278.39  5460.0  281.07  5495.2  284.16
  5503.2  286.36  5516.8  286.78  5523.3  289.05  5544.8  290.49  5552.8  292.83
  5580.8  296.58  5588.0  298.58  5608.9  299.75  5631.3  304.52  5644.9  305.52
#Mann=8,-1,0
  4086.7    0.16       0  4343.0    0.12       0  4496.4    0.07       0
  4502.4    0.12       0  5094.8    0.07       0  5121.6    0.12       0
  5330.7    0.05       0  5523.3    0.16       0
Bank Sta=4496.4,4502.4
Exp/Cntr=0.3,0.1

Type RM Length L Ch R = 1,454,0,0,0
BEGIN DESCRIPTION:
UNT 146 IN BUCR 1.0
END DESCRIPTION:
XS GIS Cut Line= 3
      3667999.61     10542060.21      3667799.61     10540660.19
      3666999.59     10540510.18
#Sta/Elev= 30
  3584.5  291.33  3655.2  287.57  3725.9  281.97  3796.7  275.33  3827.0  271.53
  3948.2  261.60  4029.0  256.73  4047.6  256.62  4271.4  256.12  4392.6  257.75
  4503.8  255.69  4662.4  255.42  4665.1  254.92  4668.4  255.42  4756.3  257.07
  4988.6  255.45  5263.3  257.06  5408.3  256.28  5455.7  258.49  5523.4  264.14
  5548.1  267.50  5578.7  270.08  5609.2  274.47  5660.1  278.85  5676.2  281.42
  5681.3  283.29  5690.6  283.34  5708.4  286.68  5792.3  299.89  5812.7  301.46
#Mann=6,-1,0
  3584.5    0.16       0  4047.6    0.12       0  4662.4    0.07       0
  4668.4    0.12       0  5523.4    0.05       0  5708.4    0.16       0
Bank Sta=4662.4,4668.4
Exp/Cntr=0.3,0.1

Chan Stop Cuts=-1