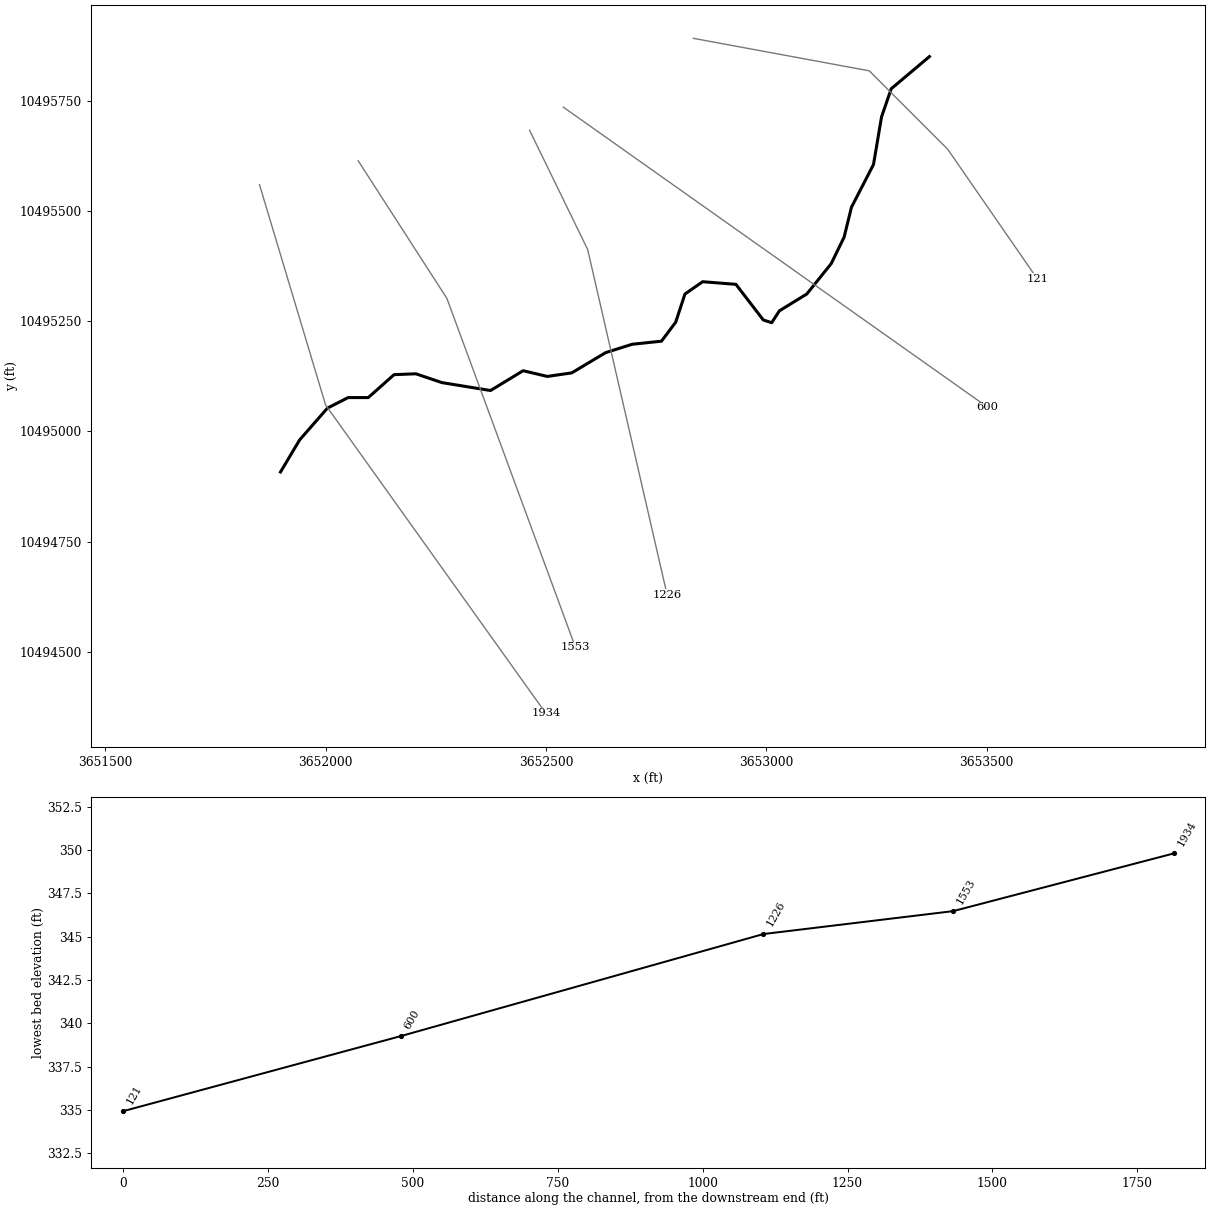
--- UNT 154 IN BUCR.prj (project) ---

Proj Title=UNT 154 IN BUCR Base Level Engineering
Current Plan=p01
Default Exp/Contr=0.3,0.1
English Units
Geom File=g01
Flow File=f01
Plan File=p01
BEGIN DESCRIPTION:
UNT 154 IN BUCR
END DESCRIPTION:

--- UNT 154 IN BUCR.p01 (plan) ---

Plan Title=Multiple Run
Short Identifier=Multiple
Geom File=g01
Flow File=f01
Subcritical Flow
K Sum by GR= 0
Std Step Tol= 0.01
Critical Tol= 0.01
Num of Std Step Trials= 20
Max Error Tol= 0.3
Flow Tol Ratio= 0.001
Split Flow NTrial= 30
Split Flow Tol= 0.02
Split Flow Ratio= 0.02
Log Output Level= 0
Friction Slope Method= 1
Unsteady Friction Slope Method= 2
Unsteady Bridges Friction Slope Method= 1
Parabolic Critical Depth
Global Vel Dist=  1 , 1 , 1
Global Log Level= 0
CheckData=True
Encroach Param= -1, 0, 0, 0
BEGIN DESCRIPTION:
Multiple Run
END DESCRIPTION:

--- UNT 154 IN BUCR.f01 (steady flow) ---

Flow Title=Multiple
Number of Profiles=7
Profile Names=10-year,25-year,50-year,1pct_min,100-year,1pct_plu,500-year
River Rch & RM= UNT 154 IN BUCR,Reach-1,1934
     784    1070    1308    1170    1582    2140    2323
Boundary for River Rch & Prof#=UNT 154 IN BUCR,Reach-1,1
Up Type=0
Dn Type=3
Dn Slope=0.005
Boundary for River Rch & Prof#=UNT 154 IN BUCR,Reach-1,2
Up Type=0
Dn Type=3
Dn Slope=0.005
Boundary for River Rch & Prof#=UNT 154 IN BUCR,Reach-1,3
Up Type=0
Dn Type=3
Dn Slope=0.005
Boundary for River Rch & Prof#=UNT 154 IN BUCR,Reach-1,4
Up Type=0
Dn Type=3
Dn Slope=0.005
Boundary for River Rch & Prof#=UNT 154 IN BUCR,Reach-1,5
Up Type=0
Dn Type=3
Dn Slope=0.005
Boundary for River Rch & Prof#=UNT 154 IN BUCR,Reach-1,6
Up Type=0
Dn Type=3
Dn Slope=0.005
Boundary for River Rch & Prof#=UNT 154 IN BUCR,Reach-1,7
Up Type=0
Dn Type=3
Dn Slope=0.005

--- UNT 154 IN BUCR.g01 (geometry) ---

Geom Title=Existing Conditions

River Reach=UNT 154 IN BUCR,Reach-1
Reach XY= 30
      3651897.25     10494908.00      3651940.75     10494981.00
      3652003.75     10495053.00      3652050.75     10495077.00
      3652096.50     10495077.00      3652155.00     10495129.00
      3652204.50     10495131.00      3652263.50     10495111.00
      3652374.00     10495093.00      3652448.00     10495138.00
      3652502.75     10495125.00      3652558.25     10495133.00
      3652635.25     10495179.00      3652695.50     10495198.00
      3652762.00     10495205.00      3652794.25     10495248.00
      3652815.25     10495312.00      3652855.50     10495340.00
      3652931.00     10495334.00      3652993.25     10495253.00
      3653012.25     10495247.00      3653029.75     10495274.00
      3653091.75     10495312.00      3653147.25     10495381.00
      3653176.50     10495441.00      3653193.25     10495509.00
      3653243.25     10495606.00      3653261.50     10495714.00
      3653283.50     10495778.00      3653370.25     10495851.00

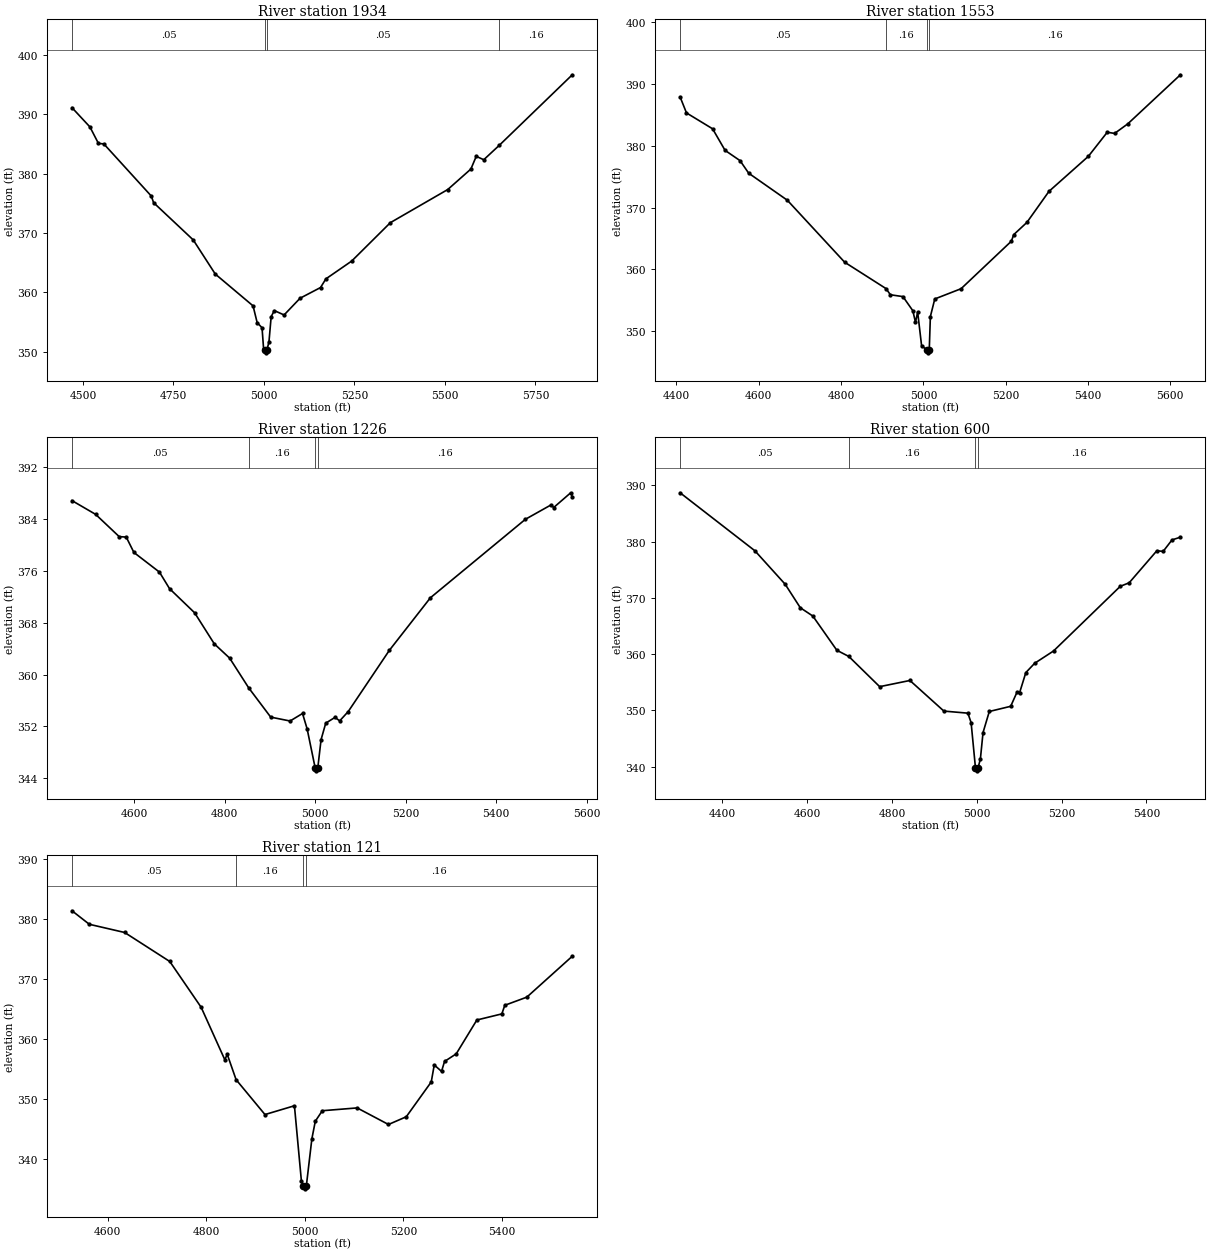
Type RM Length L Ch R = 1,1934,381,381,381
BEGIN DESCRIPTION:
UNT 154 IN BUCR 4.0
END DESCRIPTION:
XS GIS Cut Line= 3
      3651849.60     10495560.23      3651999.61     10495060.19
      3652499.61     10494360.18
#Sta/Elev= 30
  4469.6  391.10  4519.2  387.85  4542.7  385.07  4557.5  385.00  4688.9  376.20
  4695.0  375.10  4804.6  368.82  4865.5  363.07  4969.9  357.71  4981.2  354.89
  4994.7  354.02  4999.0  350.46  5002.2  350.30  5004.9  349.80  5008.2  350.30
  5013.8  351.63  5019.9  355.89  5028.5  356.92  5055.6  356.18  5099.8  359.00
  5156.3  360.80  5171.1  362.26  5242.4  365.26  5349.3  371.73  5507.8  377.31
  5571.7  380.76  5586.5  382.90  5607.3  382.33  5650.2  384.76  5851.9  396.64
#Mann=4,-1,0
  4469.6    0.05       0  5002.2    0.03       0  5008.2    0.05       0
  5650.2    0.16       0
Bank Sta=5002.2,5008.2
Exp/Cntr=0.3,0.1

Type RM Length L Ch R = 1,1553,327,327,327
BEGIN DESCRIPTION:
Mapping XS fc5efcb4
END DESCRIPTION:
XS GIS Cut Line= 3
      3652073.68     10495614.36      3652275.05     10495301.89
      3652566.71     10494510.24
#Sta/Elev= 30
  4409.0  387.93  4424.5  385.34  4487.9  382.77  4518.3  379.27  4554.6  377.61
  4575.7  375.57  4669.4  371.20  4808.8  361.15  4909.2  356.88  4919.9  355.88
  4950.4  355.58  4974.4  353.29  4980.8  351.42  4986.1  353.08  4995.7  347.60
  5008.3  346.97  5011.0  346.47  5014.3  346.97  5017.0  352.35  5027.7  355.20
  5091.6  356.86  5213.8  364.56  5219.5  365.62  5251.5  367.60  5305.1  372.63
  5400.7  378.30  5446.7  382.21  5464.6  382.02  5496.6  383.57  5624.4  391.52
#Mann=4,-1,0
  4409.0    0.05       0  4909.2    0.16       0  5008.3    0.07       0
  5014.3    0.16       0
Bank Sta=5008.3,5014.3
Exp/Cntr=0.3,0.1

Type RM Length L Ch R = 1,1226,626,626,626
BEGIN DESCRIPTION:
UNT 154 IN BUCR 3.0
END DESCRIPTION:
XS GIS Cut Line= 3
      3652462.55     10495683.85      3652594.50     10495413.00
      3652774.83     10494629.26
#Sta/Elev= 30
  4462.4  386.85  4514.6  384.73  4566.6  381.30  4582.3  381.22  4599.2  378.85
  4655.6  375.82  4678.0  373.26  4733.4  369.54  4776.8  364.75  4810.8  362.54
  4852.9  357.95  4901.5  353.44  4944.3  352.84  4971.8  354.00  4982.0  351.62
  4999.6  345.65  5002.3  345.15  5005.6  345.65  5012.8  349.97  5023.1  352.51
  5043.6  353.40  5053.9  352.86  5072.8  354.30  5163.6  363.74  5254.4  371.86
  5464.3  383.97  5521.5  386.21  5526.7  385.78  5564.4  388.06  5567.9  387.43
#Mann=4,-1,0
  4462.4    0.05       0  4852.9    0.16       0  4999.6    0.07       0
  5005.6    0.16       0
Bank Sta=4999.6,5005.6
Exp/Cntr=0.3,0.1

Type RM Length L Ch R = 1,600,479,479,479
BEGIN DESCRIPTION:
UNT 154 IN BUCR 2.0
END DESCRIPTION:
XS GIS Cut Line= 2
      3652539.35     10495736.13      3653502.52     10495054.97
#Sta/Elev= 30
  4300.5  388.68  4476.9  378.37  4548.3  372.42  4583.9  368.25  4613.5  366.77
  4670.1  360.69  4698.3  359.59  4771.1  354.22  4842.4  355.32  4922.5  349.88
  4979.1  349.51  4986.7  347.83  4997.0  339.76  4999.7  339.26  5003.0  339.76
  5008.6  341.39  5014.8  346.06  5029.6  349.81  5080.0  350.73  5094.8  353.22
  5100.9  353.11  5115.7  356.72  5136.6  358.38  5181.0  360.56  5338.5  372.06
  5359.4  372.68  5424.7  378.38  5439.5  378.26  5460.4  380.30  5480.2  380.79
#Mann=4,-1,0
  4300.5    0.05       0  4698.3    0.16       0  4997.0    0.07       0
  5003.0    0.16       0
Bank Sta=4997,5003
Exp/Cntr=0.3,0.1

Type RM Length L Ch R = 1,121,0,0,0
BEGIN DESCRIPTION:
UNT 154 IN BUCR 1.0
END DESCRIPTION:
XS GIS Cut Line= 4
      3652834.46     10495892.41      3653233.75     10495818.63
      3653411.70     10495640.67      3653615.13     10495346.35
#Sta/Elev= 30
  4527.2  381.42  4562.4  379.16  4634.1  377.79  4725.7  372.94  4789.4  365.28
  4837.3  356.53  4842.4  357.40  4860.3  353.18  4918.9  347.35  4978.7  348.82
  4992.9  336.19  4996.9  335.43  4999.7  334.93  5002.9  335.43  5014.1  343.30
  5021.1  346.24  5035.3  347.99  5106.0  348.46  5169.6  345.69  5205.7  346.98
  5256.4  352.80  5262.5  355.64  5277.3  354.57  5283.4  356.23  5307.1  357.50
  5349.0  363.16  5399.7  364.18  5405.7  365.62  5450.4  366.98  5542.7  373.82
#Mann=4,-1,0
  4527.2    0.05       0  4860.3    0.16       0  4996.9    0.07       0
  5002.9    0.16       0
Bank Sta=4996.9,5002.9
Exp/Cntr=0.3,0.1

Chan Stop Cuts=-1