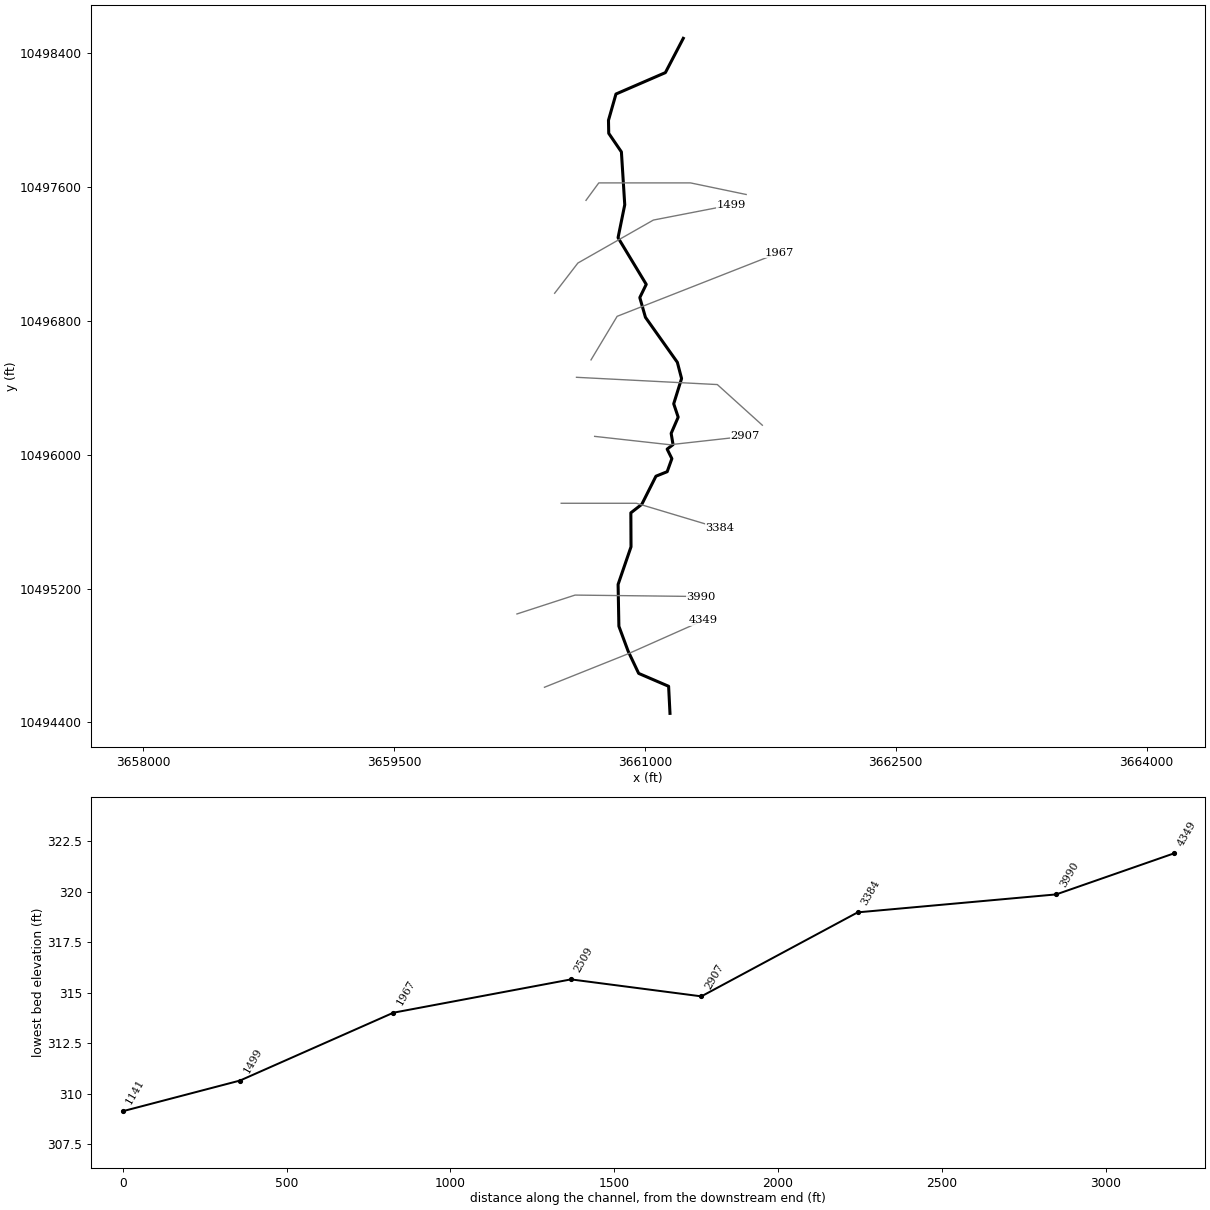
--- UNT 158 IN BUCR.prj (project) ---

Proj Title=UNT 158 IN BUCR Base Level Engineering
Current Plan=p01
Default Exp/Contr=0.3,0.1
English Units
Geom File=g01
Flow File=f01
Plan File=p01
Y Axis Title=Elevation
X Axis Title(PF)=Main Channel Distance
X Axis Title(XS)=Station
BEGIN DESCRIPTION:
UNT 158 IN BUCR
END DESCRIPTION:
DSS Export Rating Curves= 0
DSS Export Rating Curve Sorted= 0
DSS Export Volume Flow Curves= 0
DXF OffsetX= 0
DXF OffsetY= 0
DXF ScaleX= 1
DXF ScaleY= 10

--- UNT 158 IN BUCR.p01 (plan) ---

Plan Title=Multiple Run
Short Identifier=Multiple
Geom File=g01
Flow File=f01
Subcritical Flow
K Sum by GR= 0
Std Step Tol= 0.01
Critical Tol= 0.01
Num of Std Step Trials= 20
Max Error Tol= 0.3
Flow Tol Ratio= 0.001
Split Flow NTrial= 30
Split Flow Tol= 0.02
Split Flow Ratio= 0.02
Log Output Level= 0
Friction Slope Method= 1
Unsteady Friction Slope Method= 2
Unsteady Bridges Friction Slope Method= 1
Parabolic Critical Depth
Global Vel Dist=  1 , 1 , 1
Global Log Level= 0
CheckData=True
Encroach Param= -1, 0, 0, 0
BEGIN DESCRIPTION:
Multiple Run
END DESCRIPTION:

--- UNT 158 IN BUCR.f01 (steady flow) ---

Flow Title=Multiple
Program Version=4.10
Number of Profiles= 7
Profile Names=10-year,25-year,50-year,1pct_min,100-year,1pct_plu,500-year
River Rch & RM=UNT 158 IN BUCR,Reach-1         ,4349
     599     817     999     897    1214    1641    1799
Boundary for River Rch & Prof#=UNT 158 IN BUCR,Reach-1         , 1
Up Type= 0
Dn Type= 3
Dn Slope=0.006
Boundary for River Rch & Prof#=UNT 158 IN BUCR,Reach-1         , 2
Up Type= 0
Dn Type= 3
Dn Slope=0.006
Boundary for River Rch & Prof#=UNT 158 IN BUCR,Reach-1         , 3
Up Type= 0
Dn Type= 3
Dn Slope=0.006
Boundary for River Rch & Prof#=UNT 158 IN BUCR,Reach-1         , 4
Up Type= 0
Dn Type= 3
Dn Slope=0.006
Boundary for River Rch & Prof#=UNT 158 IN BUCR,Reach-1         , 5
Up Type= 0
Dn Type= 3
Dn Slope=0.006
Boundary for River Rch & Prof#=UNT 158 IN BUCR,Reach-1         , 6
Up Type= 0
Dn Type= 3
Dn Slope=0.006
Boundary for River Rch & Prof#=UNT 158 IN BUCR,Reach-1         , 7
Up Type= 0
Dn Type= 3
Dn Slope=0.006
DSS Import GetInterval= 0
DSS Import GetPeak= 0
DSS Import FillOption= 0

--- UNT 158 IN BUCR.g01 (geometry) ---

Geom Title=Existing Conditions
Program Version=4.10

River Reach=UNT 158 IN BUCR ,Reach-1
Reach XY= 30
        3661150.       10494454.      3661141.75       10494616.
      3660962.75       10494693.      3660899.75       10494826.
       3660844.5       10494975.      3660839.75       10495225.
        3660917.       10495450.        3660916.       10495653.
       3660981.5       10495704.        3661066.       10495872.
      3661133.25       10495899.      3661161.25       10495977.
        3661133.       10496034.      3661168.25       10496061.
        3661157.       10496128.        3661199.       10496225.
      3661172.25       10496305.      3661219.25       10496456.
        3661194.       10496553.      3661003.25       10496822.
       3660969.5       10496940.        3661008.       10497019.
       3660839.5       10497298.       3660879.5       10497495.
       3660859.5       10497811.      3660783.75       10497922.
      3660782.25       10498000.        3660827.       10498157.
       3661122.5       10498285.       3661229.5       10498490.

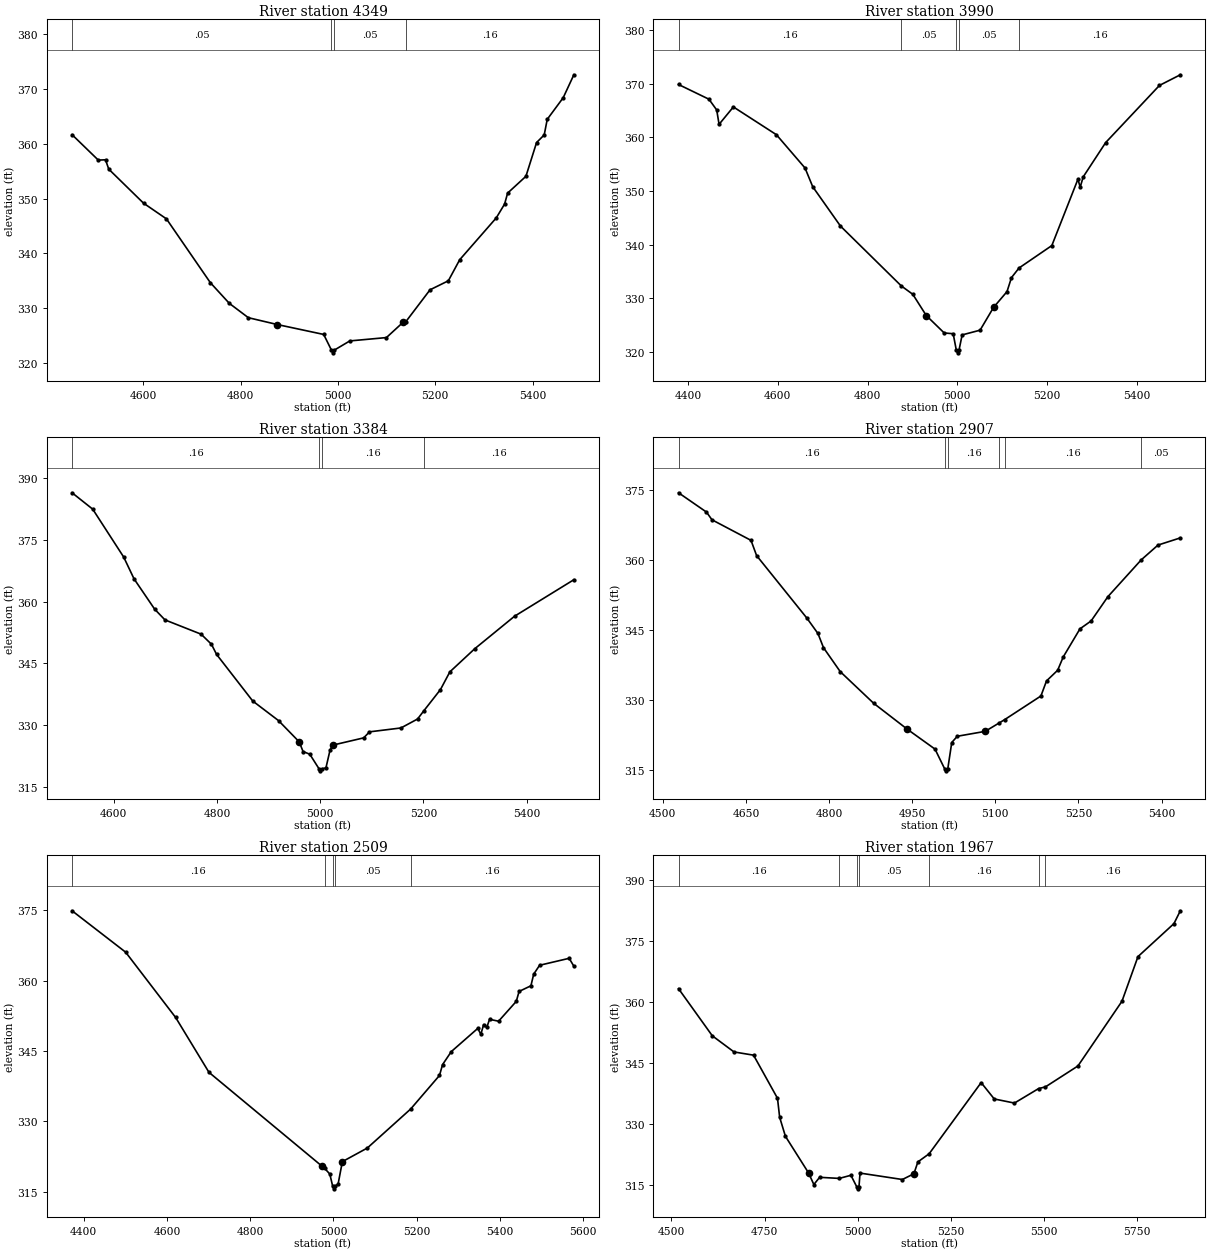
Type RM Length L Ch R = 1 ,4349    ,359,359,359
BEGIN DESCRIPTION:
UNT 158 IN BUCR 7.0
END DESCRIPTION:
XS GIS Cut Line= 3
      3660399.58     10494610.18      3660899.61     10494810.19
      3661349.62     10495010.19
#Sta/Elev= 30
  4453.8  361.63  4507.7     357  4522.5  357.06  4529.2  355.35  4600.6  349.16
  4647.7   346.3  4737.9  334.68  4776.9  330.91    4816   328.3  4875.2  327.06
  4970.8  325.25  4986.7   322.4  4989.4   321.9  4992.7   322.4  5024.5  324.07
  5099.7  324.68  5134.6  327.52  5139.8   327.6  5189.3  333.38  5226.9  335.02
  5250.2  338.85  5325.4  346.48  5342.5     349  5348.7  350.99  5386.3  354.05
  5408.2   360.2  5423.9  361.59  5430.1  364.43  5462.9  368.36  5484.8  372.54
#Mann= 4 ,-1 , 0
  4453.8     .05       0  4986.7     .03       0  4992.7     .05       0
  5139.8     .16       0
Bank Sta=4875.2,5134.6
XS Rating Curve= 0 ,0
Exp/Cntr=0.3,0.1

Type RM Length L Ch R = 1 ,3990    ,606,606,606
BEGIN DESCRIPTION:
UNT 158 IN BUCR 6.0
END DESCRIPTION:
XS GIS Cut Line= 3
      3660235.11     10495048.41      3660582.35     10495161.26
      3661336.08      10495152.6
#Sta/Elev= 30
  4378.6  369.85  4446.4  367.11  4463.7  365.11    4469  362.43  4500.9  365.67
  4596.8   360.5  4660.7  354.29  4677.8  350.81  4739.7  343.48  4875.5  332.32
    4901  330.77    4931  326.82    4971  323.57    4991  323.43    4998  320.37
  5000.7  319.87    5004  320.37    5011  323.21    5051  324.09    5081  328.33
    5111  331.27    5121  333.88  5137.8  335.67    5211  339.85  5269.2  352.21
  5274.2  350.72    5281  352.65    5331  359.03    5451  369.68  5497.5  371.66
#Mann= 5 ,-1 , 0
  4378.6     .16       0  4875.5     .05       0    4998     .03       0
    5004     .05       0  5137.8     .16       0
Bank Sta=4931,5081
XS Rating Curve= 0 ,0
Exp/Cntr=0.3,0.1

Type RM Length L Ch R = 1 ,3384    ,477,477,477
BEGIN DESCRIPTION:
UNT 158 IN BUCR 5.0
END DESCRIPTION:
XS GIS Cut Line= 3
      3660499.57     10495710.19      3660949.61     10495710.19
      3661449.65     10495560.18
#Sta/Elev= 30
  4519.2  386.37  4559.2   382.4  4619.2  370.79  4639.2  365.52  4679.2  358.16
  4699.2  355.56  4769.2   352.1  4789.2  349.66  4799.2  347.19  4869.2   335.9
  4919.2  331.15  4959.2  326.01  4966.7  323.66  4979.7  323.01  4997.6  319.48
  5000.3  318.98  5003.6  319.48    5011  319.69  5018.8  323.92  5024.1  325.21
  5084.1  326.97  5095.4  328.43  5156.3  329.37  5188.5  331.54  5200.9  333.57
  5232.9  338.68  5251.1  342.97    5299  348.54  5376.4  356.45  5491.3   365.3
#Mann= 4 ,-1 , 0
  4519.2     .16       0  4997.6     .03       0  5003.6     .16       0
  5200.9     .16       0
Bank Sta=4959.2,5024.1
XS Rating Curve= 0 ,0
Exp/Cntr=0.3,0.1

Type RM Length L Ch R = 1 ,2907    ,398,398,398
BEGIN DESCRIPTION:
UNT 158 IN BUCR 4.0
END DESCRIPTION:
XS GIS Cut Line= 3
      3660699.56     10496110.19      3661149.61     10496060.19
      3661599.62     10496110.19
#Sta/Elev= 30
  4528.3  374.48  4578.7  370.34  4588.7  368.68  4659.1  364.27  4669.2     361
  4759.8  347.61  4779.9  344.29  4789.9  341.25  4820.1  336.11  4880.5  329.31
  4940.9  323.77  4991.2  319.48  5008.3  315.32  5011.1  314.82  5014.3  315.32
  5021.4   320.9  5031.4  322.24  5081.7  323.29  5107.2  325.11  5116.9  325.81
  5182.3  330.88  5192.4  334.11  5212.5   336.4  5222.6  339.26  5252.8  345.29
  5272.9  346.98  5303.1  352.18  5363.2  360.07  5393.6  363.26  5433.9   364.8
#Mann= 6 ,-1 , 0
  4528.3     .16       0  5008.3     .07       0  5014.3     .16       0
  5107.2     .05       0  5116.9     .16       0  5363.2     .05       0
Bank Sta=4940.9,5081.7
XS Rating Curve= 0 ,0
Exp/Cntr=0.3,0.1

Type RM Length L Ch R = 1 ,2509    ,542,542,542
BEGIN DESCRIPTION:
UNT 158 IN BUCR 3.0
END DESCRIPTION:
XS GIS Cut Line= 3
      3660591.01     10496463.35      3661433.04     10496419.94
      3661702.16     10496176.86
#Sta/Elev= 30
  4371.8  374.86  4500.6  366.04  4620.7  352.14  4700.8  340.46  4971.2  320.57
  4978.6  320.04  4991.2   318.8  4998.2  316.16    5001  315.66  5004.2  316.16
  5011.2  316.74  5021.3  321.45  5081.3  324.35  5185.5  332.66  5254.7   339.8
  5262.1  342.11  5283.1  344.88  5346.6  349.81  5354.1  348.57  5360.8  350.64
  5368.3  350.02    5375  351.75  5396.7  351.35  5439.2  355.57    5446  357.69
  5474.4  358.89  5481.1  361.37  5495.3  363.26  5566.3  364.74  5577.6  363.06
#Mann= 5 ,-1 , 0
  4371.8     .16       0  4978.6     .05       0  4998.2     .03       0
  5004.2     .05       0  5185.5     .16       0
Bank Sta=4971.2,5021.3
XS Rating Curve= 0 ,0
Exp/Cntr=0.3,0.1

Type RM Length L Ch R = 1 ,1967    ,468,468,468
BEGIN DESCRIPTION:
UNT 158 IN BUCR 2.0
END DESCRIPTION:
XS GIS Cut Line= 3
      3660677.84     10496567.53      3660834.08     10496827.93
      3661805.44     10497209.53
#Sta/Elev= 30
  4518.9  363.32  4609.6  351.71  4667.9  347.73  4720.3  346.94  4784.6  336.32
  4790.4  331.64  4805.9  326.95  4867.9  317.95  4882.2  315.07  4897.7  316.85
  4950.5  316.58  4981.7  317.35  4997.4  314.51  5000.2  314.01  5003.4  314.51
  5006.2  317.89  5119.9  316.31  5150.8  317.72  5161.6  320.65  5191.8  322.65
  5331.4  340.18  5366.6  336.15  5420.8  335.14  5485.5   338.7  5504.1  339.13
  5591.3  344.28  5709.5  360.22  5752.5  371.22  5849.1  379.35  5866.2  382.51
#Mann= 7 ,-1 , 0
  4518.9     .16       0  4950.5     .05       0  4997.4     .03       0
  5003.4     .05       0  5191.8     .16       0  5485.5     .05       0
  5504.1     .16       0
Bank Sta=4867.9,5150.8
XS Rating Curve= 0 ,0
Exp/Cntr=0.3,0.1

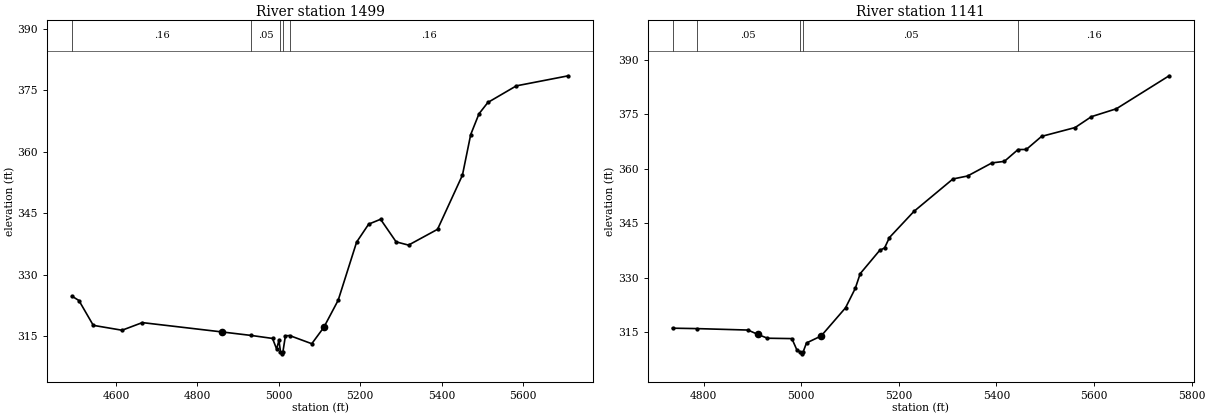
Type RM Length L Ch R = 1 ,1499    ,358,358,358
BEGIN DESCRIPTION:
Mapping XS b200e155
END DESCRIPTION:
XS GIS Cut Line= 4
      3660460.37     10496965.93      3660599.27     10497146.51
      3661050.66     10497403.45      3661515.28      10497493.6
#Sta/Elev= 30
  4491.3  324.74  4508.8  323.66  4544.1   317.6  4614.8  316.41  4664.6  318.27
  4860.7  315.99    4932  315.14  4984.6  314.41  4994.7  311.83  5000.4  313.94
  5004.2  311.15  5006.9  310.65  5010.2  311.15  5016.3  315.04  5026.4  315.12
  5081.1  313.12  5110.7  317.11    5146  323.73  5191.3  337.91  5220.9  342.29
  5250.2  343.48  5288.4  337.97  5318.9  337.18  5390.2  341.03  5451.4  354.25
  5471.7  364.14  5492.1  369.22  5513.9  371.98  5583.8  376.03  5711.8  378.49
#Mann= 5 ,-1 , 0
  4491.3     .16       0    4932     .05       0  5004.2     .03       0
  5010.2     .05       0  5026.4     .16       0
Bank Sta=4860.7,5110.7
XS Rating Curve= 0 ,0
Exp/Cntr=0.3,0.1

Type RM Length L Ch R = 1 ,1141    ,0,0,0
BEGIN DESCRIPTION:
UNT 158 IN BUCR 1.0
END DESCRIPTION:
XS GIS Cut Line= 4
      3660647.87     10497521.48      3660724.27     10497625.67
      3661272.88     10497625.67      3661605.43     10497556.39
#Sta/Elev= 30
  4736.3  316.18  4785.5  316.07  4890.8  315.67  4910.8  314.49  4930.8  313.42
  4980.8  313.32  4990.8  310.29  4997.8  309.63  5000.6  309.13  5003.8  309.63
  5010.8  312.12  5040.8  314.04  5090.8  321.79  5110.8  327.15  5120.8  331.17
  5160.8  337.58  5170.8  338.25  5180.8  341.11  5230.8  348.27  5310.8   357.2
  5340.8  358.02  5390.8  361.62  5416.2  362.04  5444.2  365.29  5461.1  365.31
  5492.5  368.91  5561.2  371.34  5594.6  374.33  5645.7   376.5  5753.8  385.57
#Mann= 5 ,-1 , 0
  4736.3     .16       0  4785.5     .05       0  4997.8     .03       0
  5003.8     .05       0  5444.2     .16       0
Bank Sta=4910.8,5040.8
XS Rating Curve= 0 ,0
Exp/Cntr=0.3,0.1

Chan Stop Cuts=-1
Use User Specified Reach Order=0
Composite Channel Slope=5