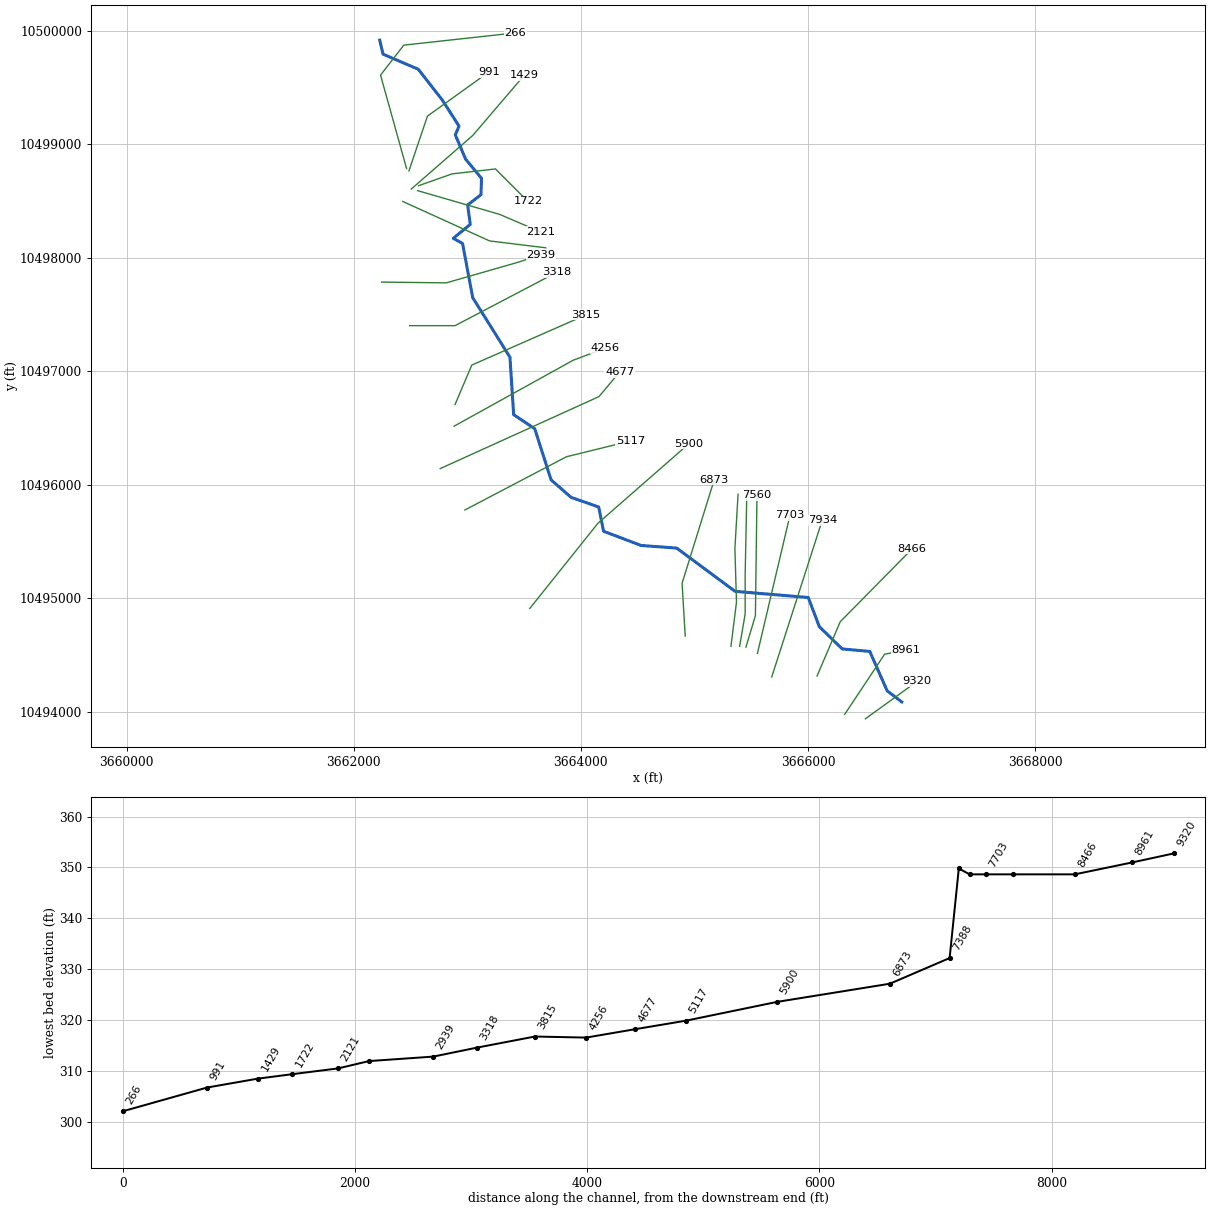
--- UNT 159 IN BUCR.prj (project) ---

Proj Title=UNT 159 IN BUCR Base Level Engineering
Current Plan=p01
Default Exp/Contr=0.3,0.1
English Units
Geom File=g01
Flow File=f01
Plan File=p01
BEGIN DESCRIPTION:
UNT 159 IN BUCR
END DESCRIPTION:

--- UNT 159 IN BUCR.p01 (plan) ---

Plan Title=Multiple Run
Short Identifier=Multiple
Geom File=g01
Flow File=f01
Subcritical Flow
K Sum by GR= 0
Std Step Tol= 0.01
Critical Tol= 0.01
Num of Std Step Trials= 20
Max Error Tol= 0.3
Flow Tol Ratio= 0.001
Split Flow NTrial= 30
Split Flow Tol= 0.02
Split Flow Ratio= 0.02
Log Output Level= 0
Friction Slope Method= 1
Unsteady Friction Slope Method= 2
Unsteady Bridges Friction Slope Method= 1
Parabolic Critical Depth
Global Vel Dist=  1 , 1 , 1
Global Log Level= 0
CheckData=True
Encroach Param= -1, 0, 0, 0
BEGIN DESCRIPTION:
Multiple Run
END DESCRIPTION:

--- UNT 159 IN BUCR.f01 (steady flow) ---

Flow Title=Multiple
Number of Profiles=7
Profile Names=10-year,25-year,50-year,1pct_min,100-year,1pct_plu,500-year
River Rch & RM= UNT 159 IN BUCR,Reach-1,9320
     602     830    1023     927    1253    1695    1890
River Rch & RM= UNT 159 IN BUCR,Reach-1,7934
     957    1355    1697    1561    2111    2855    3284
River Rch & RM= UNT 159 IN BUCR,Reach-1,5900
    1079    1525    1909    1753    2371    3206    3676
Boundary for River Rch & Prof#=UNT 159 IN BUCR,Reach-1,1
Up Type=0
Dn Type=3
Dn Slope=0.005
Boundary for River Rch & Prof#=UNT 159 IN BUCR,Reach-1,2
Up Type=0
Dn Type=3
Dn Slope=0.005
Boundary for River Rch & Prof#=UNT 159 IN BUCR,Reach-1,3
Up Type=0
Dn Type=3
Dn Slope=0.005
Boundary for River Rch & Prof#=UNT 159 IN BUCR,Reach-1,4
Up Type=0
Dn Type=3
Dn Slope=0.005
Boundary for River Rch & Prof#=UNT 159 IN BUCR,Reach-1,5
Up Type=0
Dn Type=3
Dn Slope=0.005
Boundary for River Rch & Prof#=UNT 159 IN BUCR,Reach-1,6
Up Type=0
Dn Type=3
Dn Slope=0.005
Boundary for River Rch & Prof#=UNT 159 IN BUCR,Reach-1,7
Up Type=0
Dn Type=3
Dn Slope=0.005

--- UNT 159 IN BUCR.g01 (geometry) ---

Geom Title=Existing Conditions

River Reach=UNT 159 IN BUCR,Reach-1
Reach XY= 30
      3666826.00     10494087.00      3666697.50     10494184.00
      3666544.00     10494532.00      3666301.00     10494554.00
      3666099.50     10494750.00      3666002.25     10495007.00
      3665357.75     10495061.00      3664843.50     10495442.00
      3664530.50     10495465.00      3664199.50     10495590.00
      3664156.50     10495804.00      3663913.25     10495889.00
      3663737.25     10496043.00      3663593.25     10496493.00
      3663407.75     10496617.00      3663375.00     10497123.00
      3663047.25     10497647.00      3662957.50     10498125.00
      3662876.00     10498170.00      3663025.50     10498293.00
      3663002.25     10498464.00      3663120.00     10498554.00
      3663124.50     10498699.00      3662984.75     10498867.00
      3662893.75     10499081.00      3662926.50     10499158.00
      3662780.75     10499386.00      3662567.75     10499659.00
      3662257.00     10499792.00      3662228.00     10499916.00

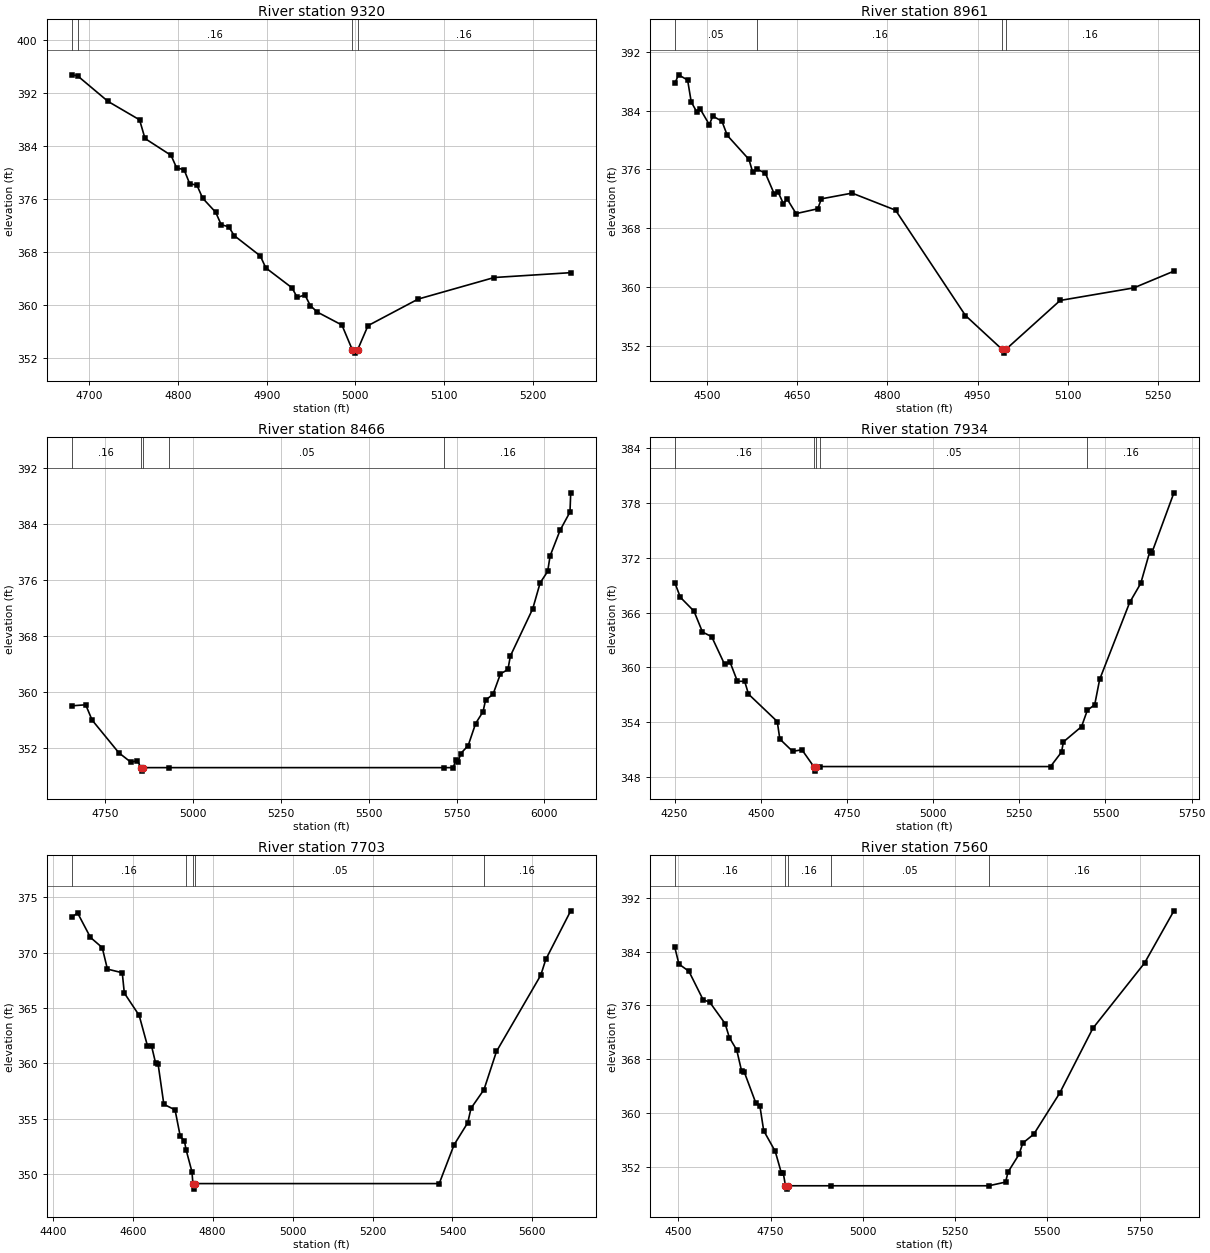
Type RM Length L Ch R = 1,9320,359,359,359
BEGIN DESCRIPTION:
UNT 159 IN BUCR 16.0
END DESCRIPTION:
XS GIS Cut Line= 2
      3666505.18     10493938.41      3666960.93     10494268.28
#Sta/Elev= 30
  4680.1  394.68  4686.8  394.53  4721.1  390.68  4756.7  387.90  4762.8  385.09
  4792.2  382.55  4798.4  380.68  4806.9  380.38  4813.1  378.31  4821.4  378.04
  4827.8  376.10  4842.5  373.98  4848.7  372.11  4857.2  371.79  4863.4  370.46
  4892.8  367.40  4899.0  365.60  4928.4  362.61  4934.5  361.15  4943.1  361.53
  4949.2  359.91  4957.1  358.94  4984.8  356.99  4996.5  353.26  4999.3  352.76
  5002.5  353.26  5014.2  356.90  5070.7  360.90  5156.5  364.15  5242.7  364.88
#Mann=4,-1,0
  4680.1    0.05       0  4686.8    0.16       0  4996.5    0.07       0
  5002.5    0.16       0
Bank Sta=4996.5,5002.5
Exp/Cntr=0.3,0.1

Type RM Length L Ch R = 1,8961,495,495,495
BEGIN DESCRIPTION:
Mapping XS 9ca50c11
END DESCRIPTION:
XS GIS Cut Line= 3
      3666322.88     10493977.44      3666674.47     10494506.99
      3666864.98     10494545.96
#Sta/Elev= 30
  4446.4  387.70  4452.6  388.87  4467.7  388.16  4473.7  385.18  4482.7  383.86
  4488.7  384.21  4503.7  382.10  4509.7  383.25  4524.8  382.55  4533.7  380.62
  4569.7  377.36  4575.9  375.63  4582.8  376.03  4596.9  375.50  4612.0  372.62
  4618.0  372.95  4627.0  371.33  4633.0  372.00  4648.1  369.98  4684.2  370.64
  4690.2  371.99  4741.3  372.77  4813.5  370.45  4929.8  356.11  4990.9  351.49
  4993.6  350.99  4996.9  351.49  5087.3  358.16  5209.8  359.87  5276.5  362.15
#Mann=4,-1,0
  4446.4    0.05       0  4582.8    0.16       0  4990.9    0.07       0
  4996.9    0.16       0
Bank Sta=4990.9,4996.9
Exp/Cntr=0.3,0.1

Type RM Length L Ch R = 1,8466,532,532,532
BEGIN DESCRIPTION:
Mapping XS 441ab3c5
END DESCRIPTION:
XS GIS Cut Line= 3
      3666079.85     10494316.02      3666283.84     10494793.45
      3666917.24     10495435.52
#Sta/Elev= 30
  4654.0  357.99  4694.1  358.14  4712.2  355.96  4788.5  351.27  4823.0  349.92
  4841.1  350.16  4851.3  349.15  4854.0  348.65  4857.3  349.15  4932.0  349.15
  5714.5  349.15  5740.7  349.15  5747.7  350.26  5754.8  350.01  5761.8  351.16
  5783.1  352.30  5804.3  355.46  5825.5  357.16  5832.6  358.81  5853.8  359.63
  5875.0  362.56  5896.3  363.19  5903.3  365.12  5967.0  371.88  5988.1  375.59
  6009.4  377.21  6016.4  379.43  6044.7  383.09  6073.0  385.71  6075.1  388.46
#Mann=5,-1,0
  4654.0    0.16       0  4851.3   0.035       0  4857.3    0.16       0
  4932.0    0.05       0  5714.5    0.16       0
Bank Sta=4851.3,4857.3
Exp/Cntr=0.3,0.1

Type RM Length L Ch R = 1,7934,231,231,231
BEGIN DESCRIPTION:
Mapping XS 95934aee
END DESCRIPTION:
XS GIS Cut Line= 2
      3665680.53     10494307.30      3666124.61     10495685.20
#Sta/Elev= 30
  4250.8  369.28  4266.8  367.68  4306.4  366.16  4331.0  363.88  4357.8  363.36
  4395.1  360.35  4411.4  360.54  4432.4  358.48  4453.5  358.48  4464.5  357.08
  4548.0  354.08  4555.4  352.16  4592.7  350.81  4619.5  350.99  4653.8  349.15
  4656.6  348.65  4659.8  349.15  4673.1  349.15  5340.6  349.15  5372.6  350.74
  5378.0  351.85  5430.6  353.52  5447.4  355.31  5468.8  355.92  5483.1  358.68
  5570.2  367.11  5602.3  369.20  5629.1  372.75  5634.4  372.53  5698.5  379.11
#Mann=5,-1,0
  4250.8    0.16       0  4653.8   0.033       0  4659.8    0.16       0
  4673.1    0.05       0  5447.4    0.16       0
Bank Sta=4653.8,4659.8
Exp/Cntr=0.3,0.1

Type RM Length L Ch R = 1,7703,143,143,143
BEGIN DESCRIPTION:
Mapping XS 4eba91a1
END DESCRIPTION:
XS GIS Cut Line= 2
      3665554.67     10494515.64      3665841.13     10495730.94
#Sta/Elev= 30
  4447.2  373.18  4462.1  373.58  4494.3  371.37  4523.8  370.45  4536.7  368.51
  4573.9  368.18  4579.0  366.35  4616.2  364.33  4636.8  361.60  4647.1  361.58
  4657.4  360.01  4663.7  359.90  4677.9  356.31  4706.0  355.80  4719.0  353.41
  4729.3  353.01  4733.8  352.17  4748.4  350.19  4750.5  349.15  4753.3  348.65
  4756.5  349.15  5366.8  349.15  5404.0  352.65  5438.2  354.64  5446.4  355.95
  5478.8  357.63  5510.1  361.08  5620.9  367.96  5633.4  369.38  5695.8  373.77
#Mann=5,-1,0
  4447.2    0.16       0  4733.8    0.05       0  4750.5   0.033       0
  4756.5    0.05       0  5478.8    0.16       0
Bank Sta=4750.5,4756.5
Exp/Cntr=0.3,0.1

Type RM Length L Ch R = 1,7560,93,93,93
BEGIN DESCRIPTION:
UNT 159 IN BUCR 15.0
END DESCRIPTION:
XS GIS Cut Line= 3
      3665453.37     10494569.49      3665536.70     10494847.27
      3665550.59     10495909.77
#Sta/Elev= 30
  4490.6  384.65  4501.8  382.16  4528.8  381.09  4567.1  376.87  4585.3  376.48
  4627.0  373.29  4638.4  371.22  4658.4  369.37  4671.5  366.26  4679.3  366.02
  4710.6  361.41  4721.0  361.10  4731.5  357.35  4762.8  354.27  4779.5  351.03
  4784.6  351.03  4790.5  349.15  4793.3  348.65  4796.5  349.15  4913.5  349.15
  5341.8  349.15  5387.1  349.70  5393.6  351.19  5423.6  353.83  5433.6  355.50
  5463.6  356.84  5533.6  362.94  5623.6  372.60  5763.6  382.31  5843.2  390.09
#Mann=5,-1,0
  4490.6    0.16       0  4790.5   0.033       0  4796.5    0.16       0
  4913.5    0.05       0  5341.8    0.16       0
Bank Sta=4790.5,4796.5
Exp/Cntr=0.3,0.1

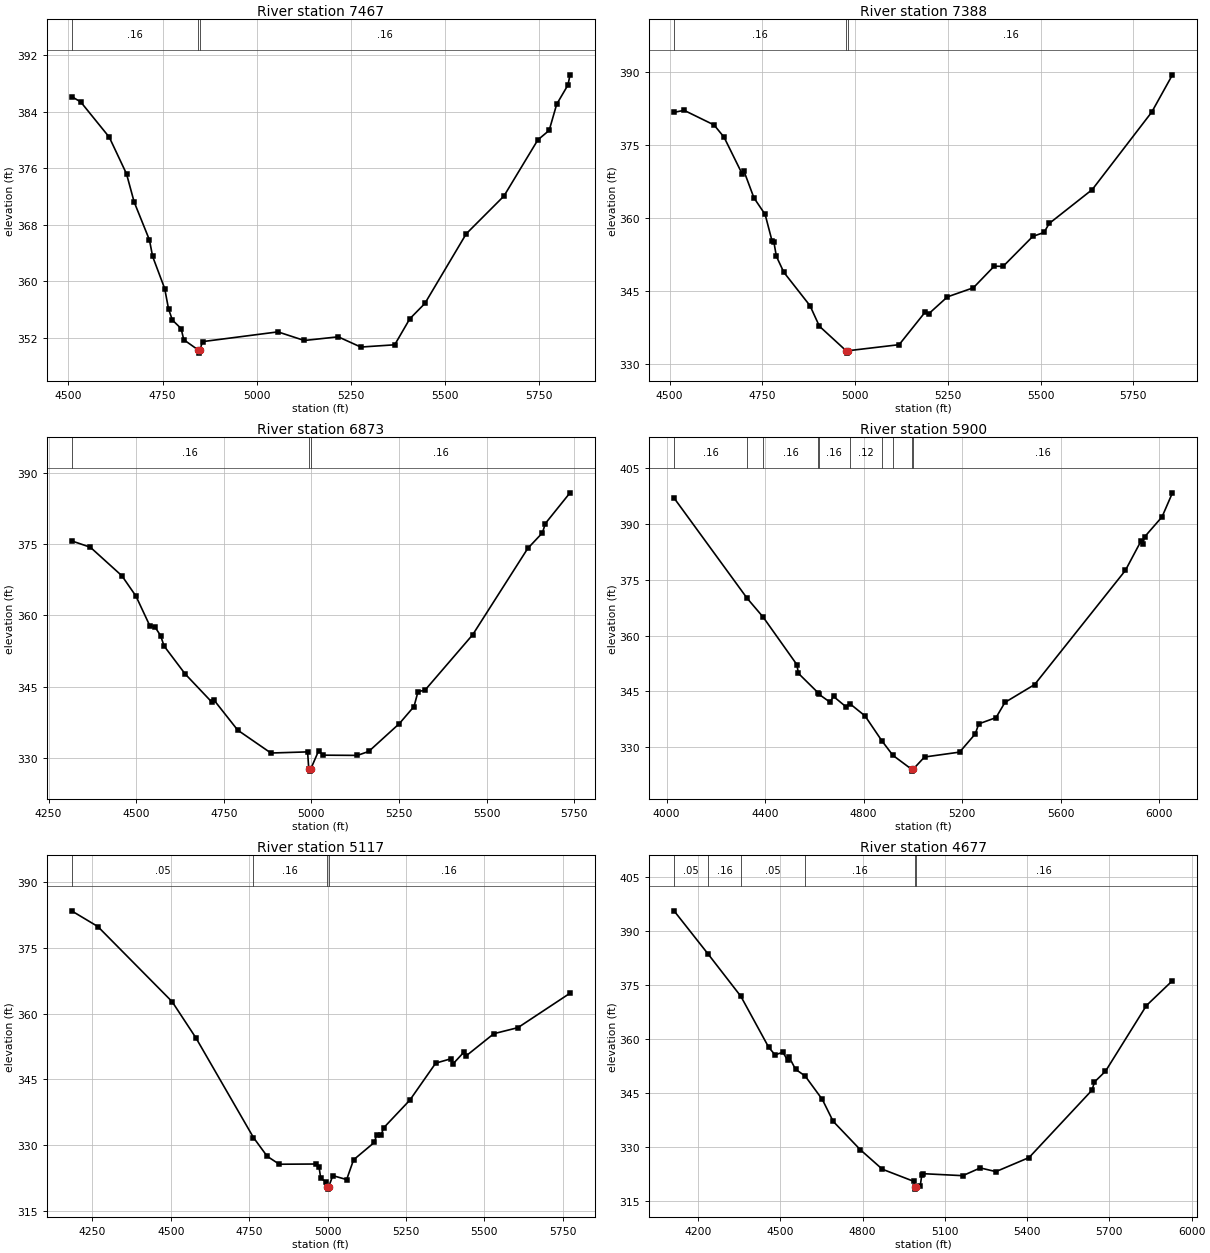
Type RM Length L Ch R = 1,7467,79,79,79
BEGIN DESCRIPTION:
UNT 159 IN BUCR 14.0
END DESCRIPTION:
XS GIS Cut Line= 4
      3665397.82     10494576.47      3665446.42     10494861.16
      3665446.42     10495201.44      3665460.31     10495895.51
#Sta/Elev= 30
  4508.6  386.14  4532.7  385.39  4608.6  380.39  4654.4  375.20  4674.7  371.21
  4715.3  365.83  4723.8  363.49  4755.8  358.94  4766.0  356.06  4776.1  354.49
  4799.4  353.28  4806.4  351.70  4843.4  350.30  4846.2  349.80  4849.4  350.30
  4856.4  351.43  5056.4  352.81  5126.4  351.59  5216.5  352.11  5276.5  350.66
  5366.5  350.98  5406.5  354.66  5446.5  356.83  5556.5  366.71  5656.5  372.05
  5746.6  380.01  5776.6  381.35  5796.6  385.06  5826.6  387.79  5831.9  389.22
#Mann=3,-1,0
  4508.6    0.16       0  4843.4    0.07       0  4849.4    0.16       0
Bank Sta=4843.4,4849.4
Exp/Cntr=0.3,0.1

Type RM Length L Ch R = 1,7388,515,515,515
BEGIN DESCRIPTION:
UNT 159 IN BUCR 13.0
END DESCRIPTION:
XS GIS Cut Line= 4
      3665321.43     10494576.46      3665370.03     10494965.33
      3665356.15     10495437.55      3665383.88     10495915.93
#Sta/Elev= 30
  4512.1  381.79  4539.4  382.20  4620.0  379.19  4646.9  376.68  4695.6  369.14
  4700.6  369.70  4727.5  364.19  4757.7  360.77  4776.2  355.35  4781.3  355.08
  4788.0  352.15  4808.1  348.87  4878.7  341.99  4903.9  337.77  4975.9  332.73
  4978.6  332.23  4981.9  332.73  5118.9  333.97  5189.0  340.67  5199.0  340.35
  5249.0  343.81  5319.0  345.68  5375.2  350.13  5399.1  350.08  5479.2  356.26
  5509.3  357.06  5523.5  358.92  5639.5  365.90  5799.8  381.84  5855.6  389.51
#Mann=3,-1,0
  4512.1    0.16       0  4975.9    0.07       0  4981.9    0.16       0
Bank Sta=4975.9,4981.9
Exp/Cntr=0.3,0.1

Type RM Length L Ch R = 1,6873,973,973,973
BEGIN DESCRIPTION:
Mapping XS c4d1321b
END DESCRIPTION:
XS GIS Cut Line= 3
      3664918.64     10494666.75      3664890.87     10495131.99
      3665174.57     10496045.37
#Sta/Elev= 30
  4315.7  375.65  4369.2  374.31  4459.4  368.29  4499.5  364.01  4539.5  357.70
  4552.9  357.60  4569.6  355.73  4579.6  353.53  4639.7  347.65  4716.9  341.64
  4721.9  342.17  4789.8  335.82  4884.6  331.00  4989.3  331.24  4992.6  327.69
  4995.4  327.19  4998.6  327.69  5020.7  331.46  5033.4  330.55  5131.1  330.50
  5163.7  331.33  5251.1  337.19  5293.0  340.79  5304.4  343.92  5324.4  344.23
  5460.5  355.90  5617.6  374.06  5659.5  377.34  5667.8  379.30  5738.2  385.76
#Mann=3,-1,0
  4315.7    0.16       0  4992.6    0.07       0  4998.6    0.16       0
Bank Sta=4992.6,4998.6
Exp/Cntr=0.3,0.1

Type RM Length L Ch R = 1,5900,783,783,783
BEGIN DESCRIPTION:
UNT 159 IN BUCR 12.0
END DESCRIPTION:
XS GIS Cut Line= 3
      3663549.63     10494910.22      3664149.61     10495660.19
      3664949.58     10496360.16
#Sta/Elev= 30
  4030.2  396.92  4327.0  370.00  4392.0  364.95  4528.8  352.21  4535.2  349.85
  4614.2  344.70  4616.8  344.33  4663.3  342.13  4677.7  343.66  4727.3  340.94
  4743.9  341.73  4805.7  338.43  4873.6  331.79  4918.7  327.86  4994.7  324.12
  4997.5  323.62  5000.7  324.12  5047.1  327.41  5189.5  328.72  5253.1  333.60
  5267.3  336.30  5337.5  337.98  5373.6  342.06  5494.1  346.85  5862.4  377.46
  5926.0  385.37  5933.6  384.48  5940.2  386.45  6011.4  391.85  6053.6  398.30
#Mann=10,-1,0
  4030.2    0.16       0  4327.0    0.12       0  4392.0    0.16       0
  4614.2    0.12       0  4616.8    0.16       0  4743.9    0.12       0
  4873.6    0.05       0  4918.7    0.16       0  4994.7    0.07       0
  5000.7    0.16       0
Bank Sta=4994.7,5000.7
Exp/Cntr=0.3,0.1

Type RM Length L Ch R = 1,5117,440,440,440
BEGIN DESCRIPTION:
UNT 159 IN BUCR 11.0
END DESCRIPTION:
XS GIS Cut Line= 3
      3662978.20     10495777.59      3663872.28     10496246.33
      3664435.46     10496384.96
#Sta/Elev= 30
  4183.4  383.43  4267.0  379.85  4504.0  362.71  4580.2  354.41  4763.5  331.70
  4807.2  327.43  4845.7  325.62  4964.1  325.67  4972.4  325.07  4978.0  322.38
  4994.5  321.63  4997.1  320.44  4999.9  319.94  5003.1  320.44  5016.5  323.02
  5060.6  322.12  5082.7  326.63  5148.9  330.60  5156.0  332.21  5170.9  332.37
  5178.6  333.92  5262.2  340.25  5344.6  348.68  5394.1  349.70  5399.3  348.47
  5435.7  351.28  5440.8  350.29  5530.0  355.40  5606.9  356.78  5772.9  364.63
#Mann=4,-1,0
  4183.4    0.05       0  4763.5    0.16       0  4997.1    0.07       0
  5003.1    0.16       0
Bank Sta=4997.1,5003.1
Exp/Cntr=0.3,0.1

Type RM Length L Ch R = 1,4677,421,421,421
BEGIN DESCRIPTION:
UNT 159 IN BUCR 10.0
END DESCRIPTION:
XS GIS Cut Line= 3
      3662761.14     10496142.16      3664158.74     10496775.85
      3664341.05     10496992.89
#Sta/Elev= 30
  4111.9  395.62  4235.8  383.65  4355.7  371.85  4457.2  357.69  4480.3  355.59
  4508.8  356.30  4526.4  354.10  4531.9  354.94  4555.0  351.58  4590.1  349.71
  4652.9  343.18  4692.2  337.12  4791.0  329.24  4871.6  323.80  4987.1  320.40
  4989.6  318.76  4992.3  318.26  4995.6  318.76  5010.2  319.24  5015.6  322.19
  5021.5  322.55  5165.2  322.00  5228.9  324.15  5286.1  323.13  5407.0  327.04
  5636.4  345.76  5645.6  348.05  5685.7  351.03  5835.0  369.29  5929.9  376.20
#Mann=6,-1,0
  4111.9    0.05       0  4235.8    0.16       0  4355.7    0.05       0
  4590.1    0.16       0  4989.6    0.07       0  4995.6    0.16       0
Bank Sta=4989.6,4995.6
Exp/Cntr=0.3,0.1

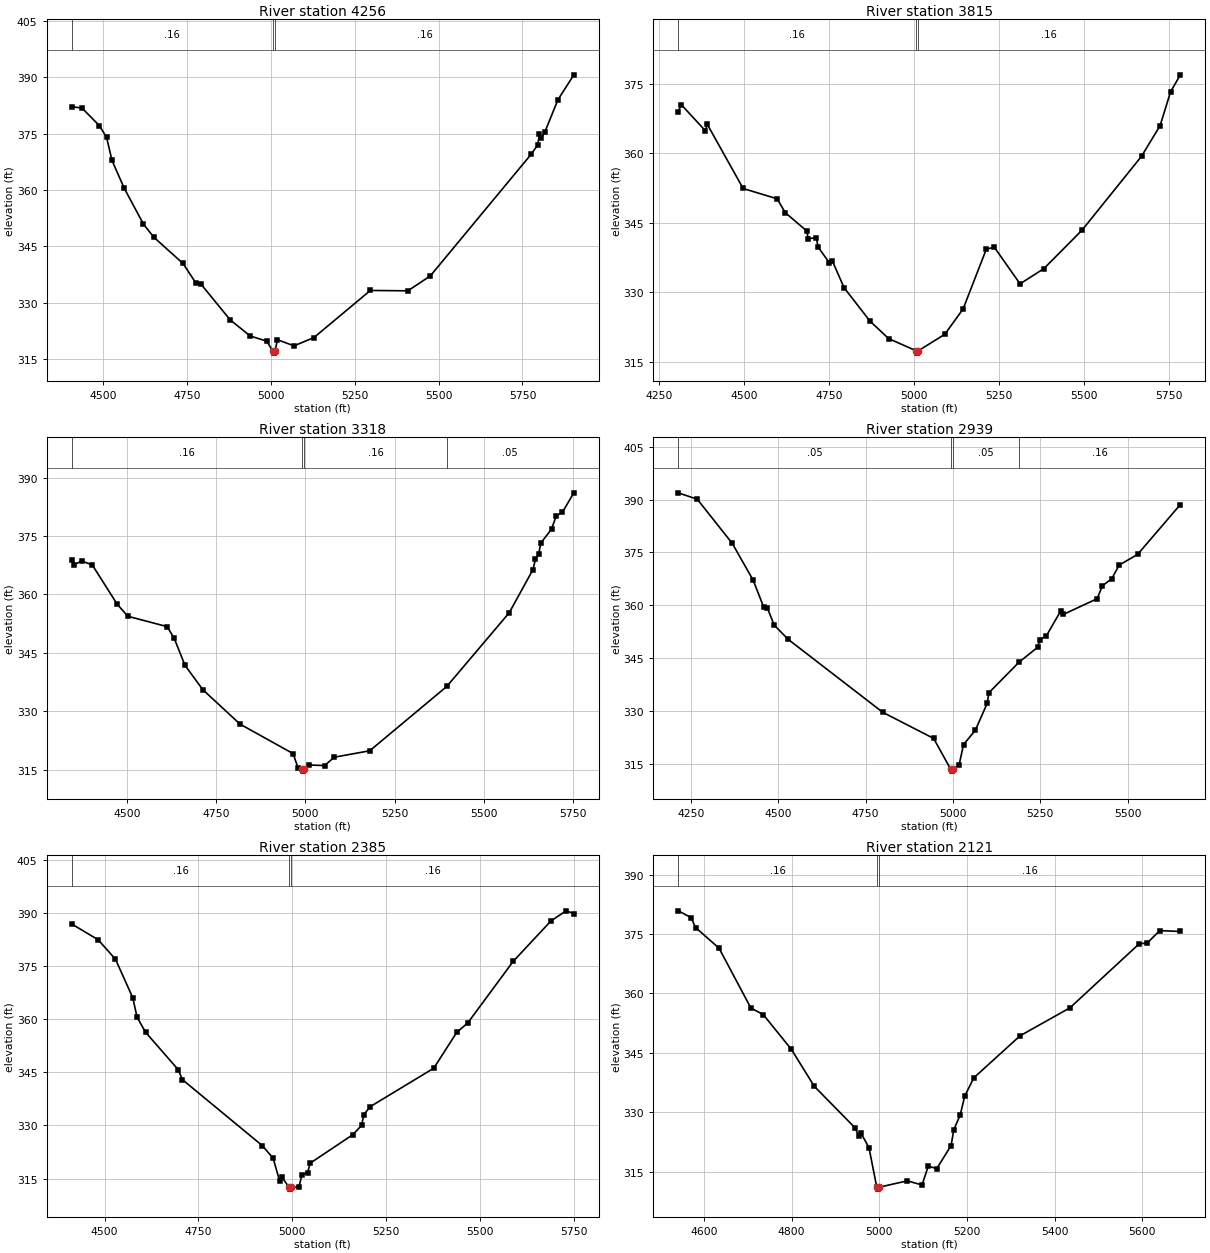
Type RM Length L Ch R = 1,4256,441,441,441
BEGIN DESCRIPTION:
UNT 159 IN BUCR 9.0
END DESCRIPTION:
XS GIS Cut Line= 3
      3662882.73     10496515.45      3663933.04     10497097.03
      3664210.78     10497201.18
#Sta/Elev= 30
  4406.1  382.21  4436.8  381.82  4488.2  377.18  4510.0  374.02  4526.0  367.91
  4562.6  360.49  4619.7  350.97  4650.8  347.46  4737.8  340.48  4775.6  335.36
  4791.2  335.00  4878.6  325.46  4938.2  321.18  4987.4  319.81  5006.1  317.12
  5008.9  316.62  5012.1  317.12  5019.5  320.20  5068.7  318.55  5128.2  320.76
  5296.5  333.30  5408.4  333.20  5475.2  337.16  5775.8  369.52  5795.3  371.96
  5800.7  374.82  5806.0  373.79  5816.6  375.40  5855.9  384.06  5903.3  390.68
#Mann=3,-1,0
  4406.1    0.16       0  5006.1    0.07       0  5012.1    0.16       0
Bank Sta=5006.1,5012.1
Exp/Cntr=0.3,0.1

Type RM Length L Ch R = 1,3815,497,497,497
BEGIN DESCRIPTION:
UNT 159 IN BUCR 8.0
END DESCRIPTION:
XS GIS Cut Line= 3
      3662891.39     10496706.43      3663038.94     10497053.63
      3664043.95     10497495.48
#Sta/Elev= 30
  4306.9  368.90  4315.8  370.46  4386.7  364.81  4392.2  366.21  4497.6  352.36
  4597.6  350.13  4621.3  347.15  4684.1  343.21  4689.2  341.52  4712.5  341.74
  4718.0  339.70  4750.4  336.38  4759.2  336.82  4794.1  330.95  4870.6  323.71
  4925.2  319.96  5006.1  317.33  5008.8  316.83  5012.1  317.33  5090.0  320.89
  5143.7  326.34  5212.2  339.29  5235.6  339.68  5311.1  331.78  5381.1  335.07
  5493.2  343.36  5668.0  359.31  5722.6  365.92  5753.2  373.19  5782.0  376.89
#Mann=3,-1,0
  4306.9    0.16       0  5006.1    0.07       0  5012.1    0.16       0
Bank Sta=5006.1,5012.1
Exp/Cntr=0.3,0.1

Type RM Length L Ch R = 1,3318,379,379,379
BEGIN DESCRIPTION:
UNT 159 IN BUCR 7.0
END DESCRIPTION:
XS GIS Cut Line= 3
      3662492.11     10497400.85      3662891.37     10497400.85
      3663785.04     10497869.37
#Sta/Elev= 30
  4344.6  368.89  4352.1  367.67  4372.1  368.60  4402.1  367.59  4472.1  357.48
  4502.1  354.40  4612.1  351.75  4632.1  348.71  4662.1  341.83  4712.1  335.57
  4816.5  326.73  4965.3  319.16  4979.0  315.57  4990.0  315.16  4992.8  314.66
  4996.0  315.16  5009.4  316.24  5053.6  316.09  5081.3  318.24  5180.3  319.88
  5396.4  336.39  5571.7  355.32  5637.9  366.33  5645.2  369.01  5654.3  370.35
  5659.9  373.14  5690.3  376.79  5704.0  380.26  5720.5  381.06  5752.9  386.09
#Mann=4,-1,0
  4344.6    0.16       0  4990.0    0.07       0  4996.0    0.16       0
  5396.4    0.05       0
Bank Sta=4990,4996
Exp/Cntr=0.3,0.1

Type RM Length L Ch R = 1,2939,554,554,554
BEGIN DESCRIPTION:
UNT 159 IN BUCR 6.0
END DESCRIPTION:
XS GIS Cut Line= 4
      3662245.07     10497784.77      3662814.48     10497777.83
      3663449.61     10497960.19      3663645.56     10498025.51
#Sta/Elev= 30
  4214.0  391.94  4268.5  390.12  4368.6  377.58  4428.6  367.09  4458.6  359.46
  4468.6  359.35  4488.6  354.37  4528.6  350.32  4799.2  329.60  4944.9  322.18
  4993.9  313.39  4996.6  312.89  4999.9  313.39  5017.7  314.61  5030.4  320.44
  5064.1  324.48  5097.9  332.10  5103.1  335.16  5189.1  343.82  5243.2  348.13
  5248.4  350.27  5267.4  351.30  5309.0  358.47  5315.8  357.39  5413.0  361.87
  5427.4  365.48  5454.8  367.58  5475.9  371.42  5528.6  374.44  5650.8  388.60
#Mann=4,-1,0
  4214.0    0.05       0  4993.9   0.035       0  4999.9    0.05       0
  5189.1    0.16       0
Bank Sta=4993.9,4999.9
Exp/Cntr=0.3,0.1

Type RM Length L Ch R = 1,2385,264,264,264
BEGIN DESCRIPTION:
UNT 159 IN BUCR 5.0
END DESCRIPTION:
XS GIS Cut Line= 3
      3662431.32     10498494.59      3663195.19     10498147.38
      3663689.99     10498086.61
#Sta/Elev= 30
  4412.4  386.86  4482.7  382.42  4528.8  376.93  4575.0  366.02  4586.3  360.58
  4609.0  356.30  4695.8  345.77  4707.1  342.93  4919.9  324.30  4948.8  320.77
  4966.0  314.37  4971.5  315.46  4991.6  312.51  4994.3  312.01  4997.6  312.51
  5017.6  312.59  5025.7  316.14  5040.7  316.66  5047.6  319.34  5161.5  327.41
  5184.6  330.02  5190.4  333.04  5207.7  335.31  5376.8  346.15  5437.9  356.25
  5467.5  358.95  5588.4  376.32  5689.2  387.75  5729.5  390.59  5750.0  389.83
#Mann=3,-1,0
  4412.4    0.16       0  4991.6    0.07       0  4997.6    0.16       0
Bank Sta=4991.6,4997.6
Exp/Cntr=0.3,0.1

Type RM Length L Ch R = 1,2121,399,399,399
BEGIN DESCRIPTION:
UNT 159 IN BUCR 4.0
END DESCRIPTION:
XS GIS Cut Line= 3
      3662561.53     10498590.08      3663282.00     10498381.75
      3663645.63     10498225.91
#Sta/Elev= 30
  4541.4  380.87  4570.6  379.17  4581.0  376.65  4634.6  371.42  4707.1  356.33
  4735.5  354.65  4799.6  345.87  4851.9  336.54  4945.4  326.00  4952.8  323.99
  4958.0  324.80  4976.6  321.05  4994.4  311.08  4997.2  310.58  5000.4  311.08
  5064.0  312.67  5097.7  311.63  5111.9  316.38  5131.3  315.77  5164.0  321.59
  5170.1  325.57  5184.8  329.33  5195.2  334.12  5216.0  338.71  5321.4  349.31
  5435.3  356.38  5593.4  372.57  5611.2  372.72  5640.2  375.88  5687.0  375.65
#Mann=3,-1,0
  4541.4    0.16       0  4994.4    0.07       0  5000.4    0.16       0
Bank Sta=4994.4,5000.4
Exp/Cntr=0.3,0.1

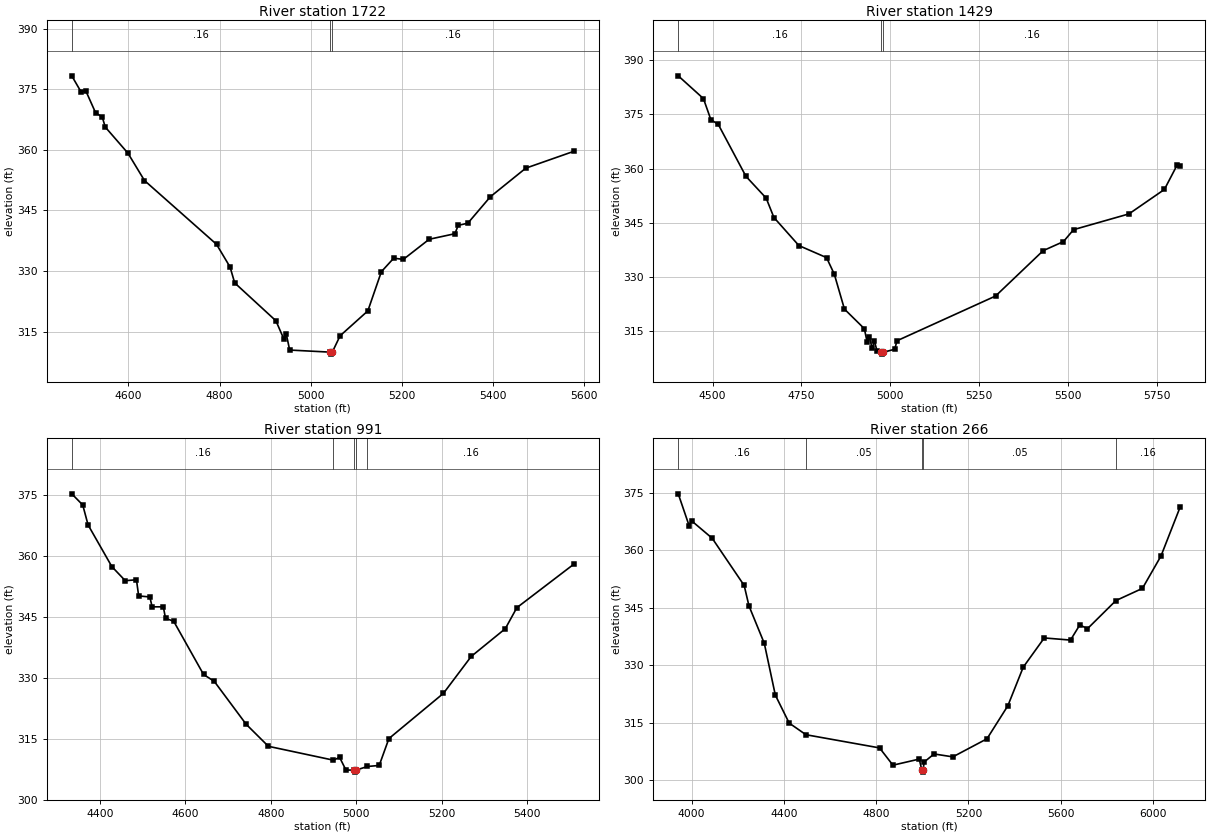
Type RM Length L Ch R = 1,1722,293,293,293
BEGIN DESCRIPTION:
Mapping XS 8fdc4e00
END DESCRIPTION:
XS GIS Cut Line= 4
      3662570.18     10498633.48      3662865.33     10498737.65
      3663247.28     10498781.06      3663533.44     10498494.89
#Sta/Elev= 30
  4475.7  378.30  4496.3  374.28  4506.2  374.66  4528.1  369.13  4542.5  368.13
  4549.3  365.61  4599.0  359.16  4635.3  352.39  4793.4  336.61  4823.2  330.98
  4833.3  327.06  4923.8  317.68  4941.5  313.09  4946.5  314.43  4954.0  310.44
  5041.6  309.93  5044.4  309.43  5047.6  309.93  5064.7  313.97  5125.6  320.13
  5155.3  329.83  5182.4  333.17  5203.6  332.88  5260.2  337.85  5316.8  339.23
  5323.9  341.30  5345.1  341.83  5394.6  348.38  5472.3  355.45  5577.8  359.62
#Mann=3,-1,0
  4475.7    0.16       0  5041.6    0.07       0  5047.6    0.16       0
Bank Sta=5041.6,5047.6
Exp/Cntr=0.3,0.1

Type RM Length L Ch R = 1,1429,438,438,438
BEGIN DESCRIPTION:
UNT 159 IN BUCR 3.0
END DESCRIPTION:
XS GIS Cut Line= 3
      3662506.15     10498604.22      3663047.81     10499076.44
      3663499.21     10499604.23
#Sta/Elev= 30
  4403.5  385.71  4474.4  379.40  4495.3  373.57  4516.2  372.24  4594.0  357.86
  4651.0  351.81  4672.8  346.44  4743.1  338.66  4820.9  335.32  4842.8  330.72
  4871.3  321.05  4927.3  315.62  4934.9  312.04  4941.5  313.33  4949.1  310.19
  4955.7  312.12  4963.3  309.37  4974.6  309.07  4977.3  308.57  4980.6  309.07
  5012.7  309.93  5019.3  312.28  5296.7  324.68  5430.6  337.25  5487.7  339.76
  5516.2  343.07  5672.1  347.44  5771.8  354.21  5807.1  360.88  5816.6  360.61
#Mann=3,-1,0
  4403.5    0.16       0  4974.6    0.07       0  4980.6    0.16       0
Bank Sta=4974.6,4980.6
Exp/Cntr=0.3,0.1

Type RM Length L Ch R = 1,991,725,725,725
BEGIN DESCRIPTION:
UNT 159 IN BUCR 2.0
END DESCRIPTION:
XS GIS Cut Line= 3
      3662485.32     10498763.97      3662648.51     10499246.58
      3663189.96     10499635.31
#Sta/Elev= 30
  4333.7  375.26  4359.4  372.52  4371.9  367.61  4427.6  357.36  4459.0  353.90
  4485.2  354.12  4490.4  350.15  4516.6  349.90  4521.9  347.47  4548.1  347.47
  4553.3  344.66  4572.5  343.91  4642.4  330.83  4667.5  329.14  4742.0  318.61
  4794.2  313.17  4946.5  309.76  4961.1  310.44  4975.9  307.33  4993.7  307.32
  4996.5  306.82  4999.7  307.32  5026.2  308.21  5053.8  308.46  5076.5  315.07
  5204.3  326.20  5269.3  335.27  5349.1  342.09  5376.2  347.26  5509.7  357.96
#Mann=5,-1,0
  4333.7    0.16       0  4946.5    0.05       0  4993.7    0.03       0
  4999.7    0.05       0  5026.2    0.16       0
Bank Sta=4993.7,4999.7
Exp/Cntr=0.3,0.1

Type RM Length L Ch R = 1,266,0,0,0
BEGIN DESCRIPTION:
UNT 159 IN BUCR 1.0
END DESCRIPTION:
XS GIS Cut Line= 4
      3662464.49     10498784.74      3662235.31     10499607.69
      3662440.17     10499871.58      3663422.86     10499979.22
#Sta/Elev= 30
  3942.0  374.78  3989.2  366.47  3999.6  367.75  4089.2  363.19  4227.9  350.87
  4248.7  345.54  4315.2  335.76  4362.9  322.28  4423.0  314.97  4495.7  311.93
  4814.9  308.49  4872.9  303.98  4986.9  305.57  4998.4  302.67  5001.1  302.17
  5004.4  302.67  5007.7  304.78  5051.2  306.91  5132.6  306.15  5280.7  310.87
  5371.2  319.49  5437.8  329.55  5529.0  337.18  5642.8  336.62  5683.1  340.58
  5716.4  339.59  5839.7  346.93  5954.7  350.11  6035.1  358.56  6118.9  371.44
#Mann=5,-1,0
  3942.0    0.16       0  4495.7    0.05       0  4998.4    0.03       0
  5004.4    0.05       0  5839.7    0.16       0
Bank Sta=4998.4,5004.4
Exp/Cntr=0.3,0.1

Chan Stop Cuts=-1