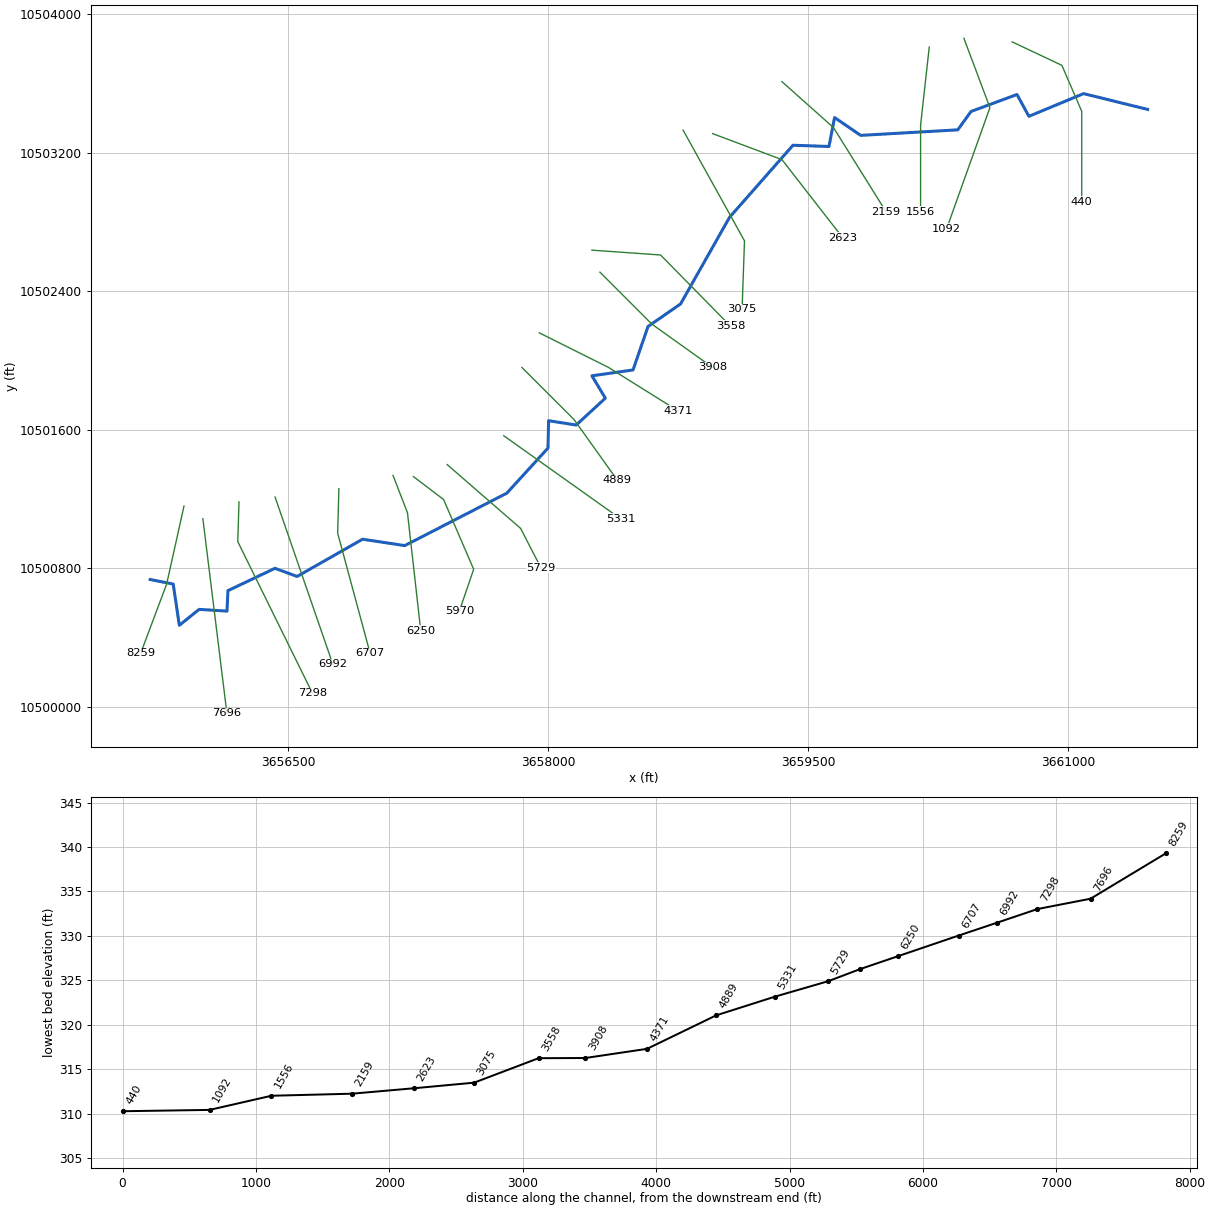
--- UNT 160 IN BUCR.prj (project) ---

Proj Title=UNT 160 IN BUCR Base Level Engineering
Current Plan=p01
Default Exp/Contr=0.3,0.1
English Units
Geom File=g01
Flow File=f01
Plan File=p01
BEGIN DESCRIPTION:
UNT 160 IN BUCR
END DESCRIPTION:

--- UNT 160 IN BUCR.p01 (plan) ---

Plan Title=Multiple Run
Short Identifier=Multiple
Geom File=g01
Flow File=f01
Subcritical Flow
K Sum by GR= 0
Std Step Tol= 0.01
Critical Tol= 0.01
Num of Std Step Trials= 20
Max Error Tol= 0.3
Flow Tol Ratio= 0.001
Split Flow NTrial= 30
Split Flow Tol= 0.02
Split Flow Ratio= 0.02
Log Output Level= 0
Friction Slope Method= 1
Unsteady Friction Slope Method= 2
Unsteady Bridges Friction Slope Method= 1
Parabolic Critical Depth
Global Vel Dist=  1 , 1 , 1
Global Log Level= 0
CheckData=True
Encroach Param= -1, 0, 0, 0
BEGIN DESCRIPTION:
Multiple Run
END DESCRIPTION:

--- UNT 160 IN BUCR.f01 (steady flow) ---

Flow Title=Multiple
Number of Profiles=7
Profile Names=10-year,25-year,50-year,1pct_min,100-year,1pct_plu,500-year
River Rch & RM= UNT 160 IN BUCR,Reach-1,8259
     739    1011    1236    1109    1500    2029    2220
Boundary for River Rch & Prof#=UNT 160 IN BUCR,Reach-1,1
Up Type=0
Dn Type=3
Dn Slope=0.005
Boundary for River Rch & Prof#=UNT 160 IN BUCR,Reach-1,2
Up Type=0
Dn Type=3
Dn Slope=0.005
Boundary for River Rch & Prof#=UNT 160 IN BUCR,Reach-1,3
Up Type=0
Dn Type=3
Dn Slope=0.005
Boundary for River Rch & Prof#=UNT 160 IN BUCR,Reach-1,4
Up Type=0
Dn Type=3
Dn Slope=0.005
Boundary for River Rch & Prof#=UNT 160 IN BUCR,Reach-1,5
Up Type=0
Dn Type=3
Dn Slope=0.005
Boundary for River Rch & Prof#=UNT 160 IN BUCR,Reach-1,6
Up Type=0
Dn Type=3
Dn Slope=0.005
Boundary for River Rch & Prof#=UNT 160 IN BUCR,Reach-1,7
Up Type=0
Dn Type=3
Dn Slope=0.005

--- UNT 160 IN BUCR.g01 (geometry) ---

Geom Title=Existing Conditions

River Reach=UNT 160 IN BUCR,Reach-1
Reach XY= 30
      3655704.64     10500736.29      3655837.50     10500710.00
      3655872.75     10500472.00      3655987.00     10500564.00
      3656147.75     10500554.00      3656153.25     10500672.00
      3656424.75     10500801.00      3656552.25     10500754.00
      3656930.00     10500969.00      3657173.50     10500932.00
      3657762.50     10501235.00      3657999.75     10501495.00
      3658003.25     10501653.00      3658162.50     10501628.00
      3658330.75     10501783.00      3658253.25     10501912.00
      3658490.50     10501946.00      3658577.00     10502197.00
      3658764.75     10502327.00      3659047.25     10502827.00
      3659413.25     10503243.00      3659621.00     10503236.00
      3659653.25     10503403.00      3659804.00     10503300.00
      3660364.25     10503332.00      3660440.50     10503438.00
      3660705.75     10503536.00      3660774.50     10503410.00
      3661089.75     10503541.00      3661459.50     10503450.00

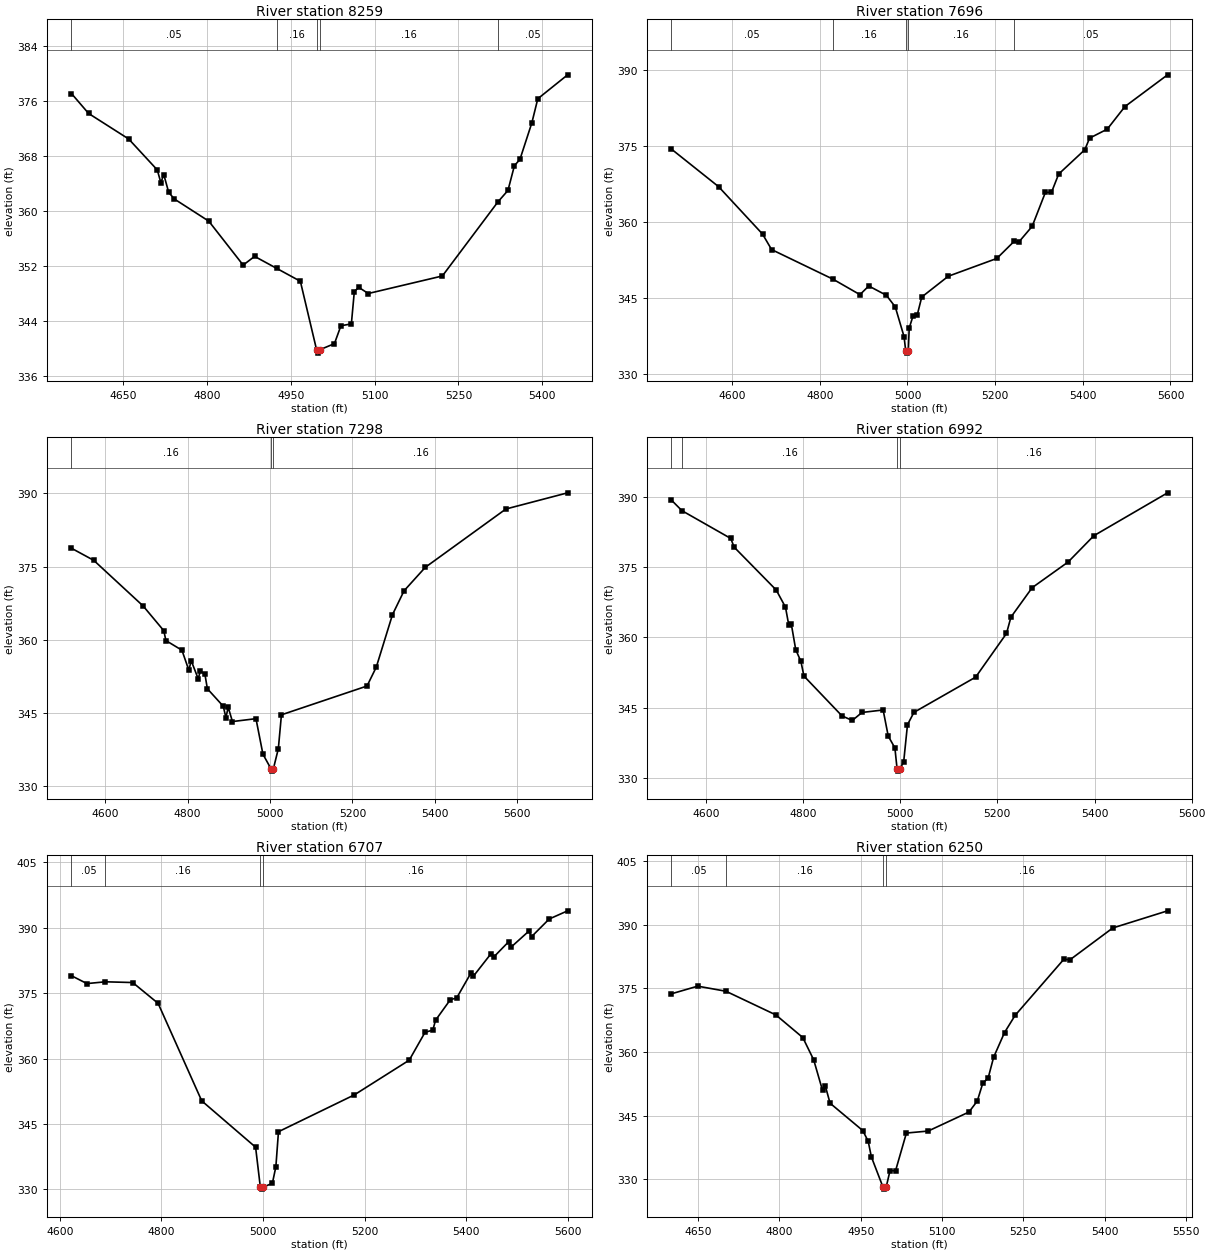
Type RM Length L Ch R = 1,8259,563,563,563
BEGIN DESCRIPTION:
UNT 160 IN BUCR 17.0
END DESCRIPTION:
XS GIS Cut Line= 3
      3655899.60     10501160.16      3655799.61     10500710.19
      3655649.63     10500310.23
#Sta/Elev= 30
  4557.3  377.03  4588.0  374.13  4659.7  370.42  4710.9  365.92  4717.3  364.06
  4722.5  365.25  4731.4  362.64  4741.7  361.68  4803.1  358.47  4864.6  352.08
  4885.1  353.35  4924.5  351.61  4967.0  349.73  4996.0  339.78  4998.8  339.28
  5002.0  339.78  5028.0  340.66  5039.6  343.26  5058.3  343.53  5063.6  348.24
  5071.6  348.84  5088.6  347.95  5221.2  350.50  5320.6  361.27  5338.6  362.94
  5350.2  366.55  5360.0  367.44  5381.4  372.78  5392.0  376.27  5445.4  379.75
#Mann=5,-1,0
  4557.3    0.05       0  4924.5    0.16       0  4996.0    0.07       0
  5002.0    0.16       0  5320.6    0.05       0
Bank Sta=4996,5002
Exp/Cntr=0.3,0.1

Type RM Length L Ch R = 1,7696,398,398,398
BEGIN DESCRIPTION:
UNT 160 IN BUCR 16.0
END DESCRIPTION:
XS GIS Cut Line= 2
      3656008.57     10501087.00      3656147.25     10499963.63
#Sta/Elev= 30
  4461.5  374.42  4569.1  367.01  4669.4  357.66  4690.0  354.61  4830.1  348.77
  4891.6  345.72  4911.7  347.43  4952.0  345.59  4972.2  343.30  4992.3  337.42
  4995.9  334.69  4998.7  334.19  5001.9  334.69  5004.0  339.14  5012.5  341.46
  5022.5  341.79  5032.6  345.25  5093.1  349.35  5203.9  352.86  5243.5  356.24
  5254.3  356.12  5284.5  359.19  5314.7  365.89  5328.4  365.86  5345.0  369.50
  5404.5  374.28  5415.5  376.58  5455.8  378.35  5496.1  382.80  5593.4  389.06
#Mann=5,-1,0
  4461.5    0.05       0  4830.1    0.16       0  4995.9    0.07       0
  5001.9    0.16       0  5243.5    0.05       0
Bank Sta=4995.9,5001.9
Exp/Cntr=0.3,0.1

Type RM Length L Ch R = 1,7298,306,306,306
BEGIN DESCRIPTION:
UNT 160 IN BUCR 15.0
END DESCRIPTION:
XS GIS Cut Line= 3
      3656216.89     10501184.26      3656209.95     10500955.10
      3656640.52     10500080.07
#Sta/Elev= 30
  4518.0  378.75  4572.1  376.27  4692.2  366.89  4742.2  361.83  4747.2  359.82
  4786.2  357.83  4803.0  353.71  4808.6  355.70  4825.5  352.01  4831.0  353.51
  4841.9  352.94  4847.9  349.93  4886.5  346.34  4892.9  344.02  4898.5  346.12
  4908.8  343.20  4965.9  343.79  4982.8  336.51  5002.2  333.53  5005.0  333.03
  5008.2  333.53  5020.2  337.63  5027.7  344.58  5235.5  350.49  5258.0  354.37
  5297.3  365.13  5325.4  370.02  5376.9  374.83  5572.6  386.80  5722.5  390.12
#Mann=3,-1,0
  4518.0    0.16       0  5002.2    0.07       0  5008.2    0.16       0
Bank Sta=5002.2,5008.2
Exp/Cntr=0.3,0.1

Type RM Length L Ch R = 1,6992,285,285,285
BEGIN DESCRIPTION:
UNT 160 IN BUCR 14.0
END DESCRIPTION:
XS GIS Cut Line= 2
      3656425.21     10501212.09      3656758.58     10500246.73
#Sta/Elev= 30
  4529.1  389.27  4550.7  387.02  4651.3  381.09  4658.1  379.25  4744.8  370.10
  4763.9  366.44  4770.7  362.60  4776.0  362.77  4785.0  357.37  4795.6  354.89
  4801.9  351.75  4880.2  343.26  4901.4  342.28  4921.4  343.99  4964.9  344.52
  4975.4  338.95  4989.1  336.43  4993.6  331.98  4996.4  331.48  4999.6  331.98
  5007.2  333.46  5015.0  341.37  5028.3  344.01  5155.3  351.52  5218.8  360.83
  5228.0  364.32  5271.7  370.60  5345.7  376.07  5398.6  381.67  5550.4  390.82
#Mann=4,-1,0
  4529.1    0.05       0  4550.7    0.16       0  4993.6    0.07       0
  4999.6    0.16       0
Bank Sta=4993.6,4999.6
Exp/Cntr=0.3,0.1

Type RM Length L Ch R = 1,6707,457,457,457
BEGIN DESCRIPTION:
Mapping XS 4e782181
END DESCRIPTION:
XS GIS Cut Line= 3
      3656793.28     10501260.63      3656786.34     10501003.71
      3656973.83     10500309.29
#Sta/Elev= 30
  4623.0  379.00  4653.4  377.20  4689.8  377.61  4743.5  377.44  4793.5  372.66
  4879.3  350.30  4985.3  339.67  4994.6  330.55  4997.3  330.05  5000.6  330.55
  5018.3  331.37  5025.2  335.19  5030.3  343.22  5179.6  351.67  5287.6  359.63
  5318.7  366.02  5334.0  366.53  5339.4  368.79  5368.7  373.54  5380.8  373.87
  5408.6  379.53  5413.8  378.88  5448.5  384.05  5453.7  383.27  5483.2  386.79
  5488.4  385.60  5523.1  389.24  5528.3  387.96  5563.0  392.01  5599.3  393.89
#Mann=4,-1,0
  4623.0    0.05       0  4689.8    0.16       0  4994.6    0.07       0
  5000.6    0.16       0
Bank Sta=4994.6,5000.6
Exp/Cntr=0.3,0.1

Type RM Length L Ch R = 1,6250,280,280,280
BEGIN DESCRIPTION:
UNT 160 IN BUCR 13.0
END DESCRIPTION:
XS GIS Cut Line= 3
      3657105.79     10501337.03      3657189.12     10501121.77
      3657265.51     10500441.17
#Sta/Elev= 30
  4600.7  373.69  4649.2  375.49  4701.4  374.29  4793.5  368.72  4843.2  363.39
  4863.3  358.14  4879.6  350.94  4884.6  352.07  4893.5  347.94  4953.9  341.50
  4963.9  338.97  4969.7  335.32  4991.1  328.22  4993.9  327.72  4997.1  328.22
  5004.2  332.09  5014.3  332.02  5034.4  340.92  5074.6  341.39  5149.9  345.87
  5165.2  348.46  5175.3  352.62  5185.3  353.89  5195.4  358.77  5215.5  364.58
  5235.0  368.61  5325.1  381.84  5336.3  381.70  5415.2  389.18  5516.4  393.22
#Mann=4,-1,0
  4600.7    0.05       0  4701.4    0.16       0  4991.1    0.07       0
  4997.1    0.16       0
Bank Sta=4991.1,4997.1
Exp/Cntr=0.3,0.1

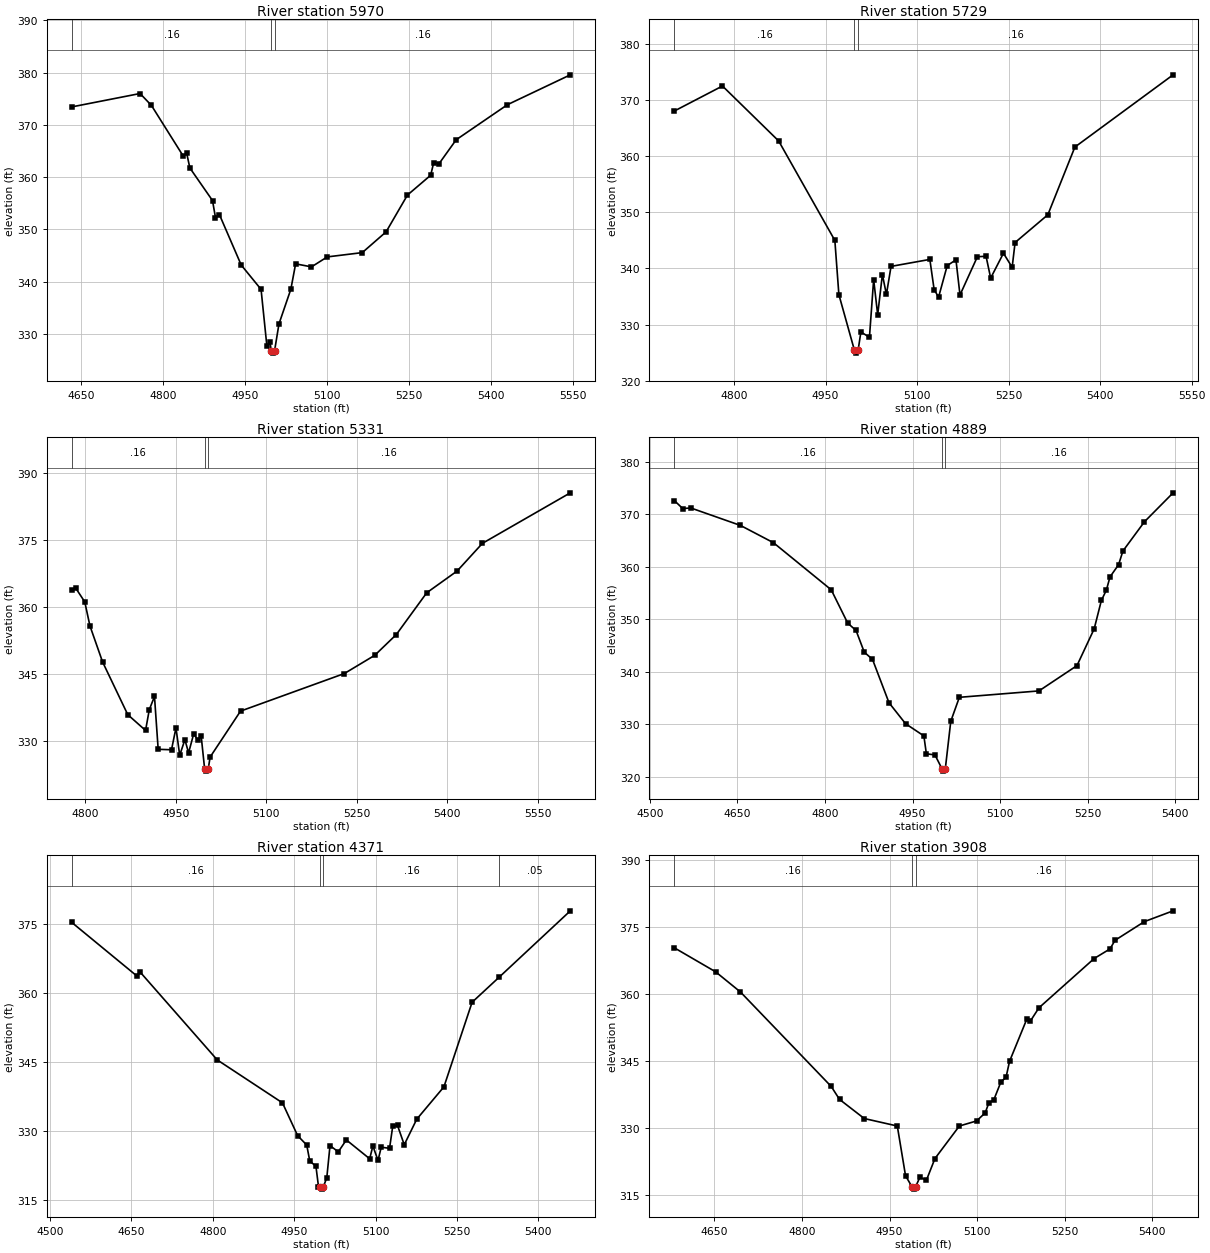
Type RM Length L Ch R = 1,5970,241,241,241
BEGIN DESCRIPTION:
UNT 160 IN BUCR 12.0
END DESCRIPTION:
XS GIS Cut Line= 4
      3657223.84     10501330.10      3657397.45     10501198.16
      3657571.06     10500795.38      3657488.22     10500553.74
#Sta/Elev= 30
  4633.1  373.44  4758.3  376.01  4779.1  373.73  4837.3  364.02  4843.6  364.55
  4849.4  361.75  4890.8  355.51  4896.2  352.25  4903.4  352.83  4943.3  343.16
  4979.6  338.50  4990.3  327.58  4995.8  328.35  4998.4  326.79  5001.1  326.29
  5004.4  326.79  5012.3  331.87  5034.1  338.54  5042.8  343.39  5071.8  342.81
  5100.7  344.72  5164.7  345.54  5208.3  349.52  5247.3  356.56  5289.8  360.36
  5295.2  362.73  5305.1  362.57  5336.4  367.15  5430.2  373.87  5545.2  379.59
#Mann=3,-1,0
  4633.1    0.16       0  4998.4    0.07       0  5004.4    0.16       0
Bank Sta=4998.4,5004.4
Exp/Cntr=0.3,0.1

Type RM Length L Ch R = 1,5729,398,398,398
BEGIN DESCRIPTION:
Mapping XS 59f636bf
END DESCRIPTION:
XS GIS Cut Line= 3
      3657418.25     10501399.58      3657841.89     10501031.49
      3657959.22     10500803.75
#Sta/Elev= 30
  4702.2  368.02  4781.0  372.47  4873.1  362.69  4965.2  344.98  4971.8  335.34
  4997.3  325.42  5000.1  324.92  5003.3  325.42  5007.9  328.69  5021.9  327.74
  5028.8  338.02  5035.4  331.74  5043.1  338.91  5049.7  335.36  5057.3  340.36
  5120.9  341.60  5127.9  336.24  5135.2  334.88  5149.4  340.51  5163.7  341.52
  5170.3  335.27  5198.8  342.08  5213.0  342.16  5220.6  338.28  5241.5  342.70
  5255.8  340.20  5260.6  344.61  5314.3  349.55  5358.6  361.60  5519.6  374.46
#Mann=3,-1,0
  4702.2    0.16       0  4997.3    0.07       0  5003.3    0.16       0
Bank Sta=4997.3,5003.3
Exp/Cntr=0.3,0.1

Type RM Length L Ch R = 1,5331,442,442,442
BEGIN DESCRIPTION:
UNT 160 IN BUCR 11.0
END DESCRIPTION:
XS GIS Cut Line= 2
      3657744.65     10501566.23      3658418.30     10501087.04
#Sta/Elev= 30
  4777.1  363.77  4784.1  364.18  4798.9  361.13  4807.5  355.75  4828.4  347.68
  4870.2  335.85  4899.7  332.31  4905.9  336.98  4914.5  339.92  4920.6  328.08
  4942.7  327.98  4950.1  332.88  4956.3  326.74  4964.9  330.24  4971.0  327.28
  4979.5  331.56  4985.8  330.24  4991.9  331.03  4997.6  323.69  5000.3  323.19
  5003.6  323.69  5006.7  326.34  5057.1  336.64  5229.3  345.07  5279.7  349.16
  5315.4  353.81  5365.8  363.17  5416.2  368.05  5458.1  374.25  5603.8  385.57
#Mann=3,-1,0
  4777.1    0.16       0  4997.6    0.07       0  5003.6    0.16       0
Bank Sta=4997.6,5003.6
Exp/Cntr=0.3,0.1

Type RM Length L Ch R = 1,4889,518,518,518
BEGIN DESCRIPTION:
UNT 160 IN BUCR 10.0
END DESCRIPTION:
XS GIS Cut Line= 3
      3657849.59     10501960.21      3658149.61     10501660.19
      3658399.60     10501310.20
#Sta/Elev= 30
  4542.0  372.61  4556.2  371.10  4570.3  371.20  4655.2  367.88  4711.7  364.59
  4810.7  355.62  4839.0  349.26  4853.2  347.88  4867.3  343.74  4881.4  342.37
  4909.7  334.10  4938.0  330.12  4969.4  327.79  4973.7  324.38  4988.4  324.17
  5000.2  321.58  5002.9  321.08  5006.2  321.58  5015.5  330.57  5030.2  335.14
  5166.6  336.36  5231.7  341.18  5261.2  348.19  5273.5  353.59  5282.1  355.57
  5288.3  358.08  5303.0  360.40  5310.4  363.01  5347.3  368.58  5396.4  374.09
#Mann=3,-1,0
  4542.0    0.16       0  5000.2    0.07       0  5006.2    0.16       0
Bank Sta=5000.2,5006.2
Exp/Cntr=0.3,0.1

Type RM Length L Ch R = 1,4371,463,463,463
BEGIN DESCRIPTION:
UNT 160 IN BUCR 9.0
END DESCRIPTION:
XS GIS Cut Line= 3
      3657949.60     10502160.19      3658349.61     10501960.19
      3658749.59     10501710.20
#Sta/Elev= 30
  4539.9  375.34  4660.1  363.67  4665.7  364.58  4808.2  345.42  4928.4  336.08
  4956.4  328.94  4973.1  326.91  4978.7  323.45  4990.1  322.27  4994.8  317.87
  4997.7  317.82  5000.4  317.32  5003.7  317.82  5010.1  319.81  5016.0  326.78
  5031.3  325.43  5046.1  328.02  5089.1  323.92  5095.0  326.70  5104.5  323.56
  5110.4  326.44  5125.7  326.19  5131.6  331.00  5140.4  331.17  5152.8  326.97
  5175.8  332.52  5225.9  339.56  5277.8  357.95  5328.2  363.46  5458.8  377.83
#Mann=4,-1,0
  4539.9    0.16       0  4997.7    0.07       0  5003.7    0.16       0
  5328.2    0.05       0
Bank Sta=4997.7,5003.7
Exp/Cntr=0.3,0.1

Type RM Length L Ch R = 1,3908,350,350,350
BEGIN DESCRIPTION:
UNT 160 IN BUCR 8.0
END DESCRIPTION:
XS GIS Cut Line= 3
      3658299.60     10502510.20      3658599.61     10502210.19
      3658949.61     10501960.18
#Sta/Elev= 30
  4581.3  370.39  4652.0  365.01  4694.5  360.49  4850.0  339.31  4864.2  336.41
  4906.6  332.12  4963.2  330.44  4977.3  319.30  4988.4  316.79  4991.2  316.29
  4994.4  316.79  5002.0  318.97  5013.0  318.27  5027.7  323.15  5069.5  330.44
  5099.0  331.58  5113.7  333.38  5119.9  335.57  5128.5  336.30  5140.8  340.36
  5149.4  341.33  5155.5  344.95  5185.0  354.39  5191.1  353.96  5205.9  356.95
  5300.5  368.00  5327.6  370.15  5336.2  372.08  5386.5  376.27  5435.7  378.69
#Mann=3,-1,0
  4581.3    0.16       0  4988.4    0.07       0  4994.4    0.16       0
Bank Sta=4988.4,4994.4
Exp/Cntr=0.3,0.1

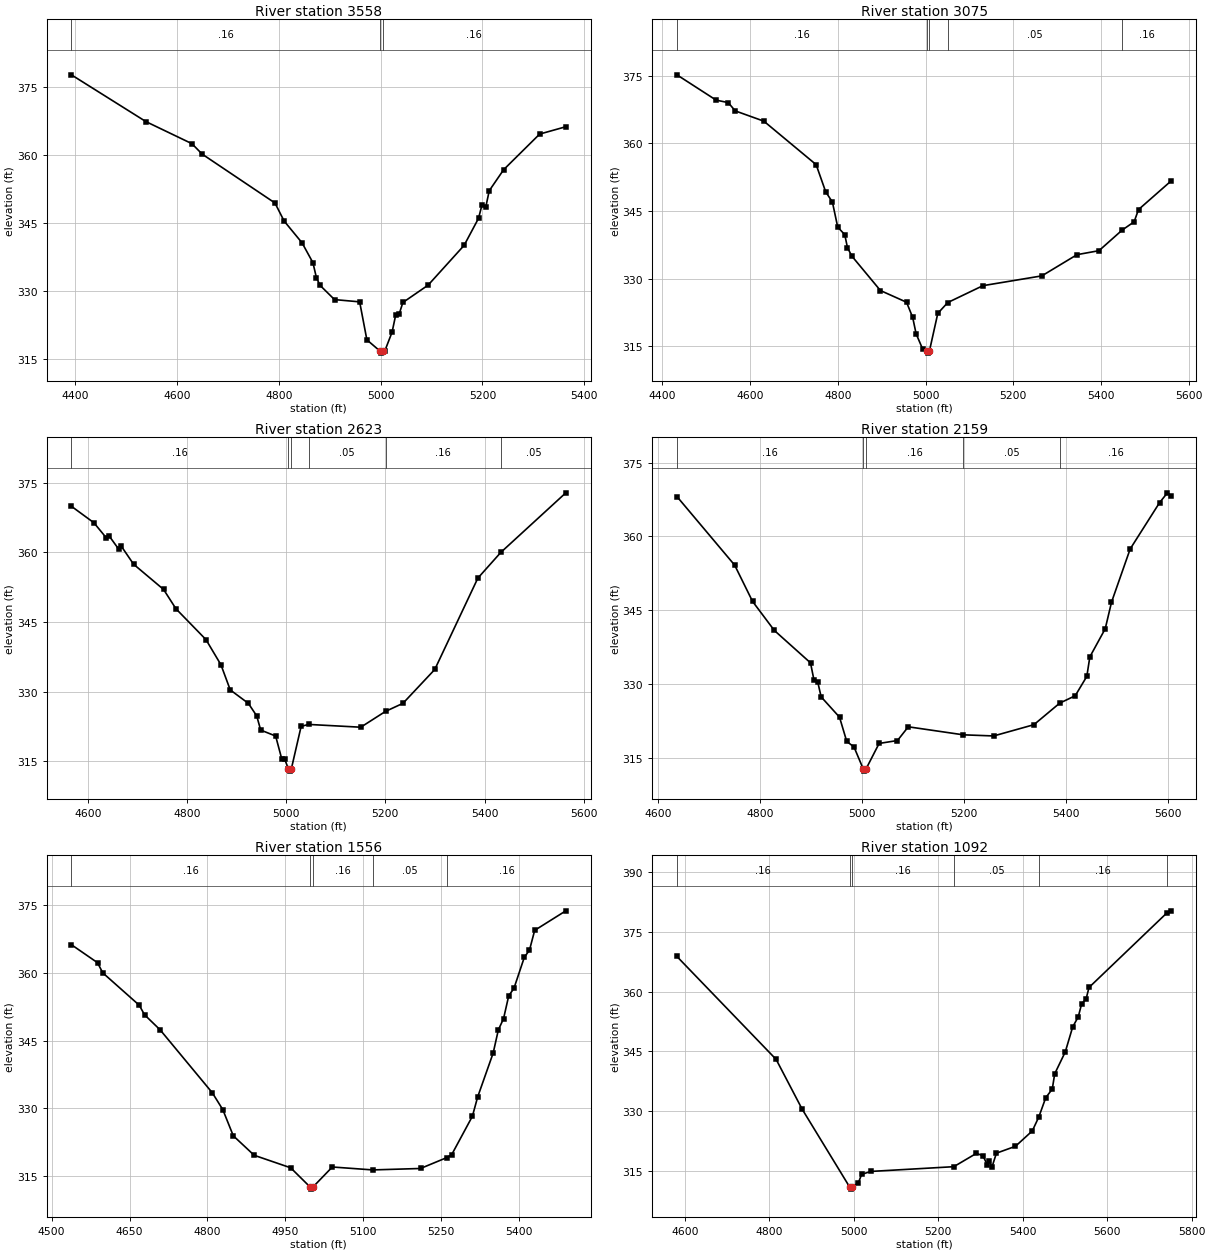
Type RM Length L Ch R = 1,3558,483,483,483
BEGIN DESCRIPTION:
UNT 160 IN BUCR 7.0
END DESCRIPTION:
XS GIS Cut Line= 3
      3658253.39     10502637.39      3658649.19     10502609.61
      3659051.96     10502199.90
#Sta/Elev= 30
  4392.5  377.66  4539.1  367.33  4629.3  362.47  4649.3  360.18  4792.4  349.39
  4810.4  345.41  4845.7  340.59  4867.0  336.22  4874.0  332.84  4881.1  331.21
  4909.4  328.08  4958.8  327.58  4973.0  319.20  4998.3  316.77  5001.0  316.27
  5004.3  316.77  5008.4  316.80  5022.5  320.91  5029.5  324.62  5036.7  324.99
  5043.7  327.44  5093.3  331.27  5164.0  340.04  5192.3  346.00  5199.3  349.05
  5206.4  348.42  5213.4  352.10  5241.7  356.74  5312.4  364.59  5363.8  366.21
#Mann=3,-1,0
  4392.5    0.16       0  4998.3    0.07       0  5004.3    0.16       0
Bank Sta=4998.3,5004.3
Exp/Cntr=0.3,0.1

Type RM Length L Ch R = 1,3075,452,452,452
BEGIN DESCRIPTION:
UNT 160 IN BUCR 6.0
END DESCRIPTION:
XS GIS Cut Line= 3
      3658779.42     10503330.06      3659133.56     10502691.21
      3659119.67     10502295.40
#Sta/Elev= 30
  4433.5  375.19  4522.9  369.58  4550.4  369.04  4566.4  367.20  4631.6  364.92
  4750.7  355.29  4772.4  349.29  4787.8  346.98  4799.9  341.44  4815.9  339.78
  4822.1  336.89  4832.0  335.03  4897.2  327.39  4956.7  324.80  4970.7  321.43
  4978.5  317.80  4993.6  314.38  5002.9  314.02  5005.7  313.52  5008.9  314.02
  5027.9  322.33  5050.6  324.73  5130.8  328.47  5265.0  330.64  5345.1  335.34
  5395.1  336.22  5448.0  340.79  5475.2  342.62  5485.2  345.33  5560.0  351.72
#Mann=5,-1,0
  4433.5    0.16       0  5002.9    0.07       0  5008.9    0.16       0
  5050.6    0.05       0  5448.0    0.16       0
Bank Sta=5002.9,5008.9
Exp/Cntr=0.3,0.1

Type RM Length L Ch R = 1,2623,464,464,464
BEGIN DESCRIPTION:
UNT 160 IN BUCR 5.0
END DESCRIPTION:
XS GIS Cut Line= 3
      3658949.64     10503310.18      3659349.61     10503160.19
      3659699.64     10502710.15
#Sta/Elev= 30
  4566.7  369.89  4612.1  366.34  4637.0  363.11  4642.3  363.58  4661.9  360.69
  4667.2  361.32  4692.2  357.41  4752.7  351.98  4777.6  347.83  4838.1  341.20
  4868.4  335.77  4887.1  330.37  4923.6  327.48  4940.5  324.78  4948.5  321.73
  4978.7  320.44  4991.2  315.44  4997.0  315.44  5004.4  313.39  5007.2  312.89
  5010.4  313.39  5030.1  322.52  5045.1  322.94  5150.4  322.34  5200.4  325.75
  5235.5  327.48  5299.7  334.77  5386.6  354.43  5433.0  359.97  5564.0  372.78
#Mann=6,-1,0
  4566.7    0.16       0  5004.4    0.07       0  5010.4    0.16       0
  5045.1    0.05       0  5200.4    0.16       0  5433.0    0.05       0
Bank Sta=5004.4,5010.4
Exp/Cntr=0.3,0.1

Type RM Length L Ch R = 1,2159,603,603,603
BEGIN DESCRIPTION:
UNT 160 IN BUCR 4.0
END DESCRIPTION:
XS GIS Cut Line= 3
      3659349.60     10503610.20      3659647.12     10503344.84
      3659949.63     10502860.16
#Sta/Elev= 30
  4636.6  368.10  4749.9  354.15  4785.0  346.78  4827.7  340.88  4898.7  334.29
  4905.4  330.84  4912.9  330.39  4919.6  327.37  4955.6  323.25  4969.8  318.31
  4984.0  317.20  5001.9  312.78  5004.6  312.28  5007.9  312.78  5033.3  317.91
  5069.3  318.50  5090.5  321.29  5198.4  319.66  5258.0  319.43  5337.0  321.72
  5387.6  326.10  5418.0  327.60  5440.8  331.54  5446.7  335.50  5476.9  341.22
  5489.2  346.61  5525.8  357.43  5583.6  366.87  5598.9  368.85  5606.6  368.22
#Mann=5,-1,0
  4636.6    0.16       0  5001.9    0.07       0  5007.9    0.16       0
  5198.4    0.05       0  5387.6    0.16       0
Bank Sta=5001.9,5007.9
Exp/Cntr=0.3,0.1

Type RM Length L Ch R = 1,1556,464,464,464
BEGIN DESCRIPTION:
UNT 160 IN BUCR 3.0
END DESCRIPTION:
XS GIS Cut Line= 3
      3660199.61     10503810.23      3660149.61     10503360.19
      3660149.61     10502860.20
#Sta/Elev= 30
  4538.0  366.27  4588.4  362.27  4598.4  360.03  4668.8  352.84  4678.9  350.73
  4709.1  347.37  4809.7  333.40  4829.8  329.68  4850.0  323.88  4890.2  319.56
  4960.6  316.78  4997.8  312.55  5000.6  312.05  5003.8  312.55  5040.8  316.96
  5118.7  316.31  5210.8  316.63  5261.8  319.06  5270.8  319.68  5310.8  328.22
  5320.8  332.45  5350.8  342.24  5360.8  347.38  5370.8  349.86  5380.8  354.95
  5390.8  356.57  5410.8  363.46  5420.8  365.07  5430.8  369.45  5490.8  373.78
#Mann=5,-1,0
  4538.0    0.16       0  4997.8    0.07       0  5003.8    0.16       0
  5118.7    0.05       0  5261.8    0.16       0
Bank Sta=4997.8,5003.8
Exp/Cntr=0.3,0.1

Type RM Length L Ch R = 1,1092,652,652,652
BEGIN DESCRIPTION:
UNT 160 IN BUCR 2.0
END DESCRIPTION:
XS GIS Cut Line= 3
      3660399.61     10503860.18      3660549.61     10503460.19
      3660299.61     10502760.18
#Sta/Elev= 30
  4581.4  368.84  4816.3  343.01  4877.8  330.54  4990.5  310.96  4993.2  310.46
  4996.5  310.96  5011.2  312.10  5018.7  314.16  5040.4  314.90  5236.9  316.09
  5290.5  319.44  5305.9  318.83  5316.0  316.60  5321.3  317.57  5327.1  315.95
  5337.8  319.48  5382.9  321.21  5422.7  325.06  5438.3  328.60  5454.6  333.41
  5470.0  335.56  5475.8  339.40  5500.8  344.89  5518.3  351.14  5531.6  353.71
  5539.5  356.94  5550.1  358.18  5557.0  361.06  5740.6  379.69  5751.9  380.29
#Mann=6,-1,0
  4581.4    0.16       0  4990.5    0.07       0  4996.5    0.16       0
  5236.9    0.05       0  5438.3    0.16       0  5740.6    0.05       0
Bank Sta=4990.5,4996.5
Exp/Cntr=0.3,0.1

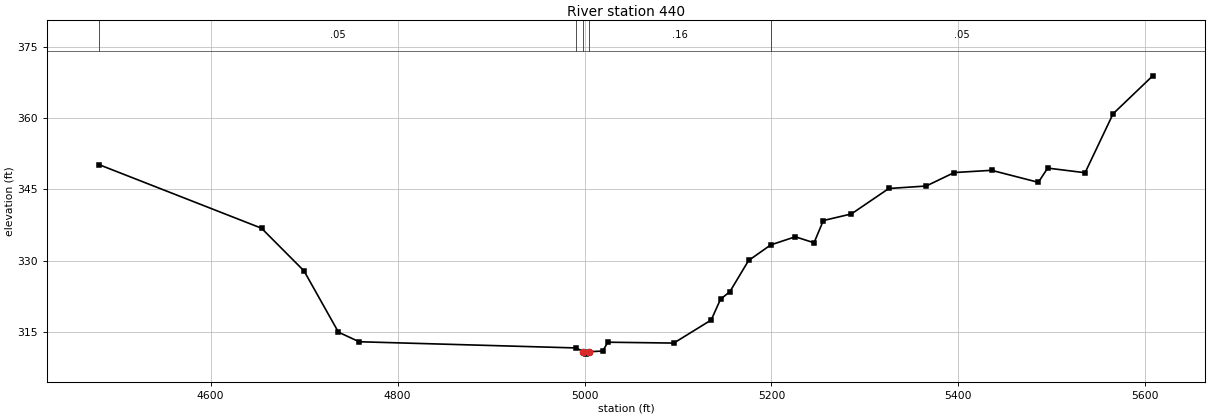
Type RM Length L Ch R = 1,440,0,0,0
BEGIN DESCRIPTION:
UNT 160 IN BUCR 1.0
END DESCRIPTION:
XS GIS Cut Line= 4
      3660678.34     10503839.64      3660964.83     10503704.22
      3661079.41     10503438.59      3661079.41     10502917.76
#Sta/Elev= 30
  4480.9  350.21  4654.4  336.84  4699.9  327.84  4736.7  314.94  4758.8  312.92
  4991.3  311.61  4998.4  310.81  5001.2  310.31  5004.4  310.81  5019.5  310.96
  5024.9  312.82  5095.5  312.64  5135.5  317.50  5145.5  321.88  5155.5  323.47
  5175.5  330.04  5199.2  333.32  5225.5  335.04  5245.5  333.77  5255.5  338.46
  5285.5  339.85  5325.5  345.21  5365.5  345.73  5395.5  348.57  5435.5  349.04
  5485.5  346.51  5495.5  349.51  5535.5  348.53  5565.5  360.96  5607.9  368.95
#Mann=5,-1,0
  4480.9    0.05       0  4991.3    0.16       0  4998.4    0.07       0
  5004.4    0.16       0  5199.2    0.05       0
Bank Sta=4998.4,5004.4
Exp/Cntr=0.3,0.1

Chan Stop Cuts=-1