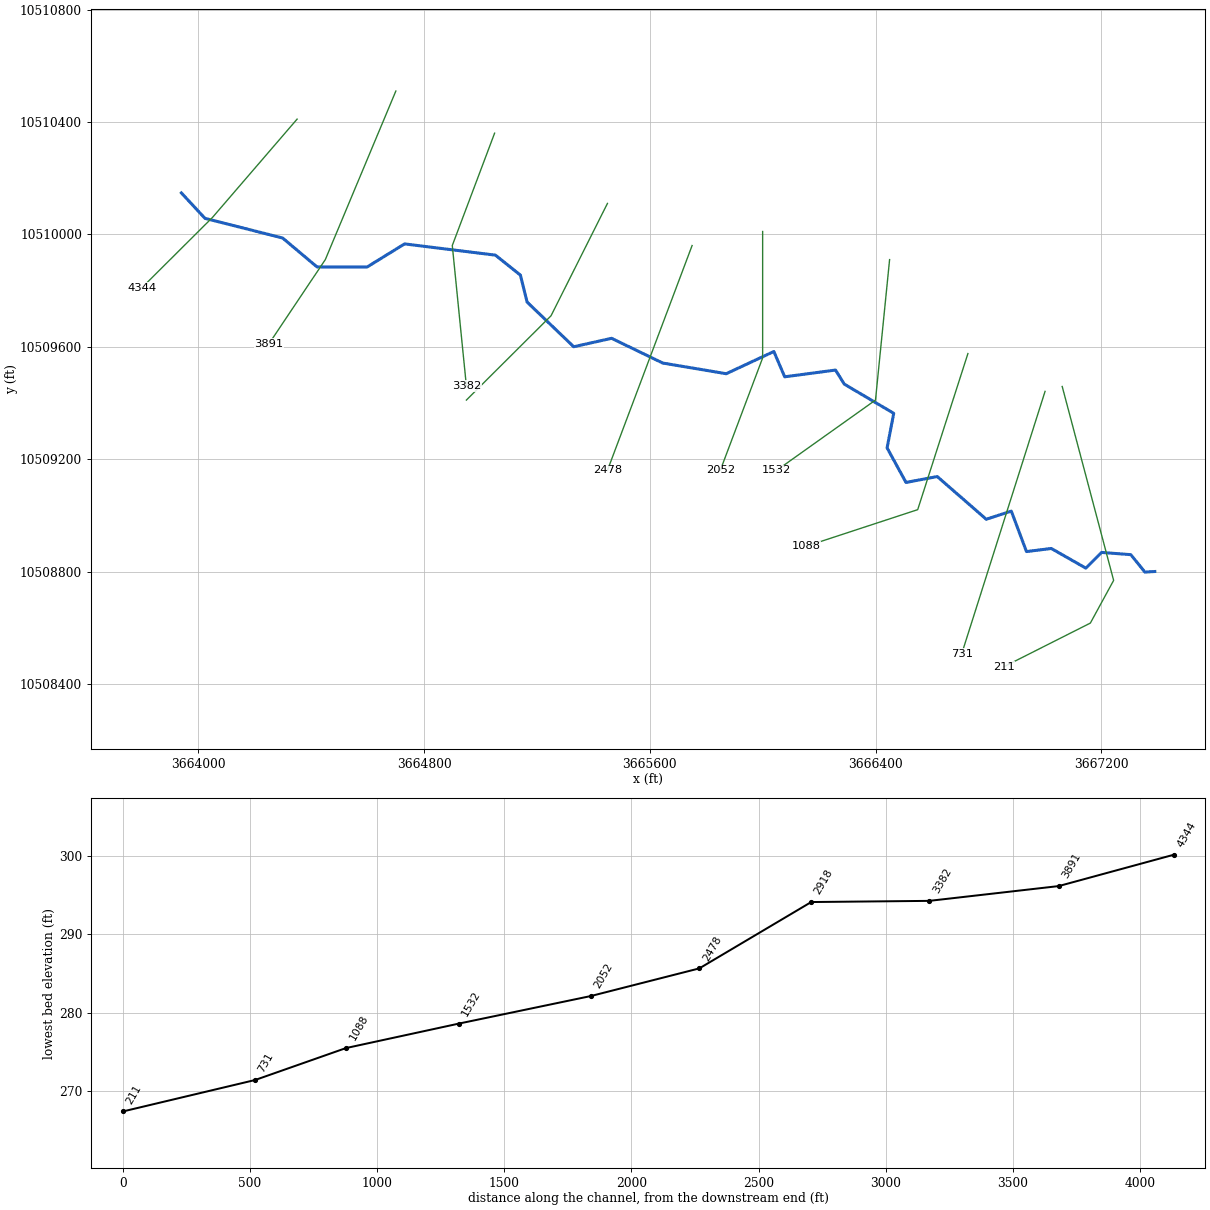
--- UNT 163 IN BUCR.prj (project) ---

Proj Title=UNT 163 IN BUCR Base Level Engineering
Current Plan=p01
Default Exp/Contr=0.3,0.1
English Units
Geom File=g01
Flow File=f01
Plan File=p01
BEGIN DESCRIPTION:
UNT 163 IN BUCR
END DESCRIPTION:

--- UNT 163 IN BUCR.p01 (plan) ---

Plan Title=Multiple Run
Short Identifier=Multiple
Geom File=g01
Flow File=f01
Subcritical Flow
K Sum by GR= 0
Std Step Tol= 0.01
Critical Tol= 0.01
Num of Std Step Trials= 20
Max Error Tol= 0.3
Flow Tol Ratio= 0.001
Split Flow NTrial= 30
Split Flow Tol= 0.02
Split Flow Ratio= 0.02
Log Output Level= 0
Friction Slope Method= 1
Unsteady Friction Slope Method= 2
Unsteady Bridges Friction Slope Method= 1
Parabolic Critical Depth
Global Vel Dist=  1 , 1 , 1
Global Log Level= 0
CheckData=True
Encroach Param= -1, 0, 0, 0
BEGIN DESCRIPTION:
Multiple Run
END DESCRIPTION:

--- UNT 163 IN BUCR.f01 (steady flow) ---

Flow Title=Multiple
Number of Profiles=7
Profile Names=10-year,25-year,50-year,1pct_min,100-year,1pct_plu,500-year
River Rch & RM= UNT 163 IN BUCR,Reach-1,4344
     522     705     856     764    1033    1397    1510
Boundary for River Rch & Prof#=UNT 163 IN BUCR,Reach-1,1
Up Type=0
Dn Type=3
Dn Slope=0.005
Boundary for River Rch & Prof#=UNT 163 IN BUCR,Reach-1,2
Up Type=0
Dn Type=3
Dn Slope=0.005
Boundary for River Rch & Prof#=UNT 163 IN BUCR,Reach-1,3
Up Type=0
Dn Type=3
Dn Slope=0.005
Boundary for River Rch & Prof#=UNT 163 IN BUCR,Reach-1,4
Up Type=0
Dn Type=3
Dn Slope=0.005
Boundary for River Rch & Prof#=UNT 163 IN BUCR,Reach-1,5
Up Type=0
Dn Type=3
Dn Slope=0.005
Boundary for River Rch & Prof#=UNT 163 IN BUCR,Reach-1,6
Up Type=0
Dn Type=3
Dn Slope=0.005
Boundary for River Rch & Prof#=UNT 163 IN BUCR,Reach-1,7
Up Type=0
Dn Type=3
Dn Slope=0.005

--- UNT 163 IN BUCR.g01 (geometry) ---

Geom Title=Existing Conditions

River Reach=UNT 163 IN BUCR,Reach-1
Reach XY= 30
      3663939.43     10510147.46      3664023.00     10510057.00
      3664298.25     10509987.00      3664420.25     10509884.00
      3664598.00     10509884.00      3664730.50     10509966.00
      3665052.50     10509926.00      3665141.00     10509855.00
      3665164.75     10509759.00      3665330.00     10509600.00
      3665464.25     10509630.00      3665645.50     10509542.00
      3665870.50     10509504.00      3666039.25     10509583.00
      3666077.75     10509493.00      3666258.00     10509517.00
      3666289.00     10509467.00      3666464.25     10509363.00
      3666440.75     10509240.00      3666507.75     10509117.00
      3666618.50     10509138.00      3666792.25     10508986.00
      3666881.00     10509015.00      3666934.75     10508871.00
      3667022.75     10508882.00      3667145.25     10508812.00
      3667200.75     10508868.00      3667304.50     10508860.00
      3667354.50     10508798.00      3667389.50     10508800.00

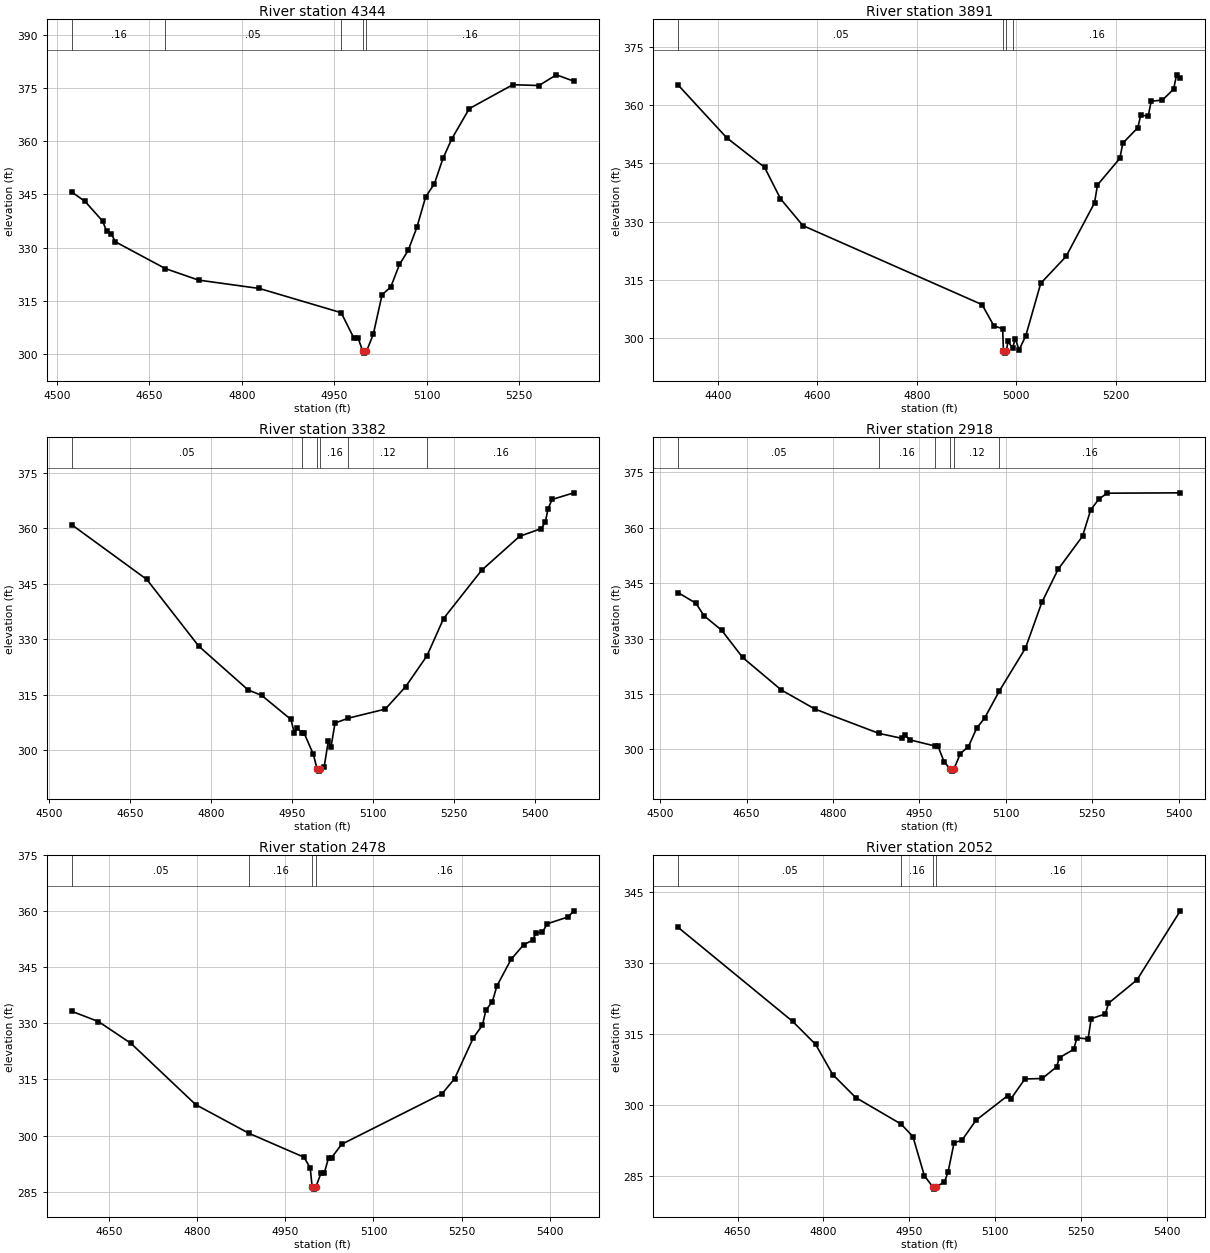
Type RM Length L Ch R = 1,4344,453,453,453
BEGIN DESCRIPTION:
UNT 163 IN BUCR 9.0
END DESCRIPTION:
XS GIS Cut Line= 3
      3664349.58     10510410.15      3664049.61     10510060.19
      3663799.60     10509810.18
#Sta/Elev= 30
  4524.3  345.65  4545.7  343.04  4574.2  337.49  4580.8  334.68  4588.5  333.84
  4595.0  331.62  4676.1  324.05  4730.0  320.80  4828.8  318.43  4961.3  311.60
  4981.9  304.45  4988.8  304.45  4996.4  300.68  4999.1  300.18  5002.4  300.68
  5013.5  305.54  5027.7  316.68  5041.8  318.84  5055.9  325.22  5070.1  329.19
  5084.2  335.73  5098.4  344.30  5112.5  347.98  5126.6  355.20  5140.8  360.68
  5169.1  369.21  5239.8  375.97  5282.2  375.74  5310.5  378.76  5338.8  376.96
#Mann=5,-1,0
  4524.3    0.16       0  4676.1    0.05       0  4961.3    0.16       0
  4996.4    0.07       0  5002.4    0.16       0
Bank Sta=4996.4,5002.4
Exp/Cntr=0.3,0.1

Type RM Length L Ch R = 1,3891,509,509,509
BEGIN DESCRIPTION:
UNT 163 IN BUCR 8.0
END DESCRIPTION:
XS GIS Cut Line= 3
      3664699.60     10510510.16      3664449.61     10509910.19
      3664249.62     10509610.21
#Sta/Elev= 30
  4319.8  365.08  4417.3  351.55  4493.6  343.94  4525.6  335.87  4570.6  328.97
  4931.3  308.64  4955.1  303.19  4972.8  302.43  4974.3  296.67  4977.0  296.17
  4980.3  296.67  4983.3  299.17  4992.7  297.55  4998.3  299.86  5005.8  296.99
  5019.3  300.64  5049.4  314.12  5100.5  321.06  5157.6  334.79  5163.6  339.42
  5208.6  346.25  5214.6  350.16  5244.7  354.13  5250.7  357.36  5265.7  357.12
  5271.7  360.96  5294.3  361.22  5316.8  364.05  5322.8  367.73  5330.3  366.80
#Mann=4,-1,0
  4319.8    0.05       0  4974.3    0.07       0  4980.3    0.05       0
  4992.7    0.16       0
Bank Sta=4974.3,4980.3
Exp/Cntr=0.3,0.1

Type RM Length L Ch R = 1,3382,464,464,464
BEGIN DESCRIPTION:
UNT 163 IN BUCR 7.0
END DESCRIPTION:
XS GIS Cut Line= 3
      3665049.63     10510360.24      3664899.61     10509960.19
      3664949.60     10509460.23
#Sta/Elev= 30
  4542.4  360.93  4681.3  346.14  4777.4  328.11  4869.1  316.23  4894.0  314.78
  4948.3  308.25  4954.5  304.56  4959.9  305.89  4968.6  304.71  4972.2  304.71
  4989.8  298.80  4996.8  294.78  4999.5  294.28  5002.8  294.78  5009.8  295.46
  5017.4  302.40  5022.4  300.80  5029.9  307.29  5054.8  308.62  5122.9  311.06
  5160.6  317.12  5200.2  325.49  5230.9  335.57  5301.3  348.61  5371.6  357.80
  5411.8  359.90  5419.4  361.71  5424.4  365.32  5431.9  367.78  5472.1  369.57
#Mann=6,-1,0
  4542.4    0.05       0  4968.6    0.16       0  4996.8    0.07       0
  5002.8    0.16       0  5054.8    0.12       0  5200.2    0.16       0
Bank Sta=4996.8,5002.8
Exp/Cntr=0.3,0.1

Type RM Length L Ch R = 1,2918,440,440,440
BEGIN DESCRIPTION:
UNT 163 IN BUCR 6.0
END DESCRIPTION:
XS GIS Cut Line= 3
      3665449.59     10510110.15      3665249.61     10509710.19
      3664949.63     10509410.21
#Sta/Elev= 30
  4531.5  342.42  4562.2  339.57  4576.2  336.19  4606.9  332.25  4643.3  324.89
  4710.3  316.10  4769.0  310.91  4879.7  304.35  4920.0  302.99  4925.6  303.78
  4933.9  302.58  4976.5  300.95  4982.2  300.95  4992.8  296.70  5003.9  294.63
  5006.7  294.13  5009.9  294.63  5021.1  298.89  5035.2  300.77  5049.4  305.73
  5063.5  308.56  5089.0  315.87  5134.2  327.44  5162.5  339.78  5190.8  348.75
  5233.2  357.71  5247.4  364.87  5261.5  367.72  5275.7  369.35  5402.9  369.45
#Mann=6,-1,0
  4531.5    0.05       0  4879.7    0.16       0  4976.5    0.12       0
  5003.9    0.07       0  5009.9    0.12       0  5089.0    0.16       0
Bank Sta=5003.9,5009.9
Exp/Cntr=0.3,0.1

Type RM Length L Ch R = 1,2478,426,426,426
BEGIN DESCRIPTION:
UNT 163 IN BUCR 5.0
END DESCRIPTION:
XS GIS Cut Line= 3
      3665749.61     10509960.19      3665599.61     10509560.19
      3665449.61     10509160.19
#Sta/Elev= 30
  4586.6  333.25  4632.0  330.51  4687.2  324.69  4797.5  308.27  4888.3  300.58
  4981.8  294.19  4992.4  291.33  4995.7  286.15  4998.4  285.65  5001.7  286.15
  5011.1  290.06  5016.5  290.06  5023.6  294.05  5028.9  294.10  5045.8  297.65
  5216.7  311.17  5238.1  315.23  5270.1  326.21  5285.3  329.49  5291.5  333.62
  5302.2  335.82  5310.2  340.08  5334.2  347.15  5355.6  351.08  5370.7  352.27
  5376.9  354.26  5387.6  354.41  5395.6  356.68  5431.2  358.51  5441.0  360.15
#Mann=4,-1,0
  4586.6    0.05       0  4888.3    0.16       0  4995.7    0.07       0
  5001.7    0.16       0
Bank Sta=4995.7,5001.7
Exp/Cntr=0.3,0.1

Type RM Length L Ch R = 1,2052,520,520,520
BEGIN DESCRIPTION:
UNT 163 IN BUCR 4.0
END DESCRIPTION:
XS GIS Cut Line= 3
      3665999.61     10510010.15      3665999.61     10509560.19
      3665849.60     10509160.16
#Sta/Elev= 30
  4546.3  337.44  4746.3  317.57  4786.3  312.72  4816.3  306.34  4856.3  301.49
  4935.6  295.88  4956.3  293.24  4976.3  284.97  4990.8  282.62  4993.5  282.12
  4996.8  282.62  5011.4  283.61  5017.6  285.69  5028.3  291.95  5041.7  292.41
  5066.6  296.69  5121.8  301.87  5127.1  301.14  5152.0  305.41  5182.3  305.51
  5207.2  307.96  5212.5  309.93  5237.5  311.69  5242.8  314.13  5262.4  313.85
  5267.7  318.16  5292.6  319.16  5298.0  321.42  5347.8  326.36  5423.5  340.96
#Mann=4,-1,0
  4546.3    0.05       0  4935.6    0.16       0  4990.8    0.07       0
  4996.8    0.16       0
Bank Sta=4990.8,4996.8
Exp/Cntr=0.3,0.1

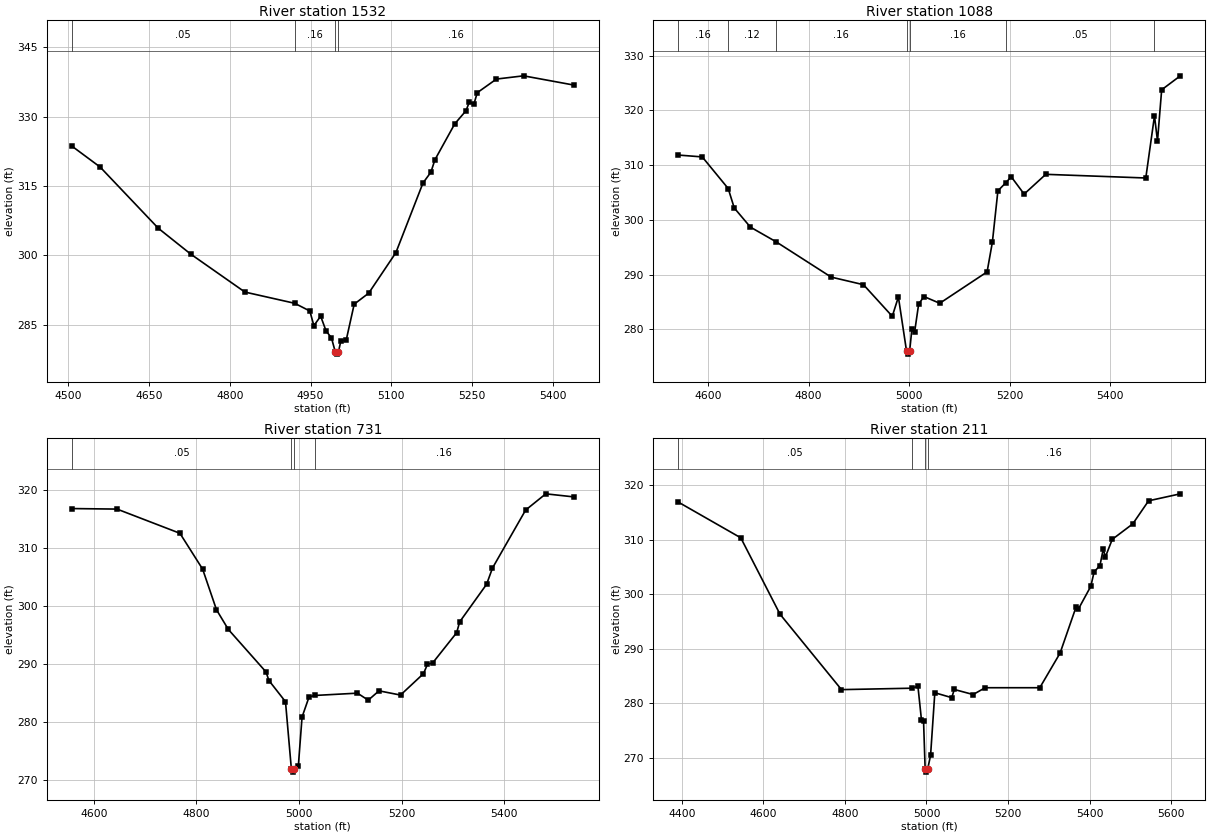
Type RM Length L Ch R = 1,1532,444,444,444
BEGIN DESCRIPTION:
UNT 163 IN BUCR 3.0
END DESCRIPTION:
XS GIS Cut Line= 3
      3666449.61     10509910.15      3666399.61     10509410.19
      3666049.59     10509160.17
#Sta/Elev= 30
  4506.4  323.62  4559.1  319.07  4667.2  305.82  4727.5  300.22  4828.0  292.02
  4920.5  289.59  4948.6  287.92  4956.1  284.75  4968.7  286.80  4978.7  283.63
  4988.8  282.10  4995.8  279.09  4998.6  278.59  5001.8  279.09  5006.3  281.52
  5016.2  281.64  5031.0  289.40  5058.0  291.79  5108.4  300.54  5158.8  315.63
  5173.5  317.96  5180.9  320.64  5217.8  328.42  5238.7  331.26  5244.8  333.13
  5253.4  332.70  5259.6  335.16  5295.2  338.11  5345.6  338.81  5439.0  336.81
#Mann=4,-1,0
  4506.4    0.05       0  4920.5    0.16       0  4995.8    0.07       0
  5001.8    0.16       0
Bank Sta=4995.8,5001.8
Exp/Cntr=0.3,0.1

Type RM Length L Ch R = 1,1088,357,357,357
BEGIN DESCRIPTION:
UNT 163 IN BUCR 2.0
END DESCRIPTION:
XS GIS Cut Line= 3
      3666727.20     10509575.74      3666549.24     10509020.19
      3666154.41     10508890.02
#Sta/Elev= 30
  4540.7  311.82  4588.5  311.48  4640.1  305.71  4652.2  302.15  4684.3  298.66
  4735.4  295.98  4845.0  289.53  4909.3  288.14  4966.6  282.37  4978.8  285.90
  4995.1  275.96  4997.8  275.46  5001.1  275.96  5005.7  280.06  5011.0  279.45
  5019.1  284.59  5029.6  285.98  5061.1  284.75  5155.3  290.48  5165.8  295.90
  5176.8  305.28  5192.7  306.78  5203.3  307.86  5229.0  304.69  5272.1  308.30
  5471.1  307.63  5488.4  318.97  5494.4  314.39  5502.7  323.74  5539.8  326.29
#Mann=7,-1,0
  4540.7    0.16       0  4640.1    0.12       0  4735.4    0.16       0
  4995.1    0.07       0  5001.1    0.16       0  5192.7    0.05       0
  5488.4    0.16       0
Bank Sta=4995.1,5001.1
Exp/Cntr=0.3,0.1

Type RM Length L Ch R = 1,731,520,520,520
BEGIN DESCRIPTION:
Mapping XS cae0d835
END DESCRIPTION:
XS GIS Cut Line= 2
      3667000.63     10509441.19      3666705.50     10508508.05
#Sta/Elev= 30
  4557.2  316.80  4645.4  316.71  4768.0  312.54  4812.3  306.36  4839.3  299.36
  4862.4  295.97  4935.8  288.65  4941.5  287.17  4973.8  283.52  4985.3  271.88
  4988.0  271.38  4991.3  271.88  4998.8  272.40  5006.1  280.87  5019.7  284.33
  5030.6  284.59  5114.1  284.99  5135.1  283.78  5156.1  285.39  5198.0  284.66
  5242.8  288.35  5250.5  289.95  5261.0  290.23  5307.4  295.40  5313.4  297.28
  5365.8  303.75  5377.3  306.55  5441.9  316.54  5481.2  319.34  5535.9  318.81
#Mann=4,-1,0
  4557.2    0.05       0  4985.3    0.03       0  4991.3    0.05       0
  5030.6    0.16       0
Bank Sta=4985.3,4991.3
Exp/Cntr=0.3,0.1

Type RM Length L Ch R = 1,211,0,0,0
BEGIN DESCRIPTION:
UNT 163 IN BUCR 1.0
END DESCRIPTION:
XS GIS Cut Line= 4
      3667061.41     10509458.51      3667243.69     10508768.45
      3667161.22     10508616.54      3666853.86     10508460.70
#Sta/Elev= 30
  4391.3  316.89  4544.7  310.33  4640.9  296.32  4791.6  282.49  4963.5  282.75
  4979.1  283.09  4987.7  276.97  4992.9  276.68  4996.8  267.86  4999.6  267.36
  5002.8  267.86  5010.1  270.45  5020.5  281.92  5061.9  281.02  5068.3  282.52
  5114.4  281.59  5144.0  282.84  5277.9  282.84  5327.6  289.18  5366.6  297.59
  5372.2  297.22  5403.0  301.44  5411.1  304.08  5425.4  305.25  5433.4  308.21
  5439.0  306.87  5455.6  310.05  5505.8  312.88  5544.7  317.12  5622.5  318.40
#Mann=4,-1,0
  4391.3    0.05       0  4963.5    0.16       0  4996.8    0.07       0
  5002.8    0.16       0
Bank Sta=4996.8,5002.8
Exp/Cntr=0.3,0.1

Chan Stop Cuts=-1