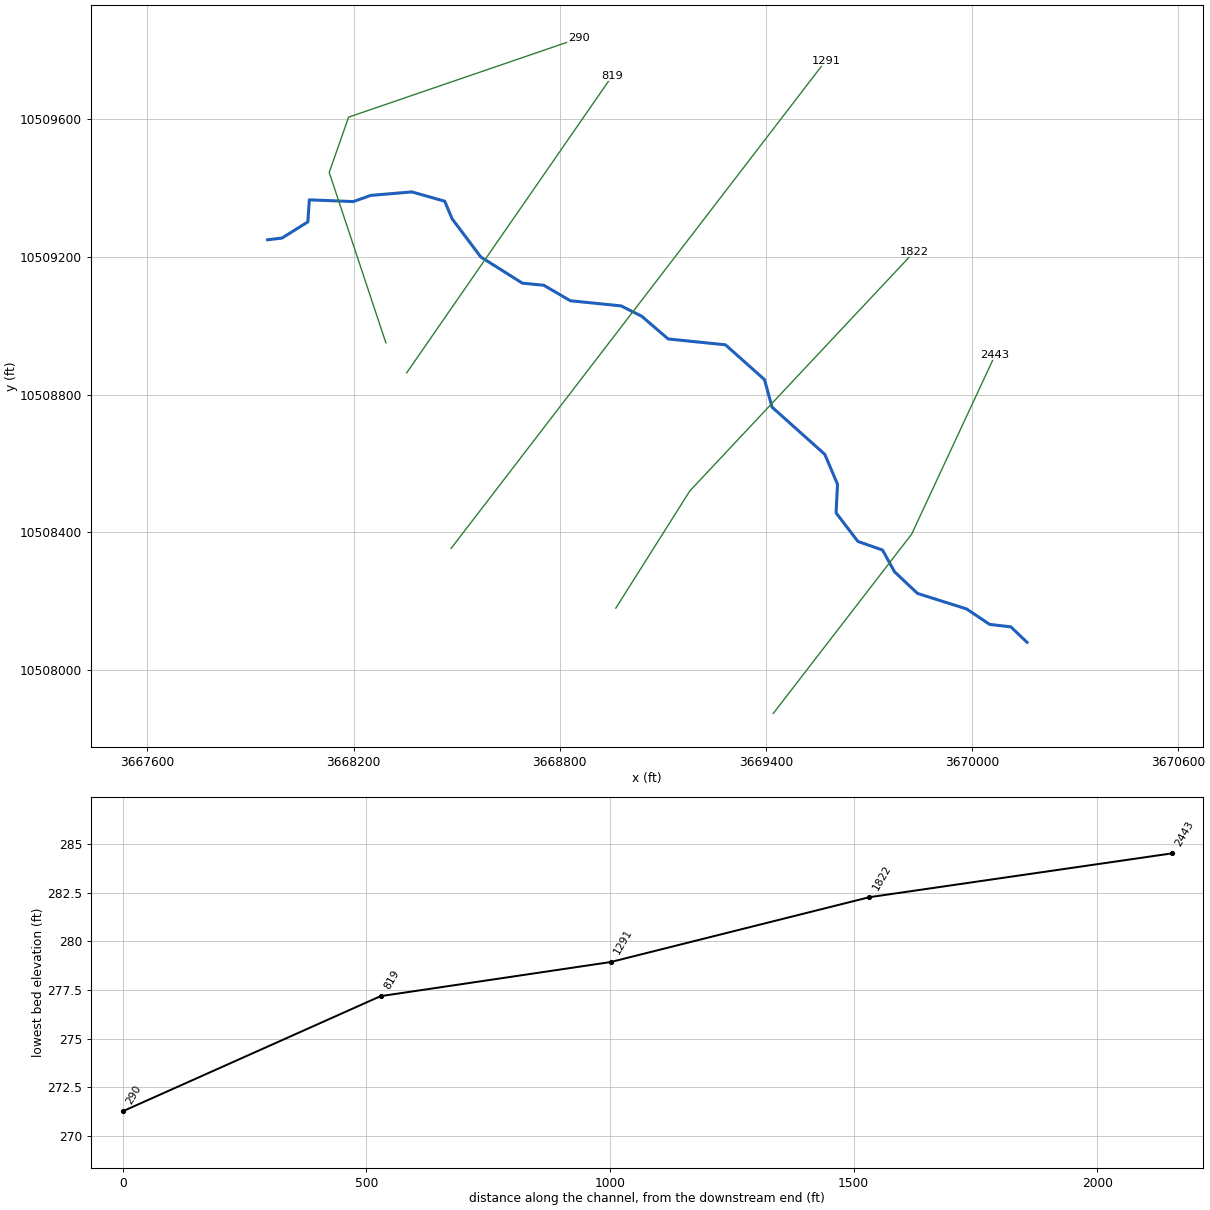
--- UNT 164 IN BUCR.prj (project) ---

Proj Title=UNT 164 IN BUCR Base Level Engineering
Current Plan=p01
Default Exp/Contr=0.3,0.1
English Units
Geom File=g01
Flow File=f01
Plan File=p01
BEGIN DESCRIPTION:
UNT 164 IN BUCR
END DESCRIPTION:

--- UNT 164 IN BUCR.p01 (plan) ---

Plan Title=Multiple Run
Short Identifier=Multiple
Geom File=g01
Flow File=f01
Subcritical Flow
K Sum by GR= 0
Std Step Tol= 0.01
Critical Tol= 0.01
Num of Std Step Trials= 20
Max Error Tol= 0.3
Flow Tol Ratio= 0.001
Split Flow NTrial= 30
Split Flow Tol= 0.02
Split Flow Ratio= 0.02
Log Output Level= 0
Friction Slope Method= 1
Unsteady Friction Slope Method= 2
Unsteady Bridges Friction Slope Method= 1
Parabolic Critical Depth
Global Vel Dist=  1 , 1 , 1
Global Log Level= 0
CheckData=True
Encroach Param= -1, 0, 0, 0
BEGIN DESCRIPTION:
Multiple Run
END DESCRIPTION:

--- UNT 164 IN BUCR.f01 (steady flow) ---

Flow Title=Multiple
Number of Profiles=7
Profile Names=10-year,25-year,50-year,1pct_min,100-year,1pct_plu,500-year
River Rch & RM= UNT 164 IN BUCR,Reach-1,2443
     524     713     870     781    1056    1428    1561
Boundary for River Rch & Prof#=UNT 164 IN BUCR,Reach-1,1
Up Type=0
Dn Type=3
Dn Slope=0.005
Boundary for River Rch & Prof#=UNT 164 IN BUCR,Reach-1,2
Up Type=0
Dn Type=3
Dn Slope=0.005
Boundary for River Rch & Prof#=UNT 164 IN BUCR,Reach-1,3
Up Type=0
Dn Type=3
Dn Slope=0.005
Boundary for River Rch & Prof#=UNT 164 IN BUCR,Reach-1,4
Up Type=0
Dn Type=3
Dn Slope=0.005
Boundary for River Rch & Prof#=UNT 164 IN BUCR,Reach-1,5
Up Type=0
Dn Type=3
Dn Slope=0.005
Boundary for River Rch & Prof#=UNT 164 IN BUCR,Reach-1,6
Up Type=0
Dn Type=3
Dn Slope=0.005
Boundary for River Rch & Prof#=UNT 164 IN BUCR,Reach-1,7
Up Type=0
Dn Type=3
Dn Slope=0.005

--- UNT 164 IN BUCR.g01 (geometry) ---

Geom Title=Existing Conditions

River Reach=UNT 164 IN BUCR,Reach-1
Reach XY= 30
      3670159.75     10508081.00      3670112.50     10508126.00
      3670051.00     10508133.00      3669983.75     10508178.00
      3669841.00     10508223.00      3669774.00     10508286.00
      3669739.25     10508349.00      3669667.50     10508374.00
      3669604.00     10508457.00      3669608.25     10508540.00
      3669571.25     10508627.00      3669417.75     10508764.00
      3669395.75     10508844.00      3669282.25     10508945.00
      3669115.50     10508962.00      3669038.50     10509028.00
      3668978.50     10509058.00      3668830.75     10509073.00
      3668753.50     10509118.00      3668691.25     10509124.00
      3668570.25     10509200.00      3668486.75     10509311.00
      3668465.25     10509362.00      3668369.75     10509389.00
      3668250.25     10509379.00      3668199.50     10509361.00
      3668071.25     10509366.00      3668067.00     10509302.00
      3667991.75     10509255.00      3667949.75     10509250.00

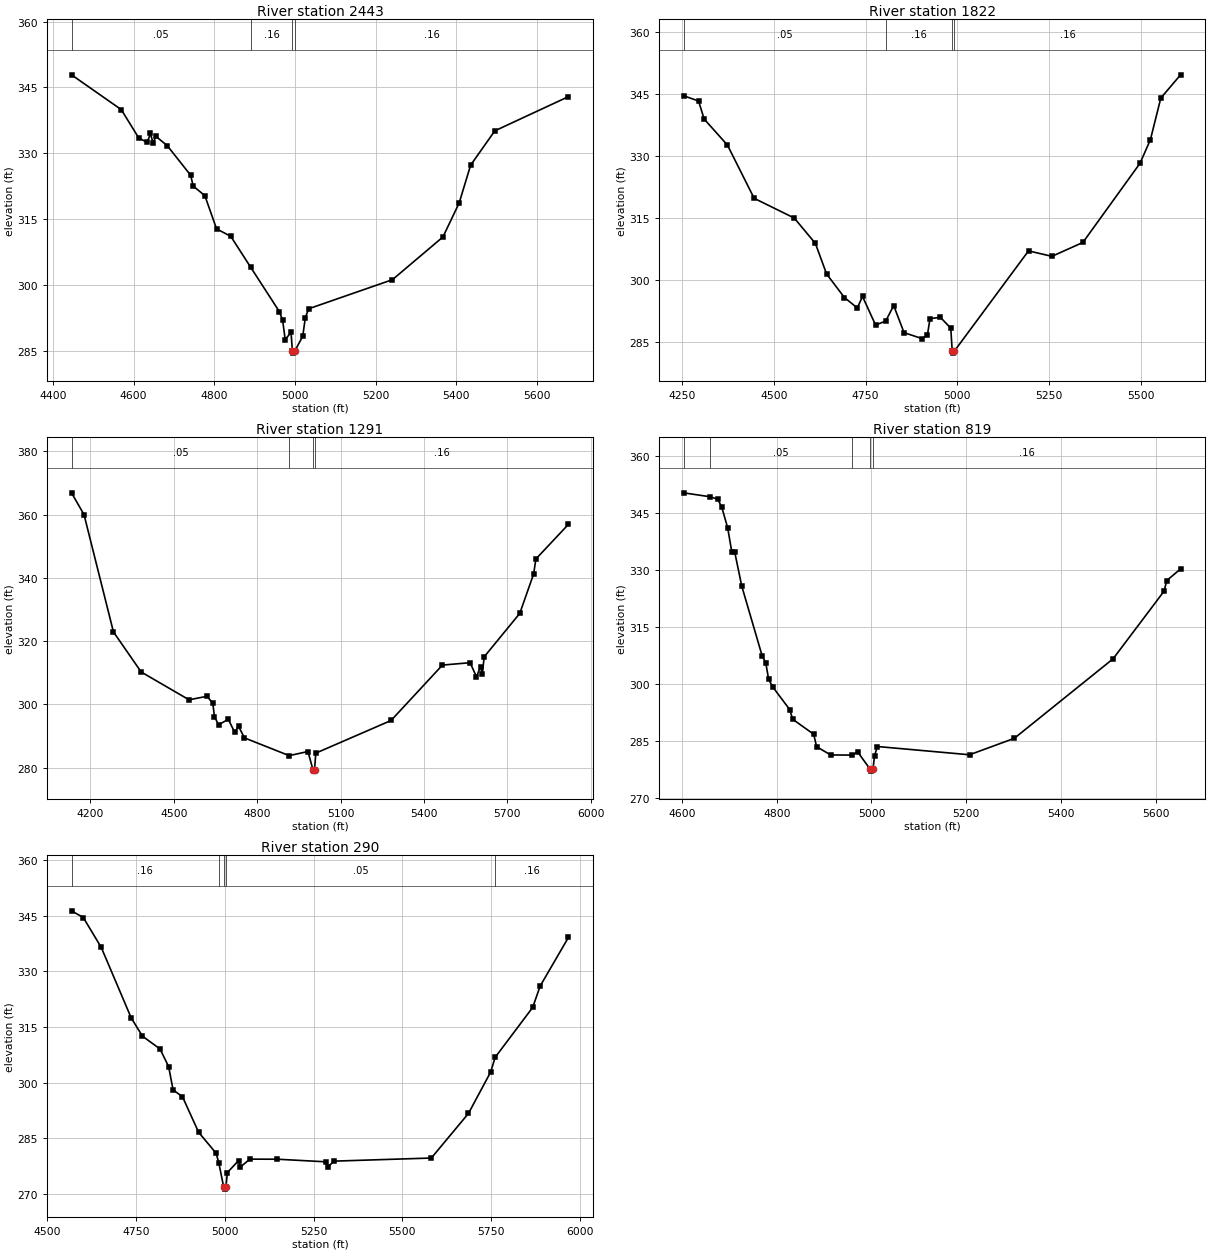
Type RM Length L Ch R = 1,2443,621,621,621
BEGIN DESCRIPTION:
UNT 164 IN BUCR 3.0
END DESCRIPTION:
XS GIS Cut Line= 3
      3669421.42     10507874.68      3669824.20     10508395.52
      3670066.97     10508915.74
#Sta/Elev= 30
  4446.0  347.87  4569.4  339.95  4612.8  333.50  4633.7  332.48  4641.8  334.52
  4648.1  332.34  4655.2  333.87  4683.5  331.74  4741.4  325.02  4747.8  322.55
  4776.7  320.36  4805.7  312.81  4841.0  311.10  4890.3  304.07  4961.5  293.97
  4969.6  292.00  4975.9  287.60  4990.4  289.25  4993.8  285.02  4996.5  284.52
  4999.8  285.02  5019.4  288.35  5025.8  292.54  5033.9  294.61  5241.9  301.24
  5367.2  310.97  5407.4  318.71  5435.8  327.31  5495.8  335.12  5678.5  342.91
#Mann=4,-1,0
  4446.0    0.05       0  4890.3    0.16       0  4993.8    0.07       0
  4999.8    0.16       0
Bank Sta=4993.8,4999.8
Exp/Cntr=0.3,0.1

Type RM Length L Ch R = 1,1822,531,531,531
BEGIN DESCRIPTION:
Mapping XS 6a9cb330
END DESCRIPTION:
XS GIS Cut Line= 3
      3668963.09     10508180.24      3669178.37     10508520.52
      3669831.12     10509214.93
#Sta/Elev= 30
  4253.4  344.52  4294.2  343.25  4309.5  338.88  4373.0  332.59  4445.9  319.71
  4555.3  314.94  4612.9  308.81  4643.5  301.41  4692.1  295.72  4727.3  293.20
  4741.5  295.98  4777.1  289.06  4804.8  290.03  4826.5  293.78  4854.8  287.22
  4904.1  285.78  4918.3  286.54  4925.6  290.61  4953.9  290.93  4982.3  288.30
  4986.1  282.77  4988.9  282.27  4992.1  282.77  5194.3  307.00  5258.2  305.68
  5342.7  309.04  5498.5  328.19  5526.9  333.92  5555.2  343.96  5609.1  349.58
#Mann=4,-1,0
  4253.4    0.05       0  4804.8    0.16       0  4986.1    0.07       0
  4992.1    0.16       0
Bank Sta=4986.1,4992.1
Exp/Cntr=0.3,0.1

Type RM Length L Ch R = 1,1291,472,472,472
BEGIN DESCRIPTION:
Mapping XS 4f4270b6
END DESCRIPTION:
XS GIS Cut Line= 2
      3668483.90     10508353.82      3669574.21     10509770.53
#Sta/Elev= 30
  4132.0  366.85  4177.0  359.97  4282.9  322.90  4382.6  310.26  4554.8  301.47
  4619.1  302.57  4640.0  300.47  4646.3  296.16  4660.8  293.58  4696.1  295.31
  4718.8  291.22  4733.1  293.06  4754.1  289.44  4915.0  283.83  4982.5  285.14
  5000.3  279.44  5003.0  278.94  5006.3  279.44  5010.7  284.62  5281.5  294.94
  5466.3  312.44  5565.9  313.19  5588.7  308.71  5603.2  311.97  5609.5  309.50
  5616.4  315.04  5744.5  328.77  5794.3  341.22  5802.5  345.96  5919.7  356.91
#Mann=4,-1,0
  4132.0    0.05       0  4915.0    0.16       0  5000.3    0.07       0
  5006.3    0.16       0
Bank Sta=5000.3,5006.3
Exp/Cntr=0.3,0.1

Type RM Length L Ch R = 1,819,529,529,529
BEGIN DESCRIPTION:
UNT 164 IN BUCR 2.0
END DESCRIPTION:
XS GIS Cut Line= 2
      3668354.80     10508863.93      3668952.92     10509726.44
#Sta/Elev= 30
  4603.2  350.35  4658.9  349.32  4675.4  348.67  4683.8  346.57  4696.3  341.15
  4705.1  334.74  4711.2  334.75  4726.1  325.80  4769.0  307.54  4776.7  305.69
  4782.8  301.33  4791.6  299.30  4827.4  293.36  4833.5  290.84  4878.0  286.88
  4884.1  283.62  4913.8  281.44  4959.9  281.41  4970.6  282.28  4997.2  277.69
  5000.0  277.19  5003.2  277.69  5006.4  281.20  5012.5  283.66  5207.1  281.49
  5301.6  285.81  5510.3  306.72  5617.7  324.46  5623.8  327.30  5652.8  330.35
#Mann=5,-1,0
  4603.2    0.16       0  4658.9    0.05       0  4959.9    0.16       0
  4997.2    0.07       0  5003.2    0.16       0
Bank Sta=4997.2,5003.2
Exp/Cntr=0.3,0.1

Type RM Length L Ch R = 1,290,0,0,0
BEGIN DESCRIPTION:
UNT 164 IN BUCR 1.0
END DESCRIPTION:
XS GIS Cut Line= 4
      3668294.04     10508950.74      3668129.11     10509445.54
      3668185.53     10509606.13      3668855.00     10509835.04
#Sta/Elev= 30
  4568.6  346.27  4601.7  344.47  4652.3  336.42  4736.7  317.41  4768.3  312.50
  4817.8  309.05  4842.1  304.28  4854.6  298.00  4881.0  296.19  4926.4  286.61
  4975.9  280.93  4983.6  278.22  4997.2  271.78  4999.9  271.28  5003.2  271.78
  5007.5  275.76  5039.1  278.97  5044.4  277.26  5070.7  279.36  5148.1  279.34
  5284.5  278.64  5289.7  277.13  5307.0  278.82  5581.7  279.66  5686.2  291.67
  5748.8  302.84  5761.4  306.79  5867.1  320.24  5888.2  326.01  5967.9  339.13
#Mann=5,-1,0
  4568.6    0.16       0  4983.6    0.05       0  4997.2    0.03       0
  5003.2    0.05       0  5761.4    0.16       0
Bank Sta=4997.2,5003.2
Exp/Cntr=0.3,0.1

Chan Stop Cuts=-1