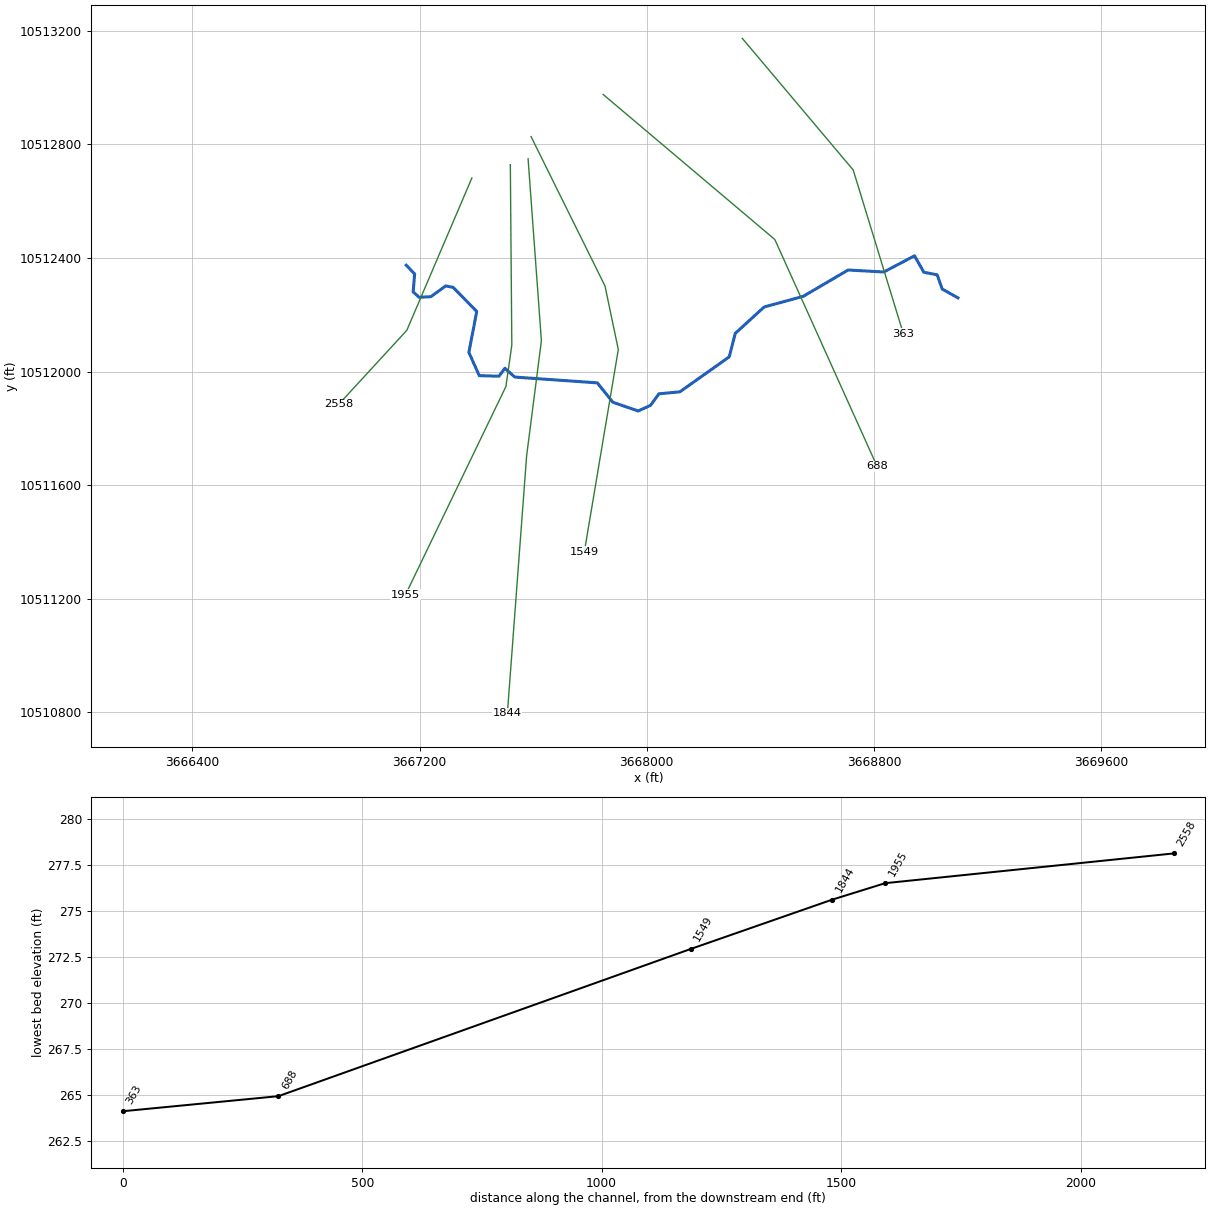
--- UNT 166 IN BUCR.prj (project) ---

Proj Title=UNT 166 IN BUCR Base Level Engineering
Current Plan=p01
Default Exp/Contr=0.3,0.1
English Units
Geom File=g01
Flow File=f01
Plan File=p01
BEGIN DESCRIPTION:
UNT 166 IN BUCR
END DESCRIPTION:

--- UNT 166 IN BUCR.p01 (plan) ---

Plan Title=Multiple Run
Short Identifier=Multiple
Geom File=g01
Flow File=f01
Subcritical Flow
K Sum by GR= 0
Std Step Tol= 0.01
Critical Tol= 0.01
Num of Std Step Trials= 20
Max Error Tol= 0.3
Flow Tol Ratio= 0.001
Split Flow NTrial= 30
Split Flow Tol= 0.02
Split Flow Ratio= 0.02
Log Output Level= 0
Friction Slope Method= 1
Unsteady Friction Slope Method= 2
Unsteady Bridges Friction Slope Method= 1
Parabolic Critical Depth
Global Vel Dist=  1 , 1 , 1
Global Log Level= 0
CheckData=True
Encroach Param= -1, 0, 0, 0
BEGIN DESCRIPTION:
Multiple Run
END DESCRIPTION:

--- UNT 166 IN BUCR.f01 (steady flow) ---

Flow Title=Multiple
Number of Profiles=7
Profile Names=10-year,25-year,50-year,1pct_min,100-year,1pct_plu,500-year
River Rch & RM= UNT 166 IN BUCR,Reach-1,2558
     503     682     830     743    1005    1359    1479
Boundary for River Rch & Prof#=UNT 166 IN BUCR,Reach-1,1
Up Type=0
Dn Type=3
Dn Slope=0.005
Boundary for River Rch & Prof#=UNT 166 IN BUCR,Reach-1,2
Up Type=0
Dn Type=3
Dn Slope=0.005
Boundary for River Rch & Prof#=UNT 166 IN BUCR,Reach-1,3
Up Type=0
Dn Type=3
Dn Slope=0.005
Boundary for River Rch & Prof#=UNT 166 IN BUCR,Reach-1,4
Up Type=0
Dn Type=3
Dn Slope=0.005
Boundary for River Rch & Prof#=UNT 166 IN BUCR,Reach-1,5
Up Type=0
Dn Type=3
Dn Slope=0.005
Boundary for River Rch & Prof#=UNT 166 IN BUCR,Reach-1,6
Up Type=0
Dn Type=3
Dn Slope=0.005
Boundary for River Rch & Prof#=UNT 166 IN BUCR,Reach-1,7
Up Type=0
Dn Type=3
Dn Slope=0.005

--- UNT 166 IN BUCR.g01 (geometry) ---

Geom Title=Existing Conditions

River Reach=UNT 166 IN BUCR,Reach-1
Reach XY= 30
      3667153.25     10512375.00      3667182.75     10512344.00
      3667177.50     10512281.00      3667198.50     10512262.00
      3667240.00     10512264.00      3667292.25     10512302.00
      3667318.25     10512297.00      3667401.50     10512212.00
      3667373.75     10512068.00      3667410.25     10511986.00
      3667479.75     10511984.00      3667500.50     10512012.00
      3667535.25     10511981.00      3667826.05     10511960.53
      3667880.73     10511892.30      3667969.80     10511861.57
      3668013.55     10511881.36      3668043.00     10511922.00
      3668116.75     10511929.00      3668290.50     10512052.00
      3668312.00     10512135.00      3668414.00     10512228.00
      3668550.75     10512265.00      3668709.25     10512358.00
      3668835.00     10512351.00      3668943.25     10512408.00
      3668976.00     10512350.00      3669023.00     10512341.00
      3669040.50     10512291.00      3669096.00     10512260.00

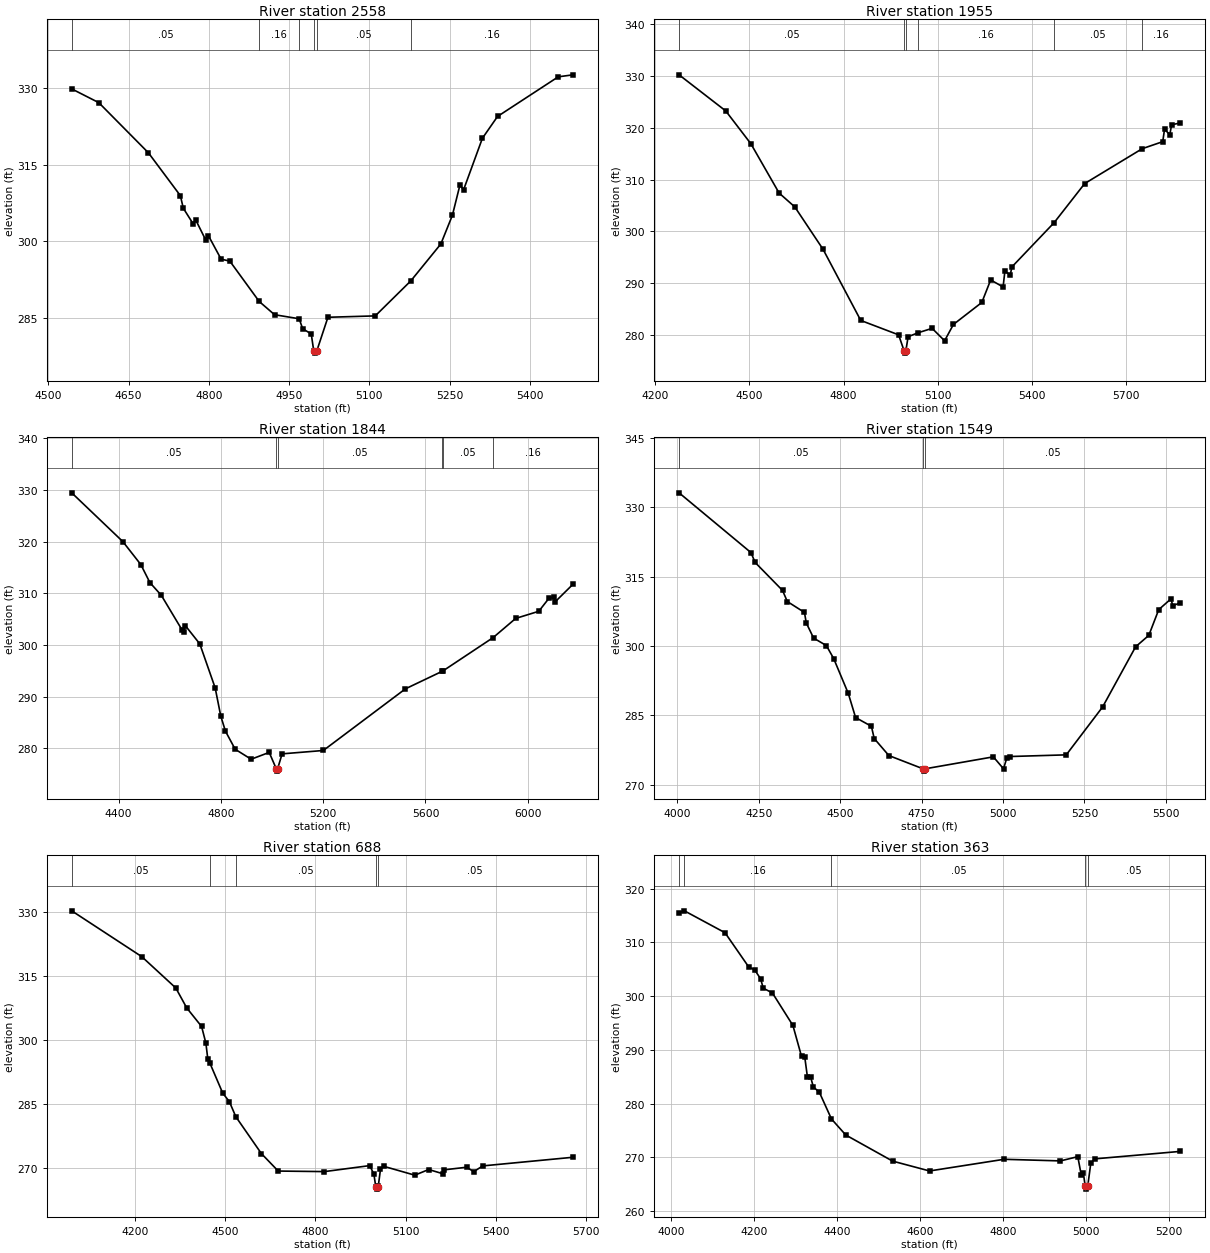
Type RM Length L Ch R = 1,2558,603,603,603
BEGIN DESCRIPTION:
UNT 166 IN BUCR 2.0
END DESCRIPTION:
XS GIS Cut Line= 3
      3667384.36     10512682.02      3667155.19     10512145.57
      3666915.62     10511885.16
#Sta/Elev= 30
  4543.6  329.80  4594.2  327.11  4687.0  317.30  4746.7  308.93  4752.2  306.47
  4770.3  303.47  4775.7  304.12  4793.9  300.30  4799.3  301.08  4822.9  296.51
  4839.2  296.13  4894.1  288.24  4922.8  285.65  4968.8  284.86  4975.4  282.91
  4991.4  281.89  4996.0  278.64  4998.8  278.14  5002.0  278.64  5022.6  285.15
  5111.1  285.42  5177.6  292.27  5233.7  299.48  5255.3  305.09  5269.4  311.01
  5276.2  310.07  5311.4  320.15  5339.7  324.41  5453.2  332.16  5480.8  332.55
#Mann=6,-1,0
  4543.6    0.05       0  4894.1    0.16       0  4968.8    0.05       0
  4996.0    0.03       0  5002.0    0.05       0  5177.6    0.16       0
Bank Sta=4996,5002
Exp/Cntr=0.3,0.1

Type RM Length L Ch R = 1,1955,111,111,111
BEGIN DESCRIPTION:
Mapping XS ffcebb6e
END DESCRIPTION:
XS GIS Cut Line= 4
      3667519.77     10512728.92      3667524.98     10512093.49
      3667504.15     10511947.65      3667150.46     10511214.26
#Sta/Elev= 30
  4275.8  330.24  4424.5  323.27  4504.5  316.94  4594.5  307.42  4644.5  304.74
  4734.5  296.56  4854.6  282.83  4975.2  280.05  4992.4  277.02  4995.2  276.52
  4998.4  277.02  5005.5  279.69  5038.1  280.47  5082.0  281.30  5121.7  278.91
  5149.9  282.06  5240.3  286.30  5268.5  290.65  5308.1  289.29  5313.7  292.31
  5330.8  291.63  5336.3  293.17  5470.9  301.72  5568.0  309.25  5751.3  315.98
  5816.7  317.34  5822.3  319.69  5839.3  318.72  5844.9  320.59  5872.8  320.96
#Mann=6,-1,0
  4275.8    0.05       0  4992.4    0.04       0  4998.4    0.05       0
  5038.1    0.16       0  5470.9    0.05       0  5751.3    0.16       0
Bank Sta=4992.4,4998.4
Exp/Cntr=0.3,0.1

Type RM Length L Ch R = 1,1844,295,295,295
BEGIN DESCRIPTION:
Mapping XS cc85a23f
END DESCRIPTION:
XS GIS Cut Line= 4
      3667582.27     10512749.77      3667629.15     10512109.11
      3667577.07     10511702.86      3667509.36     10510796.64
#Sta/Elev= 30
  4216.4  329.42  4416.5  319.98  4486.7  315.55  4522.1  312.07  4566.9  309.60
  4647.1  302.98  4655.8  302.44  4660.8  303.74  4717.3  300.22  4777.5  291.70
  4799.5  286.23  4817.6  283.35  4855.7  279.85  4918.2  277.92  4988.8  279.24
  5016.0  276.12  5018.7  275.62  5022.0  276.12  5039.2  278.96  5200.5  279.61
  5521.7  291.53  5665.1  294.91  5667.8  294.97  5865.1  301.45  5952.9  305.14
  6043.2  306.52  6083.3  309.05  6102.5  309.31  6107.5  308.36  6177.1  311.75
#Mann=6,-1,0
  4216.4    0.05       0  5016.0    0.04       0  5022.0    0.05       0
  5665.1    0.08       0  5667.8    0.05       0  5865.1    0.16       0
Bank Sta=5016,5022
Exp/Cntr=0.3,0.1

Type RM Length L Ch R = 1,1549,861,861,861
BEGIN DESCRIPTION:
Mapping XS a11e95b5
END DESCRIPTION:
XS GIS Cut Line= 4
      3667592.68     10512827.88      3667853.11     10512301.82
      3667899.98     10512077.86      3667780.26     10511364.74
#Sta/Elev= 30
  4005.6  333.14  4226.2  320.22  4239.1  318.08  4323.3  312.02  4337.8  309.63
  4390.5  307.27  4396.1  304.99  4418.6  301.72  4457.8  300.10  4480.3  297.28
  4525.1  289.74  4547.5  284.53  4596.0  282.64  4604.7  279.99  4649.6  276.31
  4754.7  273.44  4757.5  272.94  4760.7  273.44  4970.4  276.03  5001.6  273.45
  5011.7  275.79  5021.8  276.10  5194.2  276.46  5305.8  286.82  5407.2  299.84
  5447.7  302.31  5478.1  307.87  5515.9  310.22  5521.0  308.71  5544.5  309.36
#Mann=3,-1,0
  4005.6    0.05       0  4754.7    0.03       0  4760.7    0.05       0
Bank Sta=4754.7,4760.7
Exp/Cntr=0.3,0.1

Type RM Length L Ch R = 1,688,325,325,325
BEGIN DESCRIPTION:
Mapping XS f64a5b48
END DESCRIPTION:
XS GIS Cut Line= 3
      3667846.95     10512975.95      3668451.15     10512465.50
      3668811.43     10511666.43
#Sta/Elev= 30
  3989.1  330.36  4222.2  319.58  4335.3  312.22  4371.7  307.53  4421.1  303.17
  4435.4  299.24  4441.9  295.43  4448.9  294.52  4491.4  287.50  4513.4  285.51
  4535.0  281.95  4620.0  273.29  4676.0  269.18  4829.8  269.05  4980.5  270.46
  4994.3  268.44  5000.6  265.43  5003.4  264.93  5006.6  265.43  5009.1  265.77
  5016.2  269.60  5026.7  270.30  5130.3  268.21  5176.5  269.54  5222.8  268.57
  5228.3  269.47  5303.2  270.08  5326.3  269.03  5356.3  270.39  5656.6  272.42
#Mann=5,-1,0
  3989.1    0.05       0  4448.9    0.16       0  4535.0    0.05       0
  5000.6    0.03       0  5006.6    0.05       0
Bank Sta=5000.6,5006.6
Exp/Cntr=0.3,0.1

Type RM Length L Ch R = 1,363,0,0,0
BEGIN DESCRIPTION:
UNT 166 IN BUCR 1.0
END DESCRIPTION:
XS GIS Cut Line= 3
      3668336.55     10513173.86      3668727.20     10512710.29
      3668903.82     10512133.66
#Sta/Elev= 30
  4018.5  315.52  4031.3  315.88  4129.3  311.81  4186.5  305.44  4200.8  304.90
  4215.1  303.25  4221.6  301.49  4243.7  300.60  4293.1  294.56  4313.9  288.80
  4321.7  288.67  4328.2  284.94  4336.0  284.91  4342.5  283.11  4356.8  282.15
  4386.1  277.16  4420.6  274.18  4533.7  269.32  4622.7  267.49  4802.6  269.66
  4938.6  269.36  4980.4  270.15  4988.6  266.79  4993.8  267.12  4998.3  264.61
  5001.1  264.11  5004.3  264.61  5011.8  268.97  5021.3  269.74  5227.8  271.13
#Mann=5,-1,0
  4018.5    0.05       0  4031.3    0.16       0  4386.1    0.05       0
  4998.3    0.03       0  5004.3    0.05       0
Bank Sta=4998.3,5004.3
Exp/Cntr=0.3,0.1

Chan Stop Cuts=-1