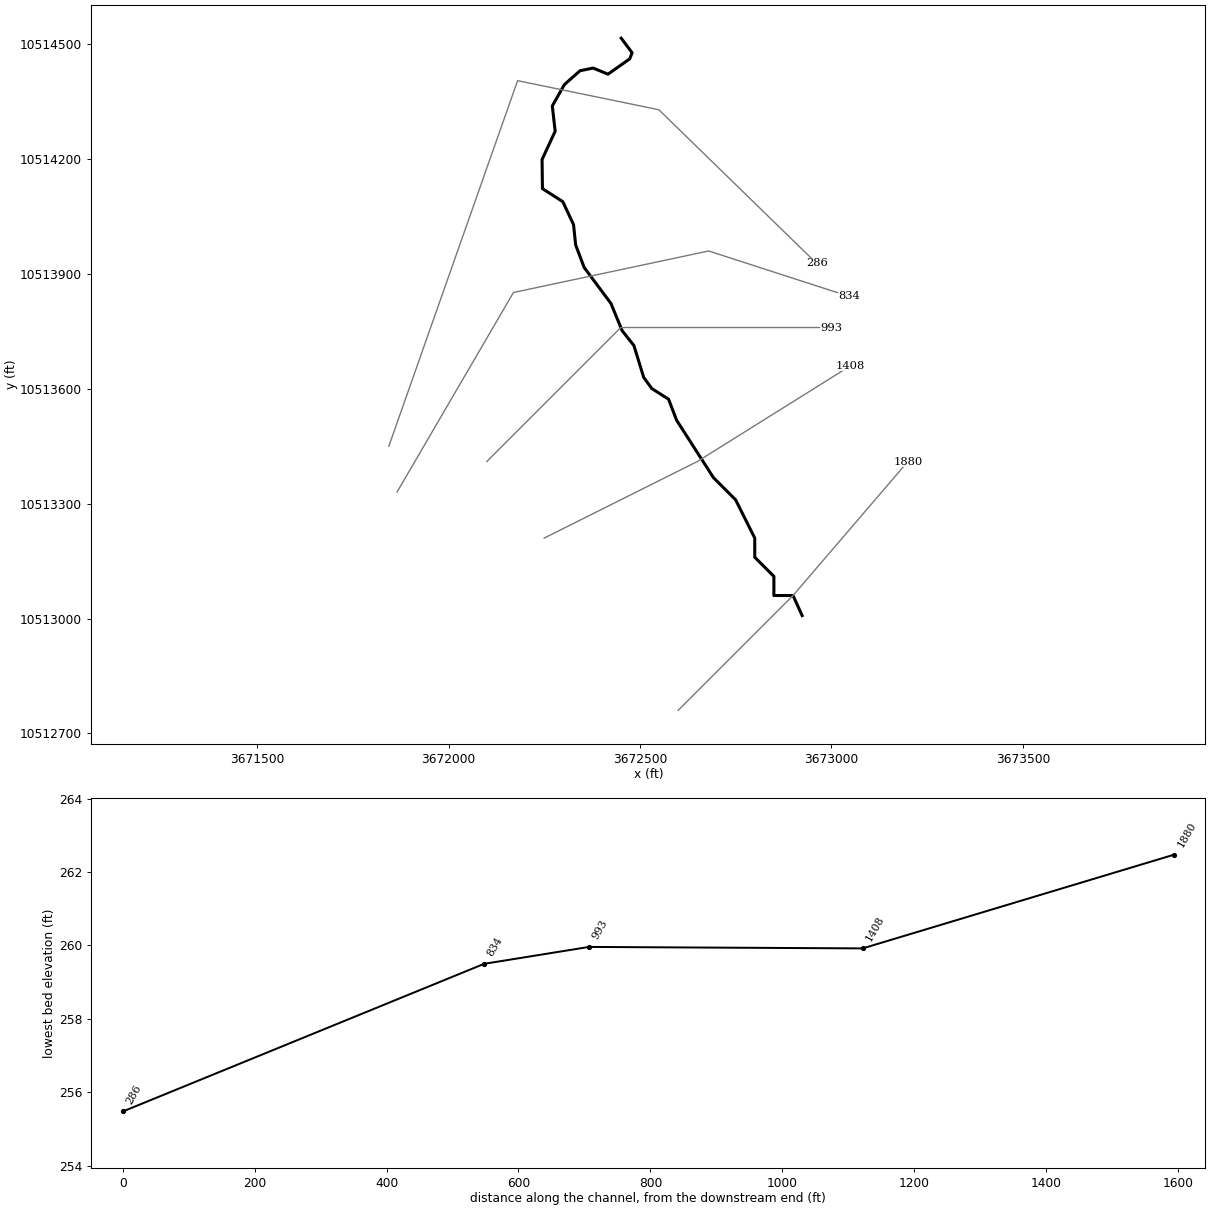
--- UNT 167 IN BUCR.prj (project) ---

Proj Title=UNT 167 IN BUCR Base Level Engineering
Current Plan=p01
Default Exp/Contr=0.3,0.1
English Units
Geom File=g01
Flow File=f01
Plan File=p01
BEGIN DESCRIPTION:
UNT 167 IN BUCR
END DESCRIPTION:

--- UNT 167 IN BUCR.p01 (plan) ---

Plan Title=Multiple Run
Short Identifier=Multiple
Geom File=g01
Flow File=f01
Subcritical Flow
K Sum by GR= 0
Std Step Tol= 0.01
Critical Tol= 0.01
Num of Std Step Trials= 20
Max Error Tol= 0.3
Flow Tol Ratio= 0.001
Split Flow NTrial= 30
Split Flow Tol= 0.02
Split Flow Ratio= 0.02
Log Output Level= 0
Friction Slope Method= 1
Unsteady Friction Slope Method= 2
Unsteady Bridges Friction Slope Method= 1
Parabolic Critical Depth
Global Vel Dist=  1 , 1 , 1
Global Log Level= 0
CheckData=True
Encroach Param= -1, 0, 0, 0
BEGIN DESCRIPTION:
Multiple Run
END DESCRIPTION:

--- UNT 167 IN BUCR.f01 (steady flow) ---

Flow Title=Multiple
Number of Profiles=7
Profile Names=10-year,25-year,50-year,1pct_min,100-year,1pct_plu,500-year
River Rch & RM= UNT 167 IN BUCR,Reach-1,1880
     560     763     932     837    1133    1532    1679
Boundary for River Rch & Prof#=UNT 167 IN BUCR,Reach-1,1
Up Type=0
Dn Type=3
Dn Slope=0.005
Boundary for River Rch & Prof#=UNT 167 IN BUCR,Reach-1,2
Up Type=0
Dn Type=3
Dn Slope=0.005
Boundary for River Rch & Prof#=UNT 167 IN BUCR,Reach-1,3
Up Type=0
Dn Type=3
Dn Slope=0.005
Boundary for River Rch & Prof#=UNT 167 IN BUCR,Reach-1,4
Up Type=0
Dn Type=3
Dn Slope=0.005
Boundary for River Rch & Prof#=UNT 167 IN BUCR,Reach-1,5
Up Type=0
Dn Type=3
Dn Slope=0.005
Boundary for River Rch & Prof#=UNT 167 IN BUCR,Reach-1,6
Up Type=0
Dn Type=3
Dn Slope=0.005
Boundary for River Rch & Prof#=UNT 167 IN BUCR,Reach-1,7
Up Type=0
Dn Type=3
Dn Slope=0.005

--- UNT 167 IN BUCR.g01 (geometry) ---

Geom Title=Existing Conditions

River Reach=UNT 167 IN BUCR,Reach-1
Reach XY= 30
      3672923.44     10513007.81      3672899.61     10513060.19
      3672849.61     10513060.19      3672849.61     10513110.19
      3672799.61     10513160.19      3672799.61     10513210.19
      3672749.61     10513310.19      3672691.84     10513367.96
      3672595.50     10513518.00      3672574.50     10513573.00
      3672530.50     10513601.00      3672509.50     10513630.00
      3672484.00     10513713.00      3672453.25     10513752.00
      3672424.00     10513823.00      3672354.00     10513917.00
      3672331.75     10513976.00      3672326.25     10514029.00
      3672298.25     10514089.00      3672245.00     10514123.00
      3672244.00     10514199.00      3672278.25     10514273.00
      3672270.75     10514339.00      3672302.50     10514395.00
      3672343.25     10514431.00      3672377.50     10514438.00
      3672416.25     10514422.00      3672473.00     10514462.00
      3672479.25     10514478.00      3672450.75     10514516.00

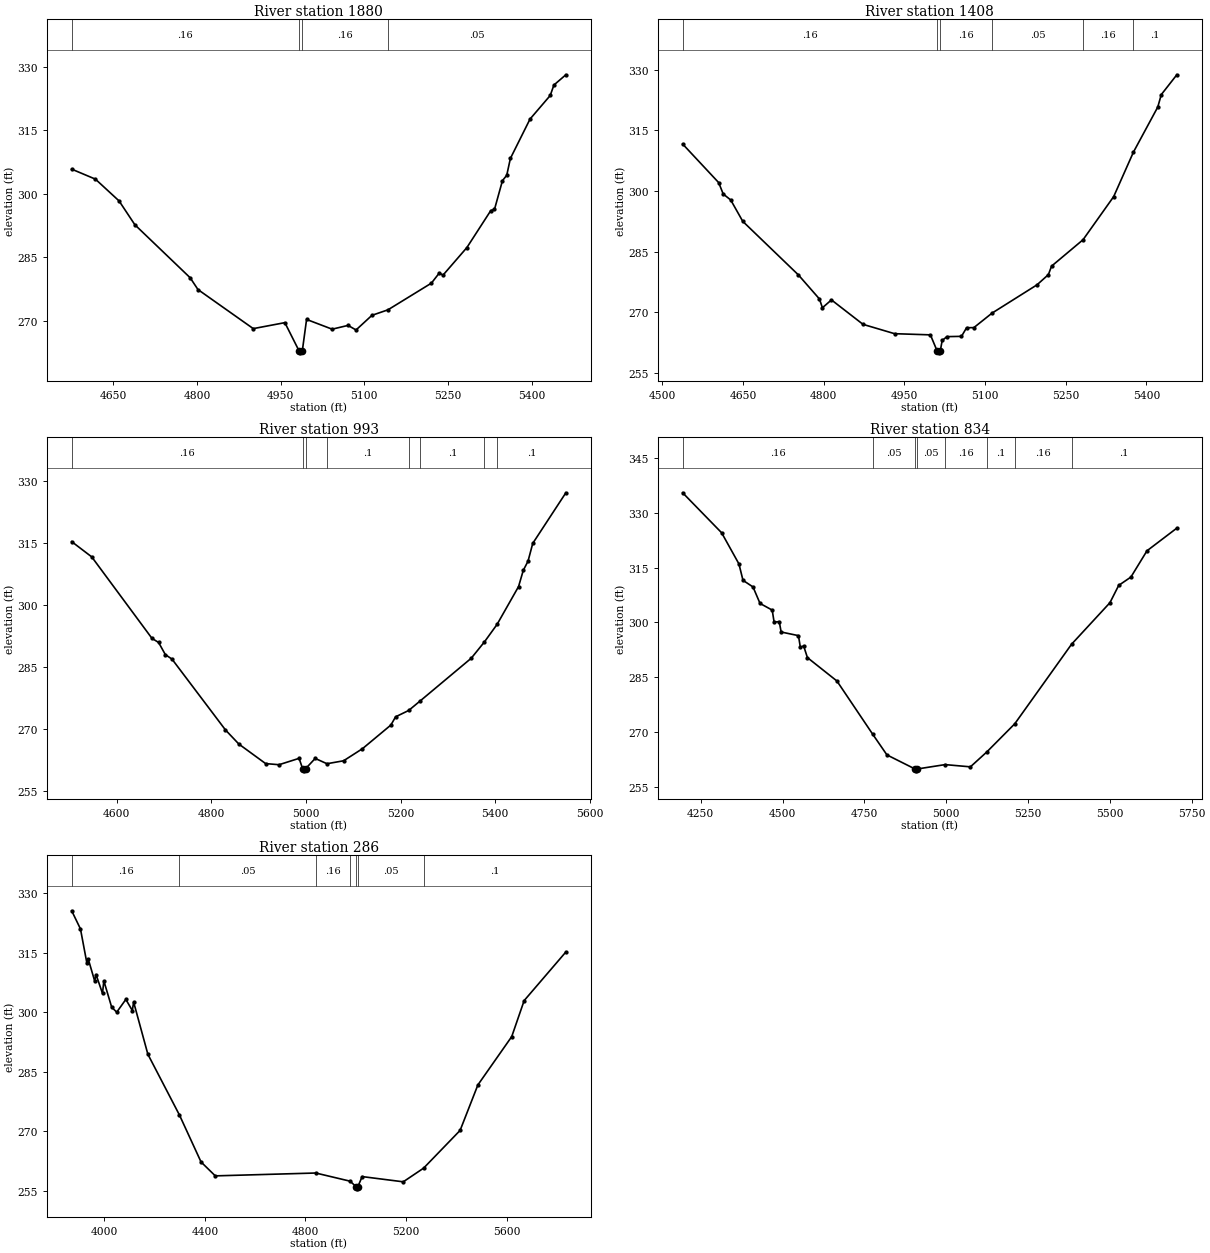
Type RM Length L Ch R = 1,1880,472,472,472
BEGIN DESCRIPTION:
UNT 167 IN BUCR 4.0
END DESCRIPTION:
XS GIS Cut Line= 3
      3672599.58     10512760.16      3672899.61     10513060.19
      3673199.62     10513410.21
#Sta/Elev= 30
  4575.7  305.86  4618.2  303.50  4660.6  298.35  4688.9  292.72  4787.9  280.21
  4802.0  277.41  4901.0  268.19  4957.6  269.60  4982.9  262.97  4985.6  262.47
  4988.9  262.97  4996.5  270.36  5042.3  268.06  5070.8  268.95  5085.1  267.87
  5113.6  271.33  5142.3  272.63  5220.1  278.93  5234.3  281.33  5240.9  280.82
  5283.7  287.34  5326.5  296.07  5333.1  296.33  5347.4  303.14  5355.1  304.41
  5361.6  308.38  5396.8  317.69  5433.0  323.26  5439.6  325.73  5461.0  328.15
#Mann=4,-1,0
  4575.7    0.16       0  4982.9    0.07       0  4988.9    0.16       0
  5142.3    0.05       0
Bank Sta=4982.9,4988.9
Exp/Cntr=0.3,0.1

Type RM Length L Ch R = 1,1408,415,415,415
BEGIN DESCRIPTION:
UNT 167 IN BUCR 3.0
END DESCRIPTION:
XS GIS Cut Line= 3
      3672249.64     10513210.20      3672649.61     10513410.19
      3673049.63     10513660.20
#Sta/Elev= 30
  4537.5  311.60  4604.5  302.05  4612.9  299.24  4626.9  297.75  4649.3  292.46
  4752.7  279.21  4791.8  273.26  4797.4  271.08  4814.2  273.02  4872.9  266.97
  4931.6  264.66  4998.2  264.37  5010.6  260.42  5013.3  259.92  5016.6  260.42
  5020.1  262.98  5028.9  263.93  5056.0  264.00  5065.5  266.14  5079.0  266.16
  5112.9  269.76  5196.4  276.75  5217.6  279.28  5223.5  281.38  5282.0  287.91
  5339.0  298.59  5375.8  309.62  5421.0  320.76  5427.5  323.83  5456.4  328.74
#Mann=6,-1,0
  4537.5    0.16       0  5010.6    0.07       0  5016.6    0.16       0
  5112.9    0.05       0  5282.0    0.16       0  5375.8     0.1       0
Bank Sta=5010.6,5016.6
Exp/Cntr=0.3,0.1

Type RM Length L Ch R = 1,993,159,159,159
BEGIN DESCRIPTION:
UNT 167 IN BUCR 2.0
END DESCRIPTION:
XS GIS Cut Line= 3
      3672099.63     10513410.21      3672449.61     10513760.19
      3672999.57     10513760.19
#Sta/Elev= 30
  4504.7  315.37  4547.1  311.68  4674.4  291.99  4688.5  290.99  4702.7  288.06
  4716.8  286.97  4829.9  269.84  4858.2  266.43  4914.8  261.71  4943.1  261.44
  4985.5  262.98  4993.1  260.46  4995.9  259.96  4999.1  260.46  5019.6  262.96
  5044.5  261.68  5079.6  262.39  5119.6  265.32  5179.6  271.03  5189.6  273.02
  5217.2  274.55  5242.2  276.92  5349.6  287.19  5377.3  291.11  5404.2  295.37
  5449.6  304.51  5459.6  308.44  5469.6  310.64  5479.6  314.95  5549.6  327.18
#Mann=8,-1,0
  4504.7    0.16       0  4993.1    0.07       0  4999.1    0.16       0
  5044.5     0.1       0  5217.2    0.16       0  5242.2     0.1       0
  5377.3    0.16       0  5404.2     0.1       0
Bank Sta=4993.1,4999.1
Exp/Cntr=0.3,0.1

Type RM Length L Ch R = 1,834,548,548,548
BEGIN DESCRIPTION:
Mapping XS 32869d88
END DESCRIPTION:
XS GIS Cut Line= 4
      3671865.45     10513330.87      3672169.25     10513851.68
      3672679.23     10513960.19      3673046.36     10513841.41
#Sta/Elev= 30
  4194.5  335.41  4313.6  324.49  4366.5  315.99  4378.9  311.51  4409.5  309.70
  4431.0  305.20  4468.2  303.38  4474.0  300.10  4489.7  300.24  4495.5  297.40
  4548.4  296.41  4554.2  293.21  4564.2  293.60  4575.8  290.41  4665.9  284.03
  4775.8  269.43  4818.8  263.85  4904.8  260.00  4907.5  259.50  4910.8  260.00
  4996.7  261.20  5073.9  260.59  5123.6  264.62  5209.4  272.34  5383.0  294.06
  5500.3  305.40  5527.1  310.13  5564.4  312.40  5613.5  319.57  5704.7  325.76
#Mann=8,-1,0
  4194.5    0.16       0  4775.8    0.05       0  4904.8    0.07       0
  4910.8    0.05       0  4996.7    0.16       0  5123.6     0.1       0
  5209.4    0.16       0  5383.0     0.1       0
Bank Sta=4904.8,4910.8
Exp/Cntr=0.3,0.1

Type RM Length L Ch R = 1,286,0,0,0
BEGIN DESCRIPTION:
UNT 167 IN BUCR 1.0
END DESCRIPTION:
XS GIS Cut Line= 4
      3671843.73     10513450.19      3672180.10     10514405.07
      3672549.03     10514329.11      3672961.39     10513927.60
#Sta/Elev= 30
  3870.6  325.60  3905.5  321.02  3931.2  312.34  3936.5  313.42  3962.1  307.87
  3967.4  309.51  3993.1  304.77  3998.4  307.93  4029.6  301.28  4049.7  300.03
  4085.9  303.25  4111.6  300.45  4116.9  302.57  4173.5  289.41  4299.2  274.07
  4384.9  262.25  4441.5  258.75  4840.9  259.47  4977.5  257.41  5002.0  255.98
  5004.8  255.48  5008.0  255.98  5025.4  258.57  5188.8  257.25  5269.7  260.70
  5414.8  270.22  5485.5  281.69  5620.0  293.87  5669.4  302.95  5835.2  315.21
#Mann=7,-1,0
  3870.6    0.16       0  4299.2    0.05       0  4840.9    0.16       0
  4977.5    0.05       0  5002.0    0.03       0  5008.0    0.05       0
  5269.7     0.1       0
Bank Sta=5002,5008
Exp/Cntr=0.3,0.1

Chan Stop Cuts=-1