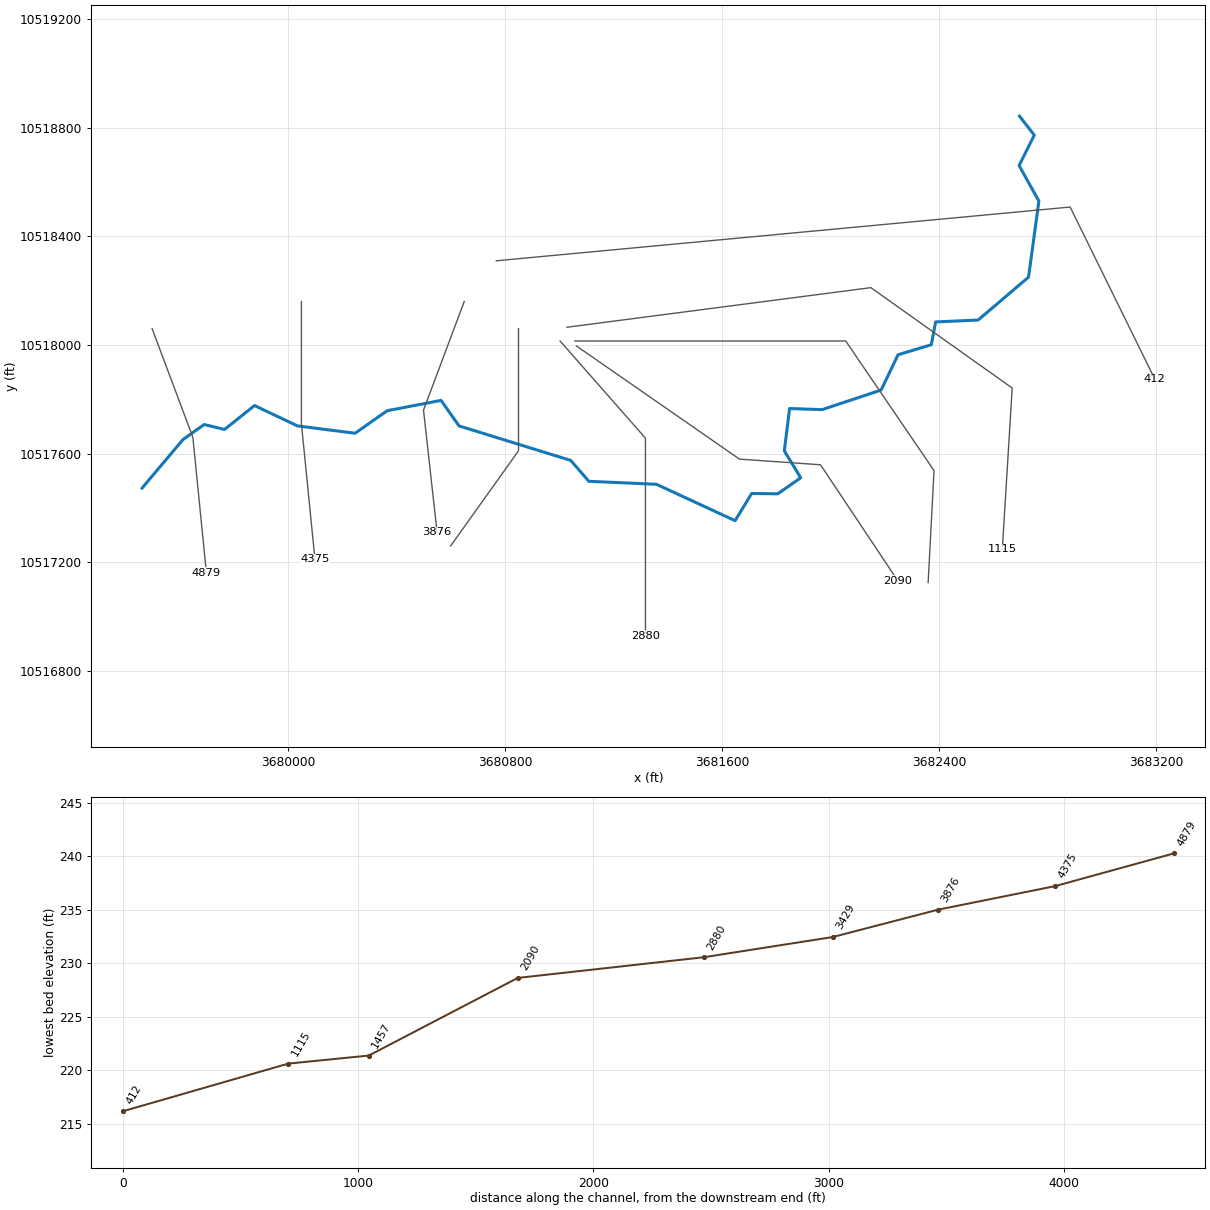
--- UNT 170 IN BUCR.prj (project) ---

Proj Title=UNT 170 IN BUCR Base Level Engineering
Current Plan=p01
Default Exp/Contr=0.3,0.1
English Units
Geom File=g01
Flow File=f01
Plan File=p01
Y Axis Title=Elevation
X Axis Title(PF)=Main Channel Distance
X Axis Title(XS)=Station
BEGIN DESCRIPTION:
UNT 170 IN BUCR
END DESCRIPTION:
DSS Export Rating Curves= 0
DSS Export Rating Curve Sorted= 0
DSS Export Volume Flow Curves= 0
DXF OffsetX= 0
DXF OffsetY= 0
DXF ScaleX= 1
DXF ScaleY= 10

--- UNT 170 IN BUCR.p01 (plan) ---

Plan Title=Multiple Run
Short Identifier=Multiple
Geom File=g01
Flow File=f01
Subcritical Flow
K Sum by GR= 0
Std Step Tol= 0.01
Critical Tol= 0.01
Num of Std Step Trials= 20
Max Error Tol= 0.3
Flow Tol Ratio= 0.001
Split Flow NTrial= 30
Split Flow Tol= 0.02
Split Flow Ratio= 0.02
Log Output Level= 0
Friction Slope Method= 1
Unsteady Friction Slope Method= 2
Unsteady Bridges Friction Slope Method= 1
Parabolic Critical Depth
Global Vel Dist=  1 , 1 , 1
Global Log Level= 0
CheckData=True
Encroach Param= -1, 0, 0, 0
BEGIN DESCRIPTION:
Multiple Run
END DESCRIPTION:

--- UNT 170 IN BUCR.f01 (steady flow) ---

Flow Title=Multiple
Number of Profiles=7
Profile Names=10-year,25-year,50-year,1pct_min,100-year,1pct_plu,500-year
River Rch & RM= UNT 170 IN BUCR,Reach-1,4879
     871    1217    1512    1380    1866    2524    2855
Boundary for River Rch & Prof#=UNT 170 IN BUCR,Reach-1,1
Up Type=0
Dn Type=3
Dn Slope=0.005
Boundary for River Rch & Prof#=UNT 170 IN BUCR,Reach-1,2
Up Type=0
Dn Type=3
Dn Slope=0.005
Boundary for River Rch & Prof#=UNT 170 IN BUCR,Reach-1,3
Up Type=0
Dn Type=3
Dn Slope=0.005
Boundary for River Rch & Prof#=UNT 170 IN BUCR,Reach-1,4
Up Type=0
Dn Type=3
Dn Slope=0.005
Boundary for River Rch & Prof#=UNT 170 IN BUCR,Reach-1,5
Up Type=0
Dn Type=3
Dn Slope=0.005
Boundary for River Rch & Prof#=UNT 170 IN BUCR,Reach-1,6
Up Type=0
Dn Type=3
Dn Slope=0.005
Boundary for River Rch & Prof#=UNT 170 IN BUCR,Reach-1,7
Up Type=0
Dn Type=3
Dn Slope=0.005

--- UNT 170 IN BUCR.g01 (geometry) ---

Geom Title=Existing Conditions
Program Version=4.10

River Reach=UNT 170 IN BUCR ,Reach-1
Reach XY= 30
      3679462.42       10517473.       3679613.5       10517652.
      3679691.25       10517707.       3679766.5       10517689.
      3679876.75       10517777.      3680035.25       10517702.
       3680247.5       10517675.      3680365.75       10517758.
      3680564.25       10517796.       3680630.5       10517702.
        3681042.       10517575.      3681108.75       10517498.
        3681358.       10517487.      3681647.75       10517353.
      3681708.75       10517453.      3681805.25       10517452.
       3681889.5       10517511.      3681829.25       10517610.
       3681848.5       10517766.      3681968.25       10517762.
      3682185.75       10517834.      3682248.25       10517964.
      3682370.75       10518001.      3682386.75       10518085.
       3682543.5       10518092.        3682729.       10518250.
      3682767.25       10518530.      3682694.25       10518661.
      3682750.25       10518773.      3682695.75       10518843.

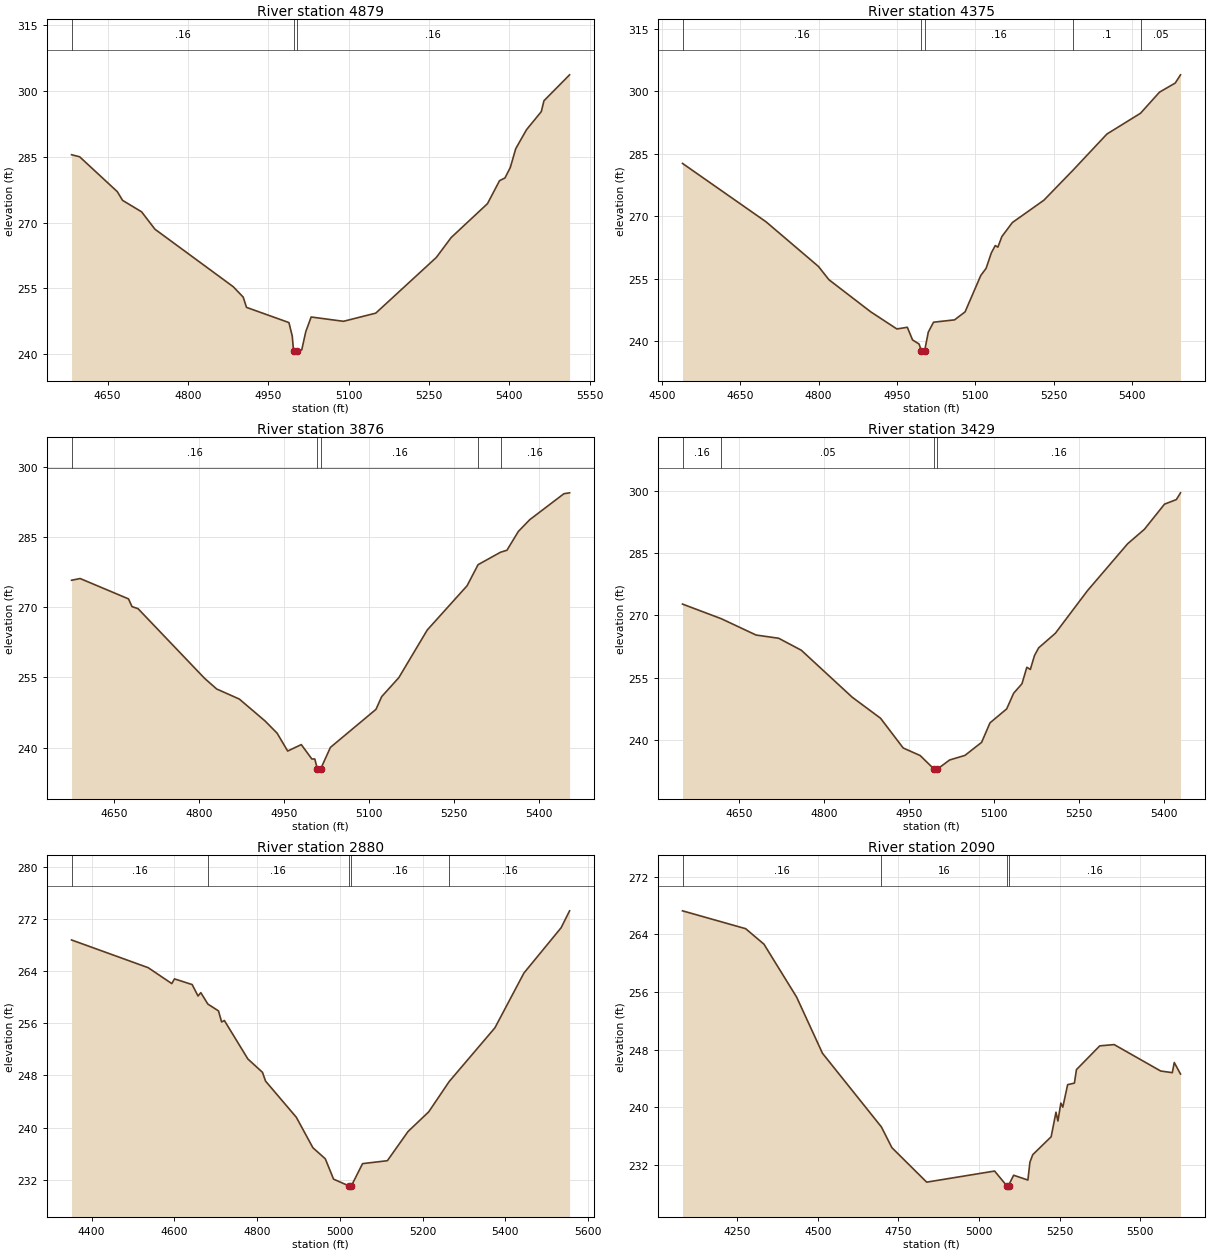
Type RM Length L Ch R = 1 ,4879    ,504,504,504
BEGIN DESCRIPTION:
UNT 170 IN BUCR 5.0
END DESCRIPTION:
XS GIS Cut Line= 3
      3679499.62     10518060.16      3679649.61     10517660.19
      3679699.61     10517160.15
#Sta/Elev= 30
  4582.8  285.44  4597.9  284.97  4668.2  277.03    4678  275.05  4713.6  272.43
  4738.5  268.47  4884.5  255.39  4903.2  253.01  4909.4  250.67  4988.6  247.21
  4994.8  244.13  4997.2  240.75  4999.9  240.25  5003.2  240.75  5012.5  240.99
    5020  245.12  5030.1  248.48  5090.4   247.5  5150.7  249.36  5263.7  262.04
  5291.4  266.57  5359.2  274.29  5381.8  279.54  5391.9  280.15  5401.9  282.55
    5412  286.82  5432.1  291.14  5459.7  295.26  5464.7  297.74  5512.5  303.64
#Mann= 3 ,-1 , 0
  4582.8     .16       0  4997.2     .07       0  5003.2     .16       0
Bank Sta=4997.2,5003.2
XS Rating Curve= 0 ,0
Exp/Cntr=0.3,0.1

Type RM Length L Ch R = 1 ,4375    ,499,499,499
BEGIN DESCRIPTION:
UNT 170 IN BUCR 4.0
END DESCRIPTION:
XS GIS Cut Line= 3
      3680049.61     10518160.15      3680049.61     10517710.19
      3680099.61     10517210.14
#Sta/Elev= 30
  4539.8  282.72  4699.8  268.69  4799.8     258  4819.8  254.82  4899.8  247.11
  4949.8     243  4969.8   243.4  4979.8  240.37  4992.3  239.38  4996.8   237.7
  4999.6   237.2  5002.8   237.7  5009.9  242.23  5019.9  244.62  5060.1  245.18
  5080.2  247.09  5110.4  255.86  5120.4  257.52  5130.5  261.26    5138  263.01
    5143  262.63  5150.6  265.16  5170.7  268.53    5231  273.89  5287.2  281.16
  5351.6  289.77  5415.8  294.75  5452.1  299.81  5482.2     302  5492.3  303.97
#Mann= 5 ,-1 , 0
  4539.8     .16       0  4996.8     .07       0  5002.8     .16       0
  5287.2      .1       0  5415.8     .05       0
Bank Sta=4996.8,5002.8
XS Rating Curve= 0 ,0
Exp/Cntr=0.3,0.1

Type RM Length L Ch R = 1 ,3876    ,447,447,447
BEGIN DESCRIPTION:
UNT 170 IN BUCR 3.0
END DESCRIPTION:
XS GIS Cut Line= 3
      3680649.63     10518160.23      3680499.61     10517760.19
      3680549.61      10517310.2
#Sta/Elev= 30
  4574.4  275.77  4589.6  276.14    4675  271.79  4681.2  270.14  4691.9   269.7
  4809.4  254.82  4830.8  252.54  4870.8  250.39  4916.2  245.72  4937.6   243.1
  4956.3  239.28  4980.3  240.66    4999  237.58  5004.2  237.58  5008.7  235.49
  5011.5  234.99  5014.7  235.49  5031.8  240.06  5112.3  248.19  5122.4  250.91
  5152.6  254.95  5202.9  265.14  5273.3   274.6  5292.7   279.1  5332.4  281.76
  5343.7  282.18  5363.9   286.2    5384  288.71  5444.4  294.26  5454.4  294.45
#Mann= 5 ,-1 , 0
  4574.4     .16       0  5008.7     .07       0  5014.7     .16       0
  5292.7      .1       0  5332.4     .16       0
Bank Sta=5008.7,5014.7
XS Rating Curve= 0 ,0
Exp/Cntr=0.3,0.1

Type RM Length L Ch R = 1 ,3429    ,549,549,549
BEGIN DESCRIPTION:
UNT 170 IN BUCR 2.0
END DESCRIPTION:
XS GIS Cut Line= 3
      3680849.61     10518060.17      3680849.61     10517610.19
      3680599.61     10517260.19
#Sta/Elev= 30
  4549.4  272.71    4618  269.18  4679.4  265.25  4719.4  264.47  4759.4  261.58
  4849.4  250.25  4899.4  245.19  4939.4  238.02  4969.4   236.2  4993.9  232.94
  4996.6  232.44  4999.9  232.94  5021.5  235.13  5048.5  236.23    5078  239.38
  5092.8  244.08  5122.3  247.44  5134.6  251.22  5149.3   253.5  5157.9  257.48
  5164.1  256.95  5171.4  260.29  5178.8  262.16  5208.3  265.67  5264.8   275.9
  5336.1  287.26  5365.6  290.73  5401.2   296.8  5422.1   297.9  5429.5  299.53
#Mann= 4 ,-1 , 0
  4549.4     .16       0    4618     .05       0  4993.9     .07       0
  4999.9     .16       0
Bank Sta=4993.9,4999.9
XS Rating Curve= 0 ,0
Exp/Cntr=0.3,0.1

Type RM Length L Ch R = 1 ,2880    ,790,790,790
BEGIN DESCRIPTION:
Mapping XS c9b97340
END DESCRIPTION:
XS GIS Cut Line= 3
      3681002.78     10518014.84      3681317.44     10517656.78
      3681317.44     10516929.75
#Sta/Elev= 30
  4351.5  268.77  4536.7  264.52  4593.7  262.08  4600.3   262.8    4643  261.93
  4657.2  260.17  4663.9  260.69  4680.9  258.94  4706.6  257.89  4714.2  256.19
  4720.8  256.42  4777.7  250.51  4812.9  248.47  4820.4  247.12  4894.8  241.57
  4934.8   236.9  4964.8   235.2  4984.8  232.08  5021.8  231.05  5024.5  230.55
  5027.8  231.05  5054.8  234.46  5114.8  234.91  5164.8  239.39  5214.8  242.41
  5264.3  247.06  5374.8   255.3  5444.8  263.69  5534.8  270.65  5555.2  273.24
#Mann= 5 ,-1 , 0
  4351.5     .16       0  4680.9     .16       0  5021.8     .03       0
  5027.8     .16       0  5264.3     .16       0
Bank Sta=5021.8,5027.8
XS Rating Curve= 0 ,0
Exp/Cntr=0.3,0.1

Type RM Length L Ch R = 1 ,2090    ,633,633,633
BEGIN DESCRIPTION:
Mapping XS b536b3b7
END DESCRIPTION:
XS GIS Cut Line= 4
      3681063.18      10517996.4      3681663.88     10517579.74
      3681962.49      10517558.9      3682247.22     10517131.81
#Sta/Elev= 30
  4080.9  267.26  4276.7  264.78  4333.4  262.63  4434.8  255.27  4514.7  247.49
  4697.5  237.25  4729.9  234.38  4837.8  229.59  5048.3  231.13  5085.4  229.12
  5088.1  228.62  5091.4  229.12  5107.3  230.55  5151.5  229.88  5157.8  232.36
  5166.5   233.4  5223.6  235.89  5238.6   239.3  5244.6  238.08  5253.7  240.57
  5259.7     240  5274.7  243.12  5295.7  243.34    5302  245.21  5374.2  248.51
  5418.9  248.69  5563.1  245.02  5599.2  244.79  5605.2   246.2  5624.6   244.6
#Mann= 4 ,-1 , 0
  4080.9     .16       0  4697.5      16       0  5085.4     .03       0
  5091.4     .16       0
Bank Sta=5085.4,5091.4
XS Rating Curve= 0 ,0
Exp/Cntr=0.3,0.1

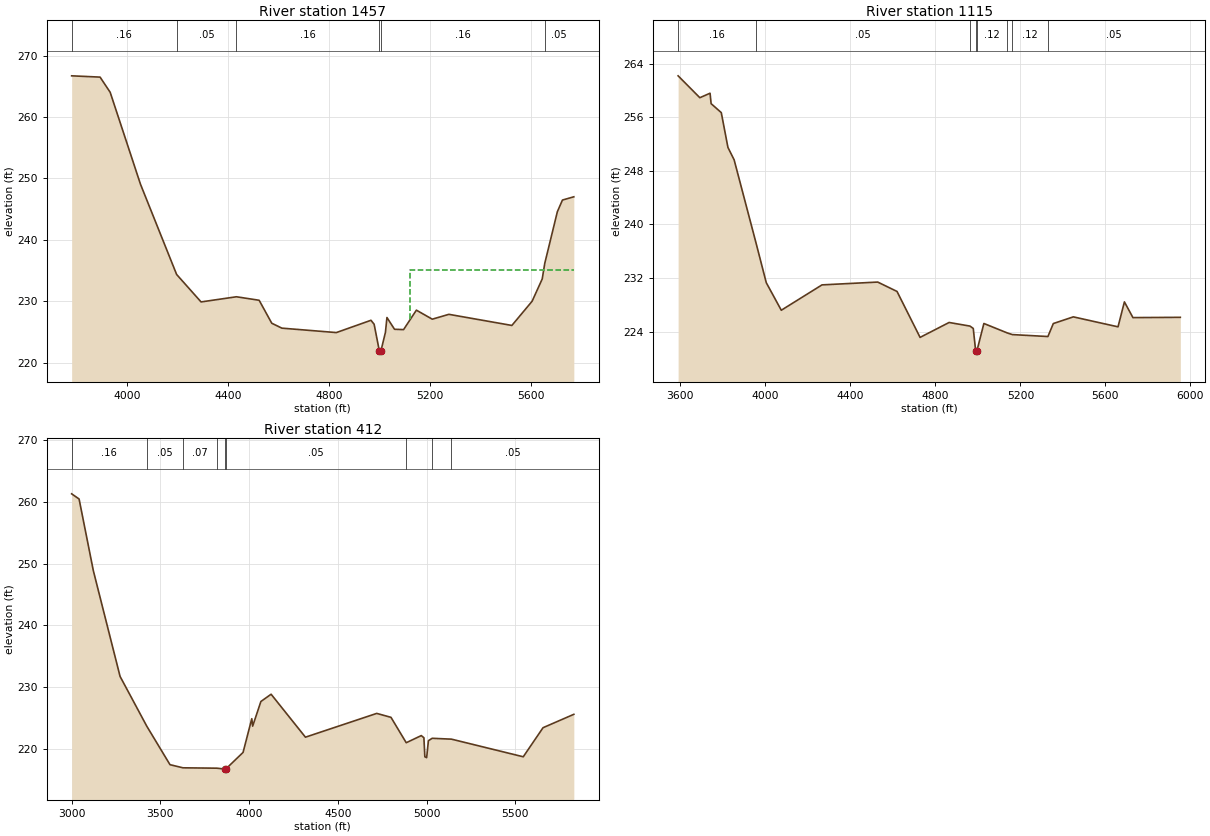
Type RM Length L Ch R = 1 ,1457    ,342,342,342
BEGIN DESCRIPTION:
Mapping XS 5e024a75
END DESCRIPTION:
XS GIS Cut Line= 4
      3681057.02     10518014.85      3682055.29     10518014.85
      3682380.81     10517537.42      3682359.11      10517125.1
#Sta/Elev= 30
  3779.7  266.69  3892.3  266.48  3932.3  264.01  4052.3  249.04  4195.5  234.34
  4292.3  229.87  4432.3  230.71  4522.3  230.14  4572.3   226.4  4612.3   225.6
    4828  224.88  4965.2  226.88  4977.7  226.24  4998.5  221.87  5001.2  221.37
  5004.5  221.87  5022.5  224.92  5028.5  227.33  5058.4  225.42  5094.3  225.36
  5145.1  228.53    5208  227.06  5273.8  227.85  5523.3  226.04  5603.4  229.98
  5643.4   233.6  5653.5  236.14  5703.5  244.57  5723.6  246.46  5768.7  246.99
#Mann= 6 ,-1 , 0
  3779.7     .16       0  4195.5     .05       0  4432.3     .16       0
  4998.5     .07       0  5004.5     .16       0  5653.5     .05       0
#XS Ineff= 2 , 0
                         5120.74          235.02
Permanent Ineff=
       F       F
Bank Sta=4998.5,5004.5
XS Rating Curve= 0 ,0
Exp/Cntr=0.3,0.1

Type RM Length L Ch R = 1 ,1115    ,703,703,703
BEGIN DESCRIPTION:
Mapping XS ab0e5e6c
END DESCRIPTION:
XS GIS Cut Line= 4
      3681028.24     10518065.43      3682148.04     10518211.27
      3682668.88     10517841.47      3682632.42     10517247.71
#Sta/Elev= 30
  3589.5  262.22  3691.7  258.95  3739.8  259.62  3744.8  258.06  3792.6  256.72
  3823.9  251.52  3853.1  249.66  3954.5  237.43  4004.3   231.3  4074.9  227.18
  4266.5  230.97  4528.7  231.39  4619.5  229.99    4728  223.12  4864.6  225.35
  4962.8  224.81  4978.2  224.46  4989.5  221.12  4992.2  220.62  4995.5  221.12
  5028.2   225.2  5138.9  223.78  5162.2  223.54  5329.5  223.25  5354.9  225.19
    5449  226.19  5659.4   224.7  5689.4  228.43  5729.5  226.08  5952.4  226.12
#Mann= 8 ,-1 , 0
  3589.5     .16       0  3954.5     .05       0  4962.8     .12       0
  4989.5     .07       0  4995.5     .12       0  5138.9     .05       0
  5162.2     .12       0  5329.5     .05       0
Bank Sta=4989.5,4995.5
XS Rating Curve= 0 ,0
Exp/Cntr=0.3,0.1

Type RM Length L Ch R = 1 ,412     ,0,0,0
BEGIN DESCRIPTION:
UNT 170 IN BUCR 1.0
END DESCRIPTION:
XS GIS Cut Line= 3
      3680767.85     10518310.23      3682882.42     10518508.14
      3683194.25     10517874.52
#Sta/Elev= 30
    3000  261.33  3041.9  260.49  3122.3  248.85  3272.9   231.7  3423.7  223.61
  3554.2  217.38  3627.2  216.87    3818  216.81  3862.5  216.67  3865.3  216.17
  3868.5  216.67    3966  219.37  4015.1  224.84  4020.1  223.63  4066.4  227.63
    4124  228.81  4317.5  221.84  4719.2   225.7  4799.6  225.06  4885.5  220.94
  4970.3   222.1  4985.1  221.75  4990.4  218.66  5000.5  218.52  5010.5  221.27
  5031.7  221.66  5140.5  221.52    5545  218.66  5656.5  223.38    5830  225.55
#Mann= 9 ,-1 , 0
    3000     .16       0  3423.7     .05       0  3627.2     .07       0
    3818     .05       0  3862.5     .07       0  3868.5     .05       0
  4885.5     .12       0  5031.7     .07       0  5140.5     .05       0
Bank Sta=3862.5,3868.5
XS Rating Curve= 0 ,0
Exp/Cntr=0.3,0.1

Chan Stop Cuts=-1
Use User Specified Reach Order=0
Composite Channel Slope=5