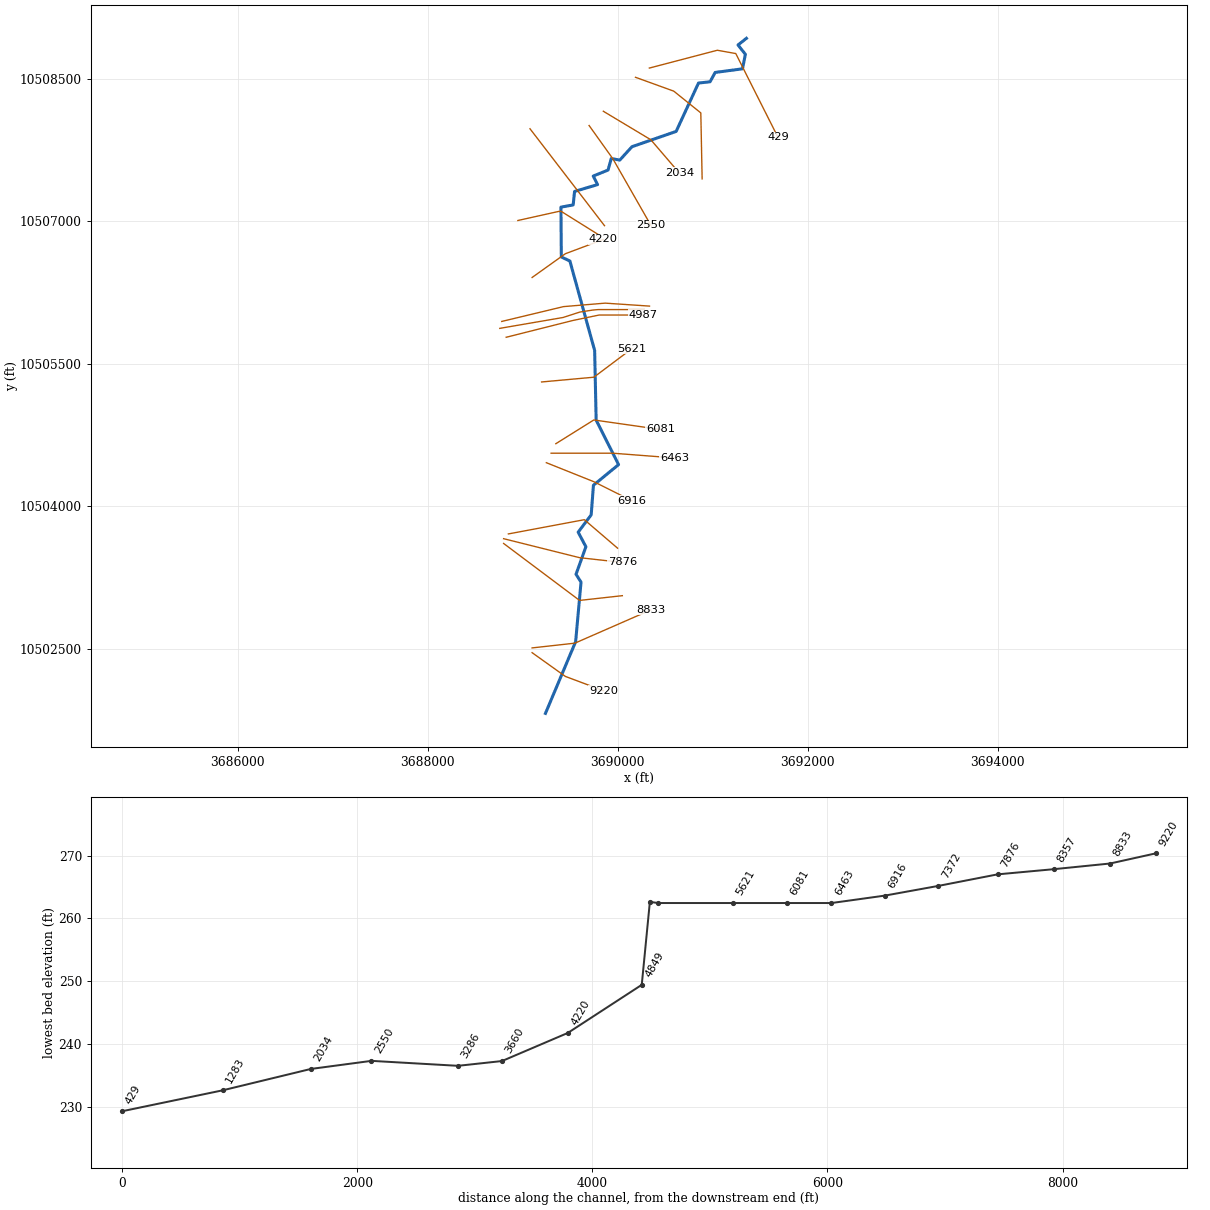
--- UNT 175 IN BUCR.prj (project) ---

Proj Title=UNT 175 IN BUCR Base Level Engineering
Current Plan=p01
Default Exp/Contr=0.3,0.1
English Units
Geom File=g01
Flow File=f01
Plan File=p01
BEGIN DESCRIPTION:
UNT 175 IN BUCR
END DESCRIPTION:

--- UNT 175 IN BUCR.p01 (plan) ---

Plan Title=Multiple Run
Short Identifier=Multiple
Geom File=g01
Flow File=f01
Subcritical Flow
K Sum by GR= 0
Std Step Tol= 0.01
Critical Tol= 0.01
Num of Std Step Trials= 20
Max Error Tol= 0.3
Flow Tol Ratio= 0.001
Split Flow NTrial= 30
Split Flow Tol= 0.02
Split Flow Ratio= 0.02
Log Output Level= 0
Friction Slope Method= 1
Unsteady Friction Slope Method= 2
Unsteady Bridges Friction Slope Method= 1
Parabolic Critical Depth
Global Vel Dist=  1 , 1 , 1
Global Log Level= 0
CheckData=True
Encroach Param= -1, 0, 0, 0
BEGIN DESCRIPTION:
Multiple Run
END DESCRIPTION:

--- UNT 175 IN BUCR.f01 (steady flow) ---

Flow Title=Multiple
Number of Profiles=7
Profile Names=10-year,25-year,50-year,1pct_min,100-year,1pct_plu,500-year
River Rch & RM= UNT 175 IN BUCR,Reach-1,9220
    1111    1574    1973    1815    2454    3319    3818
Boundary for River Rch & Prof#=UNT 175 IN BUCR,Reach-1,1
Up Type=0
Dn Type=3
Dn Slope=0.005
Boundary for River Rch & Prof#=UNT 175 IN BUCR,Reach-1,2
Up Type=0
Dn Type=3
Dn Slope=0.005
Boundary for River Rch & Prof#=UNT 175 IN BUCR,Reach-1,3
Up Type=0
Dn Type=3
Dn Slope=0.005
Boundary for River Rch & Prof#=UNT 175 IN BUCR,Reach-1,4
Up Type=0
Dn Type=3
Dn Slope=0.005
Boundary for River Rch & Prof#=UNT 175 IN BUCR,Reach-1,5
Up Type=0
Dn Type=3
Dn Slope=0.005
Boundary for River Rch & Prof#=UNT 175 IN BUCR,Reach-1,6
Up Type=0
Dn Type=3
Dn Slope=0.005
Boundary for River Rch & Prof#=UNT 175 IN BUCR,Reach-1,7
Up Type=0
Dn Type=3
Dn Slope=0.005

--- UNT 175 IN BUCR.g01 (geometry) ---

Geom Title=Existing Conditions

River Reach=UNT 175 IN BUCR,Reach-1
Reach XY= 30
      3689240.25     10501821.00      3689558.00     10502576.00
      3689614.75     10503203.00      3689562.00     10503285.00
      3689666.00     10503575.00      3689584.50     10503729.00
      3689721.75     10503911.00      3689745.50     10504223.00
      3690010.00     10504440.00      3689774.00     10504908.00
      3689758.00     10505642.00      3689497.25     10506584.00
      3689407.25     10506626.00      3689403.25     10507151.00
      3689532.00     10507174.00      3689546.50     10507316.00
      3689789.00     10507388.00      3689743.25     10507478.00
      3689899.00     10507541.00      3689933.25     10507663.00
      3690022.50     10507646.00      3690151.00     10507787.00
      3690616.00     10507948.00      3690851.50     10508457.00
      3690973.50     10508471.00      3691027.00     10508569.00
      3691314.50     10508607.00      3691345.00     10508760.00
      3691267.50     10508858.00      3691355.75     10508928.00

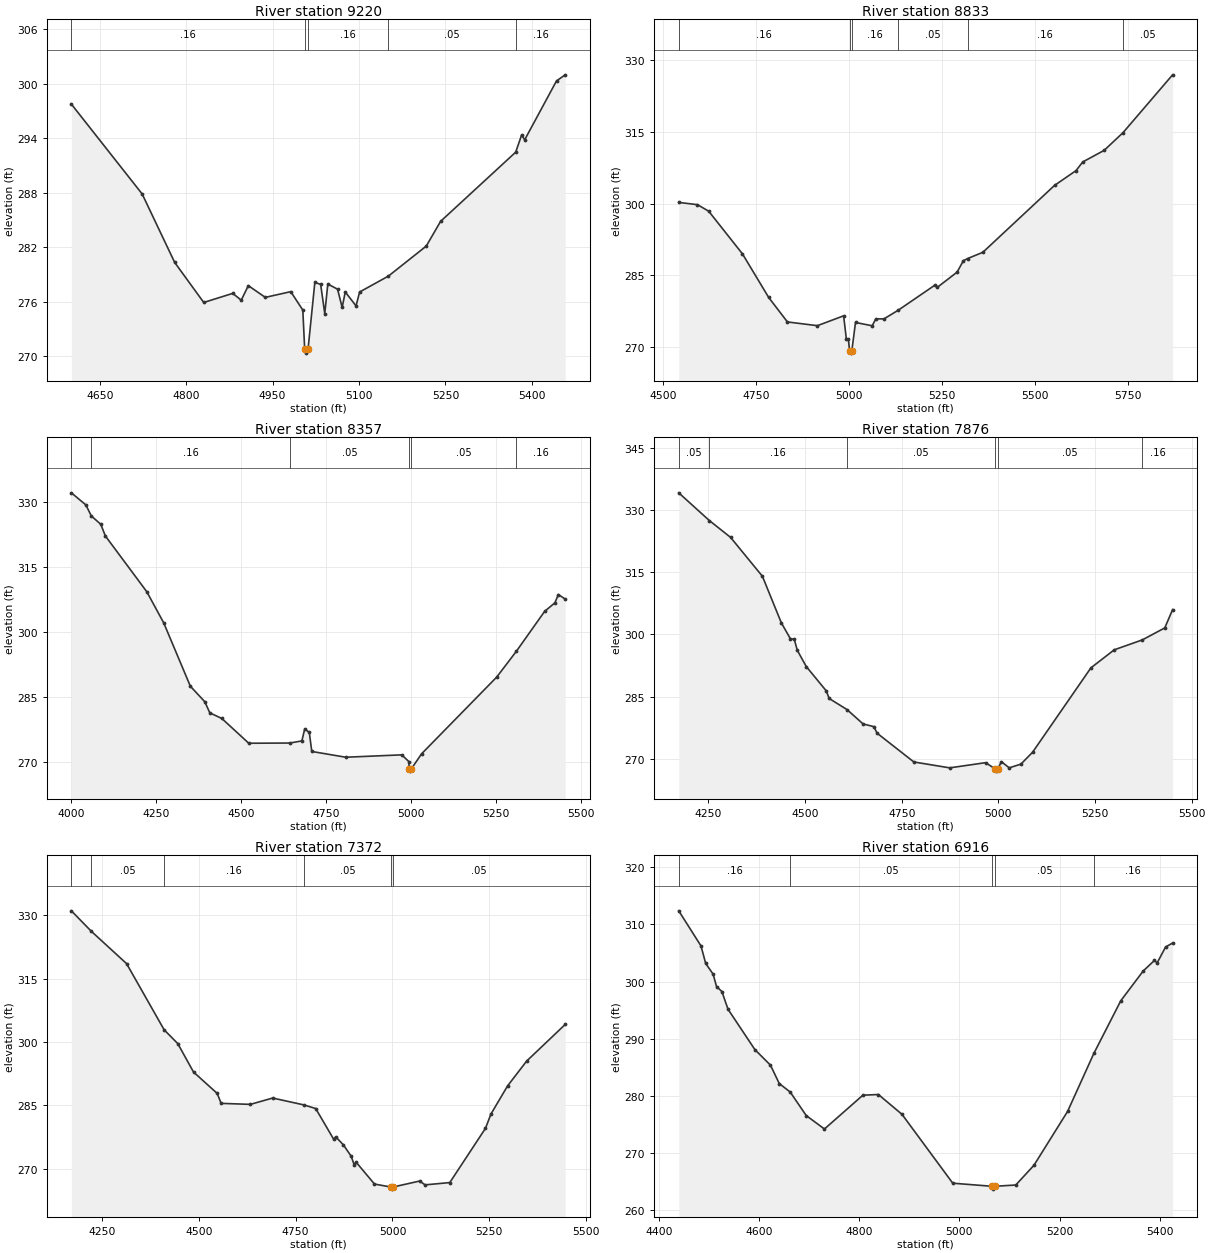
Type RM Length L Ch R = 1,9220,387,387,387
BEGIN DESCRIPTION:
UNT 175 IN BUCR 18.0
END DESCRIPTION:
XS GIS Cut Line= 3
      3689099.63     10502460.17      3689449.61     10502210.19
      3689849.62     10502060.19
#Sta/Elev= 30
  4600.7  297.75  4723.6  287.87  4780.1  280.34  4830.5  275.94  4880.9  276.94
  4895.6  276.19  4907.9  277.79  4937.4  276.50  4981.6  277.13  5002.5  275.10
  5005.7  270.87  5008.4  270.37  5011.7  270.87  5023.4  278.16  5033.5  277.92
  5040.6  274.71  5045.9  277.97  5062.8  277.40  5070.8  275.39  5076.2  277.10
  5094.9  275.56  5101.1  277.09  5151.1  278.84  5216.8  282.14  5241.7  284.86
  5372.1  292.47  5382.3  294.35  5387.7  293.83  5442.9  300.30  5458.0  300.97
#Mann=5,-1,0
  4600.7    0.16       0  5005.7    0.07       0  5011.7    0.16       0
  5151.1    0.05       0  5372.1    0.16       0
Bank Sta=5005.7,5011.7
Exp/Cntr=0.3,0.1

Type RM Length L Ch R = 1,8833,476,476,476
BEGIN DESCRIPTION:
UNT 175 IN BUCR 17.0
END DESCRIPTION:
XS GIS Cut Line= 3
      3689099.64     10502510.19      3689549.61     10502560.19
      3690349.65     10502910.21
#Sta/Elev= 30
  4542.9  300.27  4593.2  299.80  4623.4  298.43  4713.9  289.52  4784.4  280.40
  4834.7  275.28  4915.2  274.50  4985.6  276.56  4993.1  271.61  4998.4  271.61
  5001.6  269.26  5004.4  268.76  5007.6  269.26  5017.5  275.17  5062.3  274.48
  5072.0  275.92  5093.9  275.92  5132.0  277.72  5231.5  283.02  5236.9  282.50
  5290.4  285.70  5307.1  288.08  5318.4  288.53  5359.4  289.84  5551.9  303.83
  5609.6  306.92  5627.6  308.73  5685.2  311.16  5735.7  314.85  5868.9  326.95
#Mann=6,-1,0
  4542.9    0.16       0  5001.6    0.07       0  5007.6    0.16       0
  5132.0    0.05       0  5318.4    0.16       0  5735.7    0.05       0
Bank Sta=5001.6,5007.6
Exp/Cntr=0.3,0.1

Type RM Length L Ch R = 1,8357,481,481,481
BEGIN DESCRIPTION:
UNT 175 IN BUCR 16.0
END DESCRIPTION:
XS GIS Cut Line= 3
      3688799.61     10503610.18      3689599.61     10503010.19
      3690049.65     10503060.19
#Sta/Elev= 30
  4000.1  332.14  4042.8  329.35  4058.7  326.81  4086.6  324.88  4100.1  322.18
  4222.0  309.30  4272.0  302.07  4350.1  287.48  4392.8  283.87  4407.4  281.32
  4442.8  280.02  4522.0  274.30  4642.8  274.35  4678.2  274.84  4686.6  277.60
  4700.1  276.79  4707.4  272.40  4807.4  271.07  4972.0  271.62  4992.8  270.08
  4994.0  268.36  4996.7  267.86  5000.0  268.36  5030.3  271.85  5251.6  289.60
  5309.3  295.55  5392.5  304.77  5422.7  306.74  5432.7  308.65  5452.9  307.60
#Mann=6,-1,0
  4000.1    0.05       0  4058.7    0.16       0  4642.8    0.05       0
  4994.0    0.03       0  5000.0    0.05       0  5309.3    0.16       0
Bank Sta=4994,5000
Exp/Cntr=0.3,0.1

Type RM Length L Ch R = 1,7876,504,504,504
BEGIN DESCRIPTION:
UNT 175 IN BUCR 15.0
END DESCRIPTION:
XS GIS Cut Line= 3
      3688799.64     10503660.18      3689599.61     10503460.19
      3690049.65     10503410.18
#Sta/Elev= 30
  4173.3  334.16  4252.5  327.47  4307.3  323.42  4389.7  314.03  4438.7  302.79
  4461.9  298.99  4472.2  298.81  4479.9  296.18  4503.1  292.26  4554.7  286.41
  4562.4  284.55  4608.5  281.88  4650.0  278.42  4678.3  277.75  4686.1  276.20
  4781.4  269.24  4874.2  267.82  4967.0  269.07  4992.3  267.53  4995.1  267.03
  4998.3  267.53  5008.0  269.31  5028.1  267.82  5058.3  268.72  5088.4  271.57
  5239.4  291.94  5299.7  296.29  5372.5  298.69  5430.5  301.58  5450.7  305.99
#Mann=6,-1,0
  4173.3    0.05       0  4252.5    0.16       0  4608.5    0.05       0
  4992.3    0.03       0  4998.3    0.05       0  5372.5    0.16       0
Bank Sta=4992.3,4998.3
Exp/Cntr=0.3,0.1

Type RM Length L Ch R = 1,7372,456,456,456
BEGIN DESCRIPTION:
UNT 175 IN BUCR 14.0
END DESCRIPTION:
XS GIS Cut Line= 3
      3688849.57     10503710.18      3689649.61     10503860.19
      3689999.64     10503560.16
#Sta/Elev= 30
  4171.0  331.06  4222.7  326.20  4313.5  318.57  4410.6  302.89  4445.7  299.64
  4486.4  292.90  4547.5  287.85  4557.7  285.49  4633.1  285.25  4690.8  286.75
  4771.4  285.12  4801.8  284.27  4848.5  276.96  4853.6  277.57  4873.1  275.69
  4893.4  272.98  4901.0  270.99  4906.1  271.58  4953.6  266.39  4995.7  265.69
  4998.5  265.19  5001.7  265.69  5070.0  267.10  5084.3  266.20  5148.0  266.74
  5240.2  279.59  5254.4  282.98  5297.2  289.62  5346.6  295.51  5446.0  304.17
#Mann=6,-1,0
  4171.0    0.16       0  4222.7    0.05       0  4410.6    0.16       0
  4771.4    0.05       0  4995.7    0.03       0  5001.7    0.05       0
Bank Sta=4995.7,5001.7
Exp/Cntr=0.3,0.1

Type RM Length L Ch R = 1,6916,453,453,453
BEGIN DESCRIPTION:
UNT 175 IN BUCR 13.0
END DESCRIPTION:
XS GIS Cut Line= 3
      3689249.63     10504460.18      3689749.61     10504260.19
      3690149.60     10504060.19
#Sta/Elev= 30
  4439.8  312.38  4484.2  306.23  4493.6  303.16  4508.4  301.29  4515.2  299.12
  4525.9  298.25  4538.1  295.15  4591.9  288.06  4622.9  285.35  4640.4  282.13
  4662.2  280.65  4694.2  276.53  4730.6  274.17  4807.3  280.09  4838.3  280.21
  4885.4  276.74  4986.7  264.68  5064.7  264.14  5067.5  263.64  5070.7  264.14
  5112.5  264.36  5148.8  267.82  5215.9  277.25  5268.5  287.44  5322.1  296.63
  5366.8  301.84  5389.2  303.69  5394.8  303.28  5411.5  306.05  5425.5  306.74
#Mann=5,-1,0
  4439.8    0.16       0  4662.2    0.05       0  5064.7    0.03       0
  5070.7    0.05       0  5268.5    0.16       0
Bank Sta=5064.7,5070.7
Exp/Cntr=0.3,0.1

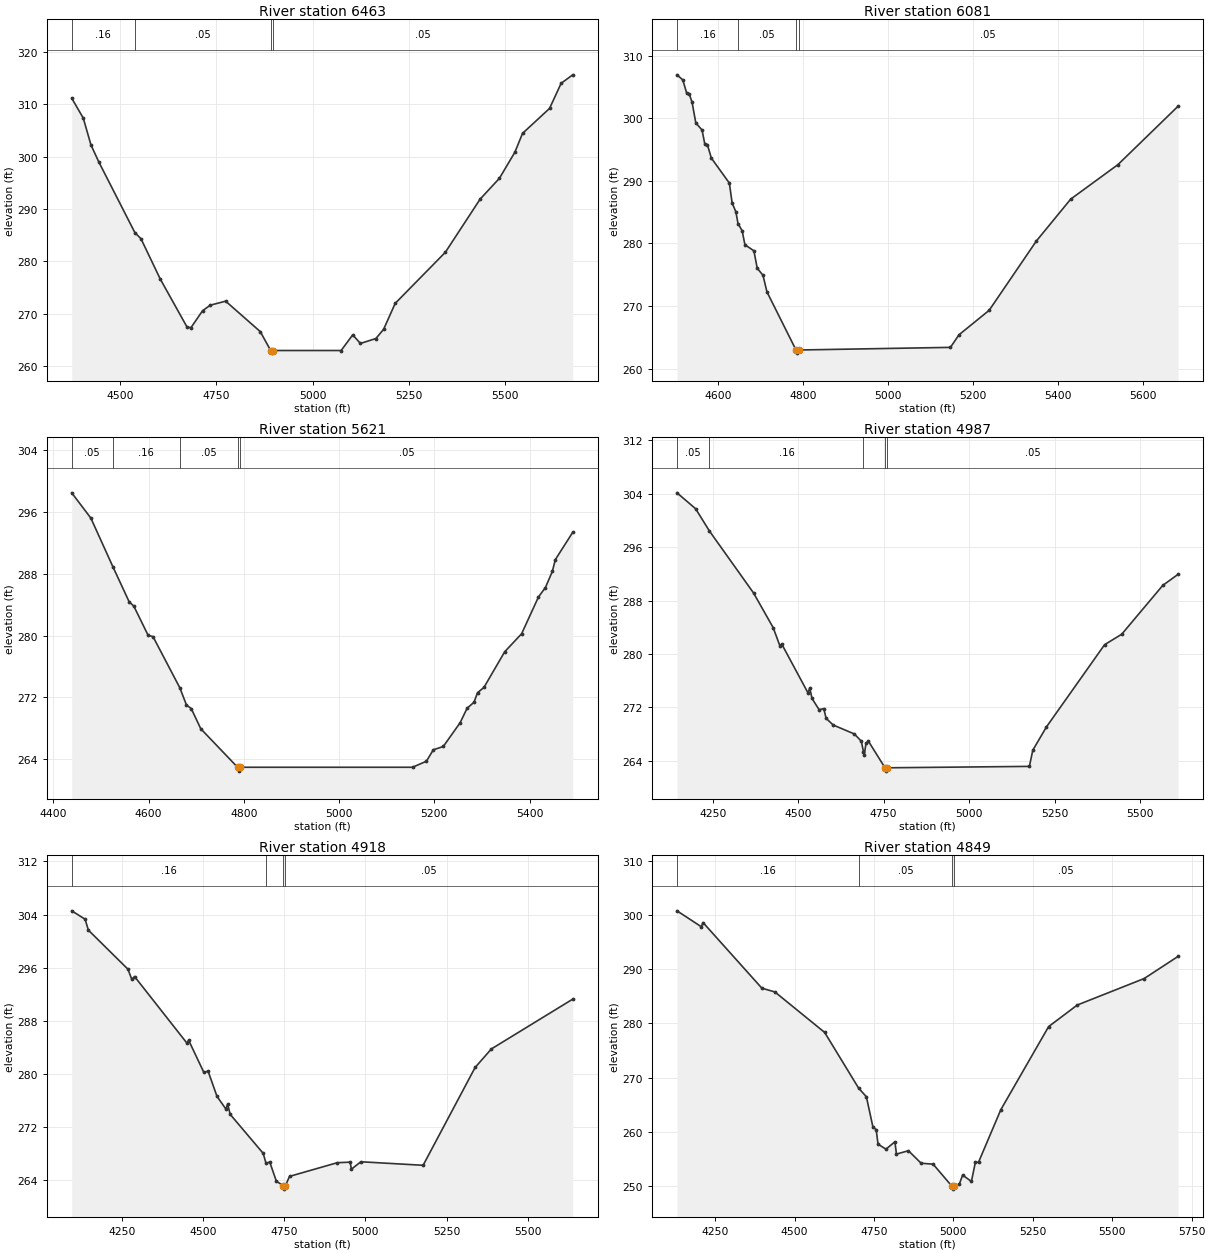
Type RM Length L Ch R = 1,6463,382,382,382
BEGIN DESCRIPTION:
UNT 175 IN BUCR 12.0
END DESCRIPTION:
XS GIS Cut Line= 3
      3689299.61     10504560.19      3689949.61     10504560.19
      3690599.59     10504510.19
#Sta/Elev= 30
  4374.2  311.18  4404.2  307.37  4424.2  302.25  4444.2  299.05  4538.4  285.48
  4554.2  284.32  4604.2  276.63  4674.2  267.40  4684.2  267.34  4714.2  270.56
  4734.2  271.62  4774.2  272.39  4864.2  266.57  4891.2  262.96  4894.0  262.46
  4897.2  262.96  5074.3  262.96  5104.4  265.95  5124.5  264.31  5164.6  265.25
  5184.7  267.01  5214.8  271.97  5345.1  281.73  5435.4  291.88  5485.6  295.87
  5525.7  300.84  5545.7  304.45  5615.9  309.22  5646.0  314.02  5676.1  315.64
#Mann=4,-1,0
  4374.2    0.16       0  4538.4    0.05       0  4891.2    0.03       0
  4897.2    0.05       0
Bank Sta=4891.2,4897.2
Exp/Cntr=0.3,0.1

Type RM Length L Ch R = 1,6081,460,460,460
BEGIN DESCRIPTION:
UNT 175 IN BUCR 11.0
END DESCRIPTION:
XS GIS Cut Line= 3
      3689349.59     10504660.18      3689749.61     10504910.19
      3690449.59     10504810.19
#Sta/Elev= 30
  4503.2  306.95  4516.8  306.14  4526.2  303.98  4532.1  303.86  4538.6  302.59
  4547.4  299.28  4562.2  298.11  4568.7  295.85  4574.6  295.79  4584.0  293.64
  4626.4  289.64  4632.9  286.47  4641.8  285.03  4646.7  283.18  4656.5  282.02
  4663.0  279.79  4684.2  278.81  4691.9  276.04  4705.5  274.90  4714.9  272.24
  4783.2  262.96  4786.0  262.46  4789.2  262.96  5146.6  263.38  5166.8  265.40
  5237.6  269.30  5348.7  280.38  5429.5  287.08  5540.6  292.59  5682.0  301.92
#Mann=4,-1,0
  4503.2    0.16       0  4646.7    0.05       0  4783.2   0.033       0
  4789.2    0.05       0
Bank Sta=4783.2,4789.2
Exp/Cntr=0.3,0.1

Type RM Length L Ch R = 1,5621,634,634,634
BEGIN DESCRIPTION:
UNT 175 IN BUCR 10.0
END DESCRIPTION:
XS GIS Cut Line= 3
      3689199.62     10505310.19      3689749.61     10505360.19
      3690149.64     10505660.21
#Sta/Elev= 30
  4438.4  298.47  4478.6  295.20  4524.7  288.93  4558.9  284.39  4568.9  283.80
  4599.0  280.02  4609.1  279.87  4665.4  273.25  4679.4  271.02  4689.4  270.56
  4709.5  267.94  4786.8  262.96  4789.6  262.46  4792.8  262.96  5154.2  262.96
  5183.4  263.74  5197.9  265.22  5218.8  265.65  5254.2  268.72  5268.8  270.59
  5283.4  271.38  5290.7  272.60  5304.2  273.29  5347.9  277.91  5383.4  280.24
  5418.8  285.00  5433.4  286.22  5447.9  288.30  5454.2  289.83  5490.7  293.36
#Mann=5,-1,0
  4438.4    0.05       0  4524.7    0.16       0  4665.4    0.05       0
  4786.8   0.033       0  4792.8    0.05       0
Bank Sta=4786.8,4792.8
Exp/Cntr=0.3,0.1

Type RM Length L Ch R = 1,4987,69,69,69
BEGIN DESCRIPTION:
UNT 175 IN BUCR 9.0
END DESCRIPTION:
XS GIS Cut Line= 4
      3688826.72     10505780.69      3689529.89     10505957.78
      3689805.94     10506015.07      3690264.28     10506015.07
#Sta/Elev= 30
  4145.8  304.14  4200.2  301.76  4240.4  298.44  4369.7  289.14  4427.2  283.94
  4446.8  281.21  4451.9  281.51  4529.0  274.17  4534.1  274.93  4540.6  273.35
  4561.3  271.67  4575.2  271.81  4581.9  270.37  4602.5  269.37  4664.4  268.03
  4685.0  266.94  4691.2  265.36  4693.3  264.82  4698.5  266.61  4705.6  266.95
  4754.2  262.96  4756.9  262.46  4760.2  262.96  5176.5  263.17  5186.5  265.60
  5226.5  269.09  5396.5  281.40  5446.5  282.96  5566.5  290.27  5611.2  291.93
#Mann=5,-1,0
  4145.8    0.05       0  4240.4    0.16       0  4691.2    0.05       0
  4754.2    0.03       0  4760.2    0.05       0
Bank Sta=4754.2,4760.2
Exp/Cntr=0.3,0.1

Type RM Length L Ch R = 1,4918,69,69,69
BEGIN DESCRIPTION:
Mapping XS fa7be937
END DESCRIPTION:
XS GIS Cut Line= 6
      3688759.07     10505874.45      3689425.73     10505989.03
      3689602.81     10506046.32      3689738.23     10506067.16
      3689795.52     10506072.37      3690279.93     10506072.37
#Sta/Elev= 30
  4096.4  304.56  4137.5  303.30  4147.7  301.65  4269.4  295.77  4281.3  294.23
  4289.7  294.67  4451.0  284.63  4456.1  285.08  4502.8  280.24  4516.0  280.41
  4543.4  276.62  4570.9  274.70  4576.0  275.47  4584.0  273.91  4685.5  268.04
  4694.2  266.55  4705.7  266.73  4726.0  263.85  4747.8  263.15  4750.5  262.65
  4753.8  263.15  4766.6  264.57  4913.5  266.63  4952.8  266.71  4957.1  265.66
  4986.1  266.77  5177.6  266.24  5337.6  280.97  5387.6  283.76  5637.9  291.26
#Mann=4,-1,0
  4096.4    0.16       0  4694.2    0.05       0  4747.8    0.03       0
  4753.8    0.05       0
Bank Sta=4747.8,4753.8
Exp/Cntr=0.3,0.1

Type RM Length L Ch R = 1,4849,629,629,629
BEGIN DESCRIPTION:
UNT 175 IN BUCR 8.0
END DESCRIPTION:
XS GIS Cut Line= 4
      3688779.93     10505947.37      3689430.94     10506103.62
      3689868.44     10506140.07      3690335.89     10506108.91
#Sta/Elev= 30
  4130.1  300.80  4206.7  297.86  4212.0  298.64  4397.2  286.52  4438.3  285.82
  4594.9  278.35  4701.6  268.08  4726.2  266.47  4746.8  260.89  4757.1  260.39
  4762.9  257.72  4787.9  256.80  4815.9  258.16  4820.9  255.89  4858.5  256.51
  4898.6  254.20  4936.3  254.03  4996.0  249.92  4998.7  249.42  5002.0  249.92
  5019.0  250.38  5029.1  252.01  5056.8  250.84  5069.2  254.36  5079.2  254.39
  5149.5  264.10  5299.9  279.43  5390.1  283.41  5600.6  288.30  5707.1  292.38
#Mann=4,-1,0
  4130.1    0.16       0  4701.6    0.05       0  4996.0    0.03       0
  5002.0    0.05       0
Bank Sta=4996,5002
Exp/Cntr=0.3,0.1

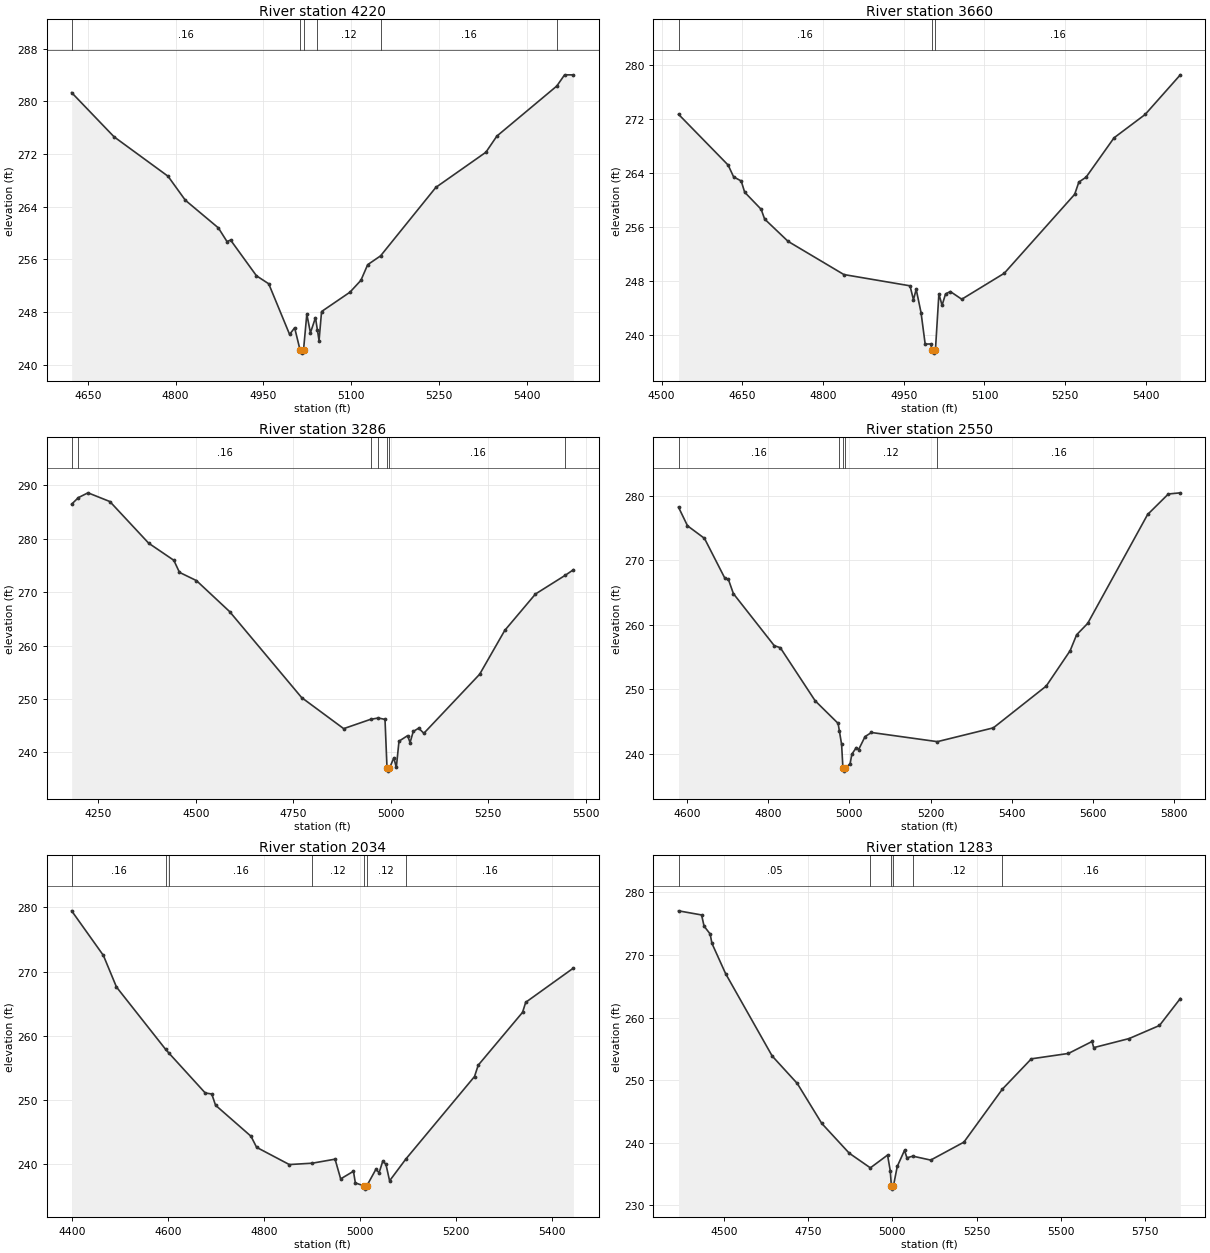
Type RM Length L Ch R = 1,4220,560,560,560
BEGIN DESCRIPTION:
UNT 175 IN BUCR 7.0
END DESCRIPTION:
XS GIS Cut Line= 3
      3689099.61     10506410.19      3689449.61     10506660.19
      3689849.60     10506810.19
#Sta/Elev= 30
  4622.5  281.34  4695.0  274.62  4787.2  268.63  4816.7  264.99  4873.2  260.78
  4887.9  258.71  4894.1  258.93  4938.3  253.50  4959.2  252.29  4994.9  244.59
  5003.5  245.60  5012.7  242.25  5015.5  241.75  5018.7  242.25  5024.3  247.67
  5030.5  244.84  5039.1  247.14  5042.4  245.25  5045.2  243.65  5049.5  248.07
  5098.0  251.01  5116.7  252.81  5128.3  255.19  5150.3  256.53  5244.8  266.94
  5330.3  272.28  5349.0  274.73  5451.4  282.34  5464.7  284.04  5479.8  284.03
#Mann=6,-1,0
  4622.5    0.16       0  5012.7    0.07       0  5018.7    0.16       0
  5042.4    0.12       0  5150.3    0.16       0  5451.4    0.12       0
Bank Sta=5012.7,5018.7
Exp/Cntr=0.3,0.1

Type RM Length L Ch R = 1,3660,374,374,374
BEGIN DESCRIPTION:
UNT 175 IN BUCR 6.0
END DESCRIPTION:
XS GIS Cut Line= 3
      3688949.65     10507010.20      3689399.61     10507110.19
      3689799.58     10506860.21
#Sta/Elev= 30
  4531.4  272.68  4623.6  265.15  4633.8  263.40  4647.9  262.79  4654.3  261.13
  4685.0  258.59  4691.4  257.15  4735.0  253.84  4838.7  248.92  4961.6  247.25
  4968.0  245.19  4973.1  246.73  4982.1  243.29  4989.8  238.61  5000.0  238.63
  5002.9  237.77  5005.6  237.27  5008.9  237.77  5015.3  246.05  5021.2  244.36
  5027.7  246.05  5036.6  246.40  5057.8  245.26  5136.8  249.11  5267.7  260.82
  5275.4  262.63  5288.9  263.36  5340.8  269.19  5398.6  272.65  5464.0  278.53
#Mann=3,-1,0
  4531.4    0.16       0  5002.9    0.07       0  5008.9    0.16       0
Bank Sta=5002.9,5008.9
Exp/Cntr=0.3,0.1

Type RM Length L Ch R = 1,3286,736,736,736
BEGIN DESCRIPTION:
UNT 175 IN BUCR 5.0
END DESCRIPTION:
XS GIS Cut Line= 2
      3689077.23     10507976.16      3689861.96     10506955.32
#Sta/Elev= 30
  4181.2  286.46  4198.6  287.69  4223.2  288.58  4279.3  286.95  4379.0  279.15
  4443.4  275.96  4457.9  273.70  4501.4  272.16  4586.6  266.36  4771.4  250.27
  4879.3  244.46  4948.3  246.20  4968.1  246.45  4985.3  246.19  4990.5  237.01
  4993.2  236.51  4996.5  237.01  5008.0  239.01  5014.3  237.19  5021.2  242.11
  5043.3  243.15  5049.6  241.85  5057.8  243.93  5071.7  244.55  5085.0  243.59
  5228.2  254.64  5292.5  262.83  5371.4  269.65  5448.2  273.17  5468.8  274.19
#Mann=7,-1,0
  4181.2    0.05       0  4198.6    0.16       0  4948.3    0.12       0
  4968.1    0.16       0  4990.5    0.07       0  4996.5    0.16       0
  5448.2    0.12       0
Bank Sta=4990.5,4996.5
Exp/Cntr=0.3,0.1

Type RM Length L Ch R = 1,2550,516,516,516
BEGIN DESCRIPTION:
UNT 175 IN BUCR 4.0
END DESCRIPTION:
XS GIS Cut Line= 3
      3689699.62     10508010.17      3689949.61     10507660.19
      3690349.60     10506960.21
#Sta/Elev= 30
  4579.2  278.22  4601.3  275.34  4643.1  273.39  4693.5  267.19  4702.1  267.02
  4714.4  264.82  4815.1  256.75  4829.9  256.44  4915.9  248.20  4972.4  244.70
  4975.6  243.49  4981.0  241.44  4984.2  237.80  4986.9  237.30  4990.2  237.80
  5001.9  238.43  5006.2  239.92  5017.2  240.95  5023.0  240.65  5038.8  242.66
  5054.6  243.29  5216.9  241.87  5354.8  244.01  5485.1  250.49  5544.1  255.98
  5560.0  258.44  5587.3  260.21  5734.9  277.09  5786.0  280.27  5815.5  280.45
#Mann=5,-1,0
  4579.2    0.16       0  4975.6    0.12       0  4984.2    0.07       0
  4990.2    0.12       0  5216.9    0.16       0
Bank Sta=4984.2,4990.2
Exp/Cntr=0.3,0.1

Type RM Length L Ch R = 1,2034,751,751,751
BEGIN DESCRIPTION:
UNT 175 IN BUCR 3.0
END DESCRIPTION:
XS GIS Cut Line= 3
      3689849.58     10508160.21      3690349.61     10507860.19
      3690649.60     10507510.20
#Sta/Elev= 30
  4399.6  279.48  4465.7  272.51  4492.9  267.58  4595.3  257.83  4601.3  257.32
  4677.6  251.03  4691.2  250.87  4699.0  249.12  4772.8  244.27  4784.5  242.54
  4852.5  239.85  4900.2  240.06  4947.7  240.69  4959.4  237.61  4986.0  238.80
  4989.9  236.99  5007.7  236.51  5010.5  236.01  5013.7  236.51  5032.7  239.11
  5039.3  238.57  5046.9  240.35  5053.5  239.92  5061.2  237.31  5095.1  240.72
  5237.9  253.60  5245.6  255.37  5337.8  263.62  5344.4  265.19  5443.7  270.54
#Mann=7,-1,0
  4399.6    0.16       0  4595.3    0.05       0  4601.3    0.16       0
  4900.2    0.12       0  5007.7    0.07       0  5013.7    0.12       0
  5095.1    0.16       0
Bank Sta=5007.7,5013.7
Exp/Cntr=0.3,0.1

Type RM Length L Ch R = 1,1283,854,854,854
BEGIN DESCRIPTION:
UNT 175 IN BUCR 2.0
END DESCRIPTION:
XS GIS Cut Line= 4
      3690188.38     10508517.80      3690591.14     10508371.98
      3690875.86     10508142.81      3690889.75     10507448.38
#Sta/Elev= 30
  4365.6  277.07  4434.0  276.41  4441.4  274.62  4459.4  273.37  4464.7  271.87
  4505.2  267.04  4643.4  253.87  4717.9  249.48  4790.5  243.10  4872.0  238.34
  4934.6  236.00  4985.6  238.04  4993.6  235.55  4997.0  233.10  4999.7  232.60
  5003.0  233.10  5014.4  236.23  5035.9  238.80  5043.1  237.60  5060.5  237.87
  5113.6  237.24  5212.1  240.11  5326.2  248.58  5412.1  253.42  5522.1  254.28
  5592.1  256.19  5597.1  255.21  5702.2  256.66  5792.2  258.75  5854.0  263.06
#Mann=6,-1,0
  4365.6    0.05       0  4934.6    0.16       0  4997.0    0.07       0
  5003.0    0.16       0  5060.5    0.12       0  5326.2    0.16       0
Bank Sta=4997,5003
Exp/Cntr=0.3,0.1

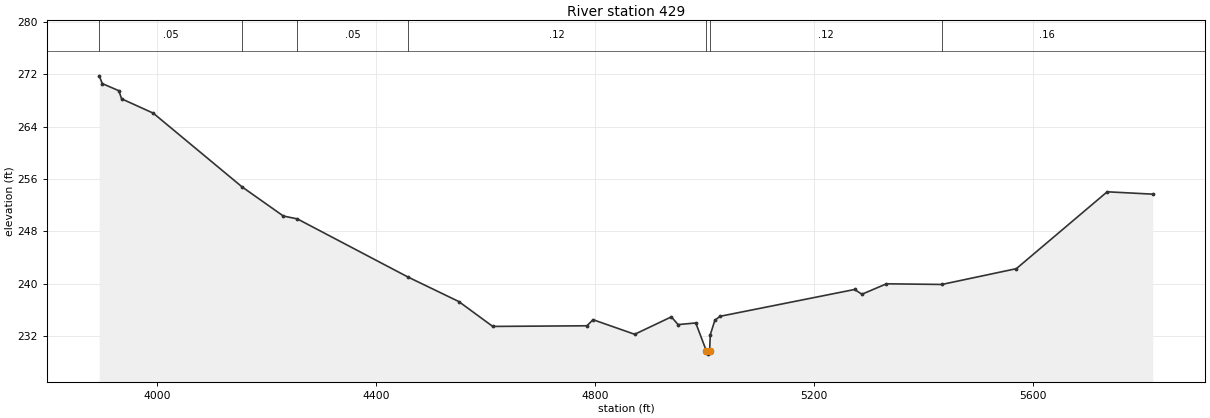
Type RM Length L Ch R = 1,429,0,0,0
BEGIN DESCRIPTION:
UNT 175 IN BUCR 1.0
END DESCRIPTION:
XS GIS Cut Line= 4
      3690334.17     10508615.03      3691049.47     10508802.53
      3691243.91     10508767.81      3691688.36     10507885.85
#Sta/Elev= 30
  3894.6  271.77  3900.3  270.58  3930.4  269.50  3935.5  268.26  3993.3  266.07
  4155.4  254.82  4231.0  250.36  4256.6  249.92  4459.0  241.03  4551.5  237.30
  4613.5  233.50  4785.6  233.60  4796.7  234.53  4872.8  232.30  4939.8  234.96
  4952.1  233.78  4984.4  234.03  5003.7  229.77  5006.4  229.27  5009.7  229.77
  5010.9  232.22  5019.3  234.45  5029.0  235.05  5274.4  239.14  5288.0  238.42
  5332.8  240.01  5433.9  239.91  5570.0  242.32  5736.0  254.06  5819.2  253.70
#Mann=7,-1,0
  3894.6    0.05       0  4155.4    0.16       0  4256.6    0.05       0
  4459.0    0.12       0  5003.7    0.07       0  5009.7    0.12       0
  5433.9    0.16       0
Bank Sta=5003.7,5009.7
Exp/Cntr=0.3,0.1

Chan Stop Cuts=-1