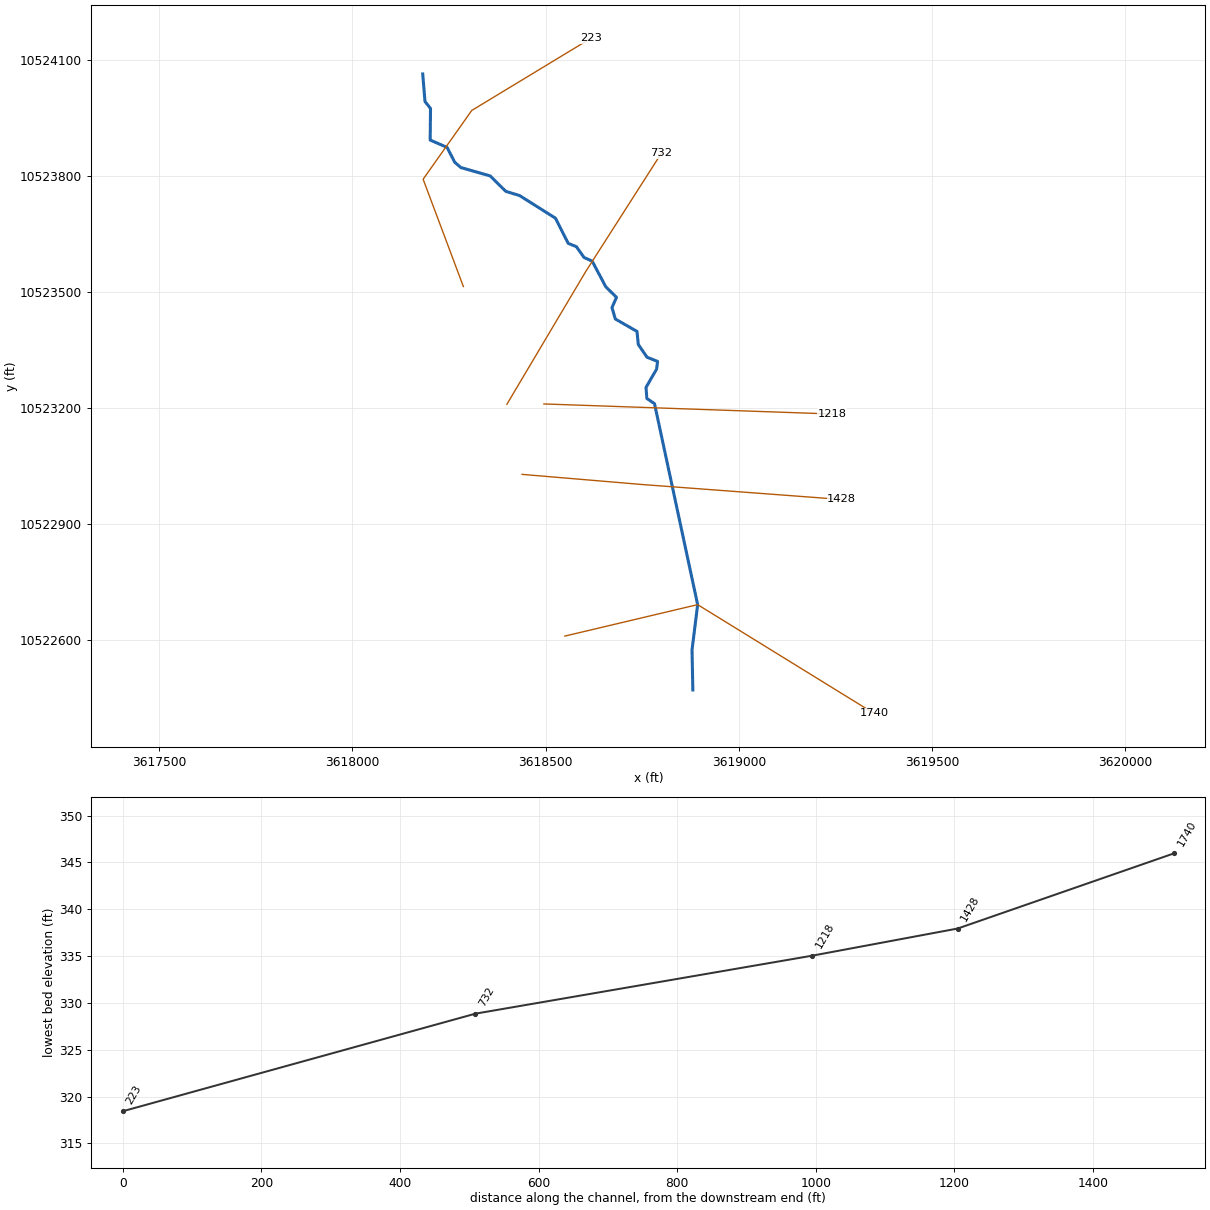
--- UNT 2 TO ALLIGATOR CR.prj (project) ---

Proj Title=UNT 2 TO ALLIGATOR CR Base Level Engineering
Current Plan=p01
Default Exp/Contr=0.3,0.1
English Units
Geom File=g01
Flow File=f01
Plan File=p01
BEGIN DESCRIPTION:
UNT 2 TO ALLIGATOR CR
END DESCRIPTION:

--- UNT 2 TO ALLIGATOR CR.p01 (plan) ---

Plan Title=Multiple Run
Short Identifier=Multiple
Geom File=g01
Flow File=f01
Subcritical Flow
K Sum by GR= 0
Std Step Tol= 0.01
Critical Tol= 0.01
Num of Std Step Trials= 20
Max Error Tol= 0.3
Flow Tol Ratio= 0.001
Split Flow NTrial= 30
Split Flow Tol= 0.02
Split Flow Ratio= 0.02
Log Output Level= 0
Friction Slope Method= 1
Unsteady Friction Slope Method= 2
Unsteady Bridges Friction Slope Method= 1
Parabolic Critical Depth
Global Vel Dist=  1 , 1 , 1
Global Log Level= 0
CheckData=True
Encroach Param= -1, 0, 0, 0
BEGIN DESCRIPTION:
Multiple Run
END DESCRIPTION:

--- UNT 2 TO ALLIGATOR CR.f01 (steady flow) ---

Flow Title=Multiple
Number of Profiles=7
Profile Names=10-year,25-year,50-year,1pct_min,100-year,1pct_plu,500-year
River Rch & RM= UNT 2 TO ALLIGAT,Reach-1,1740
     304     389     455     392     530     717     712
Boundary for River Rch & Prof#=UNT 2 TO ALLIGAT,Reach-1,1
Up Type=0
Dn Type=3
Dn Slope=0.005
Boundary for River Rch & Prof#=UNT 2 TO ALLIGAT,Reach-1,2
Up Type=0
Dn Type=3
Dn Slope=0.005
Boundary for River Rch & Prof#=UNT 2 TO ALLIGAT,Reach-1,3
Up Type=0
Dn Type=3
Dn Slope=0.005
Boundary for River Rch & Prof#=UNT 2 TO ALLIGAT,Reach-1,4
Up Type=0
Dn Type=3
Dn Slope=0.005
Boundary for River Rch & Prof#=UNT 2 TO ALLIGAT,Reach-1,5
Up Type=0
Dn Type=3
Dn Slope=0.005
Boundary for River Rch & Prof#=UNT 2 TO ALLIGAT,Reach-1,6
Up Type=0
Dn Type=3
Dn Slope=0.005
Boundary for River Rch & Prof#=UNT 2 TO ALLIGAT,Reach-1,7
Up Type=0
Dn Type=3
Dn Slope=0.005

--- UNT 2 TO ALLIGATOR CR.g01 (geometry) ---

Geom Title=Existing Conditions

River Reach=UNT 2 TO ALLIGAT,Reach-1
Reach XY= 30
      3618880.83     10522470.64      3618878.72     10522574.17
      3618893.25     10522691.61      3618781.63     10523211.82
      3618761.83     10523225.15      3618759.66     10523253.79
      3618787.00     10523301.10      3618789.61     10523321.07
      3618762.26     10523331.92      3618739.70     10523364.91
      3618736.22     10523398.76      3618680.23     10523430.88
      3618671.55     10523460.39      3618683.27     10523486.87
      3618655.49     10523514.21      3618620.34     10523580.62
      3618599.07     10523590.17      3618579.54     10523617.94
      3618558.27     10523626.62      3618525.29     10523691.73
      3618432.40     10523750.32      3618396.81     10523761.17
      3618356.45     10523801.10      3618280.49     10523822.81
      3618264.43     10523836.69      3618244.90     10523874.89
      3618201.07     10523893.99      3618201.93     10523975.58
      3618187.61     10523993.81      3618181.75     10524065.00

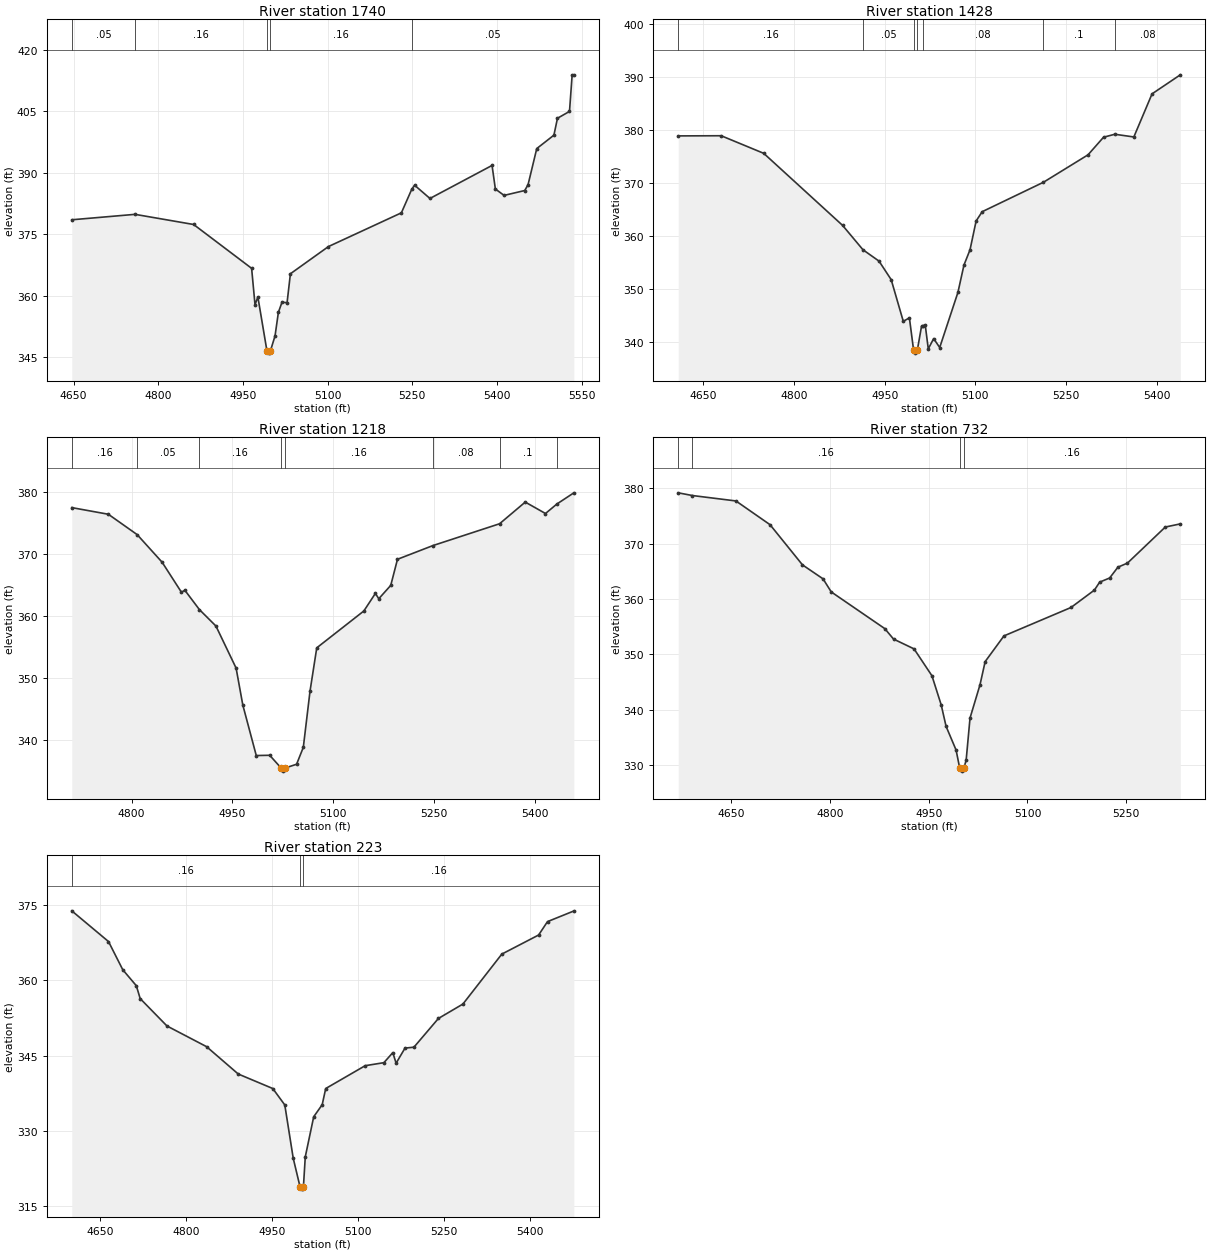
Type RM Length L Ch R = 1,1740,312,312,312
BEGIN DESCRIPTION:
UNT 2 TO ALLIGATOR CR 3.0
END DESCRIPTION:
XS GIS Cut Line= 3
      3618549.56     10522610.18      3618893.25     10522691.61
      3619349.65     10522410.17
#Sta/Elev= 30
  4646.8  378.54  4758.9  379.87  4862.7  377.39  4965.4  366.68  4971.4  357.79
  4976.5  359.67  4992.6  346.46  4995.3  345.96  4998.6  346.46  5006.9  350.18
  5012.8  355.92  5019.2  358.40  5028.2  358.28  5034.1  365.35  5101.5  372.00
  5230.7  380.24  5249.1  386.01  5254.1  386.99  5281.3  383.75  5391.3  391.82
  5397.2  386.06  5412.6  384.50  5449.2  385.69  5455.1  387.12  5470.5  395.94
  5500.9  399.22  5507.2  403.35  5528.5  405.02  5533.2  413.96  5536.2  413.96
#Mann=5,-1,0
  4646.8    0.05       0  4758.9    0.16       0  4992.6    0.07       0
  4998.6    0.16       0  5249.1    0.05       0
Bank Sta=4992.6,4998.6
Exp/Cntr=0.3,0.1

Type RM Length L Ch R = 1,1428,210,210,210
BEGIN DESCRIPTION:
Mapping XS 6bb1b186
END DESCRIPTION:
XS GIS Cut Line= 3
      3618438.85     10523028.72      3618747.02     10523002.68
      3619266.19     10522963.74
#Sta/Elev= 30
  4608.8  378.95  4679.8  378.98  4750.1  375.66  4880.5  362.05  4914.2  357.45
  4940.7  355.31  4960.8  351.81  4980.8  343.94  4990.9  344.60  4997.9  338.44
  5000.6  337.94  5003.9  338.44  5010.9  342.98  5013.6  343.08  5017.1  343.22
  5022.1  338.75  5031.0  340.68  5041.0  339.00  5071.1  349.40  5081.1  354.57
  5091.1  357.45  5101.2  362.89  5111.2  364.64  5212.5  370.20  5286.2  375.38
  5311.8  378.70  5330.4  379.26  5361.9  378.75  5392.0  386.89  5438.7  390.48
#Mann=7,-1,0
  4608.8    0.16       0  4914.2    0.05       0  4997.9    0.04       0
  5003.9    0.05       0  5013.6    0.08       0  5212.5     0.1       0
  5330.4    0.08       0
Bank Sta=4997.9,5003.9
Exp/Cntr=0.3,0.1

Type RM Length L Ch R = 1,1218,486,486,486
BEGIN DESCRIPTION:
Mapping XS c56e16b1
END DESCRIPTION:
XS GIS Cut Line= 2
      3618495.28     10523211.01      3619241.83     10523184.97
#Sta/Elev= 30
  4711.1  377.47  4765.5  376.40  4808.4  373.12  4845.5  368.68  4874.3  363.84
  4879.3  364.17  4901.0  361.05  4925.6  358.40  4955.6  351.63  4965.6  345.67
  4985.6  337.55  5005.6  337.59  5022.6  335.54  5025.4  335.04  5028.6  335.54
  5045.6  336.15  5055.6  338.87  5065.6  347.94  5075.6  354.89  5145.7  360.83
  5162.8  363.65  5167.9  362.80  5185.7  364.95  5195.7  369.15  5248.5  371.36
  5347.6  374.87  5385.8  378.36  5415.9  376.52  5432.9  378.05  5458.1  379.85
#Mann=8,-1,0
  4711.1    0.16       0  4808.4    0.05       0  4901.0    0.16       0
  5022.6    0.07       0  5028.6    0.16       0  5248.5    0.08       0
  5347.6     0.1       0  5432.9    0.08       0
Bank Sta=5022.6,5028.6
Exp/Cntr=0.3,0.1

Type RM Length L Ch R = 1,732,509,509,509
BEGIN DESCRIPTION:
UNT 2 TO ALLIGATOR CR 2.0
END DESCRIPTION:
XS GIS Cut Line= 3
      3618399.62     10523210.20      3618603.79     10523553.89
      3618799.61     10523860.18
#Sta/Elev= 30
  4569.1  379.21  4590.7  378.72  4656.8  377.74  4708.7  373.44  4758.0  366.17
  4789.3  363.64  4801.7  361.28  4883.1  354.64  4896.4  352.75  4927.6  350.97
  4954.8  346.11  4968.9  340.83  4976.3  336.95  4991.5  332.67  4997.1  329.35
  4999.8  328.85  5003.1  329.35  5006.8  330.80  5012.7  338.46  5027.9  344.49
  5035.7  348.67  5064.3  353.32  5166.2  358.46  5201.8  361.61  5209.8  363.05
  5225.0  363.80  5237.5  365.75  5252.1  366.50  5309.6  373.02  5332.4  373.59
#Mann=4,-1,0
  4569.1    0.05       0  4590.7    0.16       0  4997.1    0.07       0
  5003.1    0.16       0
Bank Sta=4997.1,5003.1
Exp/Cntr=0.3,0.1

Type RM Length L Ch R = 1,223,0,0,0
BEGIN DESCRIPTION:
UNT 2 TO ALLIGATOR CR 1.0
END DESCRIPTION:
XS GIS Cut Line= 4
      3618286.94     10523514.87      3618182.79     10523792.61
      3618308.66     10523970.56      3618616.85     10524157.21
#Sta/Elev= 30
  4601.3  373.87  4665.3  367.75  4690.2  362.13  4713.8  358.95  4720.5  356.39
  4767.2  350.93  4836.2  346.81  4891.4  341.36  4951.6  338.47  4972.5  335.20
  4987.2  324.58  4999.0  318.93  5001.8  318.43  5005.0  318.93  5008.2  324.86
  5022.9  332.85  5037.7  335.25  5043.8  338.47  5112.6  343.02  5145.2  343.62
  5160.7  345.62  5166.5  343.52  5182.0  346.53  5197.5  346.70  5240.2  352.43
  5282.9  355.30  5350.7  365.25  5414.8  369.05  5430.3  371.72  5476.2  373.84
#Mann=3,-1,0
  4601.3    0.16       0  4999.0    0.07       0  5005.0    0.16       0
Bank Sta=4999,5005
Exp/Cntr=0.3,0.1

Chan Stop Cuts=-1