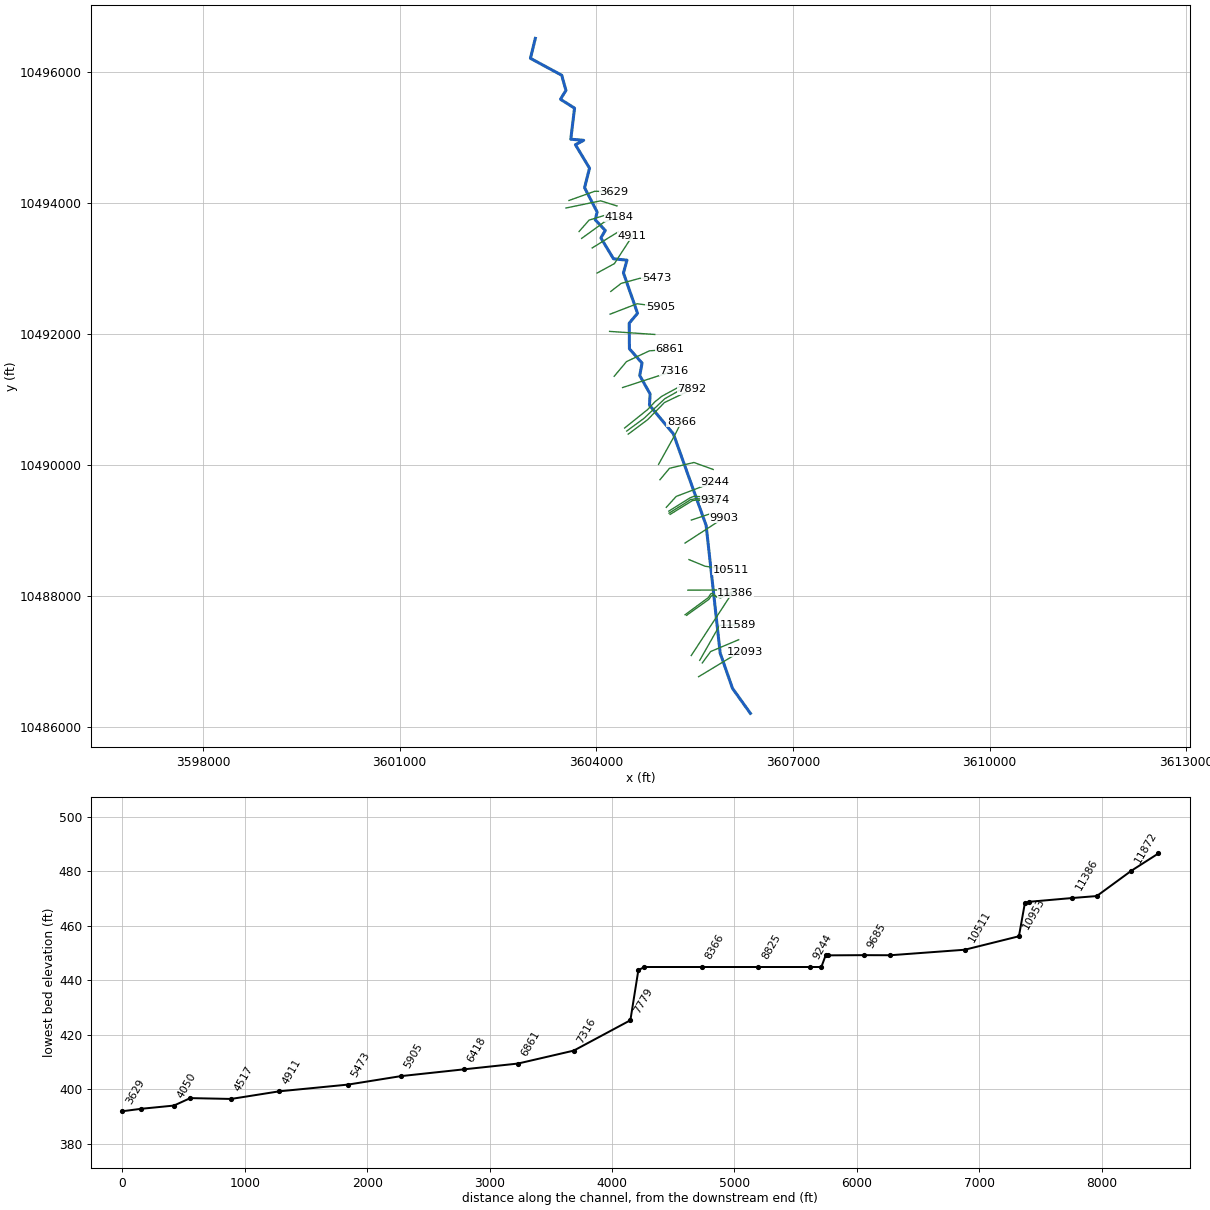
--- WEST FORK PANTHER CREEK.prj (project) ---

Proj Title=WEST FORK PANTHER CREEK Base Level Engineering
Current Plan=p01
Default Exp/Contr=0.3,0.1
English Units
Geom File=g01
Flow File=f01
Plan File=p01
BEGIN DESCRIPTION:
WEST FORK PANTHER CREEK
END DESCRIPTION:

--- WEST FORK PANTHER CREEK.p01 (plan) ---

Plan Title=Multiple Run
Short Identifier=Multiple
Geom File=g01
Flow File=f01
Subcritical Flow
K Sum by GR= 0
Std Step Tol= 0.01
Critical Tol= 0.01
Num of Std Step Trials= 20
Max Error Tol= 0.3
Flow Tol Ratio= 0.001
Split Flow NTrial= 30
Split Flow Tol= 0.02
Split Flow Ratio= 0.02
Log Output Level= 0
Friction Slope Method= 1
Unsteady Friction Slope Method= 2
Unsteady Bridges Friction Slope Method= 1
Parabolic Critical Depth
Global Vel Dist=  1 , 1 , 1
Global Log Level= 0
CheckData=True
Encroach Param= -1, 0, 0, 0
BEGIN DESCRIPTION:
Multiple Run
END DESCRIPTION:

--- WEST FORK PANTHER CREEK.f01 (steady flow) ---

Flow Title=Multiple
Number of Profiles=7
Profile Names=10-year,25-year,50-year,1pct_min,100-year,1pct_plu,500-year
River Rch & RM= WEST FORK PANTHE,Reach-1,12093
     894    1227    1502    1343    1816    2455    2646
Boundary for River Rch & Prof#=WEST FORK PANTHE,Reach-1,1
Up Type=0
Dn Type=3
Dn Slope=0.005
Boundary for River Rch & Prof#=WEST FORK PANTHE,Reach-1,2
Up Type=0
Dn Type=3
Dn Slope=0.005
Boundary for River Rch & Prof#=WEST FORK PANTHE,Reach-1,3
Up Type=0
Dn Type=3
Dn Slope=0.005
Boundary for River Rch & Prof#=WEST FORK PANTHE,Reach-1,4
Up Type=0
Dn Type=3
Dn Slope=0.005
Boundary for River Rch & Prof#=WEST FORK PANTHE,Reach-1,5
Up Type=0
Dn Type=3
Dn Slope=0.005
Boundary for River Rch & Prof#=WEST FORK PANTHE,Reach-1,6
Up Type=0
Dn Type=3
Dn Slope=0.005
Boundary for River Rch & Prof#=WEST FORK PANTHE,Reach-1,7
Up Type=0
Dn Type=3
Dn Slope=0.005

--- WEST FORK PANTHER CREEK.g01 (geometry) ---

Geom Title=Existing Conditions

River Reach=WEST FORK PANTHE,Reach-1
Reach XY= 30
      3606350.83     10486210.95      3606077.39     10486592.89
      3605889.89     10487129.35      3605675.25     10489079.00
      3605175.75     10490475.00      3604810.75     10490913.00
      3604820.50     10491085.00      3604662.25     10491365.00
      3604697.75     10491555.00      3604505.00     10491773.00
      3604501.75     10492164.00      3604628.75     10492315.00
      3604413.50     10492931.00      3604467.50     10493125.00
      3604261.50     10493147.00      3604069.50     10493465.00
      3604136.50     10493579.00      3603982.75     10493742.00
      3604012.75     10493860.00      3603820.50     10494231.00
      3603896.25     10494529.00      3603681.00     10494887.00
      3603807.25     10494954.00      3603610.25     10494971.00
      3603667.75     10495445.00      3603453.25     10495580.00
      3603536.00     10495716.00      3603472.00     10495947.00
      3602994.50     10496205.00      3603069.50     10496510.00

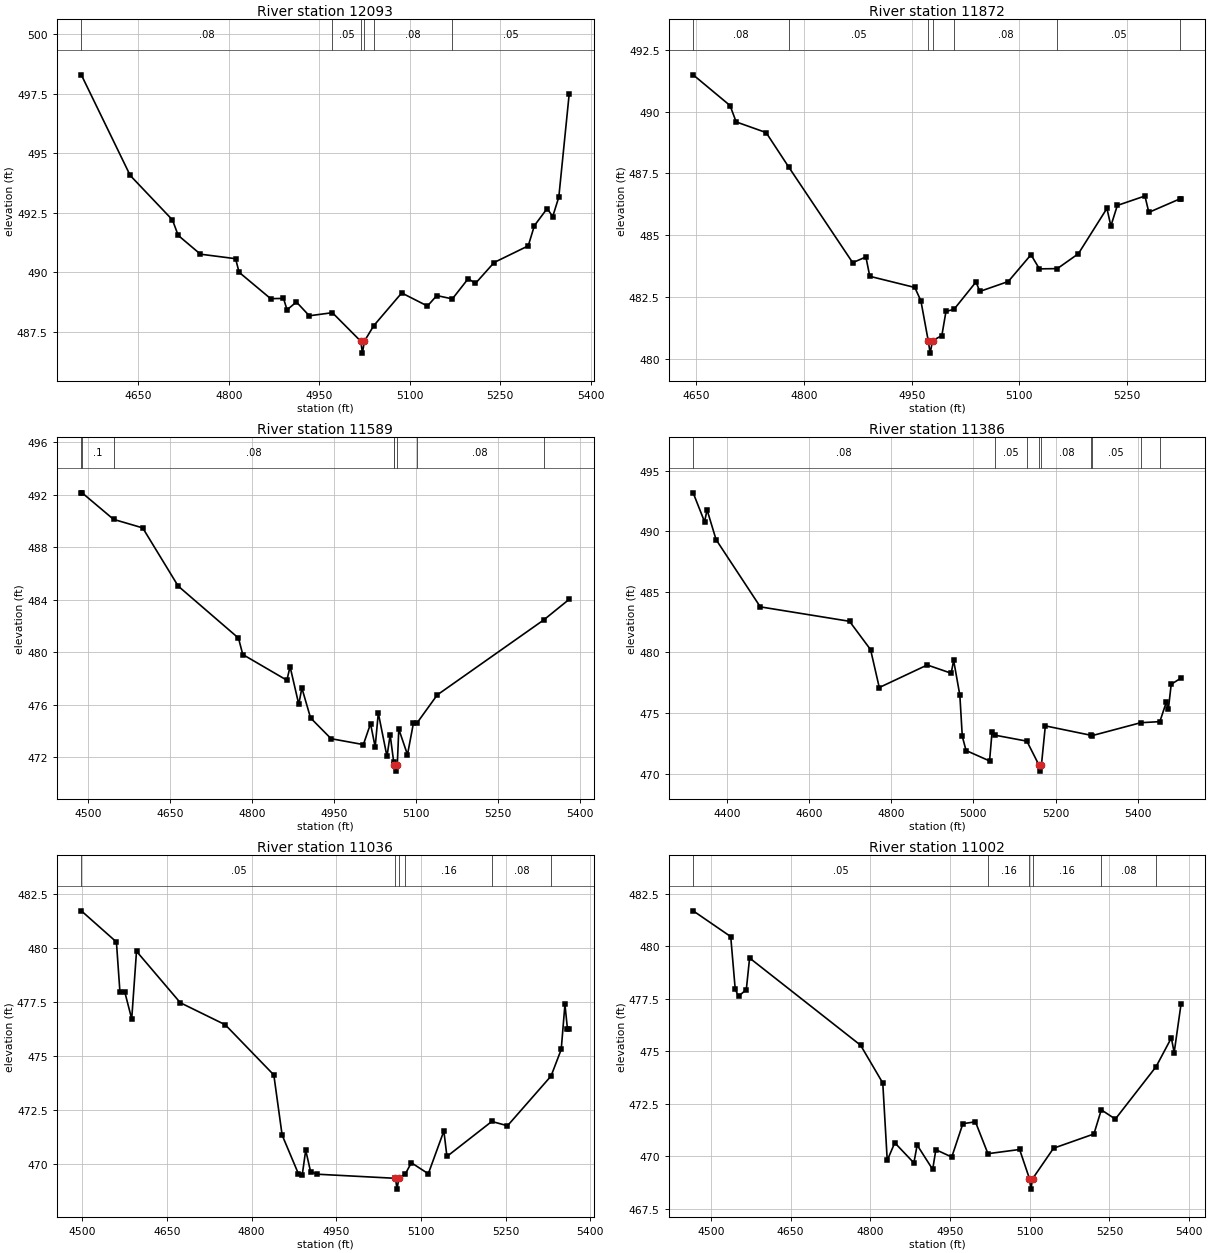
Type RM Length L Ch R = 1,12093,221,221,221
BEGIN DESCRIPTION:
WEST FORK PANTHER CREEK 25.0
END DESCRIPTION:
XS GIS Cut Line= 3
      3605560.13     10486770.23      3606164.31     10487134.82
      3606266.54     10487151.86
#Sta/Elev= 30
  4555.2  498.30  4636.3  494.07  4706.4  492.20  4715.9  491.55  4752.8  490.76
  4811.1  490.57  4816.9  490.00  4869.3  488.89  4890.6  488.90  4896.5  488.42
  4912.0  488.75  4933.4  488.17  4971.7  488.30  5018.8  487.10  5021.5  486.60
  5024.8  487.10  5040.2  487.75  5086.7  489.13  5129.4  488.58  5144.9  489.02
  5170.7  488.88  5197.0  489.73  5209.0  489.53  5240.0  490.41  5296.6  491.11
  5306.8  491.96  5328.0  492.68  5337.2  492.34  5347.3  493.16  5364.5  497.49
#Mann=6,-1,0
  4555.2    0.08       0  4971.7    0.05       0  5018.8    0.04       0
  5024.8    0.05       0  5040.2    0.08       0  5170.7    0.05       0
Bank Sta=5018.8,5024.8
Exp/Cntr=0.3,0.1

Type RM Length L Ch R = 1,11872,283,283,283
BEGIN DESCRIPTION:
Mapping XS edd0214f
END DESCRIPTION:
XS GIS Cut Line= 3
      3605616.71     10486980.33      3605744.31     10487154.79
      3606171.40     10487334.49
#Sta/Elev= 30
  4645.7  491.48  4697.1  490.24  4705.6  489.58  4747.3  489.15  4779.0  487.75
  4867.9  483.90  4886.3  484.13  4891.7  483.35  4954.4  482.90  4962.9  482.36
  4973.1  480.75  4975.8  480.25  4979.1  480.75  4992.1  480.96  4997.8  481.93
  5009.1  482.02  5039.6  483.12  5045.0  482.74  5084.6  483.14  5116.2  484.22
  5128.0  483.65  5152.9  483.66  5182.2  484.26  5222.0  486.09  5227.5  485.38
  5236.5  486.21  5274.9  486.59  5280.4  485.93  5323.3  486.47  5325.2  486.47
#Mann=7,-1,0
  4645.7    0.08       0  4779.0    0.05       0  4973.1    0.04       0
  4979.1    0.05       0  5009.1    0.08       0  5152.9    0.05       0
  5323.3    0.08       0
Bank Sta=4973.1,4979.1
Exp/Cntr=0.3,0.1

Type RM Length L Ch R = 1,11589,203,203,203
BEGIN DESCRIPTION:
WEST FORK PANTHER CREEK 24.0
END DESCRIPTION:
XS GIS Cut Line= 3
      3605577.52     10487020.26      3605879.59     10487551.49
      3606160.79     10487561.90
#Sta/Elev= 30
  4487.5  492.14  4488.9  492.14  4546.5  490.12  4599.8  489.47  4664.7  485.04
  4775.0  481.08  4782.9  479.83  4863.6  477.87  4869.4  478.91  4885.3  476.04
  4891.0  477.28  4906.9  475.00  4944.4  473.42  5003.5  472.97  5016.6  474.56
  5025.1  472.79  5030.8  475.38  5046.7  472.07  5052.5  473.71  5058.9  471.67
  5059.6  471.45  5062.3  470.95  5065.6  471.45  5068.3  474.15  5084.2  472.20
  5095.0  474.59  5101.2  474.59  5138.6  476.75  5333.4  482.46  5380.0  484.03
#Mann=8,-1,0
  4487.5    0.08       0  4488.9     0.1       0  4546.5    0.08       0
  5058.9     0.1       0  5059.6    0.07       0  5065.6     0.1       0
  5101.2    0.08       0  5333.4    0.05       0
Bank Sta=5059.6,5065.6
Exp/Cntr=0.3,0.1

Type RM Length L Ch R = 1,11386,350,350,350
BEGIN DESCRIPTION:
WEST FORK PANTHER CREEK 23.0
END DESCRIPTION:
XS GIS Cut Line= 3
      3605448.36     10487093.53      3606066.40     10488037.95
      3606122.57     10488054.38
#Sta/Elev= 30
  4318.1  493.16  4345.9  490.77  4351.9  491.76  4373.9  489.30  4481.5  483.76
  4698.6  482.57  4749.9  480.23  4771.0  477.11  4887.8  478.97  4946.0  478.29
  4952.0  479.35  4967.1  476.47  4973.0  473.09  4982.2  471.92  5039.4  471.06
  5045.4  473.43  5053.0  473.18  5130.2  472.69  5159.6  470.72  5162.4  470.22
  5165.6  470.72  5175.1  473.95  5286.8  473.17  5288.2  473.14  5407.1  474.21
  5453.8  474.30  5469.2  475.88  5474.4  475.30  5481.4  477.38  5505.3  477.89
#Mann=9,-1,0
  4318.1    0.08       0  5053.0    0.05       0  5130.2    0.08       0
  5159.6    0.07       0  5165.6    0.08       0  5286.8    0.16       0
  5288.2    0.05       0  5407.1    0.08       0  5453.8     0.1       0
Bank Sta=5159.6,5165.6
Exp/Cntr=0.3,0.1

Type RM Length L Ch R = 1,11036,34,34,34
BEGIN DESCRIPTION:
Mapping XS cfb25d10
END DESCRIPTION:
XS GIS Cut Line= 6
      3605376.97     10487706.86      3605719.00     10487951.66
      3605750.25     10488000.27      3605774.56     10488010.69
      3605892.61     10487972.50      3606102.66     10488057.56
#Sta/Elev= 30
  4498.4  481.71  4560.6  480.27  4566.8  477.97  4575.4  477.96  4587.7  476.71
  4596.2  479.84  4673.8  477.46  4753.5  476.44  4839.5  474.12  4854.2  471.34
  4882.9  469.56  4889.9  469.51  4896.0  470.64  4904.6  469.65  4916.3  469.53
  5055.0  469.34  5057.8  468.84  5061.0  469.34  5072.2  469.53  5083.2  470.06
  5113.2  469.55  5140.8  471.53  5146.2  470.35  5225.7  471.97  5253.5  471.77
  5330.7  474.07  5348.7  475.30  5355.3  477.38  5359.7  476.26  5362.8  476.26
#Mann=6,-1,0
  4498.4    0.05       0  5055.0    0.03       0  5061.0    0.05       0
  5072.2    0.16       0  5225.7    0.08       0  5330.7     0.1       0
Bank Sta=5055,5061
Exp/Cntr=0.3,0.1

Type RM Length L Ch R = 1,11002,49,49,49
BEGIN DESCRIPTION:
Mapping XS 4a543485
END DESCRIPTION:
XS GIS Cut Line= 6
      3605354.44     10487715.57      3605706.85     10487975.97
      3605746.78     10488035.00      3605769.35     10488043.68
      3605840.53     10487984.65      3606116.49     10488079.51
#Sta/Elev= 30
  4466.8  481.70  4537.5  480.47  4546.0  477.95  4552.2  477.63  4566.8  477.94
  4573.0  479.45  4781.9  475.29  4823.6  473.49  4832.0  469.80  4846.2  470.64
  4882.1  469.68  4888.3  470.53  4917.5  469.37  4923.5  470.31  4953.4  469.96
  4974.3  471.55  4997.9  471.64  5021.5  470.12  5081.1  470.32  5099.6  468.93
  5102.3  468.43  5105.6  468.93  5144.9  470.38  5220.9  471.06  5234.8  472.21
  5261.2  471.77  5337.9  474.27  5366.6  475.64  5371.9  474.94  5384.8  477.25
#Mann=6,-1,0
  4466.8    0.05       0  5021.5    0.16       0  5099.6    0.03       0
  5105.6    0.16       0  5234.8    0.08       0  5337.9     0.1       0
Bank Sta=5099.6,5105.6
Exp/Cntr=0.3,0.1

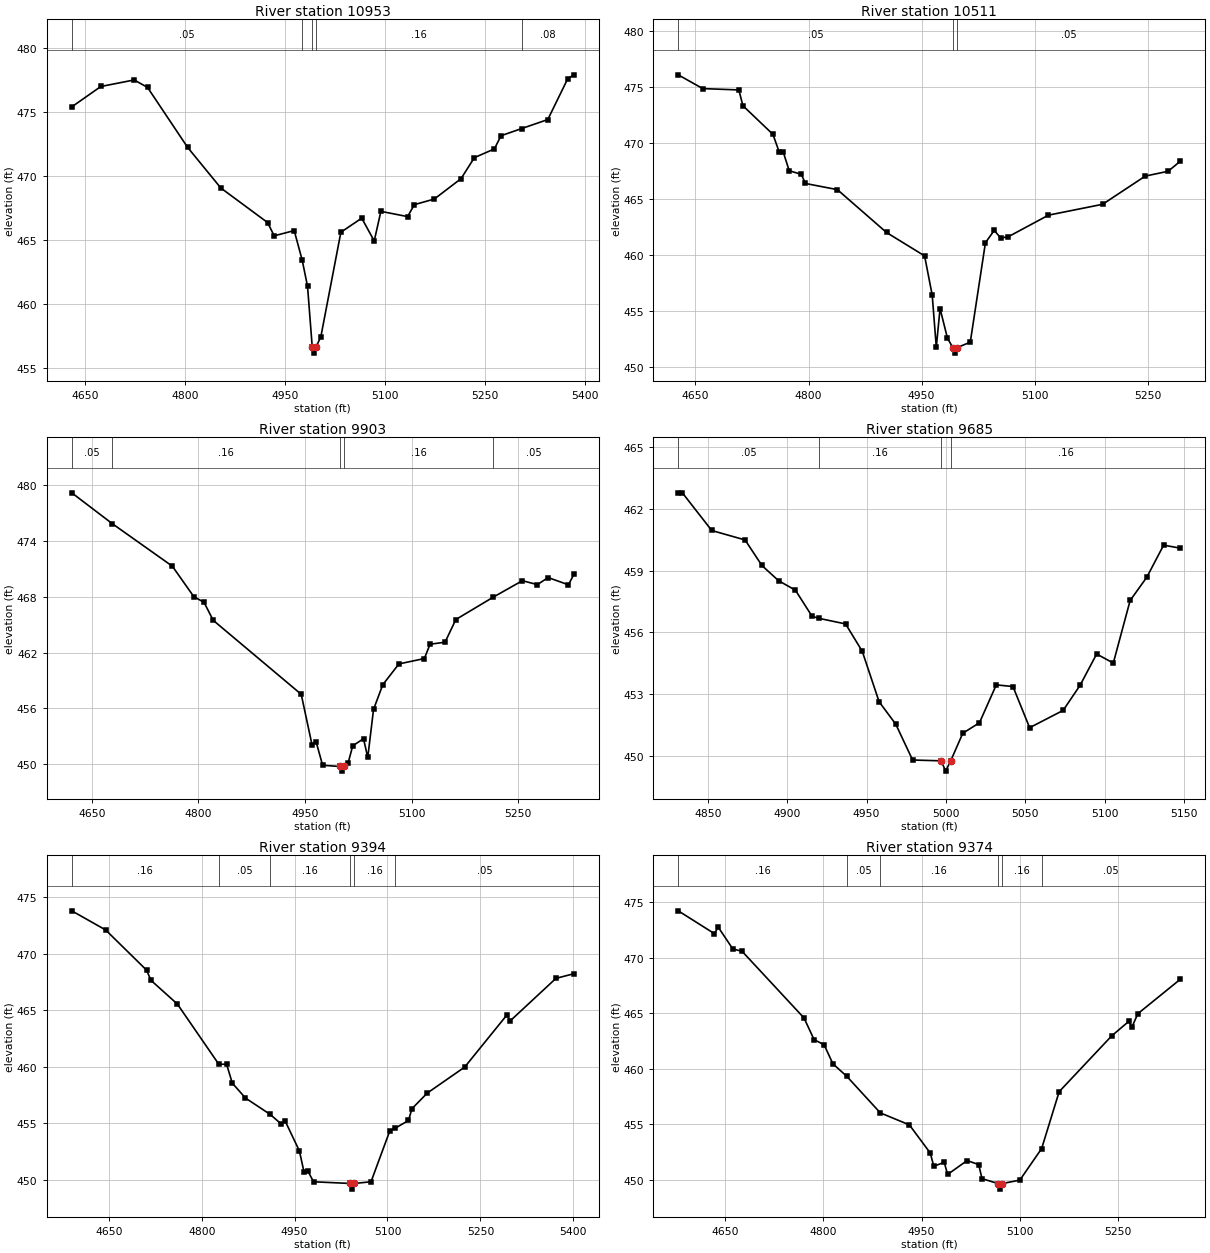
Type RM Length L Ch R = 1,10953,442,442,442
BEGIN DESCRIPTION:
WEST FORK PANTHER CREEK 22.0
END DESCRIPTION:
XS GIS Cut Line= 3
      3605396.05     10488090.55      3605830.98     10488093.16
      3606148.65     10488108.78
#Sta/Elev= 30
  4630.5  475.40  4674.1  476.99  4724.1  477.50  4744.1  476.92  4804.1  472.25
  4854.1  469.07  4924.1  466.38  4934.1  465.34  4964.1  465.75  4976.1  463.44
  4984.1  461.40  4991.1  456.69  4993.8  456.19  4997.1  456.69  5004.1  457.48
  5034.1  465.62  5065.4  466.72  5084.1  464.94  5094.1  467.25  5134.2  466.84
  5144.2  467.77  5174.2  468.21  5214.3  469.80  5234.3  471.44  5264.3  472.12
  5274.3  473.15  5305.3  473.71  5344.4  474.41  5374.4  477.60  5383.5  477.90
#Mann=5,-1,0
  4630.5    0.05       0  4976.1    0.16       0  4991.1    0.07       0
  4997.1    0.16       0  5305.3    0.08       0
Bank Sta=4991.1,4997.1
Exp/Cntr=0.3,0.1

Type RM Length L Ch R = 1,10511,608,608,608
BEGIN DESCRIPTION:
WEST FORK PANTHER CREEK 21.0
END DESCRIPTION:
XS GIS Cut Line= 3
      3605413.42     10488557.06      3605660.84     10488455.48
      3606055.63     10488400.94
#Sta/Elev= 30
  4627.2  476.12  4659.7  474.89  4707.6  474.77  4713.0  473.36  4752.8  470.80
  4761.0  469.25  4766.4  469.24  4774.4  467.55  4790.4  467.23  4796.0  466.41
  4838.3  465.86  4903.5  462.03  4954.0  459.94  4964.1  456.43  4969.5  451.78
  4974.5  455.23  4984.3  452.59  4991.4  451.75  4994.1  451.25  4997.4  451.75
  5014.6  452.23  5034.7  461.12  5046.4  462.22  5054.9  461.54  5065.0  461.65
  5118.3  463.58  5190.1  464.55  5246.7  467.07  5277.0  467.50  5293.2  468.40
#Mann=3,-1,0
  4627.2    0.05       0  4991.4    0.03       0  4997.4    0.05       0
Bank Sta=4991.4,4997.4
Exp/Cntr=0.3,0.1

Type RM Length L Ch R = 1,9903,218,218,218
BEGIN DESCRIPTION:
WEST FORK PANTHER CREEK 20.0
END DESCRIPTION:
XS GIS Cut Line= 2
      3605353.57     10488809.66      3605946.00     10489194.22
#Sta/Elev= 30
  4621.8  479.19  4678.8  475.87  4763.3  471.29  4793.6  468.00  4807.8  467.41
  4820.7  465.47  4944.6  457.50  4959.7  452.09  4965.7  452.34  4974.7  449.86
  4998.9  449.73  5001.7  449.23  5004.9  449.73  5010.5  450.10  5017.1  451.96
  5032.2  452.72  5038.2  450.70  5046.3  455.87  5059.3  458.53  5082.0  460.77
  5117.8  461.35  5125.8  462.89  5146.9  463.11  5162.1  465.55  5214.3  467.94
  5255.7  469.73  5276.8  469.31  5291.9  470.07  5320.5  469.29  5328.1  470.40
#Mann=5,-1,0
  4621.8    0.05       0  4678.8    0.16       0  4998.9    0.07       0
  5004.9    0.16       0  5214.3    0.05       0
Bank Sta=4998.9,5004.9
Exp/Cntr=0.3,0.1

Type RM Length L Ch R = 1,9685,291,291,291
BEGIN DESCRIPTION:
WEST FORK PANTHER CREEK 19.0
END DESCRIPTION:
XS GIS Cut Line= 3
      3605449.63     10489160.19      3605599.61     10489210.19
      3605749.60     10489260.19
#Sta/Elev= 30
  4831.4  462.78  4834.0  462.78  4852.5  460.95  4873.5  460.49  4884.1  459.25
  4894.6  458.51  4905.2  458.05  4915.7  456.78  4920.2  456.68  4936.8  456.41
  4947.3  455.08  4957.9  452.63  4968.4  451.54  4979.0  449.80  4997.0  449.76
  4999.8  449.26  5003.0  449.76  5010.6  451.10  5021.1  451.61  5031.7  453.45
  5042.2  453.37  5052.7  451.37  5073.8  452.21  5084.4  453.42  5094.9  454.95
  5105.4  454.51  5116.0  457.55  5126.5  458.68  5137.1  460.24  5147.6  460.09
#Mann=4,-1,0
  4831.4    0.05       0  4920.2    0.16       0  4997.0    0.07       0
  5003.0    0.16       0
Bank Sta=4997,5003
Exp/Cntr=0.3,0.1

Type RM Length L Ch R = 1,9394,20,20,20
BEGIN DESCRIPTION:
Mapping XS cea2d177
END DESCRIPTION:
XS GIS Cut Line= 4
      3605126.97     10489247.14      3605468.13     10489458.09
      3605533.24     10489465.90      3605874.39     10489421.63
#Sta/Elev= 30
  4590.2  473.79  4644.9  472.10  4710.9  468.55  4718.2  467.64  4760.7  465.55
  4827.6  460.23  4840.2  460.23  4849.4  458.56  4870.7  457.24  4910.4  455.80
  4928.6  454.94  4934.5  455.24  4957.8  452.56  4965.2  450.70  4971.1  450.82
  4980.6  449.84  5040.2  449.69  5042.9  449.19  5046.2  449.69  5073.4  449.84
  5103.6  454.32  5112.6  454.58  5133.9  455.26  5139.5  456.30  5164.2  457.68
  5224.7  459.98  5292.9  464.59  5297.9  464.05  5372.0  467.82  5400.9  468.23
#Mann=6,-1,0
  4590.2    0.16       0  4827.6    0.05       0  4910.4    0.16       0
  5040.2    0.07       0  5046.2    0.16       0  5112.6    0.05       0
Bank Sta=5040.2,5046.2
Exp/Cntr=0.3,0.1

Type RM Length L Ch R = 1,9374,35,35,35
BEGIN DESCRIPTION:
Mapping XS 2c927ff0
END DESCRIPTION:
XS GIS Cut Line= 5
      3605108.79     10489265.40      3605390.01     10489439.86
      3605434.28     10489471.11      3605517.61     10489486.73
      3605814.49     10489471.11
#Sta/Elev= 30
  4578.2  474.21  4633.4  472.16  4639.3  472.74  4661.5  470.79  4675.9  470.56
  4770.4  464.57  4785.8  462.62  4801.1  462.16  4814.5  460.45  4835.9  459.31
  4887.0  456.03  4931.4  454.95  4963.3  452.42  4968.7  451.23  4984.7  451.58
  4989.8  450.49  5019.6  451.74  5037.3  451.38  5042.4  450.11  5067.1  449.67
  5069.9  449.17  5073.1  449.67  5100.2  449.98  5133.5  452.82  5160.3  457.94
  5240.4  462.95  5266.6  464.26  5271.6  463.76  5280.4  464.95  5345.4  468.05
#Mann=6,-1,0
  4578.2    0.16       0  4835.9    0.05       0  4887.0    0.16       0
  5067.1    0.07       0  5073.1    0.16       0  5133.5    0.05       0
Bank Sta=5067.1,5073.1
Exp/Cntr=0.3,0.1

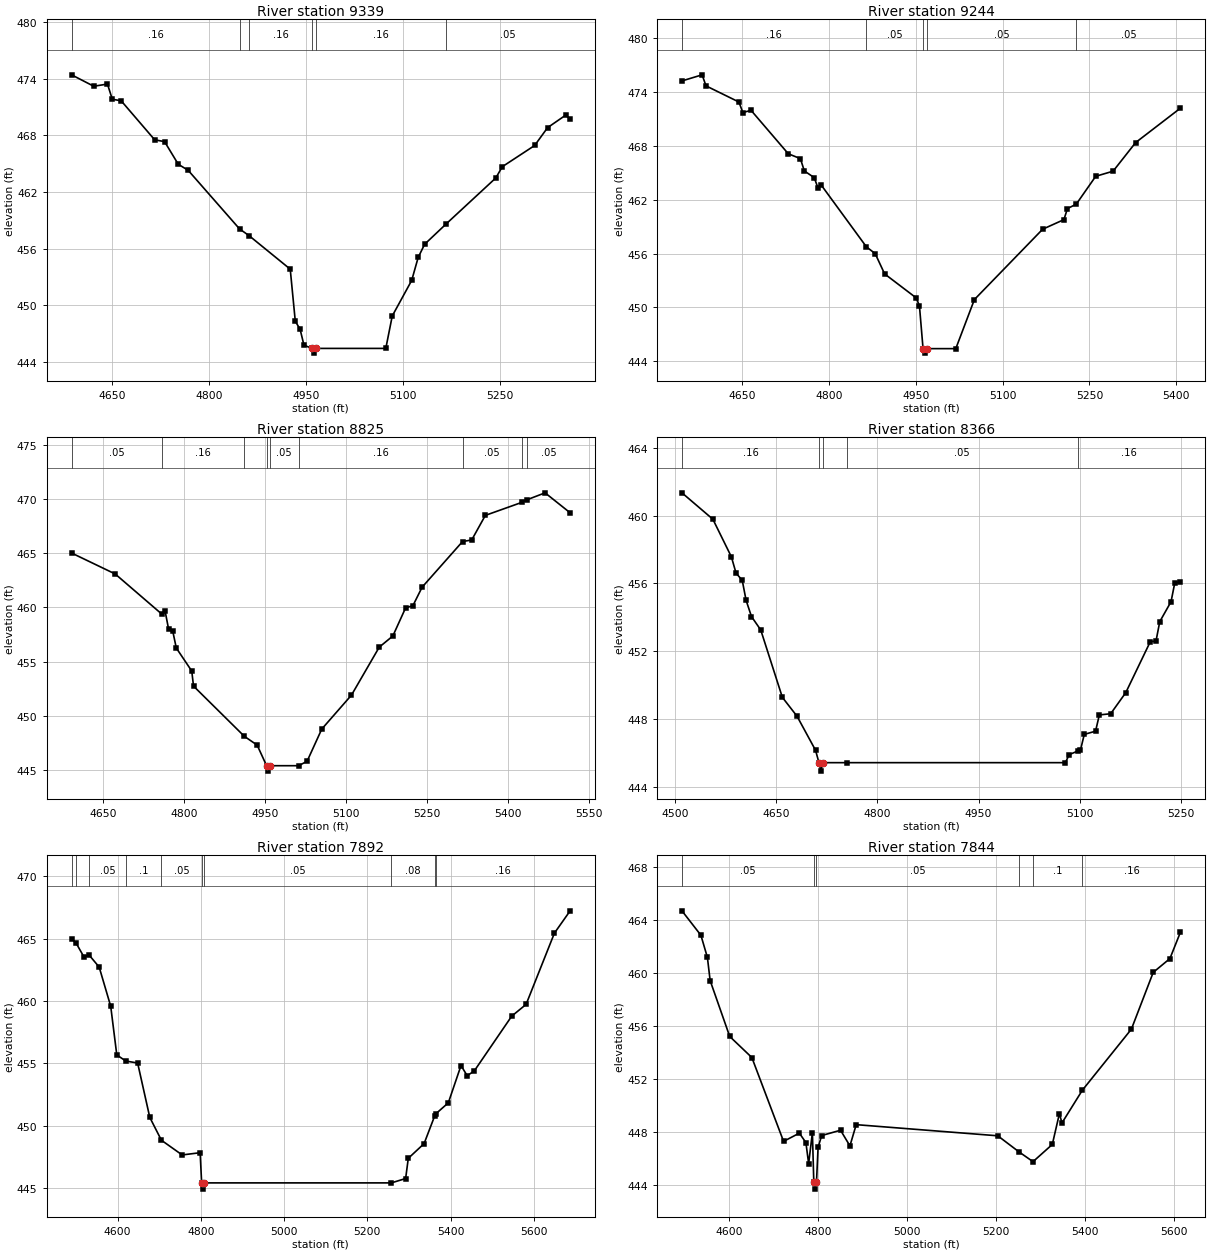
Type RM Length L Ch R = 1,9339,95,95,95
BEGIN DESCRIPTION:
Mapping XS 9fd3c93f
END DESCRIPTION:
XS GIS Cut Line= 4
      3605106.17     10489296.64      3605426.47     10489497.15
      3605488.97     10489523.19      3605814.46     10489504.96
#Sta/Elev= 30
  4586.8  474.41  4621.1  473.20  4642.3  473.43  4649.8  471.82  4663.5  471.66
  4715.4  467.52  4730.7  467.33  4751.9  464.93  4767.2  464.29  4846.7  458.08
  4861.7  457.35  4925.2  453.81  4933.0  448.30  4940.5  447.43  4946.4  445.76
  4958.7  445.41  4961.5  444.91  4964.7  445.41  5073.1  445.41  5083.1  448.85
  5113.2  452.62  5123.2  455.05  5133.2  456.45  5166.9  458.63  5243.4  463.48
  5253.4  464.67  5303.5  466.92  5323.5  468.81  5351.4  470.13  5358.4  469.74
#Mann=6,-1,0
  4586.8    0.16       0  4846.7    0.05       0  4861.7    0.16       0
  4958.7    0.07       0  4964.7    0.16       0  5166.9    0.05       0
Bank Sta=4958.7,4964.7
Exp/Cntr=0.3,0.1

Type RM Length L Ch R = 1,9244,419,419,419
BEGIN DESCRIPTION:
WEST FORK PANTHER CREEK 18.0
END DESCRIPTION:
XS GIS Cut Line= 3
      3605067.12     10489353.95      3605218.13     10489520.59
      3605811.89     10489747.15
#Sta/Elev= 30
  4546.7  475.25  4581.5  475.93  4588.2  474.70  4645.0  472.90  4651.8  471.73
  4666.0  471.97  4730.2  467.13  4751.1  466.59  4757.9  465.22  4775.0  464.47
  4781.5  463.31  4786.9  463.66  4865.0  456.76  4880.2  456.00  4896.5  453.74
  4951.3  451.05  4956.6  450.15  4962.8  445.41  4965.6  444.91  4968.8  445.41
  5019.3  445.41  5051.4  450.88  5169.2  458.72  5205.9  459.79  5212.0  461.02
  5227.3  461.52  5260.8  464.62  5290.8  465.19  5329.7  468.38  5407.1  472.22
#Mann=5,-1,0
  4546.7    0.16       0  4865.0    0.05       0  4962.8    0.07       0
  4968.8    0.05       0  5227.3    0.05       0
Bank Sta=4962.8,4968.8
Exp/Cntr=0.3,0.1

Type RM Length L Ch R = 1,8825,459,459,459
BEGIN DESCRIPTION:
WEST FORK PANTHER CREEK 17.0
END DESCRIPTION:
XS GIS Cut Line= 4
      3604970.75     10489775.81      3605116.57     10489950.27
      3605488.97     10490038.82      3605783.24     10489932.04
#Sta/Elev= 30
  4591.7  465.02  4672.4  463.09  4758.5  459.40  4764.8  459.68  4771.3  458.01
  4779.1  457.80  4785.6  456.26  4814.2  454.14  4817.5  452.75  4911.6  448.12
  4935.3  447.31  4952.8  445.41  4955.6  444.91  4958.8  445.41  5012.2  445.41
  5027.8  445.82  5055.0  448.79  5110.0  451.92  5161.4  456.34  5186.6  457.37
  5210.2  459.96  5223.8  460.17  5240.8  461.87  5315.7  466.08  5332.6  466.22
  5357.9  468.49  5424.9  469.68  5435.0  469.93  5468.5  470.57  5514.9  468.73
#Mann=9,-1,0
  4591.7    0.05       0  4758.5    0.16       0  4911.6    0.05       0
  4952.8   0.033       0  4958.8    0.05       0  5012.2    0.16       0
  5315.7    0.05       0  5424.9    0.16       0  5435.0    0.05       0
Bank Sta=4952.8,4958.8
Exp/Cntr=0.3,0.1

Type RM Length L Ch R = 1,8366,474,474,474
BEGIN DESCRIPTION:
WEST FORK PANTHER CREEK 16.0
END DESCRIPTION:
XS GIS Cut Line= 3
      3604949.59     10490010.16      3605199.61     10490460.19
      3605299.60     10490660.17
#Sta/Elev= 30
  4510.6  461.35  4556.4  459.79  4583.8  457.57  4590.7  456.61  4599.9  456.18
  4605.6  455.00  4613.6  454.04  4627.3  453.25  4659.3  449.27  4681.1  448.15
  4708.5  446.14  4713.5  445.41  4716.3  444.91  4719.5  445.41  4754.5  445.41
  5078.5  445.41  5084.1  445.88  5096.9  446.10  5100.9  446.16  5106.5  447.08
  5123.2  447.27  5128.8  448.23  5145.6  448.30  5168.0  449.55  5204.3  452.56
  5212.7  452.59  5218.3  453.74  5235.0  454.92  5240.6  456.04  5249.0  456.08
#Mann=5,-1,0
  4510.6    0.16       0  4713.5   0.033       0  4719.5    0.16       0
  4754.5    0.05       0  5096.9    0.16       0
Bank Sta=4713.5,4719.5
Exp/Cntr=0.3,0.1

Type RM Length L Ch R = 1,7892,48,48,48
BEGIN DESCRIPTION:
Mapping XS ababe102
END DESCRIPTION:
XS GIS Cut Line= 4
      3604486.39     10490471.13      3604780.63     10490689.86
      3605038.44     10490952.88      3605456.19     10491152.67
#Sta/Elev= 30
  4489.3  464.96  4499.7  464.66  4518.7  463.54  4531.5  463.67  4555.6  462.71
  4583.3  459.57  4597.9  455.67  4619.4  455.18  4648.0  455.02  4677.2  450.66
  4705.1  448.83  4755.0  447.65  4798.2  447.83  4801.8  445.41  4804.6  444.91
  4807.8  445.41  5257.7  445.41  5292.0  445.76  5298.4  447.38  5336.4  448.56
  5361.4  450.74  5365.3  450.97  5394.6  451.83  5425.1  454.82  5439.9  454.00
  5457.1  454.39  5547.0  458.78  5581.5  459.72  5649.5  465.43  5687.3  467.22
#Mann=10,-1,0
  4489.3    0.05       0  4499.7    0.16       0  4531.5    0.05       0
  4619.4     0.1       0  4705.1    0.05       0  4801.8   0.033       0
  4807.8    0.05       0  5257.7    0.08       0  5361.4     0.1       0
  5365.3    0.16       0
Bank Sta=4801.8,4807.8
Exp/Cntr=0.3,0.1

Type RM Length L Ch R = 1,7844,65,65,65
BEGIN DESCRIPTION:
Mapping XS ad4d55d2
END DESCRIPTION:
XS GIS Cut Line= 5
      3604462.96     10490518.01      3604728.55     10490713.29
      3604960.32     10490932.04      3605046.26     10491012.77
      3605355.36     10491186.81
#Sta/Elev= 30
  4493.8  464.69  4536.4  462.85  4551.0  461.18  4557.2  459.43  4601.2  455.22
  4651.0  453.63  4722.3  447.31  4757.8  447.93  4772.5  447.22  4778.7  445.63
  4787.1  447.97  4790.3  444.21  4793.1  443.71  4796.3  444.21  4799.9  446.86
  4808.0  447.75  4850.4  448.15  4871.5  446.97  4885.6  448.57  5204.0  447.73
  5252.0  446.51  5283.2  445.78  5326.6  447.08  5342.5  449.40  5348.3  448.70
  5394.2  451.17  5504.4  455.77  5553.5  460.05  5591.0  461.09  5614.8  463.09
#Mann=6,-1,0
  4493.8    0.05       0  4790.3    0.04       0  4796.3    0.05       0
  5252.0    0.16       0  5283.2     0.1       0  5394.2    0.16       0
Bank Sta=4790.3,4796.3
Exp/Cntr=0.3,0.1

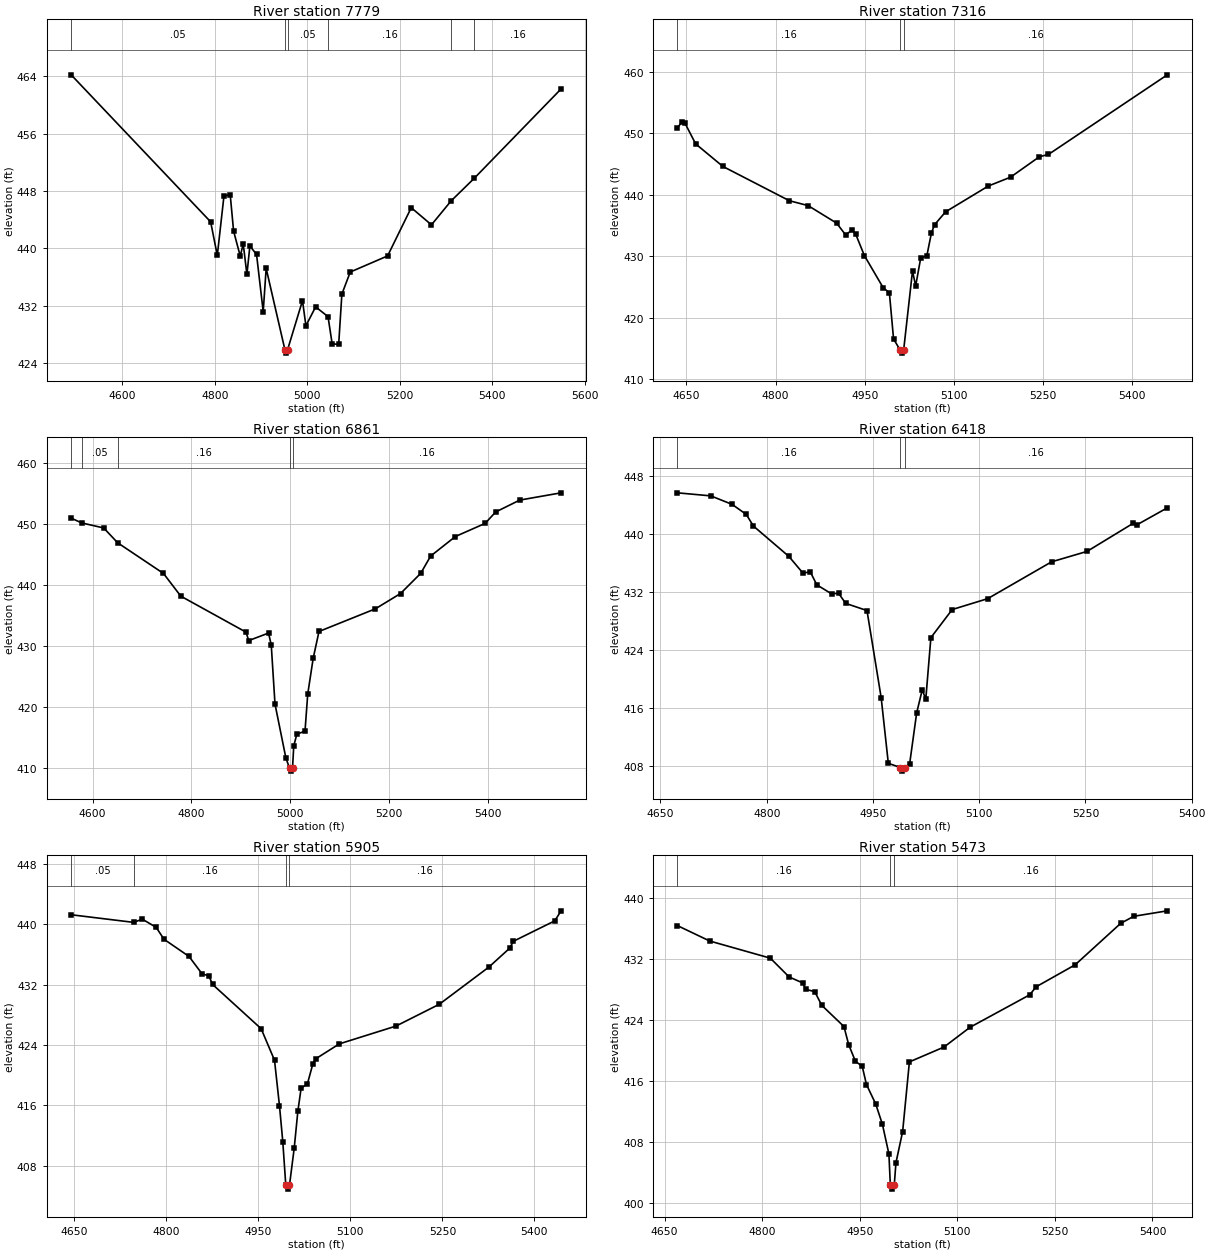
Type RM Length L Ch R = 1,7779,463,463,463
BEGIN DESCRIPTION:
WEST FORK PANTHER CREEK 15.0
END DESCRIPTION:
XS GIS Cut Line= 5
      3604431.64     10490564.83      3604788.44     10490851.32
      3604890.01     10490960.69      3604999.38     10491049.23
      3605272.82     10491197.67
#Sta/Elev= 30
  4489.7  464.22  4791.1  443.70  4805.5  439.01  4819.9  447.31  4833.4  447.49
  4840.7  442.41  4855.1  438.91  4861.5  440.62  4869.5  436.36  4875.9  440.33
  4890.3  439.15  4904.7  431.16  4911.1  437.20  4951.5  425.87  4954.2  425.37
  4957.5  425.87  4989.6  432.70  4997.0  429.19  5018.0  431.83  5044.8  430.46
  5053.7  426.67  5067.8  426.59  5074.7  433.61  5092.8  436.69  5173.5  438.94
  5224.6  445.67  5268.3  443.28  5310.9  446.63  5360.5  449.76  5548.4  462.25
#Mann=6,-1,0
  4489.7    0.05       0  4951.5    0.04       0  4957.5    0.05       0
  5044.8    0.16       0  5310.9     0.1       0  5360.5    0.16       0
Bank Sta=4951.5,4957.5
Exp/Cntr=0.3,0.1

Type RM Length L Ch R = 1,7316,455,455,455
BEGIN DESCRIPTION:
WEST FORK PANTHER CREEK 14.0
END DESCRIPTION:
XS GIS Cut Line= 2
      3604400.45     10491182.05      3605184.25     10491437.24
#Sta/Elev= 30
  4634.8  450.88  4642.1  451.83  4647.3  451.72  4665.5  448.30  4711.2  444.63
  4823.2  439.04  4854.8  438.24  4902.7  435.39  4917.9  433.47  4928.4  434.25
  4934.6  433.65  4949.4  430.11  4981.0  424.88  4991.5  424.04  4998.5  416.55
  5009.5  414.72  5012.3  414.22  5015.5  414.72  5030.4  427.60  5035.7  425.16
  5044.1  429.66  5054.6  430.11  5062.3  433.83  5067.6  435.14  5086.1  437.23
  5158.1  441.44  5195.3  442.87  5243.9  446.20  5259.2  446.58  5459.1  459.54
#Mann=3,-1,0
  4634.8    0.16       0  5009.5    0.07       0  5015.5    0.16       0
Bank Sta=5009.5,5015.5
Exp/Cntr=0.3,0.1

Type RM Length L Ch R = 1,6861,443,443,443
BEGIN DESCRIPTION:
WEST FORK PANTHER CREEK 13.0
END DESCRIPTION:
XS GIS Cut Line= 4
      3604272.81     10491353.91      3604460.32     10491577.88
      3604809.28     10491741.94      3605123.11     10491765.28
#Sta/Elev= 30
  4556.6  450.93  4577.9  450.15  4622.6  449.32  4650.7  446.90  4743.6  441.87
  4778.7  438.15  4910.8  432.25  4916.3  430.87  4956.4  432.10  4961.9  430.16
  4969.5  420.47  4991.6  411.61  4999.0  409.98  5001.7  409.48  5005.0  409.98
  5007.5  413.61  5013.7  415.53  5030.3  416.04  5035.8  422.10  5046.8  427.94
  5058.6  432.36  5172.7  436.07  5223.8  438.58  5264.7  441.89  5284.8  444.72
  5334.9  447.92  5395.1  450.07  5416.5  451.94  5465.3  453.89  5549.0  455.08
#Mann=5,-1,0
  4556.6     0.1       0  4577.9    0.05       0  4650.7    0.16       0
  4999.0    0.07       0  5005.0    0.16       0
Bank Sta=4999,5005
Exp/Cntr=0.3,0.1

Type RM Length L Ch R = 1,6418,513,513,513
BEGIN DESCRIPTION:
WEST FORK PANTHER CREEK 12.0
END DESCRIPTION:
XS GIS Cut Line= 2
      3604202.54     10492038.81      3604892.65     10491991.94
#Sta/Elev= 30
  4673.9  445.74  4721.1  445.32  4751.1  444.15  4771.2  442.76  4781.2  441.16
  4831.3  436.97  4851.4  434.64  4861.4  434.87  4870.7  433.05  4891.5  431.81
  4901.5  431.88  4911.5  430.49  4941.6  429.50  4961.6  417.50  4971.7  408.43
  4988.7  407.85  4991.4  407.35  4994.7  407.85  5001.7  408.27  5011.7  415.36
  5019.6  418.57  5024.6  417.27  5031.8  425.76  5061.9  429.64  5112.0  431.14
  5202.2  436.22  5252.3  437.66  5317.5  441.54  5322.6  441.32  5365.6  443.67
#Mann=3,-1,0
  4673.9    0.16       0  4988.7    0.07       0  4994.7    0.16       0
Bank Sta=4988.7,4994.7
Exp/Cntr=0.3,0.1

Type RM Length L Ch R = 1,5905,432,432,432
BEGIN DESCRIPTION:
WEST FORK PANTHER CREEK 11.0
END DESCRIPTION:
XS GIS Cut Line= 3
      3604210.29     10492301.82      3604621.78     10492460.69
      3604976.54     10492414.08
#Sta/Elev= 30
  4644.6  441.25  4746.3  440.24  4760.7  440.66  4783.2  439.58  4796.0  438.00
  4836.8  435.72  4858.3  433.39  4869.0  433.17  4875.2  432.01  4954.4  426.14
  4976.2  421.96  4984.3  415.92  4989.7  411.17  4994.6  405.37  4997.4  404.87
  5000.6  405.37  5008.3  410.29  5014.3  415.22  5019.6  418.26  5029.8  418.82
  5038.9  421.52  5044.2  422.19  5081.9  424.13  5174.3  426.49  5244.9  429.38
  5325.6  434.30  5359.5  436.80  5365.9  437.74  5433.2  440.44  5443.5  441.77
#Mann=4,-1,0
  4644.6    0.05       0  4746.3    0.16       0  4994.6    0.07       0
  5000.6    0.16       0
Bank Sta=4994.6,5000.6
Exp/Cntr=0.3,0.1

Type RM Length L Ch R = 1,5473,562,562,562
BEGIN DESCRIPTION:
WEST FORK PANTHER CREEK 10.0
END DESCRIPTION:
XS GIS Cut Line= 4
      3604220.73     10492648.18      3604376.99     10492770.59
      3604663.44     10492848.71      3604921.23     10492848.71
#Sta/Elev= 30
  4669.6  436.39  4719.4  434.36  4812.5  432.11  4841.4  429.64  4862.2  428.86
  4866.6  428.02  4880.8  427.71  4891.5  425.92  4925.7  423.12  4933.0  420.73
  4943.4  418.54  4953.7  417.92  4960.3  415.50  4974.5  412.95  4984.8  410.28
  4994.8  406.38  4997.0  402.26  4999.7  401.76  5003.0  402.26  5005.6  405.22
  5015.9  409.32  5026.3  418.48  5079.5  420.43  5119.6  423.03  5211.2  427.29
  5221.2  428.35  5281.2  431.24  5351.2  436.69  5371.2  437.61  5422.8  438.33
#Mann=3,-1,0
  4669.6    0.16       0  4997.0    0.07       0  5003.0    0.16       0
Bank Sta=4997,5003
Exp/Cntr=0.3,0.1

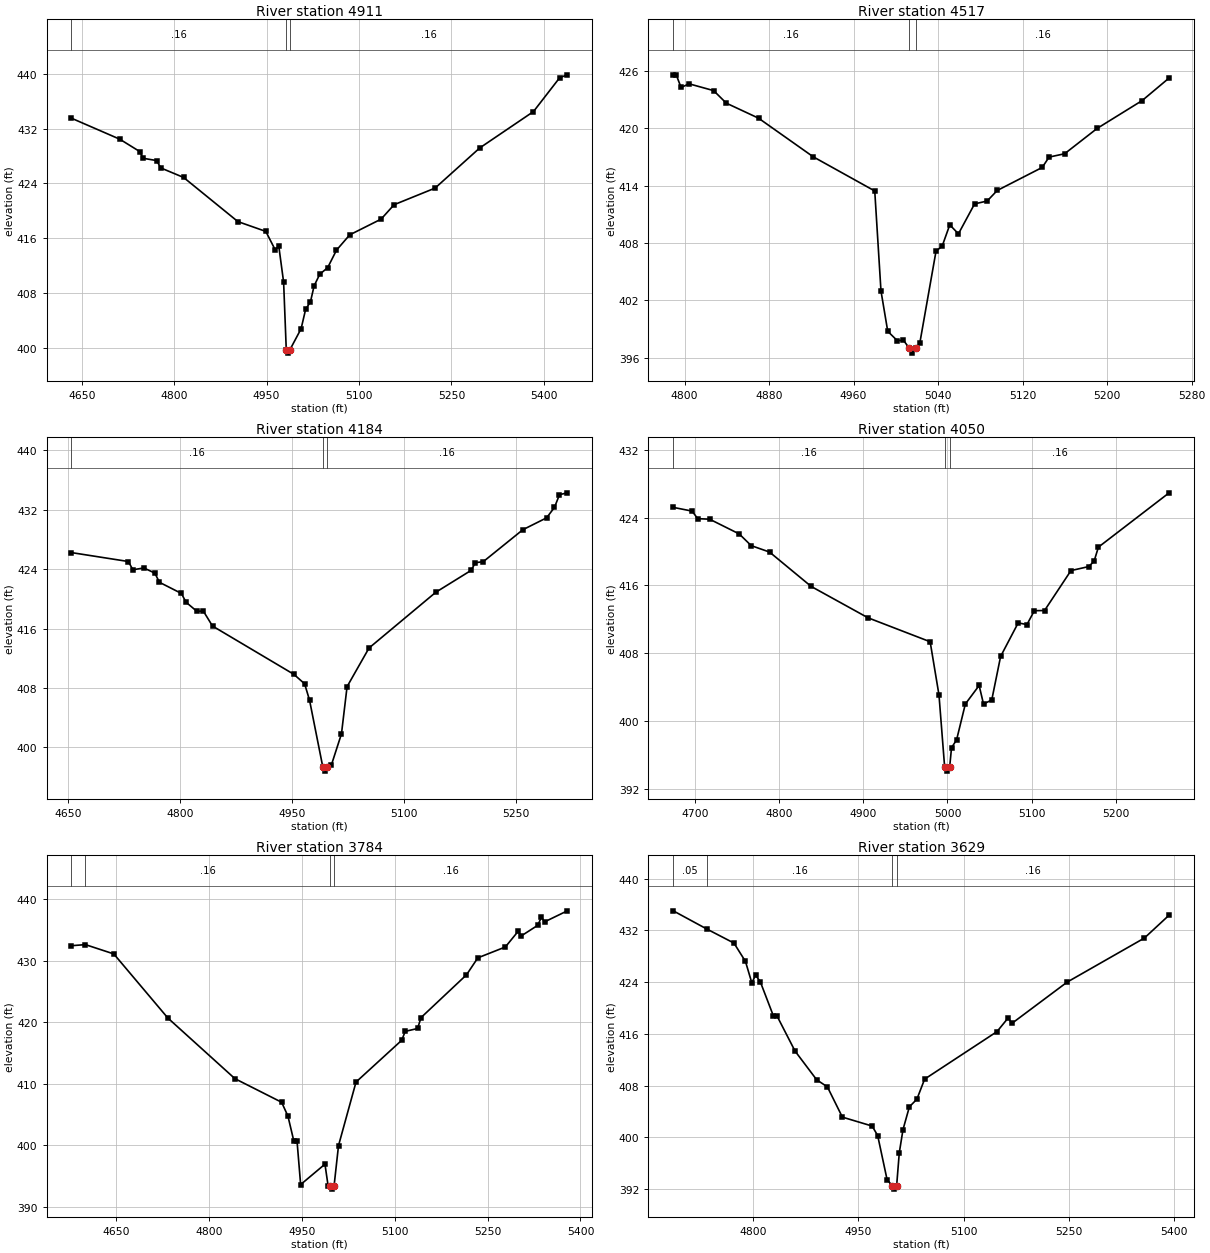
Type RM Length L Ch R = 1,4911,394,394,394
BEGIN DESCRIPTION:
WEST FORK PANTHER CREEK 9.0
END DESCRIPTION:
XS GIS Cut Line= 3
      3604012.39     10492929.43      3604275.42     10493072.67
      3604550.84     10493496.19
#Sta/Elev= 30
  4633.3  433.51  4711.8  430.45  4744.0  428.66  4749.8  427.67  4771.6  427.34
  4778.2  426.27  4815.3  424.88  4903.4  418.45  4948.7  417.02  4963.8  414.36
  4969.8  414.85  4977.6  409.63  4981.9  399.79  4984.7  399.29  4987.9  399.79
  5006.0  402.85  5013.3  405.66  5021.2  406.78  5027.1  409.09  5036.3  410.79
  5049.1  411.74  5063.4  414.29  5084.9  416.52  5135.8  418.81  5156.9  420.91
  5223.4  423.33  5295.9  429.18  5383.1  434.48  5425.7  439.42  5438.0  439.83
#Mann=3,-1,0
  4633.3    0.16       0  4981.9    0.07       0  4987.9    0.16       0
Bank Sta=4981.9,4987.9
Exp/Cntr=0.3,0.1

Type RM Length L Ch R = 1,4517,333,333,333
BEGIN DESCRIPTION:
WEST FORK PANTHER CREEK 8.0
END DESCRIPTION:
XS GIS Cut Line= 2
      3603936.85     10493312.24      3604336.27     10493558.63
#Sta/Elev= 30
  4789.3  425.58  4792.1  425.58  4796.7  424.26  4804.3  424.64  4827.5  423.93
  4839.5  422.62  4870.0  421.05  4921.8  417.01  4980.0  413.44  4985.9  402.99
  4992.3  398.77  5001.3  397.80  5007.2  397.83  5012.8  396.99  5015.5  396.49
  5018.8  396.99  5022.6  397.51  5038.0  407.15  5043.8  407.67  5051.0  409.90
  5059.2  408.96  5074.5  412.09  5086.4  412.39  5095.9  413.49  5138.5  415.90
  5145.0  416.98  5159.7  417.33  5190.5  419.98  5233.1  422.89  5258.6  425.25
#Mann=3,-1,0
  4789.3    0.16       0  5012.8    0.07       0  5018.8    0.16       0
Bank Sta=5012.8,5018.8
Exp/Cntr=0.3,0.1

Type RM Length L Ch R = 1,4184,134,134,134
BEGIN DESCRIPTION:
Mapping XS e1483107
END DESCRIPTION:
XS GIS Cut Line= 3
      3603776.56     10493457.90      3604125.54     10493710.52
      3604345.80     10493788.26
#Sta/Elev= 30
  4654.2  426.23  4730.4  425.03  4736.5  423.92  4751.2  424.16  4765.9  423.47
  4772.1  422.23  4801.5  420.73  4807.7  419.55  4822.4  418.31  4830.8  418.37
  4843.2  416.34  4952.3  409.83  4966.6  408.56  4973.2  406.36  4991.1  397.30
  4993.8  396.80  4997.1  397.30  5002.6  397.66  5016.0  401.83  5023.5  408.18
  5052.9  413.38  5142.4  420.89  5189.6  423.83  5195.4  424.87  5206.0  425.01
  5259.0  429.31  5290.8  430.91  5301.4  432.32  5308.1  434.03  5318.6  434.28
#Mann=3,-1,0
  4654.2    0.16       0  4991.1    0.07       0  4997.1    0.16       0
Bank Sta=4991.1,4997.1
Exp/Cntr=0.3,0.1

Type RM Length L Ch R = 1,4050,266,266,266
BEGIN DESCRIPTION:
WEST FORK PANTHER CREEK 7.0
END DESCRIPTION:
XS GIS Cut Line= 3
      3603736.39     10493562.29      3603890.01     10493736.73
      3604231.12     10493840.89
#Sta/Elev= 30
  4674.2  425.23  4696.6  424.79  4703.2  423.90  4717.5  423.83  4752.6  422.09
  4766.8  420.71  4788.6  419.95  4838.0  415.89  4905.6  412.18  4979.4  409.35
  4989.9  403.06  4996.6  394.56  4999.3  394.06  5002.6  394.56  5004.8  396.83
  5010.8  397.75  5021.2  401.99  5037.6  404.18  5042.8  401.99  5052.6  402.47
  5063.1  407.61  5084.0  411.58  5094.4  411.38  5103.2  413.02  5115.3  413.04
  5146.7  417.76  5167.6  418.23  5174.1  418.85  5179.3  420.53  5263.3  426.95
#Mann=3,-1,0
  4674.2    0.16       0  4996.6    0.07       0  5002.6    0.16       0
Bank Sta=4996.6,5002.6
Exp/Cntr=0.3,0.1

Type RM Length L Ch R = 1,3784,155,155,155
BEGIN DESCRIPTION:
Mapping XS 49cd5db2
END DESCRIPTION:
XS GIS Cut Line= 3
      3603537.03     10493921.47      3604065.65     10494030.83
      3604315.14     10493952.87
#Sta/Elev= 30
  4577.5  432.48  4600.1  432.65  4645.9  431.14  4733.3  420.71  4841.6  410.85
  4917.1  407.01  4927.3  404.75  4936.9  400.66  4942.0  400.68  4947.8  393.62
  4987.1  396.94  4992.2  393.41  4995.8  393.38  4998.6  392.88  5001.8  393.38
  5009.0  399.96  5037.3  410.30  5111.1  417.09  5116.8  418.54  5136.7  419.01
  5142.4  420.79  5215.8  427.74  5234.1  430.50  5278.6  432.27  5299.1  434.80
  5304.3  434.07  5331.0  435.80  5336.8  437.11  5342.1  436.36  5378.7  438.15
#Mann=4,-1,0
  4577.5    0.05       0  4600.1    0.16       0  4995.8    0.07       0
  5001.8    0.16       0
Bank Sta=4995.8,5001.8
Exp/Cntr=0.3,0.1

Type RM Length L Ch R = 1,3629,496,496,496
BEGIN DESCRIPTION:
WEST FORK PANTHER CREEK 6.0
END DESCRIPTION:
XS GIS Cut Line= 3
      3603582.72     10494036.21      3603975.94     10494176.84
      3604264.83     10494169.03
#Sta/Elev= 30
  4686.3  435.04  4733.7  432.25  4772.8  430.05  4789.2  427.21  4798.3  423.88
  4803.6  425.10  4810.4  424.05  4829.1  418.75  4834.4  418.72  4859.8  413.35
  4890.6  408.91  4906.0  407.79  4927.3  403.12  4969.7  401.74  4977.6  400.27
  4991.0  393.45  4998.6  392.48  5001.4  391.98  5004.6  392.48  5008.4  397.61
  5013.7  401.20  5022.8  404.72  5033.5  405.90  5044.5  409.00  5147.6  416.35
  5163.7  418.49  5168.7  417.61  5247.6  424.01  5357.7  430.83  5392.9  434.37
#Mann=4,-1,0
  4686.3    0.05       0  4733.7    0.16       0  4998.6    0.07       0
  5004.6    0.16       0
Bank Sta=4998.6,5004.6
Exp/Cntr=0.3,0.1