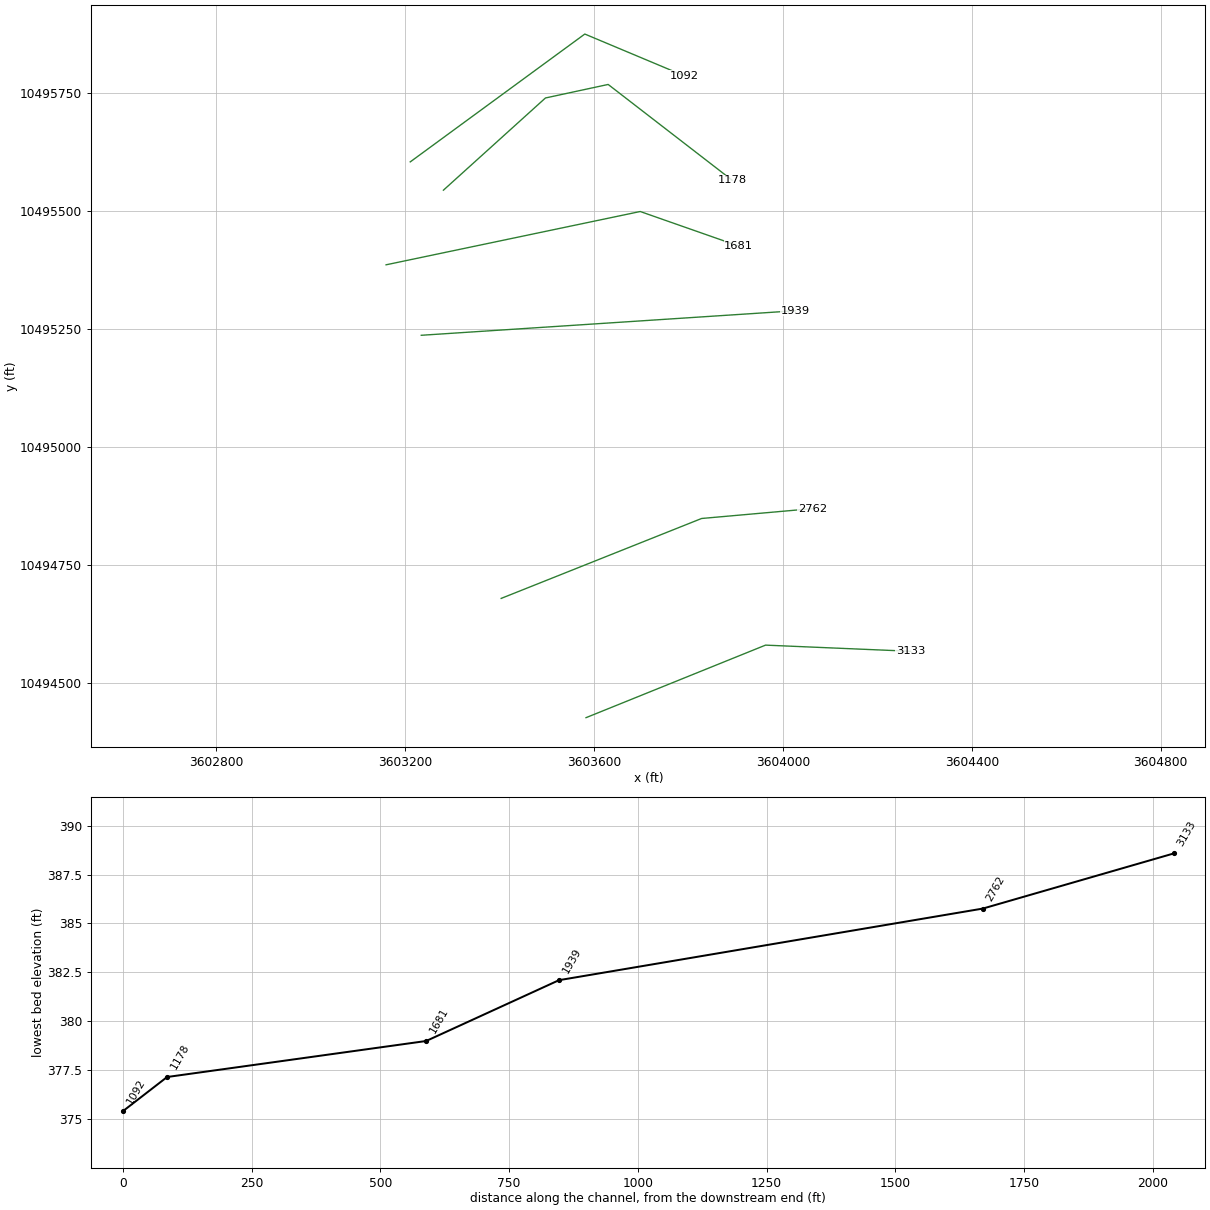
HEC-RAS study WEST FORK PANTHER CREEK.prj: WEST FORK PANTHER CREEK Base Level Engineering

--- WEST FORK PANTHER CREEK.g01 (geometry) --- (continued)

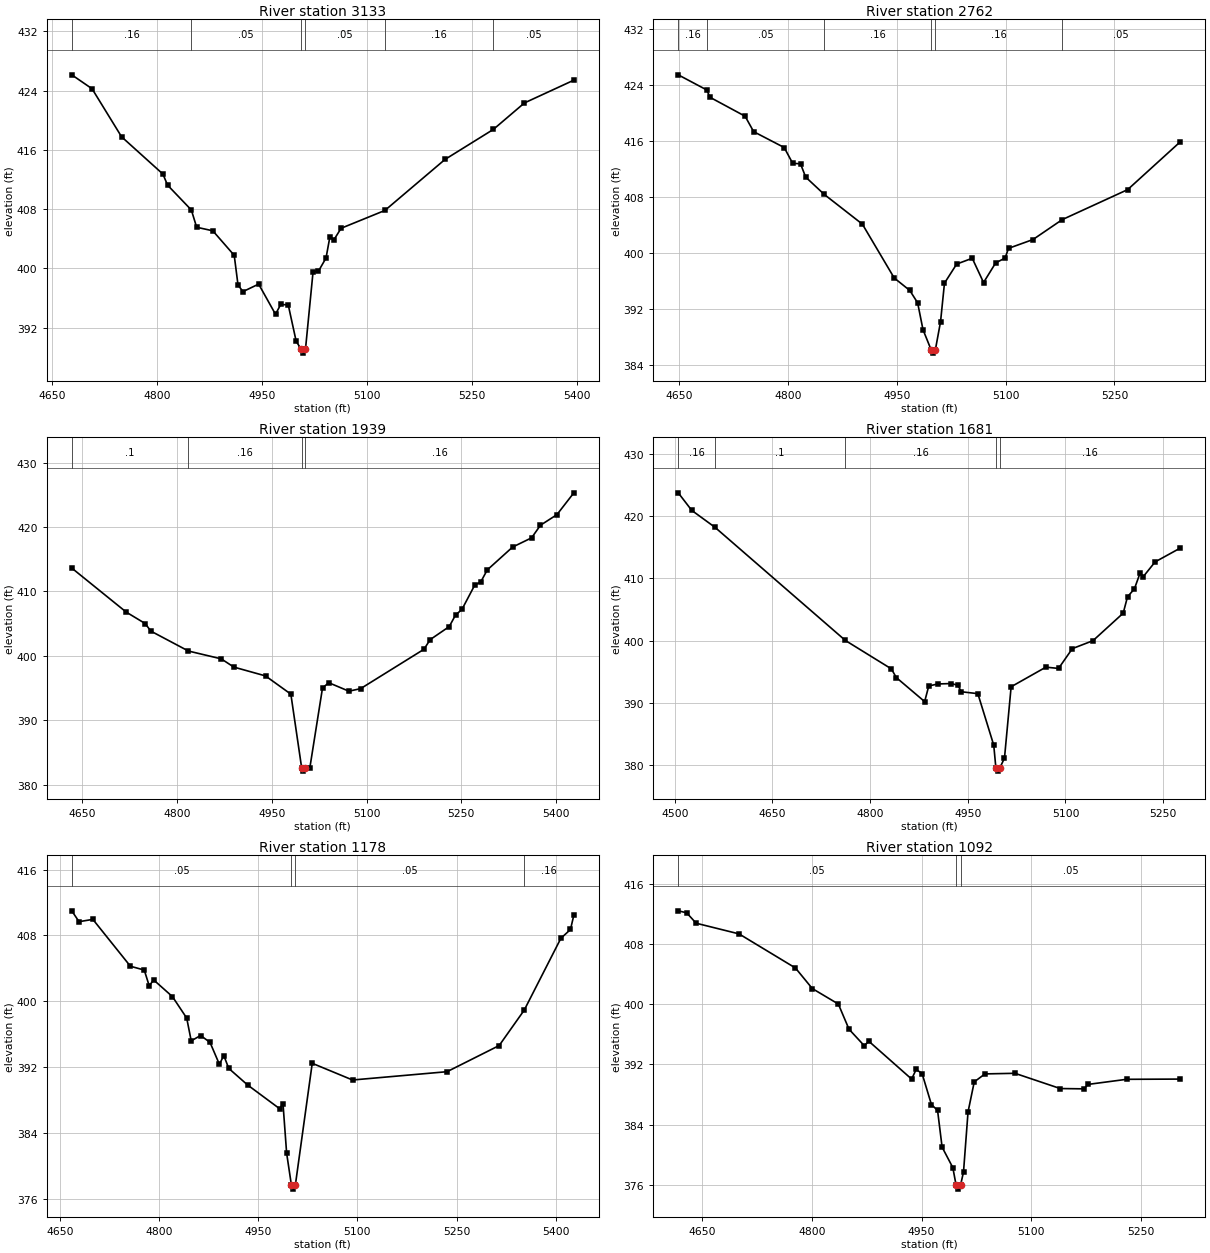
Type RM Length L Ch R = 1,3133,371,371,371
BEGIN DESCRIPTION:
WEST FORK PANTHER CREEK 5.0
END DESCRIPTION:
XS GIS Cut Line= 3
      3603582.72     10494426.84      3603962.92     10494580.48
      3604270.17     10494567.46
#Sta/Elev= 30
  4677.9  426.12  4706.9  424.24  4749.1  417.76  4808.2  412.73  4814.8  411.24
  4848.8  407.89  4856.4  405.56  4879.5  405.08  4910.1  401.77  4915.5  397.77
  4922.6  396.88  4945.0  397.89  4969.1  393.82  4976.5  395.14  4987.3  395.09
  4998.6  390.19  5005.9  389.08  5008.7  388.58  5011.9  389.08  5022.8  399.59
  5030.5  399.64  5041.3  401.41  5046.9  404.31  5052.3  403.82  5062.8  405.42
  5125.5  407.83  5211.4  414.71  5280.5  418.76  5324.9  422.33  5395.5  425.40
#Mann=6,-1,0
  4677.9    0.16       0  4848.8    0.05       0  5005.9   0.035       0
  5011.9    0.05       0  5125.5    0.16       0  5280.5    0.05       0
Bank Sta=5005.9,5011.9
Exp/Cntr=0.3,0.1

Type RM Length L Ch R = 1,2762,823,823,823
BEGIN DESCRIPTION:
WEST FORK PANTHER CREEK 4.0
END DESCRIPTION:
XS GIS Cut Line= 3
      3603403.02     10494679.44      3603827.51     10494848.71
      3604061.89     10494869.55
#Sta/Elev= 30
  4648.6  425.42  4688.0  423.26  4692.2  422.23  4740.8  419.52  4752.6  417.32
  4794.7  415.06  4806.4  412.81  4817.2  412.74  4824.3  410.85  4849.9  408.38
  4902.5  404.14  4946.4  396.47  4967.9  394.69  4978.7  392.93  4986.1  389.10
  4997.2  386.26  4999.9  385.76  5003.2  386.26  5010.3  390.24  5015.7  395.73
  5032.5  398.45  5054.0  399.28  5069.6  395.82  5086.3  398.62  5099.3  399.31
  5104.0  400.69  5137.8  401.95  5178.0  404.78  5268.3  409.06  5340.9  415.88
#Mann=6,-1,0
  4648.6    0.16       0  4688.0    0.05       0  4849.9    0.16       0
  4997.2    0.07       0  5003.2    0.16       0  5178.0    0.05       0
Bank Sta=4997.2,5003.2
Exp/Cntr=0.3,0.1

Type RM Length L Ch R = 1,1939,258,258,258
BEGIN DESCRIPTION:
WEST FORK PANTHER CREEK 3.0
END DESCRIPTION:
XS GIS Cut Line= 2
      3603233.73     10495236.73      3604026.33     10495288.70
#Sta/Elev= 30
  4633.7  413.62  4719.8  406.79  4749.8  405.01  4758.9  403.83  4818.3  400.74
  4870.1  399.53  4890.1  398.25  4940.2  396.88  4980.3  394.05  4997.4  382.60
  5000.1  382.10  5003.4  382.60  5010.4  382.65  5030.4  395.03  5040.4  395.82
  5072.1  394.51  5090.6  394.90  5190.8  401.01  5200.8  402.52  5230.9  404.54
  5240.9  406.34  5250.9  407.19  5270.9  410.92  5281.0  411.52  5291.0  413.33
  5331.1  416.88  5361.1  418.31  5375.2  420.27  5401.2  421.91  5428.0  425.30
#Mann=4,-1,0
  4633.7     0.1       0  4818.3    0.16       0  4997.4    0.07       0
  5003.4    0.16       0
Bank Sta=4997.4,5003.4
Exp/Cntr=0.3,0.1

Type RM Length L Ch R = 1,1681,503,503,503
BEGIN DESCRIPTION:
Mapping XS 040b2831
END DESCRIPTION:
XS GIS Cut Line= 3
      3603159.26     10495386.01      3603697.49     10495498.86
      3603906.11     10495425.74
#Sta/Elev= 30
  4505.4  423.79  4526.2  420.96  4561.7  418.25  4762.1  400.02  4832.7  395.45
  4840.2  394.06  4883.8  390.18  4890.1  392.70  4904.2  393.02  4924.7  393.09
  4934.9  392.81  4940.0  391.77  4965.5  391.46  4989.9  383.17  4993.2  379.49
  4995.9  378.99  4999.2  379.49  5006.4  381.10  5016.6  392.57  5070.0  395.73
  5089.4  395.52  5110.6  398.71  5142.3  399.99  5188.7  404.42  5195.3  407.05
  5205.9  408.33  5214.4  410.81  5219.7  410.32  5237.7  412.67  5276.4  414.90
#Mann=5,-1,0
  4505.4    0.16       0  4561.7     0.1       0  4762.1    0.16       0
  4993.2    0.07       0  4999.2    0.16       0
Bank Sta=4993.2,4999.2
Exp/Cntr=0.3,0.1

Type RM Length L Ch R = 1,1178,86,86,86
BEGIN DESCRIPTION:
WEST FORK PANTHER CREEK 2.0
END DESCRIPTION:
XS GIS Cut Line= 4
      3603280.66     10495544.05      3603496.78     10495739.34
      3603629.59     10495767.98      3603892.40     10495565.02
#Sta/Elev= 30
  4668.2  410.99  4679.2  409.67  4700.1  409.95  4756.9  404.25  4777.8  403.79
  4785.3  401.87  4792.0  402.59  4820.4  400.56  4842.0  397.95  4848.8  395.18
  4863.0  395.83  4877.2  395.00  4891.4  392.33  4898.1  393.39  4905.6  391.83
  4934.0  389.82  4982.5  386.93  4987.6  387.54  4993.1  381.52  5000.3  377.65
  5003.0  377.15  5006.3  377.65  5031.8  392.45  5092.8  390.42  5235.7  391.43
  5314.5  394.61  5352.4  398.92  5407.8  407.65  5422.3  408.72  5427.4  410.47
#Mann=4,-1,0
  4668.2    0.05       0  5000.3    0.03       0  5006.3    0.05       0
  5352.4    0.16       0
Bank Sta=5000.3,5006.3
Exp/Cntr=0.3,0.1

Type RM Length L Ch R = 1,1092,0,0,0
BEGIN DESCRIPTION:
WEST FORK PANTHER CREEK 1.0
END DESCRIPTION:
XS GIS Cut Line= 3
      3603210.35     10495603.94      3603580.11     10495874.75
      3603791.06     10495786.21
#Sta/Elev= 30
  4617.0  412.45  4628.5  412.19  4641.5  410.80  4700.2  409.38  4777.4  404.84
  4800.5  402.10  4836.1  400.04  4850.7  396.69  4871.6  394.49  4877.8  395.09
  4936.4  390.05  4942.6  391.33  4950.7  390.79  4963.5  386.66  4971.9  385.88
  4978.1  380.99  4992.8  378.26  4997.3  375.90  5000.1  375.40  5003.3  375.90
  5007.4  377.69  5013.6  385.68  5022.1  389.68  5036.8  390.74  5077.8  390.82
  5139.8  388.79  5172.3  388.75  5177.7  389.34  5230.6  390.02  5304.1  390.05
#Mann=3,-1,0
  4617.0    0.05       0  4997.3    0.03       0  5003.3    0.05       0
Bank Sta=4997.3,5003.3
Exp/Cntr=0.3,0.1

Chan Stop Cuts=-1