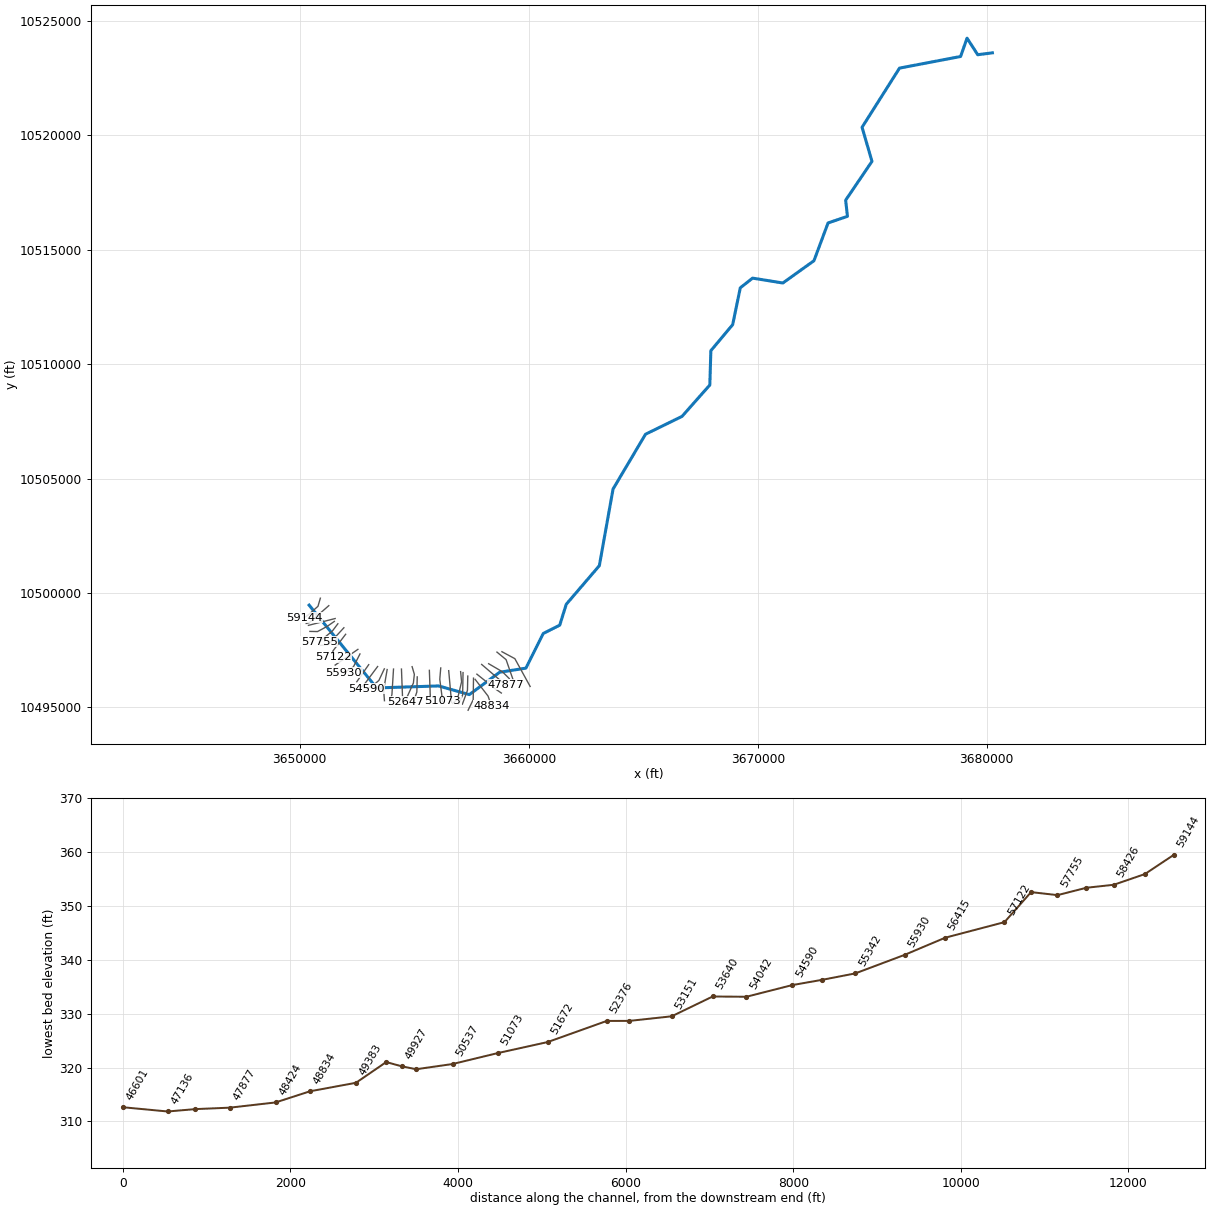
--- WHEELOCK CREEK.prj (project) ---

Proj Title=WHEELOCK CREEK Base Level Engineering
Current Plan=p01
Default Exp/Contr=0.3,0.1
English Units
Geom File=g01
Flow File=f01
Plan File=p01
Y Axis Title=Elevation
X Axis Title(PF)=Main Channel Distance
X Axis Title(XS)=Station
BEGIN DESCRIPTION:
WHEELOCK CREEK
END DESCRIPTION:
DSS Export Rating Curves= 0
DSS Export Rating Curve Sorted= 0
DSS Export Volume Flow Curves= 0
DXF OffsetX= 0
DXF OffsetY= 0
DXF ScaleX= 1
DXF ScaleY= 10

--- WHEELOCK CREEK.p01 (plan) ---

Plan Title=Multiple Run
Short Identifier=Multiple
Geom File=g01
Flow File=f01
Subcritical Flow
K Sum by GR= 0
Std Step Tol= 0.01
Critical Tol= 0.01
Num of Std Step Trials= 20
Max Error Tol= 0.3
Flow Tol Ratio= 0.001
Split Flow NTrial= 30
Split Flow Tol= 0.02
Split Flow Ratio= 0.02
Log Output Level= 0
Friction Slope Method= 1
Unsteady Friction Slope Method= 2
Unsteady Bridges Friction Slope Method= 1
Parabolic Critical Depth
Global Vel Dist=  1 , 1 , 1
Global Log Level= 0
CheckData=True
Encroach Param= -1, 0, 0, 0
BEGIN DESCRIPTION:
Multiple Run
END DESCRIPTION:

--- WHEELOCK CREEK.f01 (steady flow) ---

Flow Title=Multiple
Program Version=4.10
Number of Profiles= 7
Profile Names=10-year,25-year,50-year,1pct_min,100-year,1pct_plu,500-year
River Rch & RM=WHEELOCK CREEK,Reach-1         ,59144
     836    1149    1409    1266    1712    2315    2530
River Rch & RM=WHEELOCK CREEK,Reach-1         ,54042
    1443    2038    2546    2326    3146    4254    4816
River Rch & RM=WHEELOCK CREEK,Reach-1         ,51672
    1623    2301    2883    2640    3571    4829    5500
River Rch & RM=WHEELOCK CREEK,Reach-1         ,48834
    1637    2316    2897    2648    3581    4843    5495
River Rch & RM=WHEELOCK CREEK,Reach-1         ,45043
    1839    2611    3274    3000    4057    5487    6257
River Rch & RM=WHEELOCK CREEK,Reach-1         ,43591
    1839    2611    3274    3000    4057    5487    6257
River Rch & RM=WHEELOCK CREEK,Reach-1         ,41183
    2217    3168    3988    3668    4961    6709    7712
River Rch & RM=WHEELOCK CREEK,Reach-1         ,36684
    2892    4185    5316    4931    6669    9019   10546
River Rch & RM=WHEELOCK CREEK,Reach-1         ,34625
    2890    4170    5286    4893    6617    8949   10420
River Rch & RM=WHEELOCK CREEK,Reach-1         ,31838
    2990    4319    5478    5074    6862    9280   10819
River Rch & RM=WHEELOCK CREEK,Reach-1         ,28515
    3135    4535    5759    5338    7219    9763   11402
River Rch & RM=WHEELOCK CREEK,Reach-1         ,27304
    3130    4513    5717    5286    7149    9668   11235
River Rch & RM=WHEELOCK CREEK,Reach-1         ,24791
    3287    4746    6019    5571    7535   10190   11866
River Rch & RM=WHEELOCK CREEK,Reach-1         ,23764
    3287    4746    6019    5571    7535   10190   11866
River Rch & RM=WHEELOCK CREEK,Reach-1         ,18963
    3459    5000    6346    5878    7950   10751   12537
River Rch & RM=WHEELOCK CREEK,Reach-1         ,18346
    3459    5000    6346    5878    7950   10751   12537
River Rch & RM=WHEELOCK CREEK,Reach-1         ,15897
    3454    4981    6312    5836    7892   10673   12401
River Rch & RM=WHEELOCK CREEK,Reach-1         ,8018
    3642    5250    6651    6147    8313   11242   13051
Boundary for River Rch & Prof#=WHEELOCK CREEK,Reach-1         , 1
Up Type= 0
Dn Type= 3
Dn Slope=0.002
Boundary for River Rch & Prof#=WHEELOCK CREEK,Reach-1         , 2
Up Type= 0
Dn Type= 3
Dn Slope=0.002
Boundary for River Rch & Prof#=WHEELOCK CREEK,Reach-1         , 3
Up Type= 0
Dn Type= 3
Dn Slope=0.002
Boundary for River Rch & Prof#=WHEELOCK CREEK,Reach-1         , 4
Up Type= 0
Dn Type= 3
Dn Slope=0.002
Boundary for River Rch & Prof#=WHEELOCK CREEK,Reach-1         , 5
Up Type= 0
Dn Type= 3
Dn Slope=0.002
Boundary for River Rch & Prof#=WHEELOCK CREEK,Reach-1         , 6
Up Type= 0
Dn Type= 3
Dn Slope=0.002
Boundary for River Rch & Prof#=WHEELOCK CREEK,Reach-1         , 7
Up Type= 0
Dn Type= 3
Dn Slope=0.002
DSS Import GetInterval= 0
DSS Import GetPeak= 0
DSS Import FillOption= 0

--- WHEELOCK CREEK.g01 (geometry) ---

Geom Title=Existing Conditions
Program Version=4.10

River Reach=WHEELOCK CREEK  ,Reach-1
Reach XY= 30
       3650409.5       10499470.       3653357.5       10495852.
        3656065.       10495940.      3657404.75       10495561.
       3658730.5       10496538.      3659876.25       10496718.
      3660632.75       10498232.       3661352.5       10498594.
       3661637.5       10499507.        3663082.       10501194.
      3663681.75       10504545.      3665098.75       10506938.
      3666693.75       10507719.      3667907.25       10509091.
        3667952.       10510589.        3668905.       10511727.
      3669237.25       10513336.      3669773.75       10513760.
        3671096.       10513547.       3672453.5       10514519.
       3673070.5       10516171.       3673917.5       10516460.
      3673838.75       10517166.      3674987.75       10518863.
      3674555.25       10520352.      3676190.75       10522937.
      3678858.25       10523445.        3679139.       10524245.
        3679607.       10523522.      3680247.09     10523604.84

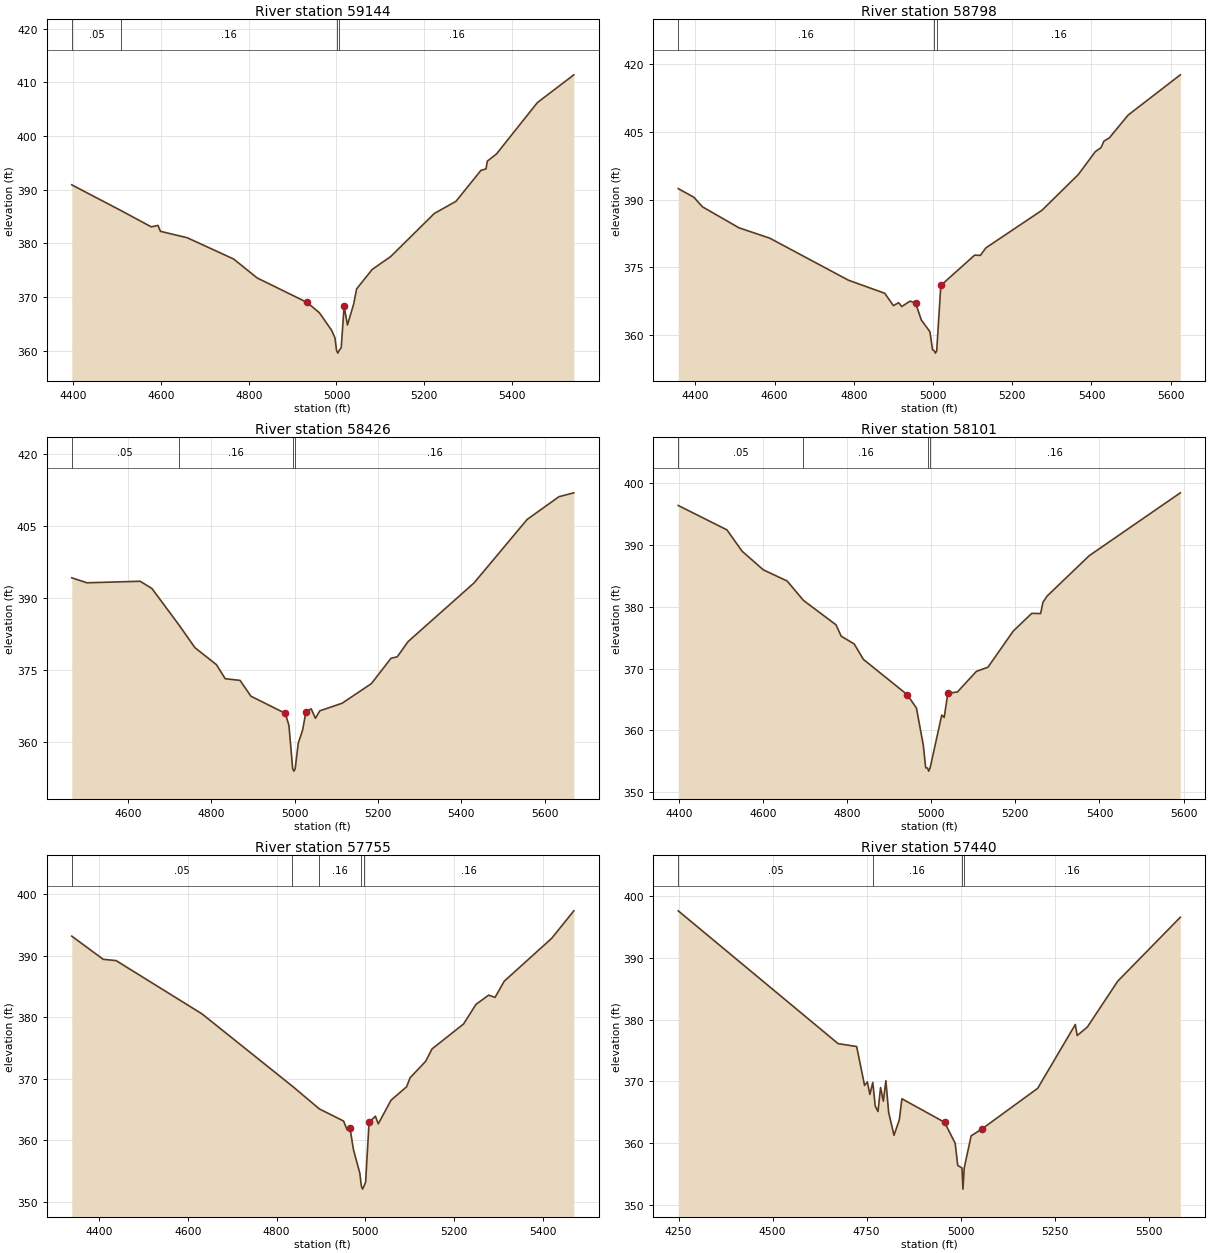
Type RM Length L Ch R = 1 ,59144   ,346,346,346
BEGIN DESCRIPTION:
WHEELOCK CREEK 108.0
END DESCRIPTION:
XS GIS Cut Line= 4
      3650900.05     10499774.11      3650795.89     10499419.94
      3650365.33       10499038.      3650198.68      10498926.9
#Sta/Elev= 30
  4396.3  390.89  4508.7  386.09  4577.6  383.06    4593  383.33  4598.4  382.23
  4659.7  381.03  4765.5  377.06  4819.2  373.53    4933  368.97    4961  367.05
    4989  363.76  4996.5  362.37  5000.2  360.02    5003  359.52  5006.2  360.02
  5010.8  360.54  5017.4  368.26    5025  364.76  5039.2  368.68  5045.9  371.49
  5081.3  375.11  5123.7  377.53  5223.2  385.56  5272.5  387.82  5329.4  393.59
    5341  393.86    5344  395.31    5365  396.66  5458.2  406.23  5541.3   411.4
#Mann= 4 ,-1 , 0
  4396.3     .05       0  4508.7     .16       0  5000.2     .07       0
  5006.2     .16       0
Bank Sta=4933,5017.4
XS Rating Curve= 0 ,0
Exp/Cntr=0.3,0.1

Type RM Length L Ch R = 1 ,58798   ,372,372,372
BEGIN DESCRIPTION:
WHEELOCK CREEK 107.0
END DESCRIPTION:
XS GIS Cut Line= 3
      3651268.13     10499447.74      3650427.83     10498711.61
      3650283.26      10498670.3
#Sta/Elev= 30
  4356.8  392.42  4396.2  390.51    4418  388.38  4510.1  383.73  4587.9  381.43
  4786.3  372.12  4878.3   369.2  4899.9  366.48  4913.4  367.12    4921  366.27
  4941.9  367.47  4956.1  367.02  4970.4   363.3  4992.2  360.69  4998.8  356.68
  5003.3  356.44    5006  355.94  5009.3  356.44  5019.7  370.95  5105.1  377.67
  5119.4  377.61  5133.6  379.29    5275  387.61  5367.1  395.56  5409.8  400.63
    5424  401.49  5431.6  402.97    5445  403.65  5492.5  408.72  5624.3  417.65
#Mann= 3 ,-1 , 0
  4356.8     .16       0  5003.3     .07       0  5009.3     .16       0
Bank Sta=4956.1,5019.7
XS Rating Curve= 0 ,0
Exp/Cntr=0.3,0.1

Type RM Length L Ch R = 1 ,58426   ,325,325,325
BEGIN DESCRIPTION:
Mapping XS 6e9604d1
END DESCRIPTION:
XS GIS Cut Line= 2
      3651545.89     10498885.22       3650379.2     10498586.61
#Sta/Elev= 30
  4465.6  394.22    4502  393.18  4629.6   393.5  4657.9  391.99  4722.3  384.45
  4761.1  379.66  4812.7  376.12  4833.6   373.2  4869.3  372.85  4895.3  369.56
  4977.9  365.98  4986.5  363.47  4995.5  354.45  4998.3  353.95  5001.5  354.45
  5008.8  359.77  5019.2  362.46  5027.3  366.28  5039.8  366.93  5050.1  364.96
  5060.5  366.51  5114.1  368.09  5184.3  372.18  5231.4  377.46  5246.3  377.76
  5272.2  380.93  5430.3  393.13  5557.9  406.38  5634.3  411.12  5669.9  411.92
#Mann= 4 ,-1 , 0
  4465.6     .05       0  4722.3     .16       0  4995.5     .07       0
  5001.5     .16       0
Bank Sta=4977.9,5027.3
XS Rating Curve= 0 ,0
Exp/Cntr=0.3,0.1

Type RM Length L Ch R = 1 ,58101   ,346,346,346
BEGIN DESCRIPTION:
WHEELOCK CREEK 106.0
END DESCRIPTION:
XS GIS Cut Line= 4
      3651511.21     10498760.25      3651191.72       10498538.
      3650775.05     10498315.78      3650443.13     10498322.69
#Sta/Elev= 30
  4398.8  396.42  4514.6  392.47  4550.4  389.03    4601     386  4657.7  384.19
  4696.4  381.05  4773.8   377.1  4786.2  375.25    4817     374  4838.9   371.5
    4943  365.79    4965  363.62  4981.3   357.6    4987  353.95  4991.4   353.9
  4994.1   353.4  4997.4   353.9  5025.2  362.48  5030.9  362.09  5039.7  366.01
  5062.4  366.22  5107.4  369.55    5135  370.23  5195.2  376.09  5239.1  378.95
  5260.2  378.92  5265.7  380.74  5275.7  381.76  5375.7  388.29  5592.2  398.47
#Mann= 4 ,-1 , 0
  4398.8     .05       0  4696.4     .16       0  4991.4     .07       0
  4997.4     .16       0
Bank Sta=4943,5039.7
XS Rating Curve= 0 ,0
Exp/Cntr=0.3,0.1

Type RM Length L Ch R = 1 ,57755   ,315,315,315
BEGIN DESCRIPTION:
WHEELOCK CREEK 105.0
END DESCRIPTION:
XS GIS Cut Line= 3
      3651663.95     10498656.06      3651427.83     10498343.56
      3650858.43     10497871.37
#Sta/Elev= 30
  4338.4  393.21  4409.2  389.44  4438.3  389.23  4631.8  380.56  4835.8  368.77
  4896.3  365.09    4951  363.11  4958.8  361.69  4965.3  362.01  4973.1  358.48
  4987.5  354.63    4991  352.53  4993.7  352.03    4997  352.53  5000.6  353.19
  5008.3  362.88  5022.6  363.91  5029.1  362.66  5057.8   366.5  5092.9  368.69
  5100.8  370.16  5135.9  372.84  5150.2  374.85  5221.4  378.92  5249.2   382.1
  5277.9  383.61  5292.2  383.24    5313  385.88  5419.8  392.85  5469.8  397.33
#Mann= 5 ,-1 , 0
  4338.4     .05       0  4835.8      .1       0  4896.3     .16       0
    4991     .07       0    4997     .16       0
Bank Sta=4965.3,5008.3
XS Rating Curve= 0 ,0
Exp/Cntr=0.3,0.1

Type RM Length L Ch R = 1 ,57440   ,318,318,318
BEGIN DESCRIPTION:
WHEELOCK CREEK 104.0
END DESCRIPTION:
XS GIS Cut Line= 3
      3651927.83     10498482.45      3651254.22     10497753.28
      3650914.25     10497711.65
#Sta/Elev= 30
  4249.2  397.59  4674.3  376.12  4723.7  375.65  4744.7  369.36  4752.1  369.92
  4758.9   367.9  4766.6  369.84  4773.1  366.03  4780.4  365.14  4787.3  369.01
  4794.6  366.82  4801.4  370.12  4808.8     365    4823   361.3  4837.1  363.79
    4844   367.2  4957.4   363.4  4985.7     360  4992.5  356.41  5003.7  356.02
  5006.4  352.59  5009.7  356.02  5028.2  361.21    5056  362.28  5205.1  368.89
  5305.2  379.21  5310.2  377.43  5337.2   378.8  5417.8   386.2  5584.4  396.55
#Mann= 4 ,-1 , 0
  4249.2     .05       0  4766.6     .16       0  5003.7     .07       0
  5009.7     .16       0
Bank Sta=4957.4,5056
XS Rating Curve= 0 ,0
Exp/Cntr=0.3,0.1

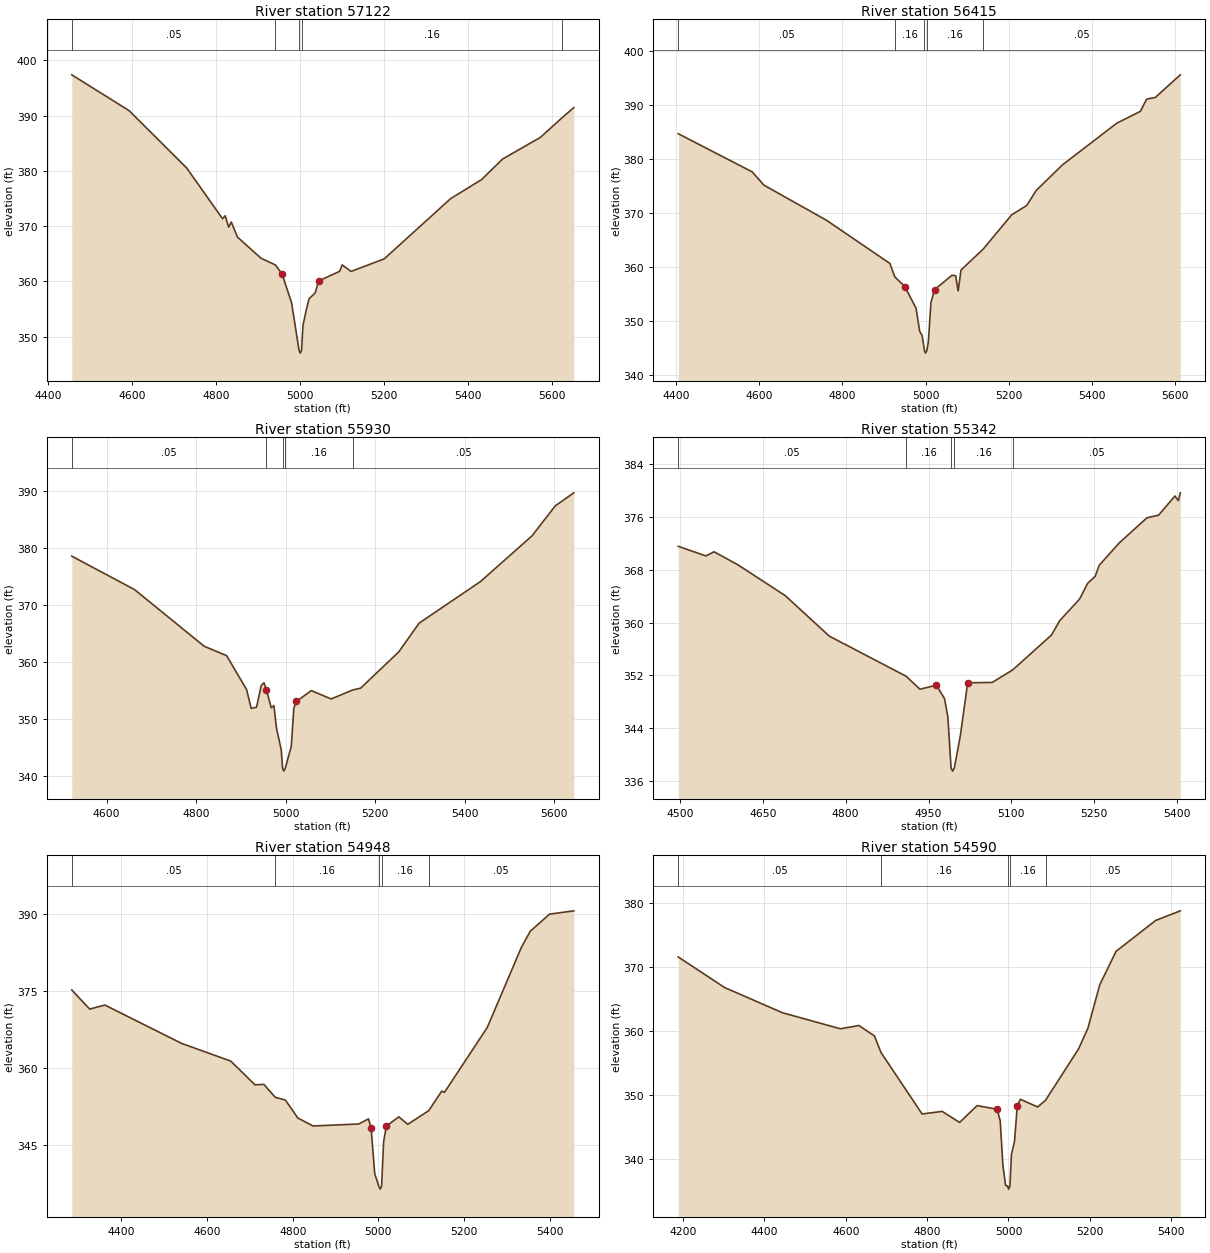
Type RM Length L Ch R = 1 ,57122   ,707,707,707
BEGIN DESCRIPTION:
WHEELOCK CREEK 103.0
END DESCRIPTION:
XS GIS Cut Line= 3
      3652004.23     10498197.73      3651448.67     10497468.56
      3651455.61     10497190.75
#Sta/Elev= 30
  4457.2  397.39  4593.6  390.91  4730.7  380.52    4816  371.34  4822.3  371.87
  4830.5  369.82  4836.8  370.74  4851.4  368.02  4907.5  364.19  4941.9  362.96
  4957.4  361.37  4980.2  356.13    4998  347.51  5000.8  347.01    5004  347.51
  5007.3  352.02  5015.6  354.98  5021.9  356.86  5036.4  357.92  5044.6  360.08
  5094.5  361.81  5100.8  362.98  5121.6   361.8  5200.6  364.07  5358.5  374.97
  5432.3  378.43  5482.3  382.15  5572.3  386.07  5624.5  389.67  5651.8  391.46
#Mann= 5 ,-1 , 0
  4457.2     .05       0  4941.9     .16       0    4998     .07       0
    5004     .16       0  5624.5     .05       0
Bank Sta=4957.4,5044.6
XS Rating Curve= 0 ,0
Exp/Cntr=0.3,0.1

Type RM Length L Ch R = 1 ,56415   ,485,485,485
BEGIN DESCRIPTION:
WHEELOCK CREEK 102.0
END DESCRIPTION:
XS GIS Cut Line= 2
      3652538.97     10497538.02      3651545.93     10496850.53
#Sta/Elev= 30
    4405  384.67  4583.1  377.61    4611  375.17  4762.2  368.65  4914.2  360.69
    4926  358.22    4950  356.43  4977.1  352.42  4985.8  348.15  4991.9  347.35
  4997.2  344.62  4999.9  344.12  5003.2  344.62  5006.8  346.26  5012.9  353.44
  5021.6  355.85  5063.5  358.51  5072.3  358.42  5078.4  355.61  5085.3  359.48
  5138.6  363.34    5207  369.67  5243.4  371.41  5266.3   374.2  5329.1   378.9
  5460.2  386.62  5516.9  388.81  5531.8  391.06  5552.7  391.37  5612.8  395.55
#Mann= 5 ,-1 , 0
    4405     .05       0    4926     .16       0  4997.2     .07       0
  5003.2     .16       0  5138.6     .05       0
Bank Sta=4950,5021.6
XS Rating Curve= 0 ,0
Exp/Cntr=0.3,0.1

Type RM Length L Ch R = 1 ,55930   ,588,588,588
BEGIN DESCRIPTION:
WHEELOCK CREEK 101.0
END DESCRIPTION:
XS GIS Cut Line= 3
      3652629.34     10497337.68      3652342.91     10496773.49
      3651927.93     10496514.13
#Sta/Elev= 30
    4522  378.62  4662.2  372.76    4818  362.82  4868.1  361.17  4912.7  355.23
  4922.9  351.94  4934.9  352.13  4945.4  355.93  4951.6  356.42  4957.2  355.14
  4967.8  352.03  4973.8  352.42  4979.4  348.52  4990.2  344.64  4993.1  341.43
  4995.8  340.93  4999.1  341.43  5012.6  345.26  5018.3  351.98    5024  353.14
  5057.3  355.05  5101.8  353.58  5150.2  355.17  5167.5  355.47    5253  361.85
  5298.4  366.88  5435.2  374.15  5550.7  382.18  5602.6  387.44  5644.1  389.72
#Mann= 5 ,-1 , 0
    4522     .05       0  4957.2     .16       0  4993.1     .07       0
  4999.1     .16       0  5150.2     .05       0
Bank Sta=4957.2,5024
XS Rating Curve= 0 ,0
Exp/Cntr=0.3,0.1

Type RM Length L Ch R = 1 ,55342   ,394,394,394
BEGIN DESCRIPTION:
WHEELOCK CREEK 100.0
END DESCRIPTION:
XS GIS Cut Line= 2
      3653011.33       10496869.      3652491.45     10496123.83
#Sta/Elev= 30
  4497.1  371.55  4547.2  370.09    4562  370.72  4605.4  368.73  4690.7  364.08
  4770.5  357.94  4909.4  351.87  4934.6   349.9  4964.2  350.51    4979  348.47
  4985.1  345.66  4990.8  337.99  4993.6  337.49  4996.8  337.99  5007.8  342.95
  5020.9  350.87  5065.4  350.93  5102.6  352.84  5172.7  358.12  5187.5  360.29
  5223.3  363.54  5238.1  365.95  5251.6     367    5259  368.67  5294.8  372.03
  5345.4  375.87  5366.3  376.26    5396  379.17  5402.1  378.46  5405.7  379.65
#Mann= 5 ,-1 , 0
  4497.1     .05       0  4909.4     .16       0  4990.8     .07       0
  4996.8     .16       0  5102.6     .05       0
Bank Sta=4964.2,5020.9
XS Rating Curve= 0 ,0
Exp/Cntr=0.3,0.1

Type RM Length L Ch R = 1 ,54948   ,358,358,358
BEGIN DESCRIPTION:
WHEELOCK CREEK 99.0
END DESCRIPTION:
XS GIS Cut Line= 3
      3653400.07     10496788.03      3652795.89      10495975.5
      3652664.29     10495885.46
#Sta/Elev= 30
  4284.2  375.16    4326  371.42  4361.5  372.21  4540.9  364.72  4655.4  361.27
  4711.9  356.65  4732.7  356.73  4759.3  354.21  4782.8  353.68    4812  350.17
  4847.5  348.62  4954.4  349.01  4976.8  350.01    4983  348.22  4991.4   339.3
  5001.3   336.8    5004   336.3  5007.3   336.8  5012.2  345.53  5018.5   348.6
  5047.7   350.4  5068.5  348.94  5117.4   351.6  5147.8  355.42  5154.1  355.16
  5254.2  367.85  5333.7  383.46  5354.6  386.62  5399.4  389.94  5456.2  390.59
#Mann= 5 ,-1 , 0
  4284.2     .05       0  4759.3     .16       0  5001.3     .07       0
  5007.3     .16       0  5117.4     .05       0
Bank Sta=4983,5018.5
XS Rating Curve= 0 ,0
Exp/Cntr=0.3,0.1

Type RM Length L Ch R = 1 ,54590   ,548,548,548
BEGIN DESCRIPTION:
WHEELOCK CREEK 98.0
END DESCRIPTION:
XS GIS Cut Line= 4
      3653693.84     10496686.72       3653455.1     10496178.87
      3653164.31     10495931.47      3652899.53     10495809.94
#Sta/Elev= 30
  4188.1  371.52  4302.1  366.75  4444.4  362.82  4586.7  360.32  4632.3  360.83
  4670.5   359.2  4686.4  356.64  4787.6  347.04    4837  347.44  4879.8  345.72
  4922.7  348.34  4972.1  347.78  4979.7  345.94  4986.3     339  4992.9   335.9
  4997.6  335.82  5000.4  335.32  5003.6  335.82  5007.2  340.72  5014.9   342.8
  5021.5  348.25  5029.2  349.33  5071.6  348.13  5091.1  349.17  5172.4   357.2
  5195.4  360.43  5224.3  367.17  5264.4  372.39  5361.8  377.21  5422.4  378.71
#Mann= 5 ,-1 , 0
  4188.1     .05       0  4686.4     .16       0  4997.6     .07       0
  5003.6     .16       0  5091.1     .05       0
Bank Sta=4972.1,5021.5
XS Rating Curve= 0 ,0
Exp/Cntr=0.3,0.1

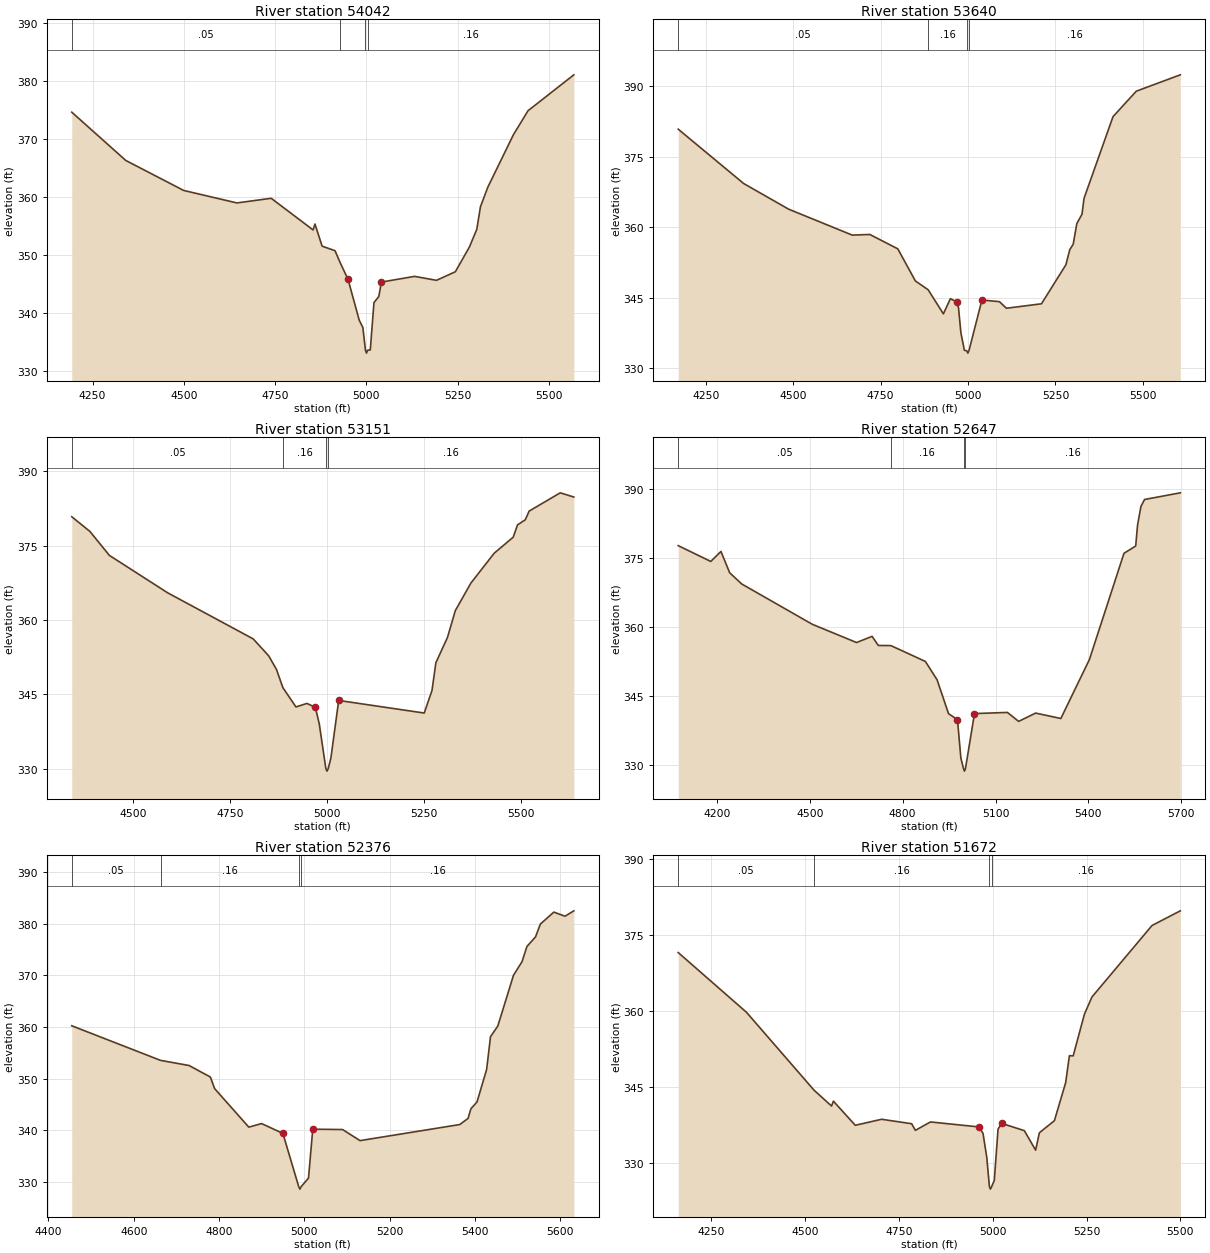
Type RM Length L Ch R = 1 ,54042   ,402,402,402
BEGIN DESCRIPTION:
WHEELOCK CREEK 97.0
END DESCRIPTION:
XS GIS Cut Line= 3
      3653816.72     10496656.07      3653663.94     10495767.17
      3653698.66     10495295.07
#Sta/Elev= 30
    4193  374.62    4341  366.31  4499.5  361.15  4645.4     359  4739.3   359.8
  4854.1  354.35  4859.2  355.37  4878.8  351.56  4914.1  350.78  4928.9  348.63
  4949.8  345.84  4980.3  338.84  4990.4  337.57  4997.5  333.65  5000.3  333.15
  5003.5  333.65  5010.7   333.7  5020.8  341.85    5034  342.89  5041.1  345.38
    5132  346.36  5192.2  345.68  5243.8  347.16  5282.4  351.44  5302.5  354.46
  5312.5  358.35  5332.6   361.7  5402.7  370.73  5442.8  374.87  5568.3  381.05
#Mann= 4 ,-1 , 0
    4193     .05       0  4928.9     .16       0  4997.5     .07       0
  5003.5     .16       0
Bank Sta=4949.8,5041.1
XS Rating Curve= 0 ,0
Exp/Cntr=0.3,0.1

Type RM Length L Ch R = 1 ,53640   ,489,489,489
BEGIN DESCRIPTION:
WHEELOCK CREEK 96.0
END DESCRIPTION:
XS GIS Cut Line= 3
       3654094.5     10496676.89      3654025.05     10495565.78
      3653941.98     10495254.24
#Sta/Elev= 30
  4171.5  380.81  4358.6  369.26  4487.1  363.81  4669.2  358.29  4719.3  358.43
  4799.4  355.37  4849.5  348.56  4886.3  346.66  4929.7  341.55  4949.7  344.77
    4968  344.09    4973  342.82  4979.8   337.5  4989.8  333.81  4996.8   333.7
  4999.6   333.2  5002.8   333.7  5039.9  344.49    5090  344.14    5110  342.74
  5210.2  343.69  5280.1  351.99  5291.1  355.19  5300.9  356.34  5311.3  360.75
    5326  362.72    5332  366.13  5414.8  383.48  5481.3  388.89  5607.2  392.37
#Mann= 4 ,-1 , 0
  4171.5     .05       0  4886.3     .16       0  4996.8     .07       0
  5002.8     .16       0
Bank Sta=4968,5039.9
XS Rating Curve= 0 ,0
Exp/Cntr=0.3,0.1

Type RM Length L Ch R = 1 ,53151   ,504,504,504
BEGIN DESCRIPTION:
WHEELOCK CREEK 95.0
END DESCRIPTION:
XS GIS Cut Line= 2
      3654441.72     10496676.94      3654490.33     10495385.25
#Sta/Elev= 30
  4342.6  380.81  4389.4  377.84  4439.4  373.02  4589.5  365.47  4809.7  356.18
  4849.7  352.76  4869.7  350.01  4886.1  346.35  4919.8  342.46    4948  343.17
  4969.8  342.37  4979.8  339.04  4996.8  330.02  4999.6  329.52  5002.8  330.02
  5009.8   332.2  5029.8  343.77    5250  341.23    5270  345.78    5280  351.37
    5310   356.5    5330  361.87  5370.1  367.43  5430.1  373.45  5479.1  376.69
  5490.2  379.16  5510.2   380.2  5520.2  381.95  5600.2  385.63  5635.2  384.78
#Mann= 4 ,-1 , 0
  4342.6     .05       0  4886.1     .16       0  4996.8     .07       0
  5002.8     .16       0
Bank Sta=4969.8,5029.8
XS Rating Curve= 0 ,0
Exp/Cntr=0.3,0.1

Type RM Length L Ch R = 1 ,52647   ,271,271,271
BEGIN DESCRIPTION:
WHEELOCK CREEK 94.0
END DESCRIPTION:
XS GIS Cut Line= 4
      3654906.99     10496781.09      3655004.22     10496447.72
      3654962.55     10496065.78      3654594.97     10495254.32
#Sta/Elev= 30
  4074.8  377.73  4179.9  374.29  4212.8  376.47    4241  371.83  4279.7   369.4
  4507.9  360.62  4650.9  356.65  4701.2  357.99  4721.4  356.01    4762  355.98
  4873.4  352.53  4911.2  348.54  4948.2  341.17  4977.1  339.86  4988.1  331.48
  4996.8  329.17  4999.6  328.67  5002.8  329.17    5032  341.19  5138.4  341.44
  5174.7  339.49  5229.6   341.3  5311.1  340.12  5403.4  352.95    5515  376.05
    5553  377.65  5558.9  382.18  5569.9  386.26  5581.6  387.77  5697.1  389.22
#Mann= 4 ,-1 , 0
  4074.8     .05       0    4762     .16       0  4996.8     .07       0
  5002.8     .16       0
Bank Sta=4977.1,5032
XS Rating Curve= 0 ,0
Exp/Cntr=0.3,0.1

Type RM Length L Ch R = 1 ,52376   ,704,704,704
BEGIN DESCRIPTION:
WHEELOCK CREEK 93.0
END DESCRIPTION:
XS GIS Cut Line= 3
      3655130.45     10496335.11      3655113.09      10495675.4
      3654948.19     10495185.02
#Sta/Elev= 30
  4454.7  360.25  4662.8  353.56  4729.7  352.57  4779.7  350.34  4789.7   348.1
  4869.8  340.65  4899.8  341.34  4949.8  339.43  4986.8  329.16  4989.6  328.66
  4992.8  329.16  5009.8  330.79  5019.8  340.25  5089.8  340.18  5130.7  338.04
  5364.5  341.15  5383.9  342.33  5390.7  344.21    5405  345.53  5427.5  351.81
  5436.6  358.15  5453.7   360.2  5490.5  370.02  5510.5  372.65    5522  375.59
  5542.1  377.43  5553.5  379.92  5585.1  382.23  5611.3  381.44    5632  382.48
#Mann= 4 ,-1 , 0
  4454.7     .05       0  4662.8     .16       0  4986.8     .07       0
  4992.8     .16       0
Bank Sta=4949.8,5019.8
XS Rating Curve= 0 ,0
Exp/Cntr=0.3,0.1

Type RM Length L Ch R = 1 ,51672   ,599,599,599
BEGIN DESCRIPTION:
WHEELOCK CREEK 92.0
END DESCRIPTION:
XS GIS Cut Line= 2
      3655659.97     10496621.53       3655707.7     10495284.98
#Sta/Elev= 30
  4162.4  371.54  4343.9  359.75  4524.1  344.32  4570.8  341.18  4575.8  342.14
    4634  337.37  4704.1  338.56  4784.1  337.68  4794.1  336.37  4834.2  338.03
  4964.3  337.04  4974.3  335.75  4984.3  331.02  4991.3  325.24    4994  324.74
  4997.3  325.24  5004.3  326.47  5014.3  336.61  5024.3  337.74  5084.3  336.31
  5114.4  332.45  5124.4  335.89  5164.4  338.28  5194.4   345.8  5204.4  351.14
  5214.4   351.1  5244.4  359.35  5264.4  362.75  5424.5   376.9  5499.8   379.8
#Mann= 4 ,-1 , 0
  4162.4     .05       0  4524.1     .16       0  4991.3     .07       0
  4997.3     .16       0
Bank Sta=4964.3,5024.3
XS Rating Curve= 0 ,0
Exp/Cntr=0.3,0.1

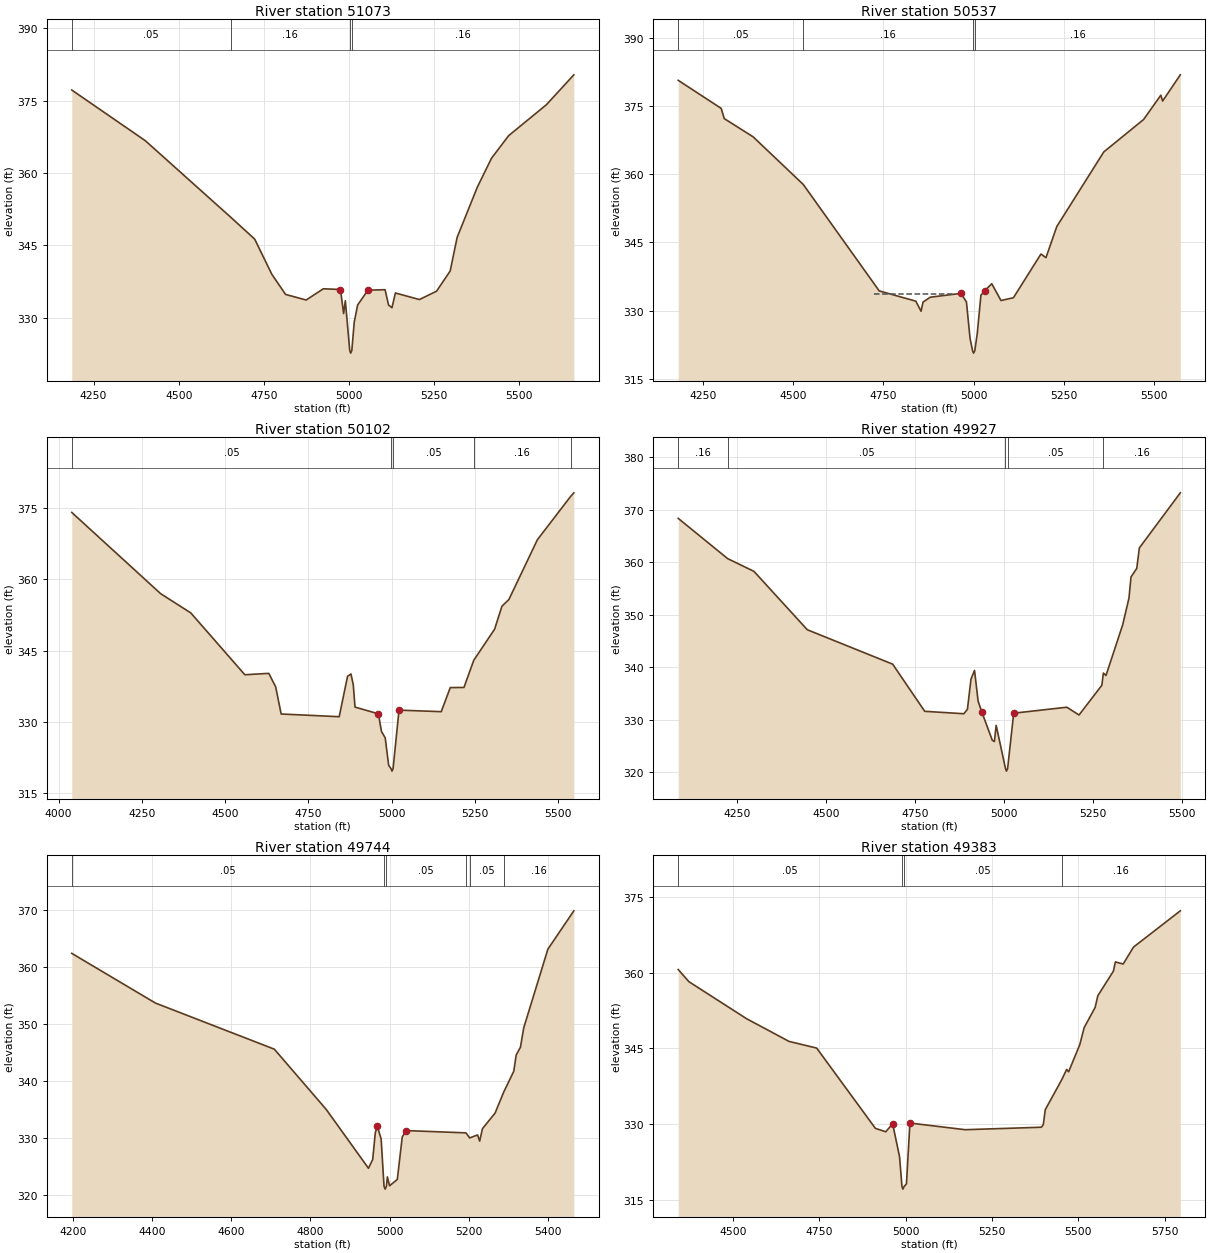
Type RM Length L Ch R = 1 ,51073   ,536,536,536
BEGIN DESCRIPTION:
WHEELOCK CREEK 91.0
END DESCRIPTION:
XS GIS Cut Line= 3
        3656157.     10496725.46      3656115.33     10496232.44
      3656240.33     10495260.22
#Sta/Elev= 30
  4185.8  377.18  4401.8  366.69  4652.2  350.87  4723.2   346.3  4773.6  339.01
  4813.9  334.84  4874.4  333.68  4924.8  336.01  4975.2  335.86  4984.4  330.88
  4989.5  333.53  5002.5  323.18  5005.2  322.68  5008.5  323.18  5015.6  329.08
  5025.6  332.65  5055.9  335.72  5106.3  335.82  5116.4  332.65  5126.5  332.09
  5136.5  335.14  5207.1  333.78  5257.5  335.51  5297.5  339.69    5318  346.67
  5377.1  357.03  5418.9  363.05  5469.3  367.73  5580.2  374.14  5660.8  380.33
#Mann= 4 ,-1 , 0
  4185.8     .05       0  4652.2     .16       0  5002.5     .07       0
  5008.5     .16       0
Bank Sta=4975.2,5055.9
XS Rating Curve= 0 ,0
Exp/Cntr=0.3,0.1

Type RM Length L Ch R = 1 ,50537   ,435,435,435
BEGIN DESCRIPTION:
WHEELOCK CREEK 90.0
END DESCRIPTION:
XS GIS Cut Line= 2
      3656504.22     10496607.47      3656629.22     10495218.58
#Sta/Elev= 30
  4179.9  380.65  4299.2  374.48  4307.7  372.24    4388  368.22  4527.4  357.73
  4738.2  334.34  4839.8  332.09  4854.3  329.88  4859.9  331.89    4880  332.96
  4965.3   333.8  4980.4  331.91  4990.4  323.93  4997.5  321.16  5000.2  320.66
  5003.5  321.16  5010.5  325.01  5020.6   333.4  5030.6  334.33  5050.7  335.92
  5076.3  332.23  5110.9  332.84  5187.3  342.45  5201.3  341.66  5231.4  348.51
  5361.9  364.91  5472.4  372.03  5520.3  377.38  5525.3   376.1  5574.4  381.86
#Mann= 4 ,-1 , 0
  4179.9     .05       0  4527.4     .16       0  4997.5     .07       0
  5003.5     .16       0
#XS Ineff= 2 ,-1
 4724.55 4946.36  333.75 5052.73 5147.27  333.93
Permanent Ineff=
       F       F
Bank Sta=4965.3,5030.6
XS Rating Curve= 0 ,0
Exp/Cntr=0.3,0.1

Type RM Length L Ch R = 1 ,50102   ,175,175,175
BEGIN DESCRIPTION:
WHEELOCK CREEK 89.0
END DESCRIPTION:
XS GIS Cut Line= 4
      3657025.05      10496565.8      3657066.72     10496121.33
      3656886.17     10495357.44      3656677.86     10495176.91
#Sta/Elev= 30
  4039.8  374.07  4306.6  356.99    4397  352.95  4559.3  339.95  4631.2  340.24
  4651.8  337.41  4668.3   331.7  4842.5  331.13  4867.6  339.63  4877.9  340.11
  4884.8   337.8    4890  333.15  4960.1  331.74  4969.4  328.03  4980.6  326.69
  4990.9  320.94  4998.2  320.19  5000.9  319.69  5004.2  320.19    5022  332.51
  5148.8  332.19  5175.9  337.25    5217  337.28  5246.4  342.99    5309  349.53
  5330.9  354.35  5351.8  355.76  5437.3  368.32  5537.5  377.47  5546.8  378.19
#Mann= 5 ,-1 , 0
  4039.8     .05       0  4998.2     .03       0  5004.2     .05       0
  5246.4     .16       0  5537.5     .05       0
#XS Ineff= 1 ,-1
 4632.73 4872.73  338.21
Permanent Ineff=
       F
Bank Sta=4960.1,5022
XS Rating Curve= 0 ,0
Exp/Cntr=0.3,0.1

Type RM Length L Ch R = 1 ,49927   ,183,183,183
BEGIN DESCRIPTION:
Mapping XS a6e2c827
END DESCRIPTION:
XS GIS Cut Line= 3
      3657130.43     10496522.93      3657113.07     10495547.21
      3656939.46     10495147.89
#Sta/Elev= 30
  4084.2  368.33  4223.1  360.67    4297  358.25    4447  347.14    4687  340.59
  4777.1  331.62  4887.1  331.16  4897.1     332  4907.1  337.74  4917.1   339.4
  4927.1  333.57  4937.1  331.57  4967.1   326.1  4972.9  325.87  4977.9  328.95
  5004.1  320.74  5006.8  320.24  5010.1  320.74  5027.1  331.26  5176.5   332.4
  5210.8  330.92  5274.9  336.57  5279.3   338.9  5286.6  338.43  5333.5  348.08
  5351.2  353.16  5356.9  357.18  5373.1  358.81  5380.4  362.71  5495.5  373.19
#Mann= 5 ,-1 , 0
  4084.2     .16       0  4223.1     .05       0  5004.1     .03       0
  5010.1     .05       0  5279.3     .16       0
#XS Ineff= 1 ,-1
 4702.73 4913.64  336.15
Permanent Ineff=
       F
Bank Sta=4937.1,5027.1
XS Rating Curve= 0 ,0
Exp/Cntr=0.3,0.1

Type RM Length L Ch R = 1 ,49744   ,361,361,361
BEGIN DESCRIPTION:
WHEELOCK CREEK 88.0
END DESCRIPTION:
XS GIS Cut Line= 3
      3657337.55     10496371.35      3657323.67     10495746.33
        3657102.     10495143.68
#Sta/Elev= 30
  4197.6  362.38  4408.8  353.66  4708.9  345.57    4840  334.99  4946.5  324.68
  4957.2  326.23  4963.7  330.89    4969  332.01  4978.5  329.82  4985.8  321.52
  4988.6  321.02  4991.8  321.52  4994.2  323.17  4999.8  321.61  5019.3  322.72
  5031.8  330.19  5042.4  331.29  5192.7  330.89  5201.9     330  5221.9  330.53
  5227.2  329.44  5234.2  331.62  5266.2  334.37  5287.9  338.05  5313.3   341.7
  5319.4  344.55  5330.1  345.91  5338.4  349.31  5399.4  363.12  5464.9  369.84
#Mann= 6 ,-1 , 0
  4197.6     .05       0  4985.8     .03       0  4991.8     .05       0
  5192.7     .08       0  5201.9     .05       0  5287.9     .16       0
Bank Sta=4969,5042.4
XS Rating Curve= 0 ,0
Exp/Cntr=0.3,0.1

Type RM Length L Ch R = 1 ,49383   ,549,549,549
BEGIN DESCRIPTION:
WHEELOCK CREEK 87.0
END DESCRIPTION:
XS GIS Cut Line= 3
      3657587.55     10496281.04      3657573.67     10495336.61
      3657351.44     10494878.27
#Sta/Elev= 30
  4341.8  360.59  4372.7  358.19  4539.9  350.86  4662.7  346.38  4742.7  345.06
  4912.7  329.19  4942.7  328.51  4962.7  330.09  4982.7  323.57  4989.7  317.67
  4992.5  317.17  4995.7  317.67  5002.7  318.23  5012.7  330.24  5172.7  328.92
  5393.4  329.41  5398.9  329.91  5404.6  332.87  5451.9  338.75  5466.6  340.84
  5472.2  340.37  5504.6  345.74  5517.3  349.11  5549.1   353.1  5556.9  355.42
  5602.1  360.29  5607.6   362.1  5630.2  361.68  5660.2  365.03  5795.7   372.2
#Mann= 4 ,-1 , 0
  4341.8     .05       0  4989.7     .03       0  4995.7     .05       0
  5451.9     .16       0
Bank Sta=4962.7,5012.7
XS Rating Curve= 0 ,0
Exp/Cntr=0.3,0.1

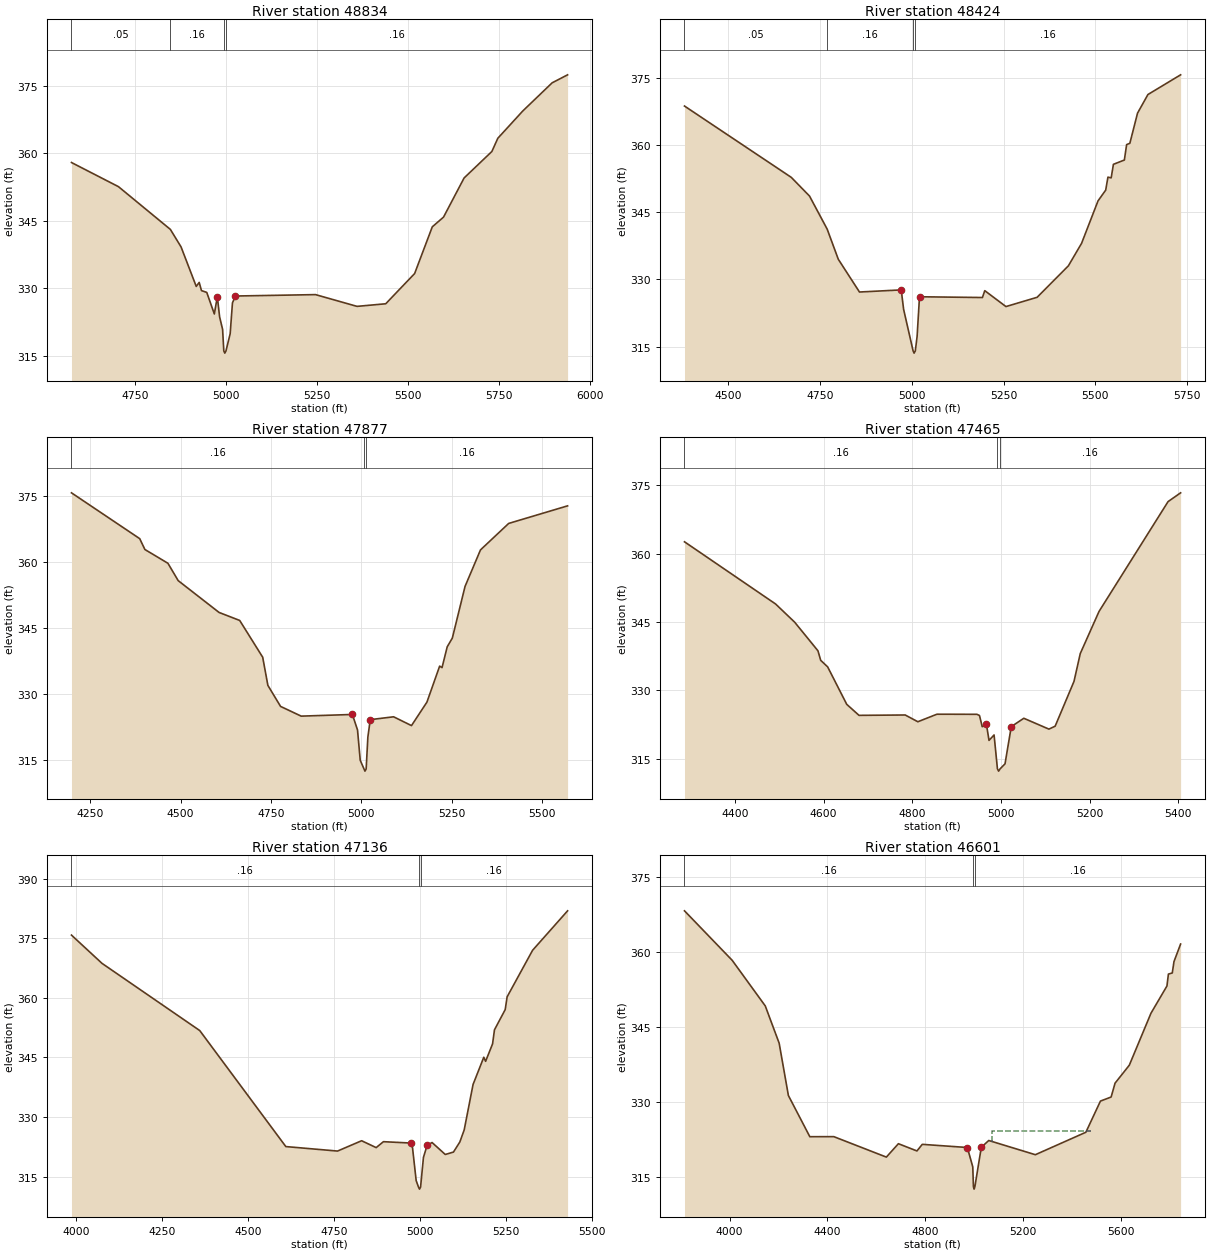
Type RM Length L Ch R = 1 ,48834   ,410,410,410
BEGIN DESCRIPTION:
WHEELOCK CREEK 86.0
END DESCRIPTION:
XS GIS Cut Line= 3
      3657656.97       10496229.      3658221.24     10495499.81
      3658368.46     10495084.13
#Sta/Elev= 30
  4576.2  357.91  4705.3  352.55  4847.9  343.06  4877.3  339.17    4919   330.4
  4927.1  331.29  4933.4  329.47  4947.9  329.07  4968.7  324.28  4976.9  328.13
  4983.2  323.64  4991.4  320.86  4994.7  316.09  4997.5  315.59  5000.7  316.09
  5012.2   319.9  5018.5  326.75  5026.7  328.27  5246.7  328.58  5360.8  325.97
  5439.6  326.55    5519  333.26  5567.5  343.63  5598.4  345.79  5654.9  354.48
  5731.2  360.36  5747.5  363.29  5816.1  369.35  5896.7   375.6  5939.2  377.38
#Mann= 4 ,-1 , 0
  4576.2     .05       0  4847.9     .16       0  4994.7     .07       0
  5000.7     .16       0
Bank Sta=4976.9,5026.7
XS Rating Curve= 0 ,0
Exp/Cntr=0.3,0.1

Type RM Length L Ch R = 1 ,48424   ,547,547,547
BEGIN DESCRIPTION:
WHEELOCK CREEK 85.0
END DESCRIPTION:
XS GIS Cut Line= 3
      3657735.14     10496454.65      3658525.05     10495820.99
      3658802.86     10495629.99
#Sta/Elev= 30
    4382  368.71  4672.5  352.78  4722.1  348.61  4770.2  341.22  4800.5  334.48
  4858.1  327.17  4971.7  327.64  4978.2  323.29    5004  314.02  5006.7  313.52
    5010  314.02  5014.9  317.26  5021.4  326.11  5192.6  325.94    5199  327.47
  5256.6  323.92  5341.4  325.99  5426.5  333.02  5462.4  338.05  5507.1  347.52
    5528  349.93  5534.1  352.82  5542.9  352.67    5549  355.69  5578.8  356.65
  5584.9  360.09  5593.7  360.39  5614.6  367.12  5642.9  371.28  5731.8  375.68
#Mann= 4 ,-1 , 0
    4382     .05       0  4770.2     .16       0    5004     .07       0
    5010     .16       0
Bank Sta=4971.7,5021.4
XS Rating Curve= 0 ,0
Exp/Cntr=0.3,0.1

Type RM Length L Ch R = 1 ,47877   ,412,412,412
BEGIN DESCRIPTION:
WHEELOCK CREEK 84.0
END DESCRIPTION:
XS GIS Cut Line= 2
      3657943.46     10496880.01      3658984.85     10495986.15
#Sta/Elev= 30
  4198.2  375.76    4387  365.35  4401.3  362.89    4465  359.76  4493.5  355.81
  4606.5  348.59  4663.6  346.77  4727.2  338.42  4741.5  332.03  4776.6  327.25
  4833.7  325.04  4975.3  325.42  4989.5   321.9    4997  315.02  5007.4  313.05
  5010.1  312.55  5013.4  313.05  5018.1  320.26  5024.7  324.24  5089.3  324.89
  5138.8  322.89  5181.5  328.22  5216.7   336.4  5223.3  336.06  5237.6  340.78
  5251.8  342.77  5286.9  354.49  5329.7   362.8  5407.7  368.81  5570.6   372.8
#Mann= 3 ,-1 , 0
  4198.2     .16       0  5007.4     .07       0  5013.4     .16       0
Bank Sta=4975.3,5024.7
XS Rating Curve= 0 ,0
Exp/Cntr=0.3,0.1

Type RM Length L Ch R = 1 ,47465   ,329,329,329
BEGIN DESCRIPTION:
WHEELOCK CREEK 83.0
END DESCRIPTION:
XS GIS Cut Line= 3
      3658249.61     10496910.19      3658849.61     10496560.19
      3659149.62     10496260.18
#Sta/Elev= 30
  4286.2  362.57  4491.7  348.93  4534.7  344.94  4587.2  338.67  4593.4  336.58
  4609.1  335.14  4652.1  326.93  4679.8  324.51    4784  324.59  4812.5  323.11
  4855.5  324.76  4945.7  324.74  4951.5  324.48  4957.7  322.02  4967.2  322.52
    4973  319.02  4984.4  320.21    4992  312.78  4994.7  312.28    4998  312.78
  5009.1  313.88  5023.2  322.04  5051.5  323.87  5108.1  321.49  5122.2  322.14
  5164.7  331.97  5178.8  338.06  5221.2  347.31  5376.8  371.38  5405.1  373.31
#Mann= 3 ,-1 , 0
  4286.2     .16       0    4992     .07       0    4998     .16       0
Bank Sta=4967.2,5023.2
XS Rating Curve= 0 ,0
Exp/Cntr=0.3,0.1

Type RM Length L Ch R = 1 ,47136   ,535,535,535
BEGIN DESCRIPTION:
WHEELOCK CREEK 82.0
END DESCRIPTION:
XS GIS Cut Line= 3
      3658611.86     10497418.21      3659011.17     10497088.35
      3659314.16     10496213.99
#Sta/Elev= 30
  3986.4  375.78  4075.2  368.67  4359.6  351.75    4610  322.55  4760.4  321.42
  4830.5  324.02  4872.8  322.29    4894  323.78  4973.1  323.44  4978.6  322.25
  4989.2  313.99    4996  312.34  4998.8  311.84    5002  312.34  5010.4  319.85
    5021  322.83  5035.4  323.57  5073.9  320.56  5097.7  321.17  5116.2   323.7
  5128.9  326.74  5154.7  338.18  5185.9  345.03  5191.2  344.01  5211.5  348.41
    5217  351.94  5248.2  357.02  5253.8  360.24  5327.9  371.96  5429.7  381.89
#Mann= 3 ,-1 , 0
  3986.4     .16       0    4996     .07       0    5002     .16       0
Bank Sta=4973.1,5021
XS Rating Curve= 0 ,0
Exp/Cntr=0.3,0.1

Type RM Length L Ch R = 1 ,46601   ,535,535,535
BEGIN DESCRIPTION:
WHEELOCK CREEK 81.0
END DESCRIPTION:
XS GIS Cut Line= 3
      3658828.91     10497435.55      3659393.11     10497131.75
      3660061.54     10495916.43
#Sta/Elev= 30
  3815.6  368.26  4010.7  358.36  4145.8  349.25  4202.5  341.81  4240.3  331.34
  4327.9  323.11    4426  323.12  4640.7  319.03  4689.9  321.71  4765.7  320.26
  4787.5  321.58  4971.7  320.95  4993.9  317.08  4996.6  313.13  4999.4  312.63
  5002.6  313.13  5028.8     321  5059.3  322.35  5249.7  319.51  5456.2     324
  5515.8  330.23  5559.4  331.04  5575.5  333.81  5633.7   337.4  5722.3  347.79
  5787.6  353.24  5793.5  355.61  5809.4  355.84  5816.3  358.11  5843.4  361.62
#Mann= 3 ,-1 , 0
  3815.6     .16       0  4996.6     .07       0  5002.6     .16       0
#XS Ineff= 1 ,-1
 5073.86 5477.27  324.34
Permanent Ineff=
       F
Bank Sta=4971.7,5028.8
XS Rating Curve= 0 ,0
Exp/Cntr=0.3,0.1