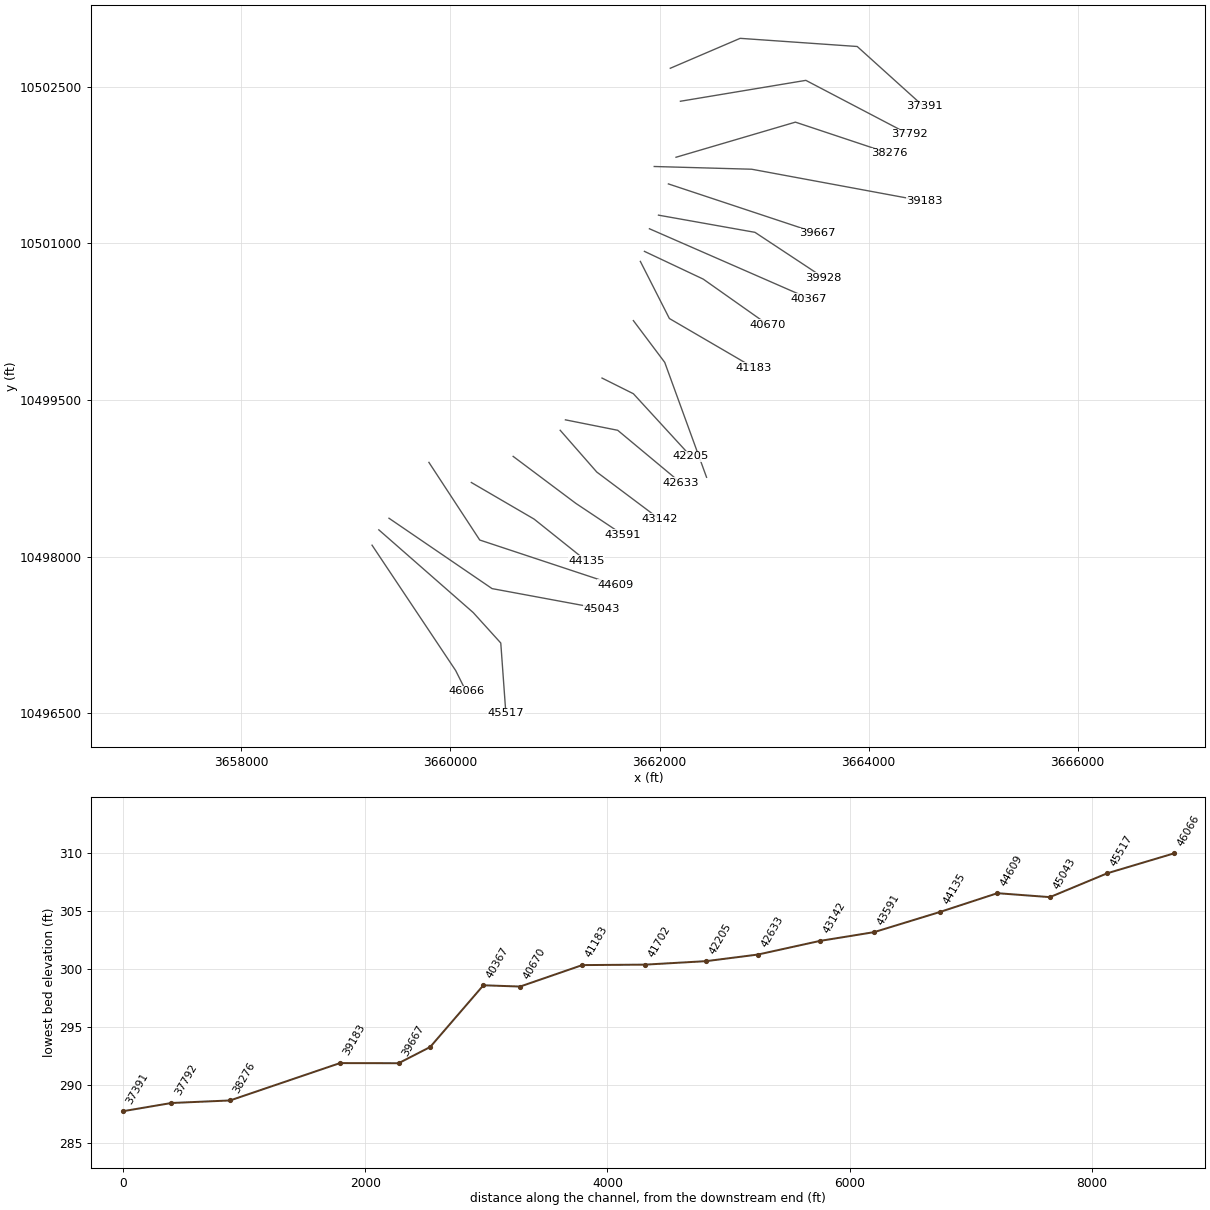
HEC-RAS study WHEELOCK CREEK.prj: WHEELOCK CREEK Base Level Engineering

--- WHEELOCK CREEK.g01 (geometry) --- (continued)

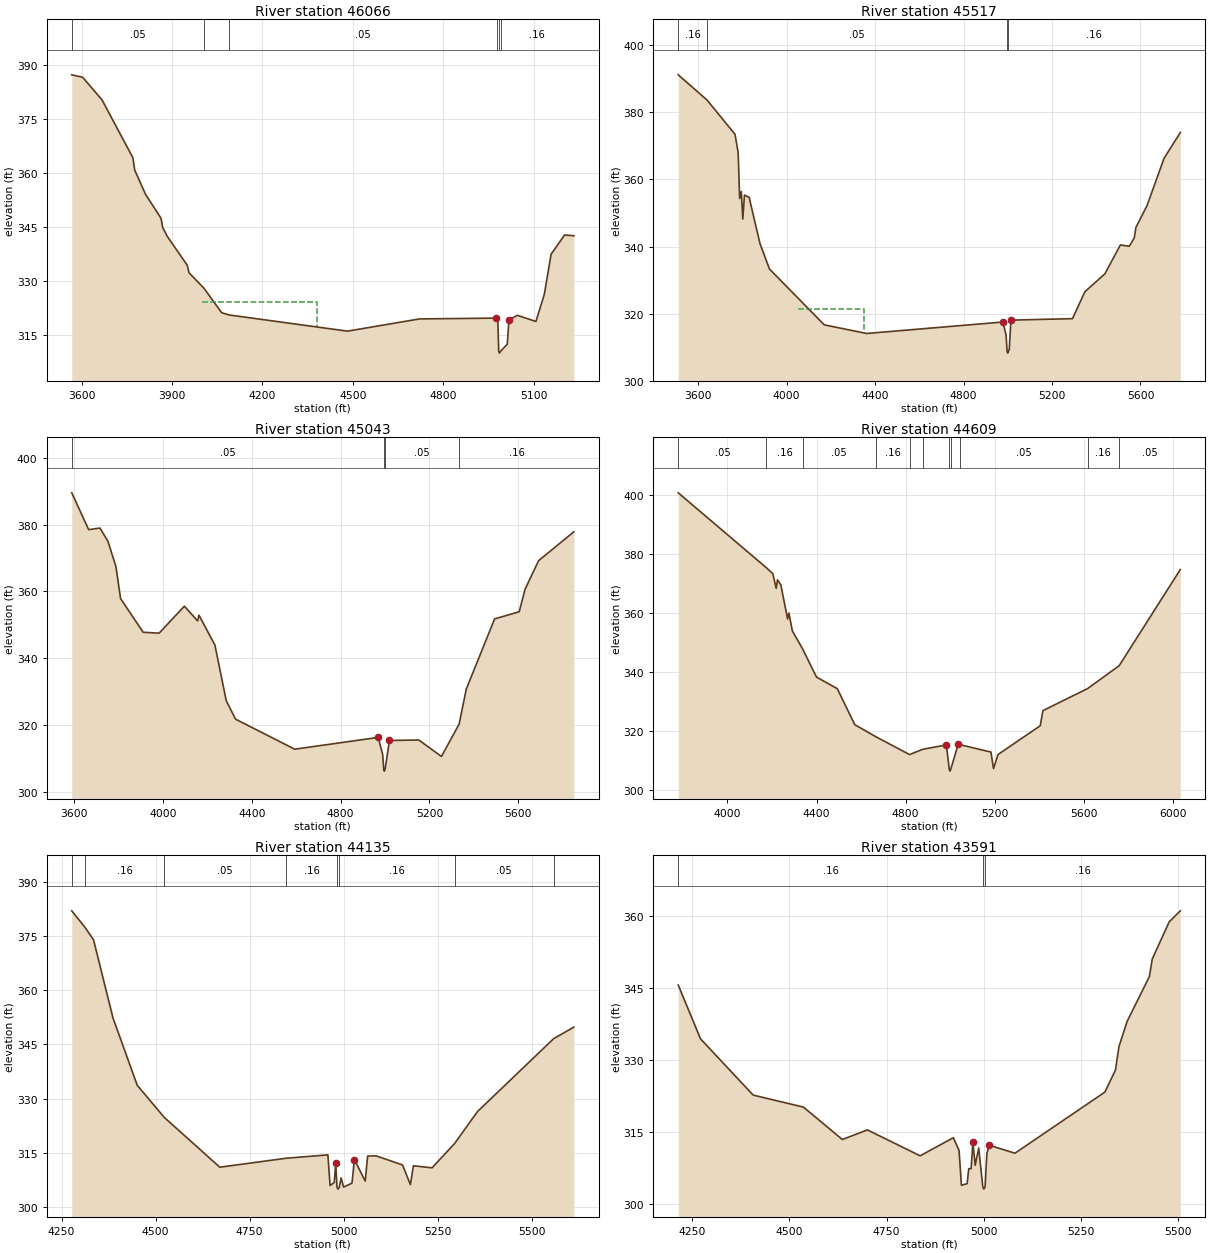
Type RM Length L Ch R = 1 ,46066   ,549,549,549
BEGIN DESCRIPTION:
WHEELOCK CREEK 80.0
END DESCRIPTION:
XS GIS Cut Line= 3
      3659249.59     10498110.22      3660049.61     10496910.19
      3660149.63     10496710.15
#Sta/Elev= 30
  3567.3  387.35  3603.4  386.68    3668  380.34  3770.1   364.3  3776.2  360.85
  3812.2  354.12  3863.3  347.49  3869.3  344.83  3884.3  342.43  3950.4  334.42
  3956.4  332.31  4005.8  328.04  4064.6  321.22  4089.2  320.59  4482.2  316.09
  4721.1  319.49  4973.5  319.71  4976.8  319.36    4981  318.92    4984  310.48
  4986.8  309.98    4990  310.48  5012.3  312.45  5017.9  319.25  5045.9  320.49
  5107.4  318.78  5135.3  326.35  5157.7  337.47  5202.4  342.83  5233.2  342.61
#Mann= 6 ,-1 , 0
  3567.3     .05       0  4005.8     .16       0  4089.2     .05       0
  4976.8     .16       0    4984     .07       0    4990     .16       0
#XS Ineff= 1 ,-1
    4000 4379.55  324.16
Permanent Ineff=
       F
Bank Sta=4973.5,5017.9
XS Rating Curve= 0 ,0
Exp/Cntr=0.3,0.1

Type RM Length L Ch R = 1 ,45517   ,474,474,474
BEGIN DESCRIPTION:
WHEELOCK CREEK 79.0
END DESCRIPTION:
XS GIS Cut Line= 4
      3659314.51     10498256.97      3660217.26     10497465.33
      3660481.15     10497173.66      3660529.76     10496500.03
#Sta/Elev= 30
  3510.6  391.18  3640.5  383.69  3767.3  373.46  3781.5  367.97  3788.2  354.35
  3795.8   356.4  3802.4  348.21    3810  355.34  3830.9  354.71  3880.2   340.9
  3922.9  333.33  4170.6   316.7  4362.3  314.12  4978.4  317.54  4992.6  313.58
  4997.1  308.77  4999.8  308.27  5003.1  308.77  5006.8  309.35  5014.3   318.1
  5292.6  318.54  5348.7  326.56    5439  331.88  5509.1   340.5  5549.2   340.1
  5571.9  342.59  5579.3   345.7  5629.5  352.21  5706.6  366.31    5780  373.99
#Mann= 4 ,-1 , 0
  3510.6     .16       0  3640.5     .05       0  4997.1     .03       0
  5003.1     .16       0
#XS Ineff= 1 ,-1
 4051.14 4348.01  321.53
Permanent Ineff=
       F
Bank Sta=4978.4,5014.3
XS Rating Curve= 0 ,0
Exp/Cntr=0.3,0.1

Type RM Length L Ch R = 1 ,45043   ,434,434,434
BEGIN DESCRIPTION:
WHEELOCK CREEK 78.0
END DESCRIPTION:
XS GIS Cut Line= 3
      3659411.72     10498368.09      3660397.81     10497694.49
      3661445.56     10497500.21
#Sta/Elev= 30
    3590  389.54  3666.1  378.52  3716.9  378.99  3752.8  375.05  3788.7  367.49
  3809.7  357.88  3911.3  347.79  3983.1  347.52  4096.8   355.6  4156.5  351.19
  4162.6   352.9  4234.4  343.94  4285.2  327.32  4327.1  321.78  4593.3  312.78
  4969.1   316.3  4989.4  311.19  4994.1  306.71  4996.9  306.21  5000.1  306.71
  5019.9   315.4  5152.2  315.52  5253.9   310.6  5333.2  320.25  5365.7  330.77
  5493.1  351.79  5603.9  353.93  5630.2  360.66  5691.2  369.23  5849.8  377.87
#Mann= 4 ,-1 , 0
    3590     .05       0  4994.1     .03       0  5000.1     .05       0
  5333.2     .16       0
Bank Sta=4969.1,5019.9
XS Rating Curve= 0 ,0
Exp/Cntr=0.3,0.1

Type RM Length L Ch R = 1 ,44609   ,474,474,474
BEGIN DESCRIPTION:
WHEELOCK CREEK 77.0
END DESCRIPTION:
XS GIS Cut Line= 3
      3659793.64     10498902.84      3660279.76     10498159.77
      3661576.49     10497729.84
#Sta/Elev= 30
    3779  400.87  4174.9  375.47  4203.6  373.46  4218.7  368.52  4224.7  371.39
  4239.8  369.62    4270   358.1    4276  360.16  4291.1  354.11    4338   347.9
  4399.7  338.43  4493.2  334.49  4571.5   322.3  4665.9  318.22  4817.6  312.16
  4877.7  313.97  4982.9  315.43    4996  307.05  4998.7  306.55    5002  307.05
  5035.9  315.69  5041.8  315.55    5183  313.01  5194.4  307.38  5214.6  312.18
  5404.3  321.93  5416.2  327.05  5616.7  334.52  5758.4  342.26  6033.1  374.87
#Mann= 11 ,-1 , 0
    3779     .05       0  4174.9     .16       0    4338     .05       0
  4665.9     .16       0  4817.6     .05       0  4877.7     .16       0
    4996     .07       0    5002     .16       0  5041.8     .05       0
  5616.7     .16       0  5758.4     .05       0
Bank Sta=4982.9,5035.9
XS Rating Curve= 0 ,0
Exp/Cntr=0.3,0.1

Type RM Length L Ch R = 1 ,44135   ,544,544,544
BEGIN DESCRIPTION:
WHEELOCK CREEK 76.0
END DESCRIPTION:
XS GIS Cut Line= 3
      3660199.59      10498710.2      3660799.61     10498360.19
      3661299.64     10497960.16
#Sta/Elev= 30
  4277.1  381.97  4312.5  377.36    4335  373.94  4386.7  352.31  4451.2  333.68
  4522.7  324.82  4670.7     311  4847.9  313.49  4958.1  314.41  4963.9  305.94
    4975  306.76    4979  312.06  4982.4  305.43  4985.1  304.93  4988.4  305.43
  4993.4  308.03  4999.8  305.49  5022.2  306.59  5028.6  313.13  5057.4  307.15
  5063.8  314.09  5086.2  314.15  5156.6  311.62  5177.5  306.18  5185.5  311.39
  5235.1  310.83  5294.9  317.54  5355.9   326.4  5558.4  346.58  5612.1  349.78
#Mann= 8 ,-1 , 0
  4277.1     .05       0  4312.5     .16       0  4522.7     .05       0
  4847.9     .16       0  4982.4     .07       0  4988.4     .16       0
  5294.9     .05       0  5558.4     .16       0
Bank Sta=4979,5028.6
XS Rating Curve= 0 ,0
Exp/Cntr=0.3,0.1

Type RM Length L Ch R = 1 ,43591   ,449,449,449
BEGIN DESCRIPTION:
WHEELOCK CREEK 75.0
END DESCRIPTION:
XS GIS Cut Line= 3
      3660599.63     10498960.17      3661199.61     10498510.19
       3661649.6     10498210.19
#Sta/Elev= 30
  4214.1  345.59  4271.4  334.41  4406.8  322.72    4536  320.23    4636   313.5
  4700.5  315.49    4836  310.11  4921.4  313.87    4936  311.25  4942.2  303.99
  4956.8  304.33    4961  307.44  4967.1  307.44  4971.6  312.88  4977.6  308.15
  4986.6  311.74  4997.1  303.69  4999.9  303.19  5003.1  303.69  5007.6  310.61
  5013.7  312.31  5079.8  310.65  5311.1  323.35  5338.2  327.94  5347.2  332.82
  5368.2  338.04  5425.3  347.32  5432.8  350.99  5476.4  358.72  5504.9     361
#Mann= 3 ,-1 , 0
  4214.1     .16       0  4997.1     .07       0  5003.1     .16       0
Bank Sta=4971.6,5013.7
XS Rating Curve= 0 ,0
Exp/Cntr=0.3,0.1

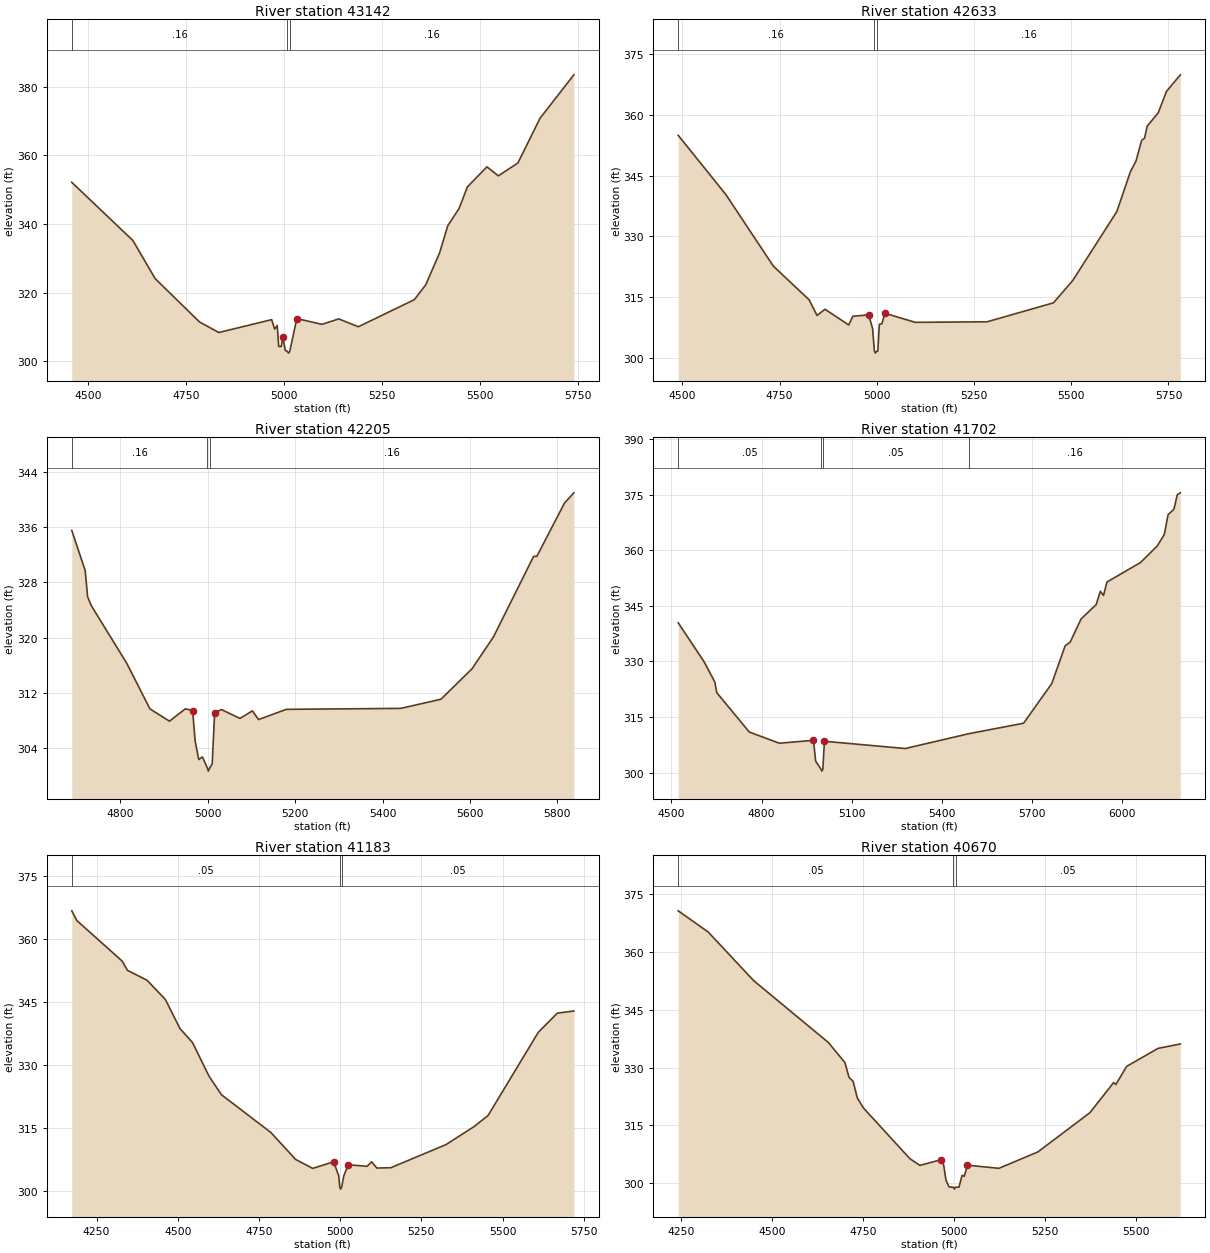
Type RM Length L Ch R = 1 ,43142   ,509,509,509
BEGIN DESCRIPTION:
WHEELOCK CREEK 74.0
END DESCRIPTION:
XS GIS Cut Line= 3
      3661049.58     10499210.22      3661399.61     10498810.19
      3661999.57     10498360.22
#Sta/Elev= 30
  4458.2  352.15  4614.4  335.19  4670.8  324.15  4784.3   311.5  4833.6  308.43
  4968.4  312.18    4976  309.44  4982.6  310.46  4986.4  304.38  4992.9  304.38
    4997  307.04  5003.3  303.19  5008.6  302.93  5011.4  302.43  5014.6  302.93
  5032.5  312.48    5097  310.81  5139.7  312.39  5189.7  310.11  5332.5  317.98
  5361.6  322.29    5397  331.59  5417.9  339.51    5447  344.58  5467.9   350.8
  5517.9  356.66    5547  354.03    5597  357.78  5653.3  370.77  5739.7  383.43
#Mann= 3 ,-1 , 0
  4458.2     .16       0  5008.6     .07       0  5014.6     .16       0
Bank Sta=4997,5032.5
XS Rating Curve= 0 ,0
Exp/Cntr=0.3,0.1

Type RM Length L Ch R = 1 ,42633   ,428,428,428
BEGIN DESCRIPTION:
WHEELOCK CREEK 73.0
END DESCRIPTION:
XS GIS Cut Line= 3
      3661099.62     10499310.19      3661599.61     10499210.19
      3662199.59      10498710.2
#Sta/Elev= 30
  4489.6   354.9    4612  340.33  4734.3  322.67  4826.1   314.4  4846.5  310.53
  4866.9  312.07  4928.1   308.2  4938.3  310.34  4979.1  310.68  4989.3  307.36
  4993.9  301.76  4996.7  301.26  4999.9  301.76  5002.7  301.76  5006.7  308.37
  5013.2   308.5    5021  311.09  5099.1  308.84  5283.9  308.98  5454.4  313.65
  5503.9  319.15  5617.2  336.11  5652.3  345.97  5666.6  348.58  5680.9  353.62
  5688.7  354.24  5695.3  357.15  5723.9   360.5  5744.7  365.69  5780.5  369.81
#Mann= 3 ,-1 , 0
  4489.6     .16       0  4993.9     .07       0  4999.9     .16       0
Bank Sta=4979.1,5021
XS Rating Curve= 0 ,0
Exp/Cntr=0.3,0.1

Type RM Length L Ch R = 1 ,42205   ,503,503,503
BEGIN DESCRIPTION:
WHEELOCK CREEK 72.0
END DESCRIPTION:
XS GIS Cut Line= 3
      3661449.61     10499710.19      3661749.61     10499560.19
      3662299.58     10498960.22
#Sta/Elev= 30
  4688.6  335.53  4719.3  329.72  4724.9  325.91  4733.3  324.64  4814.4   316.3
  4867.5   309.7  4912.2  307.92  4948.5   309.7  4965.3  309.46  4970.9  305.11
  4979.3  302.36  4987.7  302.75  4998.6  301.19  5001.4  300.69  5004.6  301.19
    5010  301.72  5015.6  309.11  5031.1   309.6  5073.6  308.32    5102  309.41
  5116.2  308.15  5179.7  309.63  5441.8  309.77  5533.6  311.09  5604.6  315.48
  5653.9  320.11  5745.8  331.76  5753.2  331.77  5816.7   339.5  5837.9  340.96
#Mann= 3 ,-1 , 0
  4688.6     .16       0  4998.6     .07       0  5004.6     .16       0
Bank Sta=4965.3,5015.6
XS Rating Curve= 0 ,0
Exp/Cntr=0.3,0.1

Type RM Length L Ch R = 1 ,41702   ,519,519,519
BEGIN DESCRIPTION:
WHEELOCK CREEK 71.0
END DESCRIPTION:
XS GIS Cut Line= 3
      3661749.62     10500260.17      3662049.61     10499860.19
      3662449.63     10498760.14
#Sta/Elev= 30
  4522.7  340.42  4609.1  329.86  4644.6  324.42  4650.8  321.58  4759.1  310.94
  4859.1  307.92  4972.7  308.71    4980  303.08  4997.8  300.89  5000.6  300.39
  5003.8  300.89  5009.1  308.45  5278.1  306.49    5490   310.5  5671.8  313.32
  5765.5  324.02  5810.1  334.21  5826.7  335.19  5863.3   341.5  5913.2  345.32
  5927.1  348.91  5937.8  347.81  5949.1  351.42  6060.8  356.69  6116.7  361.18
  6139.9  364.26  6152.6  369.63  6171.9  371.06  6183.2  375.02  6193.2   375.5
#Mann= 4 ,-1 , 0
  4522.7     .05       0  4997.8     .03       0  5003.8     .05       0
    5490     .16       0
Bank Sta=4972.7,5009.1
XS Rating Curve= 0 ,0
Exp/Cntr=0.3,0.1

Type RM Length L Ch R = 1 ,41183   ,513,513,513
BEGIN DESCRIPTION:
WHEELOCK CREEK 70.0
END DESCRIPTION:
XS GIS Cut Line= 3
      3661816.31     10500827.02      3662094.06     10500280.19
      3662899.64     10499810.17
#Sta/Elev= 30
  4173.5  366.63  4189.3   364.3  4328.4  354.68  4345.1  352.45  4405.5  350.09
    4462  345.48  4506.5  338.61  4545.4  335.25  4596.2  327.24  4634.4  322.83
  4786.8  313.83  4862.7  307.43  4915.3  305.29  4979.8  306.86  4995.5  303.54
  4998.6  300.85  5001.4  300.35  5004.6  300.85  5011.2  303.52  5024.8  306.16
  5082.7  305.78  5097.2  306.85  5112.9  305.37  5155.9  305.45  5325.8  310.95
  5412.3  315.25  5455.3  317.87  5609.9  337.68  5668.6  342.26  5719.5  342.78
#Mann= 3 ,-1 , 0
  4173.5     .05       0  4998.6     .03       0  5004.6     .05       0
Bank Sta=4979.8,5024.8
XS Rating Curve= 0 ,0
Exp/Cntr=0.3,0.1

Type RM Length L Ch R = 1 ,40670   ,303,303,303
BEGIN DESCRIPTION:
WHEELOCK CREEK 69.0
END DESCRIPTION:
XS GIS Cut Line= 3
      3661855.41     10500922.99      3662417.95     10500657.34
      3663036.14     10500220.97
#Sta/Elev= 30
  4242.2  370.65  4324.3  365.17  4449.6  352.53  4654.5  336.52  4700.1  331.29
  4711.3  327.46  4722.4  326.47  4733.9  322.17  4751.1  319.51  4878.6  306.37
    4906  304.66  4964.3  306.13  4971.2  304.74  4977.4  300.87    4986  299.04
  4997.8     299  5000.6   298.5  5003.8     299  5013.2  299.01  5021.7   302.1
  5027.8  301.83  5036.5  304.71  5122.7  303.89  5229.8  308.14  5372.6   318.3
  5437.9  326.13    5444  325.62  5473.6  330.32  5559.8  334.99    5621  336.13
#Mann= 3 ,-1 , 0
  4242.2     .05       0  4997.8     .03       0  5003.8     .05       0
Bank Sta=4964.3,5036.5
XS Rating Curve= 0 ,0
Exp/Cntr=0.3,0.1

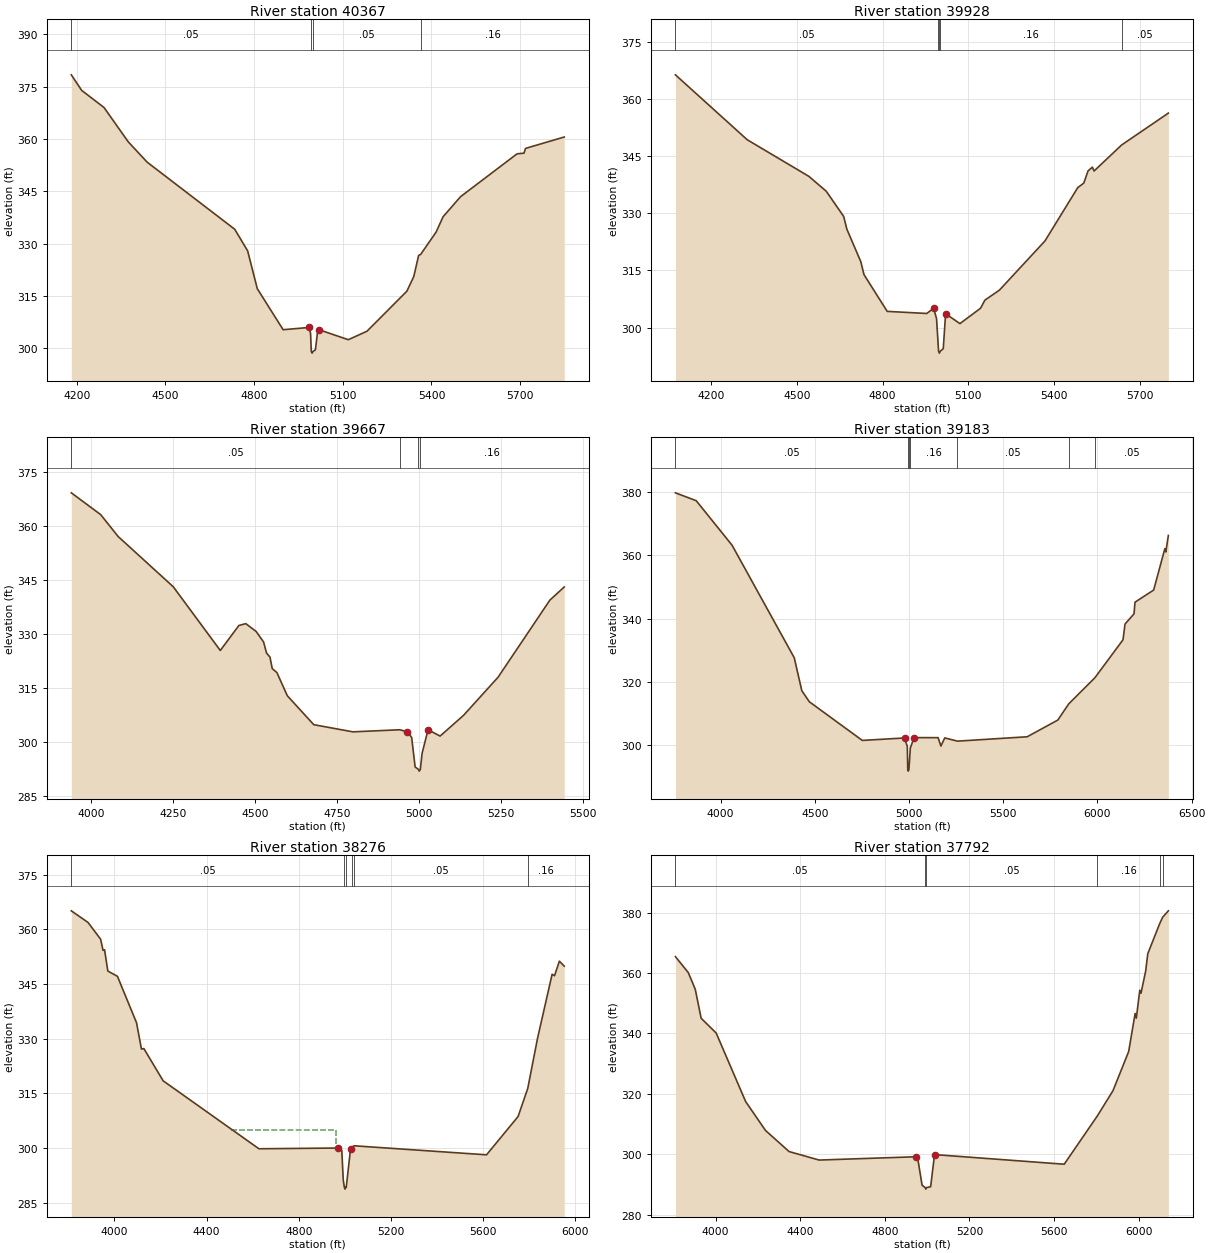
Type RM Length L Ch R = 1 ,40367   ,439,439,439
BEGIN DESCRIPTION:
WHEELOCK CREEK 68.0
END DESCRIPTION:
XS GIS Cut Line= 2
      3661903.13     10501139.55      3663430.92     10500471.14
#Sta/Elev= 30
  4181.7  378.36  4216.8   373.9  4292.4  368.99  4374.3  359.16  4438.2  353.34
  4734.5  334.11  4778.2  327.92  4810.9  317.07  4898.3  305.32  4985.5  305.96
    4991  304.34  4993.5  299.11  4996.2  298.61  4999.5  299.11  5007.4  299.54
  5014.4  304.42  5019.8  305.31  5118.8  302.46    5182  304.89  5316.9  316.36
  5340.3  320.57  5356.7  326.62  5363.3  326.87  5415.9  333.31  5439.3  337.68
  5498.6  343.45  5689.6  355.72  5712.9   355.9  5718.4  357.28  5849.3  360.54
#Mann= 4 ,-1 , 0
  4181.7     .05       0  4993.5     .03       0  4999.5     .05       0
  5363.3     .16       0
Bank Sta=4985.5,5019.8
XS Rating Curve= 0 ,0
Exp/Cntr=0.3,0.1

Type RM Length L Ch R = 1 ,39928   ,261,261,261
BEGIN DESCRIPTION:
WHEELOCK CREEK 67.0
END DESCRIPTION:
XS GIS Cut Line= 3
       3661989.9     10501269.77      3662912.74     10501105.26
       3663569.8     10500670.79
#Sta/Elev= 30
  4074.7  366.35    4326  349.31  4541.7   339.7  4602.6  335.79  4663.5  329.19
  4674.7  325.84  4723.5   317.3  4734.6  313.91  4815.9  304.25  4954.3   303.7
  4978.4  305.07  4988.6  302.33  4994.6  295.11  4995.7  293.79  4998.5  293.29
  5001.7  293.79  5012.1  294.45  5020.3  303.64  5070.4  301.04  5142.7  305.08
  5157.7  307.19  5208.9  309.85    5368  322.74  5482.7  336.73  5503.8  337.92
  5518.9  341.14  5533.9  342.11  5539.9   341.1  5636.1  347.92  5799.8   356.3
#Mann= 5 ,-1 , 0
  4074.7     .05       0  4994.6     .16       0  4995.7     .07       0
  5001.7     .16       0  5636.1     .05       0
Bank Sta=4978.4,5020.3
XS Rating Curve= 0 ,0
Exp/Cntr=0.3,0.1

Type RM Length L Ch R = 1 ,39667   ,484,484,484
BEGIN DESCRIPTION:
WHEELOCK CREEK 66.0
END DESCRIPTION:
XS GIS Cut Line= 2
      3662084.66     10501568.79      3663511.15     10501095.03
#Sta/Elev= 30
  3940.3  369.12  4029.8  363.08  4083.2  356.99  4251.1  343.06  4394.6  325.37
  4451.3  332.31  4472.4  332.82    4504  330.64  4526.6  327.72  4535.6  324.67
  4546.1  323.53    4553  320.34  4567.2  319.24  4598.8  312.83  4679.6  304.78
    4799  302.79  4941.6  303.37  4964.7  302.82  4978.1  301.24  4988.7  293.03
  4998.6  292.39  5001.3  291.89  5004.6  292.39  5009.8  296.77    5028  303.37
  5064.9  301.62  5136.2  307.36  5241.6  317.95  5399.6  339.35  5443.4     343
#Mann= 4 ,-1 , 0
  3940.3     .05       0  4941.6     .16       0  4998.6     .07       0
  5004.6     .16       0
Bank Sta=4964.7,5028
XS Rating Curve= 0 ,0
Exp/Cntr=0.3,0.1

Type RM Length L Ch R = 1 ,39183   ,907,907,907
BEGIN DESCRIPTION:
WHEELOCK CREEK 65.0
END DESCRIPTION:
XS GIS Cut Line= 3
      3661949.17     10501735.47      3662881.49     10501709.42
      3664536.16     10501402.43
#Sta/Elev= 30
  3760.7  379.79  3871.2   377.3  4061.3  363.25  4391.4  327.69  4431.4   317.3
  4471.4   313.8  4752.5   301.6  4976.3  302.37  4991.1  299.73  4993.6   292.4
  4996.3   291.9  4999.6   292.4  5007.3   299.2  5027.1  302.48  5154.7  302.47
  5169.5  299.81  5189.8  302.39  5257.4  301.37  5627.2  302.75  5789.9  308.03
  5847.9  313.15  5986.7   321.4  6135.7  333.38  6146.4  338.35  6194.2  341.57
  6199.3  345.25  6298.4  349.09  6357.8  362.17  6362.9  361.13  6376.3  366.33
#Mann= 7 ,-1 , 0
  3760.7     .05       0  4993.6     .03       0  4999.6     .05       0
  5007.3     .16       0  5257.4     .05       0  5847.9     .16       0
  5986.7     .05       0
Bank Sta=4976.3,5027.1
XS Rating Curve= 0 ,0
Exp/Cntr=0.3,0.1

Type RM Length L Ch R = 1 ,38276   ,484,484,484
BEGIN DESCRIPTION:
WHEELOCK CREEK 64.0
END DESCRIPTION:
XS GIS Cut Line= 3
      3662157.55     10501824.01      3663299.61     10502160.19
      3664199.62     10501860.19
#Sta/Elev= 30
  3813.2   365.1  3885.6  361.92  3940.4  357.31  3950.9  354.25  3957.5  354.39
  3971.7  348.56  4013.4  347.12  4096.1  334.39  4117.6  327.14  4128.1  327.27
  4211.8  318.42  4627.5  299.76  4972.4  299.97    4987  299.34  4993.3  291.24
  4998.1  289.18  5000.9  288.68  5004.1  289.18  5006.3  289.18  5024.8  299.64
  5033.3  300.32  5040.8  300.58  5615.1   298.1  5752.1  308.62    5794  316.33
  5836.4  330.07  5899.7  347.68  5910.2  347.28  5931.3  351.28  5952.4   349.9
#Mann= 6 ,-1 , 0
  3813.2     .05       0  4998.1     .03       0  5004.1     .05       0
  5033.3     .16       0  5040.8     .05       0    5794     .16       0
#XS Ineff= 1 ,-1
 4505.33 4961.96  304.97
Permanent Ineff=
       F
Bank Sta=4972.4,5024.8
XS Rating Curve= 0 ,0
Exp/Cntr=0.3,0.1

Type RM Length L Ch R = 1 ,37792   ,401,401,401
BEGIN DESCRIPTION:
WHEELOCK CREEK 63.0
END DESCRIPTION:
XS GIS Cut Line= 3
      3662199.58     10502360.18      3663399.61     10502560.19
      3664385.66      10502043.3
#Sta/Elev= 30
    3810  365.41  3870.9  360.12  3903.8  354.61  3931.7  345.01  4002.7  340.12
    4142  317.44  4235.8  307.88  4347.3  300.89  4489.3  298.08  4945.5  299.17
  4955.6  298.53  4975.9  289.76  4990.6  288.96  4993.4  288.46  4996.6  288.96
  5016.4  289.26  5034.8  299.89  5647.6   296.7  5803.8  312.63  5878.2  321.03
  5952.4     334  5982.9   346.6  5988.5  345.05  6004.9  354.27  6010.6   353.3
  6032.6  360.57  6042.7  366.37  6098.8  376.29  6112.9  378.43  6139.9  380.56
#Mann= 6 ,-1 , 0
    3810     .05       0  4990.6     .03       0  4996.6     .05       0
  5803.8     .16       0  6098.8      .1       0  6112.9     .05       0
Bank Sta=4945.5,5034.8
XS Rating Curve= 0 ,0
Exp/Cntr=0.3,0.1

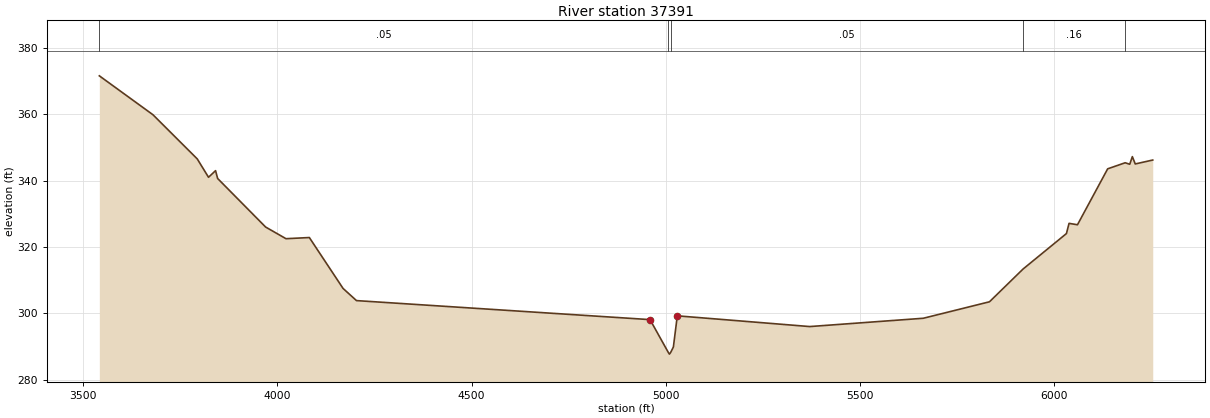
Type RM Length L Ch R = 1 ,37391   ,707,707,707
BEGIN DESCRIPTION:
Mapping XS 9df74a77
END DESCRIPTION:
XS GIS Cut Line= 5
      3662102.78     10502676.04      3662771.15     10502962.48
      3663890.94     10502884.35      3664515.94     10502320.12
       3664533.3     10502311.44
#Sta/Elev= 30
  3542.1  371.56  3680.1  359.84  3794.1  346.54  3823.1  341.01  3841.2     343
  3846.6  340.64    3970  326.03  4022.5  322.51  4082.6  322.86  4169.4  307.53
  4203.9  303.87  4959.4  298.14  5006.5  288.25  5009.3  287.75  5012.5  288.25
  5019.5  289.89  5029.6  299.28  5370.4  296.05  5662.7  298.55    5833  303.51
  5919.5  313.38  6031.1  324.06  6037.8  327.13  6059.5  326.71  6137.2  343.55
  6182.2  345.38    6194  344.93  6200.7  347.23  6208.2  345.02  6253.2   346.2
#Mann= 5 ,-1 , 0
  3542.1     .05       0  5006.5     .03       0  5012.5     .05       0
  5919.5     .16       0  6182.2      .1       0
Bank Sta=4959.4,5029.6
XS Rating Curve= 0 ,0
Exp/Cntr=0.3,0.1