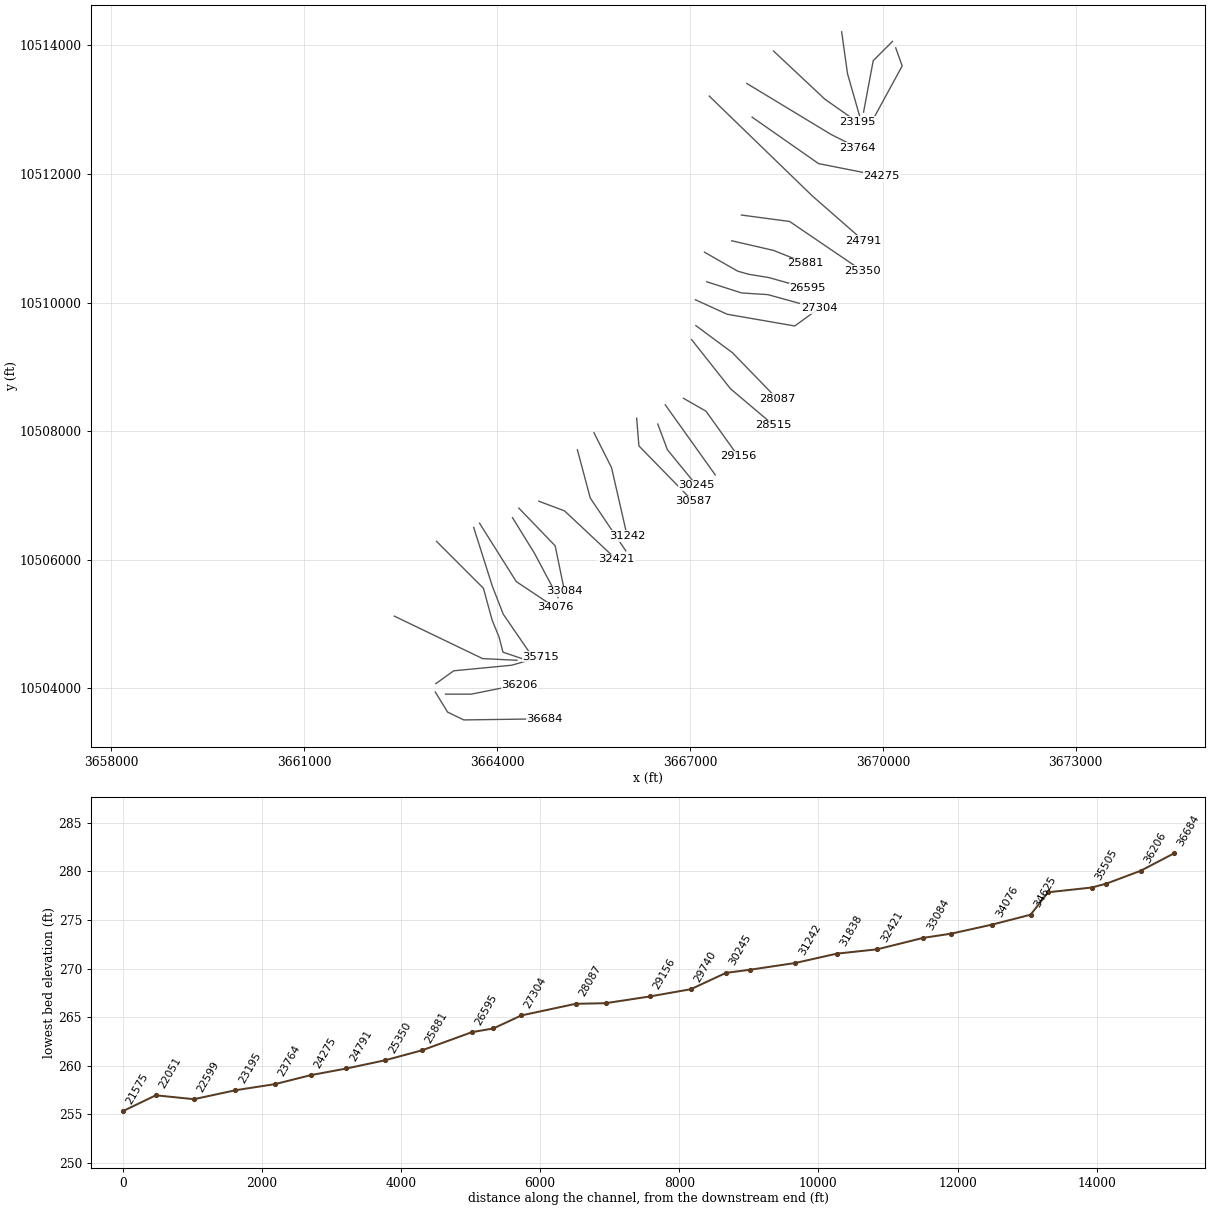
HEC-RAS study WHEELOCK CREEK.prj: WHEELOCK CREEK Base Level Engineering

--- WHEELOCK CREEK.g01 (geometry) --- (continued)

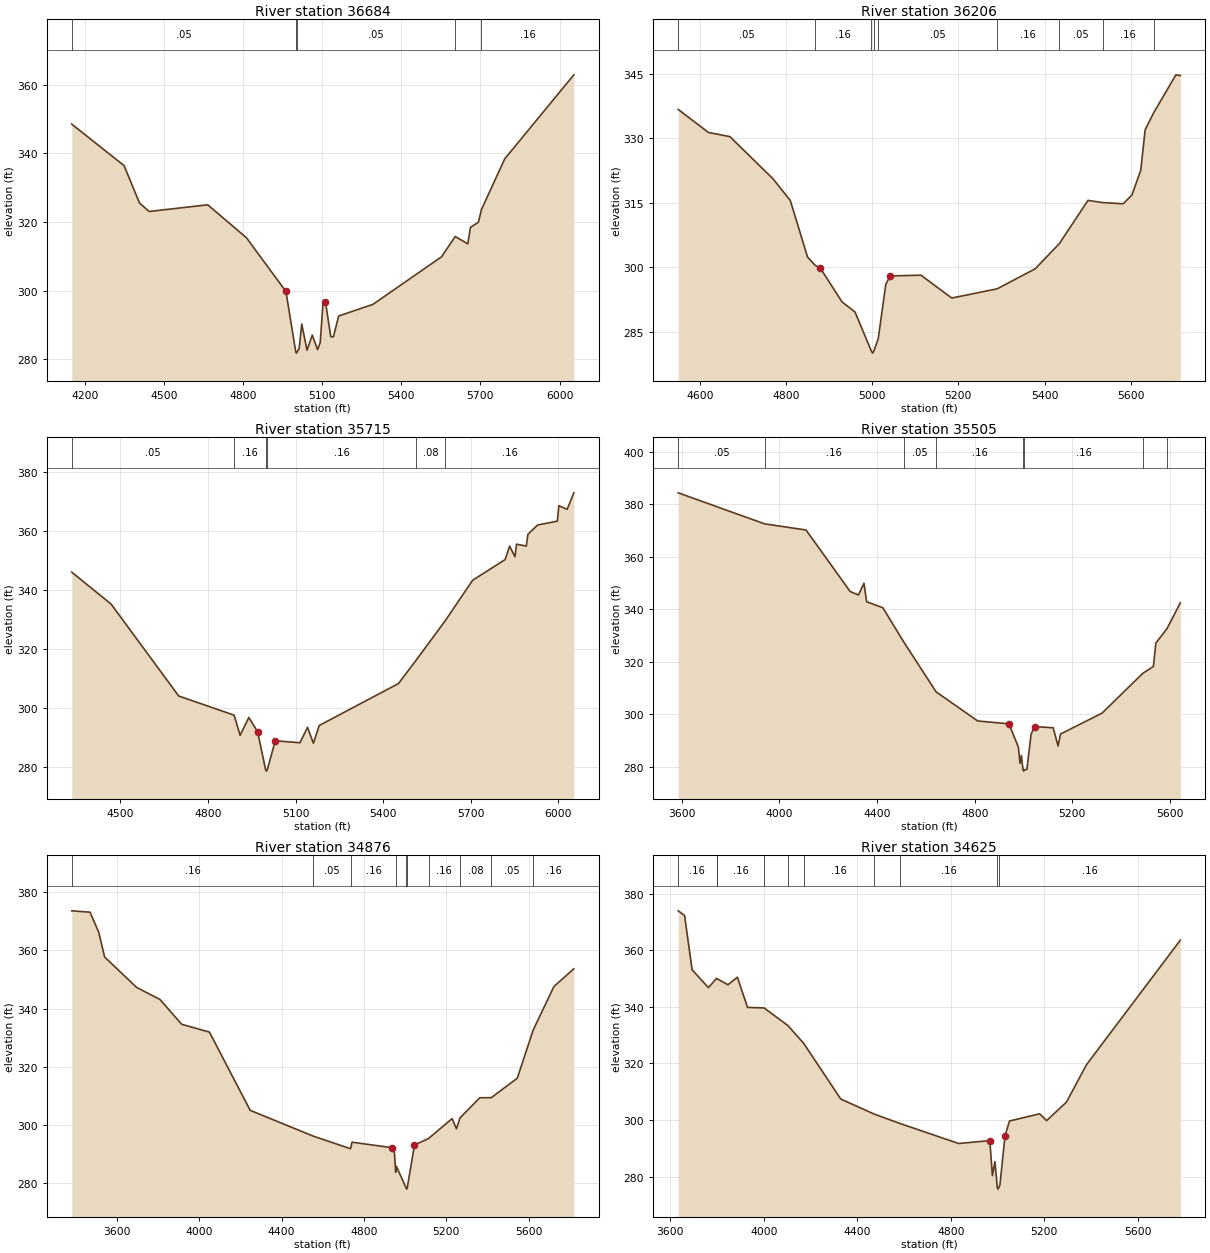
Type RM Length L Ch R = 1 ,36684   ,478,478,478
BEGIN DESCRIPTION:
WHEELOCK CREEK 61.0
END DESCRIPTION:
XS GIS Cut Line= 4
      3663040.25     10503943.38      3663231.22     10503630.88
      3663482.95     10503509.35      3664741.67     10503526.72
#Sta/Elev= 30
  4149.8  348.53  4348.4  336.44  4406.5   325.6  4443.2   323.1  4665.6  325.04
  4812.2  315.47  4962.2  299.82  4999.2  282.35    5002  281.85  5005.2  282.35
  5012.2  283.09  5022.2  290.33  5042.2  282.72  5062.2  287.11  5082.3  282.85
  5092.3  284.92  5102.3  295.95  5112.3  296.73  5132.3  286.65  5142.3  286.59
  5162.3  292.66  5292.3  296.05  5552.3  309.89  5604.5  315.81  5652.3  313.67
  5662.3   318.5  5692.3  319.95    5704  323.66  5792.3  338.43  6054.4  362.89
#Mann= 5 ,-1 , 0
  4149.8     .05       0  4999.2     .03       0  5005.2     .05       0
  5604.5     .08       0    5704     .16       0
Bank Sta=4962.2,5112.3
XS Rating Curve= 0 ,0
Exp/Cntr=0.3,0.1

Type RM Length L Ch R = 1 ,36206   ,491,491,491
BEGIN DESCRIPTION:
WHEELOCK CREEK 60.0
END DESCRIPTION:
XS GIS Cut Line= 3
      3663199.56     10503910.19      3663599.61     10503910.19
      3664349.61     10504060.19
#Sta/Elev= 30
  4550.2  336.66  4620.2  331.32  4670.2  330.34  4770.2  320.53  4810.2  315.52
  4850.2  302.38  4868.1  300.44  4880.2  299.76  4930.2  291.96  4960.4  289.61
  4998.2  280.56    5001  280.06  5004.2  280.56  5014.3  283.45  5031.8  296.05
    5042  297.99  5113.4  298.16  5184.8  292.86  5290.1  294.99  5378.6  299.66
  5434.6  305.52  5500.9  315.53  5534.6  315.03  5582.5  314.75  5602.9   316.8
  5623.3  322.53  5633.5  331.94  5653.4  335.89  5704.9   344.7  5715.1  344.53
#Mann= 9 ,-1 , 0
  4550.2     .05       0  4868.1     .16       0  4998.2     .07       0
  5004.2     .16       0  5014.3     .05       0  5290.1     .16       0
  5434.6     .05       0  5534.6     .16       0  5653.4     .08       0
Bank Sta=4880.2,5042
XS Rating Curve= 0 ,0
Exp/Cntr=0.3,0.1

Type RM Length L Ch R = 1 ,35715   ,210,210,210
BEGIN DESCRIPTION:
WHEELOCK CREEK 59.0
END DESCRIPTION:
XS GIS Cut Line= 4
      3663048.94      10504073.6       3663326.7     10504273.24
      3664229.48     10504360.05      3664680.87     10504490.26
#Sta/Elev= 30
  4333.9  346.05  4468.9  335.22  4700.1  304.15  4889.8  297.67  4910.1  290.85
  4940.1  296.89  4970.2  292.06  4997.4  279.24  5000.1  278.74  5003.4  279.24
  5030.5  289.01  5115.1  288.34    5141  293.57  5161.1  288.18  5181.2  294.18
  5452.4  308.38  5512.9  316.28  5612.7  329.66  5706.2  343.31  5817.6  350.32
  5832.8  354.88  5851.2  351.26  5856.4  355.51  5890.1  354.89  5895.3  358.85
  5928.9  362.01  5996.2   363.3  6001.4  368.55  6029.9  367.31  6052.7  372.89
#Mann= 6 ,-1 , 0
  4333.9     .05       0  4889.8     .16       0  4997.4     .07       0
  5003.4     .16       0  5512.9     .08       0  5612.7     .16       0
Bank Sta=4970.2,5030.5
XS Rating Curve= 0 ,0
Exp/Cntr=0.3,0.1

Type RM Length L Ch R = 1 ,35505   ,629,629,629
BEGIN DESCRIPTION:
Mapping XS 1b36ded2
END DESCRIPTION:
XS GIS Cut Line= 3
      3662404.23     10505122.64      3663775.81      10504462.9
      3664309.68     10504436.85
#Sta/Elev= 30
  3585.7  384.44  3939.1  372.62    4109  370.27  4290.1   346.8    4324   345.5
  4346.5  349.99  4357.3  342.94  4423.9  340.61  4509.4  327.59  4641.9  308.57
  4812.3  297.46  4940.4  296.38  4978.8   287.5  4985.7  281.28  4991.2  284.35
  4997.9  278.84  5000.7  278.34  5003.9  278.84  5013.9  278.99  5030.9   292.4
  5045.3  295.33  5121.5  294.87  5141.5  287.92  5151.6  292.49  5321.8  300.46
  5488.6  315.63    5532  318.25    5542  327.16  5587.8  332.68  5642.2   342.5
#Mann= 8 ,-1 , 0
  3585.7     .05       0  3939.1     .16       0  4509.4     .05       0
  4641.9     .16       0  4997.9     .07       0  5003.9     .16       0
  5488.6     .08       0  5587.8     .16       0
Bank Sta=4940.4,5045.3
XS Rating Curve= 0 ,0
Exp/Cntr=0.3,0.1

Type RM Length L Ch R = 1 ,34876   ,251,251,251
BEGIN DESCRIPTION:
WHEELOCK CREEK 58.0
END DESCRIPTION:
XS GIS Cut Line= 6
      3663059.68     10506285.79      3663788.83     10505556.65
      3663923.38     10505061.86      3664031.88      10504797.1
      3664092.65     10504562.72      3664439.83     10504445.55
#Sta/Elev= 30
  3381.2  373.63    3470  373.16  3512.4  366.21  3540.7  357.75  3696.2  347.27
  3809.4  343.14  3915.4  334.56  4049.8   331.9  4247.8  304.97    4553  296.12
  4735.3  291.76  4742.4  294.01  4937.7   292.1  4948.5  290.28  4954.3  283.65
  4957.7  285.73  5004.7  278.35  5007.5  277.85  5010.7  278.35  5045.8  293.04
  5114.1  295.28  5228.7  302.13  5249.4  298.61  5266.7  302.34    5363   309.3
  5418.9  309.33  5545.2  316.04  5622.3  332.61  5723.2  347.61  5819.8  353.68
#Mann= 10 ,-1 , 0
  3381.2     .16       0    4553     .05       0  4735.3     .16       0
  4957.7     .08       0  5004.7     .07       0  5010.7     .08       0
  5114.1     .16       0  5266.7     .08       0  5418.9     .05       0
  5622.3     .16       0
Bank Sta=4937.7,5045.8
XS Rating Curve= 0 ,0
Exp/Cntr=0.3,0.1

Type RM Length L Ch R = 1 ,34625   ,549,549,549
BEGIN DESCRIPTION:
WHEELOCK CREEK 57.0
END DESCRIPTION:
XS GIS Cut Line= 4
      3663636.93     10506502.79      3663927.72     10505587.03
      3664096.99       10505153.       3664504.8     10504558.64
#Sta/Elev= 30
  3634.2  373.92  3661.4  372.25  3693.6  353.07  3763.4  346.76  3797.9  350.05
  3799.3  349.97  3846.8   347.8  3887.2  350.44  3930.7  339.77  4001.3   339.6
    4103  333.39  4171.6  326.99  4329.4  307.39  4471.2  302.11    4581  298.79
  4833.7  291.67  4966.9  292.69    4978   280.3  4988.8  285.26  4999.1  276.04
  5001.8  275.54  5005.1  276.04  5010.2  276.99  5031.9  294.43  5051.1  299.62
    5180  302.17  5209.8  299.76  5294.7  306.29  5380.3  319.51  5781.7  363.55
#Mann= 10 ,-1 , 0
  3634.2     .16       0  3797.9     .05       0  3799.3     .16       0
  4001.3     .05       0    4103     .08       0  4171.6     .16       0
  4471.2     .05       0    4581     .16       0  4999.1     .07       0
  5005.1     .16       0
Bank Sta=4966.9,5031.9
XS Rating Curve= 0 ,0
Exp/Cntr=0.3,0.1

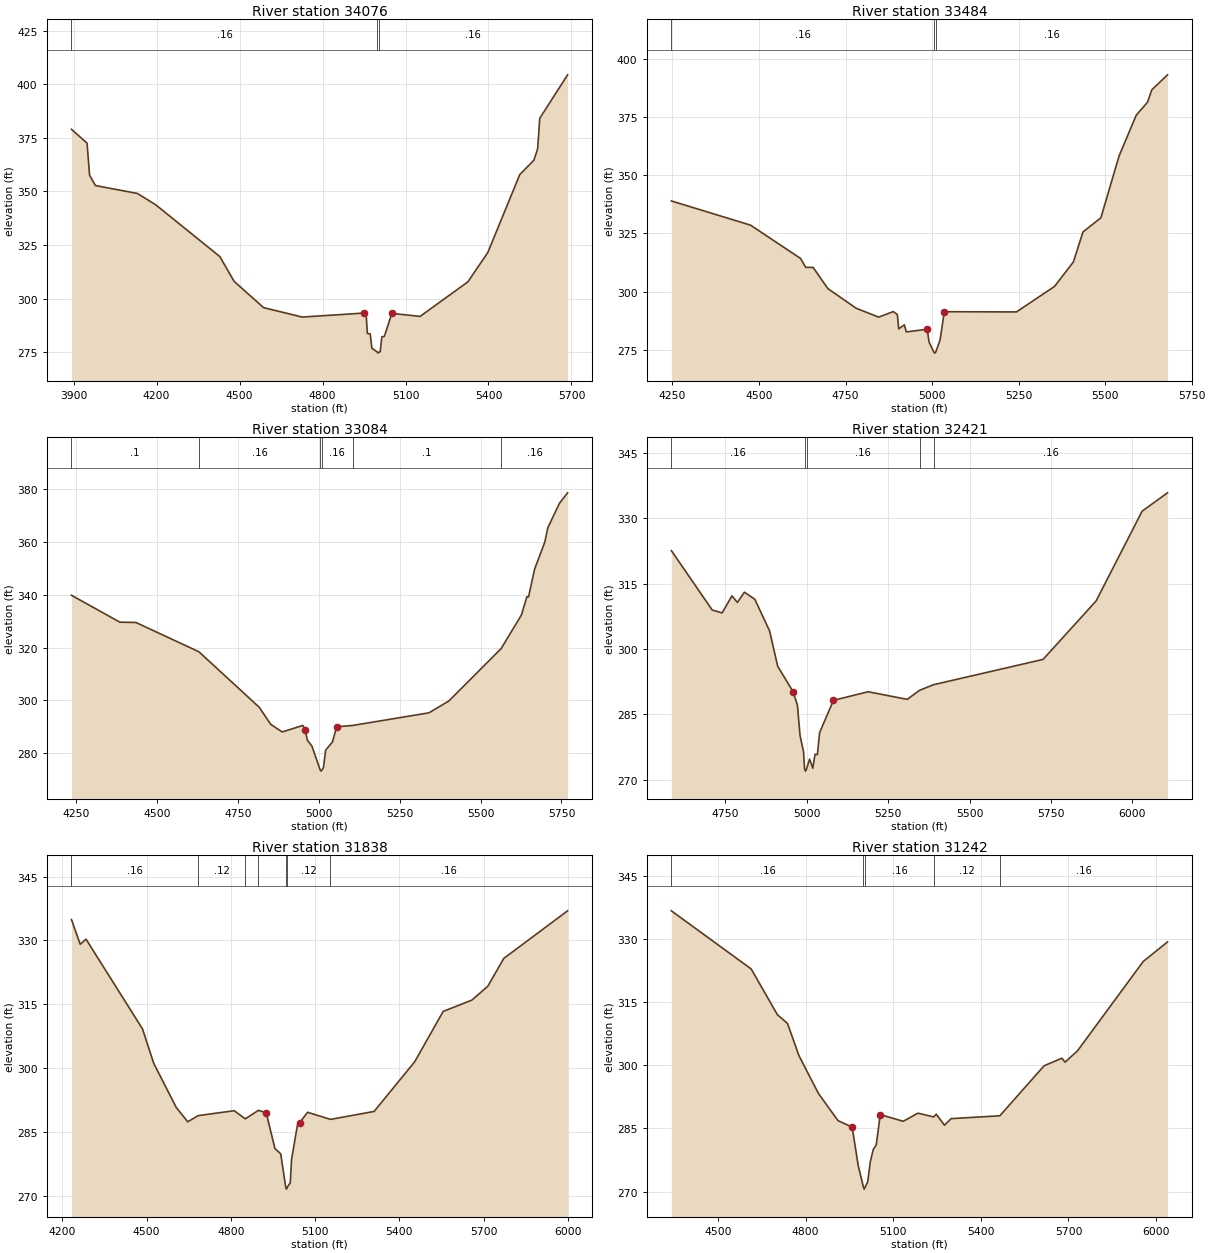
Type RM Length L Ch R = 1 ,34076   ,592,592,592
BEGIN DESCRIPTION:
WHEELOCK CREEK 56.0
END DESCRIPTION:
XS GIS Cut Line= 3
      3663728.06     10506567.94      3664299.61     10505660.19
       3664899.6      10505260.2
#Sta/Elev= 30
  3892.2  379.02  3948.6  372.54  3957.7  357.55  3978.9  352.75  4130.8  349.06
  4196.8  343.78  4428.6  319.61  4480.4  308.02  4586.8  295.77  4726.5  291.36
  4951.3  293.25  4957.3  293.37    4962  283.74  4972.4  283.49  4978.4  276.82
    4998  275.03  5000.7  274.53    5004  275.03  5008.5  275.13  5014.5  282.17
  5023.5  282.31  5050.5  293.08  5152.7  291.67  5325.5   307.8  5397.6  321.51
  5513.2  357.89  5564.3   364.6  5577.8  369.98  5585.4  384.14    5686  404.44
#Mann= 3 ,-1 , 0
  3892.2     .16       0    4998     .07       0    5004     .16       0
Bank Sta=4951.3,5050.5
XS Rating Curve= 0 ,0
Exp/Cntr=0.3,0.1

Type RM Length L Ch R = 1 ,33484   ,400,400,400
BEGIN DESCRIPTION:
WHEELOCK CREEK 55.0
END DESCRIPTION:
XS GIS Cut Line= 3
      3664240.24      10506654.7       3664583.1     10506099.18
       3664949.6      10505410.2
#Sta/Elev= 30
    4247   338.9  4475.6  328.52  4619.8  314.27  4635.2  310.39  4656.4  310.39
    4699  301.29  4781.1  292.84  4845.6  289.04  4888.2  291.42  4899.8  290.14
  4903.7  284.01    4920  285.74  4925.6   282.7  4985.9  283.83  4991.6  278.27
  5004.9  274.09  5007.6  273.59  5010.9  274.09  5023.3  279.33  5035.5  291.37
  5243.9  291.27  5353.8  302.21  5408.4  312.73    5436  325.59  5487.7  331.66
  5540.2  358.14  5589.8  375.69  5622.4  381.26  5634.9   386.6  5680.2  393.03
#Mann= 3 ,-1 , 0
    4247     .16       0  5004.9     .07       0  5010.9     .16       0
Bank Sta=4985.9,5035.5
XS Rating Curve= 0 ,0
Exp/Cntr=0.3,0.1

Type RM Length L Ch R = 1 ,33084   ,663,663,663
BEGIN DESCRIPTION:
WHEELOCK CREEK 54.0
END DESCRIPTION:
XS GIS Cut Line= 3
      3664340.01     10506802.34      3664904.28     10506216.37
      3665049.62     10505510.16
#Sta/Elev= 30
  4234.5   339.8  4384.3  329.61  4433.7   329.5  4628.6   318.4  4815.7  297.31
  4850.9  290.88  4886.5  288.01    4950  290.47  4957.2  288.93  4964.1  284.89
  4978.3  282.61  5003.6  273.66  5006.3  273.16  5009.6  273.66  5013.8  274.45
  5020.7  281.11  5041.9  284.23  5054.5  289.95  5104.1  290.47  5340.2  295.25
  5401.7  299.74  5563.6  319.63    5626  332.27  5643.1  339.25  5648.2  339.19
  5666.9  349.67  5698.6     360  5707.7  365.36  5743.8  374.66    5769  378.63
#Mann= 6 ,-1 , 0
  4234.5      .1       0  4628.6     .16       0  5003.6     .07       0
  5009.6     .16       0  5104.1      .1       0  5563.6     .16       0
Bank Sta=4957.2,5054.5
XS Rating Curve= 0 ,0
Exp/Cntr=0.3,0.1

Type RM Length L Ch R = 1 ,32421   ,583,583,583
BEGIN DESCRIPTION:
WHEELOCK CREEK 53.0
END DESCRIPTION:
XS GIS Cut Line= 3
      3664649.59     10506910.19      3665049.61     10506760.19
      3665849.61     10506010.19
#Sta/Elev= 30
  4584.1   322.6  4709.6  308.96  4739.9   308.3  4770.1  312.22    4787  310.71
  4808.4  313.06  4840.4  311.43  4885.8  304.16  4910.7  296.04  4957.9  290.23
  4971.3  287.11  4979.3  280.11    4990  276.45  4993.2  272.48  4995.9  271.98
  4999.2  272.48  5008.6  274.74  5018.4  272.65  5025.3  275.85  5032.6  275.79
  5039.4  280.81  5081.9  288.23  5188.4   290.2  5308.5  288.46  5346.3  290.53
  5389.4  291.82  5725.7  297.63  5888.6  311.05    6030  331.66  6107.9  335.87
#Mann= 5 ,-1 , 0
  4584.1     .16       0  4993.2     .07       0  4999.2     .16       0
  5346.3     .12       0  5389.4     .16       0
Bank Sta=4957.9,5081.9
XS Rating Curve= 0 ,0
Exp/Cntr=0.3,0.1

Type RM Length L Ch R = 1 ,31838   ,596,596,596
BEGIN DESCRIPTION:
WHEELOCK CREEK 52.0
END DESCRIPTION:
XS GIS Cut Line= 3
      3665249.61      10507710.2      3665449.61     10506960.19
      3666002.34     10506138.28
#Sta/Elev= 30
  4232.6  334.89  4263.7  329.08  4284.4  330.28  4485.5  309.19  4525.6  301.08
  4605.8  290.72  4646.6  287.36  4683.5   288.8  4812.2  289.96  4851.4  288.05
  4898.6  290.05    4926  289.48  4957.1  281.09  4977.8  279.82  4995.5  272.03
  4998.2  271.53  5001.5  272.03  5011.8  273.02  5016.3  278.47  5037.3  286.61
    5045   287.1  5073.3  289.59    5155  287.92  5310.3  289.79  5454.7  301.45
  5556.3   313.3  5658.2  315.95  5715.2  319.21  5772.2  325.76  5999.3  336.94
#Mann= 7 ,-1 , 0
  4232.6     .16       0  4683.5     .12       0  4851.4     .16       0
  4898.6     .12       0  4995.5     .07       0  5001.5     .12       0
    5155     .16       0
Bank Sta=4926,5045
XS Rating Curve= 0 ,0
Exp/Cntr=0.3,0.1

Type RM Length L Ch R = 1 ,31242   ,655,655,655
BEGIN DESCRIPTION:
WHEELOCK CREEK 51.0
END DESCRIPTION:
XS GIS Cut Line= 3
       3665507.6     10507974.14      3665781.02     10507431.65
      3666024.07     10506368.27
#Sta/Elev= 30
  4340.8  336.62    4614  322.82  4703.6  311.98  4738.4  309.88  4777.4  302.26
  4844.4  293.25  4911.3  286.82  4959.7  285.29  4980.6  276.07  4998.1  271.07
  5000.8  270.57  5004.1  271.07  5012.9  272.27  5021.6  277.04  5031.9  279.97
  5042.1  281.07  5055.8  288.26  5134.4  286.67  5184.7   288.6  5239.1  287.71
  5247.3  288.36  5275.7  285.74  5298.6   287.3  5465.2  287.98  5616.6  299.84
  5677.7  301.64  5688.4  300.71  5730.9  303.38    5956   324.6  6039.1  329.24
#Mann= 5 ,-1 , 0
  4340.8     .16       0  4998.1     .07       0  5004.1     .16       0
  5239.1     .12       0  5465.2     .16       0
Bank Sta=4959.7,5055.8
XS Rating Curve= 0 ,0
Exp/Cntr=0.3,0.1

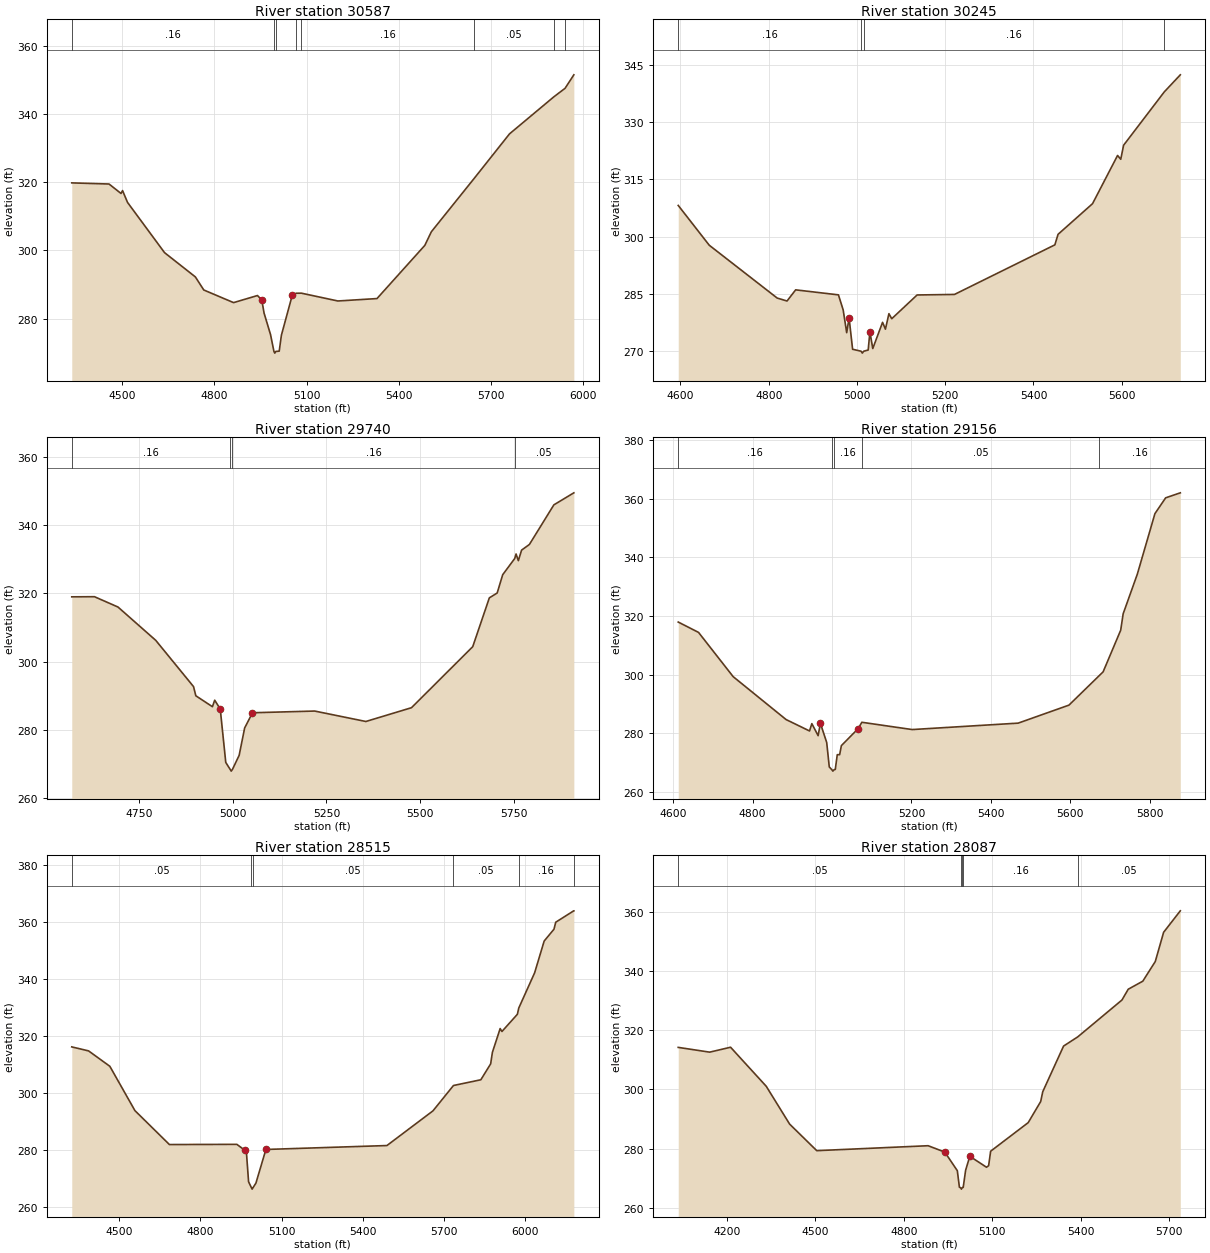
Type RM Length L Ch R = 1 ,30587   ,342,342,342
BEGIN DESCRIPTION:
WHEELOCK CREEK 50.0
END DESCRIPTION:
XS GIS Cut Line= 3
      3666171.42     10508201.11      3666206.14     10507770.52
      3667045.55      10506910.3
#Sta/Elev= 30
  4336.1  319.79  4457.4  319.46  4496.4  316.69  4501.4  317.54  4517.6  314.06
    4638  299.34  4738.3  292.22  4765.8  288.38  4862.7  284.68  4940.5  286.76
  4954.6  285.43  4961.8  281.64  4982.9  275.33    4994  270.37  4996.8  269.87
    5000  270.37  5011.2  270.45  5018.3  275.12  5053.6  286.83  5066.4  287.43
  5083.4  287.45  5202.1  285.16  5329.4  285.87    5485  301.46  5506.3  305.46
  5646.5   321.2  5760.7  334.17  5905.1  345.04  5941.4  347.52    5970  351.48
#Mann= 8 ,-1 , 0
  4336.1     .16       0    4994     .07       0    5000     .16       0
  5066.4     .12       0  5083.4     .16       0  5646.5     .05       0
  5905.1      .1       0  5941.4     .05       0
Bank Sta=4954.6,5053.6
XS Rating Curve= 0 ,0
Exp/Cntr=0.3,0.1

Type RM Length L Ch R = 1 ,30245   ,505,505,505
BEGIN DESCRIPTION:
WHEELOCK CREEK 49.0
END DESCRIPTION:
XS GIS Cut Line= 3
       3666499.6     10508110.21      3666649.61     10507710.19
      3667099.63     10507160.16
#Sta/Elev= 30
  4594.9  308.18  4665.2  297.77  4819.2  283.95  4841.5  283.18    4861   286.1
    4958  284.79  4968.7  280.86  4976.7  274.89  4982.1  278.77  4990.1  270.56
  5009.3  270.05  5012.1  269.55  5015.3  270.05  5025.4  270.36  5029.3  275.11
  5035.8  270.75    5058   277.6  5064.5  275.82  5072.4  279.87  5078.8  278.55
  5136.3  284.76    5221   284.9  5448.5  297.87  5455.7  300.62  5533.9  308.64
  5590.6  321.25  5597.8  320.25  5604.3  323.93  5696.5  337.88  5732.8  342.34
#Mann= 4 ,-1 , 0
  4594.9     .16       0  5009.3     .07       0  5015.3     .16       0
  5696.5     .05       0
Bank Sta=4982.1,5029.3
XS Rating Curve= 0 ,0
Exp/Cntr=0.3,0.1

Type RM Length L Ch R = 1 ,29740   ,584,584,584
BEGIN DESCRIPTION:
WHEELOCK CREEK 48.0
END DESCRIPTION:
XS GIS Cut Line= 2
      3666615.87      10508409.4      3667393.66      10507319.1
#Sta/Elev= 30
  4570.8  318.96  4631.3     319    4694  315.98  4794.8  306.21  4895.6  292.65
  4901.7  289.96    4946  286.76  4952.1  288.66  4966.9  286.07  4981.6  270.42
  4993.4  268.37  4996.1  267.87  4999.4  268.37  5017.3   272.5    5032  280.53
  5052.9  284.98  5218.8  285.48  5355.3  282.42    5477  286.46  5640.4  304.35
  5684.7  318.66  5705.6  320.09  5720.3  325.44  5752.4   330.2    5756  331.52
  5762.1  329.57  5770.7  332.65  5791.6  334.32  5856.8  345.92  5910.1  349.45
#Mann= 4 ,-1 , 0
  4570.8     .16       0  4993.4     .07       0  4999.4     .16       0
  5752.4     .05       0
Bank Sta=4966.9,5052.9
XS Rating Curve= 0 ,0
Exp/Cntr=0.3,0.1

Type RM Length L Ch R = 1 ,29156   ,641,641,641
BEGIN DESCRIPTION:
WHEELOCK CREEK 47.0
END DESCRIPTION:
XS GIS Cut Line= 3
       3666899.6     10508510.19      3667249.61     10508310.19
      3667749.63     10507610.15
#Sta/Elev= 30
  4613.1  317.95  4664.2  314.42  4751.3  299.34  4884.5  284.71  4943.5  280.82
  4949.3  283.32  4965.1  279.23  4970.9  283.42  4986.7  276.89  4993.2  268.56
  4999.5  267.63  5002.3  267.13  5005.5  267.63  5008.3   267.7  5013.3  272.74
  5019.3  272.74  5023.6  275.82  5065.4  281.55  5075.2  283.78  5201.8   281.3
  5468.5  283.49  5596.3  289.63  5672.7  299.71  5682.3  300.98  5726.5  315.17
  5732.7  320.77  5768.3  334.26  5812.6   354.9  5839.6  360.29  5876.5     362
#Mann= 5 ,-1 , 0
  4613.1     .16       0  4999.5     .07       0  5005.5     .16       0
  5075.2     .05       0  5672.7     .16       0
Bank Sta=4970.9,5065.4
XS Rating Curve= 0 ,0
Exp/Cntr=0.3,0.1

Type RM Length L Ch R = 1 ,28515   ,428,428,428
BEGIN DESCRIPTION:
WHEELOCK CREEK 46.0
END DESCRIPTION:
XS GIS Cut Line= 3
      3667025.58     10509423.31      3667629.76     10508659.41
      3668303.36     10508089.97
#Sta/Elev= 30
  4324.5  316.27  4386.6  314.87  4465.2  309.48    4558  293.94  4685.5  282.05
  4934.8  282.12  4963.7  280.09    4970  279.53  4978.1  269.02  4988.5  266.93
  4991.2  266.43  4994.5  266.93  5005.3  268.55  5042.2  280.33  5489.5   281.7
  5659.8  293.86  5735.5  302.74  5836.7  304.75    5873  310.33  5879.5  314.38
  5908.1  322.69  5914.7  321.67  5971.8   327.7  5976.9  329.88  6035.5  342.22
  6070.8  353.36    6107   357.5  6113.6  359.96  6180.1  363.95  6180.5  363.95
#Mann= 6 ,-1 , 0
  4324.5     .05       0  4988.5     .07       0  4994.5     .05       0
  5735.5     .05       0  5976.9     .16       0  6180.1     .05       0
Bank Sta=4963.7,5042.2
XS Rating Curve= 0 ,0
Exp/Cntr=0.3,0.1

Type RM Length L Ch R = 1 ,28087   ,783,783,783
BEGIN DESCRIPTION:
WHEELOCK CREEK 45.0
END DESCRIPTION:
XS GIS Cut Line= 3
      3667091.81     10509640.82      3667660.36     10509219.84
      3668353.97     10508504.55
#Sta/Elev= 30
  4034.9  314.21  4141.6   312.6  4212.5  314.26  4333.5  301.09  4412.9  288.32
    4505  279.35  4882.9  281.02  4939.5  278.87    4982  272.59  4989.1  266.99
  4993.1  266.87  4995.8  266.37  4999.1  266.87    5002  266.97  5010.2  272.76
  5024.4  277.45    5081  273.76  5088.2  274.28  5095.1  279.17  5222.5  288.81
  5264.9  295.93  5271.9  299.25  5342.6  314.66  5390.6  317.75  5540.7   330.2
    5562  333.84  5611.4  336.55  5653.8   343.2  5682.1  353.06  5738.7   360.3
#Mann= 5 ,-1 , 0
  4034.9     .05       0  4993.1     .03       0  4999.1     .05       0
    5002     .16       0  5390.6     .05       0
Bank Sta=4939.5,5024.4
XS Rating Curve= 0 ,0
Exp/Cntr=0.3,0.1

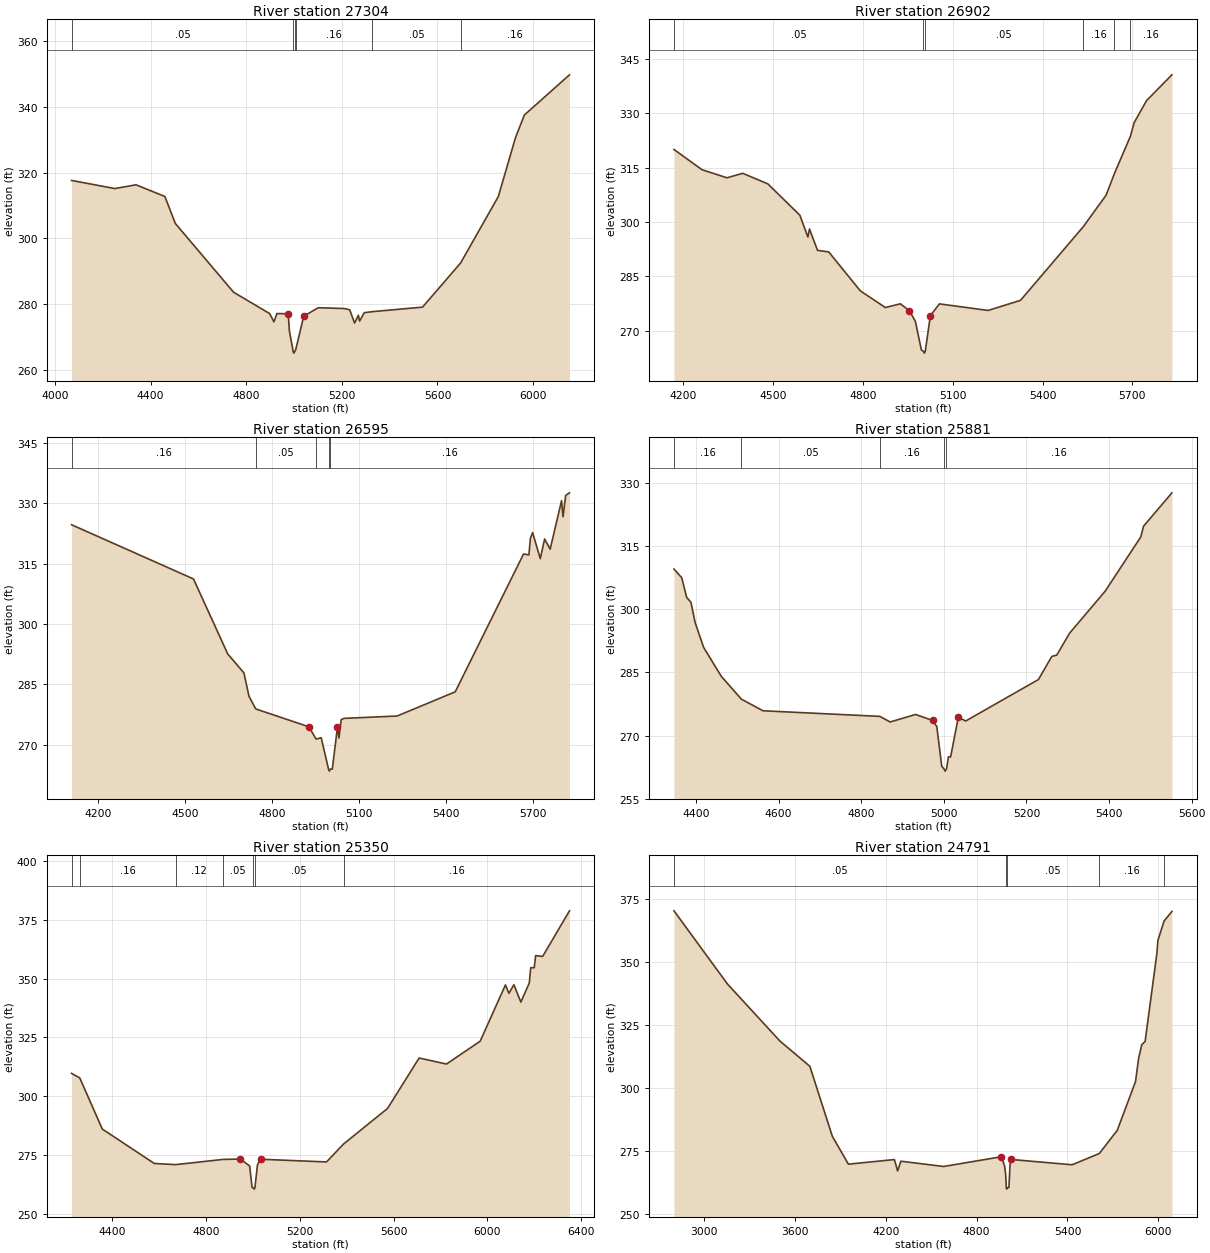
Type RM Length L Ch R = 1 ,27304   ,402,402,402
BEGIN DESCRIPTION:
WHEELOCK CREEK 44.0
END DESCRIPTION:
XS GIS Cut Line= 4
      3667084.63     10510043.08      3667579.41     10509817.39
      3668629.76      10509635.1      3669011.66     10509912.85
#Sta/Elev= 30
  4069.9  317.59  4251.2  315.13  4339.2  316.27  4460.1  312.72    4504  304.51
  4747.3  283.66  4898.1  277.18  4916.2  274.66  4928.6  277.18  4975.9  277.12
  4980.9  271.85  4996.6  265.67  4999.4  265.17  5002.6  265.67  5006.7  266.07
  5040.6  276.35  5101.1  278.95  5209.5  278.71    5233  278.32  5253.3  274.31
  5269.2  276.66  5274.3  274.89  5293.9  277.44  5326.5  277.75  5537.5  279.13
  5696.7  292.53  5854.4   312.7  5926.9  330.74  5963.4  337.45    6152  349.65
#Mann= 6 ,-1 , 0
  4069.9     .05       0  4996.6     .03       0  5002.6     .05       0
  5006.7     .16       0  5326.5     .05       0  5696.7     .16       0
Bank Sta=4975.9,5040.6
XS Rating Curve= 0 ,0
Exp/Cntr=0.3,0.1

Type RM Length L Ch R = 1 ,26902   ,307,307,307
BEGIN DESCRIPTION:
WHEELOCK CREEK 43.0
END DESCRIPTION:
XS GIS Cut Line= 4
      3667261.03     10510322.28      3667803.59     10510148.66
      3668211.57     10510122.62      3668871.27     10509940.33
#Sta/Elev= 30
  4169.2  319.98  4262.8   314.4  4346.2  312.17  4398.7  313.41  4482.6   310.5
  4589.6  301.86  4616.5  295.83  4621.7  298.05  4648.6  292.17    4686  291.73
  4791.7  280.99  4875.2   276.4  4925.3  277.43  4955.3  275.52  4975.4  272.61
  4995.4  264.72  5002.4  264.33  5005.2  263.83  5008.4  264.33  5025.5  274.14
  5055.5  277.41  5218.3   275.6  5326.5  278.38  5536.4  298.71  5612.5   307.4
  5640.1  313.34  5693.6  323.63  5706.1  327.39  5747.4  333.45  5832.1  340.56
#Mann= 6 ,-1 , 0
  4169.2     .05       0  5002.4     .03       0  5008.4     .05       0
  5536.4     .16       0  5640.1     .05       0  5693.6     .16       0
Bank Sta=4955.3,5025.5
XS Rating Curve= 0 ,0
Exp/Cntr=0.3,0.1

Type RM Length L Ch R = 1 ,26595   ,714,714,714
BEGIN DESCRIPTION:
WHEELOCK CREEK 42.0
END DESCRIPTION:
XS GIS Cut Line= 5
      3667226.35     10510782.33      3667742.82      10510487.2
      3667912.09     10510439.46      3668228.93     10510387.38
      3668832.22     10510218.11
#Sta/Elev= 30
  4109.1  324.69  4529.9  311.21    4648  292.59  4703.9  287.86  4721.4  282.07
  4744.7  278.91    4928  274.47  4953.1  271.41  4970.7  271.76  4995.9  263.95
  4998.7  263.45  5001.9  263.95    5009  263.96  5026.8  274.41  5031.9  271.68
  5039.5  276.24  5049.6  276.56  5232.8  277.15  5433.2  283.16    5669  317.42
  5687.4   317.2  5692.6  321.32  5700.2  322.74  5726.7  316.27  5741.7  321.15
  5760.8  318.62  5800.1  330.67  5805.2  326.69  5814.4     332  5827.5  332.62
#Mann= 5 ,-1 , 0
  4109.1     .16       0  4744.7     .05       0  4953.1     .16       0
  4995.9     .07       0  5001.9     .16       0
Bank Sta=4928,5026.8
XS Rating Curve= 0 ,0
Exp/Cntr=0.3,0.1

Type RM Length L Ch R = 1 ,25881   ,531,531,531
BEGIN DESCRIPTION:
WHEELOCK CREEK 41.0
END DESCRIPTION:
XS GIS Cut Line= 3
      3667649.62     10510960.19      3668299.61     10510810.19
      3668799.62     10510610.18
#Sta/Elev= 30
  4346.6   309.5  4365.4  307.44  4377.4  302.77  4387.6  301.64  4397.9  296.79
  4418.4  290.93  4461.2  284.06    4510  278.64  4562.1   275.9    4845  274.57
    4870  273.24  4931.6  275.02  4972.6  273.61  4982.9  272.17  4994.9  262.75
  5000.4  262.09  5003.2  261.59  5006.4  262.09  5011.1  264.96  5016.4  264.96
  5035.2  274.42  5052.7  273.46  5229.1  283.31  5261.4  288.78  5273.5  289.11
  5304.5   294.3  5390.6  304.25  5476.8   317.1  5483.5  319.65  5552.2  327.57
#Mann= 5 ,-1 , 0
  4346.6     .16       0    4510     .05       0    4845     .16       0
  5000.4     .07       0  5006.4     .16       0
Bank Sta=4972.6,5035.2
XS Rating Curve= 0 ,0
Exp/Cntr=0.3,0.1

Type RM Length L Ch R = 1 ,25350   ,559,559,559
BEGIN DESCRIPTION:
WHEELOCK CREEK 40.0
END DESCRIPTION:
XS GIS Cut Line= 3
      3667799.63     10511360.19      3668549.61     10511260.19
      3669680.36     10510491.52
#Sta/Elev= 30
  4226.6  309.74  4261.6  307.81  4357.7  286.09  4579.7  271.45  4670.7  270.97
  4871.2  273.17  4946.7  273.36  4986.2   270.4  4996.7  261.25  5002.6  261.06
  5005.4  260.56  5008.6  261.06  5019.5  270.83  5032.7  273.26    5314  272.11
  5387.2  279.76  5574.4  294.84  5709.2  316.28  5825.9  313.71  5969.6  323.43
  6077.3  347.34  6092.3  343.75  6113.3  347.43  6143.1  340.05  6179.1  348.17
  6185.1  354.63  6200.1  354.65  6206.1  359.81    6236  359.43  6350.5  378.82
#Mann= 7 ,-1 , 0
  4226.6     .05       0  4261.6     .16       0  4670.7     .12       0
  4871.2     .05       0  5002.6     .03       0  5008.6     .05       0
  5387.2     .16       0
Bank Sta=4946.7,5032.7
XS Rating Curve= 0 ,0
Exp/Cntr=0.3,0.1

Type RM Length L Ch R = 1 ,24791   ,516,516,516
BEGIN DESCRIPTION:
WHEELOCK CREEK 39.0
END DESCRIPTION:
XS GIS Cut Line= 3
      3667299.62     10513210.18      3668899.61     10511660.19
      3669699.63     10510960.17
#Sta/Elev= 30
  2799.7  370.22  3153.3  341.16  3499.8  318.52  3697.8  308.48  3846.3  280.67
  3952.5  269.62  4256.5  271.45  4277.7  266.94    4299   270.8  4581.8   268.7
  4963.7  272.57    4985  268.81    4992  265.42  4996.2  260.21  4998.9  259.71
  5002.2  260.21  5013.3  260.34  5020.3  269.15  5027.4  271.49  5431.2  269.38
  5610.7  273.86  5729.2  283.04  5849.8  302.39  5870.7  311.71  5891.5  317.09
  5913.4  318.37  5991.2  353.34  5997.8  358.46  6038.6  366.16  6090.4  369.97
#Mann= 5 ,-1 , 0
  2799.7     .05       0  4996.2     .03       0  5002.2     .05       0
  5610.7     .16       0  6038.6      .1       0
Bank Sta=4963.7,5027.4
XS Rating Curve= 0 ,0
Exp/Cntr=0.3,0.1

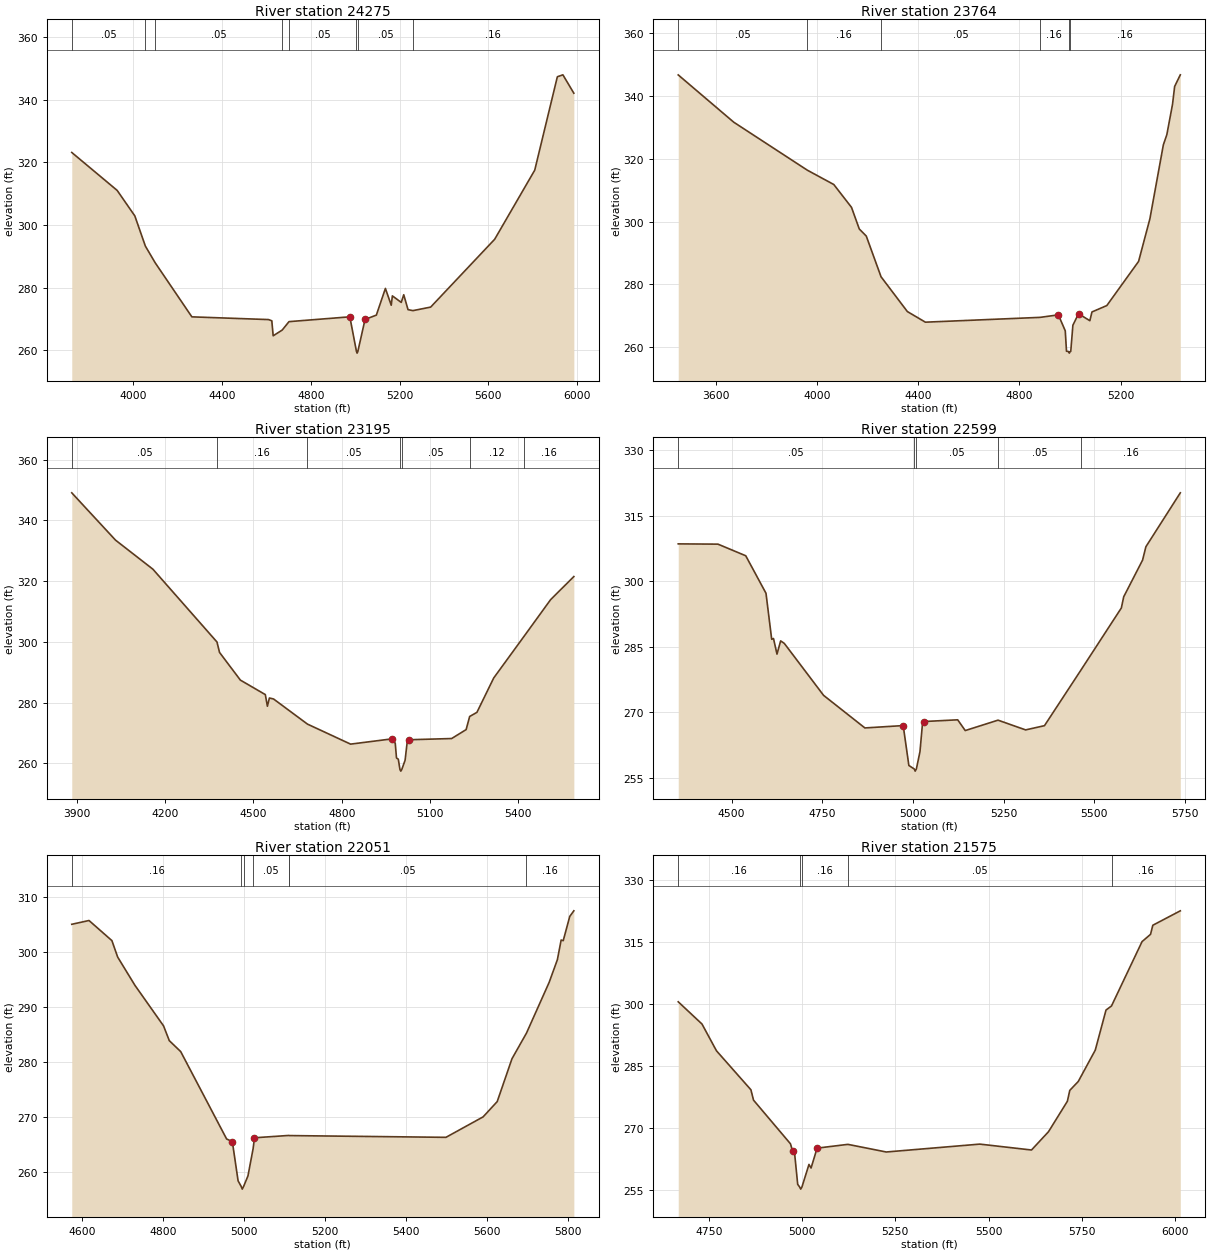
Type RM Length L Ch R = 1 ,24275   ,511,511,511
BEGIN DESCRIPTION:
WHEELOCK CREEK 38.0
END DESCRIPTION:
XS GIS Cut Line= 3
      3667966.77     10512882.17      3668999.61     10512160.19
      3669982.44     10511965.49
#Sta/Elev= 30
  3722.9  323.19  3927.4  311.06    4007  302.91  4054.5  293.25  4098.3  287.96
    4264  270.62  4609.4  269.75  4624.2  269.36  4630.3  264.56  4671.1   266.4
  4701.6  269.09  4975.7  270.63  5005.7  259.52  5008.4  259.02  5011.7  259.52
  5044.2  269.78  5095.2  271.18    5136  279.71  5162.3  274.34  5167.4  277.33
  5207.3  275.24  5218.6  277.69  5237.9  272.93  5259.8  272.61  5339.9  273.74
  5628.4  295.44  5808.8  317.53  5910.7   347.4  5935.7  348.02    5985  342.14
#Mann= 8 ,-1 , 0
  3722.9     .05       0  4054.5     .16       0  4098.3     .05       0
  4671.1     .12       0  4701.6     .05       0  5005.7     .03       0
  5011.7     .05       0  5259.8     .16       0
Bank Sta=4975.7,5044.2
XS Rating Curve= 0 ,0
Exp/Cntr=0.3,0.1

Type RM Length L Ch R = 1 ,23764   ,569,569,569
BEGIN DESCRIPTION:
WHEELOCK CREEK 37.0
END DESCRIPTION:
XS GIS Cut Line= 3
      3667883.24      10513406.8      3669199.61     10512610.19
      3669599.65     10512410.17
#Sta/Elev= 30
  3450.6  346.72  3670.2  331.66  3960.9  316.39  4065.9  311.81    4136  304.53
  4166.8  297.63  4194.4  295.39  4252.8  282.42  4356.9  271.34  4428.2  267.96
  4881.8  269.49  4954.2  270.29  4981.5  265.19  4986.3   258.7  4994.6   258.6
  4997.4   258.1  5000.6   258.6  5003.2  258.66  5011.6     267    5034  270.64
  5078.7  268.43  5087.1  271.22  5145.8  273.25  5271.5  287.32  5316.3  300.93
  5369.4  324.44  5383.3  327.72  5405.7  337.36  5414.1  343.05  5436.5  346.75
#Mann= 6 ,-1 , 0
  3450.6     .05       0  3960.9     .16       0  4252.8     .05       0
  4881.8     .16       0  4994.6     .07       0  5000.6     .16       0
Bank Sta=4954.2,5034
XS Rating Curve= 0 ,0
Exp/Cntr=0.3,0.1

Type RM Length L Ch R = 1 ,23195   ,596,596,596
BEGIN DESCRIPTION:
WHEELOCK CREEK 36.0
END DESCRIPTION:
XS GIS Cut Line= 3
      3668299.59     10513910.21      3669099.61     10513160.19
      3669599.57     10512810.21
#Sta/Elev= 30
  3882.2   349.1    4031  333.52    4158  323.96  4375.9  299.98  4384.6  296.55
  4455.4  287.44  4540.2  282.67  4547.3  278.84  4554.1  281.54  4568.3  281.22
  4683.5  272.95  4830.1  266.36  4971.7   268.1  4981.9  266.64  4986.2  261.79
  4992.3  261.41    4998  257.97  5000.8  257.47    5004  257.97  5015.4  261.05
    5022  266.59  5028.1   267.8  5173.7   268.2  5222.9  271.14  5234.9  275.46
  5259.6  276.82  5316.7  288.14  5421.1  302.03  5510.2  313.94  5589.1  321.53
#Mann= 7 ,-1 , 0
  3882.2     .05       0  4375.9     .16       0  4683.5     .05       0
    4998     .03       0    5004     .05       0  5234.9     .12       0
  5421.1     .16       0
Bank Sta=4971.7,5028.1
XS Rating Curve= 0 ,0
Exp/Cntr=0.3,0.1

Type RM Length L Ch R = 1 ,22599   ,548,548,548
BEGIN DESCRIPTION:
WHEELOCK CREEK 35.0
END DESCRIPTION:
XS GIS Cut Line= 3
      3669358.92     10514209.77      3669449.61     10513560.19
      3669649.61     10512860.18
#Sta/Elev= 30
  4353.1  308.54  4462.6  308.48  4539.2  305.82    4595  297.24  4610.7  286.71
  4615.7  286.89  4625.3  283.32  4635.4  286.35  4645.5  285.77  4753.7  273.89
  4867.6  266.43  4973.2  266.97  4988.8  257.84  5003.5  257.05  5006.2  256.55
  5009.5  257.05  5019.4     261  5025.9  267.02  5031.1   267.9  5123.4  268.29
  5144.2  265.83  5234.6  268.21  5310.6  265.98  5362.6  266.95  5463.5  279.72
  5574.5  293.88    5581  296.44    5633  304.83  5642.1  307.88    5737  320.22
#Mann= 5 ,-1 , 0
  4353.1     .05       0  5003.5     .03       0  5009.5     .05       0
  5234.6     .05       0  5463.5     .16       0
Bank Sta=4973.2,5031.1
XS Rating Curve= 0 ,0
Exp/Cntr=0.3,0.1

Type RM Length L Ch R = 1 ,22051   ,476,476,476
BEGIN DESCRIPTION:
WHEELOCK CREEK 34.0
END DESCRIPTION:
XS GIS Cut Line= 3
      3670149.64     10514060.22      3669849.61     10513760.19
      3669699.62     10512960.24
#Sta/Elev= 30
  4575.5  305.12    4618  305.81  4674.5  302.15  4688.7  299.16  4731.1  294.04
  4801.8  286.65    4816  283.96  4844.2  281.96  4957.4  266.07  4971.5  265.59
  4985.7  258.46  4993.3  257.45    4996  256.95  4999.3  257.45    5010  259.35
  5022.8  264.34  5026.1  266.29  5110.4  266.71    5112  266.69  5498.3  266.37
  5589.9  270.09  5624.7  272.87  5661.1  280.66  5696.9  285.33  5752.7  294.54
  5773.1  298.68  5782.4  302.26  5787.5  302.14  5803.6  306.55  5813.7  307.57
#Mann= 7 ,-1 , 0
  4575.5     .16       0  4993.3     .07       0  4999.3     .16       0
  5022.8     .05       0  5110.4     .12       0    5112     .05       0
  5696.9     .16       0
Bank Sta=4971.5,5026.1
XS Rating Curve= 0 ,0
Exp/Cntr=0.3,0.1

Type RM Length L Ch R = 1 ,21575   ,381,381,381
BEGIN DESCRIPTION:
WHEELOCK CREEK 33.0
END DESCRIPTION:
XS GIS Cut Line= 3
      3670199.62     10513960.15      3670300.11     10513679.04
      3669799.59     10512760.15
#Sta/Elev= 30
  4668.4  300.51  4732.1  295.14  4770.8  288.69  4863.1  279.28  4870.1  276.78
  4969.1  266.24  4974.9  264.43  4980.6  263.52  4988.4  256.47  4993.7  255.81
  4996.5  255.31  4999.7  255.81  5018.6  261.27  5024.2   260.4  5040.4   265.2
  5122.8  266.11  5225.6  264.27  5476.3  266.17  5614.7  264.75  5660.2  269.16
  5710.8  276.51  5717.2  279.13    5740  281.29  5785.5  288.85  5814.3  298.52
    5829  299.51  5910.8  315.03  5933.5  316.78  5939.7  318.98  6013.3  322.46
#Mann= 5 ,-1 , 0
  4668.4     .16       0  4993.7     .07       0  4999.7     .16       0
  5122.8     .05       0    5829     .16       0
Bank Sta=4974.9,5040.4
XS Rating Curve= 0 ,0
Exp/Cntr=0.3,0.1