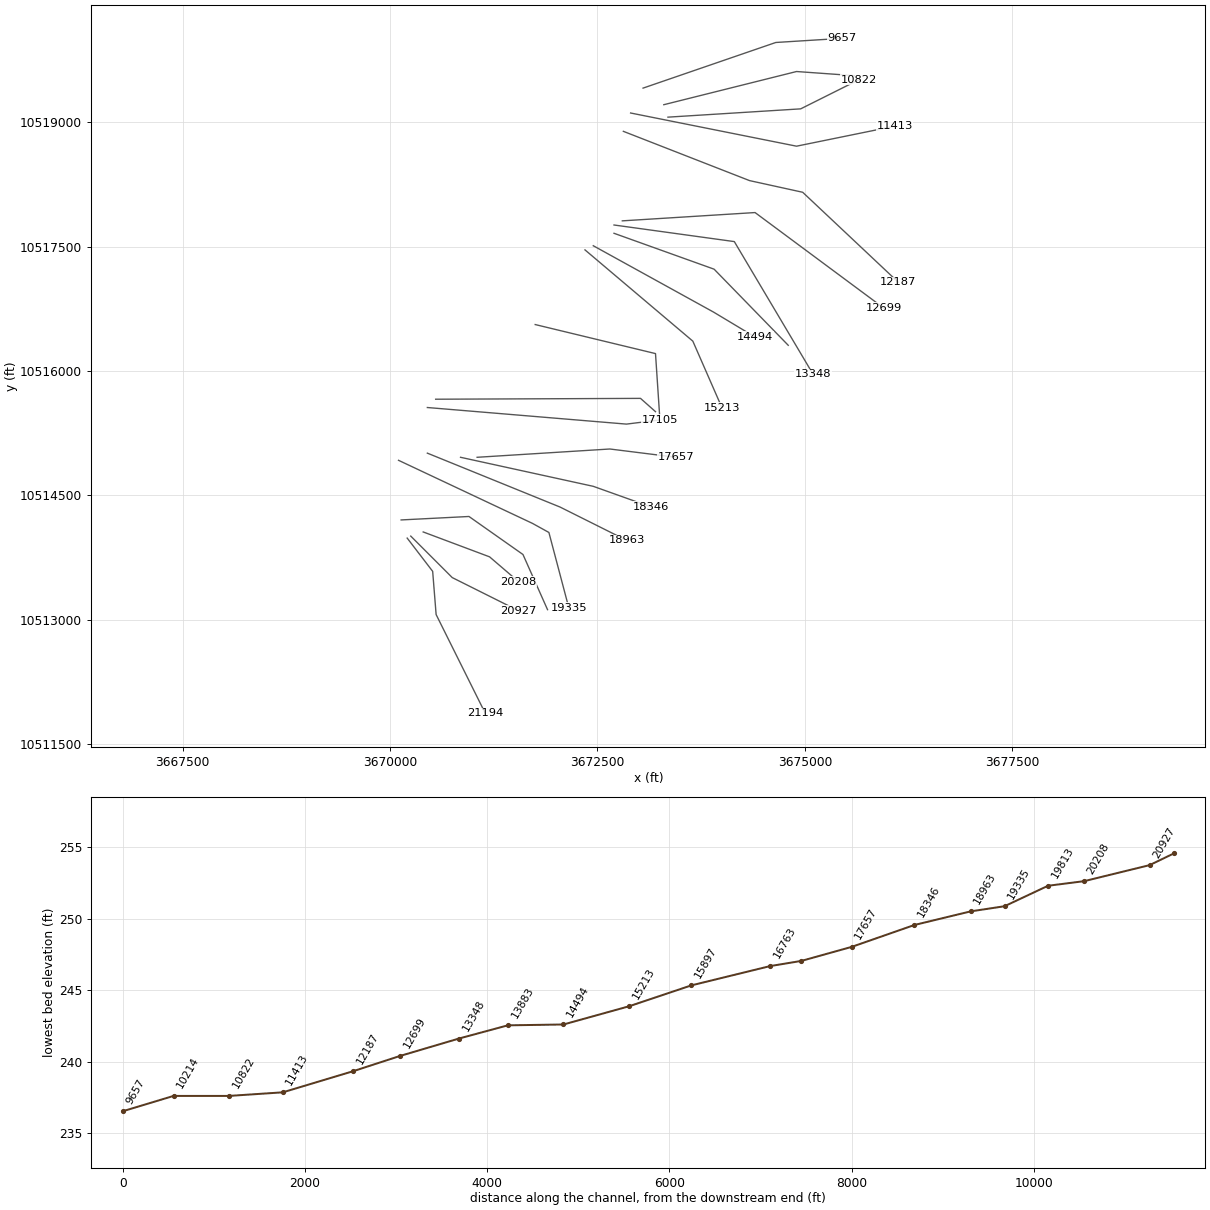
HEC-RAS study WHEELOCK CREEK.prj: WHEELOCK CREEK Base Level Engineering

--- WHEELOCK CREEK.g01 (geometry) --- (continued)

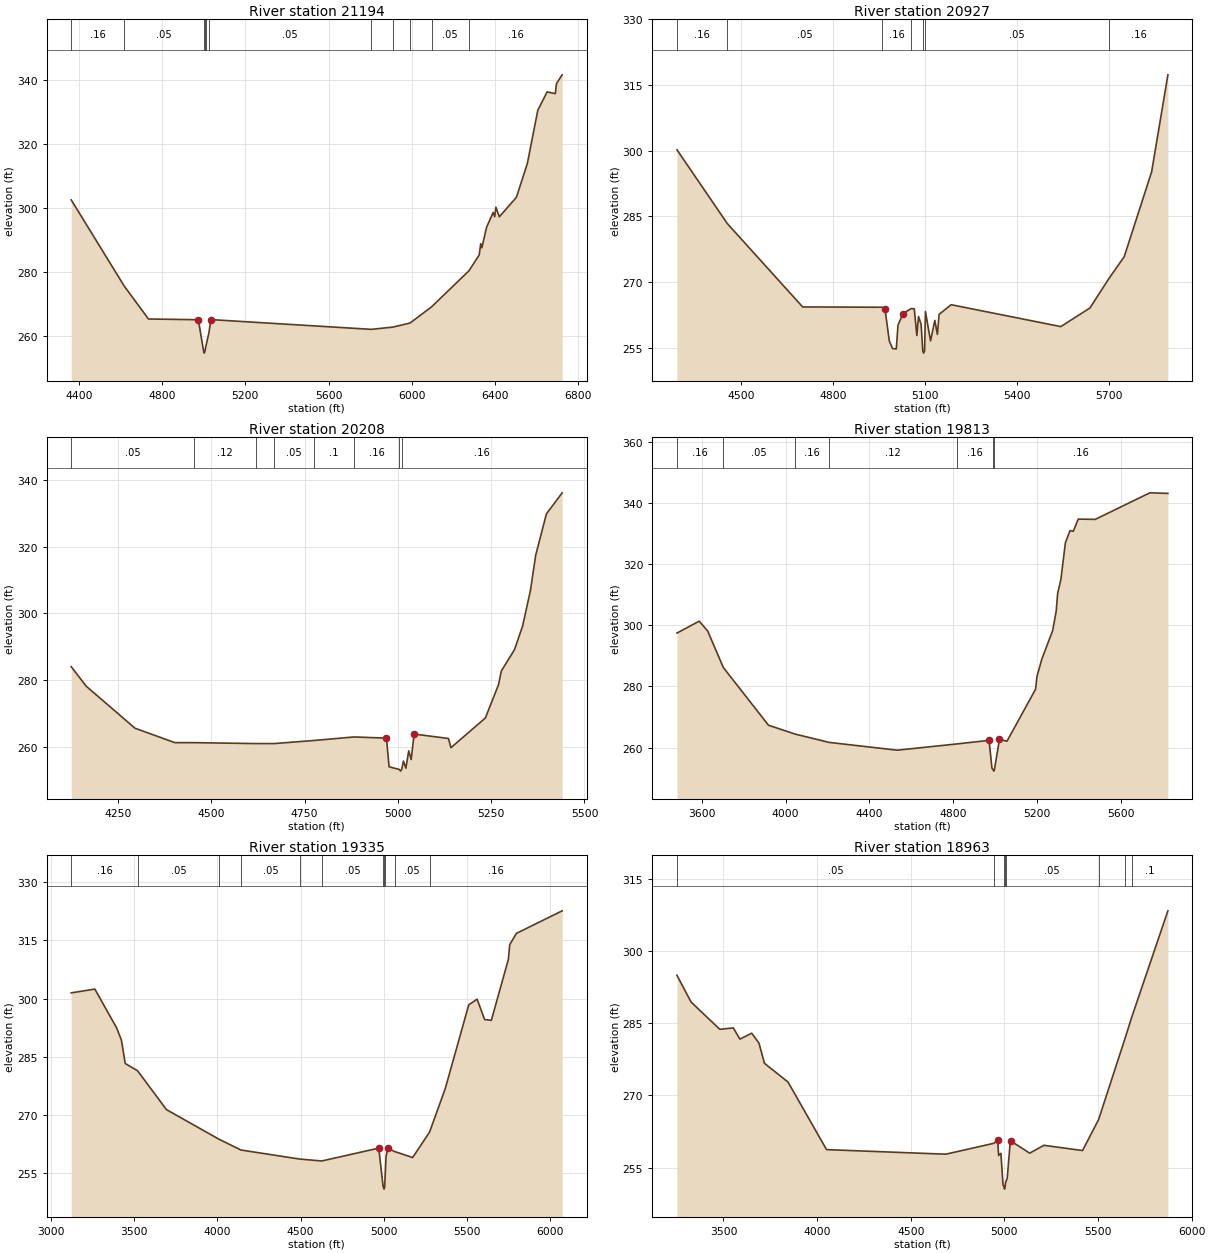
Type RM Length L Ch R = 1 ,21194   ,267,267,267
BEGIN DESCRIPTION:
Mapping XS a77bd0d8
END DESCRIPTION:
XS GIS Cut Line= 4
      3670206.35     10513986.35      3670513.65     10513585.29
      3670555.32     10513064.46      3671148.23     10511873.44
#Sta/Elev= 30
  4363.8  302.52  4618.4  275.55  4734.9  265.24  4974.5  265.01    5000  255.06
  5002.8  254.56    5006  255.06  5009.5  256.39  5025.4  260.99  5034.7  265.05
  5804.8     262  5908.8   262.7    5991  263.97  6094.4  269.03  6274.6  280.35
  6323.5  285.29  6330.7   288.8  6336.3  287.52  6358.7  293.91  6390.5  298.58
  6397.9  297.26  6403.5  300.22  6420.3  297.23  6502.2  303.32  6554.6  313.87
    6605  330.57  6649.8  336.31    6689  335.76  6694.6  338.92    6722  341.65
#Mann= 11 ,-1 , 0
  4363.8     .16       0  4618.4     .05       0    5000     .03       0
    5006     .05       0  5009.5     .16       0  5025.4     .05       0
  5804.8     .16       0  5908.8     .05       0    5991     .16       0
  6094.4     .05       0  6274.6     .16       0
Bank Sta=4974.5,5034.7
XS Rating Curve= 0 ,0
Exp/Cntr=0.3,0.1

Type RM Length L Ch R = 1 ,20927   ,719,719,719
BEGIN DESCRIPTION:
WHEELOCK CREEK 32.0
END DESCRIPTION:
XS GIS Cut Line= 3
      3670249.62     10514010.17      3670749.61     10513510.19
       3671549.6     10513110.19
#Sta/Elev= 30
  4289.6  300.19  4453.9  283.33  4699.7  264.29  4959.8  264.22  4968.4  263.71
  4982.5  256.47  4993.1  254.78  5005.1  254.69  5010.7  260.15  5027.4  262.78
  5053.4  263.91  5063.8  263.87  5072.2  257.76  5077.7  262.11  5086.1  260.27
  5091.5  254.24  5094.3  253.74  5097.5  254.24  5100.1  263.26  5116.9  256.55
  5130.8  261.22  5139.2  258.02  5144.8  262.59    5184   264.8  5541.7   259.8
  5636.8  264.05  5698.5  270.75  5748.6  275.76    5838  295.13  5891.1   317.3
#Mann= 7 ,-1 , 0
  4289.6     .16       0  4453.9     .05       0  4959.8     .16       0
  5053.4     .05       0  5091.5     .07       0  5097.5     .05       0
  5698.5     .16       0
Bank Sta=4968.4,5027.4
XS Rating Curve= 0 ,0
Exp/Cntr=0.3,0.1

Type RM Length L Ch R = 1 ,20208   ,395,395,395
BEGIN DESCRIPTION:
WHEELOCK CREEK 31.0
END DESCRIPTION:
XS GIS Cut Line= 3
       3670399.6     10514060.19      3671199.61     10513760.19
      3671549.62     10513460.18
#Sta/Elev= 30
  4124.9  284.02    4165  278.16  4295.8  265.52  4402.6  261.18  4453.9  261.18
  4620.1   260.9  4668.2   260.9  4775.4  261.83  4882.5  262.89  4969.5  262.54
  4976.6  253.92  5004.3  253.12    5007  252.62  5010.3  253.12    5015  255.63
  5021.6  253.49  5029.2  258.73  5035.8  256.11  5043.5  263.77  5135.7  262.43
  5142.3  259.67  5234.5  268.59  5269.6  278.54  5277.3  282.71  5312.4   289.1
  5334.4  296.27  5355.2  306.88  5369.5  317.59    5398  329.92  5440.3  336.27
#Mann= 8 ,-1 , 0
  4124.9     .05       0  4453.9     .12       0  4620.1     .16       0
  4668.2     .05       0  4775.4      .1       0  4882.5     .16       0
  5004.3     .07       0  5010.3     .16       0
Bank Sta=4969.5,5043.5
XS Rating Curve= 0 ,0
Exp/Cntr=0.3,0.1

Type RM Length L Ch R = 1 ,19813   ,478,478,478
BEGIN DESCRIPTION:
Mapping XS 7257c7bd
END DESCRIPTION:
XS GIS Cut Line= 4
      3670133.42     10514205.08      3670951.15     10514246.75
       3671602.2     10513788.42      3671898.31     10513123.46
#Sta/Elev= 30
  3481.9  297.45  3588.2  301.34  3628.3  298.17  3703.3  286.19  3918.7  267.32
  4045.6  264.42  4208.4  261.69  4533.3  259.15  4816.1  261.18  4971.4  262.36
  4985.3  253.24    4991   252.8  4993.8   252.3    4997   252.8    5021  262.68
    5057  262.09  5193.5  279.11    5200  283.29  5223.3  288.96  5275.2  298.34
    5292  304.69  5298.5  310.35  5313.9  314.89  5335.8  327.02  5357.7  330.95
  5373.7  330.75  5396.9  334.72  5478.1  334.63  5738.6  343.31  5824.8  343.13
#Mann= 7 ,-1 , 0
  3481.9     .16       0  3703.3     .05       0  4045.6     .16       0
  4208.4     .12       0  4816.1     .16       0    4991     .07       0
    4997     .16       0
Bank Sta=4971.4,5021
XS Rating Curve= 0 ,0
Exp/Cntr=0.3,0.1

Type RM Length L Ch R = 1 ,19335   ,372,372,372
BEGIN DESCRIPTION:
WHEELOCK CREEK 30.0
END DESCRIPTION:
XS GIS Cut Line= 4
      3670102.24     10514923.81      3671716.78     10514163.42
       3671914.7     10514054.04      3672154.29     10513147.75
#Sta/Elev= 30
  3122.7  301.47  3264.7  302.44  3395.9   292.4  3424.2  289.29    3447  283.26
    3521   281.4  3694.6  271.37  4011.7   263.7  4142.2  260.95  4494.9  258.62
  4627.2  258.13  4969.6  261.44    4996  251.42  4998.7  251.37  5001.4  250.87
  5004.7  251.37  5013.4  259.35  5023.4  261.39  5066.8  260.53    5173  259.02
  5274.7  265.58    5369  276.81  5509.8  298.37  5559.9  299.85  5605.4  294.58
  5645.6  294.39  5747.7  310.08    5756  313.91  5796.3  316.81  6070.9  322.62
#Mann= 11 ,-1 , 0
  3122.7     .16       0    3521     .05       0  4011.7     .16       0
  4142.2     .05       0  4494.9     .12       0  4627.2     .05       0
    4996     .16       0  4998.7     .07       0  5004.7     .16       0
  5066.8     .05       0  5274.7     .16       0
Bank Sta=4969.6,5023.4
XS Rating Curve= 0 ,0
Exp/Cntr=0.3,0.1

Type RM Length L Ch R = 1 ,18963   ,617,617,617
BEGIN DESCRIPTION:
WHEELOCK CREEK 29.0
END DESCRIPTION:
XS GIS Cut Line= 3
      3670449.58      10515010.2      3672049.61     10514360.19
      3672849.57     10513960.21
#Sta/Elev= 30
  3251.7  295.02  3327.3  289.44  3480.7  283.77  3552.9  284.06  3587.8  281.73
  3651.1  282.96  3689.5  280.92    3719   276.7  3844.8   272.8  4050.5  258.73
  4687.3  257.78  4943.8  260.05    4964  260.71  4969.4  257.52  4981.5  257.97
  4992.7  251.41  4998.1  251.01  5000.8  250.51  5004.1  251.01  5006.8  251.91
  5015.1  252.75  5031.8  260.58  5037.4  260.45  5135.2     258  5210.7  259.63
  5417.5  258.54  5503.3  265.01  5643.4  281.77  5678.9  286.17  5873.1  308.43
#Mann= 8 ,-1 , 0
  3251.7     .05       0  4943.8     .16       0  4998.1     .07       0
  5004.1     .16       0  5006.8     .05       0  5503.3      .1       0
  5643.4     .16       0  5678.9      .1       0
Bank Sta=4964,5037.4
XS Rating Curve= 0 ,0
Exp/Cntr=0.3,0.1

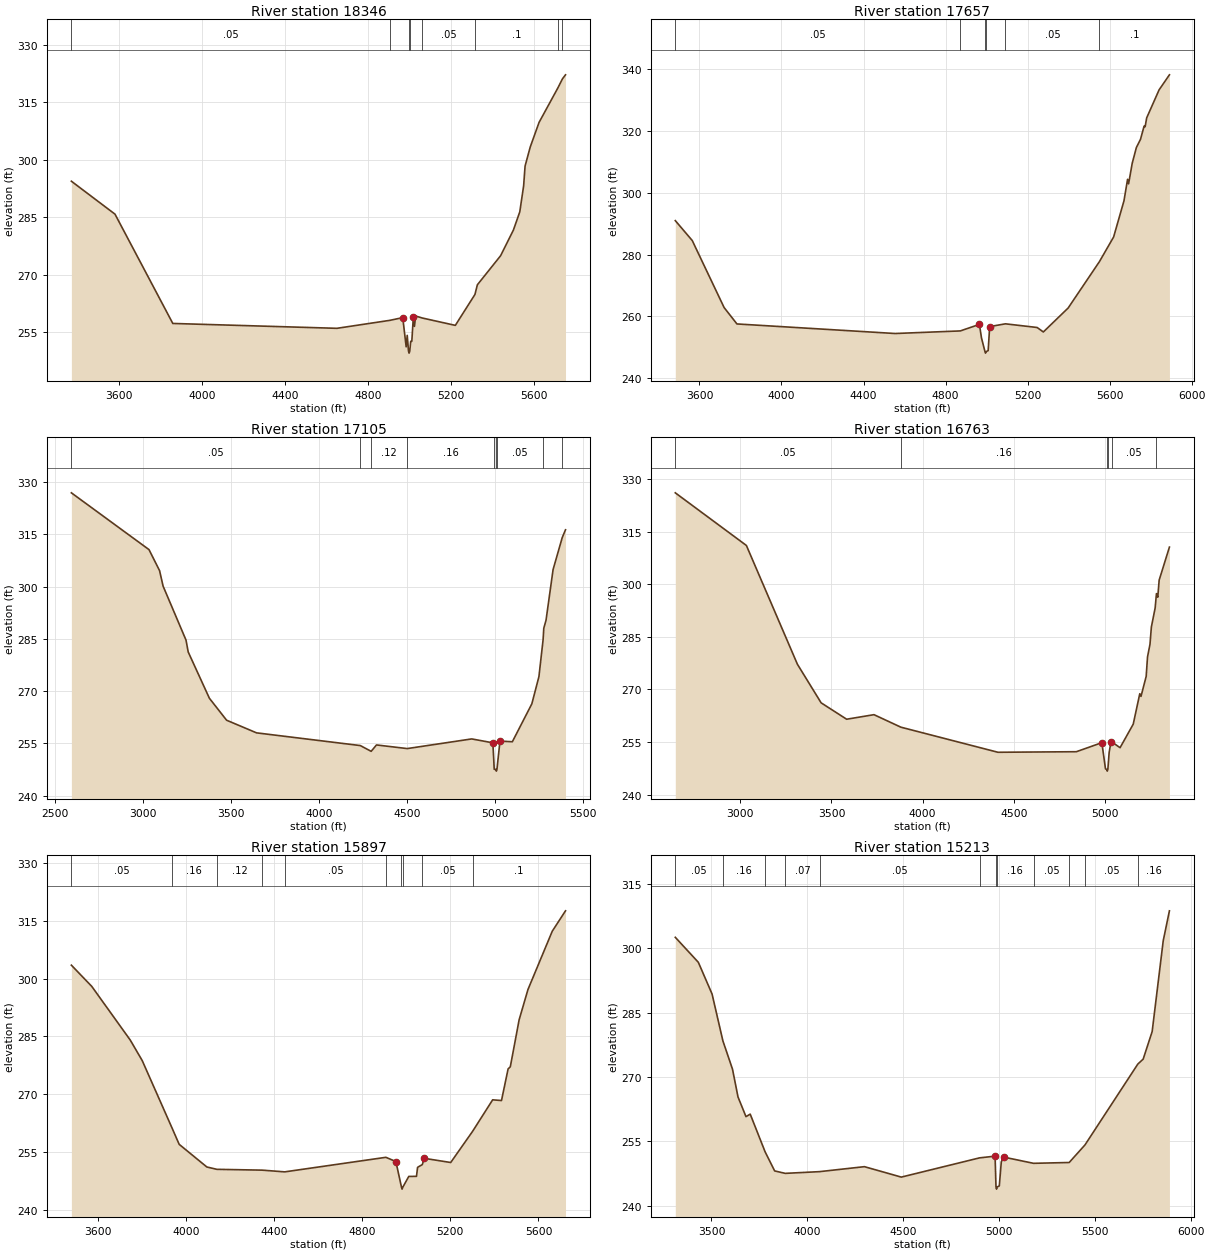
Type RM Length L Ch R = 1 ,18346   ,689,689,689
BEGIN DESCRIPTION:
WHEELOCK CREEK 28.0
END DESCRIPTION:
XS GIS Cut Line= 3
      3670849.64     10514960.18      3672449.61     10514610.19
       3673149.6     10514360.19
#Sta/Elev= 30
  3369.9   294.4  3580.1  285.81  3858.7   257.3  4649.4  256.03  4905.7  258.12
  4966.8  258.83  4983.2   251.2  4988.3  254.19  4994.5  250.06  4997.2  249.56
  5000.5  250.06  5005.1  252.64  5010.4  252.64  5017.8  259.02  5023.1  256.54
  5028.9  259.24  5060.9  258.72  5220.1   256.8  5314.6  264.86  5326.3  267.38
  5438.3  274.97  5499.9  281.65  5530.7  286.41  5549.3  293.22  5556.2  298.35
  5581.1  303.33  5623.6  309.74  5713.2  318.63  5736.4  321.11    5751  322.15
#Mann= 8 ,-1 , 0
  3369.9     .05       0  4905.7     .16       0  4994.5     .07       0
  5000.5     .16       0  5060.9     .05       0  5314.6      .1       0
  5713.2     .16       0  5736.4      .1       0
Bank Sta=4966.8,5017.8
XS Rating Curve= 0 ,0
Exp/Cntr=0.3,0.1

Type RM Length L Ch R = 1 ,17657   ,552,552,552
BEGIN DESCRIPTION:
WHEELOCK CREEK 27.0
END DESCRIPTION:
XS GIS Cut Line= 3
      3671049.59     10514960.19      3672649.61     10515060.19
      3673449.65     10514960.18
#Sta/Elev= 30
  3482.2  290.99  3564.9  284.53  3720.2  262.81  3782.8  257.49  4554.3  254.39
  4872.1  255.23  4965.1  257.35  4975.1  252.99  4992.2  248.53  4994.9  248.03
  4998.2  248.53  5007.7  248.84  5015.2  256.63  5091.9  257.53  5246.6  256.34
  5276.8  254.89  5397.7  262.65  5550.4  277.71  5619.5  285.69  5669.9  297.39
  5687.5  304.38  5692.5  302.92  5710.2  309.59  5730.3  314.67  5750.5  317.34
  5768.1  321.62  5773.1  321.42  5780.7   324.3  5841.2  333.39  5891.6  338.26
#Mann= 6 ,-1 , 0
  3482.2     .05       0  4872.1     .16       0  4992.2     .07       0
  4998.2     .16       0  5091.9     .05       0  5550.4      .1       0
Bank Sta=4965.1,5015.2
XS Rating Curve= 0 ,0
Exp/Cntr=0.3,0.1

Type RM Length L Ch R = 1 ,17105   ,342,342,342
BEGIN DESCRIPTION:
WHEELOCK CREEK 26.0
END DESCRIPTION:
XS GIS Cut Line= 3
      3670449.56     10515560.19      3672849.61     10515360.19
      3673249.63     10515410.19
#Sta/Elev= 30
    2591   326.9  3032.6  310.61  3092.8  304.58  3112.9  300.13  3243.3  284.64
  3255.8  281.24  3376.3  267.96  3474.1  261.66  3644.7  258.03  4235.2  254.38
  4296.8  252.73    4327  254.56  4502.1  253.52  4868.9  256.29  4989.3  255.17
  4992.9  251.57  4996.9  247.58  5006.4  247.55  5009.2  247.05  5012.4  247.55
  5029.6  255.66  5100.1  255.48    5211  266.36  5251.3  274.17    5275  284.75
    5279  288.06  5291.6  290.31  5331.9   304.9    5384  314.07  5402.5  316.29
#Mann= 9 ,-1 , 0
    2591     .05       0  4235.2     .16       0  4296.8     .12       0
  4502.1     .16       0  4992.9     .05       0  5006.4     .03       0
  5012.4     .05       0    5275     .16       0    5384      .1       0
Bank Sta=4989.3,5029.6
XS Rating Curve= 0 ,0
Exp/Cntr=0.3,0.1

Type RM Length L Ch R = 1 ,16763   ,866,866,866
BEGIN DESCRIPTION:
WHEELOCK CREEK 25.0
END DESCRIPTION:
XS GIS Cut Line= 3
      3670549.64     10515660.19      3673018.86     10515670.36
      3673199.57     10515510.22
#Sta/Elev= 30
  2643.5  326.11  3033.5  311.09  3313.5  277.18  3443.5  266.18  3583.5   261.5
  3733.5   262.8  3881.1  259.23  4413.5  252.07  4843.5  252.23  4983.5  254.81
  5003.5  247.32  5010.5  247.19  5013.2  246.69  5016.5  247.19  5023.5     252
  5033.5  255.02  5040.2  254.94  5083.5  253.38  5155.6  260.09  5191.6  268.78
  5198.3  268.02  5226.7  273.75    5234  279.29  5247.6   282.9  5255.1  287.79
    5276  293.29  5282.9  297.35  5290.3  296.32  5297.8  301.19  5354.2  310.62
#Mann= 6 ,-1 , 0
  2643.5     .05       0  3881.1     .16       0  5010.5     .07       0
  5016.5     .16       0  5040.2     .05       0  5282.9      .1       0
Bank Sta=4983.5,5033.5
XS Rating Curve= 0 ,0
Exp/Cntr=0.3,0.1

Type RM Length L Ch R = 1 ,15897   ,684,684,684
BEGIN DESCRIPTION:
WHEELOCK CREEK 24.0
END DESCRIPTION:
XS GIS Cut Line= 3
      3671749.62     10516560.19      3673199.61     10516210.19
      3673249.61     10515460.19
#Sta/Elev= 30
  3479.4  303.49    3572  297.98  3746.9  284.03  3801.2   278.7  3935.3  261.36
  3968.8  256.97  4094.4  251.09  4139.9  250.48  4345.3  250.27    4448  249.82
  4907.3   253.6  4952.7   252.5  4978.1  245.84  4980.8  245.34  4984.1  245.84
  5011.1  248.63  5046.2  248.66  5051.2     251  5072.7  251.71  5081.3  253.34
  5201.5  252.25  5300.5  260.31    5392  268.53  5432.1  268.34  5462.1  276.55
  5472.1   277.1  5512.2  289.31  5552.3  297.17  5662.6  312.31  5722.7   317.6
#Mann= 10 ,-1 , 0
  3479.4     .05       0  3935.3     .16       0  4139.9     .12       0
  4345.3     .16       0    4448     .05       0  4907.3     .16       0
  4978.1     .07       0  4984.1     .16       0  5072.7     .05       0
  5300.5      .1       0
Bank Sta=4952.7,5081.3
XS Rating Curve= 0 ,0
Exp/Cntr=0.3,0.1

Type RM Length L Ch R = 1 ,15213   ,719,719,719
BEGIN DESCRIPTION:
WHEELOCK CREEK 23.0
END DESCRIPTION:
XS GIS Cut Line= 3
      3672349.64     10517460.16      3673649.61     10516360.19
      3673999.61      10515560.2
#Sta/Elev= 30
  3311.6  302.52  3431.8   296.7  3503.3  289.32  3559.8   278.4  3609.9  271.81
  3638.5  265.35  3680.1  260.76  3702.2  261.34    3780  252.55  3829.6  248.12
  3884.6  247.55  4063.4  247.95  4297.6  249.11  4489.9  246.68  4897.9  251.16
  4978.8  251.56  4983.5  244.38  4986.3  243.88  4989.5  244.38  5000.8  244.63
  5011.2  250.23  5023.5  251.34  5179.3  249.89  5365.1  250.08  5447.4  254.17
  5723.1  273.01  5750.9  274.16  5797.7  280.58  5855.4  301.73  5887.7  308.69
#Mann= 12 ,-1 , 0
  3311.6     .05       0  3559.8     .16       0    3780     .05       0
  3884.6     .07       0  4063.4     .05       0  4897.9     .16       0
  4983.5     .07       0  4989.5     .16       0  5179.3     .05       0
  5365.1     .16       0  5447.4     .05       0  5723.1     .16       0
Bank Sta=4978.8,5023.5
XS Rating Curve= 0 ,0
Exp/Cntr=0.3,0.1

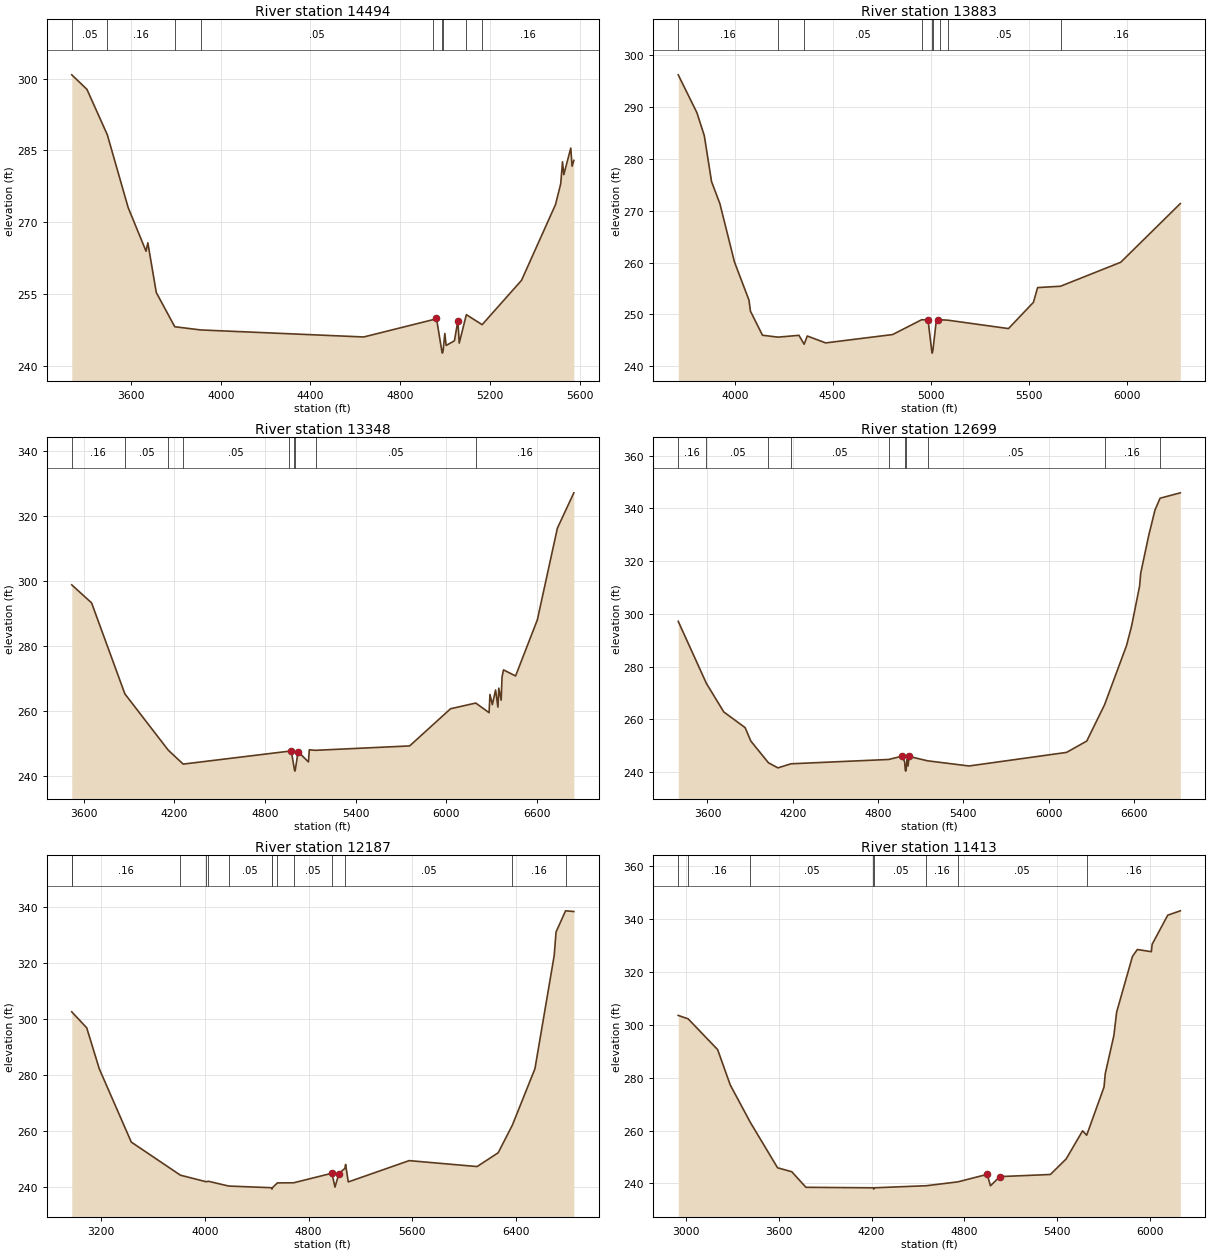
Type RM Length L Ch R = 1 ,14494   ,611,611,611
BEGIN DESCRIPTION:
WHEELOCK CREEK 22.0
END DESCRIPTION:
XS GIS Cut Line= 3
       3672449.6     10517510.19      3673899.61     10516710.19
      3674399.65     10516410.17
#Sta/Elev= 30
  3335.5  300.82  3403.1  297.79  3494.1  288.28  3586.8  273.09  3666.7  263.93
  3674.8  265.68  3712.4   255.3  3794.8  248.13  3910.2  247.46  4637.5  245.99
  4948.7  249.63  4961.8  249.96  4985.7  243.11  4988.5  242.61  4991.7  243.11
  4999.3  246.72  5005.2  244.21  5042.1  245.19  5057.6   249.4  5063.5   244.7
  5095.3  250.66  5165.7  248.56  5341.4  257.84    5493  273.69  5516.3  278.06
  5524.1  282.63    5530  279.95    5561  285.51  5566.9  281.71  5574.7  282.92
#Mann= 9 ,-1 , 0
  3335.5     .05       0  3494.1     .16       0  3794.8     .12       0
  3910.2     .05       0  4948.7     .16       0  4985.7     .07       0
  4991.7     .16       0  5095.3     .05       0  5165.7     .16       0
Bank Sta=4961.8,5057.6
XS Rating Curve= 0 ,0
Exp/Cntr=0.3,0.1

Type RM Length L Ch R = 1 ,13883   ,535,535,535
BEGIN DESCRIPTION:
WHEELOCK CREEK 21.0
END DESCRIPTION:
XS GIS Cut Line= 3
      3672699.62     10517660.19      3673906.02     10517227.65
       3674799.6      10516310.2
#Sta/Elev= 30
  3711.9  296.18  3807.5  288.86    3845  284.44  3881.9  275.61  3924.4  271.36
  3998.7  260.14  4073.1  252.75  4080.3  250.65  4141.8     246  4220.9  245.63
    4328  245.98  4354.4  244.26  4370.5  245.85  4464.1  244.52  4806.1  246.13
  4954.4  248.99  4986.7  248.93  5005.4  243.05  5008.1  242.55  5011.4  243.05
  5029.7  249.05  5036.6  248.97  5046.8  248.98  5087.5   248.9  5397.3  247.28
  5524.6  252.34  5545.9  255.18  5662.8  255.44  5970.1  260.06  6274.2  271.37
#Mann= 9 ,-1 , 0
  3711.9     .16       0  4220.9     .12       0  4354.4     .05       0
  4954.4     .16       0  5005.4     .07       0  5011.4     .16       0
  5046.8     .12       0  5087.5     .05       0  5662.8     .16       0
Bank Sta=4986.7,5036.6
XS Rating Curve= 0 ,0
Exp/Cntr=0.3,0.1

Type RM Length L Ch R = 1 ,13348   ,649,649,649
BEGIN DESCRIPTION:
WHEELOCK CREEK 20.0
END DESCRIPTION:
XS GIS Cut Line= 3
      3672699.64     10517760.18      3674149.61     10517560.19
      3675099.62     10515960.16
#Sta/Elev= 30
  3520.3  298.81  3651.5  293.29    3872  265.35  4159.9  248.03  4258.2  243.79
  4960.6  247.76  4973.9  247.78  4994.6  242.13  4997.4  241.63  5000.6  242.13
    5019  247.59  5087.3  244.45  5093.1  248.18  5134.3  248.02  5757.5  249.37
  6028.4  260.78  6195.3  262.53  6283.6  259.58  6289.4  265.17  6305.1  262.05
  6326.5  266.54  6342.1  261.28  6347.9  267.12  6363.5  263.41  6369.3  270.53
  6379.1  272.71    6459  270.85  6603.1  288.07  6735.7  316.21  6844.8  327.07
#Mann= 9 ,-1 , 0
  3520.3     .16       0    3872     .05       0  4159.9     .16       0
  4258.2     .05       0  4960.6     .07       0  4994.6     .07       0
  5000.6     .07       0  5134.3     .05       0  6195.3     .16       0
Bank Sta=4973.9,5019
XS Rating Curve= 0 ,0
Exp/Cntr=0.3,0.1

Type RM Length L Ch R = 1 ,12699   ,512,512,512
BEGIN DESCRIPTION:
WHEELOCK CREEK 19.0
END DESCRIPTION:
XS GIS Cut Line= 3
       3672799.6     10517810.19      3674399.61     10517910.19
      3675949.64     10516760.16
#Sta/Elev= 30
  3394.2  297.17  3592.4  273.66  3714.8  262.84  3865.1  256.89  3905.2   251.8
    4029  243.58  4095.6  241.64  4187.6  243.19  4875.1  244.83  4967.3  246.06
  4987.3  244.02  4991.8  240.91  4994.6  240.41  4997.8  240.91  5004.6   244.8
  5010.9  242.37  5019.3  245.98  5148.9  244.32  5440.7  242.36  6127.2  247.51
    6269  251.81  6393.9  265.51  6548.7  287.96  6584.1  295.28    6641  310.56
  6648.8  315.43  6705.1  329.71    6749  339.32  6784.9  343.83  6927.4  345.87
#Mann= 10 ,-1 , 0
  3394.2     .16       0  3592.4     .05       0    4029     .16       0
  4187.6     .05       0  4875.1     .12       0  4991.8     .07       0
  4997.8     .12       0  5148.9     .05       0  6393.9     .16       0
  6784.9     .05       0
Bank Sta=4967.3,5019.3
XS Rating Curve= 0 ,0
Exp/Cntr=0.3,0.1

Type RM Length L Ch R = 1 ,12187   ,774,774,774
BEGIN DESCRIPTION:
WHEELOCK CREEK 18.0
END DESCRIPTION:
XS GIS Cut Line= 4
      3672812.24     10518889.12       3674333.1     10518295.36
      3674973.72     10518154.74       3676124.7     10517071.47
#Sta/Elev= 30
  2974.8  302.51  2976.6  302.39  3090.1   296.8  3186.7  282.21  3433.6   256.1
  3812.3  244.31  4009.9  241.99  4027.8  242.15  4183.6  240.45  4514.8  239.85
  4517.6  239.35  4520.8  239.85  4559.3  241.57  4684.6  241.61  4977.2  244.98
  4979.5  245.02  5003.2  240.07  5033.9  244.91  5079.3  246.73  5085.1  248.14
  5105.5  241.91  5574.7   249.5  6098.3  247.39  6260.9   252.3  6370.6  262.19
  6544.2  282.24  6692.6  322.57  6706.8  330.93  6780.2  338.46  6843.9  338.22
#Mann= 14 ,-1 , 0
  2974.8     .05       0  2976.6     .16       0  3812.3     .12       0
  4009.9     .05       0  4027.8     .12       0  4183.6     .05       0
  4514.8     .07       0  4520.8     .05       0  4559.3     .12       0
  4684.6     .05       0  4977.2     .12       0  5079.3     .05       0
  6370.6     .16       0  6780.2     .05       0
Bank Sta=4979.5,5033.9
XS Rating Curve= 0 ,0
Exp/Cntr=0.3,0.1

Type RM Length L Ch R = 1 ,11413   ,591,591,591
BEGIN DESCRIPTION:
WHEELOCK CREEK 17.0
END DESCRIPTION:
XS GIS Cut Line= 3
      3672899.57      10519110.2      3674899.61     10518710.19
      3676083.09     10518951.61
#Sta/Elev= 30
  2949.2  303.48  3013.4  302.18  3204.2  290.56  3285.8   277.2  3416.1  263.02
  3591.7  245.93  3683.5  244.45  3775.3  238.56  4210.8  238.37  4213.5  237.87
  4216.8  238.37  4554.9  239.16  4758.1  240.62  4948.1  243.45  4968.5  239.12
  5029.7   242.6  5356.3   243.4  5458.3  249.27  5564.8   259.9    5591  258.22
  5703.3  276.42  5711.3  281.49    5767   295.9  5784.9  304.72    5887  325.74
  5918.6  328.37  6009.4  327.55  6014.5  330.35  6115.6  341.35  6196.7  342.98
#Mann= 8 ,-1 , 0
  2949.2     .05       0  3013.4     .16       0  3416.1     .05       0
  4210.8     .03       0  4216.8     .05       0  4554.9     .16       0
  4758.1     .05       0    5591     .16       0
Bank Sta=4948.1,5029.7
XS Rating Curve= 0 ,0
Exp/Cntr=0.3,0.1

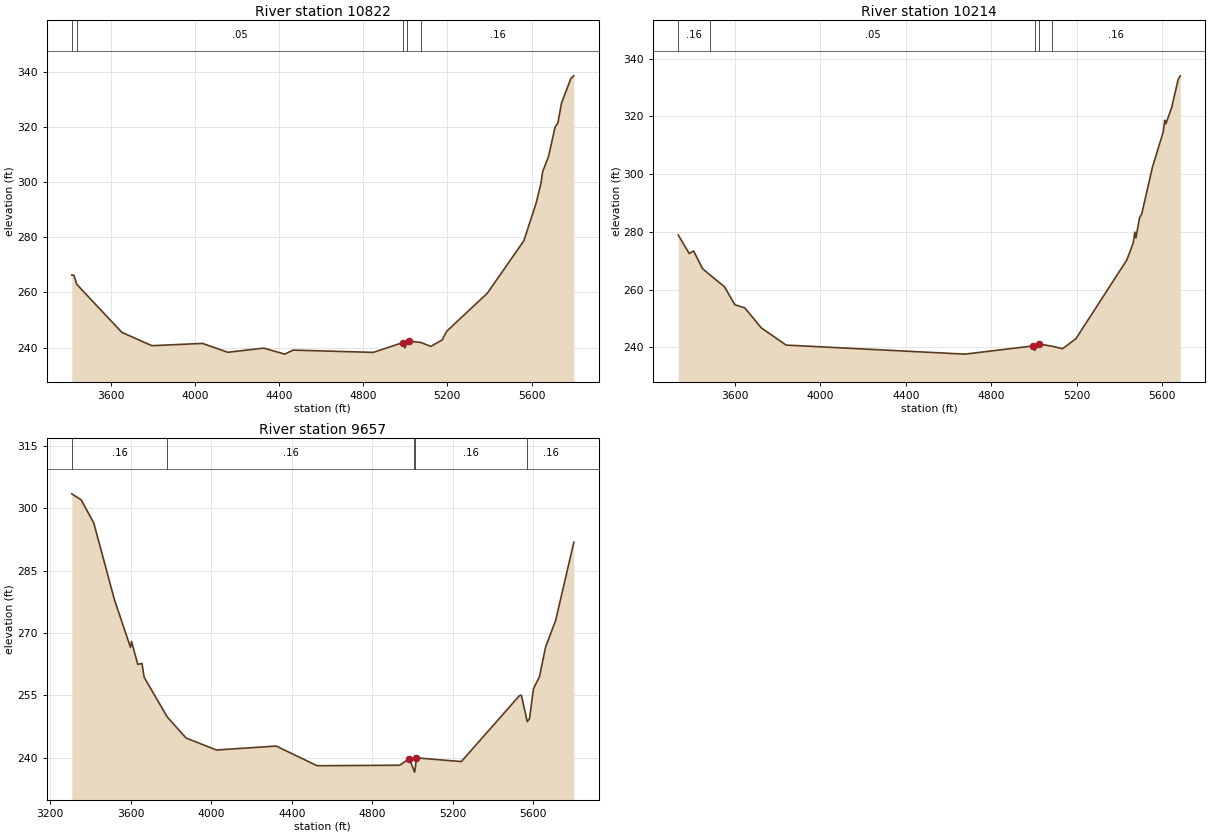
Type RM Length L Ch R = 1 ,10822   ,608,608,608
BEGIN DESCRIPTION:
WHEELOCK CREEK 16.0
END DESCRIPTION:
XS GIS Cut Line= 3
      3673349.64     10519060.19      3674949.61     10519160.19
      3675649.59     10519510.18
#Sta/Elev= 30
  3415.4  266.26  3425.4  266.24  3439.5  262.89  3653.3  245.52  3796.1  240.68
  4036.6  241.51  4156.8  238.29  4327.1   239.8  4427.1  237.62  4467.4  239.08
  4848.2  238.25  4988.4   241.8  4998.5  239.88  5008.5  241.88    5016  242.38
  5074.9  241.83  5121.9  240.42    5175  242.74  5197.4  245.96  5390.2  259.72
  5563.5  278.72  5622.2  292.45  5644.6  299.46    5653  303.79  5680.9  309.31
  5711.7  319.87  5725.7  321.51  5742.4  328.63  5787.1  337.58  5801.1  338.53
#Mann= 5 ,-1 , 0
  3415.4     .16       0  3439.5     .05       0  4988.4     .03       0
  5008.5     .05       0  5074.9     .16       0
Bank Sta=4988.4,5016
XS Rating Curve= 0 ,0
Exp/Cntr=0.3,0.1

Type RM Length L Ch R = 1 ,10214   ,557,557,557
BEGIN DESCRIPTION:
WHEELOCK CREEK 15.0
END DESCRIPTION:
XS GIS Cut Line= 3
      3673299.61     10519210.19      3674899.61     10519610.19
      3675599.59     10519560.19
#Sta/Elev= 30
  3334.6  278.91  3386.1  272.48  3406.7  273.38    3448  267.28  3483.1  265.08
  3551.1  260.98    3600  254.72  3646.4  253.64  3723.7  246.71  3839.7  240.76
  4676.9  237.62  4993.9  240.44  5003.9  238.95  5023.9  241.12  5084.1  240.37
  5134.2  239.51  5196.9  242.98    5435  270.24  5465.1  276.14  5472.6  279.89
  5477.6  277.92  5495.1   284.9  5505.2  286.29  5555.3  302.47  5605.4  314.56
  5612.9  318.69    5618  317.42  5645.5  323.16  5675.6  332.86  5685.6  334.07
#Mann= 5 ,-1 , 0
  3334.6     .16       0  3483.1     .05       0  5003.9     .03       0
  5023.9     .05       0  5084.1     .16       0
Bank Sta=4993.9,5023.9
XS Rating Curve= 0 ,0
Exp/Cntr=0.3,0.1

Type RM Length L Ch R = 1 ,9657    ,573,573,573
BEGIN DESCRIPTION:
WHEELOCK CREEK 14.0
END DESCRIPTION:
XS GIS Cut Line= 3
      3673049.65      10519410.2      3674649.61     10519960.19
       3675449.6     10520010.19
#Sta/Elev= 30
  3307.3  303.46  3354.1  302.01  3416.6  296.45  3518.7  278.09  3598.8  266.55
  3604.1  267.95  3635.3  262.45    3656  262.69  3666.8  259.36  3781.7   249.8
  3874.7  244.76  4025.6  241.87  4322.4  242.82  4525.5  238.09  4935.7  238.21
  4983.5  239.79  5006.2  237.05  5008.9  236.55  5012.2  237.05  5019.2  239.98
  5242.1  239.09  5530.2  254.92  5540.2  255.05  5569.3   248.7  5580.3  249.35
  5600.3  256.61  5630.4  259.55  5660.4  266.63  5710.5  273.05  5800.7  291.85
#Mann= 5 ,-1 , 0
  3307.3     .16       0  3781.7     .16       0  5006.2     .03       0
  5012.2     .16       0  5569.3     .16       0
Bank Sta=4983.5,5019.2
XS Rating Curve= 0 ,0
Exp/Cntr=0.3,0.1