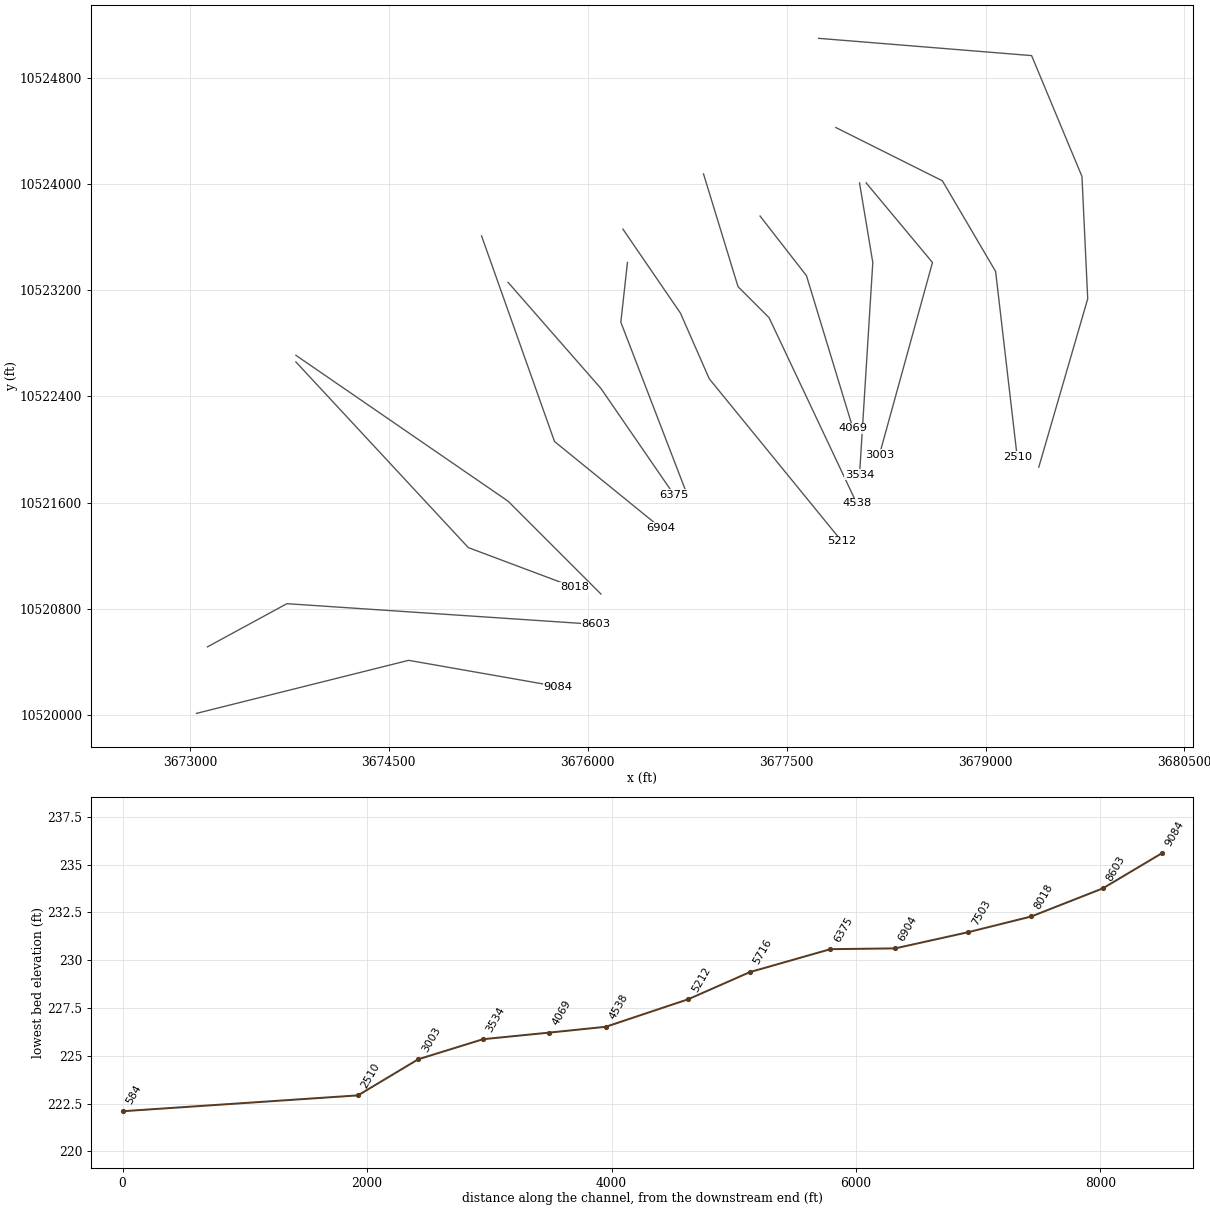
HEC-RAS study WHEELOCK CREEK.prj: WHEELOCK CREEK Base Level Engineering

--- WHEELOCK CREEK.g01 (geometry) --- (continued)

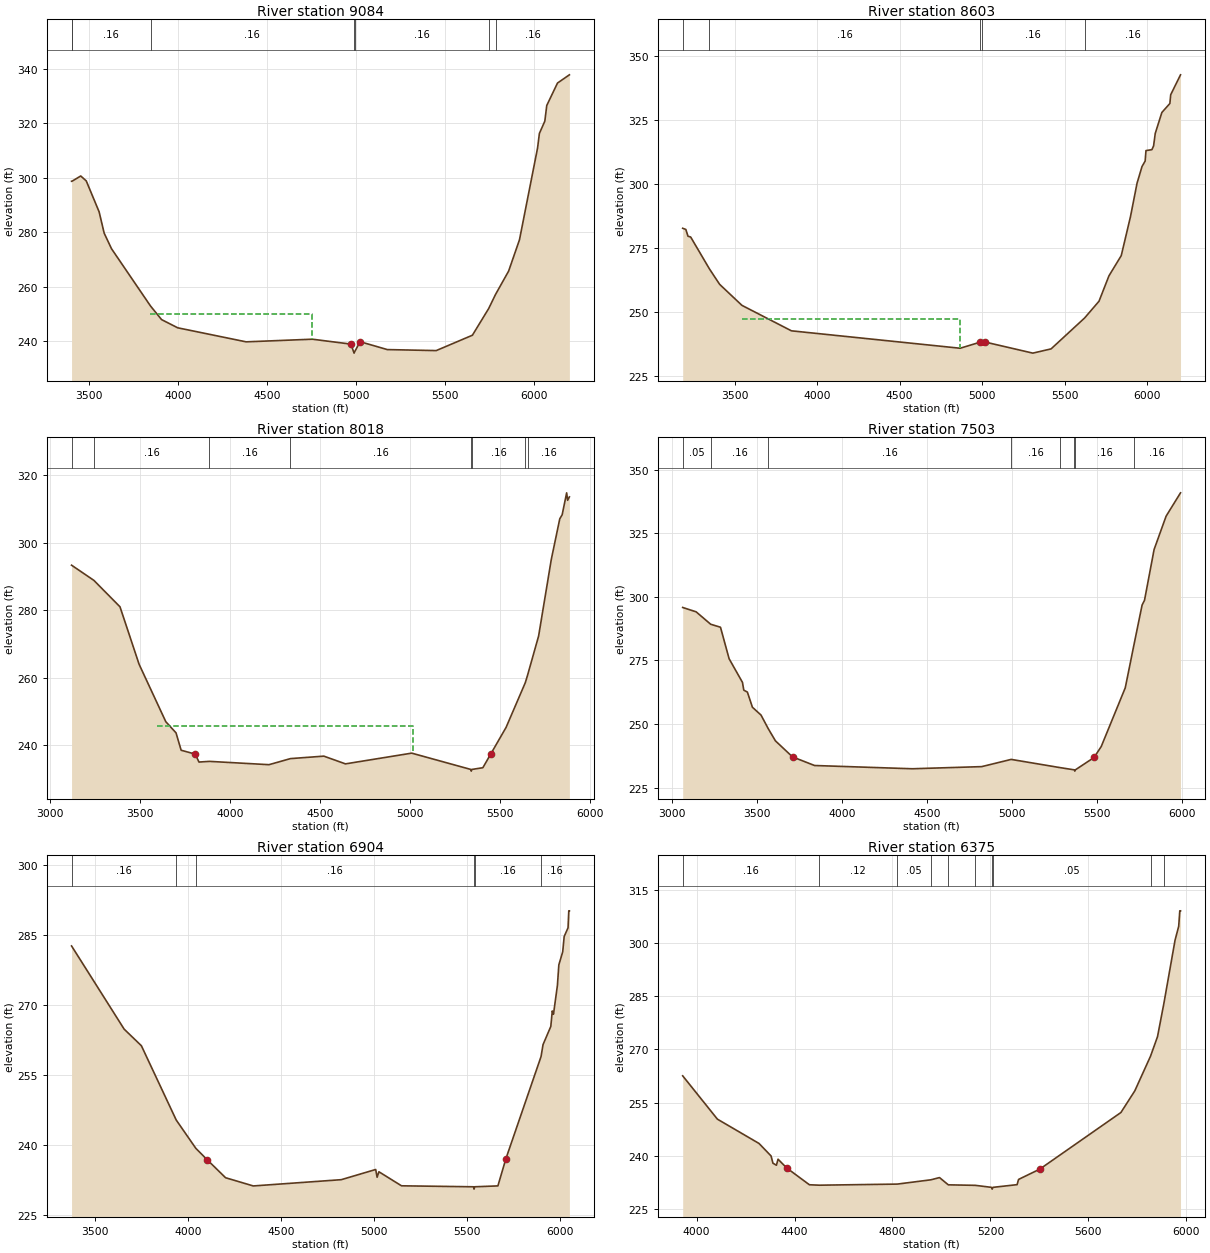
Type RM Length L Ch R = 1 ,9084    ,481,481,481
BEGIN DESCRIPTION:
WHEELOCK CREEK 13.0
END DESCRIPTION:
XS GIS Cut Line= 3
      3673049.65      10520010.2      3674649.61     10520410.19
      3675775.28     10520212.49
#Sta/Elev= 30
    3404  298.67  3407.1  298.71  3455.5  300.61  3486.4  298.81  3558.6  287.46
  3586.9  279.63  3628.1  273.91  3846.8  252.89    3909  247.89  3999.2  244.89
  4383.2  239.73  4754.3   240.7  4970.7   238.9  4985.8  236.09  4988.5  235.59
  4991.8  236.09  5022.3  239.78    5175  236.89  5449.2  236.52  5652.2  242.16
  5743.6  251.97  5781.7  257.11  5855.3   265.7  5916.2  277.19  6017.7  310.91
  6027.9  316.23  6058.3  320.73  6069.2  326.49  6129.4  334.72  6196.1  337.74
#Mann= 7 ,-1 , 0
    3404     .05       0  3407.1     .16       0  3846.8     .16       0
  4985.8     .08       0  4991.8     .16       0  5743.6     .05       0
  5781.7     .16       0
#XS Ineff= 1 ,-1
 3843.18    4750  249.89
Permanent Ineff=
       F
Bank Sta=4970.7,5022.3
XS Rating Curve= 0 ,0
Exp/Cntr=0.3,0.1

Type RM Length L Ch R = 1 ,8603    ,585,585,585
BEGIN DESCRIPTION:
WHEELOCK CREEK 12.0
END DESCRIPTION:
XS GIS Cut Line= 3
      3673132.75     10520511.82      3673731.75     10520837.36
      3676062.48     10520681.11
#Sta/Elev= 30
  3185.4  282.62  3204.6  282.16  3217.5  279.51  3233.7  279.21  3347.4  266.74
  3409.4  260.68  3544.4  252.46  3844.6  242.49  4867.2  235.67  4987.5  238.03
  4997.5  237.19  5017.6  238.11    5308  233.76  5418.5  235.42  5621.7  247.51
  5709.1  254.08  5769.3  264.01  5843.8  271.92  5899.6  287.13  5939.6  300.27
  5969.7   306.8  5988.7  308.94  5993.7  313.03  6029.8  313.39  6039.9  314.89
  6049.9  319.76    6090  327.94  6138.6  331.47  6143.6   334.9  6203.1  342.68
#Mann= 5 ,-1 , 0
  3185.4     .16       0  3347.4     .16       0  4987.5     .08       0
  4997.5     .16       0  5621.7     .16       0
#XS Ineff= 1 ,-1
  3542.9 4867.33  247.16
Permanent Ineff=
       F
Bank Sta=4987.5,5017.6
XS Rating Curve= 0 ,0
Exp/Cntr=0.3,0.1

Type RM Length L Ch R = 1 ,8018    ,515,515,515
BEGIN DESCRIPTION:
WHEELOCK CREEK 11.0
END DESCRIPTION:
XS GIS Cut Line= 3
      3673799.62     10522660.17      3675099.61     10521260.19
      3675899.63     10520960.18
#Sta/Elev= 30
  3121.4  293.31  3245.4  288.81  3390.4  280.98  3496.4  263.97  3644.9  246.93
  3701.6  243.63    3730  238.48  3807.6  237.34  3829.2  234.98  3887.4  235.18
  4218.1   234.2  4337.2     236  4522.5  236.73  4642.7  234.44  5010.6  237.62
  5338.6  232.79  5341.3  232.29  5344.6  232.79  5405.7   233.3  5449.3  237.34
  5534.7  245.25  5641.3  258.48  5653.7  260.65  5715.4  272.32  5785.7  294.99
  5832.9  307.05  5846.2  308.25  5871.1  314.75  5876.5  312.53  5886.3  313.54
#Mann= 8 ,-1 , 0
  3121.4     .05       0  3245.4     .16       0  3887.4     .16       0
  4337.2     .16       0  5338.6     .08       0  5344.6     .16       0
  5641.3     .12       0  5653.7     .16       0
#XS Ineff= 1 ,-1
 3594.89 5016.48  245.53
Permanent Ineff=
       F
Bank Sta=3807.6,5449.3
XS Rating Curve= 0 ,0
Exp/Cntr=0.3,0.1

Type RM Length L Ch R = 1 ,7503    ,599,599,599
BEGIN DESCRIPTION:
WHEELOCK CREEK 10.0
END DESCRIPTION:
XS GIS Cut Line= 3
      3673799.62     10522710.18      3675399.61     10521610.19
      3676099.62     10520910.18
#Sta/Elev= 30
  3061.5  295.82  3140.6  294.11  3226.3  289.23  3284.1  288.05  3334.8  275.67
  3413.4  266.38  3421.4   263.3  3442.4  262.56  3472.2  256.58  3522.6  253.53
  3564.8  248.23  3607.6  243.38  3708.2  237.07  3838.1  233.68  4413.2   232.4
  4822.5  233.24    4996  236.08    5281  232.88  5367.8  231.97  5370.6  231.47
  5373.8  231.97    5484  236.83  5526.4  241.17  5667.8  264.25  5717.1  280.55
  5766.8  296.78    5781  298.64  5837.5  318.61  5908.2  331.72  5993.1   340.9
#Mann= 8 ,-1 , 0
  3061.5     .05       0  3226.3     .16       0  3564.8     .16       0
    4996     .16       0    5281     .16       0  5367.8     .08       0
  5373.8     .16       0  5717.1     .16       0
Bank Sta=3708.2,5484
XS Rating Curve= 0 ,0
Exp/Cntr=0.3,0.1

Type RM Length L Ch R = 1 ,6904    ,529,529,529
BEGIN DESCRIPTION:
WHEELOCK CREEK 9.0
END DESCRIPTION:
XS GIS Cut Line= 3
       3675199.6     10523610.22      3675749.61     10522060.19
      3676549.61     10521410.19
#Sta/Elev= 30
  3375.4  282.64  3658.1  264.84  3750.7  261.29  3937.8  245.41  4043.4  239.34
  4105.2  236.87  4203.1  233.06  4352.1   231.3  4824.8  232.64    5010  234.82
  5017.5  233.16  5027.3  234.33  5148.7  231.33  5535.7  231.12  5538.5  230.62
  5541.7  231.12  5666.6  231.31  5709.7  237.12  5898.6  258.98  5909.2  261.52
    5951  265.42    5959  268.73  5965.4  268.03  5986.5  274.19  5994.2  278.59
    6015  281.38  6022.9  284.66  6043.7  286.52  6047.7  290.15  6050.9  290.15
#Mann= 6 ,-1 , 0
  3375.4     .16       0  3937.8     .16       0  4043.4     .16       0
  5535.7     .08       0  5541.7     .16       0  5898.6     .16       0
Bank Sta=4105.2,5709.7
XS Rating Curve= 0 ,0
Exp/Cntr=0.3,0.1

Type RM Length L Ch R = 1 ,6375    ,659,659,659
BEGIN DESCRIPTION:
WHEELOCK CREEK 8.0
END DESCRIPTION:
XS GIS Cut Line= 3
      3675399.63     10523260.16      3676099.61     10522460.19
      3676649.61     10521660.19
#Sta/Elev= 30
  3942.9  262.55  4084.8  250.32  4254.7  243.47    4304  239.93  4311.6   237.9
  4325.8  237.32  4332.5  239.02  4368.1  236.54  4460.6  231.81  4501.4  231.69
  4819.4     232    4957  233.21  4992.1  233.84    5028  231.79  5138.2  231.65
  5204.5  231.08  5207.2  230.58  5210.5  231.08    5309  231.84  5315.1  233.32
  5401.7  236.22  5733.2   252.2    5790  258.32  5854.2   268.1  5882.7   273.6
  5908.8  283.01  5954.4  300.84  5969.3  304.76  5973.7  309.11  5976.7  309.11
#Mann= 10 ,-1 , 0
  3942.9     .16       0  4501.4     .12       0  4819.4     .05       0
    4957     .16       0    5028     .12       0  5138.2     .05       0
  5204.5     .07       0  5210.5     .05       0  5854.2     .12       0
  5908.8     .16       0
Bank Sta=4368.1,5401.7
XS Rating Curve= 0 ,0
Exp/Cntr=0.3,0.1

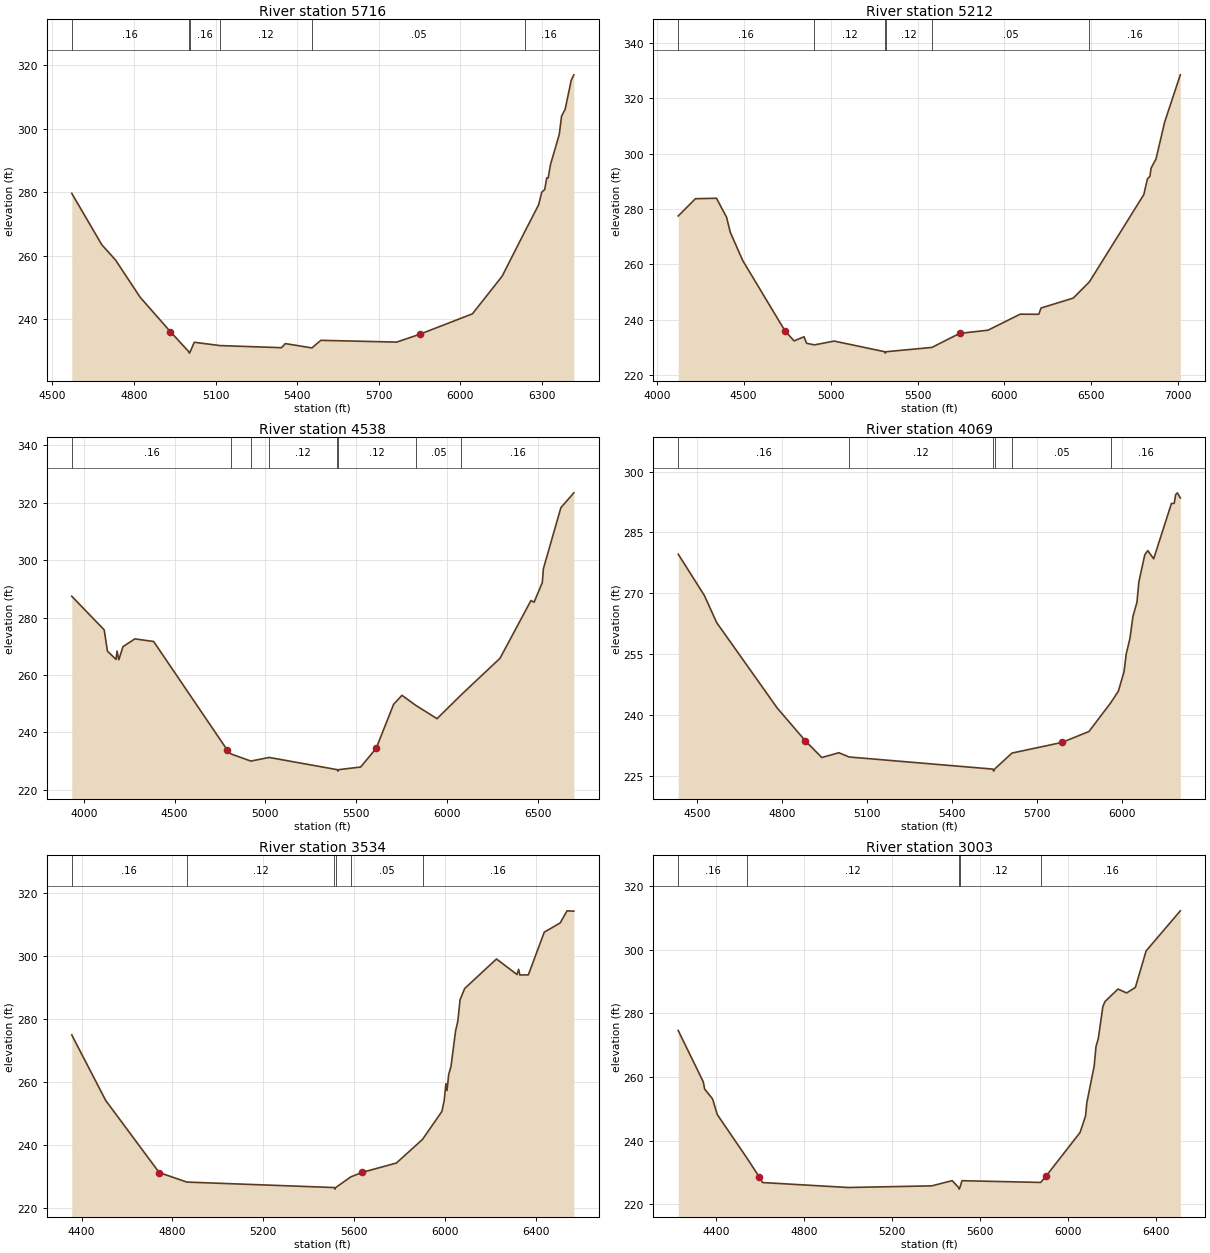
Type RM Length L Ch R = 1 ,5716    ,504,504,504
BEGIN DESCRIPTION:
WHEELOCK CREEK 7.0
END DESCRIPTION:
XS GIS Cut Line= 3
      3676299.61     10523410.19      3676249.61     10522960.19
       3676749.6      10521660.2
#Sta/Elev= 30
  4571.2  279.67  4681.9  263.46  4732.2  258.68  4822.7  246.95  4933.4  236.17
  5000.9  229.88  5003.6  229.38  5006.9  229.88  5021.5   232.8  5115.4  231.76
  5342.2  231.09  5356.1  232.38    5454  231.02  5486.8  233.41  5765.4  232.85
    5850  235.31    6044  241.75  6153.2  253.59  6236.8  267.67  6287.2  276.04
    6299  280.07  6309.7  280.87  6317.2  284.53  6322.5  284.52  6331.1  288.77
  6363.2  298.23  6371.8  304.01  6384.7   306.1  6407.2  315.26  6416.8  316.98
#Mann= 6 ,-1 , 0
  4571.2     .16       0  5000.9     .07       0  5006.9     .16       0
  5115.4     .12       0    5454     .05       0  6236.8     .16       0
Bank Sta=4933.4,5850
XS Rating Curve= 0 ,0
Exp/Cntr=0.3,0.1

Type RM Length L Ch R = 1 ,5212    ,674,674,674
BEGIN DESCRIPTION:
WHEELOCK CREEK 6.0
END DESCRIPTION:
XS GIS Cut Line= 4
      3676265.37     10523661.72      3676699.42       10523028.
      3676916.43     10522533.21      3677914.67     10521309.28
#Sta/Elev= 30
  4123.8  277.49  4222.6  283.72  4343.8  283.89    4402  277.01    4423  271.62
  4494.7  261.41  4739.8   235.8  4790.6  232.38  4847.4  233.86  4862.3  231.51
  4907.5  230.94  5020.6  232.31  5312.4  228.46  5315.1  227.96  5318.4  228.46
  5582.8  230.02  5742.6  235.09  5905.5  236.24  6090.8  242.03  6197.5  241.99
  6210.7  244.25    6396  247.84  6488.7  253.69  6801.7  285.21  6822.5   290.9
  6836.8  291.78  6843.3  294.73    6872  298.12  6921.6  311.41  7011.6  328.46
#Mann= 6 ,-1 , 0
  4123.8     .16       0  4907.5     .12       0  5312.4     .07       0
  5318.4     .12       0  5582.8     .05       0  6488.7     .16       0
Bank Sta=4739.8,5742.6
XS Rating Curve= 0 ,0
Exp/Cntr=0.3,0.1

Type RM Length L Ch R = 1 ,4538    ,469,469,469
BEGIN DESCRIPTION:
WHEELOCK CREEK 5.0
END DESCRIPTION:
XS GIS Cut Line= 4
      3676873.04      10524078.3      3677133.45     10523227.65
      3677367.82     10522993.28      3678027.53     10521595.73
#Sta/Elev= 30
  3933.1  287.44  4111.7  275.74  4129.8   268.3  4177.2  265.43  4182.5  268.35
  4192.6  265.34  4215.2  269.88  4280.8  272.59  4384.3  271.68    4788  234.05
  4810.7   232.5    4920  230.02  5020.9  231.29  5396.8  227.02  5399.6  226.52
  5402.8  227.02  5524.8  227.95  5610.3  234.44  5706.9  249.85  5752.5  252.93
  5829.6   249.4  5945.7  244.79  6079.3  253.12  6292.8  265.83  6463.2  285.94
  6480.5  285.37    6526  292.24  6531.6     297  6628.3  318.31  6699.6  323.47
#Mann= 8 ,-1 , 0
  3933.1     .16       0  4810.7     .12       0    4920     .16       0
  5020.9     .12       0  5396.8     .07       0  5402.8     .12       0
  5829.6     .05       0  6079.3     .16       0
Bank Sta=4788,5610.3
XS Rating Curve= 0 ,0
Exp/Cntr=0.3,0.1

Type RM Length L Ch R = 1 ,4069    ,535,535,535
BEGIN DESCRIPTION:
WHEELOCK CREEK 4.0
END DESCRIPTION:
XS GIS Cut Line= 3
      3677299.63     10523760.16      3677649.61     10523310.19
       3677999.6     10522160.22
#Sta/Elev= 30
  4433.2  279.64  4525.5  269.46  4568.9  262.79  4782.5  241.76    4882  233.66
  4939.9  229.56  5000.1  230.74  5036.8  229.69  5543.8  226.71  5546.6  226.21
  5549.8  226.71  5611.2  230.66  5787.2  233.27  5882.8  235.96  5959.4  243.01
  5986.6   245.9  6006.7   250.7  6014.2  254.99  6027.6  258.92  6038.1   264.3
  6052.3  267.81    6059  272.82  6079.9  279.48  6090.4  280.52  6111.3  278.51
    6174  292.13  6183.7  292.15  6188.9   294.3  6194.9  294.75  6205.3  293.49
#Mann= 6 ,-1 , 0
  4433.2     .16       0  5036.8     .12       0  5543.8     .07       0
  5549.8     .12       0  5611.2     .05       0  5959.4     .16       0
Bank Sta=4882,5787.2
XS Rating Curve= 0 ,0
Exp/Cntr=0.3,0.1

Type RM Length L Ch R = 1 ,3534    ,531,531,531
BEGIN DESCRIPTION:
WHEELOCK CREEK 3.0
END DESCRIPTION:
XS GIS Cut Line= 3
      3678049.61     10524010.17      3678149.61     10523410.19
      3678049.61     10521810.16
#Sta/Elev= 30
  4356.4  274.84  4505.9  254.03  4741.6  231.12  4863.5  228.11  5512.7  226.37
  5515.5  225.87  5518.7  226.37  5585.7  229.77    5636   231.2  5786.3  234.16
  5901.2  241.66  5986.6  250.54  5996.7  253.97  6004.2  259.35  6009.2  257.18
  6016.7  262.35  6026.7  264.81  6046.8  276.08  6056.8  279.23  6066.8  286.02
  6086.8  289.57  6227.1  298.96  6317.3  294.03  6324.8  295.66  6329.8  293.87
  6367.4  293.91  6437.5  307.46  6507.7  310.41  6537.7  314.25  6567.8  314.14
#Mann= 6 ,-1 , 0
  4356.4     .16       0  4863.5     .12       0  5512.7     .07       0
  5518.7     .12       0  5585.7     .05       0  5901.2     .16       0
Bank Sta=4741.6,5636
XS Rating Curve= 0 ,0
Exp/Cntr=0.3,0.1

Type RM Length L Ch R = 1 ,3003    ,493,493,493
BEGIN DESCRIPTION:
WHEELOCK CREEK 2.0
END DESCRIPTION:
XS GIS Cut Line= 3
      3678099.58     10524010.22      3678599.61     10523410.19
      3678199.62     10521960.21
#Sta/Elev= 30
  4226.5  274.63  4340.4  258.53  4346.9  256.23  4382.7  253.17  4404.2  248.24
  4538.4  234.66  4595.6  228.62  4609.9  226.89  5000.4  225.33    5381  225.85
  5473.4  227.49  5502.5  225.32  5505.2  224.82  5508.5  225.32  5518.1  227.47
  5876.2  226.92  5899.7  228.82  6055.3   242.6  6080.3  247.76  6086.4  252.02
  6119.8  263.52  6127.9  269.58  6138.3  272.06  6159.4  282.25  6169.4  283.77
  6228.1  287.65  6267.6  286.43  6307.2  288.17  6356.1  299.63  6511.7  312.22
#Mann= 5 ,-1 , 0
  4226.5     .16       0  4538.4     .12       0  5502.5     .07       0
  5508.5     .12       0  5876.2     .16       0
Bank Sta=4595.6,5899.7
XS Rating Curve= 0 ,0
Exp/Cntr=0.3,0.1

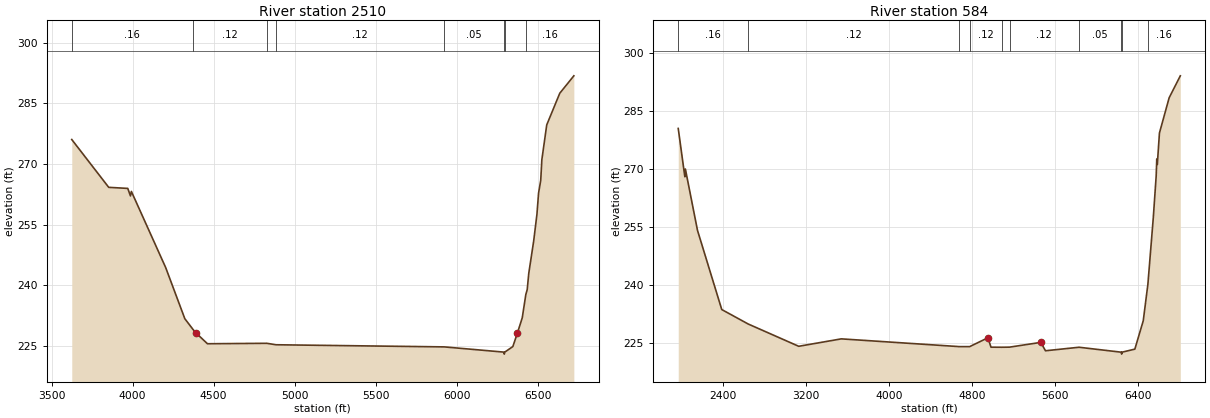
Type RM Length L Ch R = 1 ,2510    ,1926,1926,1926
BEGIN DESCRIPTION:
Mapping XS 390d2da1
END DESCRIPTION:
XS GIS Cut Line= 4
      3677871.37     10524427.62      3678674.32     10524026.15
      3679075.79     10523342.55      3679238.42     10521943.97
#Sta/Elev= 30
  3624.4  276.06  3852.5  264.22  3969.9  263.96  3986.7   262.1  3992.3  263.21
  4203.8  244.38  4322.1   231.7  4371.4  229.11  4389.2  228.24  4461.9   225.5
  4828.3  225.61  4884.5  225.25  5923.4  224.72  6290.8  223.43  6293.6  222.93
  6296.8  223.43  6346.4   224.8  6374.3  228.11  6404.5  231.92  6426.7  237.72
    6435  238.86  6444.8  242.95    6475  250.91  6495.2  257.57  6505.2  262.79
  6518.5  265.93  6525.4  271.04  6555.6  279.68  6636.1  287.52  6722.9  291.83
#Mann= 8 ,-1 , 0
  3624.4     .16       0  4371.4     .12       0  4828.3     .07       0
  4884.5     .12       0  5923.4     .05       0  6290.8     .07       0
  6296.8     .05       0  6426.7     .16       0
Bank Sta=4389.2,6374.3
XS Rating Curve= 0 ,0
Exp/Cntr=0.3,0.1

Type RM Length L Ch R = 1 ,584     ,0,0,0
BEGIN DESCRIPTION:
WHEELOCK CREEK 1.0
END DESCRIPTION:
XS GIS Cut Line= 5
      3677741.13     10525100.37      3679347.06     10524970.16
      3679726.83      10524058.7      3679770.24     10523136.39
      3679401.31     10521866.85
#Sta/Elev= 30
  1966.1  280.52    2030     268    2035  270.02    2152  254.13    2386  233.64
  2641.7  229.89  3128.4  224.13  3539.7  226.05  4679.7  224.04  4777.7  224.04
  4953.7  226.33  4983.7   223.9  5087.1  223.88  5163.2  223.91  5464.2  225.14
  5509.2  222.97  5833.1  223.88  6241.3   222.6    6244   222.1  6247.3   222.6
  6371.4  223.39  6452.6  230.74  6497.3  240.19  6549.5  257.43  6577.5  268.31
    6583  272.61  6588.2  271.18  6608.8  279.34  6702.5  288.46  6810.1  294.14
#Mann= 10 ,-1 , 0
  1966.1     .16       0  2641.7     .12       0  4679.7     .07       0
  4777.7     .12       0  5087.1     .05       0  5163.2     .12       0
  5833.1     .05       0  6241.3     .07       0  6247.3     .05       0
  6497.3     .16       0
Bank Sta=4953.7,5464.2
XS Rating Curve= 0 ,0
Exp/Cntr=0.3,0.1

Chan Stop Cuts=-1
Use User Specified Reach Order=0
Composite Channel Slope=5