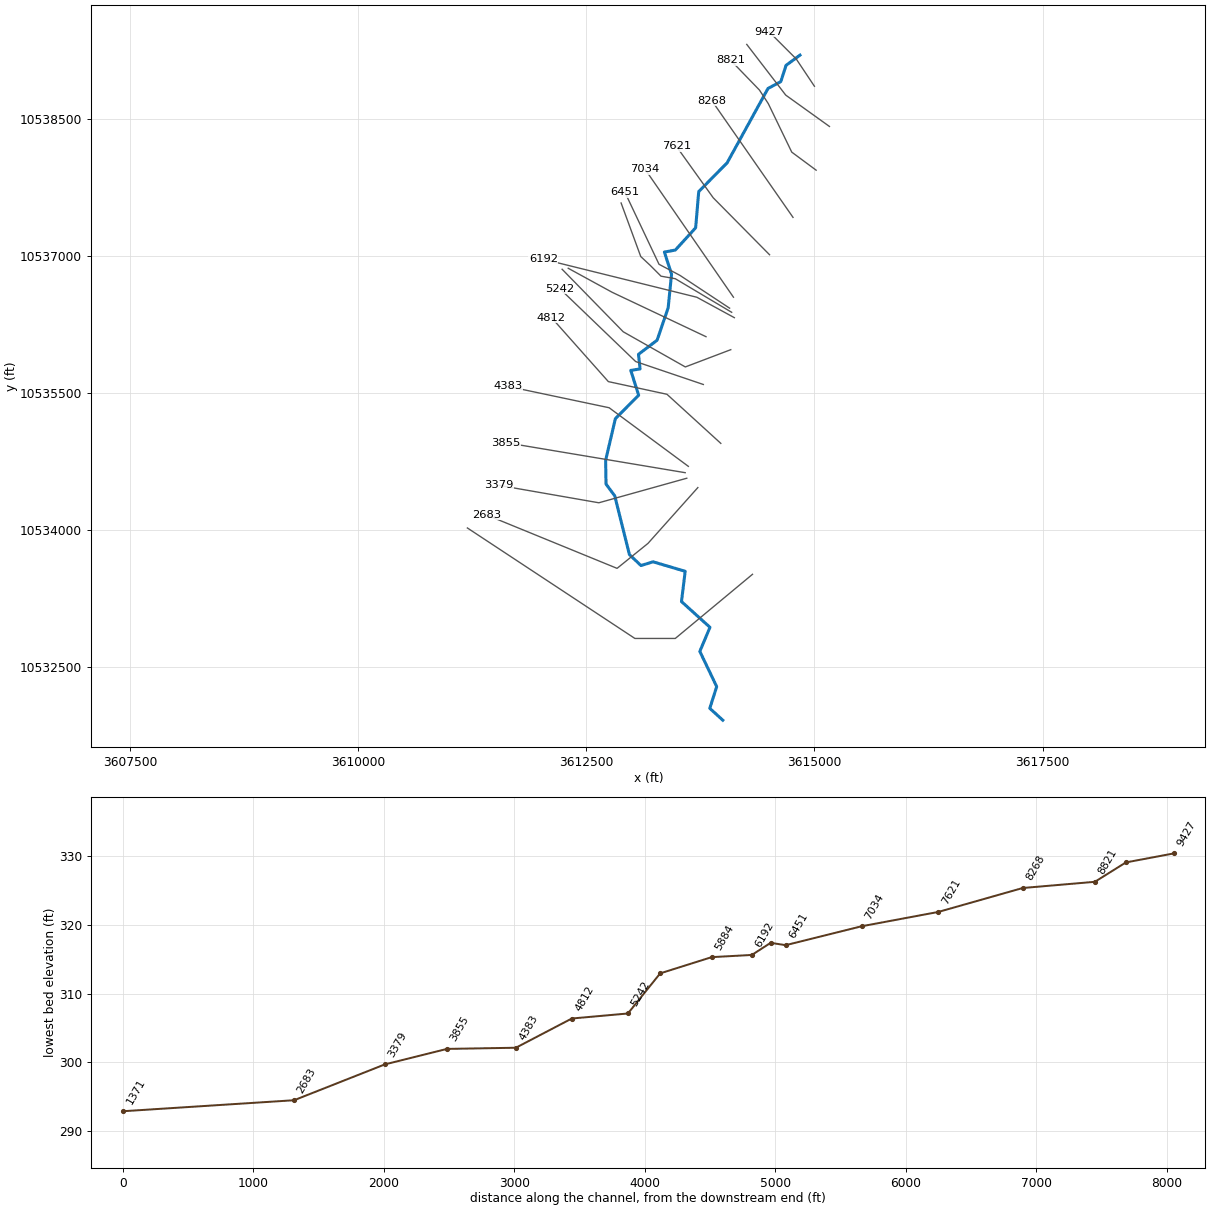
--- WHITNEY BRANCH.prj (project) ---

Proj Title=WHITNEY BRANCH Base Level Engineering
Current Plan=p01
Default Exp/Contr=0.3,0.1
English Units
Geom File=g01
Flow File=f01
Plan File=p01
Y Axis Title=Elevation
X Axis Title(PF)=Main Channel Distance
X Axis Title(XS)=Station
BEGIN DESCRIPTION:
WHITNEY BRANCH
END DESCRIPTION:
DSS File=dss
DSS Export Rating Curves= 0
DSS Export Rating Curve Sorted= 0
DSS Export Volume Flow Curves= 0
DXF OffsetX= 0
DXF OffsetY= 0
DXF ScaleX= 1
DXF ScaleY= 10

--- WHITNEY BRANCH.p01 (plan) ---

Plan Title=Multiple Run
Program Version=4.10
Short Identifier=Multiple Run
Geom File=g01
Flow File=f01
Subcritical Flow
K Sum by GR= 0
Std Step Tol= 0.01
Critical Tol= 0.01
Num of Std Step Trials= 20
Max Error Tol= 0.3
Flow Tol Ratio= 0.001
Split Flow NTrial= 30
Split Flow Tol= 0.02
Split Flow Ratio= 0.02
Log Output Level= 0
Friction Slope Method= 1
Unsteady Friction Slope Method= 2
Unsteady Bridges Friction Slope Method= 1
Parabolic Critical Depth
Global Vel Dist= 1 , 1 , 1
Global Log Level= 0
CheckData=True
Encroach Param=-1 ,0,0, 0
BEGIN DESCRIPTION:
Multiple Run
END DESCRIPTION:
Computation Interval=1HOUR
Output Interval=1HOUR
Run HTab= 0
Run UNet= 0
Run PostProcess= 0
Run WQNet= 0
UNET Theta= 1
UNET Theta Warmup= 1
UNET ZTol= 0.02
UNET ZSATol= 0.05
UNET MxIter= 20
UNET MaxInSteps= 0
UNET DtIC= 0
UNET DtMin= 0
UNET MaxCRTS= 20
UNET WFStab= 2
UNET SFStab= 1
UNET WFX= 1
UNET SFX= 1
UNET DSS MLevel= 4
UNET DZMax Abort= 100
UNET Convert EG Bridges= 0
UNET Use Existing IB Tables=-1
UNET Froude Reduction=False
UNET Froude Limit= 1
UNET Froude Power= 10
UNET Time Slicing=0,0, 5
UNET Junction Losses=0
Instantaneous Interval=1HOUR
DSS File=dss
Write IC File= 0
Write IC File at Sim End=0
Echo Input=False
Echo Parameters=False
Echo Output=False
Write Detailed= 0
WQ AD Non Conservative
WQ ULTIMATE=-1
WQ Max Comp Step=1HOUR
WQ Output Interval=15MIN
WQ Output Selected Increments= 0
WQ Output face flow=0
WQ Output face velocity=0
WQ Output face area=0
WQ Output face dispersion=0
WQ Output cell volume=0
WQ Output cell surface area=0
WQ Output cell continuity=0
WQ Output cumulative cell continuity=0
WQ Output face conc=0
WQ Output face dconc_dx=0
WQ Output face courant=0
WQ Output face peclet=0
WQ Output face adv mass=0
WQ Output face disp mass=0
WQ Output cell mass=0
WQ Output cell source sink temp=0
WQ Output cell source sink nsm=0
WQ Output MaxMinRange=-1
WQ Daily Max Min Mean=-1
WQ Daily Range=0
WQ Daily Time=0
WQ Create Restart=0
WQ Fixed Restart=0
WQ System Summary=0
WQ Use Fixed Temperature=0
Sorting and Armoring Iterations= 10
XS Update Threshold= 0.02
Hydraulics Update Threshold= 0.02
Energy Slope Method= 1
Volume Change Method= 0
XS Weighting Method= 0
Number of US Weighted Cross Sections= 1
Number of DS Weighted Cross Sections= 1
Upstream XS Weight=0.25
Main XS Weight=0.5
Downstream XS Weight=0.25
Number of DS XS's Weighted with US Boundary= 1
Upstream Boundary Weight= 1
Weight of XSs Associated with US Boundary= 0
Number of US XS's Weighted with DS Boundary= 1
Downstream Boundary Weight= 0.5
Weight of XSs Associated with DS Boundary= 0.5
Sediment Output Level= 4
Mass or Volume Output= 0
Output Increment Type= 1
Profile and TS Output Increment= 10
XS Output Flag= 0
XS Output Increment= 10
Disregard all LS=0
Disregard all Conn=0
Disregard all Breaches=0
Disregard all Pumps=0

--- WHITNEY BRANCH.f01 (steady flow) ---

Flow Title=Multiple
Program Version=4.10
Number of Profiles= 7
Profile Names=10-year,25-year,50-year,1pct_min,100-year,1pct_plu,500-year
River Rch & RM=WHITNEY BRANCH,Reach-1         ,9427
    1074    1481    1819    1632    2207    2985    3235
River Rch & RM=WHITNEY BRANCH,Reach-1         ,8268
    1344    1884    2340    2121    2868    3879    4295
River Rch & RM=WHITNEY BRANCH,Reach-1         ,6192
    2427    3502    4434    4087    5528    7475    8569
River Rch & RM=WHITNEY BRANCH,Reach-1         ,5242
    2427    3502    4434    4087    5528    7475    8569
Boundary for River Rch & Prof#=WHITNEY BRANCH,Reach-1         , 1
Up Type= 0
Dn Type= 3
Dn Slope=0.002
Boundary for River Rch & Prof#=WHITNEY BRANCH,Reach-1         , 2
Up Type= 0
Dn Type= 3
Dn Slope=0.002
Boundary for River Rch & Prof#=WHITNEY BRANCH,Reach-1         , 3
Up Type= 0
Dn Type= 3
Dn Slope=0.002
Boundary for River Rch & Prof#=WHITNEY BRANCH,Reach-1         , 4
Up Type= 0
Dn Type= 3
Dn Slope=0.002
Boundary for River Rch & Prof#=WHITNEY BRANCH,Reach-1         , 5
Up Type= 0
Dn Type= 3
Dn Slope=0.002
Boundary for River Rch & Prof#=WHITNEY BRANCH,Reach-1         , 6
Up Type= 0
Dn Type= 3
Dn Slope=0.002
Boundary for River Rch & Prof#=WHITNEY BRANCH,Reach-1         , 7
Up Type= 0
Dn Type= 3
Dn Slope=0.002
DSS Import GetInterval= 0
DSS Import GetPeak= 0
DSS Import FillOption= 0

--- WHITNEY BRANCH.g01 (geometry) ---

Geom Title=Existing Conditions
Program Version=4.10

River Reach=WHITNEY BRANCH  ,Reach-1
Reach XY= 30
      3614841.21     10539201.79      3614688.25       10539089.
      3614631.25       10538911.      3614490.75       10538836.
      3614042.75       10538021.       3613731.5       10537706.
      3613697.75       10537309.      3613475.25       10537065.
      3613355.25       10537043.       3613433.5       10536800.
       3613396.5       10536432.      3613275.25       10536077.
      3613071.25       10535922.       3613088.5       10535762.
      3612986.75       10535746.        3613073.       10535474.
        3612818.       10535217.        3612711.       10534760.
       3612715.5       10534500.      3612811.25       10534370.
        3612972.       10533727.       3613098.5       10533607.
        3613231.       10533648.        3613583.       10533544.
       3613542.5       10533212.      3613854.75       10532930.
       3613743.5       10532666.       3613928.5       10532280.
      3613852.75       10532042.      3613995.25       10531912.

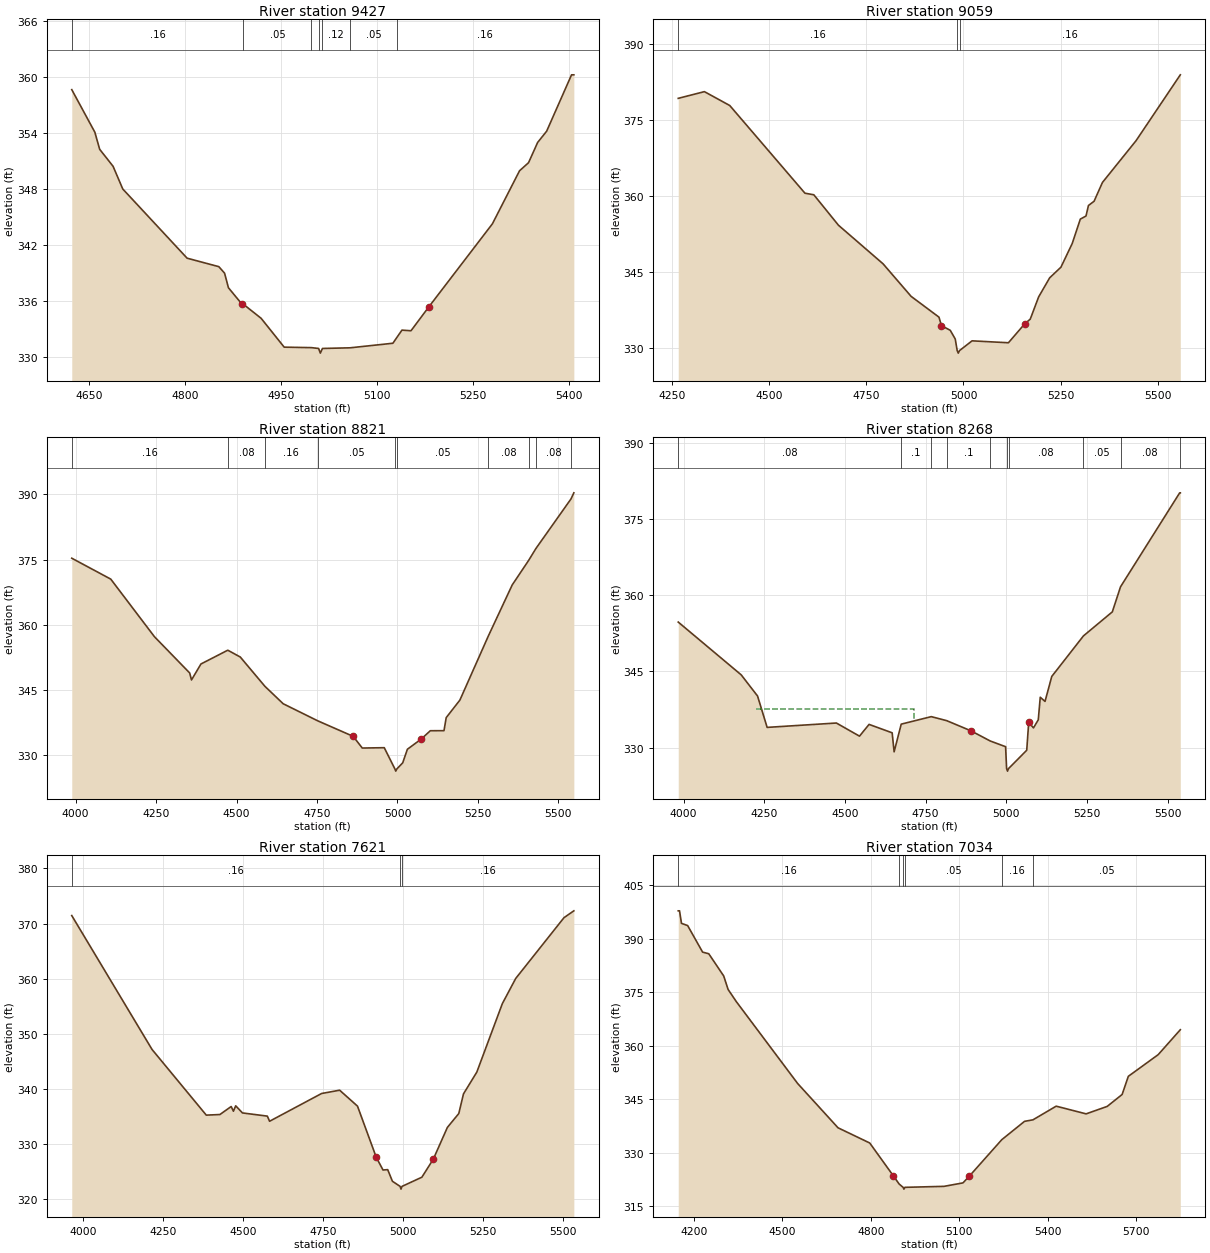
Type RM Length L Ch R = 1 ,9427    ,368,368,368
BEGIN DESCRIPTION:
WHITNEY BRANCH 16.0
END DESCRIPTION:
XS GIS Cut Line= 3
      3614999.63     10538860.15      3614799.61     10539160.19
      3614499.58     10539460.22
#Sta/Elev= 30
  4622.3  358.65  4658.4  354.08  4665.9  352.25  4686.9  350.42    4702  347.99
  4802.6  340.56  4852.2  339.65  4861.2  338.95  4867.2  337.39  4888.3  335.63
  4890.5  335.62  4918.3  334.11  4954.4  331.01  4996.8  330.96  5008.2  330.87
  5010.9  330.37  5014.2  330.87  5057.4  330.94  5124.3  331.43  5130.3  332.03
  5138.5  332.84  5152.6  332.77  5180.9  335.37  5279.9  344.25  5322.3  349.94
  5336.4  350.81  5350.6  352.98  5364.7  354.19  5403.6  360.24  5407.2  360.24
#Mann= 7 ,-1 , 0
  4622.3     .16       0  4890.5     .05       0  4996.8     .12       0
  5008.2     .07       0  5014.2     .12       0  5057.4     .05       0
  5130.3     .16       0
Bank Sta=4888.3,5180.9
XS Rating Curve= 0 ,0
Exp/Cntr=0.3,0.1

Type RM Length L Ch R = 1 ,9059    ,238,238,238
BEGIN DESCRIPTION:
WHITNEY BRANCH 15.0
END DESCRIPTION:
XS GIS Cut Line= 3
      3615164.24     10538419.52      3614685.04     10538763.28
      3614257.95     10539318.85
#Sta/Elev= 30
  4266.8  379.21  4334.1  380.53  4399.2   377.8  4592.5  360.54  4615.3  360.23
  4678.6  354.24  4793.4  346.63  4865.3  340.24    4937  336.14  4943.3  334.48
    4966  333.55  4978.8  331.84  4983.8  329.56  4986.6  329.06  4989.8  329.56
  5022.1  331.48  5115.5   331.1  5157.1   334.8  5171.6  335.75  5193.2  340.13
  5221.5  343.88  5250.5  345.98  5279.5  350.64  5300.3  355.44  5314.9  356.05
  5321.2  358.12  5335.7  358.96  5357.2  362.66  5443.6  370.88  5557.3  383.84
#Mann= 3 ,-1 , 0
  4266.8     .16       0  4983.8     .07       0  4989.8     .16       0
Bank Sta=4943.3,5157.1
XS Rating Curve= 0 ,0
Exp/Cntr=0.3,0.1

Type RM Length L Ch R = 1 ,8821    ,553,553,553
BEGIN DESCRIPTION:
WHITNEY BRANCH 14.0
END DESCRIPTION:
XS GIS Cut Line= 5
      3615018.35     10537940.38      3614751.02     10538138.28
      3614494.07     10538669.53      3614396.85     10538818.84
       3614077.4      10539148.7
#Sta/Elev= 30
    3988  375.31  4109.2  370.49  4244.8  357.23  4354.4  348.86    4360  347.25
  4389.4  350.93  4472.8  354.11  4511.6  352.54  4588.1  345.79  4644.9  341.77
  4752.4  337.83  4862.5  334.25  4890.7  331.56    4959  331.64  4992.1  326.74
  4994.8  326.24  4998.1  326.74  5016.3  328.15  5030.9  331.28  5073.7  333.62
  5102.1  335.55  5144.6  335.56  5151.5  338.57    5194  342.61    5282  357.31
  5356.6  369.15  5407.7  374.81  5430.2  377.54  5539.3  388.98  5548.1  390.38
#Mann= 10 ,-1 , 0
    3988     .16       0  4472.8     .08       0  4588.1     .16       0
  4752.4     .05       0  4992.1     .03       0  4998.1     .05       0
    5282     .08       0  5407.7     .05       0  5430.2     .08       0
  5539.3     .05       0
Bank Sta=4862.5,5073.7
XS Rating Curve= 0 ,0
Exp/Cntr=0.3,0.1

Type RM Length L Ch R = 1 ,8268    ,647,647,647
BEGIN DESCRIPTION:
WHITNEY BRANCH 13.0
END DESCRIPTION:
XS GIS Cut Line= 2
      3614764.88     10537423.04      3613876.02     10538700.78
#Sta/Elev= 30
  3983.2  354.75  4178.5  344.33  4229.1  340.16  4258.8  333.97  4473.5  334.83
  4545.1  332.24  4574.8  334.56  4646.4   332.9  4652.5  329.15  4674.5  334.61
  4767.6  336.09  4815.4   335.3  4890.8  333.29  4950.3  331.29  4998.1  330.16
  5001.2  325.84    5004  325.34  5007.2  325.84  5063.6  329.46  5069.7  334.98
  5084.5  333.87  5099.4  335.47  5105.5  339.92  5120.3  339.09  5141.2  344.02
  5239.4  352.02  5328.9  356.76  5354.4  361.71  5537.8  380.25  5539.7  380.25
#Mann= 10 ,-1 , 0
  3983.2     .08       0  4674.5      .1       0  4767.6     .08       0
  4815.4      .1       0  4950.3     .08       0  5001.2     .07       0
  5007.2     .08       0  5239.4     .05       0  5354.4     .08       0
  5537.8     .05       0
#XS Ineff= 1 ,-1
 4223.41 4714.32  337.52
Permanent Ineff=
       F
Bank Sta=4890.8,5069.7
XS Rating Curve= 0 ,0
Exp/Cntr=0.3,0.1

Type RM Length L Ch R = 1 ,7621    ,587,587,587
BEGIN DESCRIPTION:
WHITNEY BRANCH 12.0
END DESCRIPTION:
XS GIS Cut Line= 3
      3614507.98     10537013.26      3613889.91     10537638.28
       3613487.1     10538200.82
#Sta/Elev= 30
  3964.2  371.44  4215.4  347.17  4385.1  335.27  4427.6  335.38    4463  336.83
    4470  335.98  4477.1  336.96  4498.3  335.67  4576.1  335.09  4583.1  334.16
  4745.8  339.19  4802.4  339.79  4858.2   336.9  4917.1   327.6    4938  325.33
  4952.7  325.39  4967.5  323.28  4991.5  322.36  4994.3  321.86  4997.5  322.36
  5059.6  324.02  5095.2  327.27  5139.5  333.05  5175.1  335.56  5189.8  339.12
  5231.6  343.08  5311.4  355.48  5353.2  360.04  5504.3  371.06  5535.1   372.3
#Mann= 3 ,-1 , 0
  3964.2     .16       0  4991.5     .07       0  4997.5     .16       0
Bank Sta=4917.1,5095.2
XS Rating Curve= 0 ,0
Exp/Cntr=0.3,0.1

Type RM Length L Ch R = 1 ,7034    ,583,583,583
BEGIN DESCRIPTION:
WHITNEY BRANCH 11.0
END DESCRIPTION:
XS GIS Cut Line= 2
      3614112.14     10536547.98        3613144.     10537949.88
#Sta/Elev= 30
  4146.3  397.84  4150.7  397.84  4157.3  394.33  4178.3   393.7    4229  386.26
  4249.9   385.8  4300.6  379.57  4315.5  375.79  4343.4  372.37  4551.4  349.42
  4688.6  336.98  4796.1  332.72  4876.6  323.47  4895.9  321.21  4909.4  320.28
  4912.1  319.78  4915.4  320.28  5048.3  320.56  5112.5  321.53  5133.4  323.35
  5244.1  333.64  5321.4  338.79  5350.1  339.22  5428.8  343.05  5530.3  340.89
  5601.9  342.98  5652.6  346.33  5673.6  351.42    5775   357.5    5850  364.49
#Mann= 6 ,-1 , 0
  4146.3     .16       0  4895.9     .05       0  4909.4    .035       0
  4915.4     .05       0  5244.1     .16       0  5350.1     .05       0
Bank Sta=4876.6,5133.4
XS Rating Curve= 0 ,0
Exp/Cntr=0.3,0.1

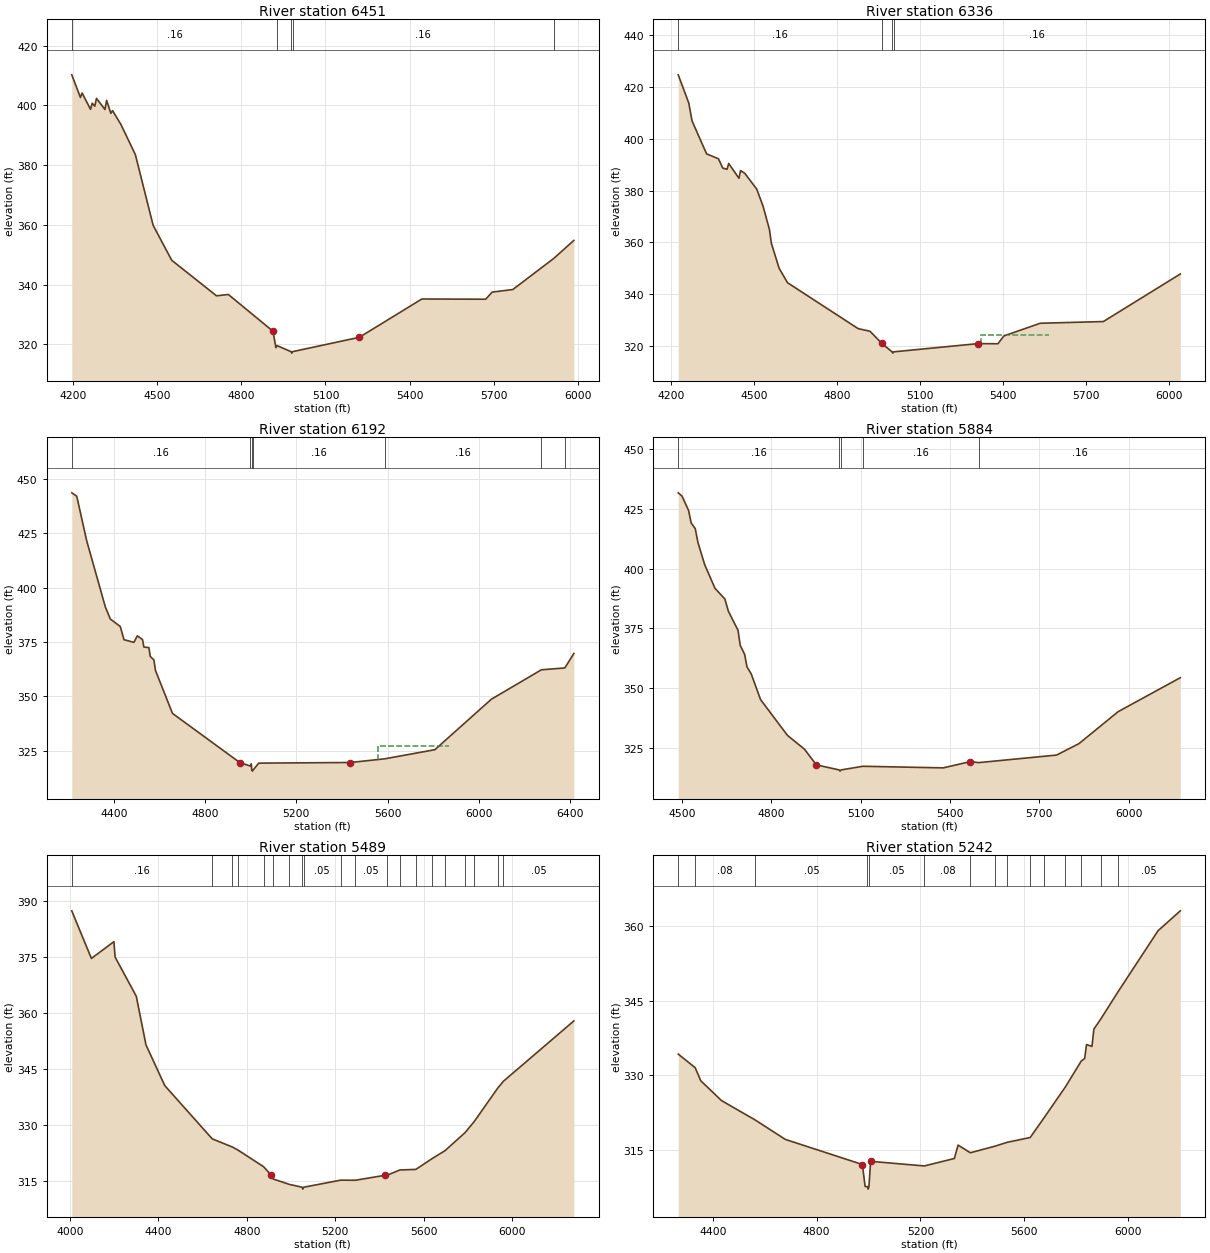
Type RM Length L Ch R = 1 ,6451    ,115,115,115
BEGIN DESCRIPTION:
WHITNEY BRANCH 10.0
END DESCRIPTION:
XS GIS Cut Line= 4
      3614069.93     10536427.96      3613525.32     10536787.59
      3613296.16     10536909.12      3612921.17     10537700.76
#Sta/Elev= 30
  4196.6  410.27  4227.4   402.7  4233.4  404.17  4263.5  398.71  4269.5  400.75
  4278.6  399.76  4284.6  402.39  4314.7  398.65  4320.7  401.72  4335.8  397.37
  4341.8  398.28  4371.9   393.6  4423.1  383.53  4486.3  359.87  4552.5  348.15
  4712.1  336.23  4754.2  336.68  4913.1  324.37  4923.6  318.88  4927.6  319.56
  4977.2  317.53    4980  317.03  4983.2  317.53  5220.5  322.32  5443.3  335.16
  5670.7  335.09  5693.5  337.47  5767.3  338.34  5912.9  348.74  5984.6   354.8
#Mann= 5 ,-1 , 0
  4196.6     .16       0  4927.6     .05       0  4977.2     .03       0
  4983.2     .16       0  5912.9     .16       0
Bank Sta=4913.1,5220.5
XS Rating Curve= 0 ,0
Exp/Cntr=0.3,0.1

Type RM Length L Ch R = 1 ,6336    ,144,144,144
BEGIN DESCRIPTION:
Mapping XS fc868a14
END DESCRIPTION:
XS GIS Cut Line= 6
       3614092.5     10536382.79      3613474.48     10536750.82
      3613318.23      10536778.6      3613200.17     10536896.66
      3613096.01     10536993.88      3612880.73     10537580.69
#Sta/Elev= 30
  4226.7  424.61  4264.8  413.74  4276.6  406.83  4329.1  394.15  4371.9  392.26
  4387.5  388.67  4403.1  388.22  4408.9  390.47  4445.9  384.75  4451.7  387.72
  4467.3  386.62  4510.1  380.57  4532.7  374.05    4556     365  4562.7  359.78
  4590.9  350.07  4621.1  344.51  4876.2  326.81    4919   325.8  4961.1  321.19
  4961.9  321.07  4998.7  317.87  5001.5  317.37  5004.7  317.87  5310.1  321.04
  5380.9  320.98  5401.9  323.97  5533.5  328.88  5761.5  329.54  6039.2  347.87
#Mann= 4 ,-1 , 0
  4226.7     .16       0  4961.9     .05       0  4998.7     .03       0
  5004.7     .16       0
#XS Ineff= 1 ,-1
  5319.6 5566.76  324.49
Permanent Ineff=
       F
Bank Sta=4961.1,5310.1
XS Rating Curve= 0 ,0
Exp/Cntr=0.3,0.1

Type RM Length L Ch R = 1 ,6192    ,308,308,308
BEGIN DESCRIPTION:
WHITNEY BRANCH 9.0
END DESCRIPTION:
XS GIS Cut Line= 3
      3614122.03     10536323.78      3613710.57     10536547.75
      3612028.27     10536964.41
#Sta/Elev= 30
  4215.2  443.68    4237  442.14  4280.7   421.6  4362.4  391.17  4384.3   385.6
  4427.9  382.17  4444.1   376.1  4487.8  374.88  4502.6  377.88  4525.4  376.15
  4531.5  372.71  4553.3  372.47  4559.5  368.37  4575.2  366.81  4582.3  361.94
  4656.8  342.18  4952.5  319.52  4997.9  317.97  5002.3  318.98  5004.5  316.11
  5007.2  315.61  5010.5  316.11  5034.9  319.29  5436.7  319.58  5586.7  321.26
  5807.6  325.48  6054.8  348.67  6274.5  362.25  6377.3  363.09  6416.8  369.75
#Mann= 7 ,-1 , 0
  4215.2     .16       0  4997.9     .05       0  5004.5     .03       0
  5010.5     .16       0  5586.7     .16       0  6274.5     .08       0
  6377.3      .1       0
#XS Ineff= 1 ,-1
 5556.82 5870.74  326.97
Permanent Ineff=
       F
Bank Sta=4952.5,5436.7
XS Rating Curve= 0 ,0
Exp/Cntr=0.3,0.1

Type RM Length L Ch R = 1 ,5884    ,395,395,395
BEGIN DESCRIPTION:
Mapping XS e2bb65c7
END DESCRIPTION:
XS GIS Cut Line= 3
      3613811.28     10536115.41      3612783.51     10536601.52
      3612301.05     10536865.31
#Sta/Elev= 30
  4486.9  431.65  4499.8  430.26  4521.9   424.2  4530.3  419.06  4544.1  416.69
  4553.1   410.9  4575.8   401.6  4610.4  391.72  4643.6  387.27  4655.2   382.2
  4687.9  374.12  4695.1  367.91    4710   364.1  4717.9  358.88  4732.1  355.95
  4763.4  345.22  4853.8  330.24    4911  324.47    4951   317.9  5027.8  315.79
  5030.5  315.29  5033.8  315.79  5107.4  317.32  5377.2  316.65  5468.2  319.27
  5496.7  318.85  5757.9     322  5833.4   326.8  5964.7  340.14  6173.7  354.35
#Mann= 5 ,-1 , 0
  4486.9     .16       0  5027.8     .07       0  5033.8     .16       0
  5107.4     .16       0  5496.7     .16       0
Bank Sta=4951,5468.2
XS Rating Curve= 0 ,0
Exp/Cntr=0.3,0.1

Type RM Length L Ch R = 1 ,5489    ,247,247,247
BEGIN DESCRIPTION:
WHITNEY BRANCH 8.0
END DESCRIPTION:
XS GIS Cut Line= 4
      3614082.69     10535973.05      3613584.43     10535783.81
      3612903.88     10536169.23      3612234.18     10536854.54
#Sta/Elev= 30
  4007.4  387.44  4096.3  374.69  4198.2  379.19  4203.6  375.06  4299.5  364.57
  4343.5  351.54  4428.5  340.65  4643.4  326.39  4733.3  324.24  4759.6   323.4
  4875.8  318.94  4908.2  316.82  4919.5  315.64    4992  314.21  5050.9  313.43
  5053.7  312.93  5056.9  313.43  5224.5  315.33  5291.9  315.31  5425.2  316.63
  5432.9  316.59  5492.9  318.06  5565.1  318.21  5640.3  321.15  5697.2  323.22
  5787.7  328.03  5829.3  330.99  5935.1   339.9  5961.4  341.79  6280.7  357.96
#Mann= 20 ,-1 , 0
  4007.4     .16       0  4643.4     .08       0  4733.3     .16       0
  4759.6     .05       0  4875.8     .08       0  4919.5     .16       0
    4992     .05       0  5050.9     .04       0  5056.9     .05       0
  5224.5     .08       0  5291.9     .05       0  5432.9     .16       0
  5492.9     .08       0  5565.1     .05       0  5640.3     .08       0
  5697.2     .16       0  5787.7     .05       0  5829.3     .16       0
  5935.1     .08       0  5961.4     .05       0
Bank Sta=4908.2,5425.2
XS Rating Curve= 0 ,0
Exp/Cntr=0.3,0.1

Type RM Length L Ch R = 1 ,5242    ,430,430,430
BEGIN DESCRIPTION:
WHITNEY BRANCH 7.0
END DESCRIPTION:
XS GIS Cut Line= 3
      3613781.95     10535591.52      3613040.33     10535842.81
      3612209.45     10536641.44
#Sta/Elev= 30
  4266.3  334.25  4331.6  331.52  4353.2  328.89    4433  324.91  4563.4  320.99
    4679   317.1  4976.2  312.05  4986.7  307.64  4995.5   307.6  4998.3   307.1
  5001.5   307.6  5007.9  312.69    5215  311.76  5330.8  313.26    5345  315.96
  5392.4  314.41    5487  315.73  5534.9  316.52  5623.1  317.48  5677.4  321.51
  5759.1  327.68  5819.9  332.85    5833  333.36  5840.2  336.17  5861.3   335.8
  5868.5  339.26  5895.1   341.3  5962.5  346.84    6116  359.06  6201.8  363.06
#Mann= 15 ,-1 , 0
  4266.3     .05       0  4331.6     .08       0  4563.4     .05       0
  4995.5     .03       0  5001.5     .05       0    5215     .08       0
  5392.4     .16       0    5487     .05       0  5534.9     .16       0
  5623.1     .05       0  5677.4     .16       0  5759.1     .05       0
  5819.9     .16       0  5895.1      .1       0  5962.5     .05       0
Bank Sta=4976.2,5007.9
XS Rating Curve= 0 ,0
Exp/Cntr=0.3,0.1

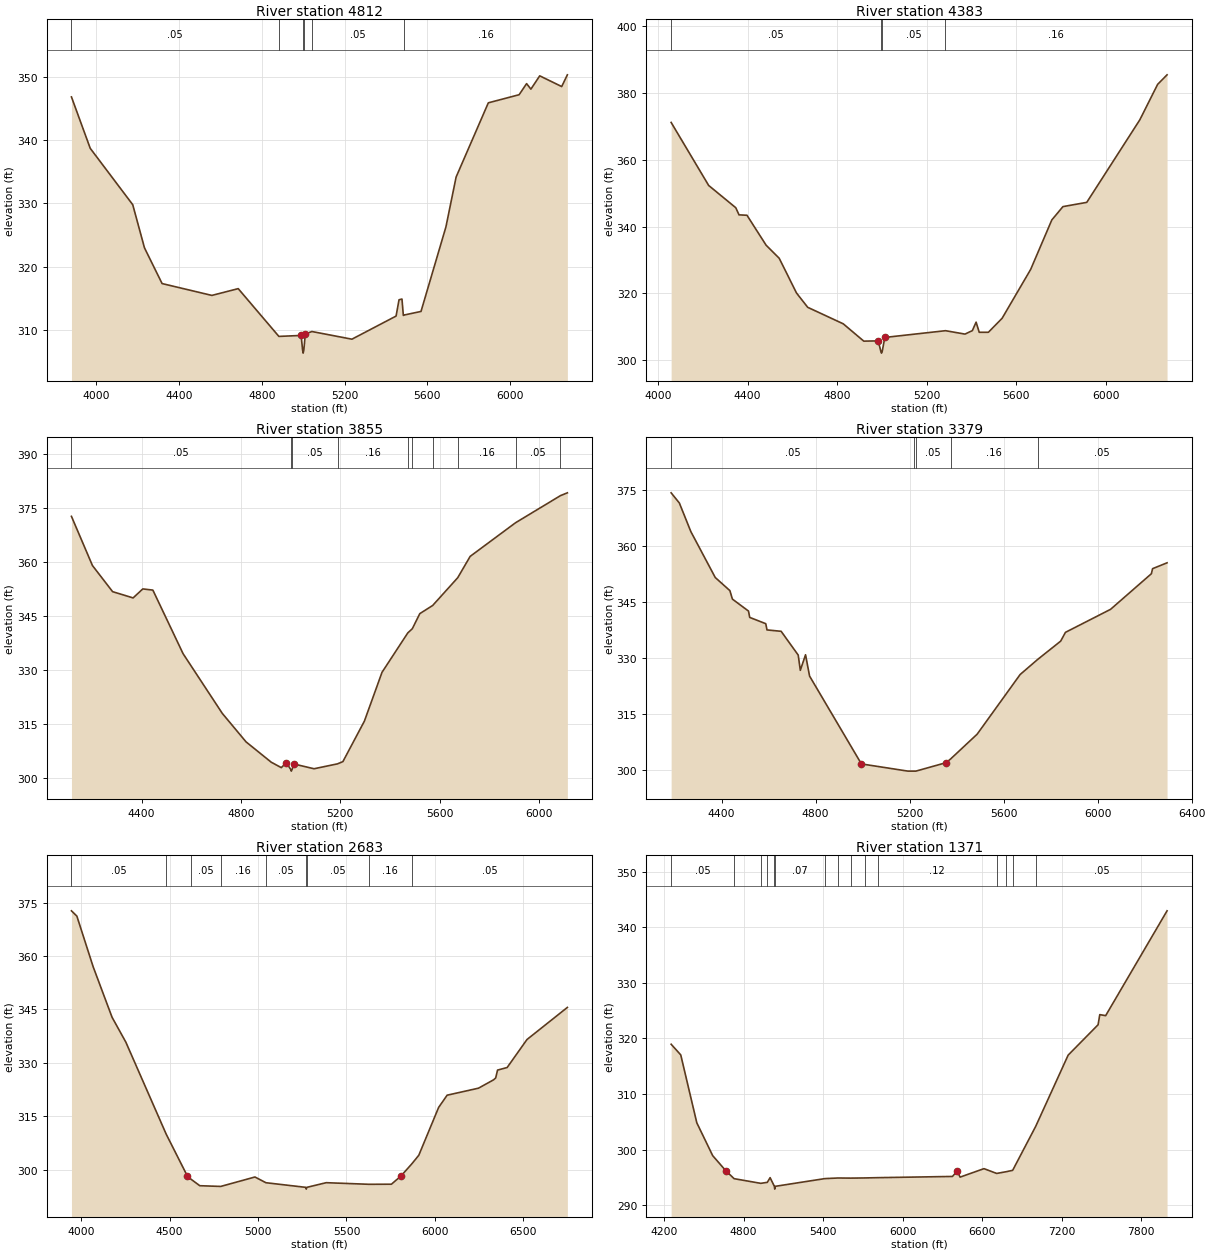
Type RM Length L Ch R = 1 ,4812    ,429,429,429
BEGIN DESCRIPTION:
WHITNEY BRANCH 6.0
END DESCRIPTION:
XS GIS Cut Line= 4
      3613973.62     10534945.94      3613383.31     10535484.16
      3612740.95     10535623.05      3612116.41     10536325.65
#Sta/Elev= 30
  3880.5  346.81  3971.2   338.7  4176.6   329.8  4233.3  322.99  4318.4  317.35
    4559  315.48  4686.2  316.55  4882.7  309.01  4990.1  309.16  4997.3  306.87
    5000  306.37  5003.3  306.87  5010.4   309.4  5042.4  309.78  5235.6  308.57
    5449  312.22  5463.2  314.79  5477.4  314.91  5484.1  312.32  5488.6  312.39
  5569.4  312.95  5689.8  326.29  5739.1  334.17  5894.7  345.88  6043.5  347.16
  6079.5  348.91  6100.4  348.04    6143  350.14  6249.2  348.45  6276.6   350.3
#Mann= 6 ,-1 , 0
  3880.5     .05       0  4882.7     .16       0  4997.3     .07       0
  5003.3     .16       0  5042.4     .05       0  5488.6     .16       0
Bank Sta=4990.1,5010.4
XS Rating Curve= 0 ,0
Exp/Cntr=0.3,0.1

Type RM Length L Ch R = 1 ,4383    ,528,528,528
BEGIN DESCRIPTION:
WHITNEY BRANCH 5.0
END DESCRIPTION:
XS GIS Cut Line= 3
      3613617.67     10534694.24      3612749.63     10535336.59
      3611638.54     10535570.96
#Sta/Elev= 30
  4058.4  371.21    4226  352.34  4347.1  345.67  4361.7  343.53  4397.2  343.41
  4482.7  334.44  4541.2  330.53  4618.4  320.13  4668.5  315.84  4827.2   310.9
    4919  305.71  4983.7  305.79  4995.3  302.62  4998.1  302.12  5001.3  302.62
  5012.9  306.82    5284  308.84    5371  307.82    5404  308.86  5420.8   311.4
  5434.7  308.36  5475.6  308.36  5536.9  312.55  5664.5  327.19    5759  342.01
  5808.7     346    5915  347.27  6152.1  371.99  6231.8  382.62  6273.8  385.47
#Mann= 4 ,-1 , 0
  4058.4     .05       0  4995.3     .03       0  5001.3     .05       0
    5284     .16       0
Bank Sta=4983.7,5012.9
XS Rating Curve= 0 ,0
Exp/Cntr=0.3,0.1

Type RM Length L Ch R = 1 ,3855    ,476,476,476
BEGIN DESCRIPTION:
WHITNEY BRANCH 4.0
END DESCRIPTION:
XS GIS Cut Line= 2
      3613582.94     10534624.79      3611613.54     10534954.47
#Sta/Elev= 30
  4117.9  372.74  4202.4  359.08  4283.5  351.82  4366.1  350.08  4405.2  352.58
  4445.7  352.25  4567.4  334.58  4725.3  317.99  4820.9  310.08  4922.3  304.43
  4962.8  302.92  4983.1  304.32  5000.4  302.45  5003.1  301.95  5006.4  302.45
  5013.5  303.93  5094.6  302.61  5189.2  303.97  5210.9   304.6  5297.4  315.84
  5368.4  329.41  5472.2  340.36  5490.3  341.51  5520.5  345.71  5572.4  347.98
  5673.3   355.7  5723.3  361.62  5906.1  370.97  6086.9   378.5  6114.7  379.28
#Mann= 10 ,-1 , 0
  4117.9     .05       0  5000.4     .03       0  5006.4     .05       0
  5189.2     .16       0  5472.2     .05       0  5490.3      .1       0
  5572.4     .05       0  5673.3     .16       0  5906.1     .05       0
  6086.9     .16       0
Bank Sta=4983.1,5013.5
XS Rating Curve= 0 ,0
Exp/Cntr=0.3,0.1

Type RM Length L Ch R = 1 ,3379    ,696,696,696
BEGIN DESCRIPTION:
WHITNEY BRANCH 3.0
END DESCRIPTION:
XS GIS Cut Line= 3
      3613600.37     10534564.03      3612636.78     10534294.92
      3611543.78     10534485.77
#Sta/Elev= 30
  4185.3  374.22  4220.3  371.49  4269.2  363.83    4373  351.54  4435.3  348.03
    4446  345.76  4514.4  342.56  4519.6  340.86  4587.9  339.18  4593.1  337.51
  4653.3  337.14    4726  330.77  4734.9  326.69  4757.1  330.86  4774.3  325.15
  4994.8  301.63    5193   299.7  5220.5   299.7  5226.5   299.7  5355.5  301.97
  5374.8  302.98  5487.4   309.6  5670.2  325.57  5744.3  329.58  5842.7  334.51
    5863  336.86  6055.1  343.03  6228.5  352.55  6233.7  353.91  6295.3  355.48
#Mann= 5 ,-1 , 0
  4185.3     .05       0  5220.5     .03       0  5226.5     .05       0
  5374.8     .16       0  5744.3     .05       0
Bank Sta=4994.8,5355.5
XS Rating Curve= 0 ,0
Exp/Cntr=0.3,0.1

Type RM Length L Ch R = 1 ,2683    ,1312,1312,1312
BEGIN DESCRIPTION:
WHITNEY BRANCH 2.0
END DESCRIPTION:
XS GIS Cut Line= 4
      3613721.84     10534461.58      3613174.98     10533849.61
      3612836.43     10533576.17      3611404.42       10534162.
#Sta/Elev= 30
  3945.5  372.74  3976.1  371.25  4068.1  357.02  4175.1   342.8  4252.8  335.83
  4480.7  309.98  4599.7  298.26  4619.8  297.33  4670.8  295.45  4789.4  295.25
  4982.7   297.9  5044.8  296.29  5270.1  294.99  5272.9  294.49  5276.1  294.99
  5385.3   296.3  5626.1  295.85  5753.9  295.87  5807.3  298.14  5869.4   301.6
  5908.8  304.01    6021  317.47    6069   320.9    6246  322.87  6330.7   325.2
  6343.2  325.72    6354  327.96  6408.1  328.68  6520.4  336.56  6748.6  345.58
#Mann= 9 ,-1 , 0
  3945.5     .05       0  4480.7      .1       0  4619.8     .05       0
  4789.4     .16       0  5044.8     .05       0  5270.1     .07       0
  5276.1     .05       0  5626.1     .16       0  5869.4     .05       0
Bank Sta=4599.7,5807.3
XS Rating Curve= 0 ,0
Exp/Cntr=0.3,0.1

Type RM Length L Ch R = 1 ,1371    ,0,0,0
BEGIN DESCRIPTION:
WHITNEY BRANCH 1.0
END DESCRIPTION:
XS GIS Cut Line= 4
      3614320.83     10533511.08      3613474.45     10532807.95
      3613031.75     10532807.95      3611195.79      10534018.9
#Sta/Elev= 30
  4253.8  318.95  4326.3  317.03  4447.4  304.82  4567.4  298.91  4667.4  296.17
    4729  294.77  4930.3  293.93  4979.4  294.11  5000.7  294.95  5032.9  293.39
  5035.6  292.89  5038.9  293.39  5413.1  294.78    5512  294.89  5610.8  294.87
    5713   294.9  5811.3  294.95  6376.7  295.17  6412.9  296.14  6434.3  295.05
  6614.6  296.57  6710.5  295.71    6784  296.03  6831.1  296.27  7004.6  304.16
  7249.9  316.99  7475.7  322.45  7488.5  324.27  7532.9  324.09  7996.2  342.94
#Mann= 15 ,-1 , 0
  4253.8     .05       0    4729     .12       0  4930.3     .05       0
  4979.4     .07       0  5032.9     .07       0  5038.9     .07       0
  5413.1     .05       0    5512     .07       0  5610.8     .05       0
    5713     .07       0  5811.3     .12       0  6710.5     .05       0
    6784     .12       0  6831.1     .16       0  7004.6     .05       0
Bank Sta=4667.4,6412.9
XS Rating Curve= 0 ,0
Exp/Cntr=0.3,0.1

Chan Stop Cuts=-1
Use User Specified Reach Order=0
Composite Channel Slope=5