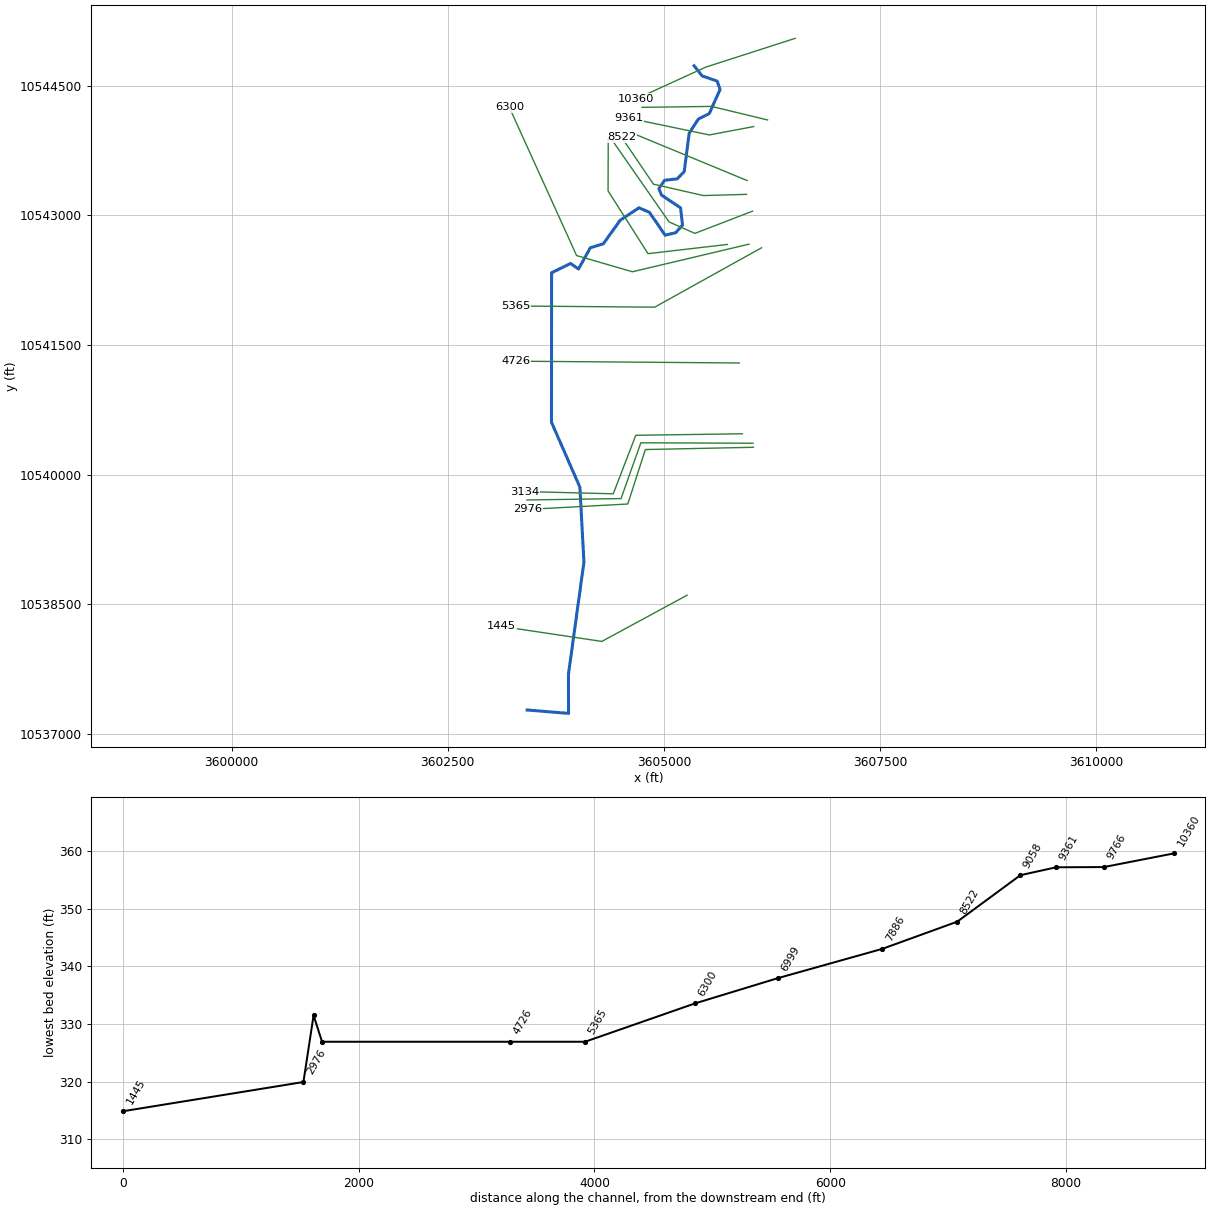
--- WILKERSON SPRING BRANCH.prj (project) ---

Proj Title=WILKERSON SPRING BRANCH Base Level Engineering
Current Plan=p01
Default Exp/Contr=0.3,0.1
English Units
Geom File=g01
Flow File=f01
Plan File=p01
BEGIN DESCRIPTION:
WILKERSON SPRING BRANCH
END DESCRIPTION:

--- WILKERSON SPRING BRANCH.p01 (plan) ---

Plan Title=Multiple Run
Short Identifier=Multiple
Geom File=g01
Flow File=f01
Subcritical Flow
K Sum by GR= 0
Std Step Tol= 0.01
Critical Tol= 0.01
Num of Std Step Trials= 20
Max Error Tol= 0.3
Flow Tol Ratio= 0.001
Split Flow NTrial= 30
Split Flow Tol= 0.02
Split Flow Ratio= 0.02
Log Output Level= 0
Friction Slope Method= 1
Unsteady Friction Slope Method= 2
Unsteady Bridges Friction Slope Method= 1
Parabolic Critical Depth
Global Vel Dist=  1 , 1 , 1
Global Log Level= 0
CheckData=True
Encroach Param= -1, 0, 0, 0
BEGIN DESCRIPTION:
Multiple Run
END DESCRIPTION:

--- WILKERSON SPRING BRANCH.f01 (steady flow) ---

Flow Title=Multiple
Number of Profiles=7
Profile Names=10-year,25-year,50-year,1pct_min,100-year,1pct_plu,500-year
River Rch & RM= WILKERSON SPRING,Reach-1,10360
    1185    1645    2029    1828    2472    3343    3653
River Rch & RM= WILKERSON SPRING,Reach-1,6300
    1770    2505    3129    2850    3854    5212    5827
Boundary for River Rch & Prof#=WILKERSON SPRING,Reach-1,1
Up Type=0
Dn Type=3
Dn Slope=0.005
Boundary for River Rch & Prof#=WILKERSON SPRING,Reach-1,2
Up Type=0
Dn Type=3
Dn Slope=0.005
Boundary for River Rch & Prof#=WILKERSON SPRING,Reach-1,3
Up Type=0
Dn Type=3
Dn Slope=0.005
Boundary for River Rch & Prof#=WILKERSON SPRING,Reach-1,4
Up Type=0
Dn Type=3
Dn Slope=0.005
Boundary for River Rch & Prof#=WILKERSON SPRING,Reach-1,5
Up Type=0
Dn Type=3
Dn Slope=0.005
Boundary for River Rch & Prof#=WILKERSON SPRING,Reach-1,6
Up Type=0
Dn Type=3
Dn Slope=0.005
Boundary for River Rch & Prof#=WILKERSON SPRING,Reach-1,7
Up Type=0
Dn Type=3
Dn Slope=0.005

--- WILKERSON SPRING BRANCH.g01 (geometry) ---

Geom Title=Existing Conditions

River Reach=WILKERSON SPRING,Reach-1
Reach XY= 30
      3605349.00     10544731.00      3605441.50     10544613.00
      3605615.75     10544553.00      3605649.50     10544456.00
      3605524.75     10544177.00      3605398.25     10544114.00
      3605292.00     10543949.00      3605235.00     10543507.00
      3605153.75     10543422.00      3605007.00     10543405.00
      3604942.00     10543309.00      3604972.50     10543234.00
      3605192.50     10543087.00      3605215.00     10542887.00
      3605135.75     10542798.00      3605014.25     10542770.00
      3604831.50     10543035.00      3604711.25     10543087.00
      3604494.50     10542943.00      3604300.00     10542671.00
      3604148.75     10542624.00      3604012.00     10542378.00
      3603919.75     10542443.00      3603701.50     10542335.00
      3603699.50     10540606.00      3604028.25     10539854.00
      3604075.25     10538988.00      3603896.50     10537690.00
      3603897.25     10537236.00      3603418.25     10537275.00

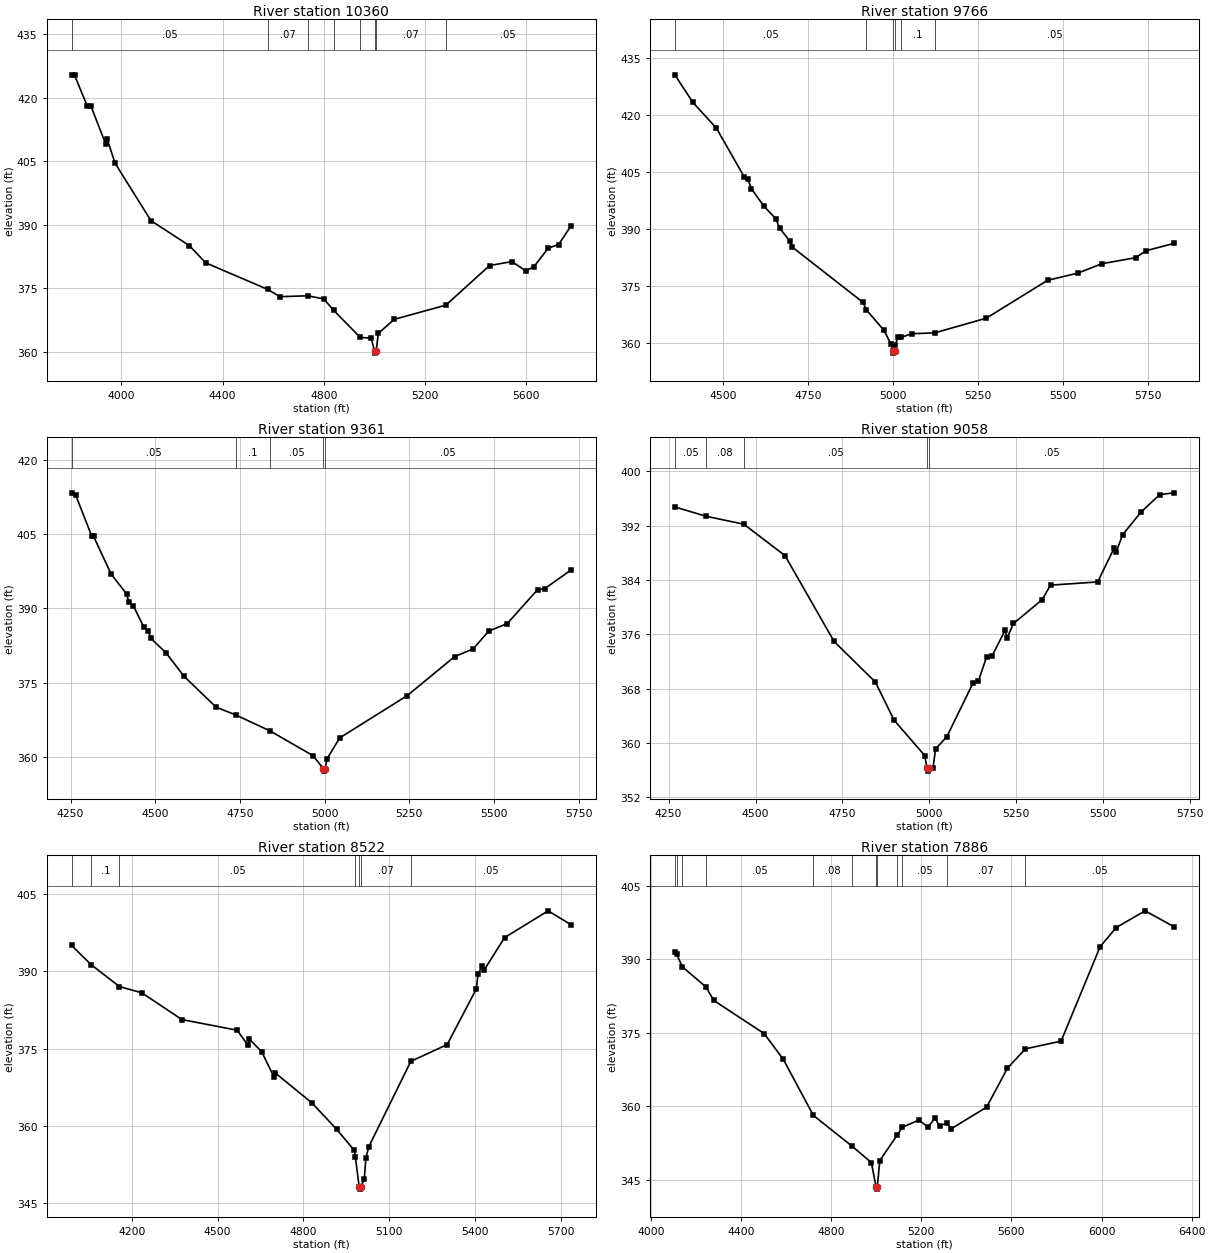
Type RM Length L Ch R = 1,10360,594,594,594
BEGIN DESCRIPTION:
WILKERSON SPRING BRANCH 10.0
END DESCRIPTION:
XS GIS Cut Line= 3
      3606518.14     10545047.88      3605483.38     10544714.53
      3604677.81     10544346.47
#Sta/Elev= 30
  3802.9  425.44  3814.4  425.36  3864.4  418.11  3878.5  418.16  3937.4  409.11
  3942.7  410.36  3974.7  404.53  4116.5  390.95  4268.6  385.03  4332.7  380.98
  4578.1  374.69  4626.5  372.97  4736.1  373.18  4799.4  372.45  4838.7  369.75
  4943.4  363.34  4986.2  363.17  5000.7  360.12  5003.4  359.62  5006.7  360.12
  5015.1  364.29  5078.3  367.61  5282.2  370.97  5454.9  380.33  5543.2  381.27
  5597.8  379.09  5629.9  380.04  5686.9  384.46  5727.5  385.29  5775.7  389.61
#Mann=8,-1,0
  3802.9    0.05       0  4578.1    0.07       0  4736.1    0.05       0
  4838.7    0.16       0  4943.4    0.07       0  5000.7    0.07       0
  5006.7    0.07       0  5282.2    0.05       0
Bank Sta=5000.7,5006.7
Exp/Cntr=0.3,0.1

Type RM Length L Ch R = 1,9766,405,405,405
BEGIN DESCRIPTION:
WILKERSON SPRING BRANCH 9.0
END DESCRIPTION:
XS GIS Cut Line= 3
      3606198.66     10544103.42      3605549.61     10544260.19
      3604747.30     10544249.25
#Sta/Elev= 30
  4356.8  430.57  4409.7  423.34  4479.3  416.53  4561.6  403.63  4571.9  403.03
  4582.3  400.58  4619.0  395.99  4654.2  392.66  4666.0  390.12  4695.3  386.82
  4702.8  385.18  4911.4  370.60  4920.7  368.68  4973.1  363.23  4993.7  359.56
  4998.0  357.75  5000.8  357.25  5004.0  357.75  5006.2  359.48  5014.2  361.38
  5023.4  361.40  5054.5  362.36  5122.3  362.59  5274.5  366.46  5454.6  376.43
  5544.6  378.34  5614.6  380.81  5714.6  382.40  5744.6  384.22  5826.9  386.16
#Mann=6,-1,0
  4356.8    0.05       0  4920.7    0.08       0  4998.0    0.07       0
  5004.0    0.08       0  5023.4     0.1       0  5122.3    0.05       0
Bank Sta=4998,5004
Exp/Cntr=0.3,0.1

Type RM Length L Ch R = 1,9361,303,303,303
BEGIN DESCRIPTION:
WILKERSON SPRING BRANCH 8.0
END DESCRIPTION:
XS GIS Cut Line= 3
      3606038.93     10544027.03      3605525.04     10543929.81
      3604594.54     10544124.24
#Sta/Elev= 30
  4253.1  413.30  4265.3  412.81  4312.6  404.56  4317.7  404.56  4370.0  396.89
  4415.2  392.95  4422.4  391.30  4435.6  390.48  4466.1  386.27  4479.8  385.48
  4486.5  384.01  4532.1  381.04  4584.5  376.35  4679.9  370.09  4737.1  368.55
  4838.2  365.34  4965.5  360.34  4996.6  357.71  4999.4  357.21  5002.6  357.71
  5006.4  359.60  5044.5  363.90  5244.4  372.45  5384.2  380.31  5439.3  381.87
  5484.2  385.42  5539.3  386.95  5629.0  393.80  5650.0  393.98  5726.7  397.71
#Mann=5,-1,0
  4253.1    0.05       0  4737.1     0.1       0  4838.2    0.05       0
  4996.6   0.035       0  5002.6    0.05       0
Bank Sta=4996.6,5002.6
Exp/Cntr=0.3,0.1

Type RM Length L Ch R = 1,9058,536,536,536
BEGIN DESCRIPTION:
WILKERSON SPRING BRANCH 7.0
END DESCRIPTION:
XS GIS Cut Line= 2
      3605962.56     10543402.03      3604636.14     10543950.65
#Sta/Elev= 30
  4267.9  394.76  4357.6  393.39  4466.4  392.22  4584.8  387.59  4726.0  374.94
  4844.6  368.97  4898.7  363.33  4986.7  358.13  4993.1  356.34  4995.9  355.84
  4999.1  356.34  5010.6  356.37  5017.8  359.11  5050.2  360.91  5126.0  368.86
  5140.9  369.10  5164.8  372.71  5180.1  372.80  5218.0  376.61  5223.4  375.46
  5241.9  377.59  5324.5  381.10  5348.4  383.24  5484.1  383.71  5531.9  388.77
  5537.3  388.13  5555.8  390.67  5609.0  394.02  5662.3  396.57  5703.3  396.84
#Mann=5,-1,0
  4267.9    0.05       0  4357.6    0.08       0  4466.4    0.05       0
  4993.1   0.035       0  4999.1    0.05       0
Bank Sta=4993.1,4999.1
Exp/Cntr=0.3,0.1

Type RM Length L Ch R = 1,8522,636,636,636
BEGIN DESCRIPTION:
WILKERSON SPRING BRANCH 5.0
END DESCRIPTION:
XS GIS Cut Line= 4
      3605955.55     10543242.31      3605455.60     10543228.42
      3604879.21     10543360.37      3604511.17     10543902.01
#Sta/Elev= 30
  3989.0  394.95  4057.3  391.23  4156.1  387.00  4235.0  385.77  4375.1  380.60
  4568.3  378.54  4606.1  375.61  4611.2  376.80  4654.1  374.37  4697.0  369.49
  4702.2  370.23  4830.9  364.41  4915.9  359.38  4977.5  355.32  4982.0  353.90
  4995.0  348.27  4997.7  347.77  5001.0  348.27  5012.9  349.71  5018.5  353.77
  5028.7  355.97  5175.9  372.52  5303.0  375.76  5404.8  386.52  5410.8  389.37
  5425.8  391.06  5431.8  390.14  5503.7  396.47  5656.3  401.66  5735.3  399.01
#Mann=7,-1,0
  3989.0    0.08       0  4057.3     0.1       0  4156.1    0.05       0
  4982.0    0.07       0  4995.0    0.07       0  5001.0    0.07       0
  5175.9    0.05       0
Bank Sta=4995,5001
Exp/Cntr=0.3,0.1

Type RM Length L Ch R = 1,7886,887,887,887
BEGIN DESCRIPTION:
WILKERSON SPRING BRANCH 4.0
END DESCRIPTION:
XS GIS Cut Line= 5
      3606025.08     10543047.88      3605358.38     10542790.92
      3605059.76     10542922.87      3604393.10     10543881.20
      3604386.18     10543881.20
#Sta/Elev= 30
  4106.0  391.47  4113.9  391.07  4139.1  388.48  4243.5  384.39  4279.1  381.59
  4502.9  374.82  4587.5  369.56  4721.2  358.10  4893.4  351.80  4978.6  348.47
  4998.9  343.55  5001.7  343.05  5004.9  343.55  5015.9  348.89  5092.6  354.06
  5116.4  355.70  5188.7  357.15  5230.6  355.73  5260.2  357.58  5281.2  355.93
  5313.9  356.57  5331.8  355.36  5489.8  359.79  5582.3  367.75  5662.0  371.71
  5820.6  373.29  5993.4  392.55  6065.0  396.49  6193.3  399.91  6321.3  396.67
#Mann=12,-1,0
  4106.0    0.16       0  4113.9    0.05       0  4139.1     0.1       0
  4243.5    0.05       0  4721.2    0.08       0  4893.4    0.05       0
  4998.9   0.035       0  5004.9    0.05       0  5092.6    0.16       0
  5116.4    0.05       0  5313.9    0.07       0  5662.0    0.05       0
Bank Sta=4998.9,5004.9
Exp/Cntr=0.3,0.1

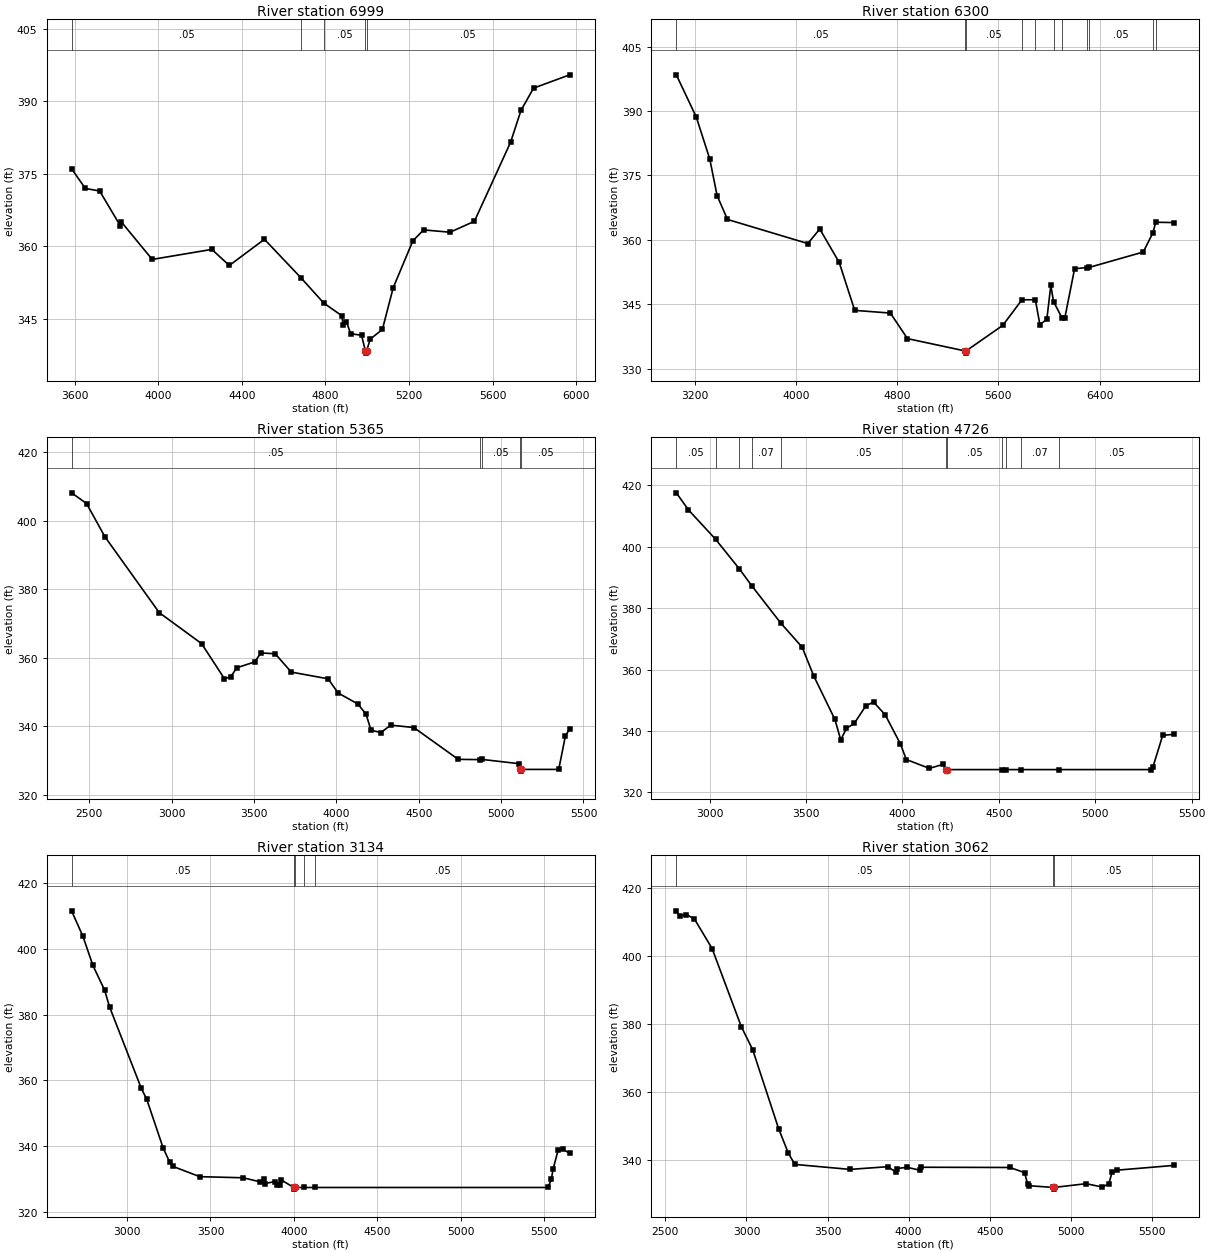
Type RM Length L Ch R = 1,6999,699,699,699
BEGIN DESCRIPTION:
WILKERSON SPRING BRANCH 3.0
END DESCRIPTION:
XS GIS Cut Line= 4
      3605733.14     10542662.43      3604816.01     10542556.00
      3604354.06     10543282.90      3604356.32     10543882.95
#Sta/Elev= 30
  3584.3  376.06  3650.2  371.99  3718.7  371.46  3817.5  364.28  3822.5  365.07
  3970.4  357.32  4255.8  359.39  4339.5  356.07  4507.6  361.48  4683.5  353.48
  4791.7  348.30  4878.5  345.68  4884.4  343.79  4899.7  344.48  4920.8  341.97
  4972.5  341.65  4990.7  338.46  4993.4  337.96  4996.7  338.46  5014.8  340.88
  5072.4  342.85  5124.1  351.46  5218.1  361.15  5269.8  363.42  5396.1  362.94
  5513.0  365.20  5686.1  381.53  5736.1  388.13  5796.1  392.71  5968.9  395.46
#Mann=5,-1,0
  3584.3    0.05       0  4683.5     0.1       0  4791.7    0.05       0
  4990.7    0.04       0  4996.7    0.05       0
Bank Sta=4990.7,4996.7
Exp/Cntr=0.3,0.1

Type RM Length L Ch R = 1,6300,935,935,935
BEGIN DESCRIPTION:
Mapping XS 8539fb3e
END DESCRIPTION:
XS GIS Cut Line= 4
      3605983.38     10542665.92      3604636.15     10542346.48
      3603990.32     10542533.98      3603212.52     10544249.29
#Sta/Elev= 30
  3051.7  398.43  3209.7  388.58  3316.3  378.81  3374.2  370.30  3456.4  364.74
  4091.8  359.13  4186.5  362.51  4340.2  354.74  4463.1  343.56  4745.1  342.93
  4880.4  336.98  5337.6  334.10  5340.4  333.60  5343.6  334.10  5634.1  340.06
  5786.1  346.02  5892.0  346.04  5928.1  340.25  5983.0  341.48  6014.5  349.39
  6035.8  345.62  6103.6  341.76  6125.8  341.89  6202.6  353.26  6297.9  353.53
  6315.3  353.55  6745.6  357.15  6822.1  361.62  6844.5  364.09  6992.2  364.01
#Mann=11,-1,0
  3051.7    0.05       0  5337.6    0.03       0  5343.6    0.05       0
  5786.1    0.07       0  5892.0    0.12       0  6035.8    0.07       0
  6103.6    0.05       0  6297.9     0.1       0  6315.3    0.05       0
  6822.1     0.1       0  6844.5    0.05       0
Bank Sta=5337.6,5343.6
Exp/Cntr=0.3,0.1

Type RM Length L Ch R = 1,5365,639,639,639
BEGIN DESCRIPTION:
Mapping XS 3888d757
END DESCRIPTION:
XS GIS Cut Line= 3
      3606129.23     10542624.27      3604893.10     10541936.75
      3603283.32     10541950.63
#Sta/Elev= 30
  2391.9  408.19  2483.0  405.06  2593.7  395.41  2924.2  373.21  3181.0  364.18
  3319.9  353.93  3357.7  354.44  3395.4  357.11  3504.0  358.82  3541.8  361.45
  3628.7  361.19  3725.9  355.85  3949.9  353.88  4009.9  349.76  4129.9  346.54
  4179.9  343.58  4209.9  338.89  4269.9  338.19  4329.9  340.36  4469.9  339.66
  4739.9  330.37  4870.0  330.29  4883.7  330.35  5109.9  329.10  5116.9  327.43
  5119.6  326.93  5122.9  327.43  5349.9  327.43  5389.9  337.08  5416.2  339.30
#Mann=5,-1,0
  2391.9    0.05       0  4870.0    0.12       0  4883.7    0.05       0
  5116.9    0.03       0  5122.9    0.05       0
Bank Sta=5116.9,5122.9
Exp/Cntr=0.3,0.1

Type RM Length L Ch R = 1,4726,1592,1592,1592
BEGIN DESCRIPTION:
Mapping XS 5fdf49c7
END DESCRIPTION:
XS GIS Cut Line= 2
      3605872.23     10541290.92      3603288.91     10541311.75
#Sta/Elev= 30
  2827.2  417.55  2889.8  412.02  3031.2  402.40  3154.7  392.74  3218.0  387.32
  3369.0  375.13  3479.8  367.29  3539.8  357.95  3649.8  343.75  3679.8  337.12
  3709.8  340.86  3749.9  342.45  3809.9  348.17  3849.9  349.43  3909.9  345.35
  3989.9  335.74  4019.9  330.71  4139.9  327.82  4209.9  329.12  4226.9  327.43
  4229.6  326.93  4232.9  327.43  4516.3  327.43  4535.8  327.43  4615.2  327.43
  4813.0  327.43  5289.9  327.43  5299.9  328.40  5349.9  338.57  5410.6  338.94
#Mann=11,-1,0
  2827.2    0.05       0  3031.2    0.07       0  3154.7    0.05       0
  3218.0    0.07       0  3369.0    0.05       0  4226.9    0.03       0
  4232.9    0.05       0  4516.3    0.07       0  4535.8    0.05       0
  4615.2    0.07       0  4813.0    0.05       0
Bank Sta=4226.9,4232.9
Exp/Cntr=0.3,0.1

Type RM Length L Ch R = 1,3134,72,72,72
BEGIN DESCRIPTION:
WILKERSON SPRING BRANCH 2.0
END DESCRIPTION:
XS GIS Cut Line= 4
      3605907.42     10540471.48      3604674.78     10540454.12
      3604414.36     10539777.03      3603390.09     10539803.07
#Sta/Elev= 30
  2668.2  411.56  2736.0  403.84  2796.0  394.95  2866.0  387.45  2896.0  382.30
  3086.1  357.54  3117.9  354.31  3216.1  339.53  3256.1  335.05  3276.1  333.82
  3436.1  330.72  3696.1  330.38  3796.1  329.16  3822.9  329.98  3827.9  328.64
  3886.1  329.24  3896.0  328.18  3915.9  328.31  3925.3  329.68  3998.6  327.43
  4001.3  326.93  4004.6  327.43  4059.5  327.43  4127.8  327.43  5521.4  327.43
  5541.4  329.91  5551.5  332.94  5581.5  338.70  5611.5  339.10  5651.0  337.77
#Mann=5,-1,0
  2668.2    0.05       0  3998.6   0.033       0  4004.6    0.05       0
  4059.5    0.08       0  4127.8    0.05       0
Bank Sta=3998.6,4004.6
Exp/Cntr=0.3,0.1

Type RM Length L Ch R = 1,3062,86,86,86
BEGIN DESCRIPTION:
Mapping XS 0b98b091
END DESCRIPTION:
XS GIS Cut Line= 4
      3606030.29     10540362.10      3604733.38     10540367.31
      3604504.21     10539721.48      3603415.64     10539705.85
#Sta/Elev= 30
  2567.8  413.28  2588.5  411.70  2628.5  412.19  2678.5  410.96  2788.5  402.19
  2968.5  379.24  3038.5  372.48  3198.5  349.27  3258.5  342.05  3298.5  338.76
  3638.5  337.30  3872.3  338.09  3920.4  336.52  3925.7  337.53  3989.0  337.91
  4069.5  337.07  4074.8  337.93  4624.6  337.86  4714.6  336.35  4734.6  332.91
  4744.6  332.49  4891.7  332.00  4894.4  331.50  4897.7  332.00  5094.7  333.10
  5194.7  332.10  5234.7  333.09  5254.7  336.54  5284.7  337.07  5638.7  338.48
#Mann=3,-1,0
  2567.8    0.05       0  4891.7    0.03       0  4897.7    0.05       0
Bank Sta=4891.7,4897.7
Exp/Cntr=0.3,0.1

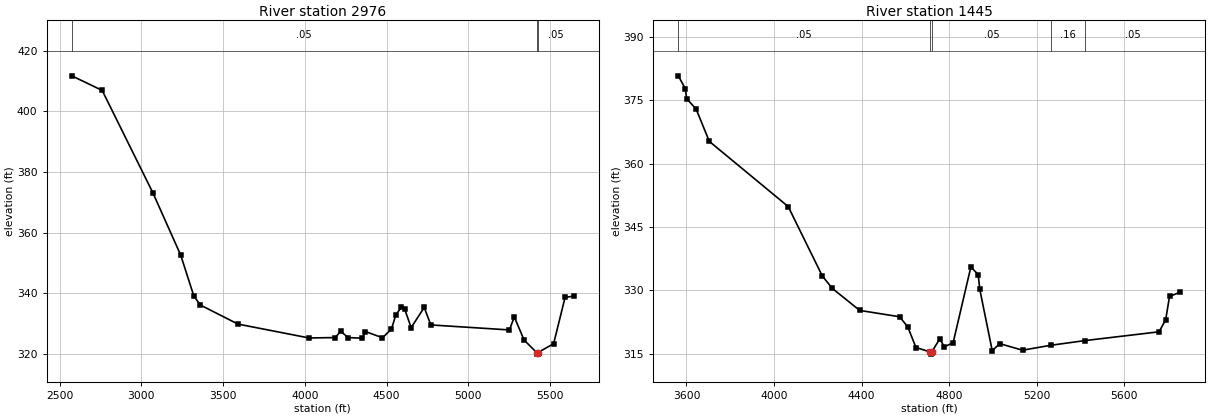
Type RM Length L Ch R = 1,2976,1531,1531,1531
BEGIN DESCRIPTION:
Mapping XS b99df59d
END DESCRIPTION:
XS GIS Cut Line= 4
      3606035.42     10540315.23      3604785.46     10540289.18
      3604582.33     10539658.98      3603426.09     10539596.48
#Sta/Elev= 30
  2574.5  411.73  2760.4  406.92  3070.4  373.16  3240.5  352.62  3320.5  339.18
  3360.5  336.15  3590.5  329.85  4025.8  325.27  4186.1  325.40  4218.2  327.49
  4265.0  325.39  4351.7  325.19  4370.0  327.39  4474.6  325.35  4529.7  328.21
  4555.9  332.86  4589.7  335.40  4609.8  334.88  4649.8  328.67  4729.9  335.35
  4770.0  329.57  5250.7  327.92  5280.7  332.20  5340.8  324.56  5418.0  320.44
  5420.7  319.94  5424.0  320.44  5521.1  323.37  5591.2  338.66  5644.8  339.07
#Mann=3,-1,0
  2574.5    0.05       0  5418.0    0.03       0  5424.0    0.05       0
Bank Sta=5418,5424
Exp/Cntr=0.3,0.1

Type RM Length L Ch R = 1,1445,0,0,0
BEGIN DESCRIPTION:
WILKERSON SPRING BRANCH 1.0
END DESCRIPTION:
XS GIS Cut Line= 3
      3605268.12     10538603.43      3604281.99     10538068.70
      3603123.48     10538242.13
#Sta/Elev= 30
  3562.5  380.82  3594.9  377.79  3600.7  375.43  3644.4  372.93  3704.3  365.29
  4064.7  349.84  4220.6  333.39  4266.1  330.45  4391.2  325.23  4573.2  323.73
  4610.4  321.37  4648.4  316.43  4714.0  315.37  4716.8  314.87  4720.0  315.37
  4757.5  318.51  4777.7  316.60  4818.1  317.58  4899.0  335.52  4932.6  333.72
  4939.5  330.30  4996.7  315.67  5030.5  317.36  5135.0  315.80  5265.6  316.98
  5419.0  318.07  5758.5  320.16  5788.8  323.00  5806.4  328.54  5855.7  329.56
#Mann=5,-1,0
  3562.5    0.05       0  4714.0    0.03       0  4720.0    0.05       0
  5265.6    0.16       0  5419.0    0.05       0
Bank Sta=4714,4720
Exp/Cntr=0.3,0.1

Chan Stop Cuts=-1