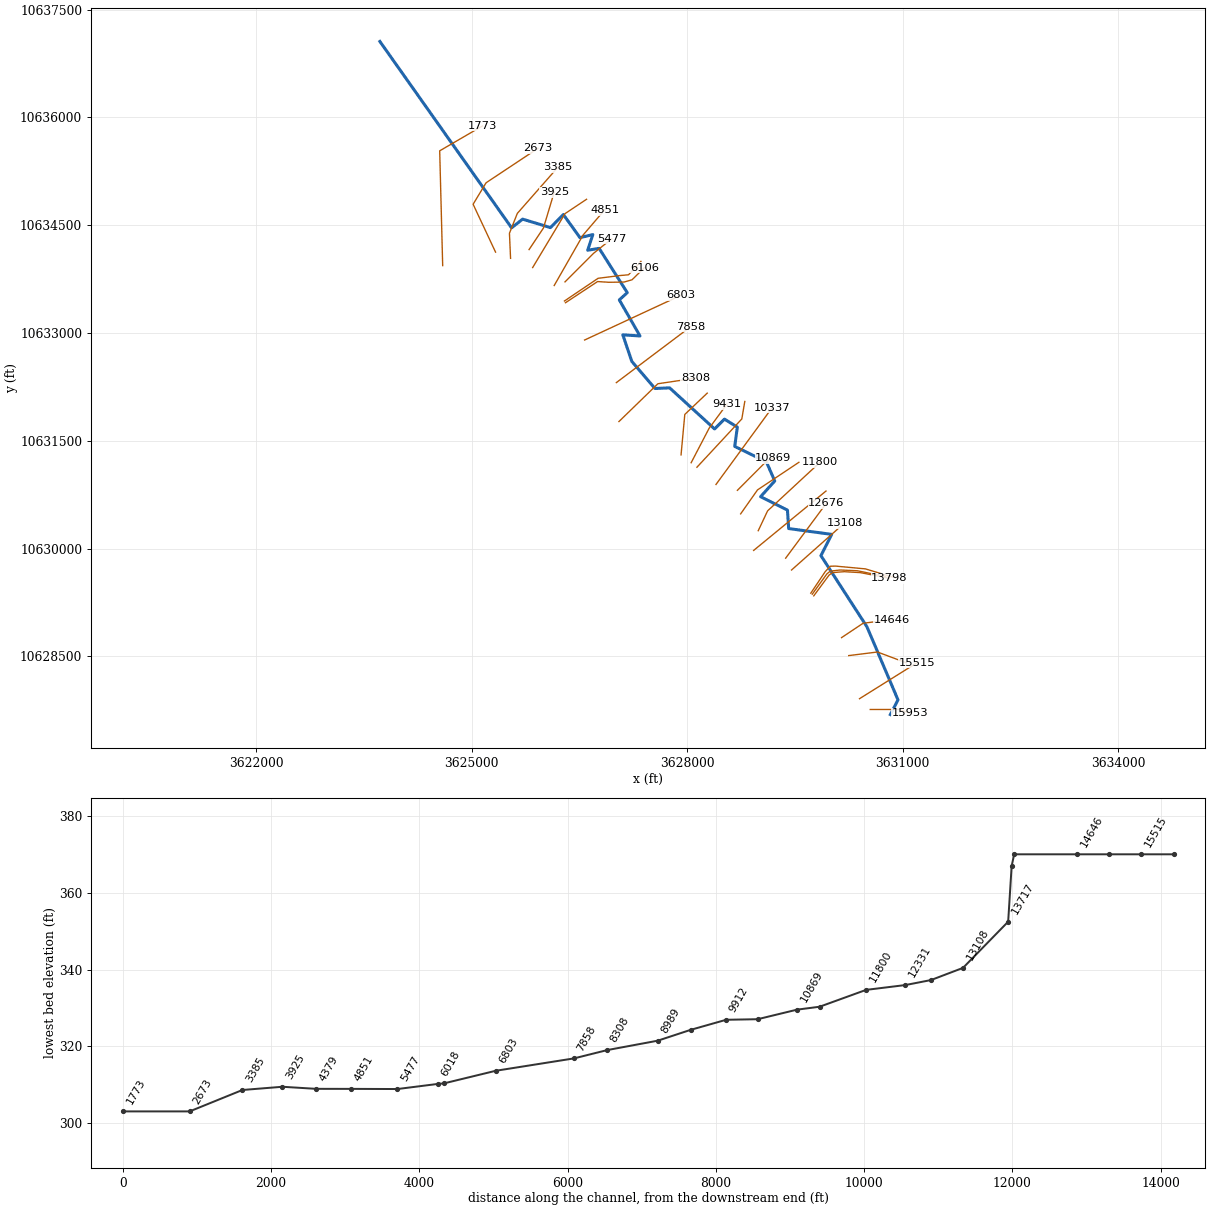
--- BALL BRANCH.prj (project) ---

Proj Title=BALL BRANCH Base Level Engineering
Current Plan=p01
Default Exp/Contr=0.3,0.1
English Units
Geom File=g01
Flow File=f01
Plan File=p01
Y Axis Title=Elevation
X Axis Title(PF)=Main Channel Distance
X Axis Title(XS)=Station
BEGIN DESCRIPTION:
BALL BRANCH
END DESCRIPTION:
DSS Export Rating Curves= 0
DSS Export Rating Curve Sorted= 0
DSS Export Volume Flow Curves= 0
DXF OffsetX= 0
DXF OffsetY= 0
DXF ScaleX= 1
DXF ScaleY= 10

--- BALL BRANCH.p01 (plan) ---

Plan Title=Multiple Run
Short Identifier=Multiple
Geom File=g01
Flow File=f01
Subcritical Flow
K Sum by GR= 0
Std Step Tol= 0.01
Critical Tol= 0.01
Num of Std Step Trials= 20
Max Error Tol= 0.3
Flow Tol Ratio= 0.001
Split Flow NTrial= 30
Split Flow Tol= 0.02
Split Flow Ratio= 0.02
Log Output Level= 0
Friction Slope Method= 1
Unsteady Friction Slope Method= 2
Unsteady Bridges Friction Slope Method= 1
Parabolic Critical Depth
Global Vel Dist=  1 , 1 , 1
Global Log Level= 0
CheckData=True
Encroach Param= -1, 0, 0, 0
BEGIN DESCRIPTION:
Multiple Run
END DESCRIPTION:

--- BALL BRANCH.f01 (steady flow) ---

Flow Title=Multiple
Number of Profiles=7
Profile Names=10-year,25-year,50-year,1pct_min,100-year,1pct_plu,500-year
River Rch & RM= BALL BRANCH,Reach-1,15953
    2655    3819    4825    4446    6013    8131    9307
River Rch & RM= BALL BRANCH,Reach-1,7858
    3070    4423    5593    5151    6966    9421   10776
Boundary for River Rch & Prof#=BALL BRANCH,Reach-1,1
Up Type=0
Dn Type=3
Dn Slope=0.005
Boundary for River Rch & Prof#=BALL BRANCH,Reach-1,2
Up Type=0
Dn Type=3
Dn Slope=0.005
Boundary for River Rch & Prof#=BALL BRANCH,Reach-1,3
Up Type=0
Dn Type=3
Dn Slope=0.005
Boundary for River Rch & Prof#=BALL BRANCH,Reach-1,4
Up Type=0
Dn Type=3
Dn Slope=0.005
Boundary for River Rch & Prof#=BALL BRANCH,Reach-1,5
Up Type=0
Dn Type=3
Dn Slope=0.005
Boundary for River Rch & Prof#=BALL BRANCH,Reach-1,6
Up Type=0
Dn Type=3
Dn Slope=0.005
Boundary for River Rch & Prof#=BALL BRANCH,Reach-1,7
Up Type=0
Dn Type=3
Dn Slope=0.005

--- BALL BRANCH.g01 (geometry) ---

Geom Title=Existing Conditions
Program Version=4.10

River Reach=BALL BRANCH     ,Reach-1
Reach XY= 30
       3630829.5       10627690.      3630935.25       10627894.
      3630503.25       10628911.      3629862.75       10629901.
      3630012.25       10630197.       3629413.5       10630278.
      3629396.75       10630534.       3629022.5       10630721.
      3629219.25       10630940.        3629103.       10631207.
       3628662.5       10631421.        3628699.       10631689.
      3628519.75       10631801.        3628382.       10631664.
        3627756.       10632236.        3627552.       10632227.
       3627229.5       10632605.       3627104.5       10632974.
      3627343.75       10632958.      3627055.75       10633460.
      3627166.75       10633561.        3626775.       10634177.
       3626615.5       10634151.        3626687.       10634369.
        3626508.       10634326.        3626277.       10634648.
      3626096.75       10634466.      3625709.75       10634584.
        3625556.       10634463.      3623722.25       10637057.

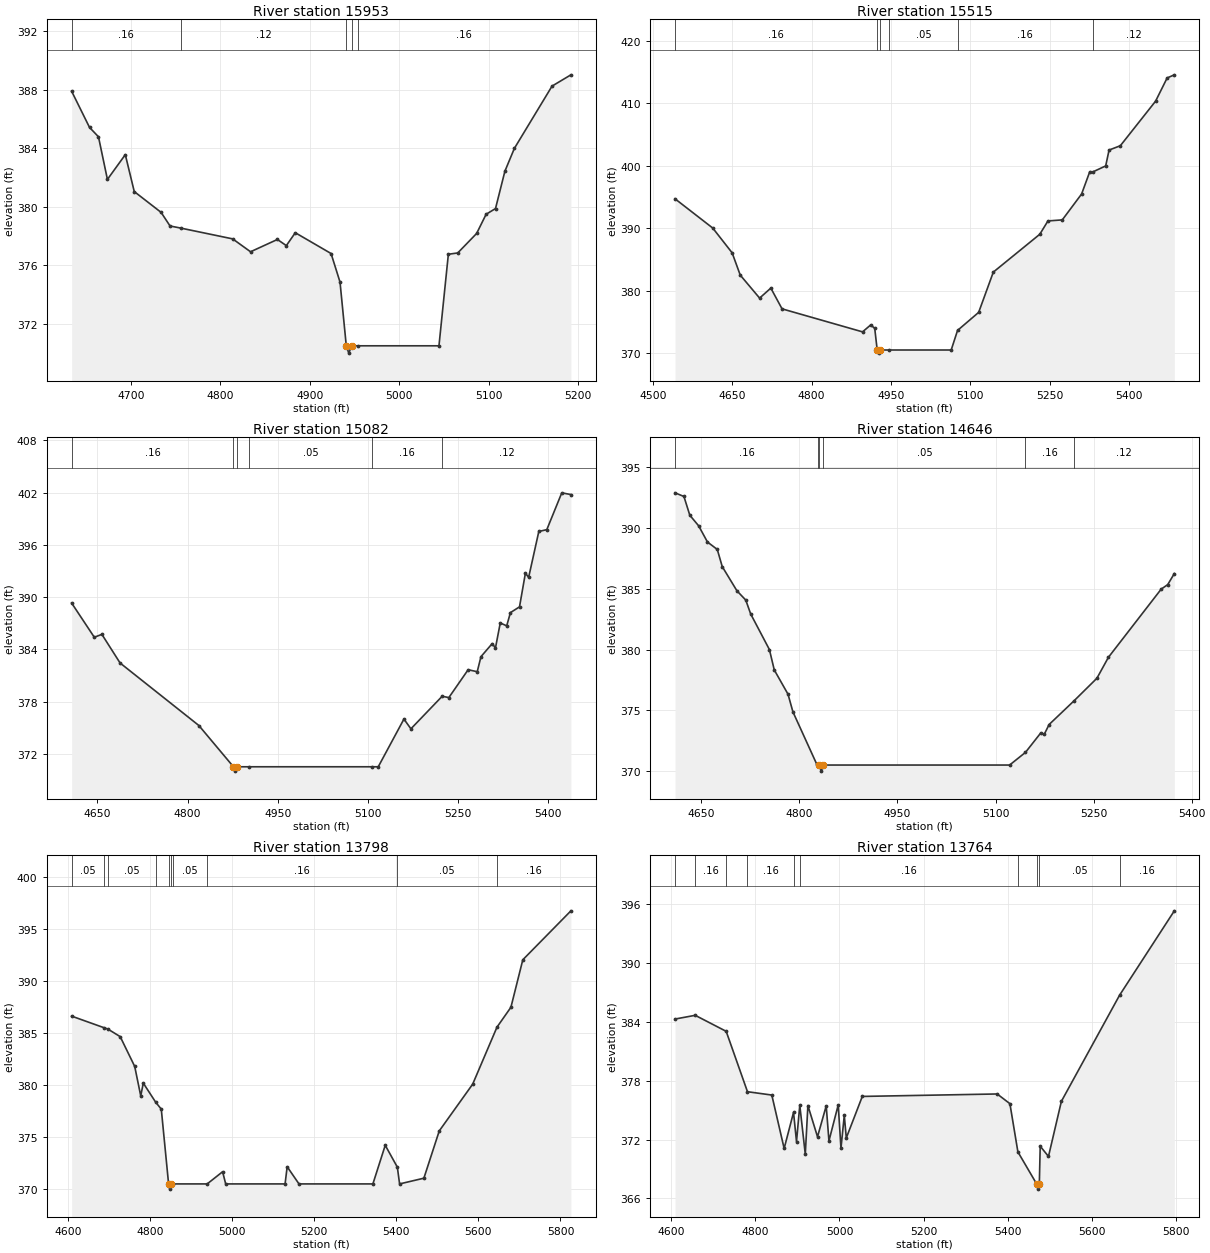
Type RM Length L Ch R = 1 ,15953   ,438,438,438
BEGIN DESCRIPTION:
BALL BRANCH 29.0
END DESCRIPTION:
XS GIS Cut Line= 3
       3630549.6     10627760.19      3630949.61     10627760.19
      3631099.58      10627710.2
#Sta/Elev= 30
  4633.9  387.89  4653.9  385.42  4663.9  384.78  4673.9  381.87  4693.9  383.56
  4703.9  381.04  4733.9  379.62  4743.9  378.69  4755.6  378.55  4813.9  377.81
  4833.9  376.93  4863.9  377.77  4873.9  377.35  4883.9  378.23  4923.9  376.81
  4933.9  374.86  4940.9  370.51  4943.7  370.01  4946.9  370.51  4953.5  370.51
  5044.5  370.51    5055  376.76  5065.5  376.85  5086.6  378.18  5097.2  379.49
  5107.7  379.88  5118.2  382.43  5128.8  383.99  5170.9  388.24    5192  389.01
#Mann= 5 ,-1 , 0
  4633.9     .16       0  4755.6     .12       0  4940.9     .07       0
  4946.9     .12       0  4953.5     .16       0
Bank Sta=4940.9,4946.9
XS Rating Curve= 0 ,0
Exp/Cntr=0.3,0.1

Type RM Length L Ch R = 1 ,15515   ,433,433,433
BEGIN DESCRIPTION:
BALL BRANCH 28.0
END DESCRIPTION:
XS GIS Cut Line= 3
      3630399.63      10627910.2      3630799.61     10628160.19
      3631199.64     10628410.21
#Sta/Elev= 30
  4542.1  394.69  4613.4  390.01    4650  386.05  4665.3  382.49  4701.9  378.81
  4723.1  380.41  4744.3  377.09  4896.4  373.41  4911.8  374.52  4919.4  373.98
  4924.1  370.51  4926.8  370.01  4930.1  370.51  4946.9  370.51  5063.9  370.51
  5075.9  373.64  5115.8  376.53  5143.5  382.97  5231.3  389.02  5246.7  391.15
  5273.8  391.32  5310.3  395.46  5325.7  399.02  5331.7     399  5355.8  399.95
  5362.2  402.49  5383.5  403.18  5450.1  410.31  5471.9  414.02  5485.5  414.52
#Mann= 6 ,-1 , 0
  4542.1     .16       0  4924.1    .033       0  4930.1     .16       0
  4946.9     .05       0  5075.9     .16       0  5331.7     .12       0
Bank Sta=4924.1,4930.1
XS Rating Curve= 0 ,0
Exp/Cntr=0.3,0.1

Type RM Length L Ch R = 1 ,15082   ,436,436,436
BEGIN DESCRIPTION:
BALL BRANCH 27.0
END DESCRIPTION:
XS GIS Cut Line= 3
      3630249.66     10628510.19      3630649.61     10628560.19
      3631049.64     10628410.18
#Sta/Elev= 30
  4607.3  389.32    4645  385.39  4657.6  385.72  4687.9  382.43  4818.9  375.25
  4876.4  370.51  4879.1  370.01  4882.4  370.51  4901.6  370.51  5107.3  370.51
  5117.2  370.51  5159.9  375.99  5171.5  374.87  5223.5  378.61  5234.6  378.46
  5266.7  381.66  5281.8  381.43    5288  383.16  5306.7  384.66  5312.1  384.16
  5320.1  387.03  5330.8   386.7    5337  388.22  5352.1  388.88  5361.9  392.75
  5367.3  392.27  5384.2  397.54  5397.5  397.75  5422.4  401.98  5437.6  401.78
#Mann= 6 ,-1 , 0
  4607.3     .16       0  4876.4    .033       0  4882.4     .16       0
  4901.6     .05       0  5107.3     .16       0  5223.5     .12       0
Bank Sta=4876.4,4882.4
XS Rating Curve= 0 ,0
Exp/Cntr=0.3,0.1

Type RM Length L Ch R = 1 ,14646   ,848,848,848
BEGIN DESCRIPTION:
BALL BRANCH 26.0
END DESCRIPTION:
XS GIS Cut Line= 3
      3630149.58     10628760.17      3630449.61     10628960.19
       3630849.6     10629010.19
#Sta/Elev= 30
  4609.8  392.87  4623.4  392.57  4632.4  391.03  4645.9  390.16  4659.4  388.83
  4674.4  388.22    4682  386.81  4704.5  384.82    4718  384.06  4725.5  382.92
  4754.1     380  4761.6  378.32  4782.6  376.33  4790.1  374.88  4826.2  370.62
  4828.9  370.55  4830.7  370.51  4833.4  370.01  4836.7  370.51  5121.6  370.51
  5145.8  371.55  5169.4  373.16  5174.5  373.03    5182  373.84  5220.2  375.79
  5255.1  377.64  5272.7  379.36  5353.4  384.96  5363.4  385.33  5373.5  386.24
#Mann= 6 ,-1 , 0
  4609.8     .16       0  4828.9     .05       0  4830.7    .033       0
  4836.7     .05       0  5145.8     .16       0  5220.2     .12       0
Bank Sta=4830.7,4836.7
XS Rating Curve= 0 ,0
Exp/Cntr=0.3,0.1

Type RM Length L Ch R = 1 ,13798   ,34,34,34
BEGIN DESCRIPTION:
BALL BRANCH 25.0
END DESCRIPTION:
XS GIS Cut Line= 6
       3629762.9     10629341.84      3629976.47     10629630.94
      3630023.34     10629664.79       3630184.8     10629677.81
      3630411.36     10629664.79      3630814.77     10629586.71
#Sta/Elev= 30
  4608.2  386.62  4687.7   385.5  4696.5  385.38  4726.6  384.65    4762  381.79
  4776.7  378.96  4782.9  380.19  4813.2  378.35  4826.8  377.69  4844.6  370.51
  4847.4  370.01  4850.6  370.51  4854.6  370.51  4938.7  370.51  4976.3  371.68
  4983.8  370.51  5128.6  370.51  5133.7  372.16  5162.5  370.51  5342.7  370.51
  5372.8  374.22  5402.3  372.12  5407.8  370.51    5467  371.06  5504.5   375.6
    5586  380.09  5645.2  385.56  5679.2  387.47  5708.2  392.03  5825.5  396.73
#Mann= 10 ,-1 , 0
  4608.2     .05       0  4687.7     .16       0  4696.5     .05       0
  4813.2     .16       0  4844.6     .07       0  4850.6     .16       0
  4854.6     .05       0  4938.7     .16       0  5402.3     .05       0
  5645.2     .16       0
Bank Sta=4844.6,4850.6
XS Rating Curve= 0 ,0
Exp/Cntr=0.3,0.1

Type RM Length L Ch R = 1 ,13764   ,47,47,47
BEGIN DESCRIPTION:
Mapping XS 41107421
END DESCRIPTION:
XS GIS Cut Line= 6
      3629742.08      10629365.3      3629945.22     10629646.56
      3629992.09     10629685.63      3630130.11     10629701.25
       3630369.7     10629690.83      3630762.95      10629610.1
#Sta/Elev= 30
  4608.6  384.27  4656.6  384.65  4730.3  383.02    4781  376.87  4838.9  376.53
  4868.3  371.09  4890.6  374.76  4897.7  371.79  4905.5  375.49  4918.6   370.5
  4924.8  375.46  4947.7  372.28  4968.4  375.43  4974.9  371.86    4997  375.53
  5003.5  371.11  5011.4  374.45  5016.2  372.16  5054.3  376.39  5375.3  376.64
  5405.6  375.65  5424.6  370.74  5469.6  367.45  5472.3  366.95  5475.6  367.45
  5477.7  371.32  5497.4  370.28  5528.1  375.89  5666.5  386.69  5796.9  395.29
#Mann= 10 ,-1 , 0
  4608.6     .05       0  4656.6     .16       0  4730.3     .05       0
    4781     .16       0  4890.6     .05       0  4905.5     .16       0
  5424.6     .05       0  5469.6     .07       0  5475.6     .05       0
  5666.5     .16       0
Bank Sta=5469.6,5475.6
XS Rating Curve= 0 ,0
Exp/Cntr=0.3,0.1

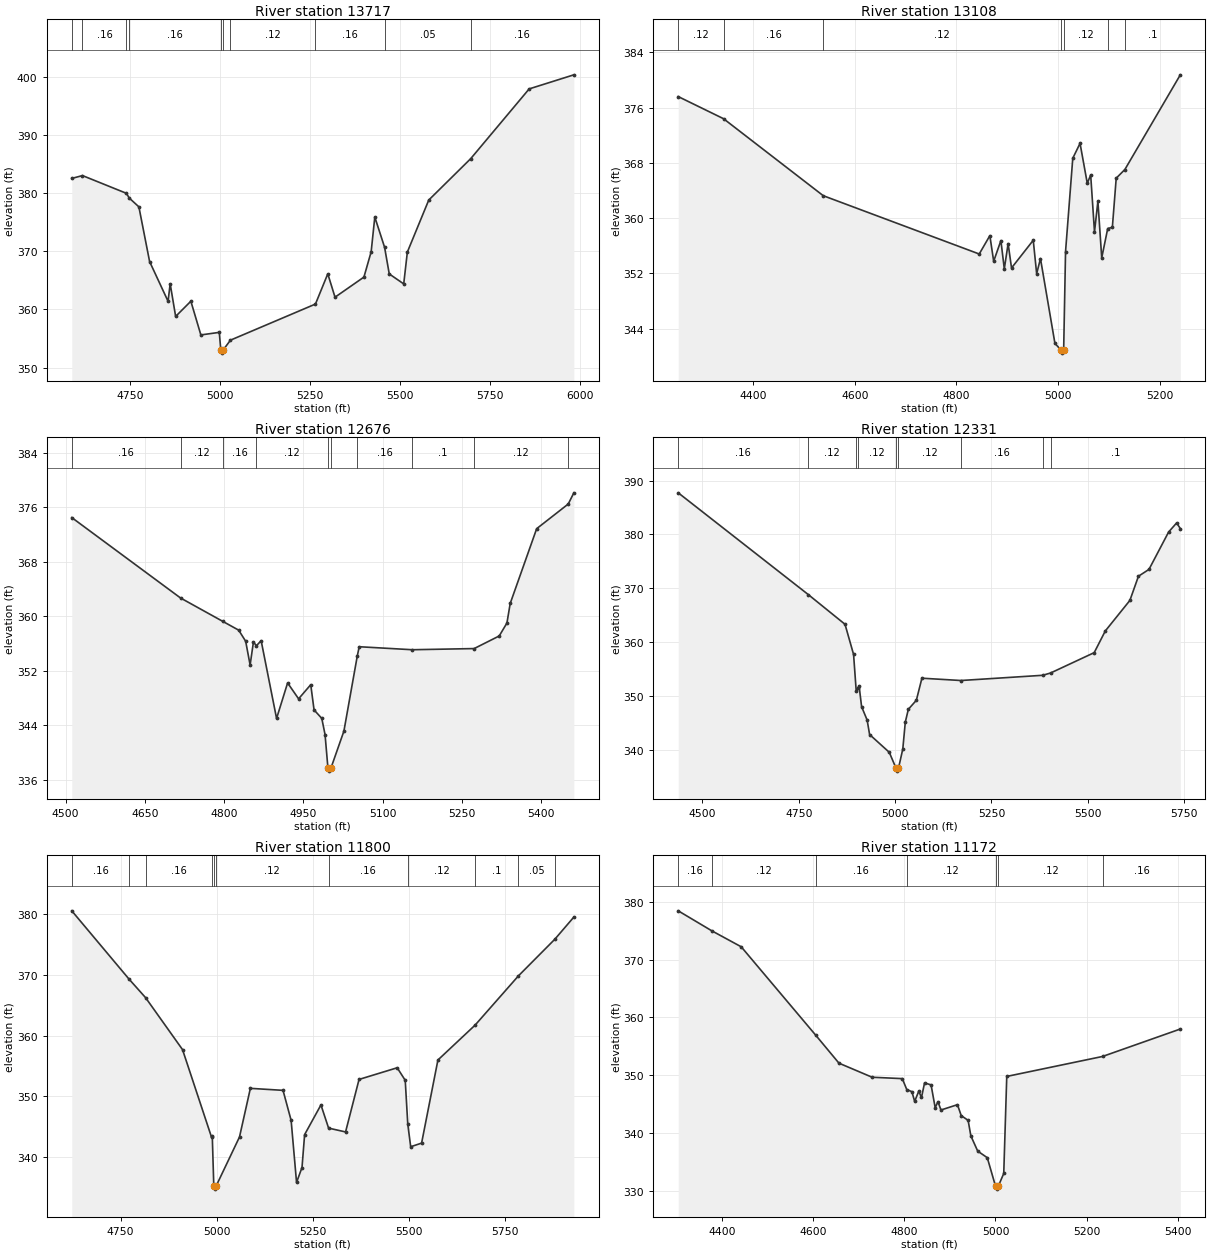
Type RM Length L Ch R = 1 ,13717   ,609,609,609
BEGIN DESCRIPTION:
BALL BRANCH 24.0
END DESCRIPTION:
XS GIS Cut Line= 6
      3629721.24     10629378.31      3629921.78     10629677.81
      3629992.09     10629753.33       3630062.4     10629755.94
      3630481.68     10629716.88      3630903.55     10629589.27
#Sta/Elev= 30
  4587.5  382.53  4617.3  383.02  4739.4  379.97  4747.4  379.15  4774.1  377.64
  4803.9  368.23  4855.2   361.4  4861.1  364.41  4876.3  358.79  4918.6  361.41
  4946.4  355.61  4997.6  356.05  5001.9  352.98  5004.7  352.48  5007.9  352.98
  5028.7  354.71    5265  360.92  5299.3  366.12  5319.4   362.1  5399.8  365.56
  5419.9  369.92    5430  375.89  5457.2  370.69  5470.2   366.1  5510.4  364.39
  5520.5  369.86    5580  378.81  5696.8  385.94  5859.2  397.93  5983.4  400.35
#Mann= 10 ,-1 , 0
  4587.5     .05       0  4617.3     .16       0  4739.4     .12       0
  4747.4     .16       0  5001.9     .07       0  5007.9     .16       0
  5028.7     .12       0    5265     .16       0  5457.2     .05       0
  5696.8     .16       0
Bank Sta=5001.9,5007.9
XS Rating Curve= 0 ,0
Exp/Cntr=0.3,0.1

Type RM Length L Ch R = 1 ,13108   ,432,432,432
BEGIN DESCRIPTION:
BALL BRANCH 23.0
END DESCRIPTION:
XS GIS Cut Line= 2
      3629453.46     10629701.25      3630191.73     10630356.33
#Sta/Elev= 30
    4253   377.6    4342   374.4  4538.1  363.25  4844.7  354.81  4865.6  357.47
  4873.1  353.76  4887.3  356.75    4894  352.66  4901.5  356.32  4908.2  352.79
  4950.9   356.8  4957.6  351.96  4965.1  354.15  4993.5  341.88  5004.7  340.96
  5007.5  340.46  5010.7  340.96  5014.4  355.17  5028.6  368.67  5042.9  370.83
  5057.1  365.05  5063.8  366.25  5071.3  358.01    5078  362.46  5085.5  354.25
  5097.3   358.5  5106.4  358.67    5114  365.79    5131  367.04    5240  380.75
#Mann= 7 ,-1 , 0
    4253     .12       0    4342     .16       0  4538.1     .12       0
  5004.7     .07       0  5010.7     .12       0  5097.3     .16       0
    5131      .1       0
Bank Sta=5004.7,5010.7
XS Rating Curve= 0 ,0
Exp/Cntr=0.3,0.1

Type RM Length L Ch R = 1 ,12676   ,345,345,345
BEGIN DESCRIPTION:
BALL BRANCH 22.0
END DESCRIPTION:
XS GIS Cut Line= 2
      3629371.78     10629866.19      3629937.75     10630630.07
#Sta/Elev= 30
  4511.6  374.49  4717.6  362.69  4797.1  359.28  4827.7  357.97  4840.9  356.34
  4849.3  352.86  4855.6  356.24  4861.2  355.68  4870.2  356.43  4899.4  345.02
  4920.3  350.23  4941.1   347.9  4964.1  349.97  4970.4  346.27    4985  345.03
  4991.2  342.66  4996.6  337.79  4999.4  337.29  5002.6  337.79  5026.9  343.16
  5052.3  354.21  5055.9  355.54  5156.4   355.1  5273.5  355.27    5321  357.12
  5335.6  359.02  5341.8  361.89  5391.9  372.86  5451.7  376.48  5462.3  378.12
#Mann= 10 ,-1 , 0
  4511.6     .16       0  4717.6     .12       0  4797.1     .16       0
  4861.2     .12       0  4996.6     .07       0  5002.6     .12       0
  5052.3     .16       0  5156.4      .1       0  5273.5     .12       0
  5451.7      .1       0
Bank Sta=4996.6,5002.6
XS Rating Curve= 0 ,0
Exp/Cntr=0.3,0.1

Type RM Length L Ch R = 1 ,12331   ,531,531,531
BEGIN DESCRIPTION:
BALL BRANCH 21.0
END DESCRIPTION:
XS GIS Cut Line= 2
      3628926.22     10629973.92      3629933.14     10630800.29
#Sta/Elev= 30
  4437.3  387.71  4774.7   368.8    4870  363.28  4892.2  357.68  4899.1  350.83
    4904  351.46  4906.6   351.8    4913  347.97  4927.4  345.48  4933.8  342.79
  4984.8  339.49  5002.6  336.49  5005.3  335.99  5008.6  336.49  5019.9   340.1
  5026.4   345.1  5034.3  347.48  5055.1  349.16  5069.5  353.26  5170.7  352.83
    5383   353.8  5403.4  354.23  5516.5  358.01  5545.2  362.03  5609.1  367.72
  5631.3  372.21  5658.6  373.48  5709.5  380.42  5730.4  382.12  5739.9  381.07
#Mann= 9 ,-1 , 0
  4437.3     .16       0  4774.7     .12       0  4899.1     .16       0
    4904     .12       0  5002.6     .07       0  5008.6     .12       0
  5170.7     .16       0    5383     .12       0  5403.4      .1       0
Bank Sta=5002.6,5008.6
XS Rating Curve= 0 ,0
Exp/Cntr=0.3,0.1

Type RM Length L Ch R = 1 ,11800   ,628,628,628
BEGIN DESCRIPTION:
BALL BRANCH 20.0
END DESCRIPTION:
XS GIS Cut Line= 3
      3628989.92     10630248.12      3629120.13     10630524.17
      3629854.97     10631204.89
#Sta/Elev= 30
  4623.1  380.57  4772.2  369.32  4815.2  366.27  4911.4  357.71  4987.1  343.25
  4988.8  343.54  4992.8  335.23  4995.5  334.73  4998.8  335.23  5059.7  343.32
    5088  351.33    5173     351  5194.1  346.05  5208.2  335.84  5222.4  338.29
  5229.2  343.71  5271.7   348.6  5291.6  344.78  5335.8  344.15  5370.9   352.8
  5470.2  354.72  5491.1  352.65  5497.7  345.44  5505.3  341.71  5533.7  342.31
  5576.2     356  5672.9  361.74  5785.8  369.86  5880.5  375.89    5930  379.54
#Mann= 11 ,-1 , 0
  4623.1     .16       0  4772.2     .12       0  4815.2     .16       0
  4987.1     .12       0  4992.8     .07       0  4998.8     .12       0
  5291.6     .16       0  5497.7     .12       0  5672.9      .1       0
  5785.8     .05       0  5880.5      .1       0
Bank Sta=4992.8,4998.8
XS Rating Curve= 0 ,0
Exp/Cntr=0.3,0.1

Type RM Length L Ch R = 1 ,11172   ,303,303,303
BEGIN DESCRIPTION:
BALL BRANCH 19.0
END DESCRIPTION:
XS GIS Cut Line= 3
      3628745.11     10630482.47      3628979.51     10630815.83
       3629556.1     10631200.23
#Sta/Elev= 30
  4304.6  378.42  4378.1  374.97  4442.6  372.21  4606.1  356.92  4656.9   352.1
  4729.6  349.67  4795.7  349.43  4805.5  347.55  4816.8  347.17  4822.8   345.5
  4831.8  347.26  4837.8  346.17  4844.5  348.69  4858.8  348.35  4867.8  344.41
  4873.9  345.45  4880.5  344.01  4916.6  344.93  4924.9  343.04    4940  342.22
    4946  339.54    4961  336.91    4982  335.77  5000.1  330.84  5002.8  330.34
  5006.1  330.84  5018.1  333.05  5024.7  349.81  5234.7  353.26  5405.1     358
#Mann= 7 ,-1 , 0
  4304.6     .16       0  4378.1     .12       0  4606.1     .16       0
  4805.5     .12       0  5000.1     .07       0  5006.1     .12       0
  5234.7     .16       0
Bank Sta=5000.1,5006.1
XS Rating Curve= 0 ,0
Exp/Cntr=0.3,0.1

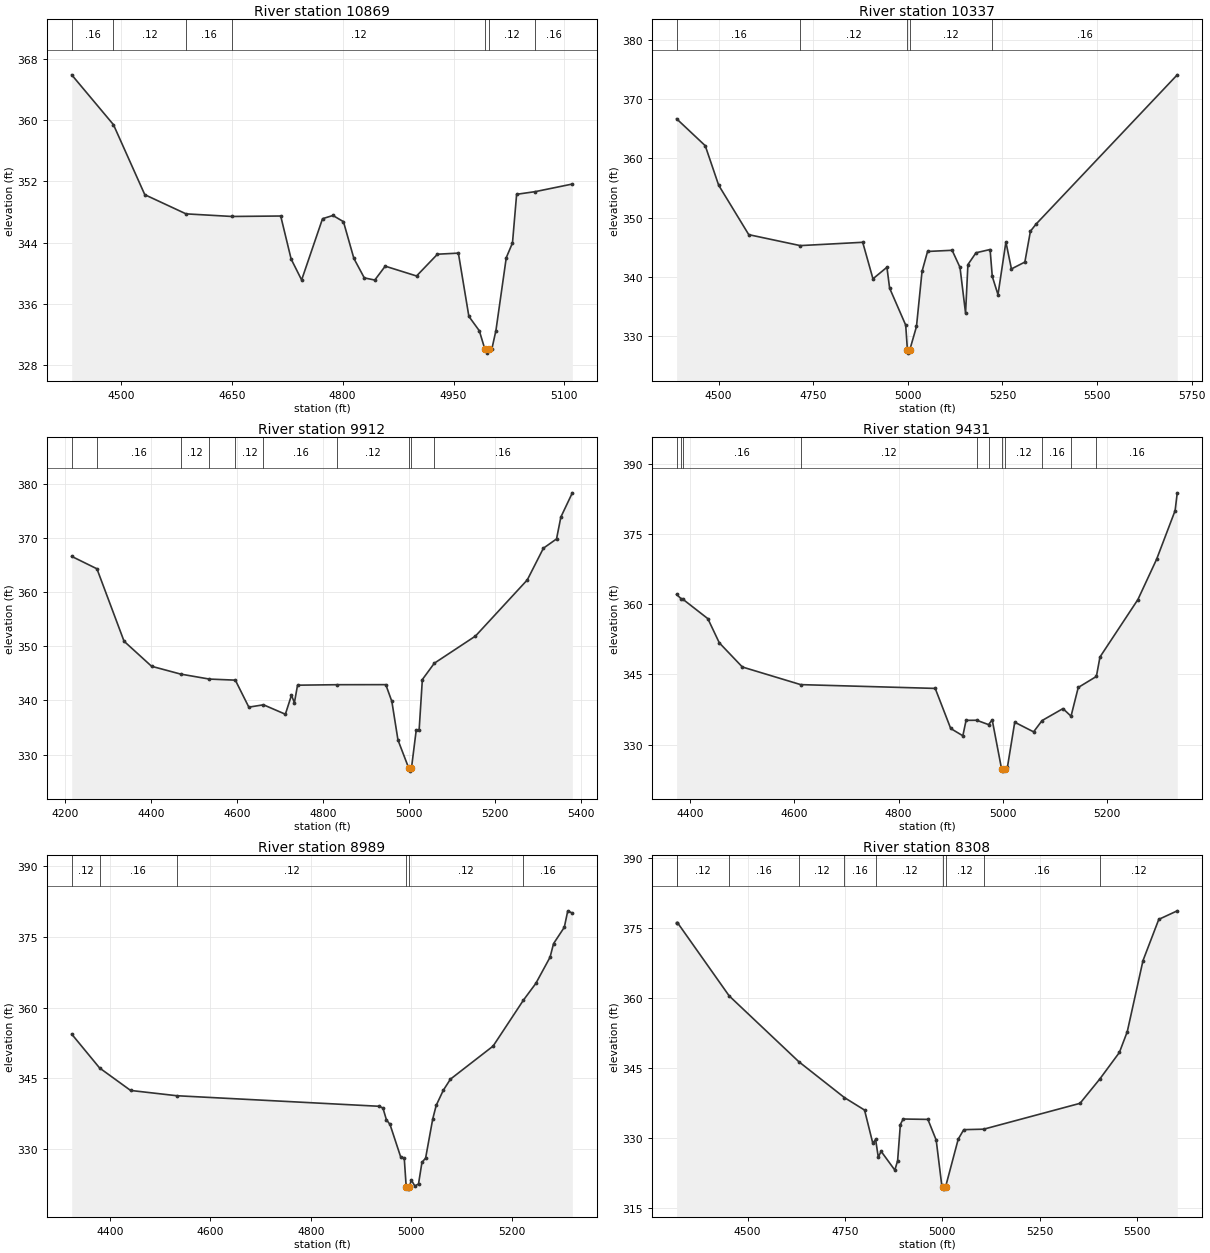
Type RM Length L Ch R = 1 ,10869   ,532,532,532
BEGIN DESCRIPTION:
BALL BRANCH 18.0
END DESCRIPTION:
XS GIS Cut Line= 3
      3628699.64     10630810.22      3629099.61     10631210.19
      3629199.57     10631260.17
#Sta/Elev= 30
  4433.4  365.88  4489.9  359.38  4532.3  350.25  4588.1  347.75  4650.2  347.41
  4716.2  347.47  4730.3  341.86  4744.5  339.13  4772.8  347.12  4786.9  347.54
  4801.1  346.73  4815.2  341.94  4829.3   339.4  4843.5  339.12  4857.6  340.93
    4900  339.65  4928.3  342.49  4956.6  342.63  4970.8  334.38  4984.9  332.51
  4992.5  330.09  4995.3  329.59  4998.5  330.09  5001.8  330.09  5007.4  332.54
  5021.4  342.04  5029.8  343.96  5035.4   350.3  5060.7  350.65  5110.8  351.64
#Mann= 7 ,-1 , 0
  4433.4     .16       0  4489.9     .12       0  4588.1     .16       0
  4650.2     .12       0  4992.5     .07       0  4998.5     .12       0
  5060.7     .16       0
Bank Sta=4992.5,4998.5
XS Rating Curve= 0 ,0
Exp/Cntr=0.3,0.1

Type RM Length L Ch R = 1 ,10337   ,425,425,425
BEGIN DESCRIPTION:
BALL BRANCH 17.0
END DESCRIPTION:
XS GIS Cut Line= 2
      3628401.73     10630891.64      3629182.98     10631959.35
#Sta/Elev= 30
    4389   366.7  4464.7  362.15  4500.2  355.47  4579.7  347.12  4715.7  345.27
  4880.8  345.83  4907.9  339.66  4944.8  341.61  4951.9  338.08  4994.4  331.84
    4999   327.6  5001.8   327.1    5005   327.6  5022.9   331.6  5037.6  340.92
  5052.2  344.28  5117.1  344.48  5137.9  341.59  5152.6  333.85  5158.8  342.06
  5180.2  344.06  5217.4  344.61  5223.2  340.06  5238.3  336.98  5259.2  345.88
  5273.8  341.33  5309.3  342.49    5324   347.7  5338.7  348.89    5712  374.13
#Mann= 5 ,-1 , 0
    4389     .16       0  4715.7     .12       0    4999     .07       0
    5005     .12       0  5223.2     .16       0
Bank Sta=4999,5005
XS Rating Curve= 0 ,0
Exp/Cntr=0.3,0.1

Type RM Length L Ch R = 1 ,9912    ,481,481,481
BEGIN DESCRIPTION:
BALL BRANCH 16.0
END DESCRIPTION:
XS GIS Cut Line= 3
      3628136.13     10631131.25       3628761.1      10631803.1
      3628802.53     10632046.51
#Sta/Elev= 30
  4215.2  366.58  4273.9  364.29    4337  350.92    4401   346.3  4468.5  344.86
  4535.2  343.94  4595.8  343.74  4627.2  338.76  4661.3  339.19  4712.2  337.45
  4726.4  340.96  4733.2  339.58  4740.5  342.81    4833   342.9  4945.8  342.91
  4959.9   339.8  4974.1  332.69  4999.4  327.45  5002.2  326.95  5005.4  327.45
  5016.6  334.54  5023.4  334.62  5030.8  343.85  5058.6  346.86  5154.4  351.88
  5274.9  362.24  5312.4  368.09  5342.9   369.8    5353  373.84  5379.7  378.31
#Mann= 10 ,-1 , 0
  4215.2     .12       0  4273.9     .16       0  4468.5     .12       0
  4535.2     .16       0  4595.8     .12       0  4661.3     .16       0
    4833     .12       0  4999.4     .07       0  5005.4     .12       0
  5058.6     .16       0
Bank Sta=4999.4,5005.4
XS Rating Curve= 0 ,0
Exp/Cntr=0.3,0.1

Type RM Length L Ch R = 1 ,9431    ,442,442,442
BEGIN DESCRIPTION:
BALL BRANCH 15.0
END DESCRIPTION:
XS GIS Cut Line= 3
      3628055.89     10631194.09      3628305.89     10631673.26
      3628555.23      10632010.9
#Sta/Elev= 30
  4374.3  362.11    4383  361.19  4386.4  361.08  4434.2  356.93  4456.2  351.76
  4500.4  346.59  4612.3  342.82  4870.3  342.01    4900  333.44  4923.3  331.88
  4929.5  335.18  4949.8   335.2  4972.6  334.27  4979.6  335.28  4997.5  324.82
  5000.2  324.32  5003.5  324.82  5008.9  325.23  5022.8  334.78    5059  332.72
  5075.3  335.14  5115.3  337.69  5130.8  336.07  5144.6  342.21  5179.4  344.57
  5186.3  348.73    5259  361.01  5294.9  369.63  5330.4  380.04  5334.5  383.84
#Mann= 11 ,-1 , 0
  4374.3     .16       0    4383     .12       0  4386.4     .16       0
  4612.3     .12       0  4949.8     .16       0  4972.6     .12       0
  4997.5     .07       0  5003.5     .12       0  5075.3     .16       0
  5130.8     .12       0  5179.4     .16       0
Bank Sta=4997.5,5003.5
XS Rating Curve= 0 ,0
Exp/Cntr=0.3,0.1

Type RM Length L Ch R = 1 ,8989    ,681,681,681
BEGIN DESCRIPTION:
BALL BRANCH 14.0
END DESCRIPTION:
XS GIS Cut Line= 3
      3627915.27     10631303.47      3627967.35     10631865.96
      3628279.83     10632162.81
#Sta/Elev= 30
  4324.4  354.41  4379.9  347.22  4441.6  342.45  4533.6  341.33  4936.2  339.09
  4943.5  338.72  4950.4  336.24  4957.6  335.23  4978.7  328.38  4985.9   328.1
  4989.8  322.01  4992.6  321.51  4995.8  322.01  5000.1  323.42    5007  322.17
  5014.3  322.61  5021.1  327.17  5028.4   328.1  5042.6  336.41  5049.5  339.29
  5063.6  342.49  5077.8  344.85  5162.7  351.87    5223  361.62  5247.6  365.16
    5276  370.74  5282.9  373.61  5304.3  377.08  5311.2  380.57  5320.3  380.08
#Mann= 6 ,-1 , 0
  4324.4     .12       0  4379.9     .16       0  4533.6     .12       0
  4989.8     .07       0  4995.8     .12       0    5223     .16       0
Bank Sta=4989.8,4995.8
XS Rating Curve= 0 ,0
Exp/Cntr=0.3,0.1

Type RM Length L Ch R = 1 ,8308    ,450,450,450
BEGIN DESCRIPTION:
BALL BRANCH 13.0
END DESCRIPTION:
XS GIS Cut Line= 3
      3627050.68       10631767.      3627592.35     10632293.05
      3628116.54      10632370.9
#Sta/Elev= 30
  4317.8   376.2    4320   376.2  4452.8  360.49  4631.6  346.38  4748.6  338.69
  4800.2  336.02  4821.3  328.93  4828.6  329.71  4835.5  325.91  4842.7  327.18
  4877.9  323.15  4885.1  325.15  4892.1  332.92  4899.2   334.1  4962.8  334.02
  4984.1  329.58  4998.3  319.95  5002.2  319.57    5005  319.07  5008.2  319.57
  5040.7   329.8  5054.9  331.82    5106  331.92  5353.2  337.46  5404.3  342.71
  5454.3  348.37  5474.5  352.82  5514.9  368.07  5555.4   376.9  5602.8  378.73
#Mann= 10 ,-1 , 0
  4317.8     .16       0    4320     .12       0  4452.8     .16       0
  4631.6     .12       0  4748.6     .16       0  4828.6     .12       0
  5002.2     .07       0  5008.2     .12       0    5106     .16       0
  5404.3     .12       0
Bank Sta=5002.2,5008.2
XS Rating Curve= 0 ,0
Exp/Cntr=0.3,0.1

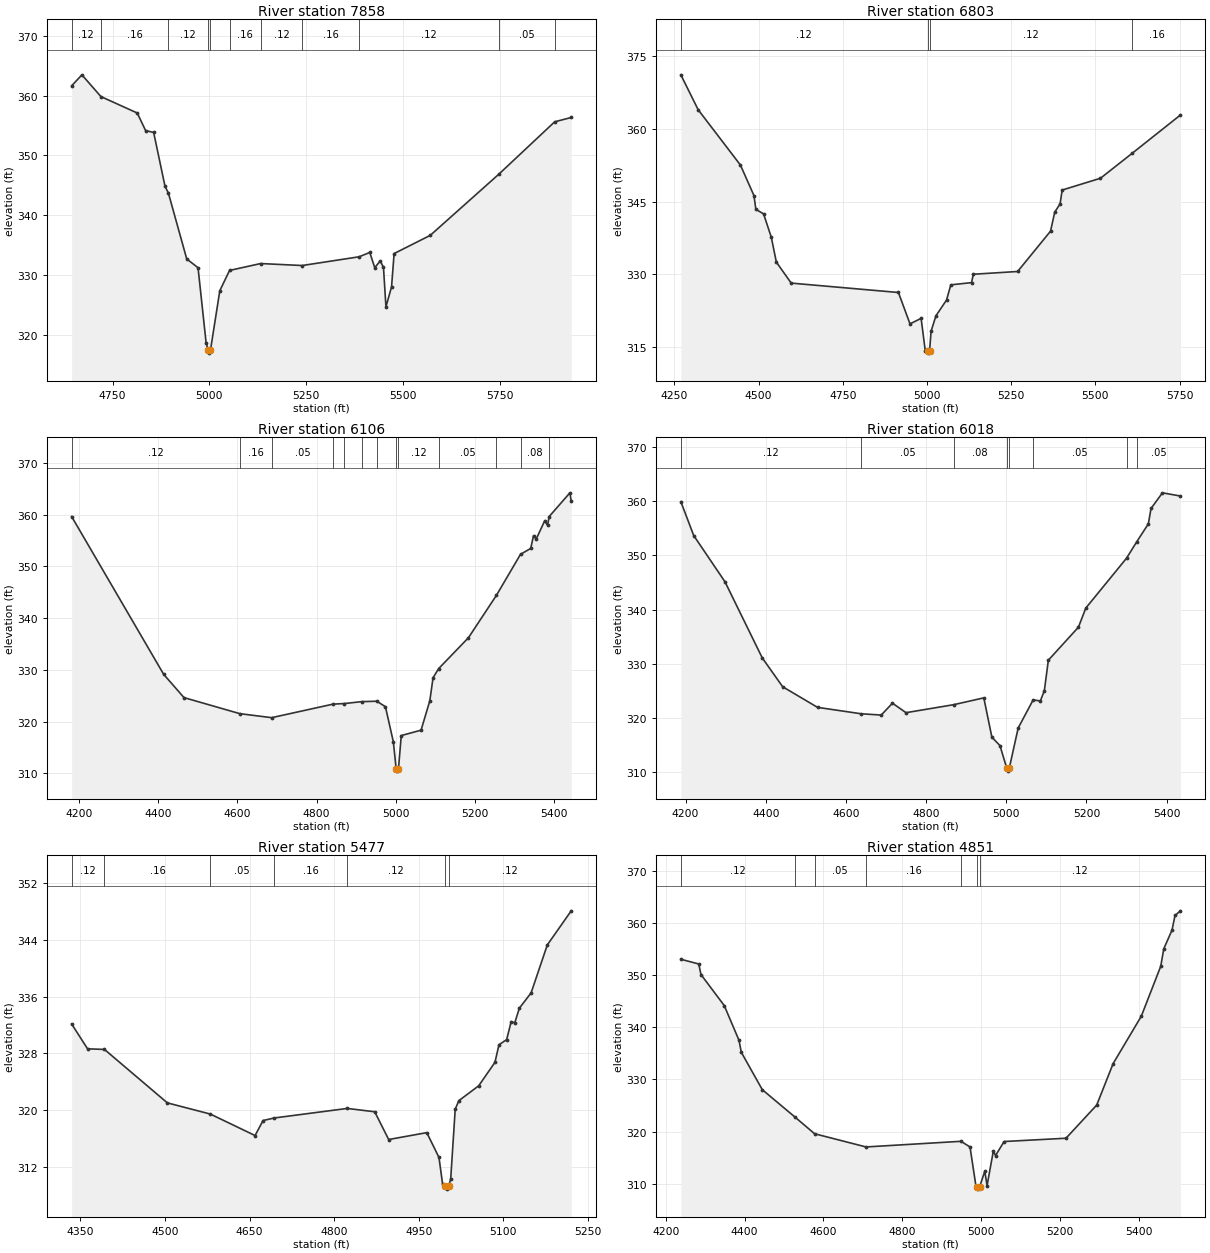
Type RM Length L Ch R = 1 ,7858    ,1055,1055,1055
BEGIN DESCRIPTION:
BALL BRANCH 12.0
END DESCRIPTION:
XS GIS Cut Line= 2
      3627014.22     10632308.66      3628045.05     10633084.39
#Sta/Elev= 30
  4644.2  361.63  4670.7  363.47  4719.8  359.83  4813.6  357.08  4835.2  354.14
    4856  353.83  4885.2  344.85  4894.1  343.67  4941.4  332.66  4970.6  331.19
  4991.4  318.66  4996.7   317.4  4999.5   316.9  5002.7   317.4  5026.8  327.34
    5052  330.74  5132.4  331.89  5239.5  331.56  5386.5  333.02  5414.1  333.75
  5426.9   331.2  5441.2  332.34  5449.5  331.23  5455.8  324.64  5470.3  327.99
  5476.9  333.56  5570.3  336.61  5747.3  346.84  5891.6  355.61  5934.3  356.33
#Mann= 11 ,-1 , 0
  4644.2     .12       0  4719.8     .16       0  4894.1     .12       0
  4996.7     .07       0  5002.7     .12       0    5052     .16       0
  5132.4     .12       0  5239.5     .16       0  5386.5     .12       0
  5747.3     .05       0  5891.6     .16       0
Bank Sta=4996.7,5002.7
XS Rating Curve= 0 ,0
Exp/Cntr=0.3,0.1

Type RM Length L Ch R = 1 ,6803    ,697,697,697
BEGIN DESCRIPTION:
BALL BRANCH 10.0
END DESCRIPTION:
XS GIS Cut Line= 2
      3626572.35     10632901.53      3627918.17     10633525.89
#Sta/Elev= 30
  4269.1  371.19  4320.5  363.98    4446  352.55  4486.3  346.22  4491.9  343.38
  4514.8  342.46  4537.7  337.63  4552.7  332.49  4596.8  328.15  4915.2  326.21
  4949.6  319.73  4982.6  320.86  4994.9   314.2  5001.7  314.18  5004.4  313.68
  5007.7  314.18  5012.3  318.23  5026.7   321.4  5058.1  324.65  5070.8  327.79
  5132.3  328.25  5137.8  329.98  5269.2  330.55  5366.9  338.88  5379.5  342.83
  5395.3  344.52  5401.5  347.38  5515.3  349.82  5610.2  355.02  5752.7  362.89
#Mann= 4 ,-1 , 0
  4269.1     .12       0  5001.7     .07       0  5007.7     .12       0
  5610.2     .16       0
Bank Sta=5001.7,5007.7
XS Rating Curve= 0 ,0
Exp/Cntr=0.3,0.1

Type RM Length L Ch R = 1 ,6106    ,88,88,88
BEGIN DESCRIPTION:
Mapping XS 3ebeb7dc
END DESCRIPTION:
XS GIS Cut Line= 6
       3626305.8     10633420.28      3626753.72     10633715.43
      3626909.97     10633705.01      3627121.78     10633708.48
      3627232.89     10633739.73      3627405.57     10633908.96
#Sta/Elev= 30
  4181.3  359.65  4413.8  329.13  4465.1  324.63  4606.5  321.52  4686.6  320.75
  4841.8  323.37  4870.2  323.48  4914.2  323.85  4952.2  323.93    4974  322.87
    4994  316.08    5001  310.91  5003.8  310.41    5007  310.91    5014  317.29
    5064  318.33  5086.2  324.03  5094.3  328.47  5108.7  330.26  5183.7  336.21
  5254.4  344.41  5315.3  352.35    5341  353.48  5348.2  355.96  5355.2  355.34
  5376.5  358.85  5383.5  357.96  5387.8  359.66    5440  364.24  5443.4  362.65
#Mann= 13 ,-1 , 0
  4181.3     .12       0  4606.5     .16       0  4686.6     .05       0
  4841.8     .08       0  4870.2     .12       0  4914.2     .08       0
  4952.2     .12       0    5001     .07       0    5007     .12       0
  5108.7     .05       0  5254.4     .16       0  5315.3     .08       0
  5387.8     .16       0
Bank Sta=5001,5007
XS Rating Curve= 0 ,0
Exp/Cntr=0.3,0.1

Type RM Length L Ch R = 1 ,6018    ,541,541,541
BEGIN DESCRIPTION:
BALL BRANCH 8.0
END DESCRIPTION:
XS GIS Cut Line= 6
      3626291.89     10633444.58      3626760.67     10633760.56
      3626899.56     10633777.93      3627062.75     10633798.76
      3627184.28     10633809.18      3627357.19     10633995.92
#Sta/Elev= 30
  4188.3   359.9  4220.4  353.66  4298.4  345.14  4391.4  331.11  4442.3   325.8
  4529.3     322  4637.9  320.82  4688.2  320.58  4716.2  322.77    4750  321.02
  4868.8  322.49  4944.1  323.75  4964.2  316.51  4984.4  314.95  5001.5  310.75
  5004.3  310.25  5007.5  310.75  5029.8  318.19  5067.2  323.38  5085.1  323.18
  5095.1  325.07  5105.1  330.69  5180.1  336.77  5198.6   340.3  5300.2  349.49
  5325.9  352.55  5354.5   355.8  5361.3  358.65  5389.7  361.53  5434.6  360.94
#Mann= 8 ,-1 , 0
  4188.3     .12       0  4637.9     .05       0  4868.8     .08       0
  5001.5     .07       0  5007.5     .08       0  5067.2     .05       0
  5300.2     .08       0  5325.9     .05       0
Bank Sta=5001.5,5007.5
XS Rating Curve= 0 ,0
Exp/Cntr=0.3,0.1

Type RM Length L Ch R = 1 ,5477    ,626,626,626
BEGIN DESCRIPTION:
BALL BRANCH 7.0
END DESCRIPTION:
XS GIS Cut Line= 3
      3626299.64     10633710.22      3626699.61     10634110.19
      3626949.61     10634310.19
#Sta/Elev= 30
  4334.5  332.14  4362.7  328.65  4392.7  328.56  4504.2  321.05  4580.4  319.48
  4659.7  316.46  4673.9  318.57  4693.8  318.93  4823.2  320.27  4871.9   319.8
  4896.6   315.9  4964.2  316.87  4985.8  313.38  4992.2  309.66  4997.2  309.43
  4999.9  308.93  5003.2  309.43  5006.6  310.35  5014.6  320.17    5021  321.36
  5056.2  323.45    5085  326.74  5092.2  329.22  5105.8  329.94  5113.8  332.47
  5120.2   332.3  5128.3  334.36  5149.1   336.5  5177.9  343.25  5220.3  348.04
#Mann= 7 ,-1 , 0
  4334.5     .12       0  4392.7     .16       0  4580.4     .05       0
  4693.8     .16       0  4823.2     .12       0  4997.2     .07       0
  5003.2     .12       0
Bank Sta=4997.2,5003.2
XS Rating Curve= 0 ,0
Exp/Cntr=0.3,0.1

Type RM Length L Ch R = 1 ,4851    ,472,472,472
BEGIN DESCRIPTION:
BALL BRANCH 6.0
END DESCRIPTION:
XS GIS Cut Line= 3
      3626149.61     10633660.19      3626549.61     10634360.19
      3626849.61     10634710.18
#Sta/Elev= 30
  4238.5     353  4283.9   352.1  4289.6  350.07  4348.6  344.13  4386.1  337.46
  4391.8  335.19  4445.1  328.02  4527.1  322.83  4577.7  319.58  4708.2  317.05
  4949.1  318.13    4972  317.04  4987.1  309.51  4990.6  309.47  4993.4  308.97
  4996.6  309.47  5009.5  312.41  5015.2  309.63  5031.1  316.25  5036.8  315.41
  5058.4  318.09  5215.4  318.72  5293.3  325.07    5335  333.02  5406.4  342.09
  5455.8  351.67  5463.4     355  5484.3  358.58    5492   361.4  5505.7  362.28
#Mann= 7 ,-1 , 0
  4238.5     .12       0  4527.1     .16       0  4577.7     .05       0
  4708.2     .16       0  4949.1     .12       0  4990.6     .07       0
  4996.6     .12       0
Bank Sta=4990.6,4996.6
XS Rating Curve= 0 ,0
Exp/Cntr=0.3,0.1

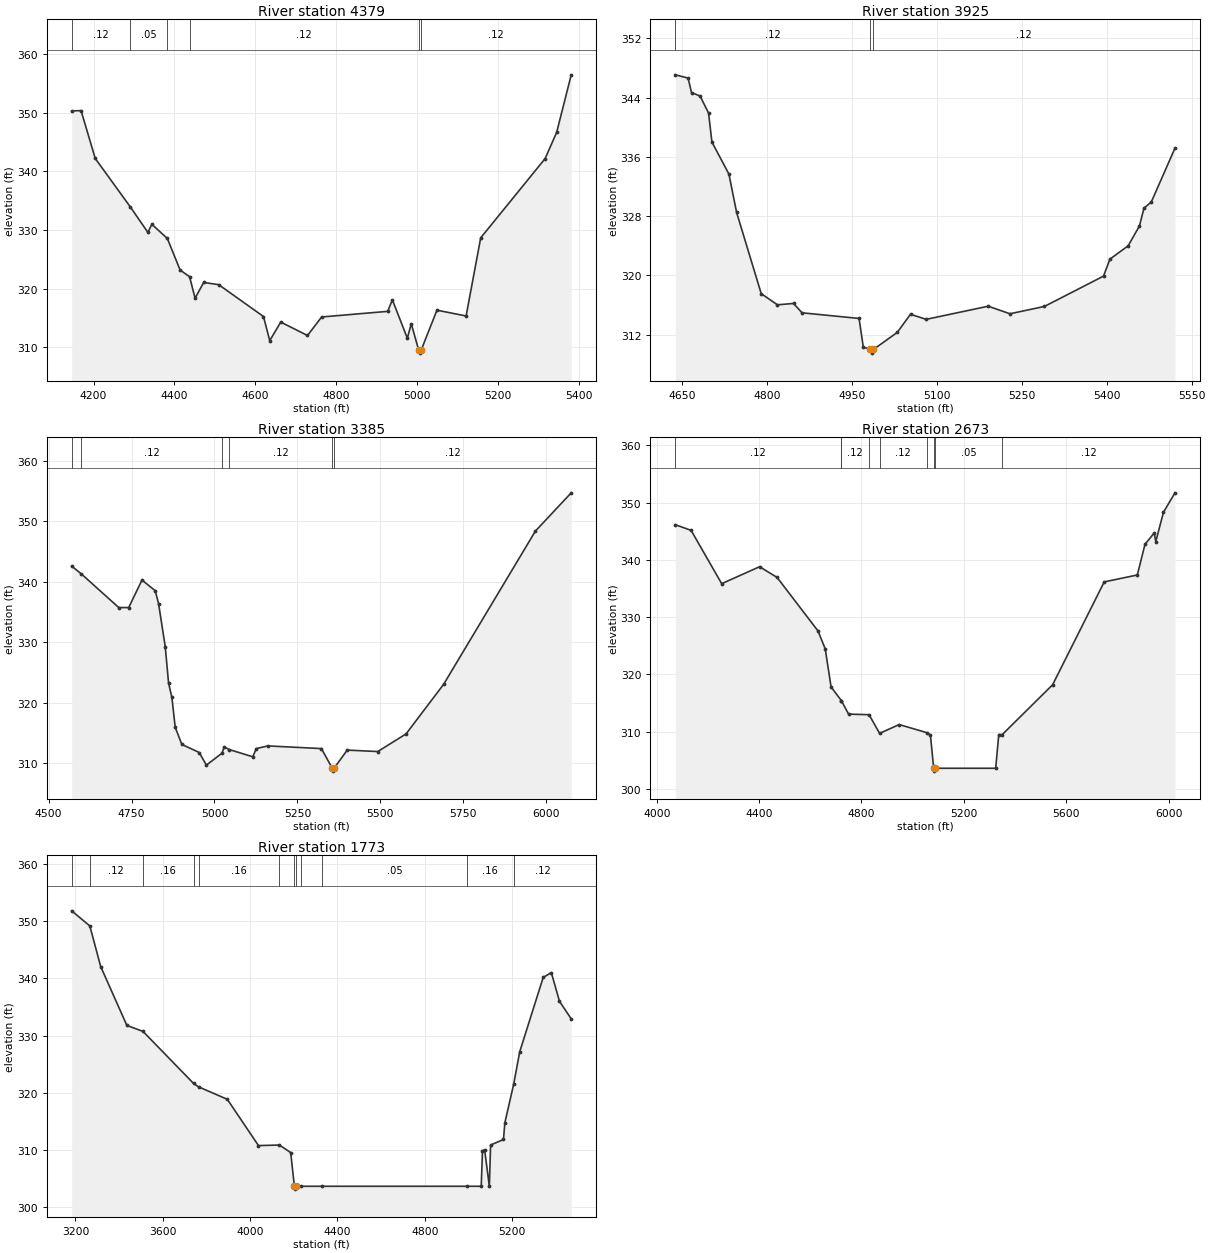
Type RM Length L Ch R = 1 ,4379    ,454,454,454
BEGIN DESCRIPTION:
BALL BRANCH 5.0
END DESCRIPTION:
XS GIS Cut Line= 3
       3625849.6     10633910.18      3626299.61     10634660.19
       3626599.6     10634860.18
#Sta/Elev= 30
  4145.7  350.32    4169  350.37    4204  342.21  4290.6  333.95  4334.2  329.59
    4344  330.97  4382.3  328.55  4413.9  323.16  4437.3  322.02  4450.9  318.35
  4472.2  321.04  4509.2  320.67    4620  315.23  4635.5  311.11  4662.7  314.28
  4728.8  311.99  4763.8  315.15  4927.1  316.11  4938.7  318.07  4975.7  311.52
  4985.4  314.01  5003.8  309.48  5006.5  308.98  5009.8  309.48  5048.9  316.31
    5121  315.32  5157.1  328.66  5316.3  342.18  5344.9  346.66  5380.9  356.48
#Mann= 6 ,-1 , 0
  4145.7     .12       0  4290.6     .05       0  4382.3     .08       0
  4437.3     .12       0  5003.8     .07       0  5009.8     .12       0
Bank Sta=5003.8,5009.8
XS Rating Curve= 0 ,0
Exp/Cntr=0.3,0.1

Type RM Length L Ch R = 1 ,3925    ,540,540,540
BEGIN DESCRIPTION:
BALL BRANCH 4.0
END DESCRIPTION:
XS GIS Cut Line= 3
      3625799.61     10634160.19      3625999.61     10634460.19
      3626149.62     10634960.22
#Sta/Elev= 30
  4637.9  347.07  4660.4  346.63  4666.4  344.68  4681.5  344.21  4696.5  341.92
  4702.5  337.99  4732.5  333.68  4746.1   328.5  4789.6  317.54  4818.2  316.04
  4846.7  316.22  4861.7  314.96  4962.4   314.2  4969.9  310.35  4981.9  310.02
  4984.7  309.52  4987.9  310.02  5029.8  312.31  5053.3  314.76  5081.1  314.08
  5190.7  315.85    5229  314.83  5289.9  315.82  5394.3  319.91  5405.6   322.2
  5437.8     324  5457.8  326.68  5465.7  329.07  5478.7  329.91  5520.5  337.17
#Mann= 3 ,-1 , 0
  4637.9     .12       0  4981.9     .07       0  4987.9     .12       0
Bank Sta=4981.9,4987.9
XS Rating Curve= 0 ,0
Exp/Cntr=0.3,0.1

Type RM Length L Ch R = 1 ,3385    ,712,712,712
BEGIN DESCRIPTION:
BALL BRANCH 3.0
END DESCRIPTION:
XS GIS Cut Line= 4
      3625541.92     10634038.32      3625526.29      10634387.3
      3625635.67     10634663.34      3626203.36     10635309.15
#Sta/Elev= 30
  4569.4   342.6  4598.3  341.32  4711.4  335.74  4741.4  335.74  4781.5  340.29
  4821.5  338.52  4831.5  336.38  4851.5  329.29  4861.6  323.26  4871.6  320.87
  4881.6  315.94  4901.6   313.1  4954.1  311.76  4975.6  309.67  5022.5  311.64
  5029.4  312.67  5045.1  312.24  5115.5  311.05  5126.1  312.41  5161.2  312.85
  5322.3  312.41  5354.9  309.18  5357.7  308.68  5360.9  309.18  5400.2  312.16
  5492.2  311.92  5577.6  314.84  5690.8  323.04  5967.5  348.39  6075.5  354.72
#Mann= 6 ,-1 , 0
  4569.4     .05       0  4598.3     .12       0  5022.5     .16       0
  5045.1     .12       0  5354.9     .07       0  5360.9     .12       0
Bank Sta=5354.9,5360.9
XS Rating Curve= 0 ,0
Exp/Cntr=0.3,0.1

Type RM Length L Ch R = 1 ,2673    ,900,900,900
BEGIN DESCRIPTION:
BALL BRANCH 2.0
END DESCRIPTION:
XS GIS Cut Line= 4
      3625332.99     10634124.61      3625020.48     10634791.31
      3625201.03     10635089.92      3625923.26     10635569.09
#Sta/Elev= 30
  4072.9  346.12  4134.3  345.14  4253.9  335.83  4401.9  338.79  4470.4  336.92
  4630.2  327.58  4658.5  324.44  4681.3   317.8  4721.4  315.42  4721.9  315.38
  4749.8  313.06  4829.7  312.96  4870.9   309.7  4947.4  311.24  5055.7  309.82
  5069.6  309.38  5082.1  303.61  5084.9  303.11  5088.1  303.61  5324.5  303.61
  5336.5  309.49  5349.9  309.48    5547  318.19  5748.5  336.14  5877.8  337.35
  5907.9  342.71    5944  344.69    5950  343.19  5980.1   348.3  6024.9  351.69
#Mann= 9 ,-1 , 0
  4072.9     .12       0  4721.4     .16       0  4721.9     .12       0
  4829.7     .16       0  4870.9     .12       0  5055.7     .05       0
  5082.1     .07       0  5088.1     .05       0  5349.9     .12       0
Bank Sta=5082.1,5088.1
XS Rating Curve= 0 ,0
Exp/Cntr=0.3,0.1

Type RM Length L Ch R = 1 ,1773    ,0,0,0
BEGIN DESCRIPTION:
BALL BRANCH 1.0
END DESCRIPTION:
XS GIS Cut Line= 3
      3624596.87     10633937.16       3624555.2     10635534.37
      3625152.45      10635881.6
#Sta/Elev= 30
  3182.5  351.83  3265.7  349.19  3315.6  342.07  3435.6  331.76  3509.1  330.73
  3740.8  321.62  3764.7     321  3895.8  318.83  4038.4  310.73  4134.6  310.83
  4185.9  309.51  4202.9  303.61  4205.6  303.11  4208.9  303.61  4232.6  303.61
  4330.6  303.61  4993.5  303.61  5058.8  303.61  5064.6  309.85  5074.5  309.97
    5096  303.61  5101.8  310.83  5160.6   311.8  5167.1  314.73  5207.7  321.52
  5235.1  327.15  5342.7  340.17  5379.9  341.02  5417.2     336  5471.1  332.91
#Mann= 12 ,-1 , 0
  3182.5     .05       0  3265.7     .12       0  3509.1     .16       0
  3740.8     .12       0  3764.7     .16       0  4134.6     .05       0
  4202.9     .07       0  4208.9     .05       0  4232.6     .16       0
  4330.6     .05       0  4993.5     .16       0  5207.7     .12       0
Bank Sta=4202.9,4208.9
XS Rating Curve= 0 ,0
Exp/Cntr=0.3,0.1

Chan Stop Cuts=-1
Use User Specified Reach Order=0
Composite Channel Slope=5