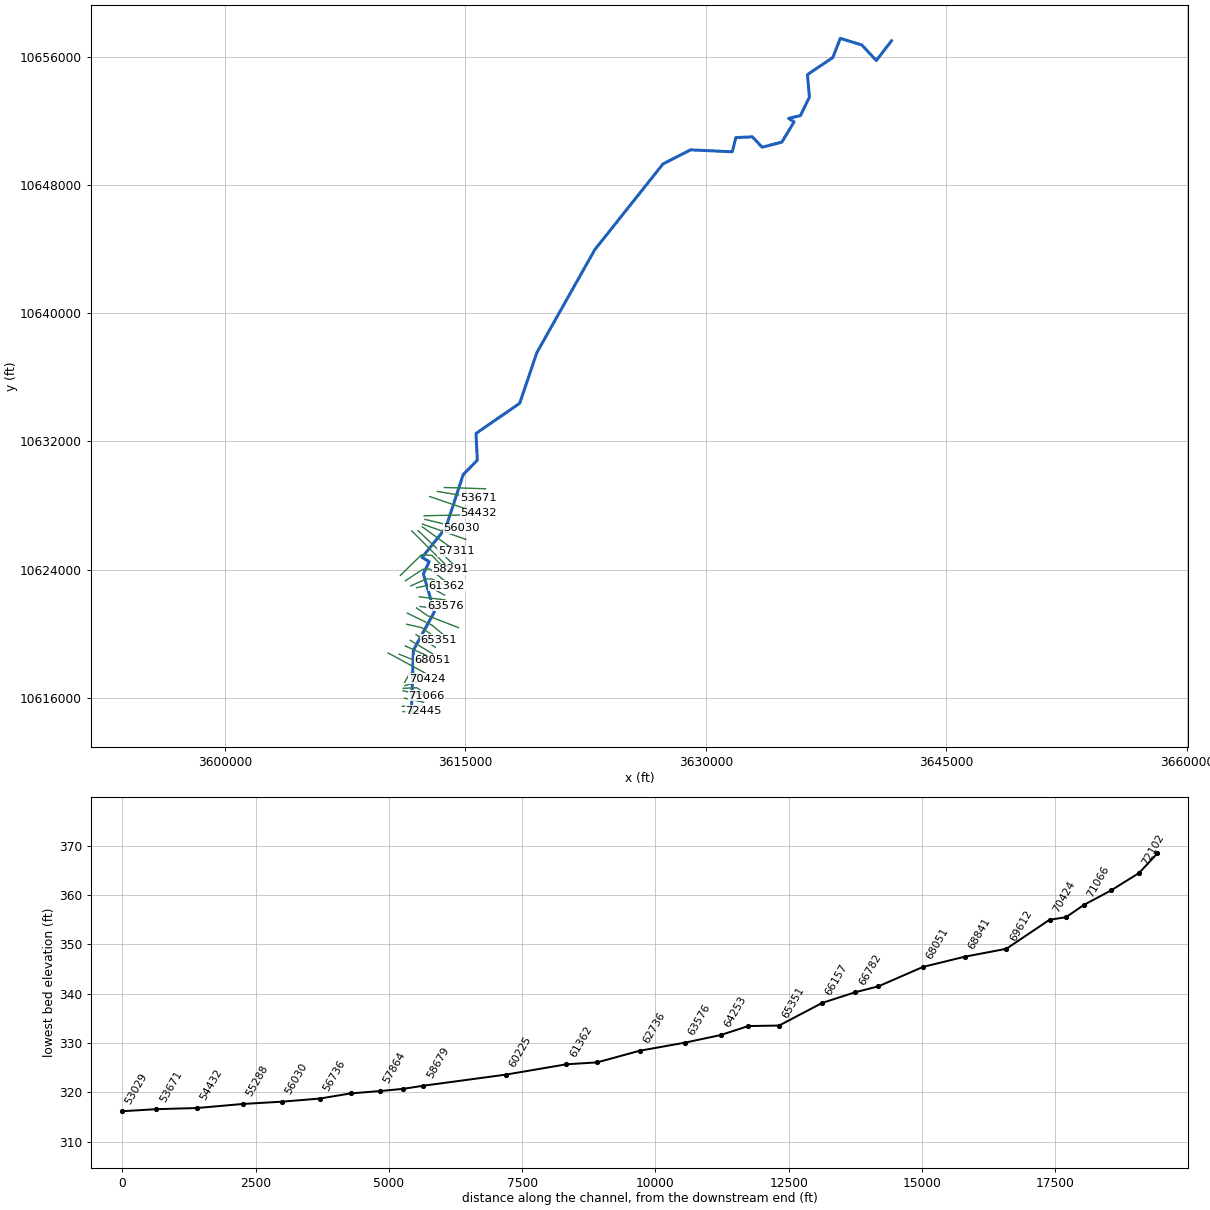
--- BIG BROWN CREEK.prj (project) ---

Proj Title=BIG BROWN CREEK Base Level Engineering
Current Plan=p01
Default Exp/Contr=0.3,0.1
English Units
Geom File=g01
Flow File=f01
Plan File=p01
Y Axis Title=Elevation
X Axis Title(PF)=Main Channel Distance
X Axis Title(XS)=Station
BEGIN DESCRIPTION:
BIG BROWN CREEK
END DESCRIPTION:
DSS Export Rating Curves= 0
DSS Export Rating Curve Sorted= 0
DSS Export Volume Flow Curves= 0
DXF OffsetX= 0
DXF OffsetY= 0
DXF ScaleX= 1
DXF ScaleY= 10

--- BIG BROWN CREEK.p01 (plan) ---

Plan Title=Multiple Run
Short Identifier=Multiple
Geom File=g01
Flow File=f01
Subcritical Flow
K Sum by GR= 0
Std Step Tol= 0.01
Critical Tol= 0.01
Num of Std Step Trials= 20
Max Error Tol= 0.3
Flow Tol Ratio= 0.001
Split Flow NTrial= 30
Split Flow Tol= 0.02
Split Flow Ratio= 0.02
Log Output Level= 0
Friction Slope Method= 1
Unsteady Friction Slope Method= 2
Unsteady Bridges Friction Slope Method= 1
Parabolic Critical Depth
Global Vel Dist=  1 , 1 , 1
Global Log Level= 0
CheckData=True
Encroach Param= -1, 0, 0, 0
BEGIN DESCRIPTION:
Multiple Run
END DESCRIPTION:

--- BIG BROWN CREEK.f01 (steady flow) ---

Flow Title=Multiple
Program Version=4.10
Number of Profiles= 7
Profile Names=10-year,25-year,50-year,1pct_min,100-year,1pct_plu,500-year
River Rch & RM=BIG BROWN CREEK,Reach-1         ,72445
    1425    1969    2422    2174    2941    3977    4320
River Rch & RM=BIG BROWN CREEK,Reach-1         ,70733
    2137    3011    3751    3406    4607    6230    6927
River Rch & RM=BIG BROWN CREEK,Reach-1         ,68051
    3987    5749    7271    6686    9043   12229   13950
River Rch & RM=BIG BROWN CREEK,Reach-1         ,58291
    5546    8104   10341    9585   12963   17531   20319
River Rch & RM=BIG BROWN CREEK,Reach-1         ,55288
    5921    8648   11031   10215   13815   18683   21618
River Rch & RM=BIG BROWN CREEK,Reach-1         ,48778
    6919   10134   12951   12009   16241   21964   25476
River Rch & RM=BIG BROWN CREEK,Reach-1         ,41732
    7045   10300   13145   12170   16459   22259   25739
River Rch & RM=BIG BROWN CREEK,Reach-1         ,37786
    8373   12303   15757   14632   19788   26761   31130
River Rch & RM=BIG BROWN CREEK,Reach-1         ,35336
   12775   19005   24548   22971   31066   42013   49607
River Rch & RM=BIG BROWN CREEK,Reach-1         ,29310
   12893   19116   24635   22994   31096   42054   49607
River Rch & RM=BIG BROWN CREEK,Reach-1         ,25453
   14328   21472   27880   26224   35465   47962   57220
River Rch & RM=BIG BROWN CREEK,Reach-1         ,22028
   15214   22798   29598   27833   37641   50905   60692
River Rch & RM=BIG BROWN CREEK,Reach-1         ,16209
   15341   22982   29833   28048   37932   51298   61134
River Rch & RM=BIG BROWN CREEK,Reach-1         ,14052
   15341   22982   29833   28048   37932   51298   61134
River Rch & RM=BIG BROWN CREEK,Reach-1         ,12018
   15402   23011   29833   28048   37932   51298   61134
River Rch & RM=BIG BROWN CREEK,Reach-1         ,317
   15695   23433   30347   28457   38485   52047   61701
Boundary for River Rch & Prof#=BIG BROWN CREEK,Reach-1         , 1
Up Type= 0
Dn Type= 3
Dn Slope=0.00142
Boundary for River Rch & Prof#=BIG BROWN CREEK,Reach-1         , 2
Up Type= 0
Dn Type= 3
Dn Slope=0.00142
Boundary for River Rch & Prof#=BIG BROWN CREEK,Reach-1         , 3
Up Type= 0
Dn Type= 3
Dn Slope=0.00142
Boundary for River Rch & Prof#=BIG BROWN CREEK,Reach-1         , 4
Up Type= 0
Dn Type= 3
Dn Slope=0.00142
Boundary for River Rch & Prof#=BIG BROWN CREEK,Reach-1         , 5
Up Type= 0
Dn Type= 3
Dn Slope=0.00142
Boundary for River Rch & Prof#=BIG BROWN CREEK,Reach-1         , 6
Up Type= 0
Dn Type= 3
Dn Slope=0.00142
Boundary for River Rch & Prof#=BIG BROWN CREEK,Reach-1         , 7
Up Type= 0
Dn Type= 3
Dn Slope=0.00142
DSS Import GetInterval= 0
DSS Import GetPeak= 0
DSS Import FillOption= 0

--- BIG BROWN CREEK.g01 (geometry) ---

Geom Title=Existing Conditions
Program Version=4.10

River Reach=BIG BROWN CREEK ,Reach-1
Reach XY= 30
       3611622.5       10615029.       3611749.5       10618968.
      3613059.25       10621365.       3612370.5       10623729.
        3612737.       10624495.       3612289.5       10624760.
        3613762.       10626584.      3614857.75       10629927.
       3615738.5       10630826.       3615654.5       10632493.
      3618382.25       10634375.        3619448.       10637531.
      3623069.75       10643962.       3627320.5       10649305.
      3629036.75       10650185.      3631642.25       10650066.
      3631869.25       10650950.      3632897.25       10650997.
      3633505.75       10650352.       3634736.5       10650668.
       3635498.5       10651930.       3635157.5       10652145.
      3635893.25       10652323.       3636456.5       10653471.
      3636334.75       10654883.        3637919.       10655950.
        3638383.       10657143.      3639732.25       10656725.
      3640627.25       10655759.       3641578.5       10656989.

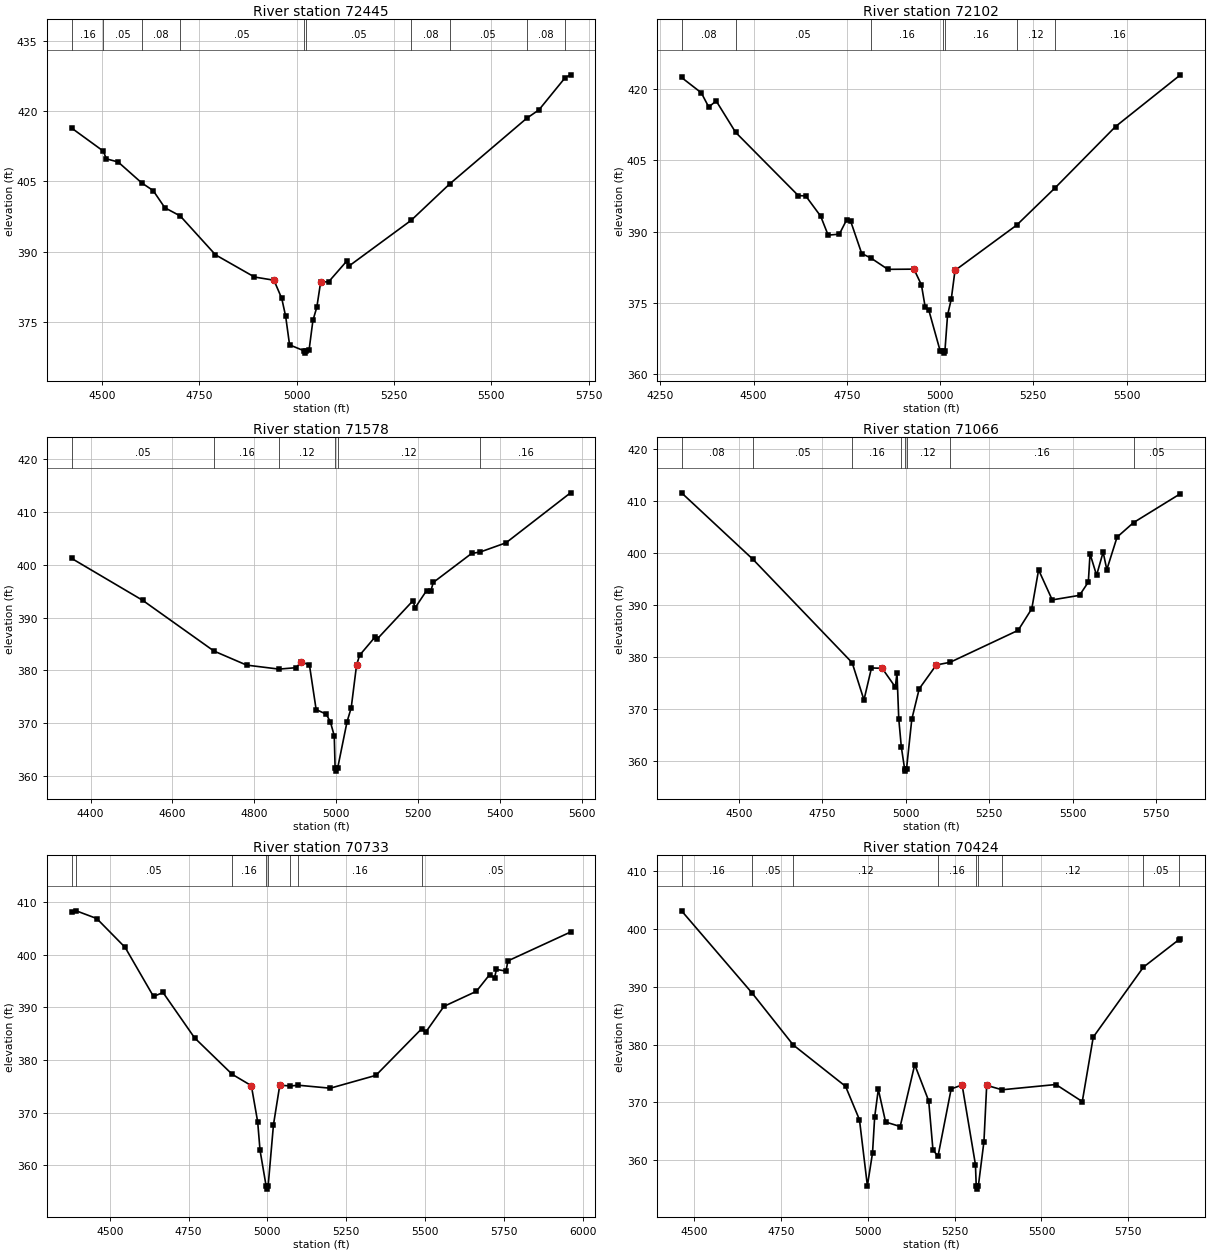
Type RM Length L Ch R = 1 ,72445   ,343,343,343
BEGIN DESCRIPTION:
BIG BROWN CREEK 111.0
END DESCRIPTION:
XS GIS Cut Line= 2
      3611100.33     10615138.79      3612380.64     10615186.53
#Sta/Elev= 30
  4422.2  416.37  4503.4  411.47  4511.5  409.81  4541.6  409.15  4602.3  404.68
  4631.6  403.06  4661.6   399.4  4701.1  397.65  4791.7  389.37  4891.8  384.64
  4941.8  383.96  4961.9  380.07  4971.9  376.25  4981.9  370.19  5018.9  368.93
  5021.6  368.43  5024.9  368.93  5031.9  369.02  5041.9  375.41  5051.9  378.21
  5061.9  383.64  5081.9  383.59  5128.8  388.04  5133.8  386.94  5294.2  396.72
  5393.1  404.47  5590.8  418.45  5622.3  420.24  5689.6   427.1  5703.4  427.71
#Mann= 10 ,-1 , 0
  4422.2     .16       0  4503.4     .05       0  4602.3     .08       0
  4701.1     .05       0  5018.9     .04       0  5024.9     .05       0
  5294.2     .08       0  5393.1     .05       0  5590.8     .08       0
  5689.6     .05       0
Bank Sta=4941.8,5061.9
XS Rating Curve= 0 ,0
Exp/Cntr=0.3,0.1

Type RM Length L Ch R = 1 ,72102   ,524,524,524
BEGIN DESCRIPTION:
BIG BROWN CREEK 110.0
END DESCRIPTION:
XS GIS Cut Line= 2
      3611056.84     10615472.99      3612393.72     10615490.35
#Sta/Elev= 30
  4307.2  422.39    4360  419.18    4380  416.19    4400  417.46    4452  410.87
    4620  397.57    4640   397.5    4680  393.24    4700  389.26    4730  389.46
    4750  392.54    4760  392.27    4790  385.39  4814.4  384.46    4860  382.07
    4930  382.11    4950   378.8    4960  374.18    4970  373.43    5000  364.98
    5007  364.96  5009.8  364.46    5013  364.96    5020  372.43    5030  375.82
    5040  381.84  5205.4  391.37  5308.8  399.24  5470.1  412.07  5644.2  422.95
#Mann= 7 ,-1 , 0
  4307.2     .08       0    4452     .05       0  4814.4     .16       0
    5007     .07       0    5013     .16       0  5205.4     .12       0
  5308.8     .16       0
Bank Sta=4930,5040
XS Rating Curve= 0 ,0
Exp/Cntr=0.3,0.1

Type RM Length L Ch R = 1 ,71578   ,512,512,512
BEGIN DESCRIPTION:
BIG BROWN CREEK 109.0
END DESCRIPTION:
XS GIS Cut Line= 2
      3611191.39     10615980.81      3612383.75     10615724.99
#Sta/Elev= 30
  4353.5  401.21    4527  393.28  4701.4  383.67  4781.2  381.01  4860.5  380.25
  4901.8  380.52  4914.2  381.55  4934.7   381.1  4951.2  372.59  4975.6  371.74
  4985.8  370.32  4995.5  367.62  4997.6  361.44  5000.3  360.94  5003.6  361.44
  5026.7  370.27  5036.9  372.92    5050     381  5057.4  382.87  5094.3  386.24
  5099.4  385.86    5188  393.21  5193.1  391.85    5221   395.1  5231.3  394.95
  5237.4  396.65  5331.1  402.14  5352.4  402.42  5415.3  404.16    5573  413.62
#Mann= 6 ,-1 , 0
  4353.5     .05       0  4701.4     .16       0  4860.5     .12       0
  4997.6     .07       0  5003.6     .12       0  5352.4     .16       0
Bank Sta=4914.2,5050
XS Rating Curve= 0 ,0
Exp/Cntr=0.3,0.1

Type RM Length L Ch R = 1 ,71066   ,333,333,333
BEGIN DESCRIPTION:
BIG BROWN CREEK 108.0
END DESCRIPTION:
XS GIS Cut Line= 2
      3611102.89       10616440.      3612565.52      10616127.7
#Sta/Elev= 30
    4328  411.61  4542.1  398.79  4839.4  378.88  4874.8   371.7  4897.3  377.87
  4929.4   377.8  4968.7   374.2  4973.8   376.9  4979.1  368.08  4986.8  362.64
  4996.5  358.49  4999.3  357.99  5002.5  358.49  5018.2  367.99  5040.4  373.85
  5091.6  378.44    5133  378.96    5337  385.12  5377.9  389.28  5398.3  396.76
  5439.2  390.98    5521  391.86  5547.4  394.42  5552.5  399.87  5572.1  395.73
  5591.8  400.18  5602.8  396.81  5633.5  403.07  5682.8  405.87  5823.6  411.45
#Mann= 8 ,-1 , 0
    4328     .08       0  4542.1     .05       0  4839.4     .16       0
  4986.8     .12       0  4996.5     .07       0  5002.5     .12       0
    5133     .16       0  5682.8     .05       0
Bank Sta=4929.4,5091.6
XS Rating Curve= 0 ,0
Exp/Cntr=0.3,0.1

Type RM Length L Ch R = 1 ,70733   ,309,309,309
BEGIN DESCRIPTION:
Mapping XS 4e8dd573
END DESCRIPTION:
XS GIS Cut Line= 3
      3611110.04     10616593.33      3611966.78     10616624.58
      3612578.73     10616236.57
#Sta/Elev= 30
  4379.1  408.21  4393.7  408.36  4458.7   406.9  4548.8  401.41  4638.8  392.09
  4668.9  392.85  4768.9  384.24    4888  377.32    4949  375.15  4969.1  368.27
  4976.5  362.88  4996.1     356  4998.8   355.5  5002.1     356  5019.1  367.72
  5039.1  375.23  5072.9   375.1  5098.4  375.23  5199.2  374.67  5343.9  377.11
  5489.5  385.99  5501.4  385.27  5559.5  390.21  5662.4  393.07  5704.8  396.26
  5720.1  395.61    5726  397.23  5756.5  396.91  5762.4  398.85    5961  404.33
#Mann= 8 ,-1 , 0
  4379.1     .16       0  4393.7     .05       0    4888     .16       0
  4996.1     .07       0  5002.1     .16       0  5072.9     .12       0
  5098.4     .16       0  5489.5     .05       0
Bank Sta=4949,5039.1
XS Rating Curve= 0 ,0
Exp/Cntr=0.3,0.1

Type RM Length L Ch R = 1 ,70424   ,812,812,812
BEGIN DESCRIPTION:
BIG BROWN CREEK 107.0
END DESCRIPTION:
XS GIS Cut Line= 2
       3611219.4       10616760.      3612589.21     10617192.29
#Sta/Elev= 30
  4463.8  403.17  4666.3  388.98  4785.3  379.95  4935.9  372.79    4976  367.01
  4998.8  355.57  5013.6  361.25  5019.8  367.49  5030.3  372.27  5051.2  366.61
  5093.2  365.83  5135.1  376.54  5175.3  370.27  5187.6  361.78  5202.1  360.67
    5240  372.33  5271.5  373.03  5309.9  359.23  5312.2  355.49  5314.9  354.99
  5318.2  355.49  5334.4  363.23  5342.3  372.96  5386.4  372.19  5541.6   373.1
  5617.5  370.15  5649.1  381.31  5793.5  393.42    5896  398.19  5900.2  398.36
#Mann= 9 ,-1 , 0
  4463.8     .16       0  4666.3     .05       0  4785.3     .12       0
  5202.1     .16       0  5312.2     .07       0  5318.2     .16       0
  5386.4     .12       0  5793.5     .05       0    5896     .16       0
Bank Sta=5271.5,5342.3
XS Rating Curve= 0 ,0
Exp/Cntr=0.3,0.1

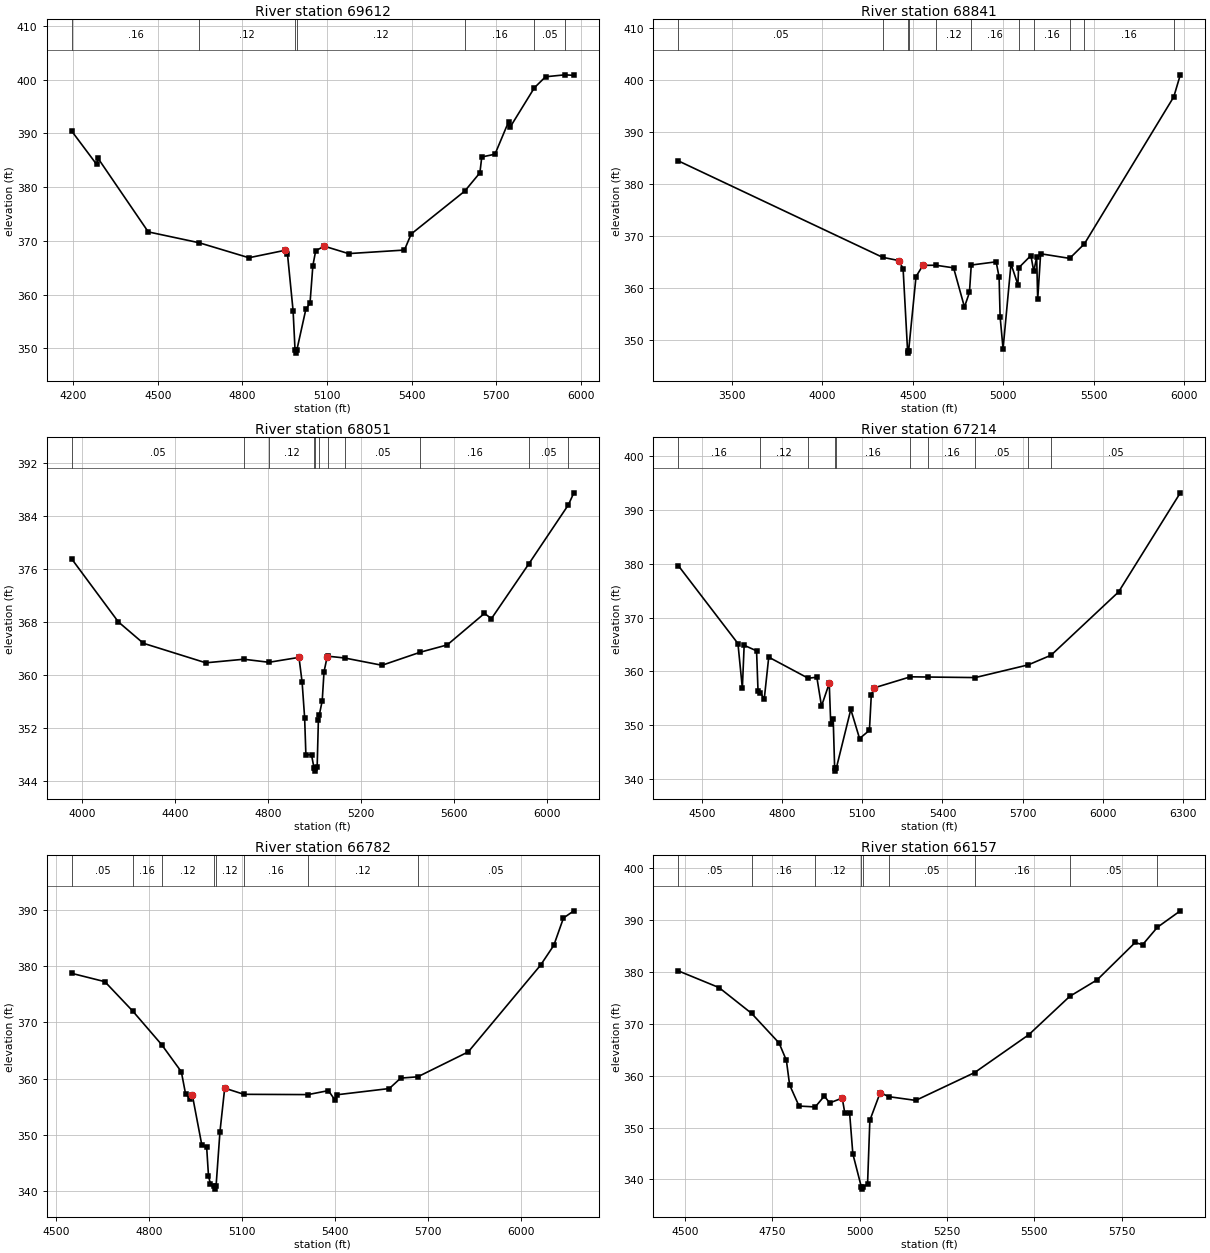
Type RM Length L Ch R = 1 ,69612   ,771,771,771
BEGIN DESCRIPTION:
BIG BROWN CREEK 105.0
END DESCRIPTION:
XS GIS Cut Line= 4
      3611209.51      10616972.3        3611522.     10617527.83
      3611945.61     10617500.05      3612612.28     10617229.22
#Sta/Elev= 30
  4194.4   390.4  4282.2  384.25  4287.9  385.33  4465.8  371.66  4646.4  369.64
    4823  366.85  4949.7  368.22  4959.7  367.59  4979.7     357  4986.7   349.6
  4989.5   349.1  4992.7   349.6  5024.9  357.24  5039.8  358.43  5049.9   365.4
  5059.9  368.14    5090  369.01  5176.5  367.62  5374.7  368.28  5398.8  371.27
  5588.8  379.25  5642.5  382.65  5649.2   385.6  5696.1  386.12  5744.2  392.14
  5749.6  391.13    5836  398.49  5875.4  400.53  5944.5  400.89  5975.9  400.79
#Mann= 7 ,-1 , 0
  4194.4     .16       0  4646.4     .12       0  4986.7     .07       0
  4992.7     .12       0  5588.8     .16       0    5836     .05       0
  5944.5     .16       0
Bank Sta=4949.7,5090
XS Rating Curve= 0 ,0
Exp/Cntr=0.3,0.1

Type RM Length L Ch R = 1 ,68841   ,790,790,790
BEGIN DESCRIPTION:
BIG BROWN CREEK 104.0
END DESCRIPTION:
XS GIS Cut Line= 2
      3610167.84     10618798.66      3612604.98     10617479.41
#Sta/Elev= 30
  3205.8   384.5  4333.6  365.95  4424.5  365.31    4447  363.73  4471.6  348.02
  4474.3  347.52  4477.6  348.02  4518.3  362.24  4556.4   364.4  4628.3  364.42
  4725.7  363.92  4785.6  356.39  4813.2   359.2  4823.2  364.46  4960.6  365.08
  4976.8  362.15  4982.5  354.53  4998.7  348.34  5042.5  364.68  5080.5   360.7
  5084.5  363.91  5152.3  366.28  5168.3  363.24  5184.2  365.99  5189.9  357.84
  5206.1  366.63  5366.3  365.74  5447.4  368.52    5941  396.81  5977.1  401.04
#Mann= 11 ,-1 , 0
  3205.8     .05       0  4333.6     .16       0  4471.6     .07       0
  4477.6     .16       0  4628.3     .12       0  4823.2     .16       0
  5084.5     .12       0  5168.3     .16       0  5366.3     .12       0
  5447.4     .16       0    5941     .05       0
Bank Sta=4424.5,4556.4
XS Rating Curve= 0 ,0
Exp/Cntr=0.3,0.1

Type RM Length L Ch R = 1 ,68051   ,837,837,837
BEGIN DESCRIPTION:
BIG BROWN CREEK 102.0
END DESCRIPTION:
XS GIS Cut Line= 3
      3610860.52     10618720.55      3611949.08     10618283.04
      3612933.48     10618329.92
#Sta/Elev= 30
  3956.6  377.46  4156.8  367.97  4264.4  364.74  4533.1  361.79  4696.3  362.33
  4804.6  361.87  4933.6  362.61  4947.1  358.82  4957.8  353.49  4963.2  347.92
  4987.4   347.9    4998  345.94  5000.8  345.44    5004  345.94  5011.6  346.03
    5017  353.18  5021.2  353.98  5033.4  356.05  5041.2  360.45  5054.9  362.72
  5057.7  362.79  5129.6  362.52  5290.5  361.42  5455.8   363.4  5570.8  364.49
    5731  369.25    5761  368.46  5920.4  376.66  6091.9  385.64  6115.3  387.45
#Mann= 11 ,-1 , 0
  3956.6     .05       0  4696.3     .16       0  4804.6     .12       0
    4998     .07       0    5004     .12       0  5021.2     .05       0
  5057.7     .16       0  5129.6     .05       0  5455.8     .16       0
  5920.4     .05       0  6091.9     .16       0
Bank Sta=4933.6,5054.9
XS Rating Curve= 0 ,0
Exp/Cntr=0.3,0.1

Type RM Length L Ch R = 1 ,67214   ,432,432,432
BEGIN DESCRIPTION:
BIG BROWN CREEK 101.0
END DESCRIPTION:
XS GIS Cut Line= 2
      3611240.73     10619236.17      3612954.27     10618470.55
#Sta/Elev= 30
  4412.2  379.65  4635.4  365.17  4651.9  356.88  4658.6  364.85    4705  363.82
  4710.5  356.31  4718.9  356.07  4733.7  354.87  4750.5  362.65  4898.3  358.73
  4930.3  358.93  4947.7  353.56  4976.7  357.79  4982.2   350.3  4991.5  351.15
  4996.9     342  4999.7   341.5  5002.9     342  5057.3  352.95    5090  347.55
  5126.9  349.07  5133.9  355.66  5144.7  356.95  5280.1     359  5345.5  358.96
  5522.3  358.86  5720.7  361.22  5805.9  363.01  6058.2  374.75    6289  393.14
#Mann= 10 ,-1 , 0
  4412.2     .16       0  4718.9     .12       0  4898.3     .16       0
  4996.9     .07       0  5002.9     .16       0  5280.1     .12       0
  5345.5     .16       0  5522.3     .05       0  5720.7     .16       0
  5805.9     .05       0
Bank Sta=4976.7,5144.7
XS Rating Curve= 0 ,0
Exp/Cntr=0.3,0.1

Type RM Length L Ch R = 1 ,66782   ,625,625,625
BEGIN DESCRIPTION:
BIG BROWN CREEK 100.0
END DESCRIPTION:
XS GIS Cut Line= 2
      3611556.35     10619582.02      3612945.77      10618749.4
#Sta/Elev= 30
  4550.2  378.75  4656.9  377.27  4747.4     372    4840  366.06  4903.7  361.22
  4917.4  357.25    4933  356.37  4938.8  357.16  4969.9  348.13  4985.4  347.77
  4991.3  342.69  4997.2  341.29  5009.7  340.81  5012.5  340.31  5015.7  340.81
  5028.3  350.54  5043.6   358.3  5105.6   357.2  5312.4  357.15  5378.2  357.86
  5399.6  356.16  5405.4  357.12  5574.6  358.23  5611.5  360.09  5666.4  360.32
  5829.3  364.76  6062.6  380.21  6105.4  383.75  6136.5  388.61    6170  389.89
#Mann= 8 ,-1 , 0
  4550.2     .05       0  4747.4     .16       0    4840     .12       0
  5009.7     .07       0  5015.7     .12       0  5105.6     .16       0
  5312.4     .12       0  5666.4     .05       0
Bank Sta=4938.8,5043.6
XS Rating Curve= 0 ,0
Exp/Cntr=0.3,0.1

Type RM Length L Ch R = 1 ,66157   ,806,806,806
BEGIN DESCRIPTION:
BIG BROWN CREEK 99.0
END DESCRIPTION:
XS GIS Cut Line= 2
       3611910.5      10619941.4      3613113.49     10619155.03
#Sta/Elev= 30
  4480.9  380.25  4597.6  377.02  4690.9  372.04  4769.5  366.33  4790.5  362.97
  4799.7  358.24  4826.7  354.16  4873.1  353.99  4899.1  356.09  4914.3  354.76
  4950.4   355.7  4957.7  352.79  4971.5  352.79  4980.7  344.94  5004.7  338.63
  5007.5  338.13  5010.7  338.63  5022.8  339.04  5029.4   351.4    5059  356.75
  5083.7  355.97  5160.8  355.25  5329.1  360.61  5484.3  367.92  5601.5  375.32
  5680.4  378.53  5788.9  385.72    5810  385.28  5852.4  388.65  5918.1  391.83
#Mann= 9 ,-1 , 0
  4480.9     .05       0  4690.9     .16       0  4873.1     .12       0
  5004.7     .07       0  5010.7     .12       0  5083.7     .05       0
  5329.1     .16       0  5601.5     .05       0  5852.4     .16       0
Bank Sta=4950.4,5059
XS Rating Curve= 0 ,0
Exp/Cntr=0.3,0.1

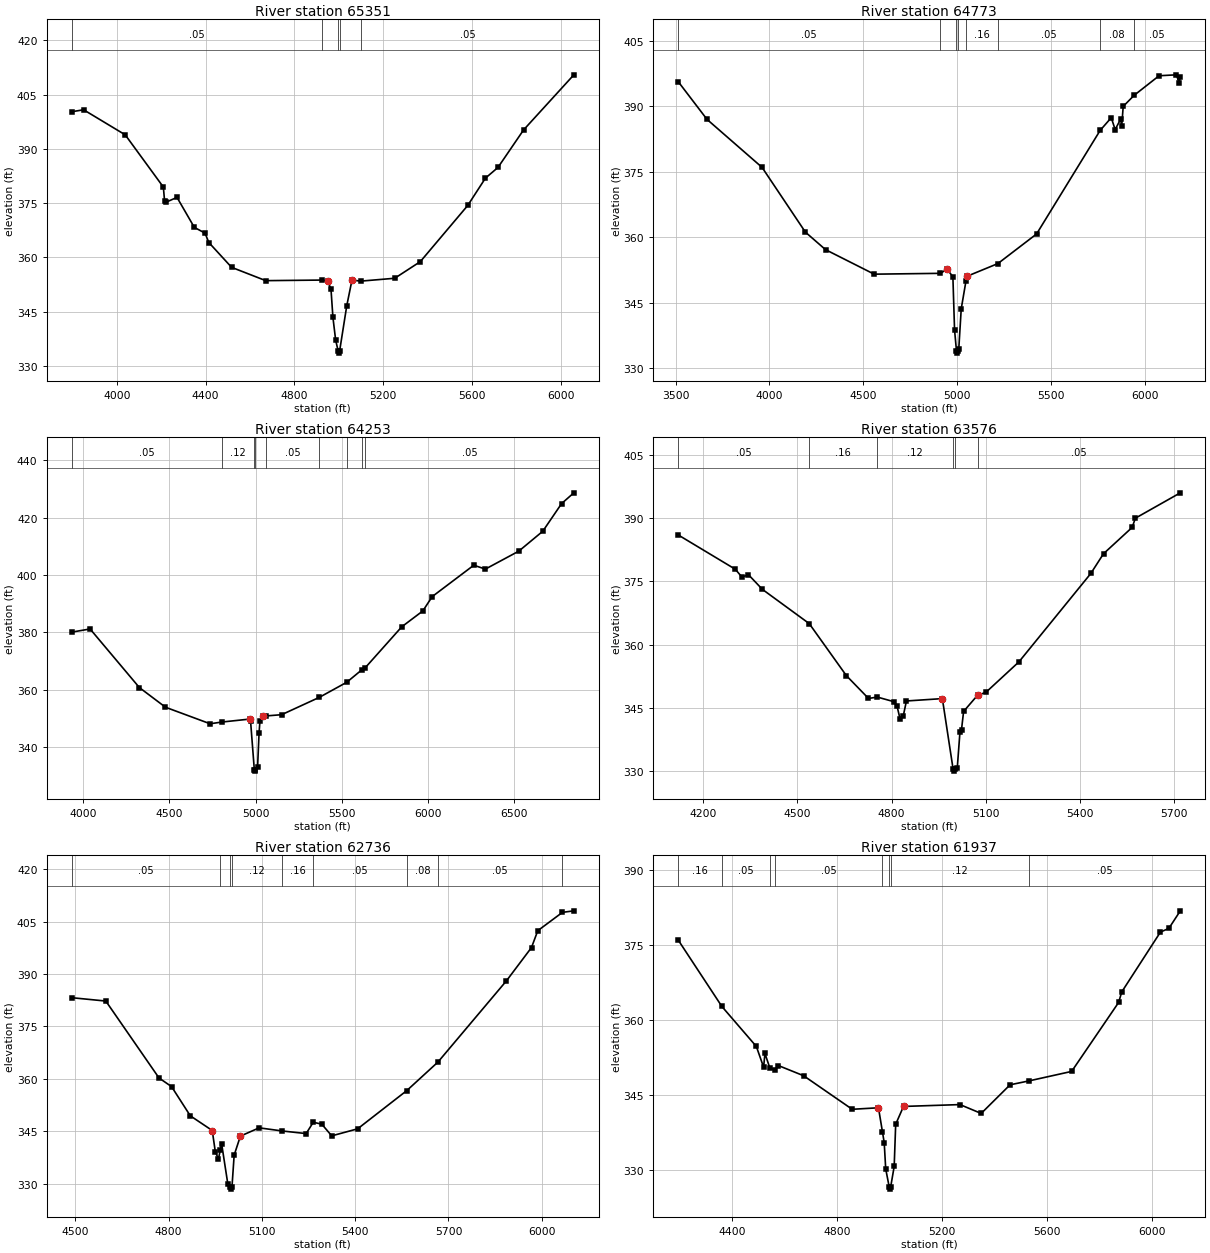
Type RM Length L Ch R = 1 ,65351   ,578,578,578
BEGIN DESCRIPTION:
BIG BROWN CREEK 96.0
END DESCRIPTION:
XS GIS Cut Line= 3
      3611337.16     10620588.11      3612274.63     10620374.57
      3613331.17      10619614.7
#Sta/Elev= 30
  3797.2  400.26  3850.6   400.8  4038.1  393.88    4210  379.44  4215.3  375.72
  4220.5  375.22  4271.5  376.59  4349.5  368.31  4397.7  366.71  4415.1  364.11
  4517.6  357.26  4671.5  353.58  4923.2  353.74  4950.9  353.51  4965.6  351.16
  4974.2  343.46  4986.5  337.17  4998.2  334.05    5001  333.55  5004.2  334.05
  5036.8  346.71  5060.1  353.73  5100.1  353.45  5252.8  354.24  5368.2  358.84
  5581.8  374.35  5661.6  381.91  5718.1  384.86  5833.5  395.23  6060.1  410.46
#Mann= 5 ,-1 , 0
  3797.2     .05       0  4923.2     .16       0  4998.2     .07       0
  5004.2     .16       0  5100.1     .05       0
Bank Sta=4950.9,5060.1
XS Rating Curve= 0 ,0
Exp/Cntr=0.3,0.1

Type RM Length L Ch R = 1 ,64773   ,520,520,520
BEGIN DESCRIPTION:
BIG BROWN CREEK 95.0
END DESCRIPTION:
XS GIS Cut Line= 3
       3611373.6     10621280.82      3612915.25     10620530.82
      3613649.65     10619911.02
#Sta/Elev= 30
  3513.7  395.64  3667.1     387  3960.3  376.01  4191.3  361.17  4298.5  357.16
  4557.7  351.54  4909.7  351.73  4946.6  352.65  4977.2  350.96  4986.1  338.77
  4996.4  333.95  4999.2  333.45  5002.4  333.95  5008.7  334.49  5021.7  343.61
  5046.9  349.96  5053.8  351.08  5217.1  353.97  5423.2  360.75    5762  384.48
  5821.1  387.39  5841.9  384.67  5870.5     387    5877  385.57  5884.8  389.98
  5943.2  392.52    6076     397  6168.3  397.21  6182.6   395.4  6189.1  396.73
#Mann= 8 ,-1 , 0
  3513.7     .05       0  4909.7     .12       0  4996.4     .07       0
  5002.4     .12       0  5046.9     .16       0  5217.1     .05       0
    5762     .08       0  5943.2     .05       0
Bank Sta=4946.6,5053.8
XS Rating Curve= 0 ,0
Exp/Cntr=0.3,0.1

Type RM Length L Ch R = 1 ,64253   ,677,677,677
BEGIN DESCRIPTION:
BIG BROWN CREEK 94.0
END DESCRIPTION:
XS GIS Cut Line= 3
      3611941.28     10621608.96       3612628.8     10621124.57
      3614561.11     10620379.78
#Sta/Elev= 30
  3934.4   380.1  4040.7   381.2  4326.4  360.77    4478   353.9  4736.6  348.14
  4807.8  348.76  4966.1  349.77  4971.4  349.04  4993.1  332.12  4995.8  331.62
  4999.1  332.12  5012.1  333.09  5020.7  344.98    5026  349.21  5044.2  350.98
  5058.9  350.86  5151.4   351.3  5370.2  357.35  5529.2  362.61  5617.7     367
  5636.9  367.71    5848  381.94  5970.3  387.48  6024.9  392.49    6266  403.43
  6333.2  402.08    6527  408.34  6666.1  415.28  6775.3  424.93  6846.3  428.68
#Mann= 9 ,-1 , 0
  3934.4     .05       0  4807.8     .12       0  4993.1     .07       0
  4999.1     .12       0  5058.9     .05       0  5370.2     .08       0
  5529.2     .05       0  5617.7     .16       0  5636.9     .05       0
Bank Sta=4966.1,5044.2
XS Rating Curve= 0 ,0
Exp/Cntr=0.3,0.1

Type RM Length L Ch R = 1 ,63576   ,840,840,840
BEGIN DESCRIPTION:
BIG BROWN CREEK 93.0
END DESCRIPTION:
XS GIS Cut Line= 3
      3612157.73     10621697.71      3612923.39     10621603.96
      3613741.07     10621739.37
#Sta/Elev= 30
    4120  386.02  4301.8   377.9  4323.4  376.01  4343.5  376.63  4388.2  373.13
  4537.5  365.02  4655.9  352.69  4726.4  347.29  4754.6  347.61    4807  346.53
    4817  345.59  4827.1  342.39  4837.2  343.15  4847.3  346.69  4961.8  347.25
    4996  330.57  4998.8  330.07    5002  330.57  5009.2   330.7  5017.8  339.24
  5022.9  339.93  5029.5  344.22  5074.2  348.06  5100.4  348.72  5205.9  355.96
  5434.9  376.89  5475.4  381.57  5566.7  387.81    5577  389.99  5720.2     396
#Mann= 6 ,-1 , 0
    4120     .05       0  4537.5     .16       0  4754.6     .12       0
    4996     .07       0    5002     .12       0  5074.2     .05       0
Bank Sta=4961.8,5074.2
XS Rating Curve= 0 ,0
Exp/Cntr=0.3,0.1

Type RM Length L Ch R = 1 ,62736   ,799,799,799
BEGIN DESCRIPTION:
BIG BROWN CREEK 91.0
END DESCRIPTION:
XS GIS Cut Line= 2
      3612110.86     10622301.88      3613714.84      10622114.4
#Sta/Elev= 30
  4488.4  383.21  4597.9  382.25    4769  360.25  4809.4  357.77  4869.7  349.42
  4940.2  345.22  4950.3  339.01  4960.3  337.16  4965.9  339.53  4970.4  341.44
  4990.5  329.83  4997.6  328.95  5000.4  328.45  5003.6  328.95  5010.7  338.16
  5030.8  343.62  5091.2  345.98    5166  345.08  5242.2  344.34  5265.2  347.58
  5292.6  347.03  5324.5  343.69  5407.9   345.7  5566.3  356.66  5666.3  364.81
  5886.6  388.05  5967.1  397.56  5987.3  402.38  6066.6  407.62  6103.3  408.06
#Mann= 9 ,-1 , 0
  4488.4     .05       0  4965.9     .12       0  4997.6     .07       0
  5003.6     .12       0    5166     .16       0  5265.2     .05       0
  5566.3     .08       0  5666.3     .05       0  6066.6      .1       0
Bank Sta=4940.2,5030.8
XS Rating Curve= 0 ,0
Exp/Cntr=0.3,0.1

Type RM Length L Ch R = 1 ,61937   ,575,575,575
BEGIN DESCRIPTION:
BIG BROWN CREEK 89.0
END DESCRIPTION:
XS GIS Cut Line= 3
      3611947.84      10622870.3      3612600.64     10623002.25
      3613696.08       10622406.
#Sta/Elev= 30
  4194.5  375.93  4360.8  362.65  4492.2  354.64  4519.8   350.5  4524.9  353.24
  4543.8   350.3  4563.1  350.01  4575.7  350.83  4672.1  348.79  4857.4  342.07
  4957.5  342.37  4972.7  337.55  4979.4  335.39  4985.1  330.13  4998.2  326.59
    5001  326.09  5004.2  326.59  5017.4  330.63  5023.1  339.07  5052.9  342.64
  5268.1  343.01  5348.9  341.24    5459  346.97  5530.9  347.75  5693.6  349.65
  5872.6  363.45  5884.5  365.56    6032  377.54    6064  378.27  6107.7  381.79
#Mann= 8 ,-1 , 0
  4194.5     .16       0  4360.8     .05       0  4543.8     .16       0
  4563.1     .05       0  4972.7     .12       0  4998.2     .07       0
  5004.2     .12       0  5530.9     .05       0
Bank Sta=4957.5,5052.9
XS Rating Curve= 0 ,0
Exp/Cntr=0.3,0.1

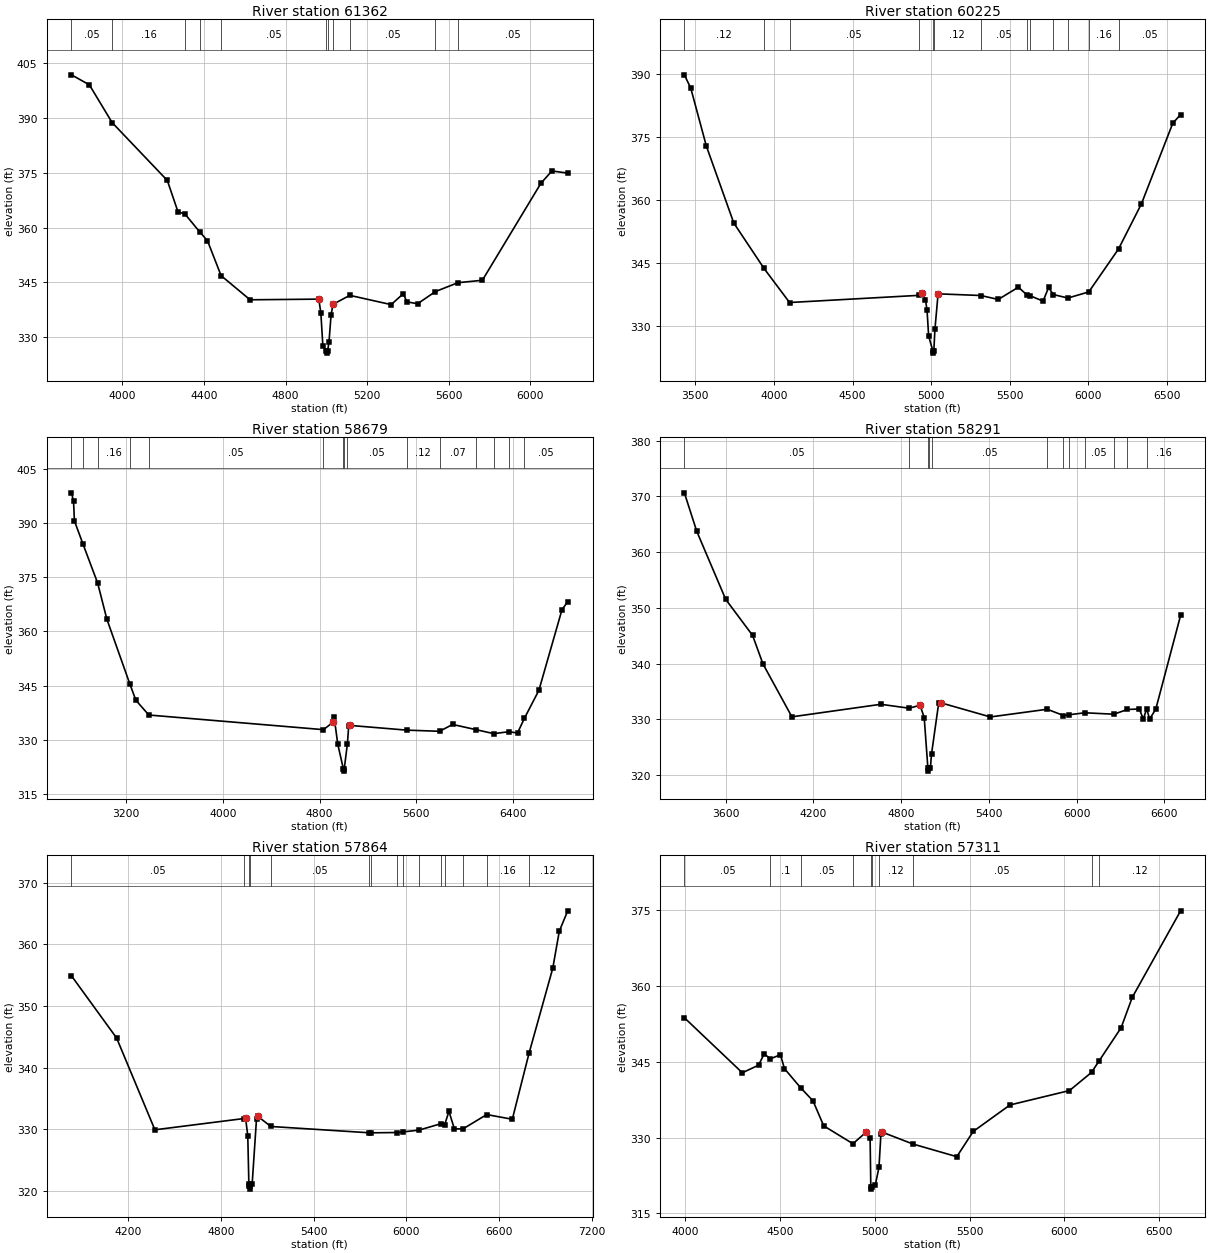
Type RM Length L Ch R = 1 ,61362   ,1137,1137,1137
BEGIN DESCRIPTION:
BIG BROWN CREEK 88.0
END DESCRIPTION:
XS GIS Cut Line= 4
      3611579.85     10622981.44      3612558.98     10623418.92
      3612885.37     10623418.92       3613829.8     10622995.31
#Sta/Elev= 30
  3750.2  401.72    3838  398.98  3949.5  388.68  4220.3  372.86  4272.2  364.36
  4307.8  363.64  4379.8  358.76  4416.9  356.45  4484.1  346.86  4626.2  340.27
  4963.3  340.45  4973.3  336.69  4983.3  327.59  5000.3   326.2    5003   325.7
  5006.3   326.2  5013.3  328.78  5023.3  336.06  5032.4  339.02  5115.4  341.48
  5318.1  338.95  5378.2  341.96  5394.8  339.71  5447.7  339.19  5535.4  342.52
  5645.8  344.94  5765.5   345.6  6052.4  372.07  6106.4  375.46  6184.1  374.88
#Mann= 11 ,-1 , 0
  3750.2     .05       0  3949.5     .16       0  4307.8     .05       0
  4379.8     .16       0  4484.1     .05       0  5000.3     .03       0
  5006.3     .05       0  5032.4     .12       0  5115.4     .05       0
  5535.4     .12       0  5645.8     .05       0
Bank Sta=4963.3,5032.4
XS Rating Curve= 0 ,0
Exp/Cntr=0.3,0.1

Type RM Length L Ch R = 1 ,60225   ,1546,1546,1546
BEGIN DESCRIPTION:
BIG BROWN CREEK 87.0
END DESCRIPTION:
XS GIS Cut Line= 4
      3611253.46     10623300.89       3612343.7     10624023.09
      3612774.25     10624036.98      3613884.88     10623155.41
#Sta/Elev= 30
  3430.2  389.88  3470.9  386.71  3570.1  372.91  3744.6  354.59  3937.1  343.77
  4099.4  335.66  4922.1  337.37    4944  337.85    4964   336.3    4974  333.77
    4984  327.67    5011  324.11  5013.8  323.61    5017  324.11    5024  329.28
    5044  337.73  5316.2  337.33  5426.7  336.39  5554.9  339.31  5609.4  337.46
  5626.1  337.33  5711.8  335.99  5747.2  339.25  5776.4  337.56  5870.1  336.73
  6002.8  338.19  6191.7  348.41  6337.4  359.15    6537  378.36  6586.7  380.41
#Mann= 13 ,-1 , 0
  3430.2     .12       0  3937.1     .16       0  4099.4     .05       0
  4922.1     .12       0    5011     .07       0    5017     .12       0
  5316.2     .05       0  5609.4     .07       0  5626.1     .12       0
  5776.4     .16       0  5870.1     .12       0  6002.8     .16       0
  6191.7     .05       0
Bank Sta=4944,5044
XS Rating Curve= 0 ,0
Exp/Cntr=0.3,0.1

Type RM Length L Ch R = 1 ,58679   ,388,388,388
BEGIN DESCRIPTION:
BIG BROWN CREEK 86.0
END DESCRIPTION:
XS GIS Cut Line= 4
      3610938.72     10623636.89      3612251.25     10624921.64
       3612905.6       10624886.      3614021.21     10623714.22
#Sta/Elev= 30
  2745.6  398.34  2762.7  396.06  2769.8  390.59  2841.9  384.08  2962.3  373.39
  3038.5  363.41  3228.3  345.53  3278.9  340.97  3386.1  336.88  4832.3  332.83
  4911.1  334.86  4921.1  336.27  4951.2  328.79  4998.2  321.86    5001  321.36
  5004.2  321.86    5031  328.97  5041.3  333.75  5051.3  334.01  5520.8   332.7
  5793.7  332.38  5902.4  334.27  6092.9  332.85  6242.5  331.73  6366.4  332.25
  6439.9  331.92    6497  335.98  6616.7  343.71  6807.6  365.96  6855.5  368.26
#Mann= 15 ,-1 , 0
  2745.6     .16       0  2841.9      .1       0  2962.3     .16       0
  3228.3     .12       0  3386.1     .05       0  4832.3     .12       0
  4998.2     .07       0  5004.2     .12       0    5031     .05       0
  5520.8     .12       0  5793.7     .07       0  6092.9     .12       0
  6242.5     .05       0  6366.4     .16       0    6497     .05       0
Bank Sta=4911.1,5051.3
XS Rating Curve= 0 ,0
Exp/Cntr=0.3,0.1

Type RM Length L Ch R = 1 ,58291   ,427,427,427
BEGIN DESCRIPTION:
BIG BROWN CREEK 85.0
END DESCRIPTION:
XS GIS Cut Line= 3
      3611649.63     10626410.17      3612849.61     10625210.19
      3614049.62     10624010.18
#Sta/Elev= 30
  3317.8  370.65  3402.6  363.74  3600.6  351.53  3784.5  345.07  3855.2  339.96
  4053.2  330.46  4661.3  332.71  4854.6  332.01    4930  332.54  4958.3  330.31
  4983.5  321.22  4986.3  320.72  4989.5  321.22  5000.7  321.35  5008.2  323.78
  5057.3  332.94  5071.4  332.98  5410.8  330.44  5799.6  331.82  5910.9   330.7
  5945.8  330.82  6056.5  331.19  6255.2  330.93  6347.7  331.78    6429  331.87
  6457.3  330.05  6479.7  331.94  6499.8  330.05  6542.2  331.85  6711.9  348.67
#Mann= 12 ,-1 , 0
  3317.8     .05       0  4854.6     .12       0  4983.5     .07       0
  4989.5     .12       0  5008.2     .05       0  5799.6     .12       0
  5910.9     .07       0  5945.8     .12       0  6056.5     .05       0
  6255.2     .16       0  6347.7     .05       0  6479.7     .16       0
Bank Sta=4930,5071.4
XS Rating Curve= 0 ,0
Exp/Cntr=0.3,0.1

Type RM Length L Ch R = 1 ,57864   ,553,553,553
BEGIN DESCRIPTION:
BIG BROWN CREEK 84.0
END DESCRIPTION:
XS GIS Cut Line= 2
      3612046.46     10626430.04      3614364.15     10624207.84
#Sta/Elev= 30
    3834  354.87  4126.2  344.78  4373.7   329.9  4947.6  331.72  4960.5  331.79
  4974.7  328.95  4981.9  321.04  4985.8  320.78  4988.6  320.28  4991.8  320.78
    5003  321.08  5031.3  331.69  5038.5   332.1  5124.2  330.44  5758.3  329.42
  5770.8  329.41  5940.1  329.46  5976.2  329.55  6082.5  329.85  6224.9  330.89
  6248.5  330.69  6276.3   332.9  6311.6  330.05  6367.3  330.05  6520.8  332.37
  6686.4  331.61  6794.5   342.3  6948.1  356.09  6990.5  362.11  7044.9  365.41
#Mann= 15 ,-1 , 0
    3834     .05       0  4947.6     .12       0  4985.8     .07       0
  4991.8     .12       0  5124.2     .05       0  5758.3      .1       0
  5770.8     .05       0  5940.1      .1       0  5976.2     .05       0
  6082.5     .16       0  6224.9     .05       0  6248.5     .16       0
  6367.3     .05       0  6520.8     .16       0  6794.5     .12       0
Bank Sta=4960.5,5038.5
XS Rating Curve= 0 ,0
Exp/Cntr=0.3,0.1

Type RM Length L Ch R = 1 ,57311   ,575,575,575
BEGIN DESCRIPTION:
BIG BROWN CREEK 83.0
END DESCRIPTION:
XS GIS Cut Line= 2
      3612306.88     10626664.42      3614424.73     10625128.11
#Sta/Elev= 30
  3996.2  353.71  4301.8  342.82  4387.7  344.33    4417  346.58  4449.3  345.57
  4502.9   346.4  4523.7  343.65    4610  339.82  4674.5  337.26  4730.9  332.32
  4884.9  328.78  4952.8  331.01  4975.5  329.97  4979.2   320.3  4981.9   319.8
  4985.2   320.3  5003.1  320.65  5022.3  324.12  5032.4  330.65  5038.6  331.08
  5201.6  328.72  5432.6  326.22  5519.1  331.21  5712.8  336.45  6026.7   339.3
  6142.8  342.89  6182.3  345.14  6298.8  351.72  6357.6  357.73  6612.6  374.86
#Mann= 10 ,-1 , 0
  3996.2     .05       0  4449.3      .1       0    4610     .05       0
  4884.9     .16       0  4979.2     .07       0  4985.2     .16       0
  5022.3     .12       0  5201.6     .05       0  6142.8     .16       0
  6182.3     .12       0
Bank Sta=4952.8,5038.6
XS Rating Curve= 0 ,0
Exp/Cntr=0.3,0.1

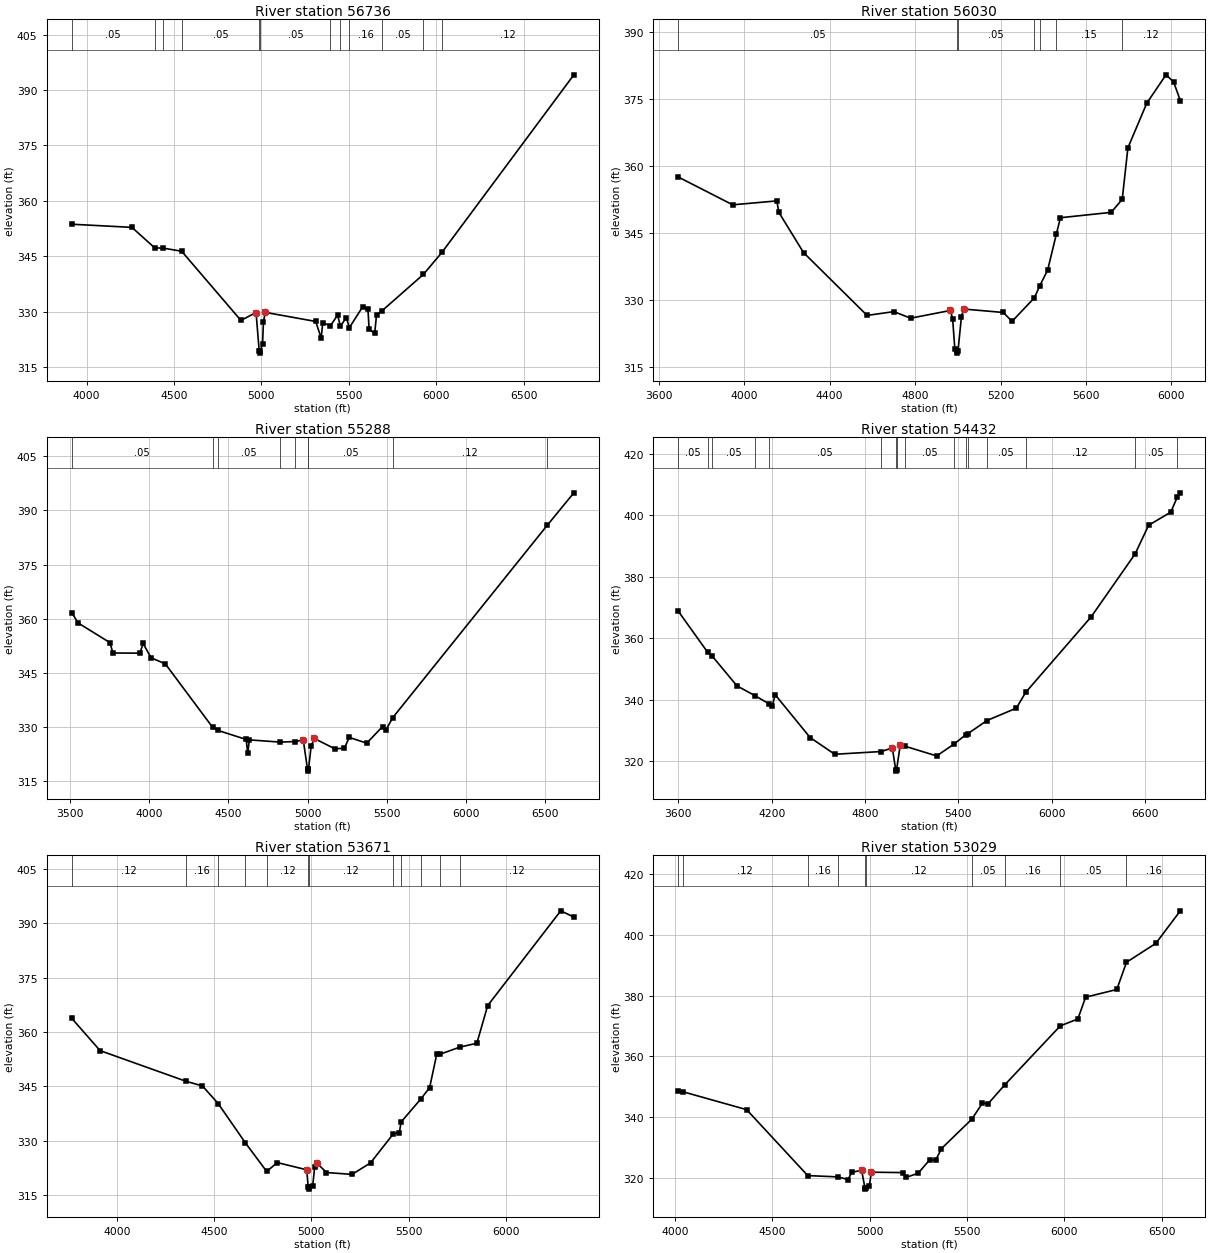
Type RM Length L Ch R = 1 ,56736   ,706,706,706
BEGIN DESCRIPTION:
BIG BROWN CREEK 81.0
END DESCRIPTION:
XS GIS Cut Line= 2
      3612315.55     10626838.03      3615023.86     10625883.18
#Sta/Elev= 30
  3915.6  353.65  4259.7   352.8  4390.2  347.24  4437.7  347.19  4544.1  346.34
    4883  327.62  4969.6  329.75  4987.8  319.26  4990.6  318.76  4993.8  319.26
  5006.8  321.33  5012.1  327.32  5022.6  329.79  5310.9  327.33  5341.9  322.85
  5351.3  326.98    5395  326.18  5436.2  329.04  5452.1  326.04    5486  328.38
  5503.3  325.65  5578.8  331.25  5609.7  330.57  5616.4  325.17  5648.2  324.13
  5658.8  329.17    5689  330.17  5926.8  340.07  6033.2  346.05  6787.3  394.09
#Mann= 12 ,-1 , 0
  3915.6     .05       0  4390.2     .08       0  4437.7     .15       0
  4544.1     .05       0  4987.8     .03       0  4993.8     .05       0
    5395     .16       0  5452.1     .05       0  5503.3     .16       0
    5689     .05       0  5926.8      .1       0  6033.2     .12       0
Bank Sta=4969.6,5022.6
XS Rating Curve= 0 ,0
Exp/Cntr=0.3,0.1

Type RM Length L Ch R = 1 ,56030   ,742,742,742
BEGIN DESCRIPTION:
BIG BROWN CREEK 79.0
END DESCRIPTION:
XS GIS Cut Line= 2
      3612471.84     10627133.16      3614754.72     10626577.63
#Sta/Elev= 30
  3691.8   357.6  3946.8  351.36  4153.1  352.24  4162.9  349.65  4278.3  340.65
  4575.6  326.58  4700.8  327.43  4779.1  325.96  4965.7  327.69    4976  325.72
  4986.3  318.98    4995  318.63  4997.8  318.13    5001  318.63  5017.1  326.32
  5027.4  328.01  5212.7  327.24  5253.9  325.25  5358.4  330.52  5383.6  333.23
  5420.5  336.73  5461.1  344.78  5480.3  348.47  5717.7  349.67  5769.5  352.59
    5796  364.13  5884.6  374.15  5974.3  380.49  6009.8  378.91  6041.3  374.73
#Mann= 7 ,-1 , 0
  3691.8     .05       0    4995     .03       0    5001     .05       0
  5358.4     .08       0  5383.6      .1       0  5461.1     .15       0
  5769.5     .12       0
Bank Sta=4965.7,5027.4
XS Rating Curve= 0 ,0
Exp/Cntr=0.3,0.1

Type RM Length L Ch R = 1 ,55288   ,856,856,856
BEGIN DESCRIPTION:
BIG BROWN CREEK 78.0
END DESCRIPTION:
XS GIS Cut Line= 2
       3612419.7     10627358.87      3615586.32      10627419.6
#Sta/Elev= 30
  3511.8  361.66  3551.7  358.78  3751.8  353.34  3771.8  350.44  3941.8   350.4
  3961.8   353.1  4011.8  349.12  4101.8  347.43  4400.9  329.78  4432.4  328.98
  4611.9  326.45  4621.9  322.59  4631.9  326.33  4825.9  325.72  4922.7  325.87
    4972  326.33    4999  318.16  5001.7  317.66    5005  318.16    5022  324.65
    5042  326.72    5172  323.84    5232  324.03    5262  327.03  5372.1  325.41
  5472.1  330.02  5492.1  328.95  5536.4  332.49  6511.7  385.91    6679  394.89
#Mann= 9 ,-1 , 0
  3511.8     .05       0  4400.9     .08       0  4432.4     .05       0
  4825.9     .16       0  4922.7     .05       0    4999     .03       0
    5005     .05       0  5536.4     .12       0  6511.7     .05       0
Bank Sta=4972,5042
XS Rating Curve= 0 ,0
Exp/Cntr=0.3,0.1

Type RM Length L Ch R = 1 ,54432   ,761,761,761
BEGIN DESCRIPTION:
BIG BROWN CREEK 76.0
END DESCRIPTION:
XS GIS Cut Line= 2
      3612766.95     10628556.78      3615822.38     10627515.16
#Sta/Elev= 30
  3599.1  368.87  3788.9  355.45  3818.4   354.2  3976.4  344.58  4093.4  341.36
  4180.9  338.78  4204.1  338.02  4221.9  341.71  4447.1  327.76  4605.6  322.32
  4905.8  323.22  4975.4  324.39  4997.2  317.34    5000  316.84  5003.2  317.34
  5026.3   325.3  5058.8  324.92  5260.6  321.78    5375  325.73  5448.3   328.7
  5459.7  328.97  5584.3   333.3  5773.2  337.33  5832.6  342.42  6253.8  367.01
  6536.2  387.45  6623.5  396.81  6765.6  401.05  6807.4  405.91  6827.2  407.35
#Mann= 16 ,-1 , 0
  3599.1     .05       0  3788.9     .12       0  3818.4     .05       0
  4093.4      .1       0  4180.9     .05       0  4905.8     .16       0
  4997.2     .07       0  5003.2     .16       0  5058.8     .05       0
    5375     .16       0  5448.3     .05       0  5459.7     .16       0
  5584.3     .05       0  5832.6     .12       0  6536.2     .05       0
  6807.4     .12       0
Bank Sta=4975.4,5026.3
XS Rating Curve= 0 ,0
Exp/Cntr=0.3,0.1

Type RM Length L Ch R = 1 ,53671   ,642,642,642
BEGIN DESCRIPTION:
BIG BROWN CREEK 75.0
END DESCRIPTION:
XS GIS Cut Line= 2
      3613235.67     10628877.97      3615786.19     10628452.88
#Sta/Elev= 30
  3765.8  363.75  3911.7  354.84  4354.6  346.37  4438.9  345.09  4520.1  340.21
  4659.6   329.4  4769.8  321.48  4824.1  323.94  4976.2  321.94  4983.3  317.11
  4986.1  316.61  4989.3  317.11  5006.6  317.49  5016.8  322.74  5026.9  323.88
  5077.6  321.19  5209.4  320.68  5304.5  323.86  5421.2  331.83  5452.7  332.17
  5461.9  335.15  5562.9  341.46  5608.7  344.61  5645.3  353.82  5663.8  353.87
  5764.8  355.82    5852  356.88  5907.8  367.28    6284  393.43  6351.5  391.72
#Mann= 12 ,-1 , 0
  3765.8     .12       0  4354.6     .16       0  4520.1     .12       0
  4659.6     .16       0  4769.8     .12       0  4983.3     .07       0
  4989.3     .12       0  5421.2     .05       0  5461.9      .1       0
  5562.9     .08       0  5663.8      .1       0  5764.8     .12       0
Bank Sta=4976.2,5026.9
XS Rating Curve= 0 ,0
Exp/Cntr=0.3,0.1

Type RM Length L Ch R = 1 ,53029   ,541,541,541
BEGIN DESCRIPTION:
BIG BROWN CREEK 73.0
END DESCRIPTION:
XS GIS Cut Line= 2
      3613678.44     10629121.02      3616255.55     10629042.93
#Sta/Elev= 30
  4017.3  348.44    4040  348.31  4368.6  342.38  4682.3  320.65  4835.5  320.23
  4888.9  319.36  4908.9  321.73  4958.9  322.41  4975.9  316.69  4978.7  316.19
  4981.9  316.69  4998.9  317.31  5008.9  321.77    5169  321.64    5189   320.1
    5249  321.41  5309.1  325.88  5339.1   325.7  5369.1  329.55  5524.7  339.23
  5579.2   344.5  5609.2  344.38    5694  350.55  5979.4     370  6069.4  372.26
  6109.4  379.45  6269.5  381.99  6319.2  390.96  6469.6  397.17  6595.6  407.91
#Mann= 10 ,-1 , 0
  4017.3     .16       0    4040     .12       0  4682.3     .16       0
  4835.5     .12       0  4975.9     .07       0  4981.9     .12       0
  5524.7     .05       0    5694     .16       0  5979.4     .05       0
  6319.2     .16       0
Bank Sta=4958.9,5008.9
XS Rating Curve= 0 ,0
Exp/Cntr=0.3,0.1