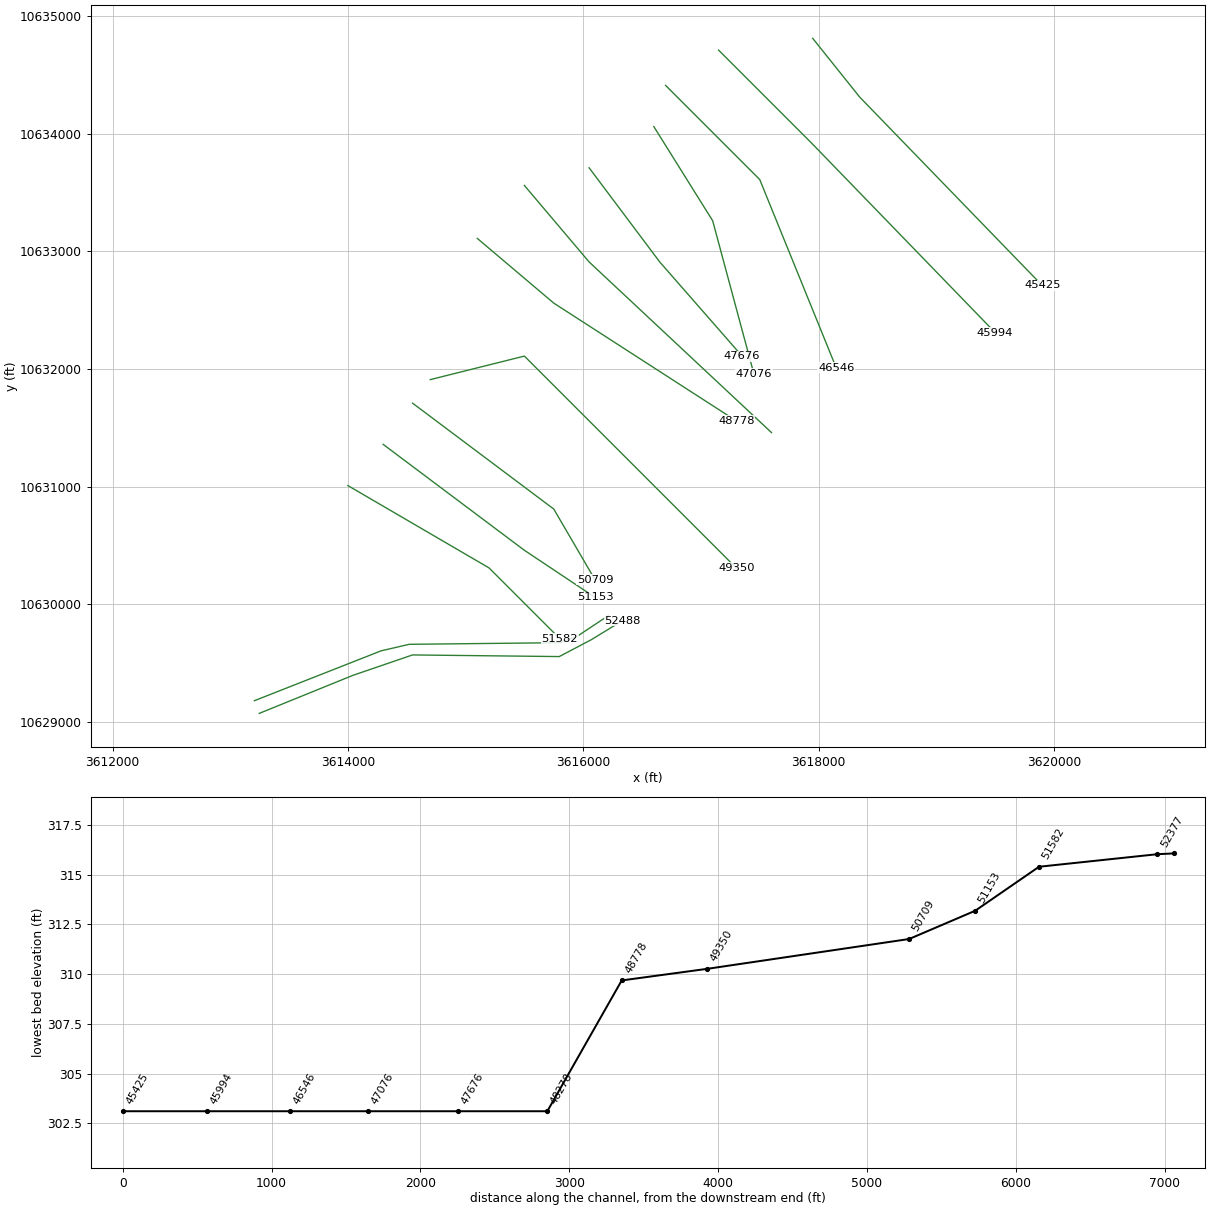
HEC-RAS study BIG BROWN CREEK.prj: BIG BROWN CREEK Base Level Engineering

--- BIG BROWN CREEK.g01 (geometry) --- (continued)

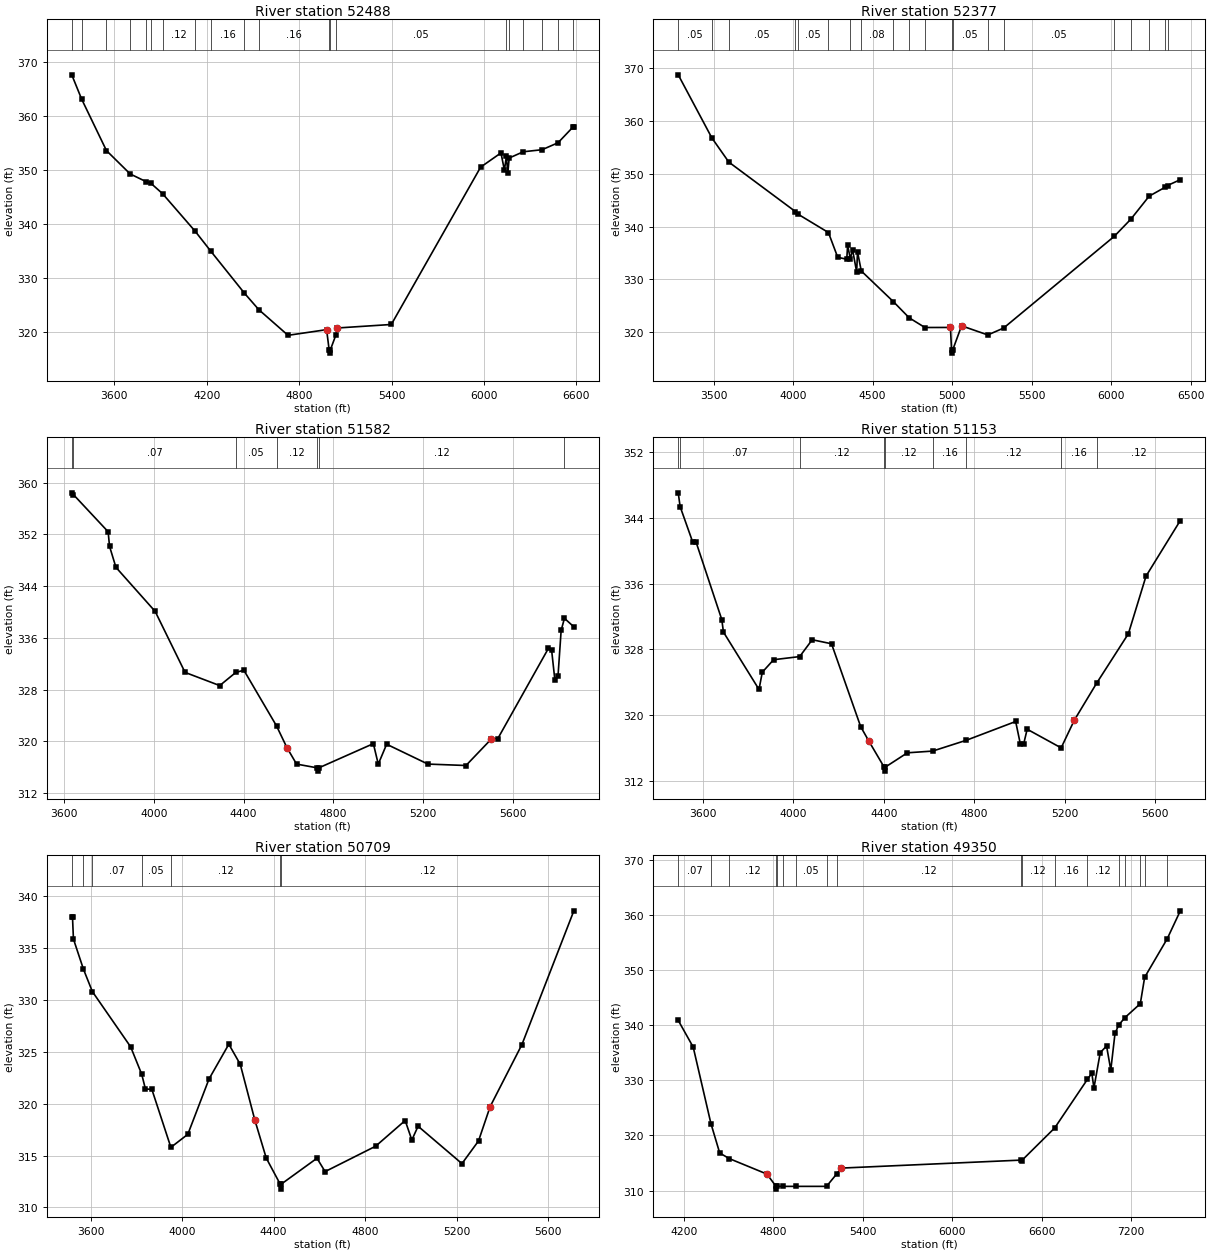
Type RM Length L Ch R = 1 ,52488   ,111,111,111
BEGIN DESCRIPTION:
BIG BROWN CREEK 72.0
END DESCRIPTION:
XS GIS Cut Line= 6
      3613247.12     10629074.31      3614042.27     10629397.23
      3614549.21     10629570.84      3615795.74     10629556.95
      3616066.57     10629699.31      3616333.97     10629862.52
#Sta/Elev= 30
  3323.4  367.64  3387.3  363.15  3548.6   353.6  3702.6  349.27  3807.7  347.82
  3837.2  347.54  3912.8  345.62  4125.3  338.63  4227.5  334.91    4445  327.16
  4537.9  324.12  4727.9  319.36  4978.3  320.41  4995.3  316.56    4998  316.06
  5001.3  316.56  5039.7   319.5  5048.3  320.72  5398.6  321.37  5978.6  350.53
  6110.9  353.17  6132.9  349.97    6146  352.54    6155  349.37    6164  352.22
  6255.5  353.38  6377.6  353.76  6481.4  355.05  6578.7  357.97    6584  357.97
#Mann= 20 ,-1 , 0
  3323.4     .08       0  3387.3     .16       0  3548.6     .08       0
  3702.6     .16       0  3807.7     .12       0  3837.2     .08       0
  3912.8     .12       0  4125.3     .08       0  4227.5     .16       0
    4445     .05       0  4537.9     .16       0  4995.3     .07       0
  5001.3     .16       0  5039.7     .05       0    6146     .16       0
    6164     .05       0  6255.5      .1       0  6377.6     .05       0
  6481.4     .16       0  6578.7     .08       0
Bank Sta=4978.3,5048.3
XS Rating Curve= 0 ,0
Exp/Cntr=0.3,0.1

Type RM Length L Ch R = 1 ,52377   ,795,795,795
BEGIN DESCRIPTION:
BIG BROWN CREEK 71.0
END DESCRIPTION:
XS GIS Cut Line= 6
      3613205.46     10629181.95      3614281.85     10629605.56
      3614521.43     10629661.11      3615802.68       10629675.
      3615955.46     10629734.03      3616212.42     10629904.18
#Sta/Elev= 30
    3278   368.8  3489.6  356.83  3596.2  352.25  4015.3  342.86  4028.7  342.42
  4222.5  338.89    4281  334.19  4337.9  333.83  4343.2  336.49  4360.1  333.94
  4374.3  335.63  4400.1  331.41  4405.4  335.25  4429.2   331.6  4630.7  325.79
  4730.4  322.72  4829.3  320.88  4989.9  320.89  4996.9  316.52  4999.7  316.02
  5002.9  316.52  5059.9   321.2  5224.8  319.47  5323.9  320.77  6019.8  338.16
  6124.3  341.42  6239.6  345.79  6341.2   347.5  6355.2  347.81  6435.5  348.92
#Mann= 20 ,-1 , 0
    3278     .05       0  3489.6      .1       0  3596.2     .05       0
  4015.3     .08       0  4028.7     .05       0  4222.5     .08       0
  4360.1     .05       0  4429.2     .08       0  4630.7     .05       0
  4730.4     .08       0  4829.3     .05       0  4996.9     .04       0
  5002.9     .05       0  5224.8     .08       0  5323.9     .05       0
  6019.8     .08       0  6124.3     .05       0  6239.6     .08       0
  6341.2     .12       0  6355.2     .05       0
Bank Sta=4989.9,5059.9
XS Rating Curve= 0 ,0
Exp/Cntr=0.3,0.1

Type RM Length L Ch R = 1 ,51582   ,429,429,429
BEGIN DESCRIPTION:
BIG BROWN CREEK 70.0
END DESCRIPTION:
XS GIS Cut Line= 3
      3613999.58     10631010.21      3615199.61     10630310.19
       3615799.6     10629710.19
#Sta/Elev= 30
  3634.2  358.43  3641.4  358.16  3796.3  352.41  3802.5  350.16    3831  346.91
  4005.9  340.09  4139.1  330.66  4293.7  328.62  4365.1  330.65  4401.2     331
  4546.7  322.39  4593.1  319.03  4636.1  316.48    4729  315.89  4731.7  315.39
    4735  315.89  4978.4  319.64  5000.3  316.47  5037.6  319.55  5221.5  316.48
  5391.2  316.26  5504.3  320.36  5532.6  320.39  5758.9  334.39    5773  334.08
  5787.2  329.56  5801.3  330.05  5815.4  337.16  5830.1  339.02    5872  337.71
#Mann= 7 ,-1 , 0
  3634.2     .12       0  3641.4     .07       0  4365.1     .05       0
  4546.7     .12       0    4729     .07       0    4735     .12       0
  5830.1     .05       0
Bank Sta=4593.1,5504.3
XS Rating Curve= 0 ,0
Exp/Cntr=0.3,0.1

Type RM Length L Ch R = 1 ,51153   ,444,444,444
BEGIN DESCRIPTION:
BIG BROWN CREEK 69.0
END DESCRIPTION:
XS GIS Cut Line= 3
      3614299.59      10631360.2      3615499.61     10630460.19
      3616099.58     10630060.21
#Sta/Elev= 30
  3490.2  347.05  3498.5  345.38  3553.8  341.09  3568.3  341.12  3682.9  331.62
  3690.2   330.1  3847.5  323.12  3862.1  325.22  3912.1  326.74  4027.4  327.12
  4082.9  329.17  4168.3  328.68  4297.5  318.58  4332.9  316.86  4400.8  313.68
  4403.5  313.18  4406.8  313.68  4503.8  315.41  4615.7  315.62    4765  316.94
  4982.9  319.22  5003.7  316.47  5018.8  316.54  5033.8  318.28  5184.1  316.01
  5242.6  319.39  5340.6  323.86  5481.5   329.9  5559.6  336.91  5711.3  343.68
#Mann= 9 ,-1 , 0
  3490.2     .05       0  3498.5     .07       0  4027.4     .12       0
  4400.8     .07       0  4406.8     .12       0  4615.7     .16       0
    4765     .12       0  5184.1     .16       0  5340.6     .12       0
Bank Sta=4332.9,5242.6
XS Rating Curve= 0 ,0
Exp/Cntr=0.3,0.1

Type RM Length L Ch R = 1 ,50709   ,1359,1359,1359
BEGIN DESCRIPTION:
BIG BROWN CREEK 68.0
END DESCRIPTION:
XS GIS Cut Line= 3
      3614549.59      10631710.2      3615749.61     10630810.19
      3616099.58     10630210.23
#Sta/Elev= 30
  3517.8     338    3521     338  3525.1  335.89  3568.8  332.98  3607.8  330.82
  3775.1  325.49  3823.6  322.84  3839.7  321.42  3867.8  321.39    3951  315.79
  4025.1  317.05  4117.8  322.39  4204.3  325.74  4254.3   323.8  4317.8  318.44
  4367.8  314.76  4428.4  312.26  4431.1  311.76  4434.4  312.26  4589.7  314.74
  4625.1  313.45    4846   315.9  4975.1  318.38  5004.3   316.5  5031.5  317.83
  5223.3  314.22  5295.7  316.41  5346.5  319.72  5485.5  325.71  5712.4  338.61
#Mann= 7 ,-1 , 0
  3517.8      .1       0  3568.8     .05       0  3607.8     .07       0
  3823.6     .05       0    3951     .12       0  4428.4     .07       0
  4434.4     .12       0
Bank Sta=4317.8,5346.5
XS Rating Curve= 0 ,0
Exp/Cntr=0.3,0.1

Type RM Length L Ch R = 1 ,49350   ,572,572,572
BEGIN DESCRIPTION:
BIG BROWN CREEK 67.0
END DESCRIPTION:
XS GIS Cut Line= 3
      3614699.66      10631910.2      3615499.61     10632110.19
      3617299.64     10630310.16
#Sta/Elev= 30
  4161.4  340.84  4261.9     336  4380.8  322.15  4439.7  316.81  4504.4  315.79
  4756.6  312.99    4818  310.76  4820.8  310.26    4824  310.76  4866.8  310.76
  4949.5  310.76  5156.7  310.76  5224.6     313  5254.7  314.07    6462  315.52
  6466.6  315.42  6688.4  321.35  6907.9  330.15  6937.6  331.26  6951.7   328.6
  6994.2  335.01  7036.6  336.19  7064.9  331.86  7093.2  338.48  7117.5  339.97
  7158.7  341.32  7263.1  343.87  7292.2  348.65    7444  355.65  7531.6   360.7
#Mann= 18 ,-1 , 0
  4161.4     .07       0  4380.8     .05       0  4504.4     .12       0
    4818    .033       0    4824     .12       0  4866.8     .07       0
  4949.5     .05       0  5156.7     .07       0  5224.6     .12       0
    6462     .16       0  6466.6     .12       0  6688.4     .16       0
  6907.9     .12       0  7117.5     .16       0  7158.7     .08       0
  7263.1     .05       0  7292.2     .16       0    7444     .05       0
Bank Sta=4756.6,5254.7
XS Rating Curve= 0 ,0
Exp/Cntr=0.3,0.1

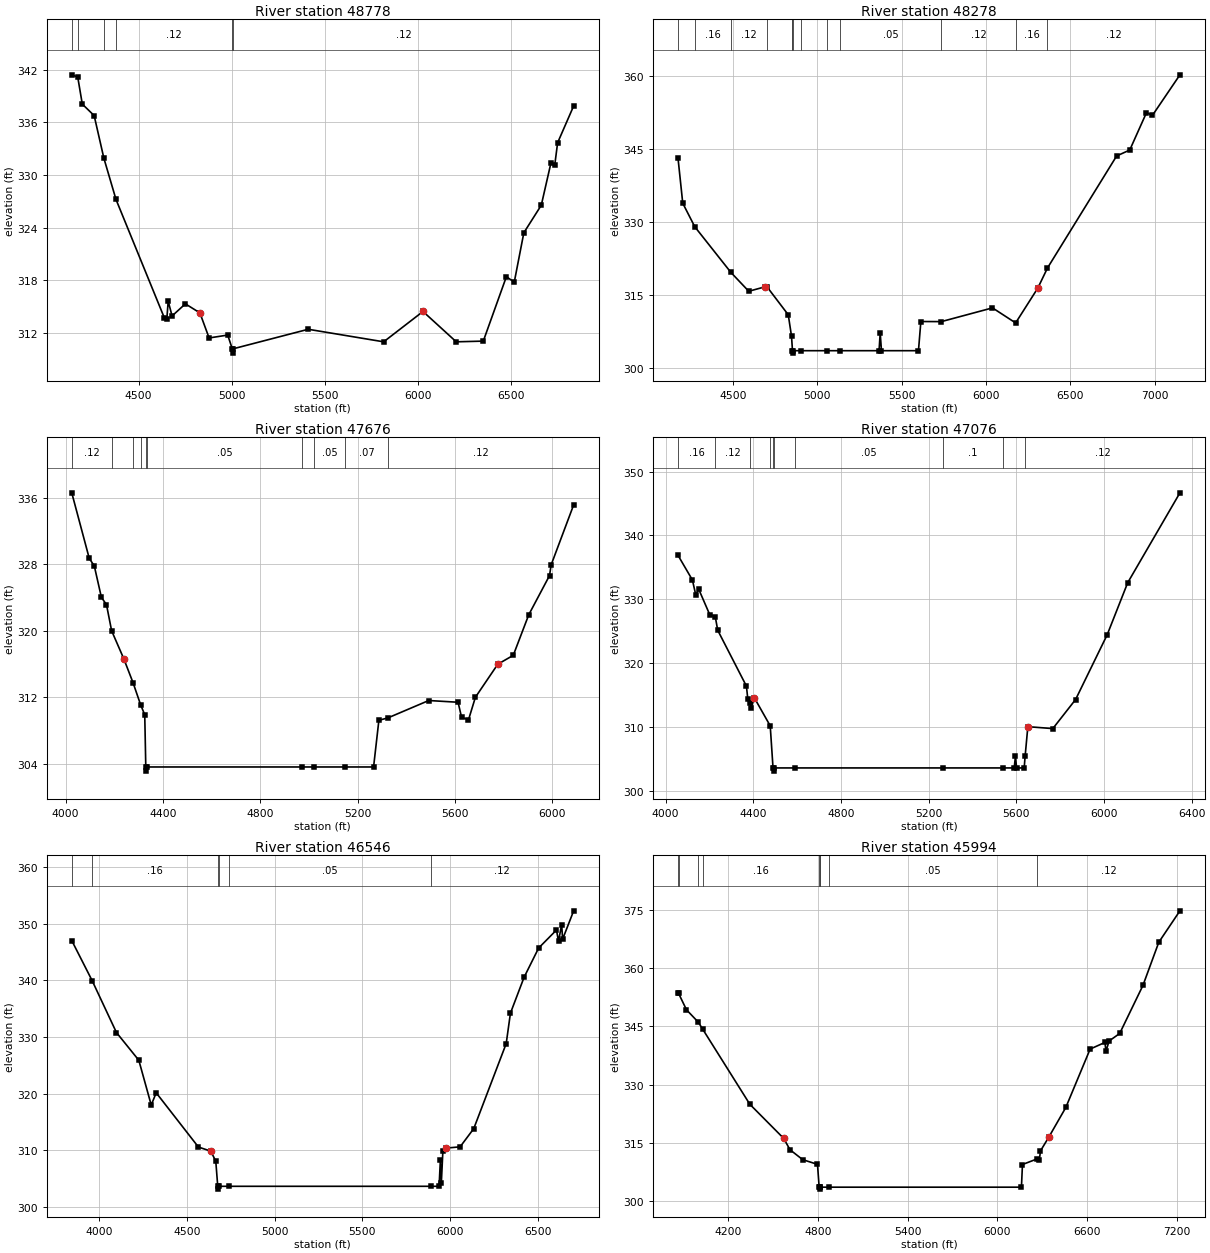
Type RM Length L Ch R = 1 ,48778   ,500,500,500
BEGIN DESCRIPTION:
BIG BROWN CREEK 66.0
END DESCRIPTION:
XS GIS Cut Line= 3
       3615099.6      10633110.2      3615749.61     10632560.19
      3617299.63     10631560.17
#Sta/Elev= 30
  4140.5  341.42  4172.6  341.17  4197.1  338.08  4260.8  336.77    4313  331.91
  4377.9  327.22  4637.7  313.71  4651.4  313.62  4658.5   315.6  4679.4  313.92
  4750.8   315.3  4828.8  314.27  4878.3  311.41  4978.3  311.74  5002.5  310.18
  5005.3  309.68  5008.5  310.18  5410.7   312.4    5816  310.97  6027.3  314.43
    6206  310.97  6351.2  311.05  6475.2   318.4  6517.5  317.77    6569  323.41
  6662.7  326.55  6714.1  331.33  6735.3  331.17  6750.4  333.67  6836.6  337.87
#Mann= 6 ,-1 , 0
  4140.5     .12       0  4172.6      .1       0    4313     .16       0
  4377.9     .12       0  5002.5     .07       0  5008.5     .12       0
Bank Sta=4828.8,6027.3
XS Rating Curve= 0 ,0
Exp/Cntr=0.3,0.1

Type RM Length L Ch R = 1 ,48278   ,602,602,602
BEGIN DESCRIPTION:
BIG BROWN CREEK 65.0
END DESCRIPTION:
XS GIS Cut Line= 3
      3615499.62     10633560.18      3616049.61     10632910.19
      3617599.64     10631460.16
#Sta/Elev= 30
  4175.8  343.11  4203.8  333.89    4275  329.06  4488.9  319.69    4595  315.81
  4693.8  316.75  4705.3  316.62    4829  310.98  4848.3  306.58    4854  303.61
  4856.7  303.11    4860  303.61  4904.3  303.61  5057.3  303.61  5134.6  303.61
    5367  303.61  5373.8   307.3  5381.2  303.61  5600.5  303.61  5614.7   309.6
  5736.2  309.58  6039.2   312.4  6176.3  309.31  6307.8  316.47    6365  320.59
  6774.8  343.59  6852.5  344.81  6951.7  352.49  6986.8  351.92  7149.8  360.25
#Mann= 13 ,-1 , 0
  4175.8     .05       0    4275     .16       0  4488.9     .12       0
  4705.3     .16       0  4848.3     .12       0    4854     .07       0
    4860     .12       0  4904.3     .16       0  5057.3     .07       0
  5134.6     .05       0  5736.2     .12       0  6176.3     .16       0
    6365     .12       0
Bank Sta=4693.8,6307.8
XS Rating Curve= 0 ,0
Exp/Cntr=0.3,0.1

Type RM Length L Ch R = 1 ,47676   ,600,600,600
BEGIN DESCRIPTION:
BIG BROWN CREEK 64.0
END DESCRIPTION:
XS GIS Cut Line= 3
      3616049.63     10633710.16      3616649.61     10632910.19
      3617349.62     10632110.17
#Sta/Elev= 30
    4025  336.61  4096.8  328.73  4117.7   327.8  4146.8  324.03  4167.7  323.15
  4188.8  320.01  4238.5  316.66  4276.7  313.77  4307.9  311.11    4325  309.89
  4329.3  303.61    4332  303.11  4335.3  303.61  4972.5  303.61  5022.4  303.61
  5148.3  303.61  5265.6  303.61  5287.4  309.23  5324.7  309.52  5492.4  311.61
  5612.9   311.4  5627.2   309.6  5655.7  309.28  5684.1     312  5776.2  315.98
  5839.8  317.05  5903.4  321.93  5988.8  326.65  5995.4  327.93    6088  335.16
#Mann= 10 ,-1 , 0
    4025     .12       0  4188.8     .16       0  4276.7     .12       0
  4307.9     .05       0  4329.3     .07       0  4335.3     .05       0
  4972.5     .16       0  5022.4     .05       0  5148.3     .07       0
  5324.7     .12       0
Bank Sta=4238.5,5776.2
XS Rating Curve= 0 ,0
Exp/Cntr=0.3,0.1

Type RM Length L Ch R = 1 ,47076   ,530,530,530
BEGIN DESCRIPTION:
BIG BROWN CREEK 63.0
END DESCRIPTION:
XS GIS Cut Line= 3
      3616599.59     10634060.22      3617099.61     10633260.19
       3617449.6     10631960.22
#Sta/Elev= 30
  4056.9  336.89  4122.4  333.04  4137.7  330.72  4151.3  331.59  4201.4  327.62
  4226.7   327.3    4238  325.16  4368.9  316.42  4375.3  314.37  4386.2   313.8
  4390.1  313.07  4405.4  314.57  4477.5   310.2  4490.3  303.61    4493  303.11
  4496.3  303.61  4590.4  303.61  5265.7  303.61  5539.8  303.61  5590.6  303.61
  5596.2  305.45  5601.4  303.61  5636.1  303.61  5640.3  305.41  5652.8  310.07
  5766.7  309.77  5870.6  314.32  6014.9  324.47  6108.4  332.61  6346.6  346.68
#Mann= 10 ,-1 , 0
  4056.9     .16       0  4226.7     .12       0  4386.2     .16       0
  4477.5      .1       0  4490.3    .033       0  4496.3      .1       0
  4590.4     .05       0  5265.7      .1       0  5539.8     .07       0
  5640.3     .12       0
Bank Sta=4405.4,5652.8
XS Rating Curve= 0 ,0
Exp/Cntr=0.3,0.1

Type RM Length L Ch R = 1 ,46546   ,552,552,552
BEGIN DESCRIPTION:
BIG BROWN CREEK 62.0
END DESCRIPTION:
XS GIS Cut Line= 3
      3616699.57     10634410.22      3617499.61     10633610.19
       3618149.6      10632010.2
#Sta/Elev= 30
  3844.6  347.05  3960.5  339.98  4099.2  330.79  4226.5  325.89  4297.2  317.98
  4325.5  320.14  4565.9  310.55  4636.6  309.82  4664.9  308.03    4676  303.61
  4678.8  303.11    4682  303.61  4737.3  303.61  5890.6  303.61  5936.7  303.61
  5943.9  308.22  5949.3  304.13  5958.2  309.85  5973.4  310.35  6056.4  310.59
  6134.1  313.81  6318.8  328.84  6342.9  334.21  6420.5  340.55  6503.5  345.73
  6605.2  348.92  6616.7  346.93  6634.7  349.89  6640.1  347.29    6703  352.31
#Mann= 6 ,-1 , 0
  3844.6     .05       0  3960.5     .16       0    4676    .033       0
    4682     .16       0  4737.3     .05       0  5890.6     .12       0
Bank Sta=4636.6,5973.4
XS Rating Curve= 0 ,0
Exp/Cntr=0.3,0.1

Type RM Length L Ch R = 1 ,45994   ,569,569,569
BEGIN DESCRIPTION:
BIG BROWN CREEK 61.0
END DESCRIPTION:
XS GIS Cut Line= 3
      3617149.63     10634710.17      3617949.61     10633910.19
       3619499.6      10632310.2
#Sta/Elev= 30
  3863.4  353.46  3866.9  353.46  3919.9  349.23  3999.2  346.03  4027.8  344.28
  4344.2  324.92  4570.5  316.16  4612.9  313.23  4697.8  310.69  4796.8  309.48
  4807.9  303.61  4810.6  303.11  4813.9  303.61  4815.6  303.61  4872.9  303.61
  6161.7  303.61  6168.6  309.44  6265.2  310.86  6281.8  310.66    6289  312.93
  6345.4  316.51  6458.6   324.1  6621.4  339.12  6720.4  340.83  6727.4  338.61
  6748.7  341.21  6819.2  343.13  6974.8  355.48    7081  366.59  7222.4  374.67
#Mann= 9 ,-1 , 0
  3863.4     .12       0  3866.9     .16       0  3999.2     .05       0
  4027.8     .16       0  4807.9    .033       0  4813.9     .16       0
  4815.6      .1       0  4872.9     .05       0  6265.2     .12       0
Bank Sta=4570.5,6345.4
XS Rating Curve= 0 ,0
Exp/Cntr=0.3,0.1

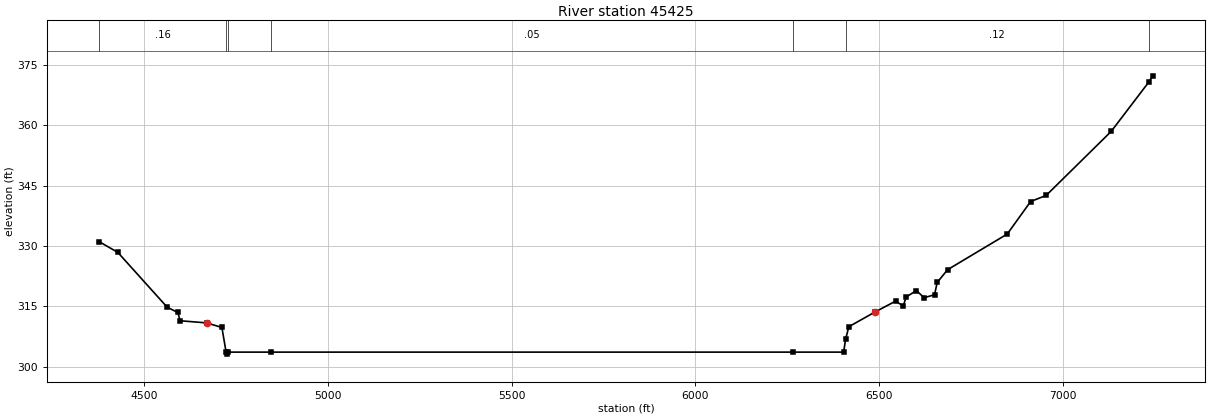
Type RM Length L Ch R = 1 ,45425   ,517,517,517
BEGIN DESCRIPTION:
BIG BROWN CREEK 60.0
END DESCRIPTION:
XS GIS Cut Line= 3
      3617949.62     10634810.17      3618349.61     10634310.19
      3619899.64     10632710.16
#Sta/Elev= 30
  4377.1  331.06  4427.5  328.41    4562  314.76  4590.8  313.48  4597.2  311.41
  4669.2  310.88  4710.8  309.74  4722.2  303.61    4725  303.11  4728.2  303.61
  4844.1  303.61  6264.3  303.61  6403.5  303.61  6408.9  306.84  6417.7  309.93
  6488.4  313.56    6545  316.29  6566.1  315.06  6573.3   317.3  6601.6  318.91
  6622.7  317.15    6651  317.87  6658.2  320.93  6686.5  324.11    6849  332.98
  6912.6  341.06    6955  342.59    7132  358.51  7234.2  370.76  7245.1  372.33
#Mann= 7 ,-1 , 0
  4377.1     .16       0  4722.2    .033       0  4728.2     .16       0
  4844.1     .05       0  6264.3     .07       0  6408.9     .12       0
  7234.2     .16       0
Bank Sta=4669.2,6488.4
XS Rating Curve= 0 ,0
Exp/Cntr=0.3,0.1