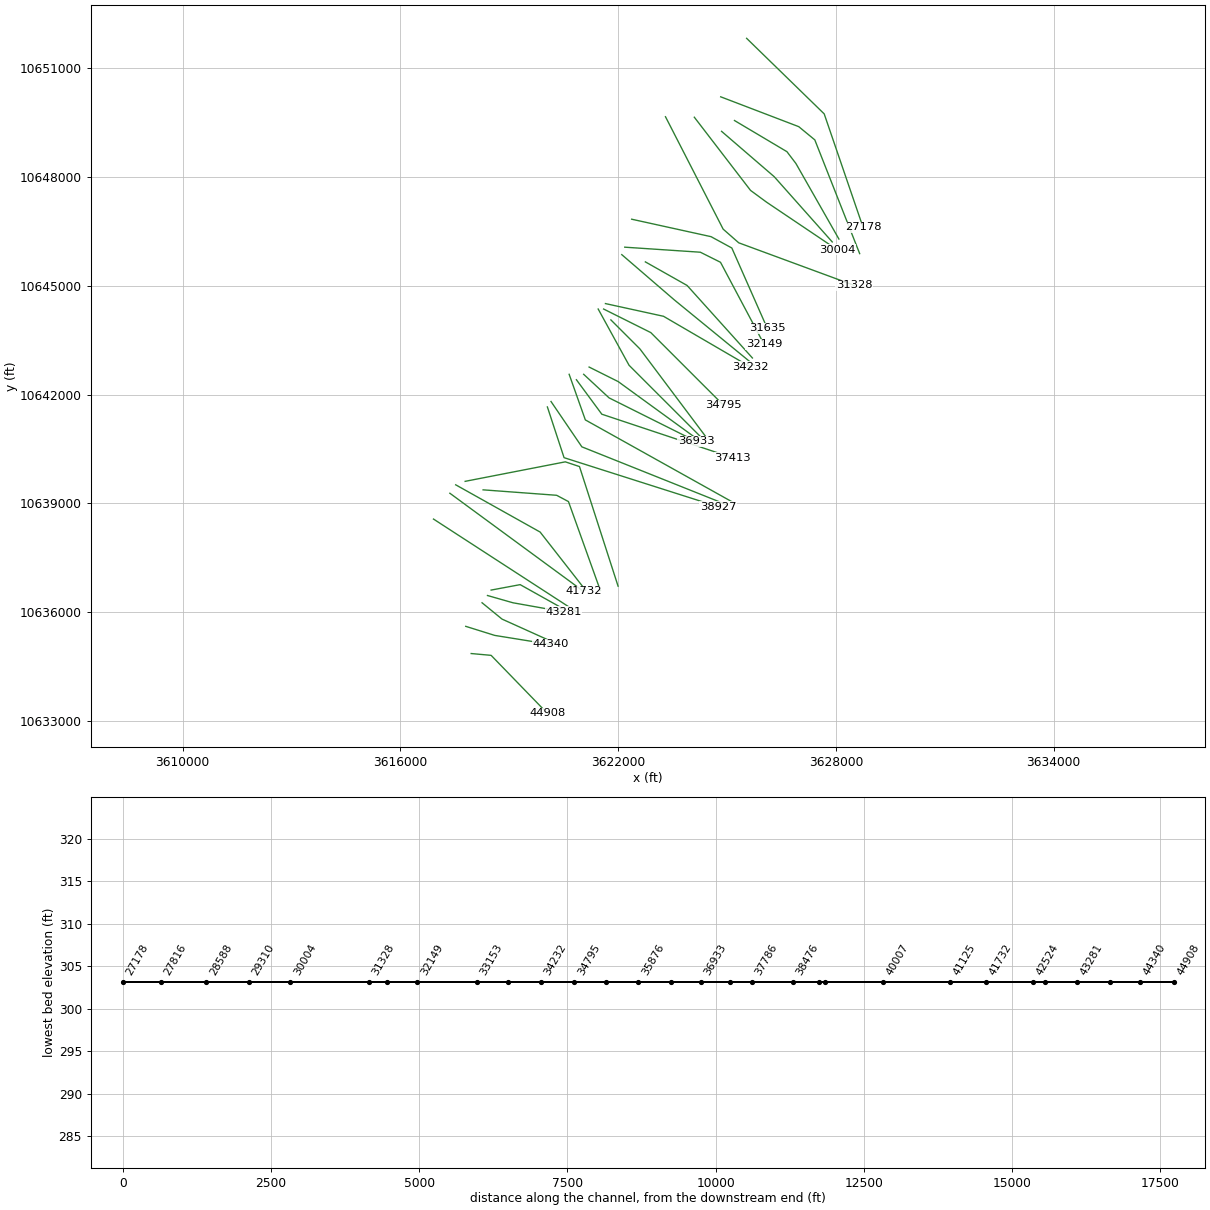
HEC-RAS study BIG BROWN CREEK.prj: BIG BROWN CREEK Base Level Engineering

--- BIG BROWN CREEK.g01 (geometry) --- (continued)

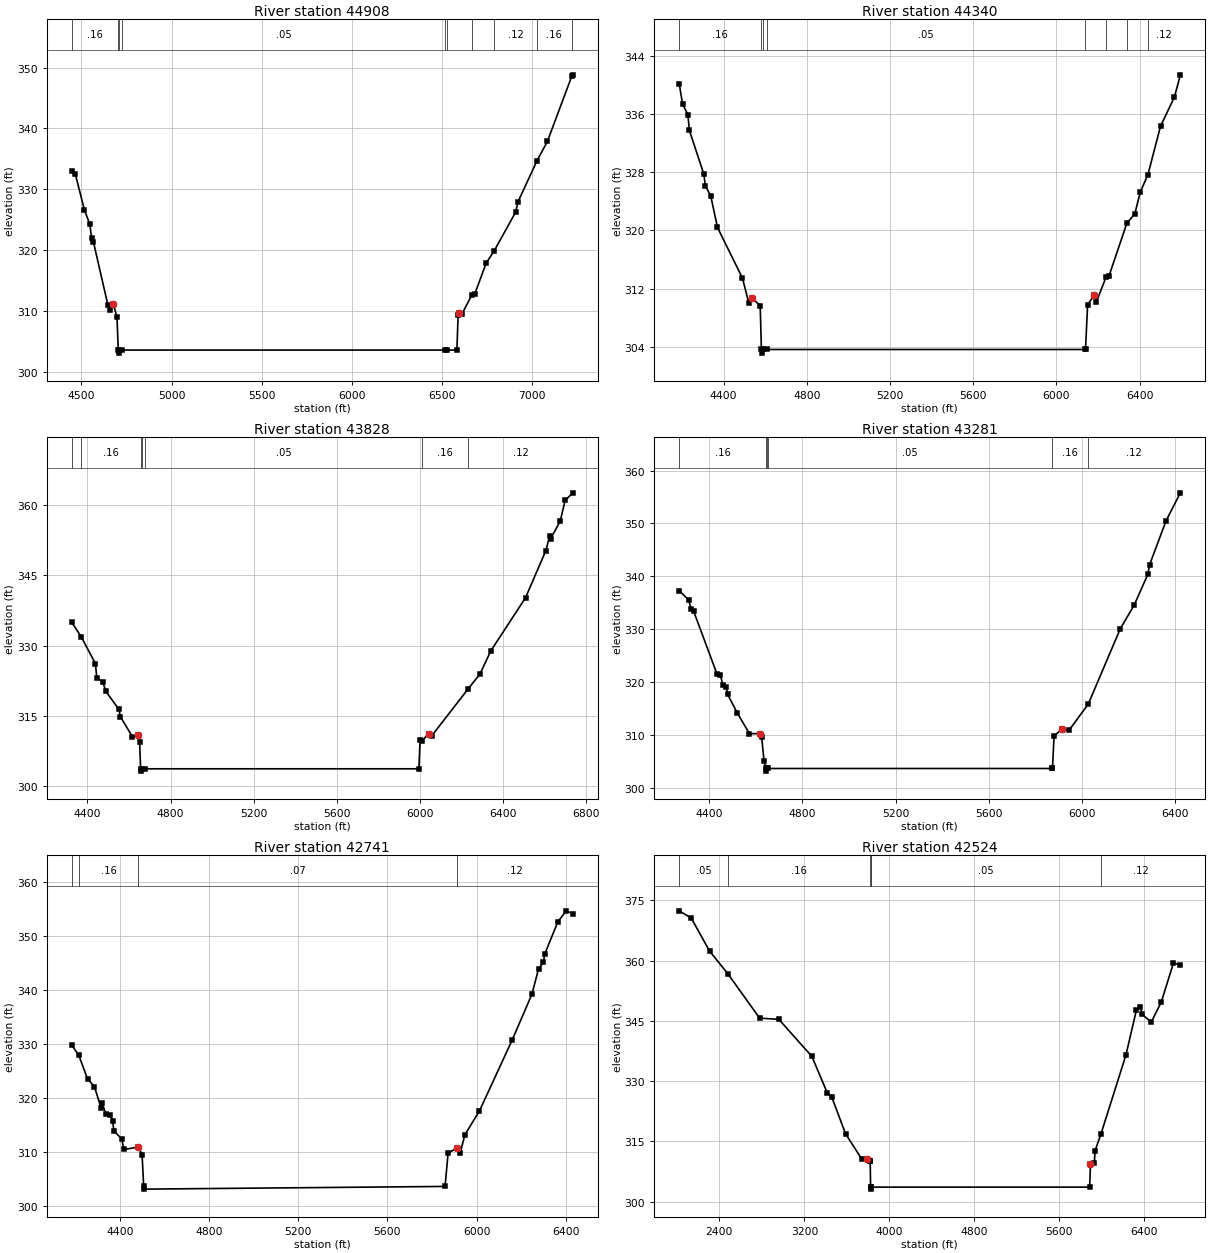
Type RM Length L Ch R = 1 ,44908   ,568,568,568
BEGIN DESCRIPTION:
BIG BROWN CREEK 59.0
END DESCRIPTION:
XS GIS Cut Line= 3
      3617949.57     10634860.19      3618499.61     10634810.19
      3620049.63     10633210.17
#Sta/Elev= 30
  4446.3  333.05  4466.4   332.5  4516.6  326.62  4546.7  324.28  4556.8  321.95
  4566.8  321.35  4647.2  310.98  4657.2  310.27  4677.3   311.1  4697.4  309.03
  4704.4  303.61  4707.2  303.11  4710.4  303.61  4724.2  303.61    6517  303.61
  6526.7  303.61  6582.8  303.61  6589.7  309.36  6596.9  309.63  6611.1  309.53
  6665.2  312.65  6681.8  312.81  6745.4   317.9  6789.8  319.91    6908  326.22
  6922.1  327.98  7027.1   334.7  7084.9  337.88  7219.8  348.56  7226.3  348.81
#Mann= 10 ,-1 , 0
  4446.3     .16       0  4704.4    .033       0  4710.4     .16       0
  4724.2     .05       0    6517     .07       0  6526.7     .12       0
  6665.2     .16       0  6789.8     .12       0  7027.1     .16       0
  7219.8     .12       0
Bank Sta=4677.3,6596.9
XS Rating Curve= 0 ,0
Exp/Cntr=0.3,0.1

Type RM Length L Ch R = 1 ,44340   ,512,512,512
BEGIN DESCRIPTION:
BIG BROWN CREEK 58.0
END DESCRIPTION:
XS GIS Cut Line= 3
      3617799.59     10635610.19      3618599.61     10635360.19
      3620149.61     10635110.19
#Sta/Elev= 30
    4187  340.19  4203.3  337.37  4228.9  335.92  4235.7  333.79  4305.9  327.69
  4312.7  326.12  4338.4  324.77  4370.9  320.41  4490.8  313.44  4522.3  309.94
  4538.5  310.65  4576.2  309.63  4582.1  303.61  4584.9  303.11  4588.1  303.61
  4607.5  303.61  6136.5  303.61  6139.4  303.61  6149.5  309.73  6179.9  311.06
    6191   310.1  6237.3  313.52  6252.8  313.77  6338.2  320.99  6376.4  322.28
  6402.7  325.28    6439  327.63    6500  334.34  6566.8  338.34  6595.2   341.4
#Mann= 8 ,-1 , 0
    4187     .16       0  4582.1    .033       0  4588.1     .16       0
  4607.5     .05       0  6136.5     .16       0  6237.3     .12       0
  6338.2     .16       0    6439     .12       0
Bank Sta=4538.5,6179.9
XS Rating Curve= 0 ,0
Exp/Cntr=0.3,0.1

Type RM Length L Ch R = 1 ,43828   ,547,547,547
BEGIN DESCRIPTION:
BIG BROWN CREEK 57.0
END DESCRIPTION:
XS GIS Cut Line= 3
      3618249.61     10636260.18      3618799.61     10635810.19
      3620349.64     10635110.17
#Sta/Elev= 30
  4324.7  334.97    4370  331.91  4438.8  326.12  4445.3  323.03    4474  322.27
  4488.4  320.21  4552.2  316.31  4558.7  314.78  4616.1  310.52  4644.8  310.79
  4651.3  309.44  4656.2  303.61  4658.9  303.11  4662.2  303.61  4679.2  303.61
  5995.2  303.61  6000.9   309.7    6010  309.59  6041.5   311.1  6055.8   310.6
    6231  320.66  6289.1  323.91  6341.1  328.85  6508.2  340.23  6606.2  350.34
  6623.8  353.39  6629.3  352.87  6675.5  356.68  6698.6  361.05  6736.1  362.69
#Mann= 7 ,-1 , 0
  4324.7     .12       0    4370     .16       0  4656.2    .033       0
  4662.2     .16       0  4679.2     .05       0    6010     .16       0
    6231     .12       0
Bank Sta=4644.8,6041.5
XS Rating Curve= 0 ,0
Exp/Cntr=0.3,0.1

Type RM Length L Ch R = 1 ,43281   ,540,540,540
BEGIN DESCRIPTION:
BIG BROWN CREEK 56.0
END DESCRIPTION:
XS GIS Cut Line= 3
      3618399.58      10636460.2      3619099.61     10636260.19
      3620499.62     10636010.19
#Sta/Elev= 30
  4271.6  337.28  4313.2  335.48  4322.3  333.72    4334  333.34  4434.1  321.46
  4448.4  321.27  4458.8  319.45  4473.1  319.12  4479.6  317.62  4521.2  314.09
  4573.2  310.19  4618.7  310.23  4625.2  309.62  4635.6  305.07    4643  303.61
  4645.8  303.11    4649  303.61  4653.8  303.61    5871  303.61  5873.2  303.61
  5879.9  309.78  5913.9  311.05  5944.4  310.85  6026.6   315.8  6164.3  330.09
  6223.2   334.5  6282.1  340.34  6289.7  342.17  6360.8  350.54  6421.8   355.8
#Mann= 6 ,-1 , 0
  4271.6     .16       0    4643    .033       0    4649     .16       0
  4653.8     .05       0    5871     .16       0  6026.6     .12       0
Bank Sta=4618.7,5913.9
XS Rating Curve= 0 ,0
Exp/Cntr=0.3,0.1

Type RM Length L Ch R = 1 ,42741   ,217,217,217
BEGIN DESCRIPTION:
BIG BROWN CREEK 55.0
END DESCRIPTION:
XS GIS Cut Line= 3
       3618499.6     10636610.19      3619299.61     10636760.19
      3620549.61     10636060.19
#Sta/Elev= 30
  4184.8  329.76  4215.5     328    4256   323.5  4286.5   322.1  4316.2  318.17
  4321.3  319.06  4337.4  317.08  4357.8  316.81  4367.9  315.79  4373.9  313.88
  4408.6  312.43  4418.8  310.45  4484.1   310.9  4500.2  309.48  4507.4  303.61
  4510.1  303.11  5858.3  303.61  5872.1  309.82  5909.7  310.64  5925.7  309.74
  5947.4  313.19  6012.5  317.59  6158.6  330.67    6248  339.23  6277.3  343.89
    6299  345.13  6305.3  346.65  6364.1  352.63  6401.7  354.65  6431.4  354.13
#Mann= 4 ,-1 , 0
  4184.8     .12       0  4215.5     .16       0  4484.1     .07       0
  5909.7     .12       0
Bank Sta=4484.1,5909.7
XS Rating Curve= 0 ,0
Exp/Cntr=0.3,0.1

Type RM Length L Ch R = 1 ,42524   ,792,792,792
BEGIN DESCRIPTION:
BIG BROWN CREEK 54.0
END DESCRIPTION:
XS GIS Cut Line= 2
      3616911.08     10638568.59      3620869.45     10635999.12
#Sta/Elev= 30
  2021.2  372.39  2135.2  370.57  2307.2  362.37  2479.7  356.71  2778.5  345.68
  2959.7  345.37  3270.8  336.14  3414.3  327.16    3458  326.03  3587.9  316.88
  3738.9  310.65  3790.2  310.72  3817.8  310.11  3819.7  310.11  3823.5  303.61
  3826.2  303.11  3829.5  303.61  5886.3  303.61  5894.1  309.44  5929.9  309.54
  5937.7  312.69    5993  316.85  6227.7  336.48  6327.2  347.76  6363.5  348.53
  6378.6  346.67  6466.3  344.67  6559.9  349.64  6674.6  359.31  6740.4  358.96
#Mann= 6 ,-1 , 0
  2021.2     .05       0  2479.7     .16       0  3817.8     .05       0
  3823.5    .033       0  3829.5     .05       0    5993     .12       0
Bank Sta=3790.2,5894.1
XS Rating Curve= 0 ,0
Exp/Cntr=0.3,0.1

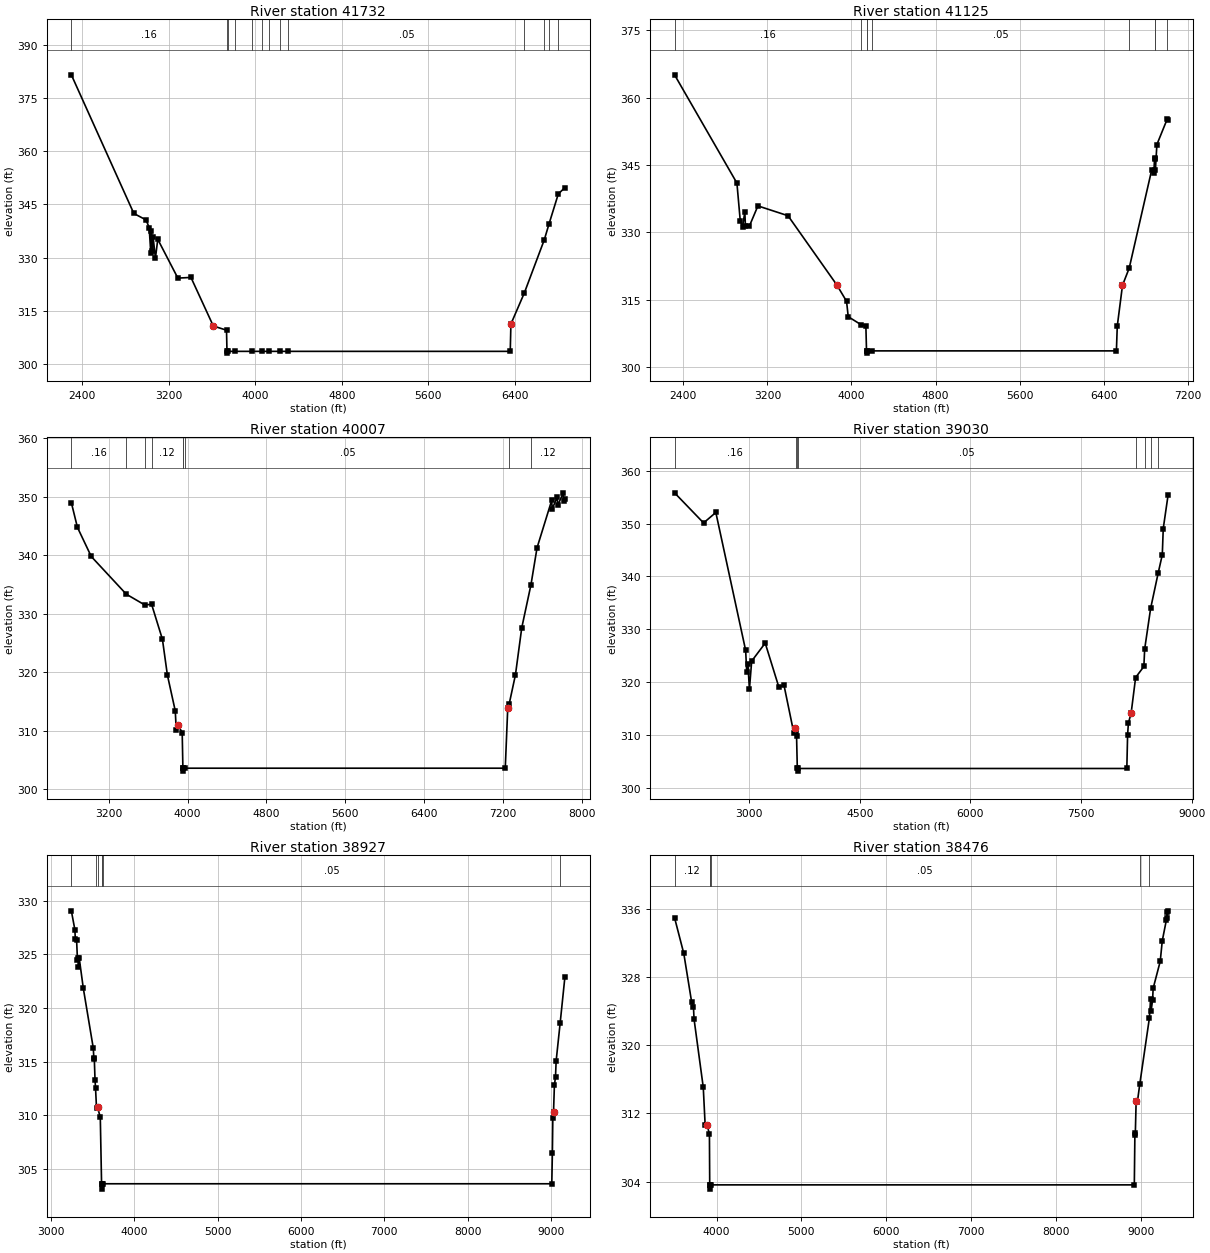
Type RM Length L Ch R = 1 ,41732   ,607,607,607
BEGIN DESCRIPTION:
BIG BROWN CREEK 53.0
END DESCRIPTION:
XS GIS Cut Line= 2
       3617362.5     10639280.37      3621043.08     10636576.36
#Sta/Elev= 30
  2297.5  381.53  2875.7  342.47  2988.8  340.64  3017.7  338.49  3032.4  331.41
  3038.6  337.66    3047  331.97  3053.2  335.97  3075.7   329.9  3097.2  335.18
  3283.1  324.25  3404.3  324.44  3611.1  310.76  3733.3  309.57  3737.7  303.61
  3740.5  303.11  3743.7  303.61  3815.7  303.61    3973  303.61  4063.8  303.61
  4130.3  303.61  4226.1  303.61  4306.4  303.61  6358.8  303.61    6365  311.31
  6489.2  320.07    6674  335.06  6718.1  339.56  6803.7  347.98  6864.6  349.75
#Mann= 13 ,-1 , 0
  2297.5     .16       0  3737.7    .033       0  3743.7     .16       0
  3815.7     .07       0    3973     .05       0  4063.8     .07       0
  4130.3     .05       0  4226.1     .07       0  4306.4     .05       0
  6489.2     .16       0    6674     .12       0  6718.1     .16       0
  6803.7     .12       0
Bank Sta=3611.1,6365
XS Rating Curve= 0 ,0
Exp/Cntr=0.3,0.1

Type RM Length L Ch R = 1 ,41125   ,1118,1118,1118
BEGIN DESCRIPTION:
BIG BROWN CREEK 52.0
END DESCRIPTION:
XS GIS Cut Line= 3
      3617523.09     10639513.08      3619849.61     10638210.19
      3621099.61     10636610.18
#Sta/Elev= 30
  2316.5  365.09    2910  340.98  2941.9  332.55  2963.6  331.17  2985.3  334.59
    2991   331.4  3028.7   331.4  3109.7   335.9  3396.2  333.71  3859.8  318.33
  3953.3  314.66  3969.3  311.22  4089.6  309.47  4137.1  309.26  4143.3  303.61
  4146.1  303.11  4149.3  303.61  4193.3  303.61  6521.4  303.61  6529.5  309.11
  6579.3  318.22  6643.3  322.05  6856.9  343.88  6877.7  343.29  6884.8  346.67
  6887.6  346.29  6892.2  343.87  6906.7  349.57  7005.6  355.28  7013.4  354.96
#Mann= 9 ,-1 , 0
  2316.5     .16       0  4089.6     .07       0  4143.3    .033       0
  4149.3     .07       0  4193.3     .05       0  6643.3      .1       0
  6884.8     .16       0  6887.6      .1       0  7005.6     .12       0
Bank Sta=3859.8,6579.3
XS Rating Curve= 0 ,0
Exp/Cntr=0.3,0.1

Type RM Length L Ch R = 1 ,40007   ,977,977,977
BEGIN DESCRIPTION:
BIG BROWN CREEK 50.0
END DESCRIPTION:
XS GIS Cut Line= 4
      3618278.24      10639374.2      3620305.21     10639223.95
      3620630.73     10639050.34      3621509.62     10636598.13
#Sta/Elev= 30
  2820.9  348.97  2882.4  344.75  3022.8  339.77  3378.2  333.33  3565.8  331.49
    3635   331.6  3744.8  325.62  3794.9  319.54  3875.1  313.39    3885  310.11
  3905.2  310.92  3945.3  309.69  3952.4  303.61  3955.1  303.11  3958.4  303.61
  3978.8  303.61  7222.3  303.61  7247.7  313.96  7262.9  314.64  7325.8  319.57
  7389.6  327.59  7483.1  334.95  7544.7  341.25  7693.1  349.34  7698.4  347.86
  7749.3  349.95  7754.6   348.5  7810.8  350.64  7816.1  349.22  7827.3  349.63
#Mann= 9 ,-1 , 0
  2820.9     .16       0  3378.2     .12       0  3565.8     .16       0
    3635     .12       0  3952.4    .033       0  3958.4     .12       0
  3978.8     .05       0  7262.9     .16       0  7483.1     .12       0
Bank Sta=3905.2,7247.7
XS Rating Curve= 0 ,0
Exp/Cntr=0.3,0.1

Type RM Length L Ch R = 1 ,39030   ,103,103,103
BEGIN DESCRIPTION:
BIG BROWN CREEK 49.0
END DESCRIPTION:
XS GIS Cut Line= 4
       3617783.5     10639608.58      3620543.92     10640146.26
      3620934.55     10640016.05      3621997.91     10636717.46
#Sta/Elev= 30
  1990.1  355.82  2383.5  350.12  2549.6   352.1    2954  325.96  2967.7  321.94
  2984.5   323.4  3004.9  318.61  3035.5  323.95  3218.9  327.36  3402.3  319.09
  3473.6  319.37    3606  310.39  3626.4  311.24  3632.6  310.56  3643.9  309.72
    3654  303.61  3656.7  303.11    3660  303.61  8120.3  303.61  8130.7  309.94
  8141.2  312.17  8179.1  314.13  8239.5  320.84  8351.3  322.93  8362.2  326.23
    8443  333.94  8544.7  340.59  8601.1  344.09    8614  349.06  8679.9  355.43
#Mann= 8 ,-1 , 0
  1990.1     .16       0  3632.6     .05       0    3654    .033       0
    3660     .05       0  8239.5      .1       0  8362.2     .08       0
    8443     .05       0  8544.7     .08       0
Bank Sta=3626.4,8179.1
XS Rating Curve= 0 ,0
Exp/Cntr=0.3,0.1

Type RM Length L Ch R = 1 ,38927   ,451,451,451
BEGIN DESCRIPTION:
BIG BROWN CREEK 48.0
END DESCRIPTION:
XS GIS Cut Line= 3
      3620049.61     10641660.18      3620509.63     10640261.06
      3624749.63     10638910.18
#Sta/Elev= 30
  3243.7  329.07  3285.8  327.32  3291.4  326.45  3306.9  326.31  3317.4  324.45
  3323.2  324.64  3328.5  323.84  3338.4  324.65  3386.8  321.87  3506.9  316.27
    3514   315.3  3519.2  315.28  3527.9  313.29  3534.3   312.5  3545.8  310.65
  3557.9  310.74  3591.1  309.82  3606.4  303.61  3609.1  303.11  3612.4  303.61
  3623.7  303.61  9009.1  303.61  9016.3  306.52  9021.5  309.75    9030  310.33
  9040.5  312.79  9053.7   313.6  9061.5  315.08  9109.1  318.57  9166.5   322.9
#Mann= 7 ,-1 , 0
  3243.7     .12       0  3534.3     .05       0  3557.9     .12       0
  3606.4    .033       0  3612.4     .12       0  3623.7     .05       0
  9109.1     .16       0
Bank Sta=3557.9,9030
XS Rating Curve= 0 ,0
Exp/Cntr=0.3,0.1

Type RM Length L Ch R = 1 ,38476   ,690,690,690
BEGIN DESCRIPTION:
BIG BROWN CREEK 47.0
END DESCRIPTION:
XS GIS Cut Line= 3
      3620149.59     10641810.22      3620999.61     10640560.19
      3624999.62     10638960.19
#Sta/Elev= 30
    3504     335  3612.9   330.8  3706.1  325.05    3727  324.51  3733.8   323.1
  3842.6  315.07  3864.7  310.64  3885.7  310.67  3915.2  309.61  3918.6  303.61
  3921.4  303.11  3924.6  303.61  3929.4  303.61  8925.3  303.61    8932   309.5
  8937.4  309.68  8946.8  313.42  8961.6  313.36  8989.1  315.41  9102.5  323.17
  9117.8  325.45  9123.2  324.02  9140.7  325.35  9147.4   326.7  9230.9  329.88
  9255.1   332.3  9302.3  334.68    9309  335.67  9314.4     335  9323.8  335.81
#Mann= 6 ,-1 , 0
    3504     .12       0  3918.6    .033       0  3924.6     .12       0
  3929.4     .05       0  8989.1     .16       0  9102.5     .12       0
Bank Sta=3885.7,8946.8
XS Rating Curve= 0 ,0
Exp/Cntr=0.3,0.1

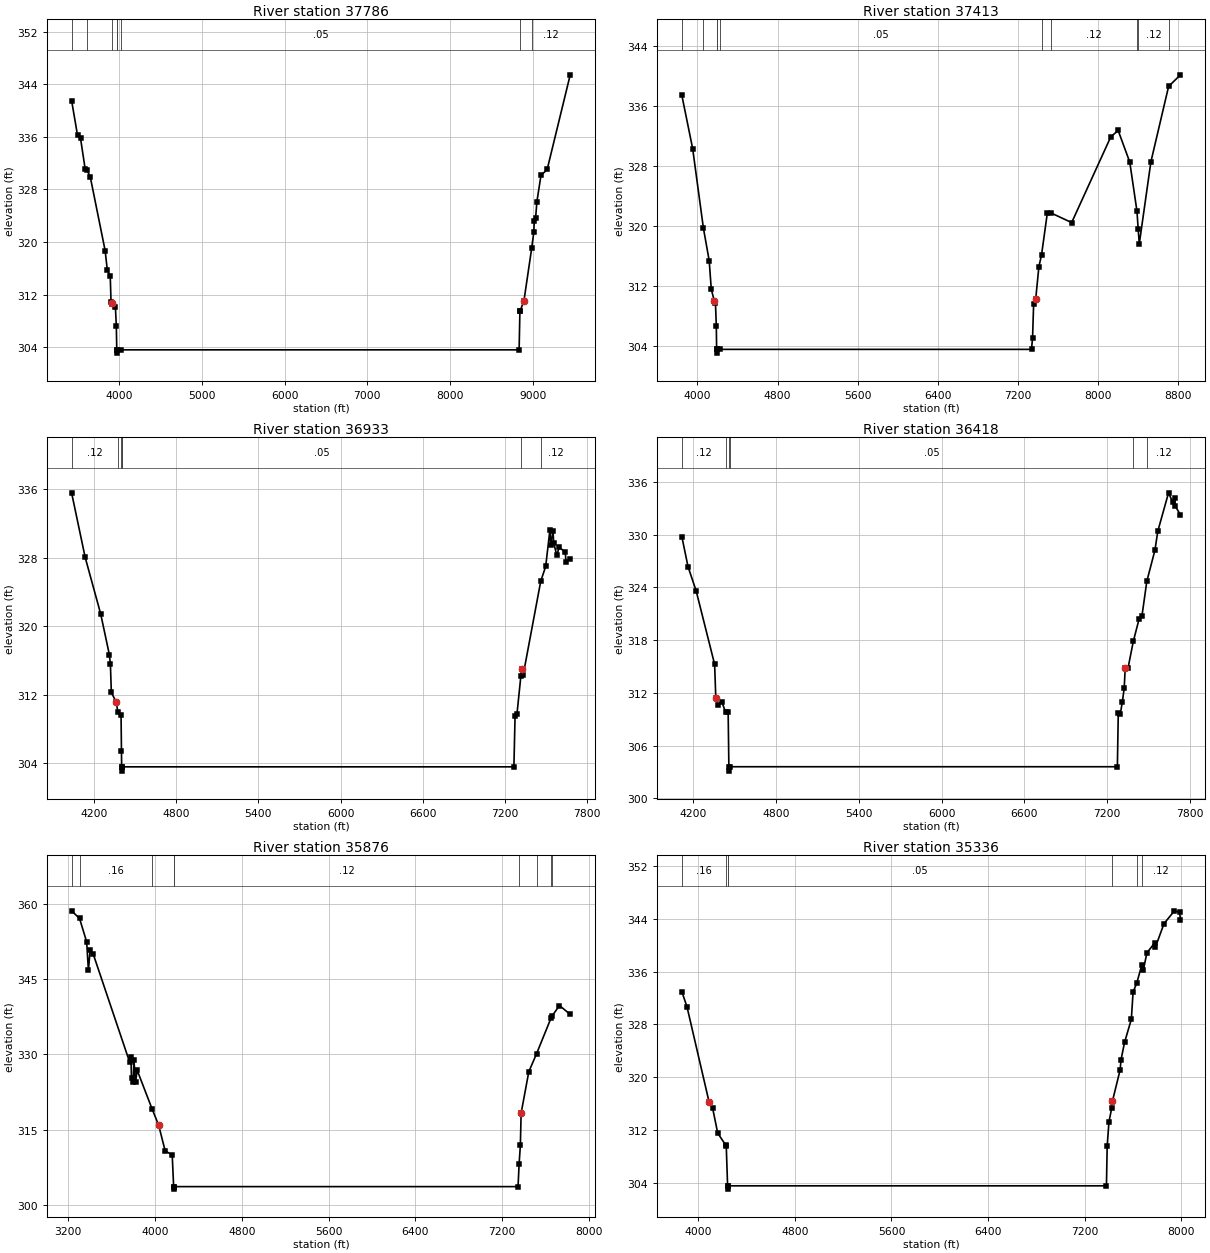
Type RM Length L Ch R = 1 ,37786   ,373,373,373
BEGIN DESCRIPTION:
BIG BROWN CREEK 46.0
END DESCRIPTION:
XS GIS Cut Line= 3
      3620649.62     10642560.16      3621095.57     10641302.73
       3625199.6      10639010.2
#Sta/Elev= 30
  3420.6  341.53  3492.5  336.23  3528.6   335.8  3585.1  331.09  3605.3     331
  3646.8   329.9  3826.8  318.69  3852.3  315.78  3888.5  314.79    3898  310.82
  3909.2  310.63  3914.1  310.71  3951.1  310.09  3961.7  307.27  3967.5  303.61
  3970.3  303.11  3973.5  303.61  4014.8  303.61  8837.2  303.61  8846.9  309.54
  8850.3  309.55    8896   311.1  8988.9  319.03  9014.8  321.49  9020.5  323.24
  9036.5  323.61  9052.5  326.16  9101.6  330.13    9177  331.06  9455.7  345.44
#Mann= 8 ,-1 , 0
  3420.6     .16       0  3605.3     .12       0  3909.2     .16       0
  3967.5    .033       0  3973.5     .16       0  4014.8     .05       0
  8850.3     .16       0  8988.9     .12       0
Bank Sta=3914.1,8896
XS Rating Curve= 0 ,0
Exp/Cntr=0.3,0.1

Type RM Length L Ch R = 1 ,37413   ,480,480,480
BEGIN DESCRIPTION:
BIG BROWN CREEK 45.0
END DESCRIPTION:
XS GIS Cut Line= 3
      3620849.59     10642410.22      3621549.61     10641460.19
      3625149.59     10640260.19
#Sta/Elev= 30
  3845.7   337.4  3953.3  330.33  4060.5  319.75  4118.3  315.42  4139.2   311.6
  4168.5   310.1  4181.1  309.72  4189.3  306.74  4192.5  303.61  4195.3  303.11
  4198.5  303.61  4222.4  303.61  7334.2  303.61  7344.8  305.16  7355.3  309.66
  7376.4  310.37    7408  314.63  7434.1  316.17  7492.4  321.79  7530.3  321.75
  7734.8  320.48  8124.8  331.88  8198.6  332.74  8314.6  328.52  8386.5  321.98
  8398.1  319.66  8409.4  317.65  8525.4  328.57    8702   338.6  8820.5  340.14
#Mann= 10 ,-1 , 0
  3845.7     .12       0  4060.5     .16       0  4192.5    .033       0
  4198.5     .16       0  4222.4     .05       0  7434.1     .16       0
  7530.3     .12       0  8386.5     .16       0  8398.1     .12       0
    8702     .05       0
Bank Sta=4168.5,7376.4
XS Rating Curve= 0 ,0
Exp/Cntr=0.3,0.1

Type RM Length L Ch R = 1 ,36933   ,515,515,515
BEGIN DESCRIPTION:
BIG BROWN CREEK 44.0
END DESCRIPTION:
XS GIS Cut Line= 3
      3621049.59     10642560.21      3621749.61     10641910.19
      3624149.65     10640710.17
#Sta/Elev= 30
  4037.7  335.55  4136.7  328.03    4250  321.43  4313.5  316.67  4320.9  315.56
  4327.7  312.28  4363.4  311.16  4375.5  309.97  4398.6  309.61  4401.6  305.42
  4402.9  303.61  4405.7  303.11  4408.9  303.61  7265.4  303.61  7273.8  309.51
  7287.7  309.76  7316.2   314.2  7326.9  314.98  7332.5  314.27  7461.2  325.25
  7497.4  326.97  7528.1  331.24  7533.7  329.45  7550.5  331.12  7556.1  329.66
  7578.4  328.29  7595.2  329.18  7639.9  328.68  7645.5  327.53  7676.3  327.83
#Mann= 7 ,-1 , 0
  4037.7     .12       0  4375.5     .16       0  4401.6     .05       0
  4402.9    .033       0  4408.9     .05       0  7316.2     .16       0
  7461.2     .12       0
Bank Sta=4363.4,7326.9
XS Rating Curve= 0 ,0
Exp/Cntr=0.3,0.1

Type RM Length L Ch R = 1 ,36418   ,542,542,542
BEGIN DESCRIPTION:
BIG BROWN CREEK 43.0
END DESCRIPTION:
XS GIS Cut Line= 3
      3621199.57     10642760.21      3621999.61     10642360.19
      3624199.64     10640760.17
#Sta/Elev= 30
  4117.4  329.77  4162.2  326.36  4220.9  323.62    4355  315.25  4363.4   311.4
  4377.4   310.6  4408.1  310.95  4435.1  309.78  4452.9  309.89  4458.2  303.61
    4461  303.11  4464.2  303.61  7274.7  303.61  7281.2  309.72  7295.9  309.59
  7310.6  310.99  7324.1  312.51  7331.5  314.85  7352.3  314.86  7390.1  317.87
  7431.9   320.4  7452.8  320.75  7488.2  324.71  7546.7  328.23  7567.9  330.41
  7645.6  334.77  7674.6  333.74  7689.3  334.18  7695.5  333.23  7732.2  332.26
#Mann= 6 ,-1 , 0
  4117.4     .12       0  4435.1     .05       0  4458.2    .033       0
  4464.2     .05       0  7390.1     .16       0  7488.2     .12       0
Bank Sta=4363.4,7331.5
XS Rating Curve= 0 ,0
Exp/Cntr=0.3,0.1

Type RM Length L Ch R = 1 ,35876   ,540,540,540
BEGIN DESCRIPTION:
BIG BROWN CREEK 42.0
END DESCRIPTION:
XS GIS Cut Line= 3
      3621449.59     10644360.22      3622299.61     10642810.19
      3624299.59     10640810.21
#Sta/Elev= 30
  3230.8  358.64  3304.2  357.11  3369.7  352.45  3385.8  346.75  3401.9  350.86
  3429.4  350.06  3766.9  328.39  3777.3  329.49    3783  325.33  3799.1  324.47
  3804.8  328.88  3820.9  324.52  3835.3  326.83  3973.5  319.07  4033.2  315.88
  4092.9  310.77  4158.3  309.91  4171.4  303.61  4174.2  303.11  4177.4  303.61
  7346.2  303.61  7355.9  308.13  7367.4  311.82  7374.5  318.27  7445.2  326.53
  7517.6  330.17  7649.2   337.2  7658.5  337.62    7728  339.74    7827  337.98
#Mann= 9 ,-1 , 0
  3230.8     .05       0  3304.2     .16       0  3973.5     .12       0
  4171.4    .033       0  4177.4     .12       0  7355.9     .16       0
  7517.6     .12       0  7649.2     .08       0  7658.5     .12       0
Bank Sta=4033.2,7374.5
XS Rating Curve= 0 ,0
Exp/Cntr=0.3,0.1

Type RM Length L Ch R = 1 ,35336   ,541,541,541
BEGIN DESCRIPTION:
BIG BROWN CREEK 41.0
END DESCRIPTION:
XS GIS Cut Line= 3
      3621799.59     10644060.21      3622599.61     10643260.19
      3624399.61     10640860.19
#Sta/Elev= 30
  3863.2  332.96  3905.7  330.67  4089.5  316.22  4117.8  315.38  4160.2  311.58
  4226.8  309.75  4230.9  309.68  4242.1  303.61  4244.8  303.11  4248.1  303.61
  7381.1  303.61  7387.3  309.63  7401.9  313.28  7424.6  315.34  7431.1  316.43
  7494.6  321.15  7501.9  322.66  7531.1  325.28  7587.3  328.79  7601.9   332.9
  7632.6  334.28  7674.3  337.01  7687.3  336.28  7716.5  338.84  7781.1  340.33
  7787.3  339.71  7858.1  343.25  7944.6  345.18  7987.3  344.94  7994.6  343.77
#Mann= 7 ,-1 , 0
  3863.2     .16       0  4226.8     .05       0  4242.1    .033       0
  4248.1     .05       0  7424.6     .16       0  7632.6     .08       0
  7674.3     .12       0
Bank Sta=4089.5,7431.1
XS Rating Curve= 0 ,0
Exp/Cntr=0.3,0.1

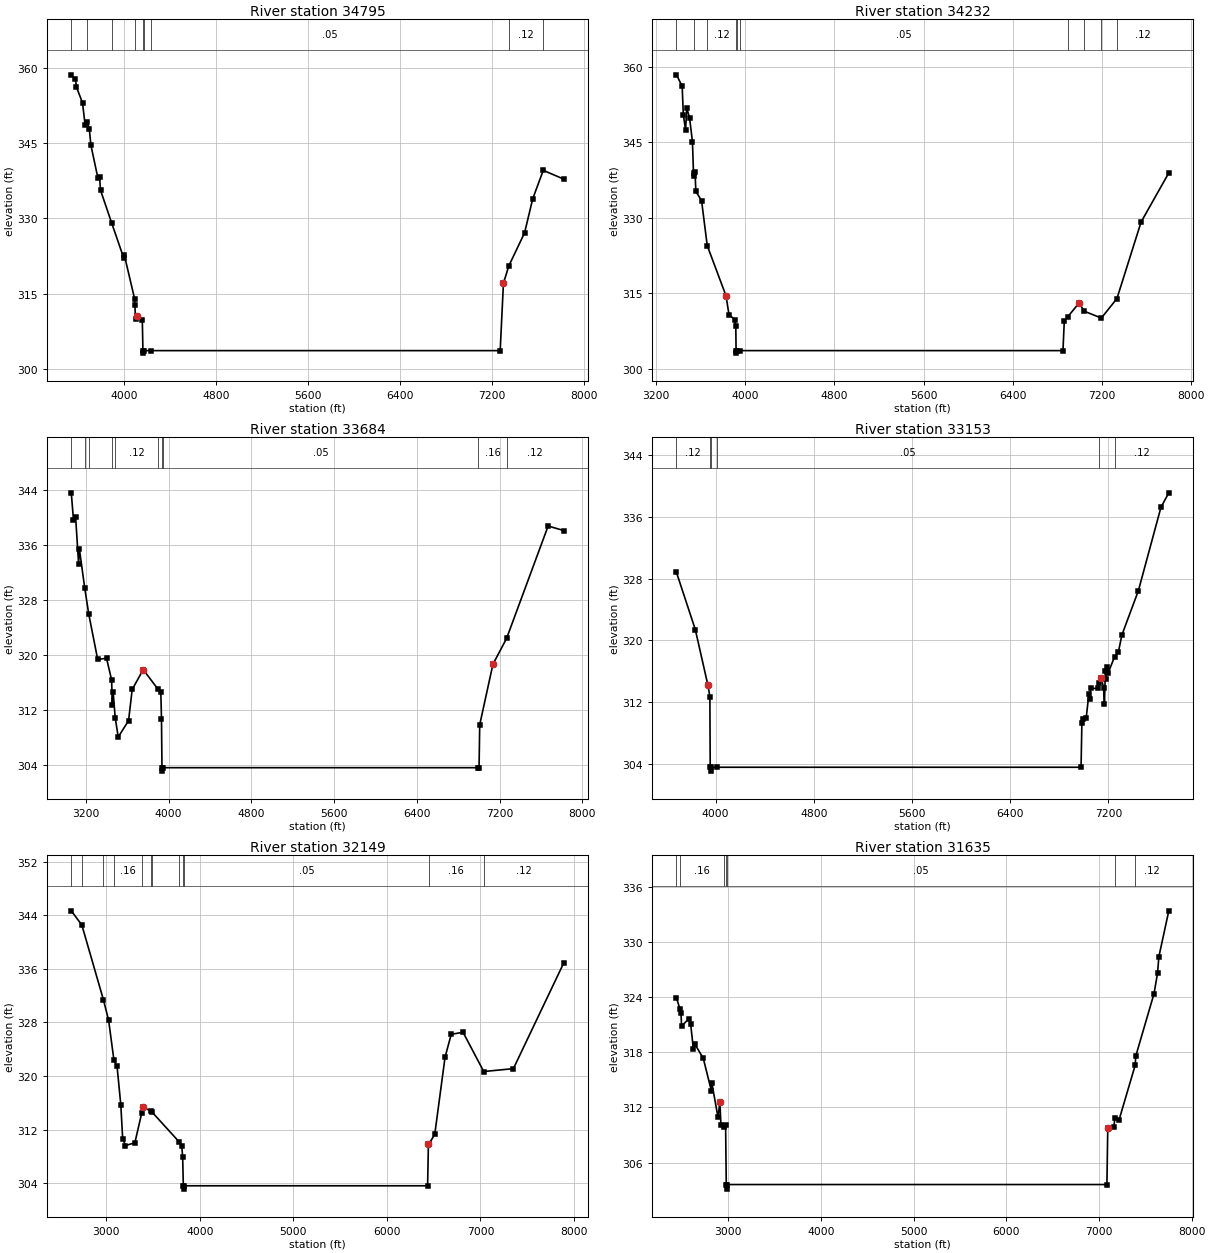
Type RM Length L Ch R = 1 ,34795   ,563,563,563
BEGIN DESCRIPTION:
BIG BROWN CREEK 40.0
END DESCRIPTION:
XS GIS Cut Line= 3
      3621599.61     10644360.19      3622899.61     10643710.19
      3624899.63     10641710.17
#Sta/Elev= 30
  3541.4  358.67  3577.7   357.8  3586.1  356.24  3639.2  353.07  3661.6  348.65
  3678.6  349.29  3697.9  347.93  3711.9  344.63  3773.4  338.01  3787.4  338.23
  3795.8  335.63  3894.2  328.99    3997  322.14  4002.6  322.71    4092  313.96
  4094.7  312.64  4100.4  309.84  4114.4  310.48  4159.1   309.8  4164.5  303.61
  4167.2  303.11  4170.5  303.61  4234.2  303.61  7271.7  303.61    7300  317.05
  7346.7  320.52  7483.9  327.13  7554.6  333.91  7646.5   339.6  7823.3  337.86
#Mann= 9 ,-1 , 0
  3541.4     .05       0  3678.6     .16       0  3894.2     .12       0
  4094.7     .16       0  4164.5    .033       0  4170.5     .16       0
  4234.2     .05       0  7346.7     .12       0  7646.5     .05       0
Bank Sta=4114.4,7300
XS Rating Curve= 0 ,0
Exp/Cntr=0.3,0.1

Type RM Length L Ch R = 1 ,34232   ,548,548,548
BEGIN DESCRIPTION:
BIG BROWN CREEK 39.0
END DESCRIPTION:
XS GIS Cut Line= 3
      3621649.66     10644510.18      3623249.61     10644160.19
      3625649.63     10642760.18
#Sta/Elev= 30
  3382.6  358.44  3433.7  356.18    3444  350.55  3464.4  347.44  3474.7  351.88
  3499.9  349.86  3525.9  345.18  3536.1  338.37  3543.6  338.95  3548.9  339.15
  3556.6  335.26  3607.8  333.42  3658.5  324.49  3827.5  314.48  3853.4  310.78
  3904.6  309.79  3914.8  308.44  3917.3  303.61  3920.1  303.11  3923.3  303.61
  3952.2  303.61  6849.6  303.61  6861.5  309.51  6890.7  310.28  6994.7  313.09
  7039.8  311.45  7193.8  310.08  7333.8  313.96  7550.4  329.18  7798.9  338.94
#Mann= 10 ,-1 , 0
  3382.6     .05       0  3543.6     .16       0  3658.5     .12       0
  3917.3    .033       0  3923.3     .12       0  3952.2     .05       0
  6890.7     .16       0  7039.8     .08       0  7193.8     .16       0
  7333.8     .12       0
Bank Sta=3827.5,6994.7
XS Rating Curve= 0 ,0
Exp/Cntr=0.3,0.1

Type RM Length L Ch R = 1 ,33684   ,531,531,531
BEGIN DESCRIPTION:
BIG BROWN CREEK 38.0
END DESCRIPTION:
XS GIS Cut Line= 3
      3622099.64     10645860.16      3623549.61     10644610.19
       3625749.6      10642810.2
#Sta/Elev= 30
  3060.5  343.56  3081.9  339.59  3102.7  339.98  3131.2  333.26  3138.9  335.39
  3190.4  329.72  3229.1  325.95  3315.5  319.35  3401.1  319.51  3450.5  316.35
  3456.3  312.76  3464.7  314.65  3484.7  310.89  3514.1  308.07  3613.9  310.44
    3649  314.98  3755.5  317.87  3894.7  315.09  3925.5  314.67  3932.1  310.68
  3936.8  303.61  3939.5  303.11  3942.8  303.61  6993.6  303.61  7000.5  303.61
    7007  309.87  7134.8  318.65  7266.2  322.39  7668.1  338.74  7817.4  338.08
#Mann= 10 ,-1 , 0
  3060.5     .05       0  3190.4     .16       0  3229.1     .12       0
  3456.3     .07       0  3484.7     .12       0  3894.7     .05       0
  3936.8    .033       0  3942.8     .05       0  6993.6     .16       0
  7266.2     .12       0
Bank Sta=3755.5,7134.8
XS Rating Curve= 0 ,0
Exp/Cntr=0.3,0.1

Type RM Length L Ch R = 1 ,33153   ,1004,1004,1004
BEGIN DESCRIPTION:
BIG BROWN CREEK 37.0
END DESCRIPTION:
XS GIS Cut Line= 3
       3622749.6     10645660.19      3623899.61     10645010.19
       3625699.6      10643010.2
#Sta/Elev= 30
  3680.7   328.8  3834.5  321.39  3936.9  314.21  3952.9  312.75  3955.6  303.61
  3958.3  303.11  3961.6  303.61    4012  303.61  6977.5  303.61  6984.2   309.3
  6991.7   309.9  7019.7  310.03    7041  313.06  7047.8  312.44  7055.2   313.8
  7118.8   313.8  7125.3  314.56  7140.4  315.18  7161.4  313.91  7168.1  311.82
  7175.6  316.02  7182.3  314.96  7189.8  316.51  7196.5  315.73  7251.4  317.92
  7281.7  318.49  7310.1   320.7  7444.6  326.43  7628.5  337.21  7692.4  339.08
#Mann= 6 ,-1 , 0
  3680.7     .12       0  3955.6    .033       0  3961.6     .12       0
    4012     .05       0  7125.3     .16       0  7251.4     .12       0
Bank Sta=3936.9,7140.4
XS Rating Curve= 0 ,0
Exp/Cntr=0.3,0.1

Type RM Length L Ch R = 1 ,32149   ,514,514,514
BEGIN DESCRIPTION:
BIG BROWN CREEK 35.0
END DESCRIPTION:
XS GIS Cut Line= 4
      3622181.53     10646065.74      3624264.84     10645926.86
       3624820.4     10645649.08      3626017.51     10643393.65
#Sta/Elev= 30
  2626.3  344.64  2739.3  342.52    2970  331.36  3025.3  328.32  3082.2  322.36
  3115.5  321.46  3155.6   315.7  3175.6  310.66  3205.7  309.62  3305.9  310.02
  3380.4  314.54  3388.7  315.31  3479.8  314.78  3490.1   314.6  3778.1  310.18
    3807  309.59    3817  307.88    3824  303.61  3826.8  303.11    3830  303.61
  6435.1  303.61  6443.6  309.79  6447.8  309.82  6511.5  311.28  6621.6   322.8
  6687.6  326.21  6813.8  326.52  7035.2  320.66  7352.2  321.09  7888.8  336.82
#Mann= 12 ,-1 , 0
  2626.3     .05       0  2739.3     .16       0    2970     .12       0
  3082.2     .16       0  3380.4     .12       0  3479.8     .16       0
  3490.1     .12       0  3778.1     .05       0    3824    .033       0
    3830     .05       0  6447.8     .16       0  7035.2     .12       0
Bank Sta=3388.7,6443.6
XS Rating Curve= 0 ,0
Exp/Cntr=0.3,0.1

Type RM Length L Ch R = 1 ,31635   ,307,307,307
BEGIN DESCRIPTION:
BIG BROWN CREEK 34.0
END DESCRIPTION:
XS GIS Cut Line= 4
      3622371.91     10646837.21      3624559.44     10646355.43
      3625132.35     10646042.93       3626108.9     10643829.43
#Sta/Elev= 30
  2441.3  323.91  2477.7  322.76  2490.1  322.27  2496.2  320.86  2572.1  321.62
  2593.9  321.12  2623.3   318.4  2637.6  318.92  2730.2  317.36  2817.7  313.82
  2822.8  314.67  2889.5  310.92    2910   312.6  2920.5  310.11  2951.7   309.9
  2971.4  310.08  2978.6  303.61  2981.4  303.11  2984.6  303.61  7085.6  303.61
  7094.8  309.81  7162.2  309.92  7170.5  310.84  7216.8  310.65  7390.7   316.6
  7396.4  317.57  7593.9  324.39  7632.1  326.63    7646   328.4  7753.2   333.4
#Mann= 7 ,-1 , 0
  2441.3     .12       0  2477.7     .16       0  2951.7     .05       0
  2978.6    .033       0  2984.6     .05       0  7170.5     .16       0
  7390.7     .12       0
Bank Sta=2910,7094.8
XS Rating Curve= 0 ,0
Exp/Cntr=0.3,0.1

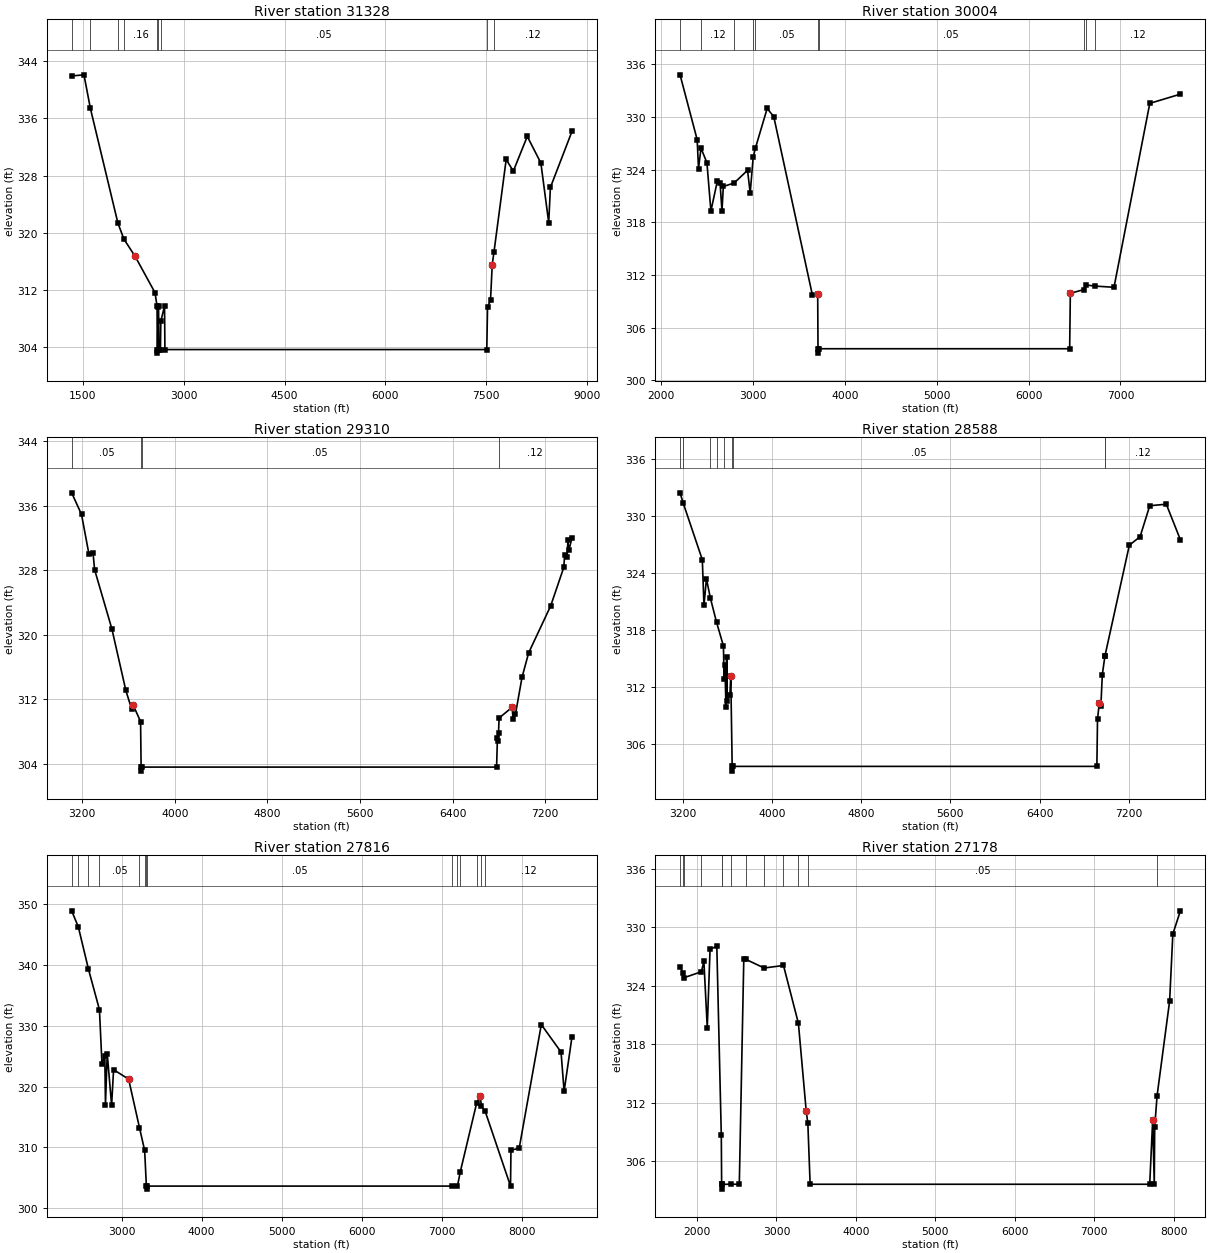
Type RM Length L Ch R = 1 ,31328   ,1324,1324,1324
BEGIN DESCRIPTION:
BIG BROWN CREEK 33.0
END DESCRIPTION:
XS GIS Cut Line= 4
       3623304.2     10649662.77      3624892.77     10646563.77
      3625322.46     10646186.16      3628498.34     10645014.73
#Sta/Elev= 30
  1335.6  341.95  1518.3  342.11  1613.6  337.41  2022.6  321.34  2112.4  319.08
    2278  316.69  2574.6  311.58  2605.3  309.67  2607.9  303.61  2610.7  303.11
  2613.9  303.61  2619.5  309.55  2627.5  309.76  2633.1  303.61  2655.3  303.61
  2660.8  307.57  2716.3   309.7  2721.9  303.61  7507.7  303.61  7518.7  309.54
  7563.4  310.55  7588.5  315.52  7614.7  317.28  7796.2  330.25    7902  328.61
  8109.7  333.48  8312.1  329.75  8428.5  321.39  8453.6  326.33  8775.1   334.2
#Mann= 9 ,-1 , 0
  1335.6     .05       0  1613.6     .16       0  2022.6     .05       0
  2112.4     .16       0  2607.9    .033       0  2613.9     .16       0
  2660.8     .05       0  7507.7     .16       0  7614.7     .12       0
Bank Sta=2278,7588.5
XS Rating Curve= 0 ,0
Exp/Cntr=0.3,0.1

Type RM Length L Ch R = 1 ,30004   ,694,694,694
BEGIN DESCRIPTION:
BIG BROWN CREEK 31.0
END DESCRIPTION:
XS GIS Cut Line= 4
       3624098.5      10649649.7      3625647.98     10647631.47
      3626090.69     10647305.95      3628043.78     10645990.87
#Sta/Elev= 30
  2204.7  334.81  2391.1  327.42  2405.6  324.13  2432.6  326.45  2497.1  324.81
  2540.7   319.3  2611.3  322.74  2640.4  322.46  2661.2   319.3  2675.7  322.09
  2793.8  322.49  2939.4  323.93  2968.5  321.36  3001.4  325.46  3025.5  326.47
  3153.3  330.98  3225.3  330.04  3645.5  309.74  3703.5   309.8  3706.9  303.61
  3709.6  303.11  3712.9  303.61  6447.3  303.61  6454.7  309.93  6601.1  310.34
  6629.5  310.87  6717.8  310.75  6930.1  310.61  7319.9  331.56  7653.2  332.61
#Mann= 10 ,-1 , 0
  2204.7     .16       0  2432.6     .12       0  2793.8     .16       0
  3001.4     .12       0  3025.5     .05       0  3706.9    .033       0
  3712.9     .05       0  6601.1     .12       0  6629.5     .05       0
  6717.8     .12       0
Bank Sta=3703.5,6454.7
XS Rating Curve= 0 ,0
Exp/Cntr=0.3,0.1

Type RM Length L Ch R = 1 ,29310   ,722,722,722
BEGIN DESCRIPTION:
BIG BROWN CREEK 30.0
END DESCRIPTION:
XS GIS Cut Line= 3
      3624849.64     10649260.17      3626299.61     10648010.19
      3627899.61     10646210.19
#Sta/Elev= 30
  3109.1   337.6  3194.1  334.92  3257.7  330.04  3293.9  330.09  3307.1  328.08
  3456.3  320.74    3577  313.11  3626.4  310.82  3640.6  311.29  3704.3  309.25
  3708.9  303.61  3711.7  303.11  3714.9  303.61    6780  303.61  6787.5  307.22
  6794.2   306.9  6796.8  307.87  6801.7  309.69  6914.6  311.03  6922.1  309.62
    6943  310.16  6999.9  314.74  7056.8  317.76  7247.4  323.59  7361.1  328.38
  7367.8  329.91  7389.6  329.62  7396.3  331.71  7403.8  330.47  7431.8  332.02
#Mann= 4 ,-1 , 0
  3109.1     .05       0  3708.9    .033       0  3714.9     .05       0
  6796.8     .12       0
Bank Sta=3640.6,6914.6
XS Rating Curve= 0 ,0
Exp/Cntr=0.3,0.1

Type RM Length L Ch R = 1 ,28588   ,772,772,772
BEGIN DESCRIPTION:
BIG BROWN CREEK 29.0
END DESCRIPTION:
XS GIS Cut Line= 4
       3625205.3     10649558.54      3626650.58     10648699.18
      3626897.98     10648373.66      3628082.85     10646290.37
#Sta/Elev= 30
  3176.2  332.44  3204.5  331.36  3375.8  325.39  3390.6  320.59  3412.8  323.37
  3448.3  321.34  3503.5   318.8  3565.1   316.3  3571.5  312.86  3578.3  314.31
  3588.1  309.83  3593.9   315.1    3600  310.53  3623.3  311.16    3631  313.17
  3643.6  303.61  3646.3  303.11  3649.6  303.61  6914.1  303.61  6919.9  308.59
  6935.7  310.28  6950.1     310  6963.1  313.29  6986.4  315.25  6986.7  315.26
  7205.3  326.92  7301.8  327.82  7388.3  331.08  7536.9  331.24  7663.2  327.49
#Mann= 9 ,-1 , 0
  3176.2     .05       0  3204.5     .16       0  3448.3     .05       0
  3503.5     .16       0  3571.5     .05       0  3643.6    .033       0
  3649.6     .05       0  6986.4     .16       0  6986.7     .12       0
Bank Sta=3631,6935.7
XS Rating Curve= 0 ,0
Exp/Cntr=0.3,0.1

Type RM Length L Ch R = 1 ,27816   ,638,638,638
BEGIN DESCRIPTION:
BIG BROWN CREEK 28.0
END DESCRIPTION:
XS GIS Cut Line= 4
      3624825.75     10650212.06       3626976.1     10649389.29
      3627418.81      10649024.7       3628655.2     10645888.19
#Sta/Elev= 30
  2377.1  348.95  2460.2  346.29  2586.6  339.34  2723.7  332.67  2755.4  323.71
  2790.8   325.1  2798.8  316.95  2820.8  325.43  2875.6  316.94  2900.3  322.78
  3087.9  321.23  3223.1  313.26  3288.2  309.48  3309.7  303.61  3312.5  303.11
  3315.7  303.61  7123.4  303.61  7194.3  303.61  7227.2  305.85  7434.8  317.35
  7477.5  318.44  7493.8  316.73  7538.6  315.98  7856.5  303.61  7861.9  309.52
  7964.8  309.85  8240.9  330.21  8487.2  325.69  8525.5  319.22  8624.4  328.24
#Mann= 14 ,-1 , 0
  2377.1     .08       0  2460.2     .05       0  2586.6     .08       0
  2723.7     .05       0  3223.1     .16       0  3288.2     .05       0
  3309.7    .033       0  3315.7     .05       0  7123.4     .16       0
  7194.3     .05       0  7227.2     .16       0  7434.8     .12       0
  7493.8     .16       0  7538.6     .12       0
Bank Sta=3087.9,7477.5
XS Rating Curve= 0 ,0
Exp/Cntr=0.3,0.1

Type RM Length L Ch R = 1 ,27178   ,505,505,505
BEGIN DESCRIPTION:
BIG BROWN CREEK 26.0
END DESCRIPTION:
XS GIS Cut Line= 3
      3625540.15     10651824.65      3627677.76      10649741.3
      3628749.61     10646610.19
#Sta/Elev= 30
  1787.5  325.95  1822.7  325.33    1840  324.82  2056.2  325.43  2087.3   326.5
  2129.7  319.69    2165  327.75  2249.9  328.04  2306.4  308.62  2310.6  303.61
  2313.4  303.11  2316.6  303.61  2427.7  303.61  2532.8  303.61  2589.4  326.75
  2614.7   326.7  2845.4  325.81  3088.6  326.07  3276.2  320.14  3374.4  311.14
  3395.2  309.85  3423.8  303.61    7696  303.61  7733.1  310.18  7753.3  303.61
  7758.6  309.47  7788.4  312.69  7946.4  322.42  7986.8   329.3  8081.9  331.68
#Mann= 13 ,-1 , 0
  1787.5     .05       0  1822.7      .1       0    1840     .15       0
  2056.2      .1       0  2310.6    .033       0  2316.6      .1       0
  2427.7     .05       0  2614.7     .08       0  2845.4     .16       0
  3088.6     .12       0  3276.2     .16       0  3395.2     .05       0
  7788.4     .12       0
Bank Sta=3374.4,7733.1
XS Rating Curve= 0 ,0
Exp/Cntr=0.3,0.1