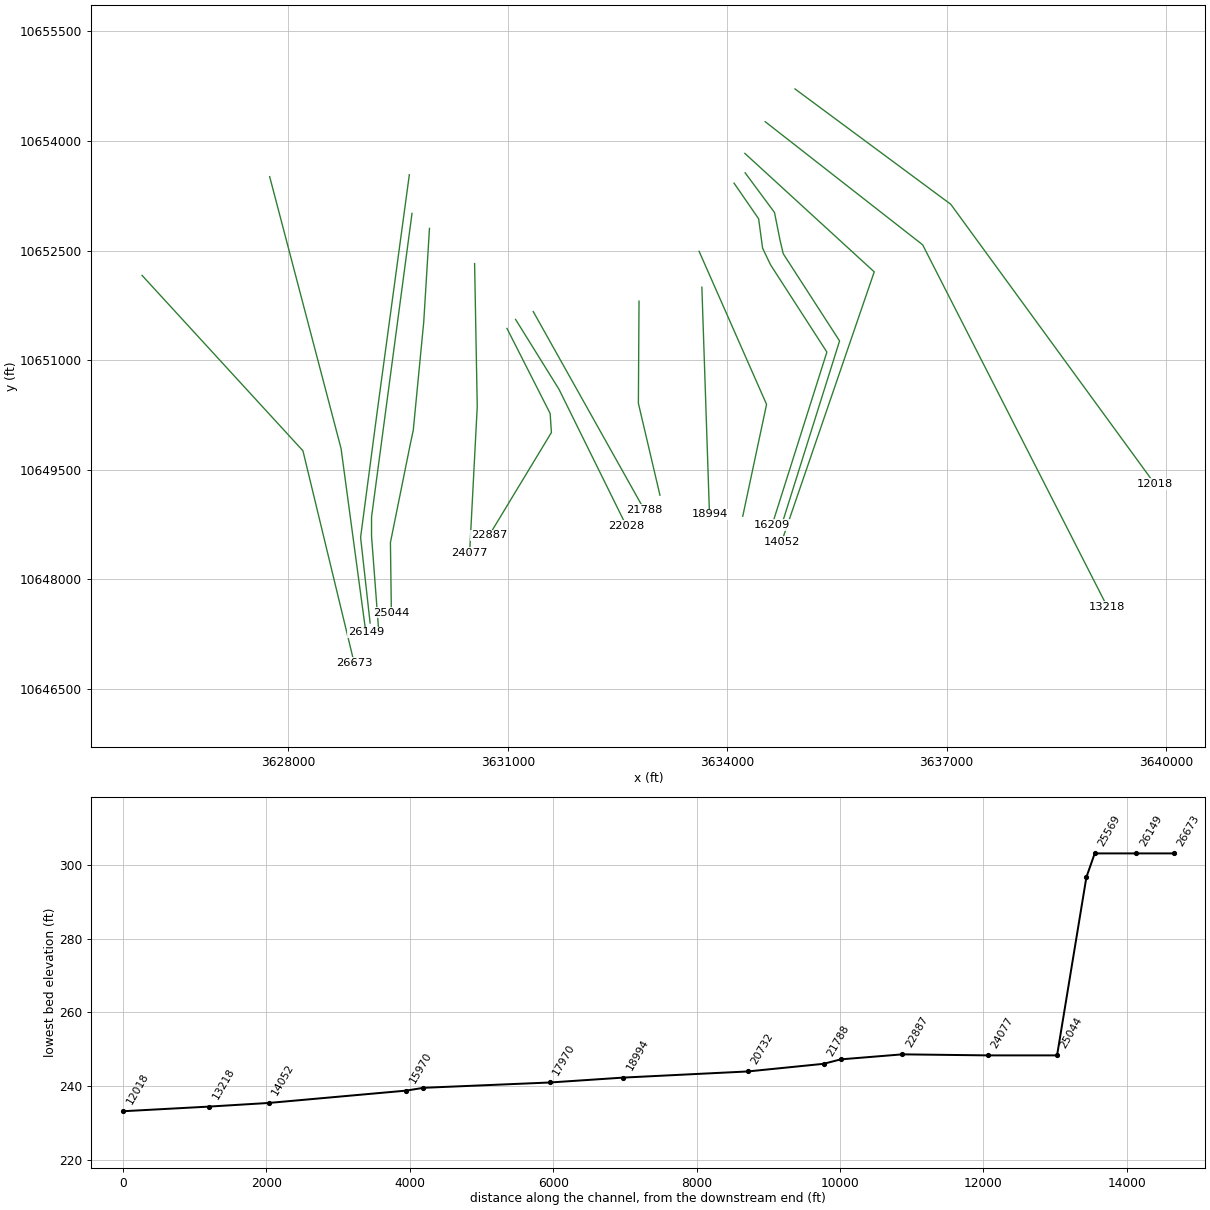
HEC-RAS study BIG BROWN CREEK.prj: BIG BROWN CREEK Base Level Engineering

--- BIG BROWN CREEK.g01 (geometry) --- (continued)

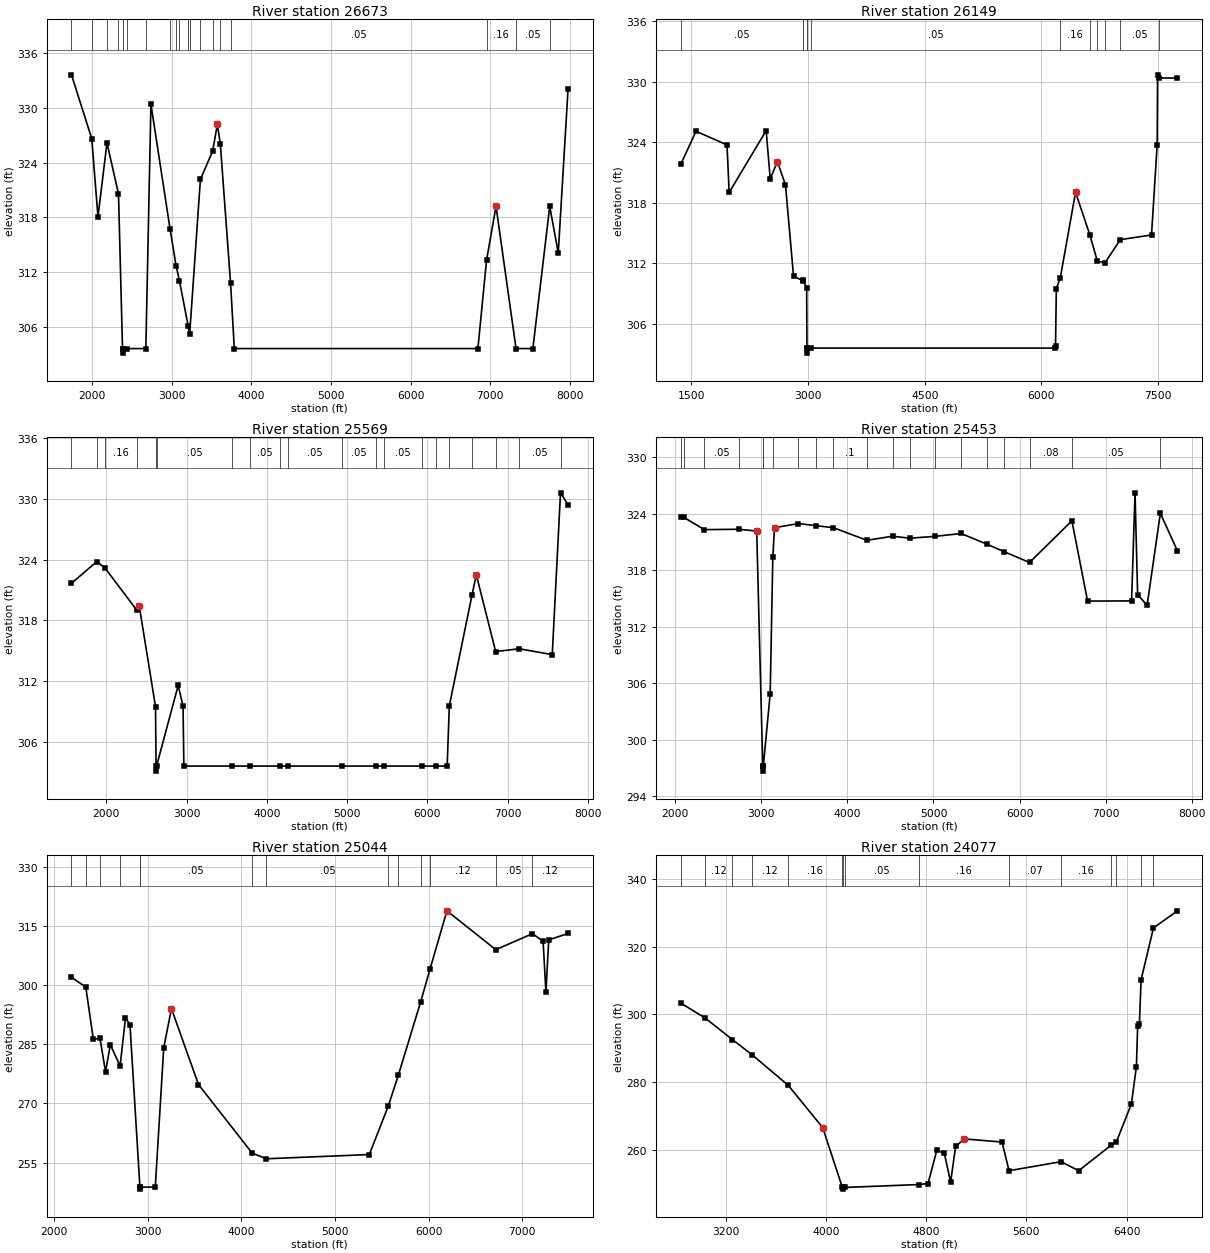
Type RM Length L Ch R = 1 ,26673   ,524,524,524
BEGIN DESCRIPTION:
BIG BROWN CREEK 25.0
END DESCRIPTION:
XS GIS Cut Line= 3
      3625999.62     10652160.17      3628199.61     10649760.19
       3628899.6     10646860.22
#Sta/Elev= 30
  1740.2  333.62  1994.7  326.62  2072.8  318.06  2185.9  326.15  2330.7  320.58
  2381.2  303.61    2384  303.11  2387.2  303.61  2433.9  303.61  2674.3  303.61
  2738.2   330.4  2978.6  316.72  3053.8  312.71  3096.3  311.05  3206.7  306.07
  3224.7  305.17  3359.7  322.15  3512.6  325.23  3573.1  328.18    3610  326.07
  3738.4  310.82  3785.8  303.61  6846.2  303.61  6954.7  313.28    7074  319.21
  7325.4  303.61  7536.9  303.61  7748.8  319.19  7855.8   314.1  7979.2  332.09
#Mann= 20 ,-1 , 0
  1740.2     .05       0  1994.7      .1       0  2185.9     .15       0
  2330.7      .1       0  2381.2    .033       0  2387.2      .1       0
  2433.9     .05       0  2674.3     .16       0  2978.6     .12       0
  3053.8     .16       0  3096.3     .05       0  3206.7     .12       0
  3224.7     .05       0  3359.7     .16       0  3512.6     .12       0
    3610     .16       0  3738.4     .05       0  6954.7     .16       0
  7325.4     .05       0  7748.8     .12       0
Bank Sta=3573.1,7074
XS Rating Curve= 0 ,0
Exp/Cntr=0.3,0.1

Type RM Length L Ch R = 1 ,26149   ,580,580,580
BEGIN DESCRIPTION:
BIG BROWN CREEK 24.0
END DESCRIPTION:
XS GIS Cut Line= 3
      3627744.56     10653510.84      3628720.89     10649790.76
      3629059.44     10647277.73
#Sta/Elev= 30
  1365.6  321.82  1560.2  325.08  1958.7  323.73  1986.6  319.02  2462.2  325.15
  2513.9  320.38  2606.9  322.08  2710.3  319.76  2813.7  310.74  2931.5  310.28
    2935  310.34  2982.6   309.6  2986.4  303.61  2989.2  303.11  2992.4  303.61
  3035.3  303.61  6170.8  303.61  6180.9  303.82    6191  309.51  6242.3  310.57
  6438.1  319.03  6620.4  314.85  6718.8  312.21  6817.3  312.07  7014.1  314.35
  7414.3  314.81  7487.1  323.74  7492.7  330.67  7510.3  330.36  7747.4  330.35
#Mann= 12 ,-1 , 0
  1365.6     .05       0  2931.5     .16       0    2935     .12       0
  2986.4    .033       0  2992.4     .12       0  3035.3     .05       0
  6242.3     .16       0  6620.4     .08       0  6718.8     .05       0
  6817.3      .1       0  7014.1     .05       0  7510.3     .12       0
Bank Sta=2606.9,6438.1
XS Rating Curve= 0 ,0
Exp/Cntr=0.3,0.1

Type RM Length L Ch R = 1 ,25569   ,116,116,116
BEGIN DESCRIPTION:
BIG BROWN CREEK 23.0
END DESCRIPTION:
XS GIS Cut Line= 4
      3629654.29     10653536.89      3629212.95     10650281.48
      3628987.82     10648575.48      3629117.95     10647404.37
#Sta/Elev= 30
  1566.6  321.67  1879.4   323.8  1978.9  323.23  2376.8  319.05    2411   319.4
  2612.8  309.49  2619.9  303.61  2622.6  303.11  2625.9  303.61  2895.3  311.58
  2955.9  309.52    2966  303.61  3570.6  303.61    3792  303.61  4167.5  303.61
    4267  303.61  4937.4  303.61  5360.9  303.61  5460.4  303.61  5930.2  303.61
  6104.6  303.61  6245.1  303.61    6272  309.56    6554  320.49  6608.1  322.51
  6848.9  314.93  7143.6   315.2  7553.9  314.62  7656.7  330.61  7750.9  329.43
#Mann= 20 ,-1 , 0
  1566.6     .05       0  1879.4      .1       0  1978.9     .16       0
  2376.8     .05       0  2619.9    .033       0  2625.9     .05       0
  3570.6     .08       0    3792     .05       0  4167.5     .08       0
    4267     .05       0  4937.4     .05       0  5360.9      .1       0
  5460.4     .05       0  5930.2     .05       0  6104.6     .05       0
    6272     .16       0    6554     .05       0  6848.9     .08       0
  7143.6     .05       0  7656.7     .12       0
Bank Sta=2411,6608.1
XS Rating Curve= 0 ,0
Exp/Cntr=0.3,0.1

Type RM Length L Ch R = 1 ,25453   ,409,409,409
BEGIN DESCRIPTION:
Mapping XS f23472d9
END DESCRIPTION:
XS GIS Cut Line= 4
      3629690.95      10653009.1      3629137.56     10648853.26
      3629137.56     10648592.85      3629236.75     10647279.02
#Sta/Elev= 30
  2064.4   323.6  2095.7  323.63  2337.6  322.31  2735.4  322.35  2945.9  322.16
  3016.1  297.16  3018.8  296.66  3022.1  297.16  3102.4  304.86  3133.1  319.36
  3152.8  322.52  3431.4  322.95  3630.3  322.74  3834.7  322.52    4227  321.18
  4525.3  321.61  4724.2   321.4  5022.5   321.6  5320.8   321.9  5619.1  320.77
    5818  319.98  6116.3  318.82  6608.6  323.25  6790.8  314.72  7302.2  314.74
  7342.3  326.22  7372.4  315.41  7482.7  314.27  7636.5  324.05  7834.9  320.06
#Mann= 20 ,-1 , 0
  2064.4     .05       0  2095.7      .1       0  2337.6     .05       0
  2735.4     .05       0  3016.1     .04       0  3022.1      .1       0
  3133.1     .05       0  3431.4      .1       0  3630.3     .05       0
  3834.7      .1       0    4227     .05       0  4525.3      .1       0
  4724.2     .05       0  5022.5      .1       0  5320.8     .05       0
  5619.1      .1       0    5818     .05       0  6116.3     .08       0
  6608.6     .05       0  7636.5     .12       0
Bank Sta=2945.9,3152.8
XS Rating Curve= 0 ,0
Exp/Cntr=0.3,0.1

Type RM Length L Ch R = 1 ,25044   ,967,967,967
BEGIN DESCRIPTION:
BIG BROWN CREEK 22.0
END DESCRIPTION:
XS GIS Cut Line= 6
      3629929.66     10652802.91      3629851.54     10651526.87
      3629708.31      10650042.5      3629669.24     10649860.21
      3629395.81     10648506.04      3629408.81     10647543.85
#Sta/Elev= 30
  2187.8  301.95  2340.4  299.47    2421  286.23  2491.6  286.51  2551.2     278
    2602  284.87  2706.7  279.51    2764  291.64  2811.7  289.99    2918  248.79
  2920.7  248.29    2924  248.79  3082.2  248.82  3172.4  284.15  3254.9  293.99
  3543.3  274.78  4115.7  257.43  4267.3  255.98  5366.4  257.05  5570.7  269.46
    5677  277.22  5914.6  295.74  6015.4  304.12  6194.7  318.79  6715.8  308.95
  7107.9     313  7221.3  311.06  7251.3  298.21  7281.3  311.43  7487.7  313.05
#Mann= 14 ,-1 , 0
  2187.8     .05       0  2340.4     .16       0  2491.6     .12       0
  2706.7     .05       0    2918     .03       0    2924     .05       0
  4115.7     .16       0  4267.3     .05       0  5570.7     .16       0
    5677     .05       0  5914.6     .16       0  6015.4     .12       0
  6715.8     .05       0  7107.9     .12       0
Bank Sta=3254.9,6194.7
XS Rating Curve= 0 ,0
Exp/Cntr=0.3,0.1

Type RM Length L Ch R = 1 ,24077   ,1190,1190,1190
BEGIN DESCRIPTION:
BIG BROWN CREEK 20.0
END DESCRIPTION:
XS GIS Cut Line= 3
      3630546.83     10652321.47      3630582.87     10650366.57
      3630478.81     10648363.31
#Sta/Elev= 30
  2843.8  303.31  3035.8  298.96  3254.9  292.54  3409.4  288.11  3700.7     279
  3975.3   266.5  4132.3  248.79  4135.1  248.29  4138.3  248.79  4156.5  248.79
  4744.5  249.65  4815.4  249.94  4885.5  259.76  4945.6  258.92  4995.7  250.37
  5035.7  260.94  5105.8  263.15  5406.2  262.22  5461.7  253.74    5877  256.41
  6017.1  253.74  6273.5  261.21  6318.5  262.31  6437.6   273.5  6477.7  284.46
  6487.7  296.45  6501.6  297.15  6515.3  310.27  6613.7  325.56    6805  330.63
#Mann= 15 ,-1 , 0
  2843.8     .05       0  3035.8     .12       0  3254.9     .16       0
  3409.4     .12       0  3700.7     .16       0  4132.3     .07       0
  4138.3     .16       0  4156.5     .05       0  4744.5     .16       0
  5461.7     .07       0    5877     .16       0  6273.5     .12       0
  6318.5     .05       0  6515.3     .16       0  6613.7     .12       0
Bank Sta=3975.3,5105.8
XS Rating Curve= 0 ,0
Exp/Cntr=0.3,0.1

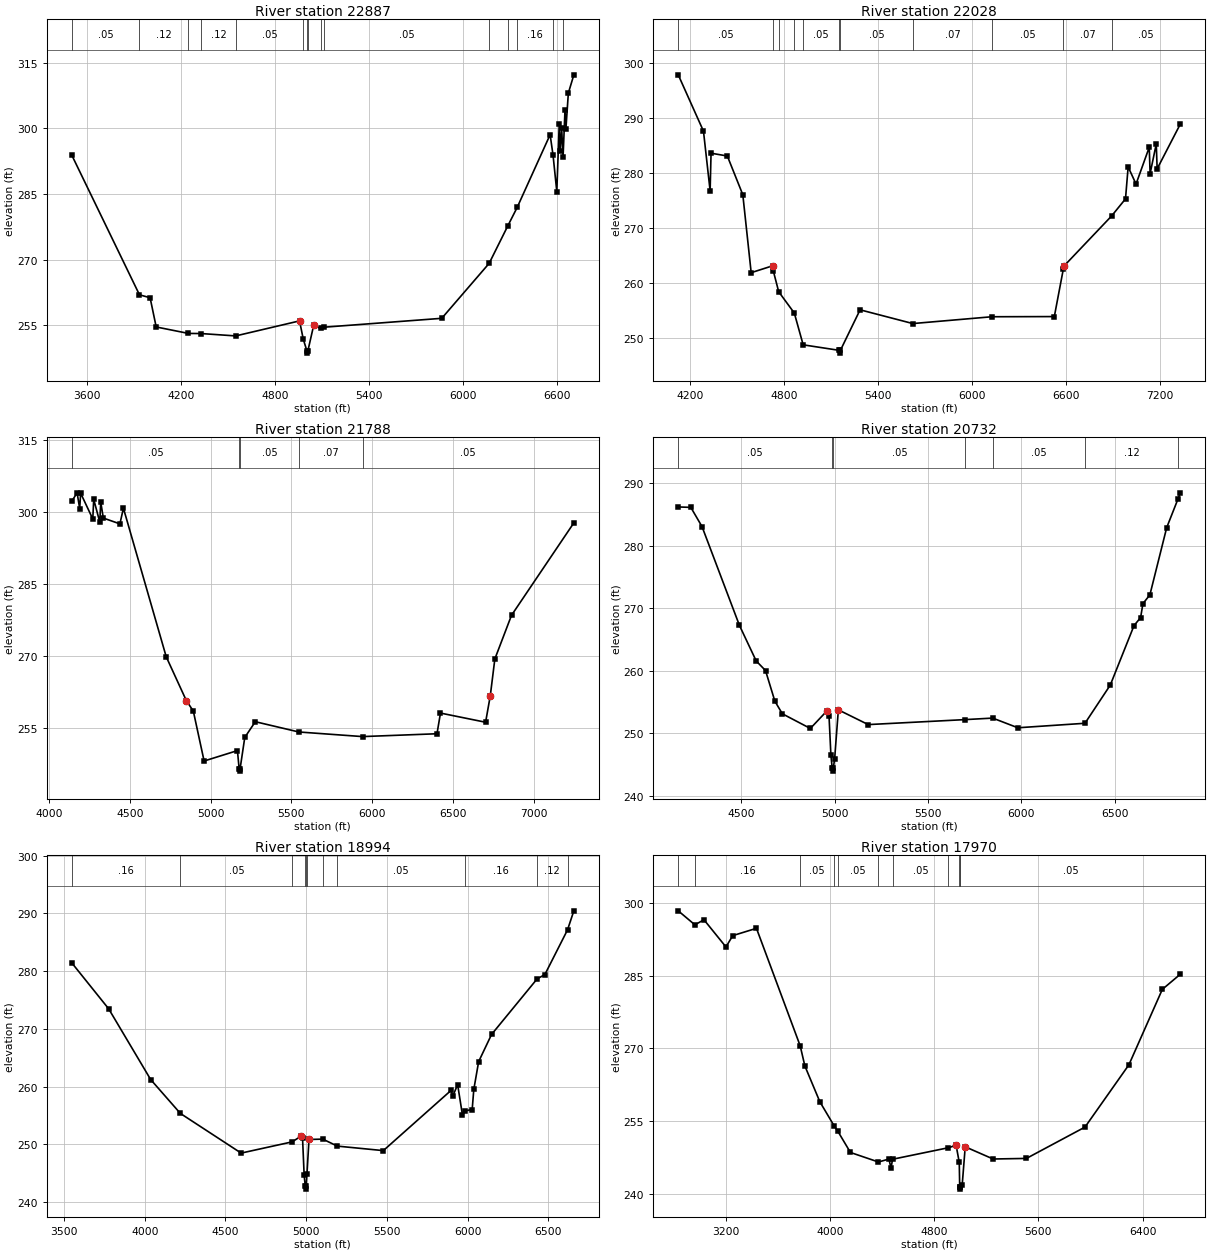
Type RM Length L Ch R = 1 ,22887   ,859,859,859
BEGIN DESCRIPTION:
Mapping XS 665d492a
END DESCRIPTION:
XS GIS Cut Line= 4
      3630989.44     10651434.29      3631579.71     10650271.11
      3631597.07      10650010.7      3630746.59      10648604.8
#Sta/Elev= 30
  3501.8   293.9  3934.4  261.92  4002.4  261.25  4041.3  254.56  4247.3  253.08
  4328.8  253.05  4549.3  252.51  4957.4  255.95  4981.2  251.76  5004.5  249.07
  5007.3  248.57  5010.5  249.07  5047.6  254.91  5091.6  254.22  5115.4  254.51
  5866.2  256.54    6169  269.12  6289.1  277.76  6348.6  281.96  6558.7  298.58
  6577.5  293.84  6601.4  285.56  6616.9  301.04  6622.8  294.88  6632.4     300
  6641.3   293.4  6653.8  304.25  6659.6  299.91  6675.1  308.09  6710.3  312.28
#Mann= 15 ,-1 , 0
  3501.8     .05       0  3934.4     .12       0  4247.3     .07       0
  4328.8     .12       0  4549.3     .05       0  4981.2     .16       0
  5004.5     .07       0  5010.5     .16       0  5091.6     .16       0
  5115.4     .05       0    6169     .16       0  6289.1     .12       0
  6348.6     .16       0  6577.5     .05       0  6641.3     .16       0
Bank Sta=4957.4,5047.6
XS Rating Curve= 0 ,0
Exp/Cntr=0.3,0.1

Type RM Length L Ch R = 1 ,22028   ,240,240,240
BEGIN DESCRIPTION:
BIG BROWN CREEK 19.0
END DESCRIPTION:
XS GIS Cut Line= 3
      3631107.03     10651558.04      3631701.24     10650600.97
      3632621.27     10648734.88
#Sta/Elev= 30
    4124  297.85  4285.2   287.6  4327.7  276.73  4333.6  283.59  4437.6  283.08
  4536.5  276.03  4589.9  261.85  4726.9   263.1  4730.9  262.21  4765.7  258.38
  4865.5   254.5    4922  248.72  5153.8  247.71  5156.5  247.21  5159.8  247.71
  5285.6  255.09  5622.4  252.59  6127.5  253.83  6526.3  253.86  6584.2  262.56
  6588.1  263.06  6891.7  272.15    6981  275.28  6997.9   281.1  7048.3  277.97
  7132.6  284.67  7138.2  279.88  7177.5  285.28  7183.1  280.74  7331.1  288.89
#Mann= 11 ,-1 , 0
    4124     .05       0  4730.9     .16       0  4765.7     .05       0
  4865.5     .16       0    4922     .05       0  5153.8     .03       0
  5159.8     .05       0  5622.4     .07       0  6127.5     .05       0
  6584.2     .07       0  6891.7     .05       0
Bank Sta=4726.9,6588.1
XS Rating Curve= 0 ,0
Exp/Cntr=0.3,0.1

Type RM Length L Ch R = 1 ,21788   ,1056,1056,1056
BEGIN DESCRIPTION:
BIG BROWN CREEK 18.0
END DESCRIPTION:
XS GIS Cut Line= 2
      3631348.82     10651664.75      3632867.06     10648953.61
#Sta/Elev= 30
  4141.4  302.26  4174.5  304.01  4190.5  300.71  4196.2  303.95  4271.5  298.55
  4277.2  302.65  4314.9  297.89  4320.6  302.12  4336.6  298.75  4439.3  297.54
    4461  300.81  4725.9  269.84  4850.3  260.71  4893.7  258.51  4960.4  248.11
  5166.7  250.28  5177.2   246.5    5180     246  5183.2   246.5  5212.1  253.02
  5277.2   256.3  5546.6  254.16  5940.9   253.2  6401.7  253.79  6423.3   258.1
  6702.5  256.19  6731.6  261.72  6759.8  269.38  6862.9  278.48  7248.7  297.75
#Mann= 5 ,-1 , 0
  4141.4     .05       0  5177.2     .03       0  5183.2     .05       0
  5546.6     .07       0  5940.9     .05       0
Bank Sta=4850.3,6731.6
XS Rating Curve= 0 ,0
Exp/Cntr=0.3,0.1

Type RM Length L Ch R = 1 ,20732   ,1738,1738,1738
BEGIN DESCRIPTION:
BIG BROWN CREEK 17.0
END DESCRIPTION:
XS GIS Cut Line= 3
      3632794.99      10651807.6      3632786.31       10650410.
        3633081.     10649153.22
#Sta/Elev= 30
  4162.9  286.22  4230.3  286.15  4290.3  283.07  4490.3  267.28  4580.3  261.57
  4630.3  260.03  4680.3  255.13  4720.3  253.11  4870.3  250.76  4960.3  253.61
  4970.3  252.78  4980.3  246.53  4987.3  244.43  4990.1  243.93  4993.3  244.43
  5000.3  245.87  5020.3  253.74  5180.3  251.38  5700.9  252.18  5846.7  252.42
  5981.5  250.87  6340.9  251.59  6476.3   257.7  6603.6  267.23  6638.8  268.51
  6651.2  270.74  6688.5  272.15  6778.5  282.91  6839.1  287.51  6851.4  288.48
#Mann= 7 ,-1 , 0
  4162.9     .05       0  4987.3     .03       0  4993.3     .05       0
  5700.9     .16       0  5846.7     .05       0  6340.9     .12       0
  6839.1     .16       0
Bank Sta=4960.3,5020.3
XS Rating Curve= 0 ,0
Exp/Cntr=0.3,0.1

Type RM Length L Ch R = 1 ,18994   ,1024,1024,1024
BEGIN DESCRIPTION:
Mapping XS a09cf07c
END DESCRIPTION:
XS GIS Cut Line= 2
      3633654.36     10651998.56      3633758.53      10648890.9
#Sta/Elev= 30
  3548.1  281.45  3776.6  273.49  4036.7  261.24  4220.7  255.37  4597.1   248.5
  4913.6  250.45  4967.3  251.43  4977.3   251.1  4987.3  244.64  4994.3  242.76
    4997  242.26  5000.3  242.76  5004.6  244.85  5017.3  250.86  5102.6  250.92
  5192.9  249.71  5477.6  248.93  5897.8  259.38  5907.8  258.36  5937.8  260.37
  5967.8  255.07  5984.4  255.82  6027.9  256.05  6037.9  259.52  6067.9  264.34
  6147.9  269.05  6429.4  278.65  6478.1  279.43  6618.3  287.16  6657.5  290.46
#Mann= 11 ,-1 , 0
  3548.1     .16       0  4220.7     .05       0  4913.6     .16       0
  4994.3     .07       0  5000.3     .16       0  5004.6     .12       0
  5102.6     .16       0  5192.9     .05       0  5984.4     .16       0
  6429.4     .12       0  6618.3     .16       0
Bank Sta=4967.3,5017.3
XS Rating Curve= 0 ,0
Exp/Cntr=0.3,0.1

Type RM Length L Ch R = 1 ,17970   ,1761,1761,1761
BEGIN DESCRIPTION:
Mapping XS f4e84c38
END DESCRIPTION:
XS GIS Cut Line= 3
       3633616.6     10652489.43      3634538.91     10650395.24
      3634213.39     10648865.28
#Sta/Elev= 30
  2837.1  298.39  2964.9   295.5  3034.5  296.55  3203.3  290.93  3255.4  293.27
  3437.3  294.78    3773   270.5  3808.8  266.36  3923.7  258.97  4033.4  253.99
  4061.6  252.88  4158.4   248.5  4373.4  246.53  4453.5  247.14  4469.7  245.31
  4481.9   247.1  4910.8  249.48  4969.2  249.98  4993.4  246.46  4996.8  241.43
  4999.5  240.93  5002.8  241.43  5015.8  241.73  5039.2  249.67  5253.2  247.15
  5508.8  247.27  5958.3  253.74  6295.1   266.6  6551.7  282.18  6689.6   285.3
#Mann= 11 ,-1 , 0
  2837.1     .12       0  2964.9     .16       0    3773     .05       0
  4033.4     .08       0  4061.6     .05       0  4373.4     .16       0
  4481.9     .05       0  4910.8     .16       0  4993.4     .05       0
  4996.8     .03       0  5002.8     .05       0
Bank Sta=4969.2,5039.2
XS Rating Curve= 0 ,0
Exp/Cntr=0.3,0.1

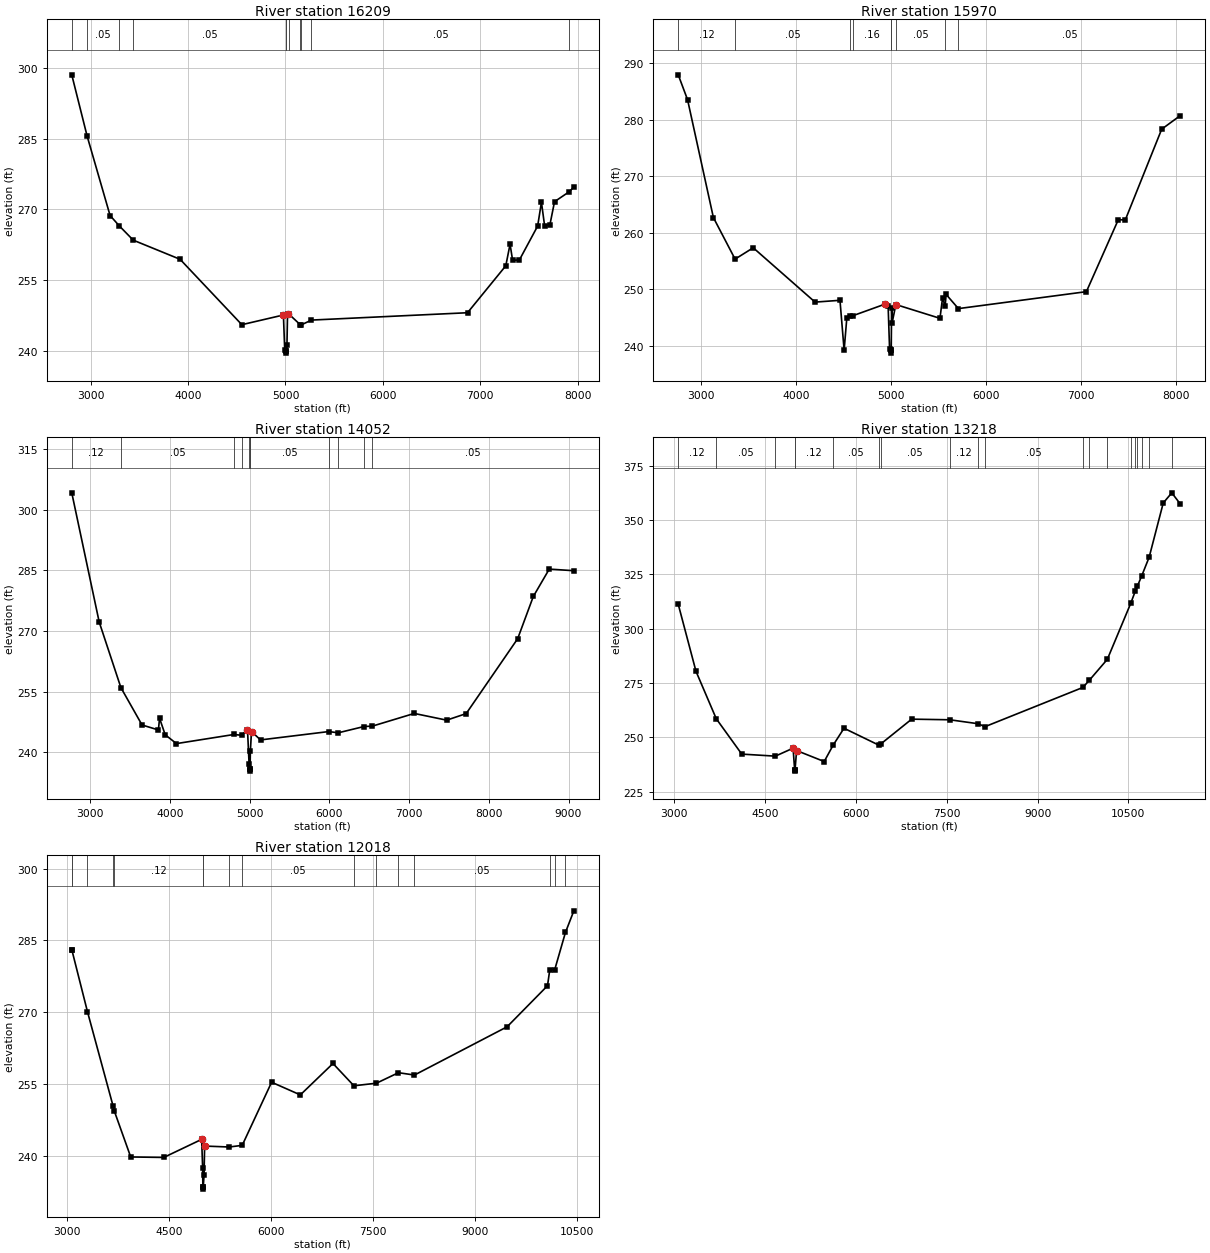
Type RM Length L Ch R = 1 ,16209   ,239,239,239
BEGIN DESCRIPTION:
BIG BROWN CREEK 16.0
END DESCRIPTION:
XS GIS Cut Line= 6
      3634094.01     10653422.62      3634430.41     10652934.31
      3634484.66     10652532.83      3634593.17     10652304.97
      3635363.56     10651111.39      3634614.85      10648745.9
#Sta/Elev= 30
  2806.4   298.6    2964  285.59  3199.6  268.72  3294.8   266.5  3437.7  263.48
  3918.3  259.42  4552.2  245.53    4979  247.59  4992.6  240.05    5003  239.99
  5005.8  239.49    5009  239.99  5015.3  241.21  5021.2  247.71  5039.4   247.7
  5153.2   245.5    5161  245.48  5267.1  246.51  6868.9  248.07  7261.7  258.04
  7305.5  262.63  7331.6  259.21  7401.4  259.28  7588.7  266.48  7627.6  271.54
  7659.9  266.58  7714.6  266.75    7762  271.66  7914.6  273.79  7960.3  274.79
#Mann= 11 ,-1 , 0
  2806.4     .12       0    2964     .05       0  3294.8     .07       0
  3437.7     .05       0    5003     .04       0    5009     .05       0
  5039.4     .16       0  5153.2     .05       0    5161     .08       0
  5267.1     .05       0  7914.6     .16       0
Bank Sta=4979,5021.2
XS Rating Curve= 0 ,0
Exp/Cntr=0.3,0.1

Type RM Length L Ch R = 1 ,15970   ,1918,1918,1918
BEGIN DESCRIPTION:
BIG BROWN CREEK 15.0
END DESCRIPTION:
XS GIS Cut Line= 6
      3634245.95     10653563.64      3634647.42     10653021.11
      3634723.37     10652641.34      3634766.78     10652456.88
      3635537.18      10651263.3      3634755.91     10648778.45
#Sta/Elev= 30
  2765.5  287.99  2863.6  283.58  3134.9  262.73    3363  255.37  3553.5  257.38
  4203.7  247.76  4465.5  248.08  4509.1  239.25    4537  244.88  4573.1  245.22
  4597.3  245.33  4941.6  247.42  4971.7  246.99  4986.9  239.46  4998.1  239.23
  5000.9  238.73  5004.1  239.23    5008  246.63    5014  244.13  5052.7  247.33
  5516.4  244.89  5543.5  248.48  5570.8  247.05  5581.2  249.12  5710.2  246.61
  7055.4  249.61  7390.9  262.35  7464.2   262.3  7846.9  278.37  8042.6  280.78
#Mann= 9 ,-1 , 0
  2765.5     .12       0    3363     .05       0  4573.1     .12       0
  4597.3     .16       0  4998.1     .07       0  5004.1     .16       0
  5052.7     .05       0  5570.8     .08       0  5710.2     .05       0
Bank Sta=4941.6,5052.7
XS Rating Curve= 0 ,0
Exp/Cntr=0.3,0.1

Type RM Length L Ch R = 1 ,14052   ,834,834,834
BEGIN DESCRIPTION:
BIG BROWN CREEK 14.0
END DESCRIPTION:
XS GIS Cut Line= 3
       3634242.5     10653828.88      3636011.03      10652208.5
      3634745.97     10648518.96
#Sta/Elev= 30
  2767.6  304.13  3111.5  272.23  3383.9  256.01  3649.2  246.78  3854.6  245.55
  3868.8  248.45  3939.7  244.36  4080.9  242.18  4802.3  244.43  4897.2  244.24
  4965.8  245.49  4973.2  245.27  4992.4  237.06  4998.5  235.88  5001.3  235.38
  5004.5  235.88  5008.3  240.35  5022.5  245.16  5135.9  243.09  5990.2  245.15
  6110.9  244.85  6434.1   246.4  6539.2   246.5  7064.4  249.63  7470.9  247.97
  7715.8  249.59    8362   268.1  8557.9  278.52    8758  285.29  9066.6  284.89
#Mann= 11 ,-1 , 0
  2767.6     .12       0  3383.9     .05       0  4802.3     .16       0
  4897.2     .12       0  4992.4     .05       0  4998.5     .03       0
  5004.5     .05       0  5990.2     .12       0  6110.9     .05       0
  6434.1     .08       0  6539.2     .05       0
Bank Sta=4965.8,5022.5
XS Rating Curve= 0 ,0
Exp/Cntr=0.3,0.1

Type RM Length L Ch R = 1 ,13218   ,1200,1200,1200
BEGIN DESCRIPTION:
BIG BROWN CREEK 13.0
END DESCRIPTION:
XS GIS Cut Line= 3
      3634520.27     10654262.91      3636673.06     10652578.87
      3639196.77     10647629.04
#Sta/Elev= 30
  3067.5  311.25  3360.5  280.37  3695.5  258.51  4116.4  242.23  4670.8  241.29
  4963.7  244.96  4989.7  234.89  4992.4  234.39  4995.7  234.89  5021.6  243.87
  5477.3  238.81  5624.4  246.32  5804.5  254.14  6375.2  246.42  6411.2  246.89
  6921.5  258.33  7550.5  258.04  8021.9  256.21  8129.9  254.84  9748.7  272.94
  9856.6   276.3 10151.8  285.88 10537.4  311.61 10612.1   317.2 10647.2  319.54
   10720  324.34 10842.9  332.97 11074.9  357.89 11216.2  362.57 11356.8  357.41
#Mann= 20 ,-1 , 0
  3067.5     .12       0  3695.5     .05       0  4670.8     .12       0
  4989.7     .07       0  4995.7     .12       0  5624.4     .05       0
  6375.2     .12       0  6411.2     .05       0  7550.5     .12       0
  8021.9     .16       0  8129.9     .05       0  9748.7     .16       0
  9856.6     .12       0 10151.8     .16       0 10537.4     .05       0
 10612.1     .12       0 10647.2     .16       0   10720     .12       0
 10842.9     .16       0 11216.2     .16       0
Bank Sta=4963.7,5021.6
XS Rating Curve= 0 ,0
Exp/Cntr=0.3,0.1

Type RM Length L Ch R = 1 ,12018   ,1885,1885,1885
BEGIN DESCRIPTION:
BIG BROWN CREEK 12.0
END DESCRIPTION:
XS GIS Cut Line= 3
      3634927.71      10654711.1       3637057.9     10653132.98
      3639847.26     10649307.01
#Sta/Elev= 30
  3069.5  282.92  3072.8  282.92  3300.3  270.15  3677.1  250.47  3697.7  249.33
  3936.5  239.84  4422.8  239.74    4980  243.51  4994.6  237.59  4997.9  233.63
  5000.6  233.13  5003.9  233.63  5015.4  236.01  5023.8  242.05    5030  242.11
  5385.3  241.92  5576.5  242.26  6009.2  255.43  6431.8  252.79  6912.1  259.34
  7219.9  254.69  7551.6  255.23  7875.7  257.42  8110.6  256.93  9473.8     267
 10067.8  275.56 10100.8  278.84 10174.7  278.94 10331.8  286.68 10455.4  291.19
#Mann= 16 ,-1 , 0
  3069.5     .12       0  3072.8     .05       0  3300.3     .12       0
  3677.1     .07       0  3697.7     .12       0  4997.9     .07       0
  5003.9     .12       0  5385.3     .07       0  5576.5     .05       0
  7219.9     .12       0  7551.6     .05       0  7875.7     .12       0
  8110.6     .05       0 10100.8     .16       0 10174.7     .12       0
 10331.8     .16       0
Bank Sta=4980,5030
XS Rating Curve= 0 ,0
Exp/Cntr=0.3,0.1