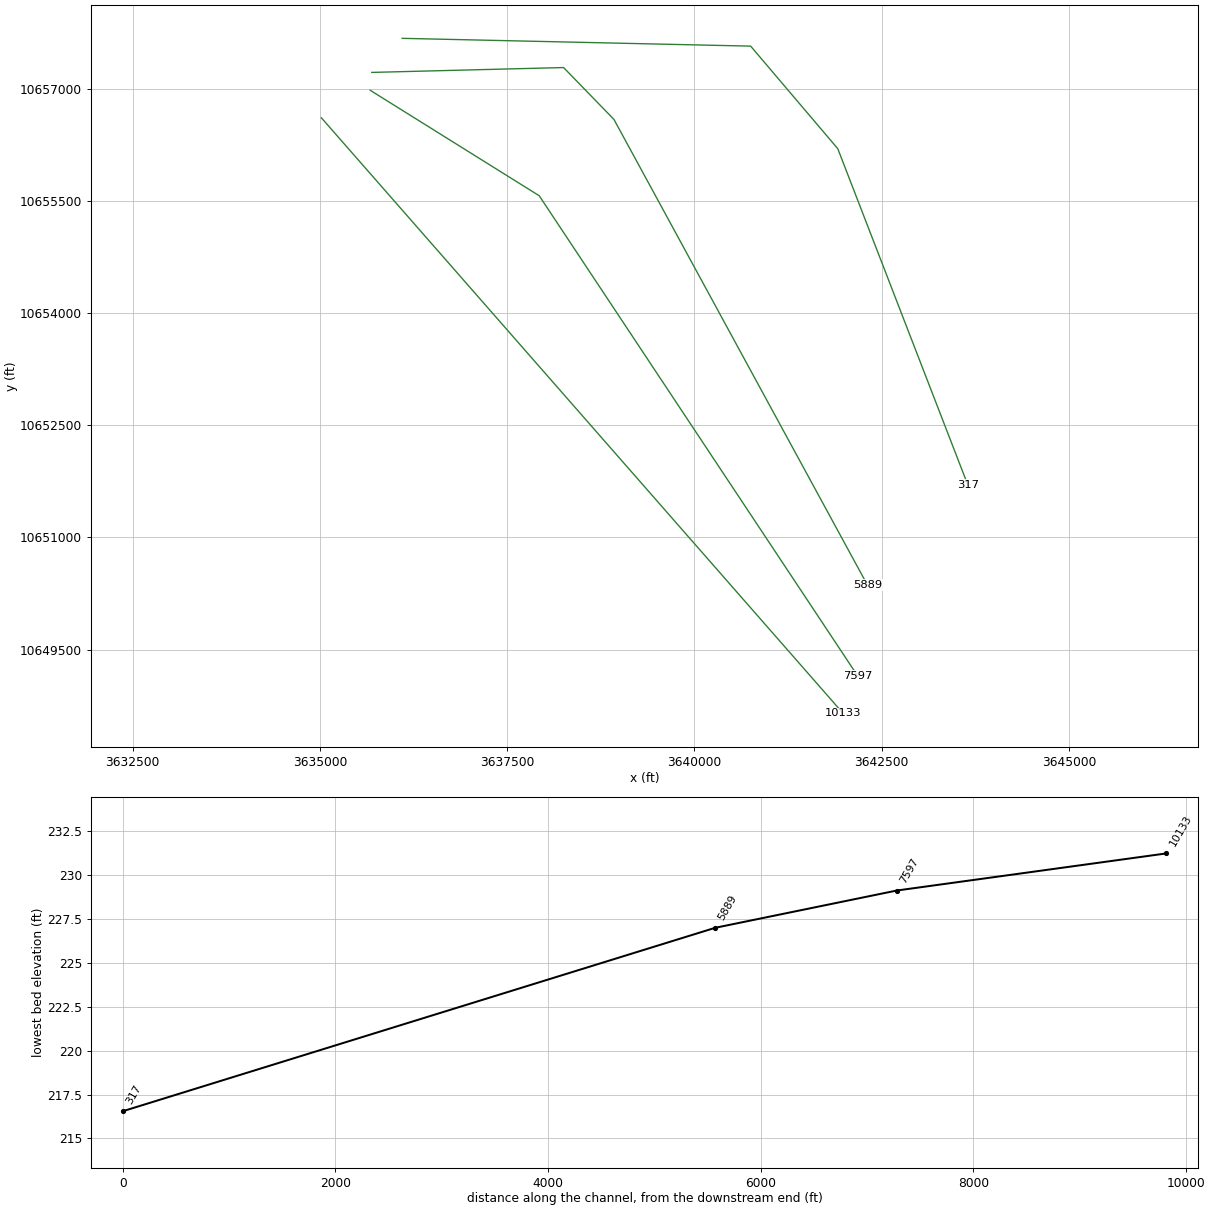
HEC-RAS study BIG BROWN CREEK.prj: BIG BROWN CREEK Base Level Engineering

--- BIG BROWN CREEK.g01 (geometry) --- (continued)

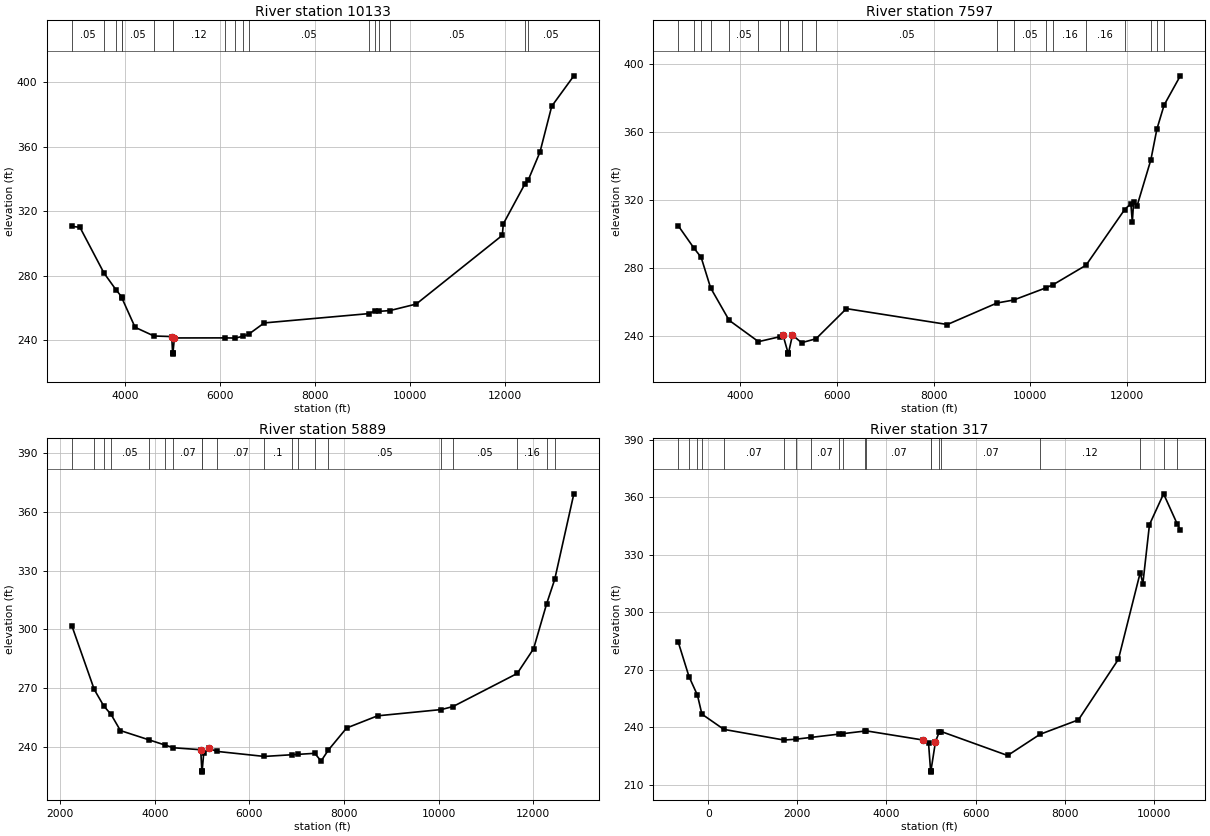
Type RM Length L Ch R = 1 ,10133   ,2536,2536,2536
BEGIN DESCRIPTION:
BIG BROWN CREEK 11.0
END DESCRIPTION:
XS GIS Cut Line= 2
      3635018.51       10656612.      3641984.61     10648647.64
#Sta/Elev= 30
  2871.9  310.51  3044.3   309.9  3549.6  281.58  3800.4  271.28  3922.7  266.76
  3927.9  266.08  4206.1  247.86  4604.9  242.46  4978.7  242.11    4997  231.71
  4999.7  231.21    5003  231.71  5035.6  241.25  6103.1  241.29  6321.6  241.19
    6489  242.38  6596.8  243.48  6927.3  250.57  9136.8  256.36  9270.9  258.24
  9343.3  257.74  9576.6  258.24 10130.6  262.28 11945.4  304.93 11966.3  312.04
 12416.8  336.59 12492.8  339.33 12738.9  356.58 12986.6  385.04 13452.9  403.92
#Mann= 18 ,-1 , 0
  2871.9     .05       0  3549.6     .16       0  3800.4     .05       0
  3922.7     .16       0  3927.9     .05       0  4604.9     .12       0
    4997     .07       0    5003     .12       0  6103.1     .05       0
  6321.6     .07       0    6489     .12       0  6596.8     .05       0
  9136.8     .16       0  9270.9     .12       0  9343.3     .16       0
  9576.6     .05       0 12416.8     .08       0 12492.8     .05       0
Bank Sta=4978.7,5035.6
XS Rating Curve= 0 ,0
Exp/Cntr=0.3,0.1

Type RM Length L Ch R = 1 ,7597    ,1708,1708,1708
BEGIN DESCRIPTION:
BIG BROWN CREEK 9.0
END DESCRIPTION:
XS GIS Cut Line= 3
      3635669.58      10656980.9      3637926.51     10655570.32
      3642179.99      10649146.7
#Sta/Elev= 30
  2729.9  304.86  3056.2  291.57  3202.8  286.23    3398  268.22  3780.5  249.07
  4386.7  236.46  4831.4   239.4  4892.7  240.35  4999.4   229.6  5002.2   229.1
  5005.4   229.6  5088.4  240.35  5274.9  235.84  5573.7  238.15  6202.1  255.94
    8287  246.58  9312.4  259.28  9654.6  261.02 10317.3  268.17 10475.7  270.17
   11149  281.56 11946.8   314.4 12074.7  317.91 12104.9   306.9 12131.9  318.97
 12204.1  316.69 12487.7  343.76 12611.7  361.83 12760.7  376.03 13095.6  393.31
#Mann= 20 ,-1 , 0
  2729.9     .05       0  3056.2      .1       0  3202.8     .05       0
    3398     .16       0  3780.5     .05       0  4386.7     .05       0
  4831.4     .12       0  4999.4     .07       0  5005.4     .12       0
  5274.9     .05       0  5573.7     .05       0  9312.4     .05       0
  9654.6     .05       0 10317.3     .12       0 10475.7     .16       0
   11149     .16       0 11946.8     .12       0 12487.7     .05       0
 12611.7     .16       0 12760.7     .05       0
Bank Sta=4892.7,5088.4
XS Rating Curve= 0 ,0
Exp/Cntr=0.3,0.1

Type RM Length L Ch R = 1 ,5889    ,5572,5572,5572
BEGIN DESCRIPTION:
BIG BROWN CREEK 8.0
END DESCRIPTION:
XS GIS Cut Line= 4
       3635691.3     10657219.62      3638252.03     10657284.73
      3638924.77     10656590.28      3642309.31     10650363.61
#Sta/Elev= 30
  2244.1  301.88  2719.5   269.2  2919.6  260.83    3075  256.46  3272.7  248.21
  3872.3  243.51  4215.2  240.82  4392.6  239.43  4969.8  238.43  4995.1  227.48
  4997.8  226.98  5001.1  227.48  5033.6  236.68  5139.5  239.14  5311.4  237.58
  6314.8     235  6901.3  235.87  7022.8  236.05  7381.5  236.59    7515  232.65
  7671.9  238.33  8054.6  249.52  8709.3  255.75 10059.8  258.96 10304.1  260.48
   11662  277.39 12008.2  290.02 12285.7   313.1 12454.8  325.43 12859.6  369.18
#Mann= 20 ,-1 , 0
  2244.1     .12       0  2719.5     .05       0  2919.6     .16       0
    3075     .05       0  3872.3     .07       0  4215.2     .05       0
  4392.6     .07       0  4995.1     .07       0  5001.1     .12       0
  5311.4     .07       0  6314.8      .1       0  6901.3     .07       0
  7022.8      .1       0  7381.5     .07       0  7671.9     .05       0
 10059.8     .12       0 10304.1     .05       0   11662     .16       0
 12285.7     .05       0 12454.8     .16       0
Bank Sta=4969.8,5139.5
XS Rating Curve= 0 ,0
Exp/Cntr=0.3,0.1

Type RM Length L Ch R = 1 ,317     ,0,0,0
BEGIN DESCRIPTION:
BIG BROWN CREEK 2.0
END DESCRIPTION:
XS GIS Cut Line= 4
      3636097.04     10657675.35      3640749.86     10657571.18
      3641913.05     10656199.66      3643648.77     10651704.15
#Sta/Elev= 30
  -673.9  284.43  -432.8  266.44    -242  256.65  -142.9  246.82   350.5  238.85
  1700.6  233.29  1962.8  233.72  2297.6  234.64  2927.8  236.37  3026.8  236.64
  3513.8  237.97  3550.1  238.07  4810.4  233.35  4945.6  231.61    4992  217.05
  4994.7  216.55    4998  217.05  5101.5  232.48  5185.8  237.51  5229.1  237.74
  6721.2  225.23  7446.7  236.27  8311.1  243.84  9208.1  275.45    9698  320.72
  9756.6  314.88  9904.9   345.7 10221.7  361.78 10531.1  345.89 10597.4  343.03
#Mann= 20 ,-1 , 0
  -673.9     .05       0  -432.8      .1       0    -242     .15       0
  -142.9     .05       0   350.5     .07       0  1700.6     .05       0
  1962.8     .07       0  2297.6     .07       0  2927.8     .05       0
  3026.8     .12       0  3513.8     .05       0  3550.1     .07       0
    4992     .07       0    4998     .07       0  5185.8     .12       0
  5229.1     .07       0  7446.7     .12       0    9698     .16       0
 10221.7     .05       0 10531.1     .16       0
Bank Sta=4810.4,5101.5
XS Rating Curve= 0 ,0
Exp/Cntr=0.3,0.1

Chan Stop Cuts=-1
Use User Specified Reach Order=0
Composite Channel Slope=5