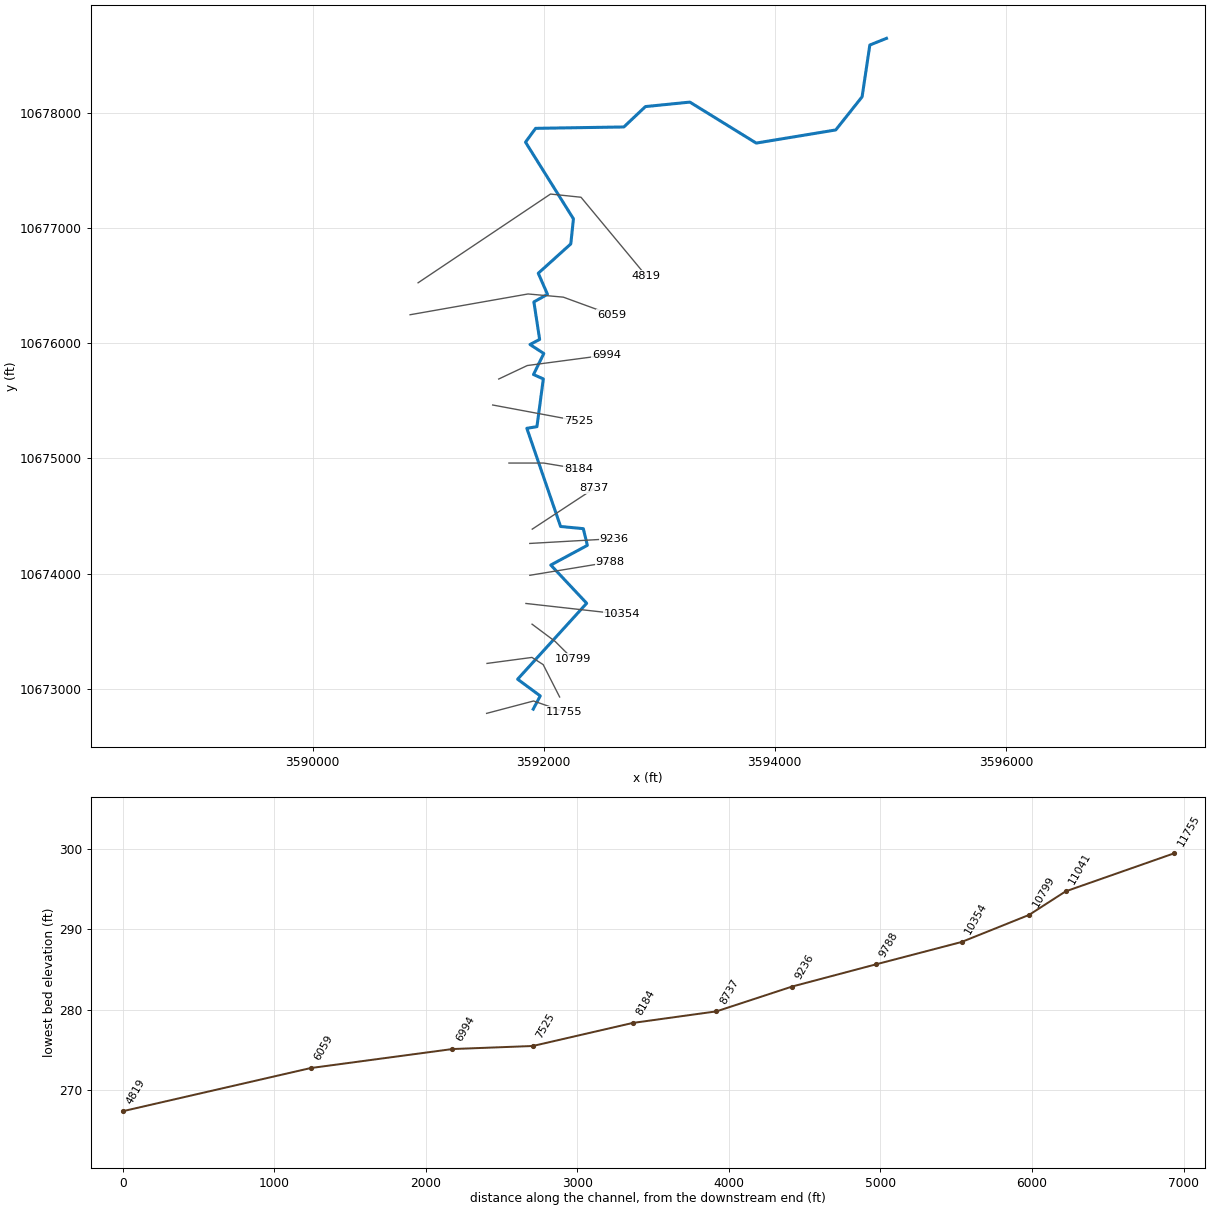
--- CAMPHOUSE DUGOUT.prj (project) ---

Proj Title=CAMPHOUSE DUGOUT Base Level Engineering
Current Plan=p01
Default Exp/Contr=0.3,0.1
English Units
Geom File=g01
Flow File=f01
Plan File=p01
BEGIN DESCRIPTION:
CAMPHOUSE DUGOUT
END DESCRIPTION:

--- CAMPHOUSE DUGOUT.p01 (plan) ---

Plan Title=Multiple Run
Short Identifier=Multiple
Geom File=g01
Flow File=f01
Subcritical Flow
K Sum by GR= 0
Std Step Tol= 0.01
Critical Tol= 0.01
Num of Std Step Trials= 20
Max Error Tol= 0.3
Flow Tol Ratio= 0.001
Split Flow NTrial= 30
Split Flow Tol= 0.02
Split Flow Ratio= 0.02
Log Output Level= 0
Friction Slope Method= 1
Unsteady Friction Slope Method= 2
Unsteady Bridges Friction Slope Method= 1
Parabolic Critical Depth
Global Vel Dist=  1 , 1 , 1
Global Log Level= 0
CheckData=True
Encroach Param= -1, 0, 0, 0
BEGIN DESCRIPTION:
Multiple Run
END DESCRIPTION:

--- CAMPHOUSE DUGOUT.f01 (steady flow) ---

Flow Title=Multiple
Number of Profiles=7
Profile Names=10-year,25-year,50-year,1pct_min,100-year,1pct_plu,500-year
River Rch & RM= CAMPHOUSE DUGOUT,Reach-1,11755
    1367    1875    2292    2044    2764    3738    4007
Boundary for River Rch & Prof#=CAMPHOUSE DUGOUT,Reach-1,1
Up Type=0
Dn Type=3
Dn Slope=0.005
Boundary for River Rch & Prof#=CAMPHOUSE DUGOUT,Reach-1,2
Up Type=0
Dn Type=3
Dn Slope=0.005
Boundary for River Rch & Prof#=CAMPHOUSE DUGOUT,Reach-1,3
Up Type=0
Dn Type=3
Dn Slope=0.005
Boundary for River Rch & Prof#=CAMPHOUSE DUGOUT,Reach-1,4
Up Type=0
Dn Type=3
Dn Slope=0.005
Boundary for River Rch & Prof#=CAMPHOUSE DUGOUT,Reach-1,5
Up Type=0
Dn Type=3
Dn Slope=0.005
Boundary for River Rch & Prof#=CAMPHOUSE DUGOUT,Reach-1,6
Up Type=0
Dn Type=3
Dn Slope=0.005
Boundary for River Rch & Prof#=CAMPHOUSE DUGOUT,Reach-1,7
Up Type=0
Dn Type=3
Dn Slope=0.005

--- CAMPHOUSE DUGOUT.g01 (geometry) ---

Geom Title=Existing Conditions

River Reach=CAMPHOUSE DUGOUT,Reach-1
Reach XY= 30
      3591909.75     10672822.00      3591970.50     10672937.00
      3591774.75     10673082.00      3592372.25     10673742.00
      3592061.75     10674074.00      3592378.25     10674245.00
      3592343.25     10674390.00      3592146.50     10674409.00
      3591854.50     10675262.00      3591941.75     10675276.00
      3591997.25     10675691.00      3591912.25     10675729.00
      3592001.25     10675912.00      3591881.75     10675990.00
      3591965.25     10676034.00      3591915.50     10676360.00
      3592033.25     10676426.00      3591953.50     10676609.00
      3592235.00     10676864.00      3592257.75     10677082.00
      3591843.00     10677748.00      3591930.50     10677868.00
      3592694.25     10677880.00      3592880.75     10678057.00
      3593265.25     10678096.00      3593839.50     10677740.00
      3594528.00     10677854.00      3594756.00     10678142.00
      3594823.00     10678592.00      3594967.25     10678650.00

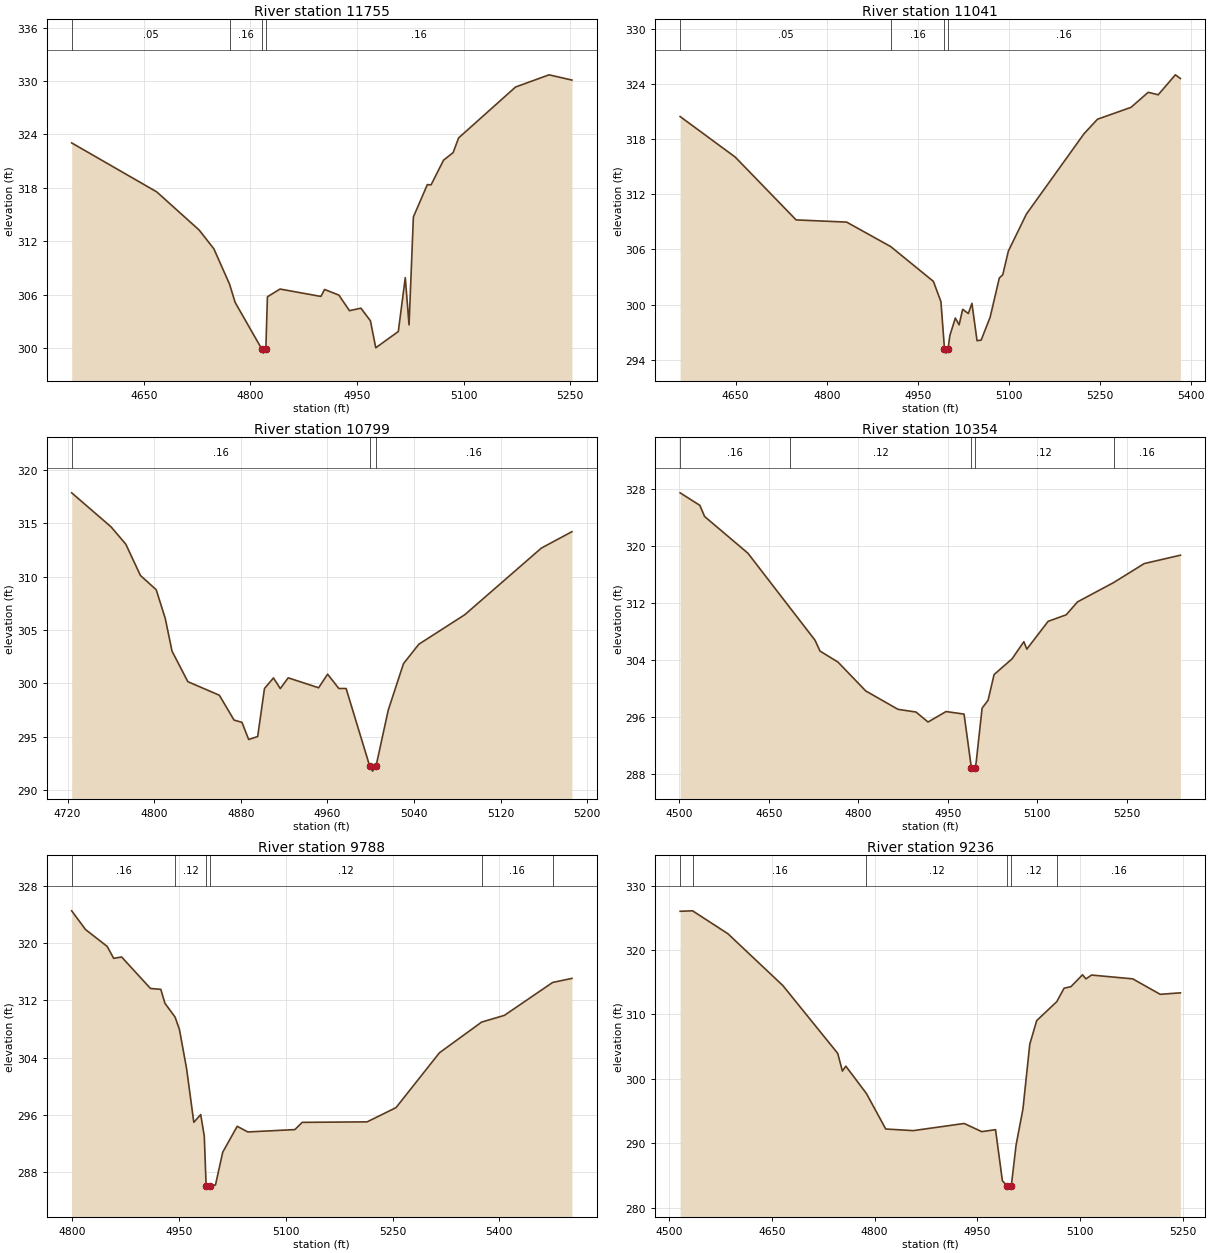
Type RM Length L Ch R = 1,11755,714,714,714
BEGIN DESCRIPTION:
CAMPHOUSE DUGOUT 13.0
END DESCRIPTION:
XS GIS Cut Line= 3
      3591506.38     10672785.25      3591912.61     10672892.88
      3592180.01     10672799.12
#Sta/Elev= 30
  4548.7  323.04  4668.3  317.54  4727.9  313.26  4748.7  311.14  4770.7  307.18
  4778.6  305.12  4815.8  299.92  4818.6  299.42  4821.8  299.92  4824.0  305.75
  4841.7  306.62  4899.2  305.79  4904.4  306.57  4924.5  305.94  4939.4  304.19
  4955.5  304.47  4968.9  303.05  4976.4  300.02  5008.1  301.85  5017.9  307.90
  5023.2  302.59  5029.3  314.72  5048.9  318.35  5054.2  318.33  5071.7  321.10
  5085.2  321.95  5092.9  323.60  5173.0  329.32  5220.1  330.69  5252.3  330.10
#Mann=4,-1,0
  4548.7    0.05       0  4770.7    0.16       0  4815.8    0.07       0
  4821.8    0.16       0
Bank Sta=4815.8,4821.8
Exp/Cntr=0.3,0.1

Type RM Length L Ch R = 1,11041,242,242,242
BEGIN DESCRIPTION:
CAMPHOUSE DUGOUT 12.0
END DESCRIPTION:
XS GIS Cut Line= 4
      3591509.86     10673219.27      3591898.72     10673271.35
      3591995.94     10673208.85      3592138.28     10672927.64
#Sta/Elev= 30
  4558.8  320.46  4649.4  316.05  4749.6  309.21  4832.7  308.97  4905.2  306.31
  4975.5  302.52  4987.9  300.31  4993.7  295.21  4996.4  294.71  4999.7  295.21
  5002.6  296.63  5011.6  298.53  5017.8  297.79  5023.7  299.48  5033.0  299.02
  5038.9  300.13  5047.3  296.06  5054.1  296.13  5068.8  298.61  5084.0  302.89
  5089.6  303.24  5098.8  305.81  5128.5  309.84  5223.2  318.58  5245.5  320.17
  5300.6  321.46  5329.0  323.10  5345.4  322.83  5373.6  325.00  5381.9  324.60
#Mann=4,-1,0
  4558.8    0.05       0  4905.2    0.16       0  4993.7    0.07       0
  4999.7    0.16       0
Bank Sta=4993.7,4999.7
Exp/Cntr=0.3,0.1

Type RM Length L Ch R = 1,10799,445,445,445
BEGIN DESCRIPTION:
CAMPHOUSE DUGOUT 11.0
END DESCRIPTION:
XS GIS Cut Line= 3
      3591899.64     10673560.17      3592099.61     10673410.19
      3592249.61     10673260.19
#Sta/Elev= 30
  4723.8  317.85  4760.2  314.66  4773.8  313.04  4787.3  310.11  4801.9  308.77
  4810.2  306.10  4816.5  303.02  4831.1  300.16  4860.2  298.89  4873.8  296.56
  4881.1  296.35  4887.3  294.74  4895.6  295.02  4901.9  299.52  4910.2  300.51
  4916.5  299.51  4923.8  300.52  4951.9  299.59  4960.2  300.86  4970.6  299.52
  4977.3  299.52  4999.0  292.28  5001.8  291.78  5005.0  292.28  5016.2  297.49
  5030.3  301.85  5044.5  303.67  5086.9  306.43  5157.6  312.67  5185.9  314.21
#Mann=3,-1,0
  4723.8    0.16       0  4999.0    0.07       0  5005.0    0.16       0
Bank Sta=4999,5005
Exp/Cntr=0.3,0.1

Type RM Length L Ch R = 1,10354,566,566,566
BEGIN DESCRIPTION:
CAMPHOUSE DUGOUT 10.0
END DESCRIPTION:
XS GIS Cut Line= 2
      3591846.68     10673740.10      3592679.92     10673646.36
#Sta/Elev= 30
  4501.4  327.47  4534.5  325.71  4542.4  324.15  4615.0  319.00  4685.8  311.31
  4727.5  306.79  4735.8  305.27  4766.0  303.72  4812.5  299.67  4866.6  297.09
  4896.8  296.71  4916.9  295.31  4947.1  296.78  4977.3  296.42  4989.5  288.92
  4992.2  288.42  4995.5  288.92  4997.5  289.58  5007.5  297.25  5017.6  298.38
  5027.6  301.97  5057.8  304.18  5077.5  306.58  5082.5  305.54  5118.2  309.44
  5148.4  310.35  5167.5  312.17  5228.0  314.88  5279.2  317.54  5339.9  318.72
#Mann=5,-1,0
  4501.4    0.16       0  4685.8    0.12       0  4989.5    0.07       0
  4995.5    0.12       0  5228.0    0.16       0
Bank Sta=4989.5,4995.5
Exp/Cntr=0.3,0.1

Type RM Length L Ch R = 1,9788,552,552,552
BEGIN DESCRIPTION:
CAMPHOUSE DUGOUT 9.0
END DESCRIPTION:
XS GIS Cut Line= 2
      3591880.47     10673984.89      3592573.16     10674099.47
#Sta/Elev= 30
  4799.7  324.53  4819.1  321.92  4849.5  319.56  4858.7  317.89  4869.8  318.08
  4910.3  313.68  4924.8  313.56  4930.6  311.61  4944.9  309.67  4950.9  307.96
  4961.0  302.47  4971.1  294.98  4980.8  296.06  4985.8  293.04  4988.4  286.14
  4991.2  285.64  4994.4  286.14  5001.5  286.21  5011.7  290.80  5032.0  294.42
  5046.9  293.63  5113.0  293.96  5123.2  294.97  5214.4  295.04  5254.9  297.03
  5315.8  304.69  5375.0  308.98  5407.0  309.92  5474.7  314.52  5501.8  315.09
#Mann=6,-1,0
  4799.7    0.16       0  4944.9    0.12       0  4988.4    0.07       0
  4994.4    0.12       0  5375.0    0.16       0  5474.7    0.12       0
Bank Sta=4988.4,4994.4
Exp/Cntr=0.3,0.1

Type RM Length L Ch R = 1,9236,499,499,499
BEGIN DESCRIPTION:
CAMPHOUSE DUGOUT 8.0
END DESCRIPTION:
XS GIS Cut Line= 2
      3591879.90     10674261.57      3592609.11     10674303.24
#Sta/Elev= 30
  4516.2  326.02  4534.4  326.09  4586.0  322.53  4666.2  314.49  4746.3  303.96
  4753.1  301.22  4758.1  301.98  4788.2  297.73  4816.4  292.22  4856.5  291.97
  4930.9  293.08  4956.6  291.81  4976.7  292.12  4986.7  284.18  4993.7  283.39
  4996.4  282.89  4999.7  283.39  5006.7  289.74  5016.7  295.32  5026.7  305.39
  5036.8  309.05  5066.1  311.99  5076.8  314.08  5086.8  314.32  5103.7  316.16
  5108.7  315.53  5116.9  316.12  5177.0  315.53  5217.1  313.13  5246.6  313.36
#Mann=6,-1,0
  4516.2    0.12       0  4534.4    0.16       0  4788.2    0.12       0
  4993.7    0.07       0  4999.7    0.12       0  5066.1    0.16       0
Bank Sta=4993.7,4999.7
Exp/Cntr=0.3,0.1

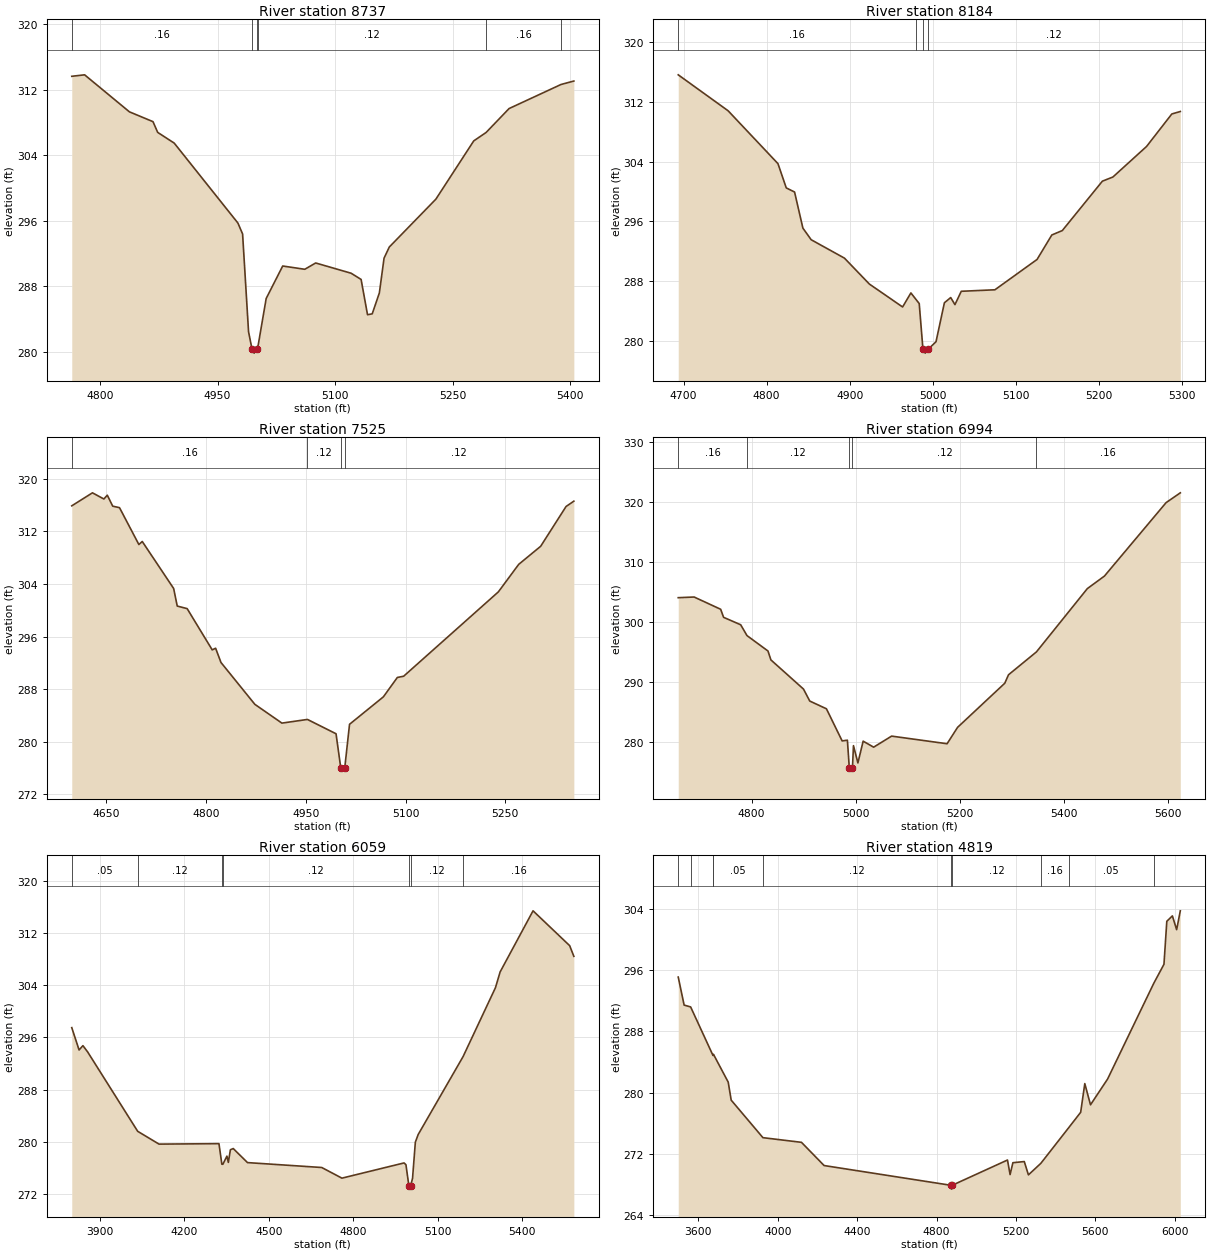
Type RM Length L Ch R = 1,8737,553,553,553
BEGIN DESCRIPTION:
CAMPHOUSE DUGOUT 7.0
END DESCRIPTION:
XS GIS Cut Line= 2
      3591901.30     10674385.92      3592436.23     10674739.08
#Sta/Elev= 30
  4763.9  313.62  4780.3  313.80  4837.5  309.28  4867.6  308.08  4873.6  306.77
  4894.7  305.46  4976.0  295.70  4982.0  294.36  4989.6  282.42  4994.0  280.31
  4996.8  279.81  5000.0  280.31  5001.9  280.78  5012.1  286.48  5033.2  290.45
  5061.4  290.05  5075.3  290.82  5120.5  289.57  5133.3  288.81  5141.5  284.50
  5147.5  284.61  5156.6  287.16  5162.6  291.41  5169.3  292.77  5228.8  298.62
  5277.1  305.73  5292.9  306.76  5322.2  309.68  5388.5  312.62  5404.9  313.04
#Mann=6,-1,0
  4763.9    0.16       0  4994.0    0.07       0  5000.0    0.16       0
  5001.9    0.12       0  5292.9    0.16       0  5388.5    0.12       0
Bank Sta=4994,5000
Exp/Cntr=0.3,0.1

Type RM Length L Ch R = 1,8184,659,659,659
BEGIN DESCRIPTION:
CAMPHOUSE DUGOUT 6.0
END DESCRIPTION:
XS GIS Cut Line= 3
      3591699.58     10674960.19      3591999.61     10674960.19
      3592299.65     10674910.18
#Sta/Elev= 30
  4693.6  315.63  4753.6  310.82  4813.6  303.74  4823.6  300.49  4833.6  299.94
  4843.6  295.11  4853.6  293.55  4893.6  291.09  4923.6  287.62  4963.6  284.55
  4973.6  286.43  4979.2  285.63  4983.6  285.01  4988.1  278.87  4990.9  278.37
  4994.1  278.87  5003.8  279.89  5013.9  285.11  5021.5  285.81  5026.6  284.86
  5034.2  286.65  5074.7  286.85  5125.4  290.91  5143.2  294.19  5155.8  294.78
  5204.0  301.39  5216.7  301.95  5257.2  306.04  5287.6  310.39  5297.8  310.72
#Mann=4,-1,0
  4693.6    0.16       0  4979.2    0.12       0  4988.1    0.07       0
  4994.1    0.12       0
Bank Sta=4988.1,4994.1
Exp/Cntr=0.3,0.1

Type RM Length L Ch R = 1,7525,531,531,531
BEGIN DESCRIPTION:
CAMPHOUSE DUGOUT 4.0
END DESCRIPTION:
XS GIS Cut Line= 2
      3591559.02     10675464.42      3592301.14     10675325.54
#Sta/Elev= 30
  4598.0  315.90  4629.1  317.88  4646.3  316.94  4651.4  317.52  4659.6  315.85
  4669.8  315.62  4698.9  310.01  4704.0  310.47  4751.2  303.32  4756.6  300.64
  4771.5  300.25  4809.2  293.97  4814.3  294.22  4822.4  292.05  4873.3  285.68
  4914.0  282.82  4952.4  283.38  4995.4  281.20  5002.5  276.01  5005.3  275.51
  5008.5  276.01  5015.7  282.64  5066.6  286.82  5087.6  289.77  5097.1  289.96
  5239.5  302.80  5270.1  306.99  5303.1  309.74  5341.3  315.80  5353.0  316.61
#Mann=4,-1,0
  4598.0    0.16       0  4952.4    0.12       0  5002.5    0.07       0
  5008.5    0.12       0
Bank Sta=5002.5,5008.5
Exp/Cntr=0.3,0.1

Type RM Length L Ch R = 1,6994,935,935,935
BEGIN DESCRIPTION:
CAMPHOUSE DUGOUT 3.0
END DESCRIPTION:
XS GIS Cut Line= 3
      3591611.07     10675690.12      3591858.47     10675807.30
      3592544.19     10675898.45
#Sta/Elev= 30
  4659.1  304.01  4689.7  304.12  4740.7  302.08  4746.3  300.74  4779.2  299.50
  4791.3  297.70  4831.7  295.13  4837.3  293.65  4900.0  288.79  4912.0  286.80
  4944.1  285.51  4974.3  280.16  4984.4  280.28  4988.1  275.63  4990.8  275.13
  4994.1  275.63  4996.1  279.37  5004.6  276.49  5014.7  280.12  5034.9  279.12
  5069.4  280.96  5176.1  279.69  5196.3  282.42  5287.1  289.77  5294.2  291.17
  5347.9  294.98  5445.8  305.52  5478.7  307.61  5597.3  319.84  5624.6  321.47
#Mann=5,-1,0
  4659.1    0.16       0  4791.3    0.12       0  4988.1    0.07       0
  4994.1    0.12       0  5347.9    0.16       0
Bank Sta=4988.1,4994.1
Exp/Cntr=0.3,0.1

Type RM Length L Ch R = 1,6059,1240,1240,1240
BEGIN DESCRIPTION:
CAMPHOUSE DUGOUT 2.0
END DESCRIPTION:
XS GIS Cut Line= 4
      3590843.98     10676248.56      3591864.83     10676429.12
      3592170.39     10676401.34      3592585.82     10676249.02
#Sta/Elev= 30
  3799.0  297.49  3825.0  294.07  3838.7  294.73  3855.5  293.77  4033.5  281.62
  4109.4  279.66  4322.6  279.73  4332.9  276.58  4336.6  276.58  4350.9  277.82
  4356.0  276.86  4363.3  278.80  4373.4  278.98  4424.2  276.83  4688.2  276.08
  4760.0  274.45  4981.1  276.78  4987.8  276.50  4998.2  273.27  5000.9  272.77
  5004.2  273.27  5011.2  274.41  5021.2  279.96  5031.3  281.13  5190.9  293.05
  5306.2  303.61  5322.8  306.02  5439.9  315.37  5570.1  310.04  5585.0  308.41
#Mann=7,-1,0
  3799.0    0.05       0  4033.5    0.12       0  4332.9    0.07       0
  4336.6    0.12       0  4998.2    0.07       0  5004.2    0.12       0
  5190.9    0.16       0
Bank Sta=4998.2,5004.2
Exp/Cntr=0.3,0.1

Type RM Length L Ch R = 1,4819,0,0,0
BEGIN DESCRIPTION:
CAMPHOUSE DUGOUT 1.0
END DESCRIPTION:
XS GIS Cut Line= 4
      3590913.41     10676526.32      3592059.28     10677297.18
      3592323.17     10677269.40      3592885.16     10676589.46
#Sta/Elev= 30
  3499.0  295.10  3528.7  291.44  3561.5  291.20  3674.0  284.87  3676.5  285.01
  3750.7  281.38  3765.7  279.03  3925.5  274.13  4119.6  273.52  4233.6  270.49
  4872.4  267.91  4875.2  267.41  4878.4  267.91  5157.1  271.21  5170.3  269.31
  5184.4  270.86  5241.7  271.01  5262.6  269.27  5325.2  270.78  5464.8  275.41
  5525.7  277.44  5546.5  281.19  5575.2  278.42  5661.2  281.78  5894.1  294.30
  5945.2  296.77  5959.5  302.38  5987.6  303.09  6009.0  301.29  6027.5  303.75
#Mann=10,-1,0
  3499.0    0.16       0  3561.5    0.12       0  3674.0    0.16       0
  3676.5    0.05       0  3925.5    0.12       0  4872.4    0.07       0
  4878.4    0.12       0  5325.2    0.16       0  5464.8    0.05       0
  5894.1    0.16       0
Bank Sta=4872.4,4878.4
Exp/Cntr=0.3,0.1

Chan Stop Cuts=-1