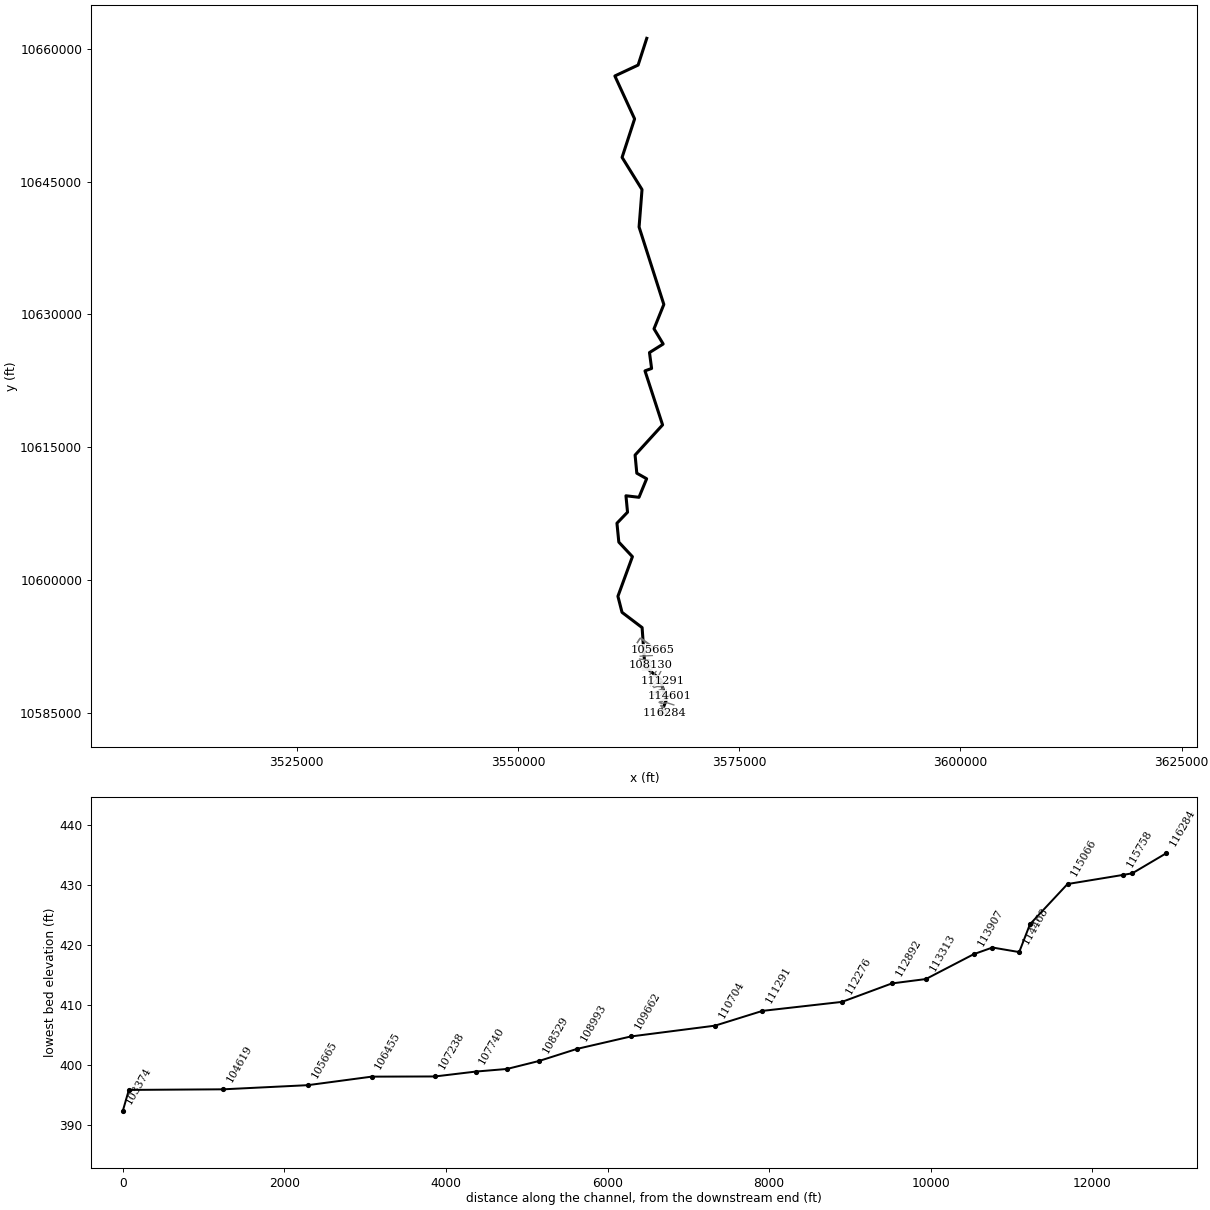
--- CANEY CREEK.prj (project) ---

Proj Title=CANEY CREEK Base Level Engineering
Current Plan=p01
Default Exp/Contr=0.3,0.1
English Units
Geom File=g01
Flow File=f01
Plan File=p01
Y Axis Title=Elevation
X Axis Title(PF)=Main Channel Distance
X Axis Title(XS)=Station
BEGIN DESCRIPTION:
CANEY CREEK
END DESCRIPTION:
DSS File=dss
DSS Export Rating Curves= 0
DSS Export Rating Curve Sorted= 0
DSS Export Volume Flow Curves= 0
DXF OffsetX= 0
DXF OffsetY= 0
DXF ScaleX= 1
DXF ScaleY= 10

--- CANEY CREEK.p01 (plan) ---

Plan Title=Multiple Run
Program Version=4.10
Short Identifier=Multiple Run
Geom File=g01
Flow File=f01
Subcritical Flow
K Sum by GR= 0
Std Step Tol= 0.01
Critical Tol= 0.01
Num of Std Step Trials= 20
Max Error Tol= 0.3
Flow Tol Ratio= 0.001
Split Flow NTrial= 30
Split Flow Tol= 0.02
Split Flow Ratio= 0.02
Log Output Level= 0
Friction Slope Method= 1
Unsteady Friction Slope Method= 2
Unsteady Bridges Friction Slope Method= 1
Parabolic Critical Depth
Global Vel Dist= 1 , 1 , 1
Global Log Level= 0
CheckData=True
Encroach Param=-1 ,0,0, 0
BEGIN DESCRIPTION:
Multiple Run
END DESCRIPTION:
Computation Interval=1HOUR
Output Interval=1HOUR
Run HTab= 0
Run UNet= 0
Run PostProcess= 0
Run WQNet= 0
UNET Theta= 1
UNET Theta Warmup= 1
UNET ZTol= 0.02
UNET ZSATol= 0.05
UNET MxIter= 20
UNET MaxInSteps= 0
UNET DtIC= 0
UNET DtMin= 0
UNET MaxCRTS= 20
UNET WFStab= 2
UNET SFStab= 1
UNET WFX= 1
UNET SFX= 1
UNET DSS MLevel= 4
UNET DZMax Abort= 100
UNET Convert EG Bridges= 0
UNET Use Existing IB Tables=-1
UNET Froude Reduction=False
UNET Froude Limit= 1
UNET Froude Power= 10
UNET Time Slicing=0,0, 5
UNET Junction Losses=0
Instantaneous Interval=1HOUR
DSS File=dss
Write IC File= 0
Write IC File at Sim End=0
Echo Input=False
Echo Parameters=False
Echo Output=False
Write Detailed= 0
WQ AD Non Conservative
WQ ULTIMATE=-1
WQ Max Comp Step=1HOUR
WQ Output Interval=15MIN
WQ Output Selected Increments= 0
WQ Output face flow=0
WQ Output face velocity=0
WQ Output face area=0
WQ Output face dispersion=0
WQ Output cell volume=0
WQ Output cell surface area=0
WQ Output cell continuity=0
WQ Output cumulative cell continuity=0
WQ Output face conc=0
WQ Output face dconc_dx=0
WQ Output face courant=0
WQ Output face peclet=0
WQ Output face adv mass=0
WQ Output face disp mass=0
WQ Output cell mass=0
WQ Output cell source sink temp=0
WQ Output cell source sink nsm=0
WQ Output MaxMinRange=-1
WQ Daily Max Min Mean=-1
WQ Daily Range=0
WQ Daily Time=0
WQ Create Restart=0
WQ Fixed Restart=0
WQ System Summary=0
WQ Use Fixed Temperature=0
Sorting and Armoring Iterations= 10
XS Update Threshold= 0.02
Hydraulics Update Threshold= 0.02
Energy Slope Method= 1
Volume Change Method= 0
XS Weighting Method= 0
Number of US Weighted Cross Sections= 1
Number of DS Weighted Cross Sections= 1
Upstream XS Weight=0.25
Main XS Weight=0.5
Downstream XS Weight=0.25
Number of DS XS's Weighted with US Boundary= 1
Upstream Boundary Weight= 1
Weight of XSs Associated with US Boundary= 0
Number of US XS's Weighted with DS Boundary= 1
Downstream Boundary Weight= 0.5
Weight of XSs Associated with DS Boundary= 0.5
Sediment Output Level= 4
Mass or Volume Output= 0
Output Increment Type= 1
Profile and TS Output Increment= 10
XS Output Flag= 0
XS Output Increment= 10
Disregard all LS=0
Disregard all Conn=0
Disregard all Breaches=0
Disregard all Pumps=0

--- CANEY CREEK.f01 (steady flow) ---

Flow Title=Multiple
Program Version=4.10
Number of Profiles= 7
Profile Names=10-year,25-year,50-year,1pct_min,100-year,1pct_plu,500-year
River Rch & RM=CANEY CREEK,Reach-1         ,116284
    2493    3543    4438    4051    5478    7408    8322
River Rch & RM=CANEY CREEK,Reach-1         ,112892
    2762    3936    4938    4512    6102    8252    9291
River Rch & RM=CANEY CREEK,Reach-1         ,108529
    4476    6507    8275    7649   10345   13990   16129
River Rch & RM=CANEY CREEK,Reach-1         ,102728
    5781    8484   10858   10092   13649   18458   21518
River Rch & RM=CANEY CREEK,Reach-1         ,101774
    5781    8484   10858   10092   13649   18458   21518
River Rch & RM=CANEY CREEK,Reach-1         ,99860
    5904    8640   11036   10234   13841   18718   21721
River Rch & RM=CANEY CREEK,Reach-1         ,94876
    7776   11499   14792   13806   18671   25250   29678
River Rch & RM=CANEY CREEK,Reach-1         ,92856
    7776   11499   14792   13806   18671   25250   29678
River Rch & RM=CANEY CREEK,Reach-1         ,91782
    7776   11499   14792   13806   18671   25250   29678
River Rch & RM=CANEY CREEK,Reach-1         ,84602
    8088   11878   15206   14116   19090   25816   30012
River Rch & RM=CANEY CREEK,Reach-1         ,79274
    8156   11930   15229   14116   19090   25816   30012
River Rch & RM=CANEY CREEK,Reach-1         ,75416
    8156   11930   15229   14116   19090   25816   30012
River Rch & RM=CANEY CREEK,Reach-1         ,68201
   14875   22124   28576   26725   36142   48878   57637
River Rch & RM=CANEY CREEK,Reach-1         ,66803
   14875   22124   28576   26725   36142   48878   57637
River Rch & RM=CANEY CREEK,Reach-1         ,65962
   14875   22124   28576   26725   36142   48878   57637
River Rch & RM=CANEY CREEK,Reach-1         ,65245
   14875   22124   28576   26725   36142   48878   57637
River Rch & RM=CANEY CREEK,Reach-1         ,62790
   14875   22124   28576   26725   36142   48878   57637
River Rch & RM=CANEY CREEK,Reach-1         ,60942
   14875   22124   28576   26725   36142   48878   57637
River Rch & RM=CANEY CREEK,Reach-1         ,57109
   14875   22124   28576   26725   36142   48878   57637
River Rch & RM=CANEY CREEK,Reach-1         ,56128
   14875   22124   28576   26725   36142   48878   57637
River Rch & RM=CANEY CREEK,Reach-1         ,46983
   14897   22124   28576   26725   36142   48878   57637
River Rch & RM=CANEY CREEK,Reach-1         ,44193
   15523   23009   29648   27655   37400   50579   59319
River Rch & RM=CANEY CREEK,Reach-1         ,43624
   15523   23009   29648   27655   37400   50579   59319
River Rch & RM=CANEY CREEK,Reach-1         ,40034
   15523   23009   29648   27655   37400   50579   59319
River Rch & RM=CANEY CREEK,Reach-1         ,39304
   18229   27076   34944   32634   44133   59685   70155
River Rch & RM=CANEY CREEK,Reach-1         ,35803
   18229   27076   34944   32634   44133   59685   70155
River Rch & RM=CANEY CREEK,Reach-1         ,31807
   19336   28784   37205   34799   47062   63645   75034
River Rch & RM=CANEY CREEK,Reach-1         ,29672
   19336   28784   37205   34799   47062   63645   75034
River Rch & RM=CANEY CREEK,Reach-1         ,28372
   19375   28807   37205   34799   47062   63645   75034
River Rch & RM=CANEY CREEK,Reach-1         ,22646
   19910   29599   38225   35716   48301   65322   76846
River Rch & RM=CANEY CREEK,Reach-1         ,20295
   19910   29599   38225   35716   48301   65322   76846
River Rch & RM=CANEY CREEK,Reach-1         ,16006
   19910   29599   38225   35716   48301   65322   76846
River Rch & RM=CANEY CREEK,Reach-1         ,14454
   19910   29599   38225   35716   48301   65322   76846
Boundary for River Rch & Prof#=CANEY CREEK,Reach-1         , 1
Up Type= 0
Dn Type= 3
Dn Slope=0.0013
Boundary for River Rch & Prof#=CANEY CREEK,Reach-1         , 2
Up Type= 0
Dn Type= 3
Dn Slope=0.0013
Boundary for River Rch & Prof#=CANEY CREEK,Reach-1         , 3
Up Type= 0
Dn Type= 3
Dn Slope=0.0013
Boundary for River Rch & Prof#=CANEY CREEK,Reach-1         , 4
Up Type= 0
Dn Type= 3
Dn Slope=0.0013
Boundary for River Rch & Prof#=CANEY CREEK,Reach-1         , 5
Up Type= 0
Dn Type= 3
Dn Slope=0.0013
Boundary for River Rch & Prof#=CANEY CREEK,Reach-1         , 6
Up Type= 0
Dn Type= 3
Dn Slope=0.0013
Boundary for River Rch & Prof#=CANEY CREEK,Reach-1         , 7
Up Type= 0
Dn Type= 3
Dn Slope=0.0013
DSS Import GetInterval= 0
DSS Import GetPeak= 0
DSS Import FillOption= 0

--- CANEY CREEK.g01 (geometry) ---

Geom Title=Existing Conditions
Program Version=4.10

River Reach=CANEY CREEK     ,Reach-1
Reach XY= 30
       3566169.5       10584930.       3566749.5       10586373.
      3566114.25       10588723.      3564343.25       10590222.
        3564034.       10594603.      3561764.25       10596327.
      3561300.75       10598140.      3562939.75       10602616.
        3561403.       10604261.       3561191.5       10606395.
        3562387.       10607641.      3562208.75       10609496.
      3563682.25       10609324.      3564546.75       10611421.
      3563434.75       10612048.      3563241.75       10614095.
        3566347.       10617504.      3564358.75       10623610.
       3565107.5       10623881.       3564867.5       10625677.
      3566416.25       10626646.      3565379.25       10628362.
       3566489.5       10631114.      3563691.75       10639862.
      3564024.25       10644093.      3561772.25       10647731.
       3563186.5       10652079.        3560955.       10656929.
      3563582.25       10658160.       3564559.5       10661181.

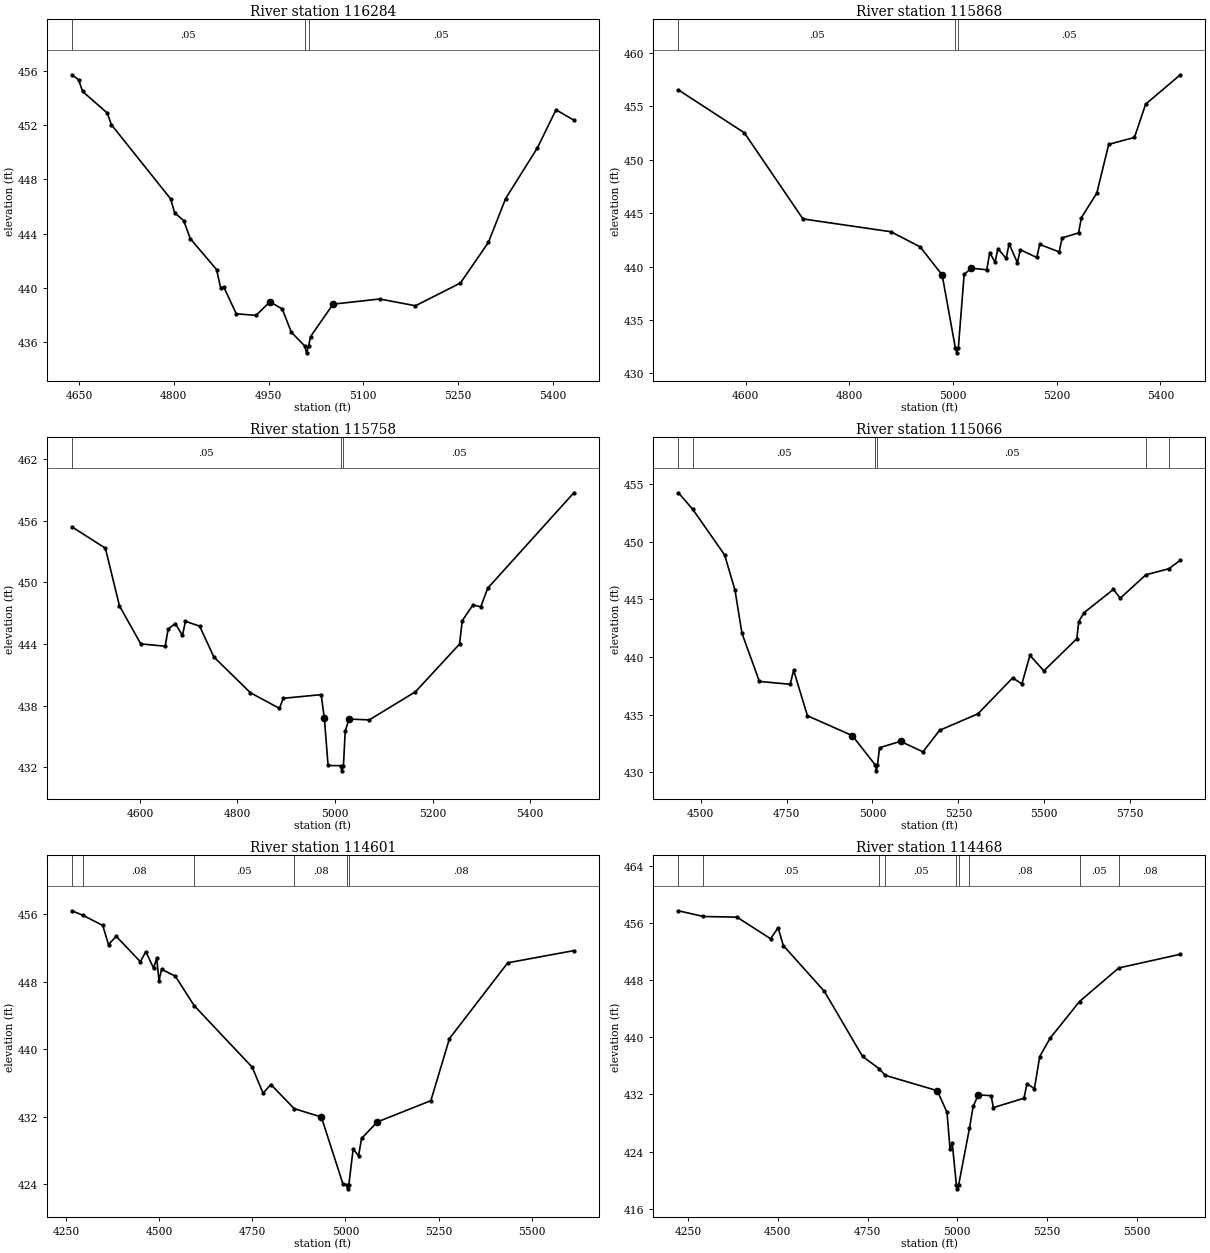
Type RM Length L Ch R = 1 ,116284  ,416,416,416
BEGIN DESCRIPTION:
CANEY CREEK 159.0
END DESCRIPTION:
XS GIS Cut Line= 3
      3565849.58      10585260.2      3566199.61     10585160.19
      3566549.57     10584910.22
#Sta/Elev= 30
    4639  455.72  4649.4  455.36  4655.9  454.49  4694.9   452.9  4701.4  452.04
    4795  446.58  4801.5  445.54  4815.8  444.97  4826.2  443.64  4867.8  441.36
  4874.3  440.01  4879.5  440.04    4899   438.1  4930.2  437.98  4952.3  438.98
  4971.8  438.45  4986.1  436.74  5007.4  435.72  5010.2  435.22  5013.4  435.72
  5016.5  436.42  5052.2  438.81  5125.9  439.19  5182.5  438.69  5253.7  440.37
    5298  443.37    5325  446.58  5375.4  450.33  5404.9  453.14  5433.1  452.37
#Mann= 3 ,-1 , 0
    4639     .05       0  5007.4     .03       0  5013.4     .05       0
Bank Sta=4952.3,5052.2
XS Rating Curve= 0 ,0
Exp/Cntr=0.3,0.1

Type RM Length L Ch R = 1 ,115868  ,110,110,110
BEGIN DESCRIPTION:
CANEY CREEK 158.0
END DESCRIPTION:
XS GIS Cut Line= 3
      3566149.61     10585760.19      3566549.61     10585360.19
      3566749.61     10585010.19
#Sta/Elev= 30
  4469.8  456.55  4597.1  452.53  4710.2  444.46  4879.9  443.26  4936.5  441.84
  4978.9  439.21  5004.2  432.41    5007  431.91  5010.2  432.41  5021.3  439.27
  5035.5  439.84    5065  439.69  5070.8  441.31  5080.8   440.4  5086.6  441.67
  5102.4  440.76  5108.2  442.13    5124  440.36  5129.8  441.57  5161.5  440.85
  5167.2  442.07  5204.7  441.37  5210.4  442.68  5242.1  443.15  5247.8  444.59
  5277.4  446.88  5300.4  451.45  5350.1   452.1  5371.7  455.22  5438.6  457.97
#Mann= 3 ,-1 , 0
  4469.8     .05       0  5004.2     .03       0  5010.2     .05       0
Bank Sta=4978.9,5035.5
XS Rating Curve= 0 ,0
Exp/Cntr=0.3,0.1

Type RM Length L Ch R = 1 ,115758  ,692,692,692
BEGIN DESCRIPTION:
CANEY CREEK 157.0
END DESCRIPTION:
XS GIS Cut Line= 4
      3566194.92     10585812.32      3566490.07     10585590.09
      3566667.15     10585388.71      3566854.56     10585045.12
#Sta/Elev= 30
  4460.7   455.4  4529.2  453.33  4558.1  447.71  4601.8  444.01  4651.8  443.78
    4658  445.45  4672.6  445.99  4687.2  444.83  4693.4  446.21  4722.6  445.73
  4751.7  442.73  4826.7  439.25  4886.2  437.73  4893.8  438.71  4971.6  439.07
  4978.2  436.77  4985.8  432.17  5011.3  432.15    5014  431.65  5017.3  432.15
  5020.9  435.49  5028.5  436.69  5070.3  436.61    5165  439.35  5255.3  443.99
  5260.9  446.27  5282.8   447.8  5298.9  447.62  5313.1  449.43  5489.7  458.72
#Mann= 3 ,-1 , 0
  4460.7     .05       0  5011.3     .03       0  5017.3     .05       0
Bank Sta=4978.2,5028.5
XS Rating Curve= 0 ,0
Exp/Cntr=0.3,0.1

Type RM Length L Ch R = 1 ,115066  ,465,465,465
BEGIN DESCRIPTION:
Mapping XS 13f7efdb
END DESCRIPTION:
XS GIS Cut Line= 3
      3566195.45     10586045.85      3566877.73     10586103.14
      3567615.98     10585863.99
#Sta/Elev= 30
  4435.3  454.25  4476.9  452.82  4569.9  448.85    4600  445.79  4620.1  442.07
  4670.9  437.88  4760.6  437.63  4770.6  438.85  4810.8   434.9  4941.2  433.18
  5008.5  430.62  5011.2  430.12  5014.5  430.62  5020.7  432.13  5081.7  432.68
    5147  431.77  5195.5  433.64    5307  435.07  5408.2  438.19  5434.9  437.66
  5458.3  440.14  5498.9   438.8  5594.9  441.59  5600.2  443.07    5616  443.85
  5701.4  445.87  5721.1   445.1  5795.7  447.13  5862.7  447.66    5896   448.4
#Mann= 6 ,-1 , 0
  4435.3     .08       0  4476.9     .05       0  5008.5     .03       0
  5014.5     .05       0  5795.7     .08       0  5862.7     .05       0
Bank Sta=4941.2,5081.7
XS Rating Curve= 0 ,0
Exp/Cntr=0.3,0.1

Type RM Length L Ch R = 1 ,114601  ,133,133,133
BEGIN DESCRIPTION:
CANEY CREEK 156.0
END DESCRIPTION:
XS GIS Cut Line= 2
      3566066.96     10586085.77      3567146.12     10586891.89
#Sta/Elev= 30
    4266  456.44  4296.2  455.89  4348.6   454.7  4364.1  452.43  4384.9  453.41
  4449.6  450.39  4464.2  451.59    4485  449.64  4493.4  450.78  4499.6  448.14
  4506.5  449.49  4543.4  448.68  4594.1  445.17  4749.7  437.87  4778.9  434.78
  4799.8  435.81  4862.6  432.94  4935.3  431.95  4993.3     424  5003.1  423.92
  5005.9  423.42  5009.1  423.92  5020.7  428.14  5035.3  427.35  5043.2   429.4
  5085.3  431.36  5229.2  433.89  5279.2  441.27  5435.5  450.26    5613  451.71
#Mann= 6 ,-1 , 0
    4266     .05       0  4296.2     .08       0  4594.1     .05       0
  4862.6     .08       0  5003.1     .07       0  5009.1     .08       0
Bank Sta=4935.3,5085.3
XS Rating Curve= 0 ,0
Exp/Cntr=0.3,0.1

Type RM Length L Ch R = 1 ,114468  ,331,331,331
BEGIN DESCRIPTION:
CANEY CREEK 155.0
END DESCRIPTION:
XS GIS Cut Line= 2
       3565962.8     10586168.24      3567078.27     10587010.27
#Sta/Elev= 30
  4223.4  457.68  4293.1  456.88  4386.4  456.79  4480.1  453.77  4500.9   455.3
  4515.5  452.82  4629.9  446.41  4736.1  437.31  4781.9  435.61  4799.1  434.67
  4944.2  432.52  4971.3  429.49  4979.6  424.43  4985.9   425.2  4997.5  419.29
  5000.2  418.79  5003.5  419.29  5033.9  427.28  5044.1  430.34  5058.7  431.93
  5094.1  431.82  5100.4  430.15  5185.7  431.47    5194  433.49  5214.8  432.82
  5229.4  437.29  5258.5  439.87  5340.3  444.99  5449.4  449.68    5621   451.6
#Mann= 9 ,-1 , 0
  4223.4     .08       0  4293.1     .05       0  4781.9     .08       0
  4799.1     .05       0  4997.5     .03       0  5003.5     .05       0
  5033.9     .08       0  5340.3     .05       0  5449.4     .08       0
Bank Sta=4944.2,5058.7
XS Rating Curve= 0 ,0
Exp/Cntr=0.3,0.1

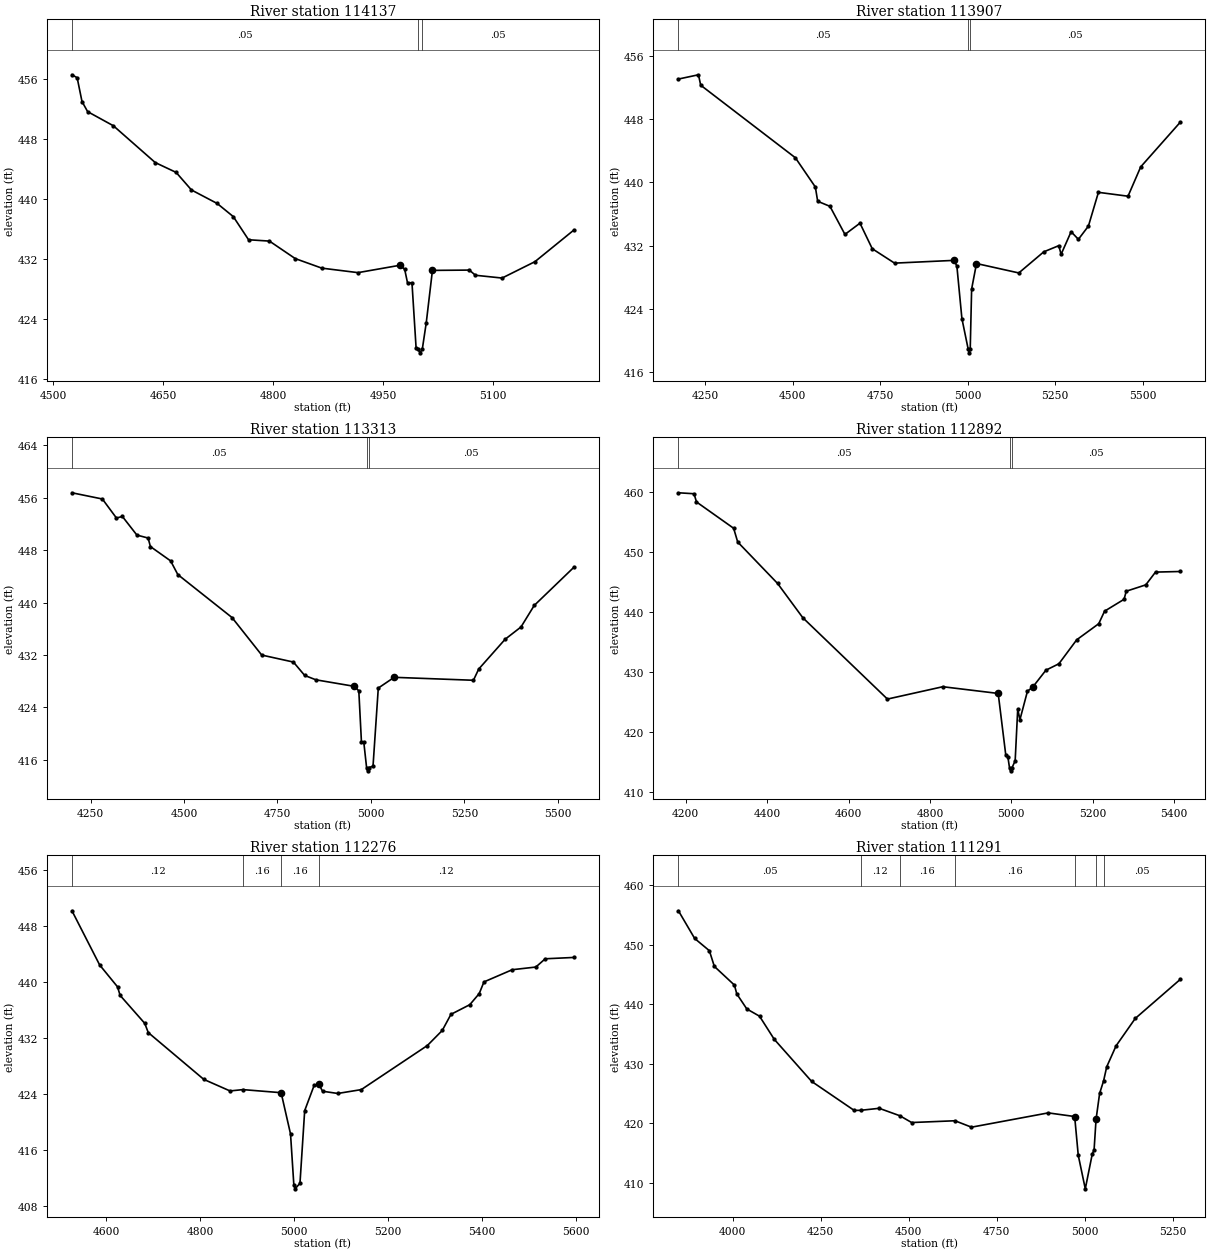
Type RM Length L Ch R = 1 ,114137  ,230,230,230
BEGIN DESCRIPTION:
CANEY CREEK 154.0
END DESCRIPTION:
XS GIS Cut Line= 3
      3566099.62      10586560.2      3566399.61     10586910.19
      3566599.63      10587010.2
#Sta/Elev= 30
  4525.2  456.58  4532.3  456.19  4538.9  453.02  4546.6  451.67  4581.7  449.79
  4638.8  444.89  4667.3  443.58  4688.2  441.24  4723.3  439.44  4745.3  437.69
  4766.1  434.61  4794.6  434.43  4829.8   432.1    4866  430.83  4915.4  430.23
  4972.4  431.21    4979  430.69  4982.9  428.88    4989  428.88  4994.6  420.22
  4997.1  420.05  4999.9  419.55  5003.1  420.05  5008.5  423.57  5016.9  430.53
  5067.2  430.57  5075.6  429.88  5111.9  429.51  5156.7  431.69  5209.8   435.9
#Mann= 3 ,-1 , 0
  4525.2     .05       0  4997.1     .03       0  5003.1     .05       0
Bank Sta=4972.4,5016.9
XS Rating Curve= 0 ,0
Exp/Cntr=0.3,0.1

Type RM Length L Ch R = 1 ,113907  ,594,594,594
BEGIN DESCRIPTION:
CANEY CREEK 153.0
END DESCRIPTION:
XS GIS Cut Line= 2
      3565651.28     10586567.98      3566743.87     10587495.81
#Sta/Elev= 30
  4173.7  453.06  4230.9   453.6  4237.4  452.28  4507.7  443.11  4564.8  439.41
  4571.4  437.61  4606.5  436.97  4649.3  433.42  4692.2  434.84  4727.3  431.61
    4791  429.79  4961.3  430.14    4969   429.4  4983.3  422.79  5001.1  418.95
  5003.9  418.45  5007.1  418.95  5011.1  426.52    5025  429.74  5145.8  428.55
  5217.2  431.22  5260.1     432  5266.6   430.9  5295.2  433.76    5316   432.8
  5344.6  434.47  5373.2  438.74  5457.7  438.25    5494  441.96  5607.1  447.61
#Mann= 3 ,-1 , 0
  4173.7     .05       0  5001.1     .03       0  5007.1     .05       0
Bank Sta=4961.3,5025
XS Rating Curve= 0 ,0
Exp/Cntr=0.3,0.1

Type RM Length L Ch R = 1 ,113313  ,421,421,421
BEGIN DESCRIPTION:
CANEY CREEK 152.0
END DESCRIPTION:
XS GIS Cut Line= 3
      3565273.53     10586982.66      3565999.61     10587260.19
      3566399.61     10587660.19
#Sta/Elev= 30
    4200  456.76  4281.4  455.81    4319  452.91    4335  453.14  4373.8   450.3
  4403.8  449.85  4409.9  448.55    4464  446.36  4483.3  444.27  4628.3  437.71
  4707.8  431.98  4792.6  430.91  4822.7  428.87  4852.7   428.2  4955.9   427.2
  4967.6  426.51  4974.6  418.74  4980.8  418.74  4988.4   414.8  4991.2   414.3
  4994.4   414.8  5005.6     415  5019.7  426.94  5062.2  428.58  5274.3  428.13
  5288.4  429.84  5359.1  434.39  5401.6  436.27  5436.9  439.55    5543  445.38
#Mann= 3 ,-1 , 0
    4200     .05       0  4988.4     .03       0  4994.4     .05       0
Bank Sta=4955.9,5062.2
XS Rating Curve= 0 ,0
Exp/Cntr=0.3,0.1

Type RM Length L Ch R = 1 ,112892  ,616,616,616
BEGIN DESCRIPTION:
CANEY CREEK 151.0
END DESCRIPTION:
XS GIS Cut Line= 2
      3565304.09      10587258.1      3566445.12     10587726.66
#Sta/Elev= 30
  4181.9  459.95  4220.3  459.79  4226.3  458.42  4317.6  454.03  4327.6  451.74
  4425.7  444.82  4487.6  439.11  4695.6  425.54  4831.7   427.6  4967.8  426.48
  4986.4  416.22  4991.8  415.81  4995.6  414.07  4998.4  413.57  5001.6  414.07
  5009.5  415.24  5015.8  423.89  5021.2   422.1  5039.7  426.85  5052.7  427.54
  5085.1  430.36    5117  431.43  5160.8  435.43  5214.9  438.11  5229.2   440.2
  5277.1  442.18  5282.5  443.53  5330.5  444.59  5354.4  446.72  5415.4  446.82
#Mann= 3 ,-1 , 0
  4181.9     .05       0  4995.6     .03       0  5001.6     .05       0
Bank Sta=4967.8,5052.7
XS Rating Curve= 0 ,0
Exp/Cntr=0.3,0.1

Type RM Length L Ch R = 1 ,112276  ,985,985,985
BEGIN DESCRIPTION:
CANEY CREEK 150.0
END DESCRIPTION:
XS GIS Cut Line= 3
      3565381.65     10587836.81      3565742.75     10587947.92
      3566430.21     10587892.37
#Sta/Elev= 30
  4527.4  450.18  4586.3  442.45  4624.3  439.33  4629.9   438.1  4682.2  434.12
  4689.7   432.8  4807.8  426.12  4863.6  424.47  4891.1  424.66  4972.3  424.22
  4992.3  418.33  4999.4     411  5002.1   410.5  5012.4   411.3  5022.4  421.66
  5042.5  425.26  5052.5  425.44  5060.4  424.43  5092.7  424.11  5142.8  424.66
  5283.3  430.95    5315   433.1  5333.5   435.4  5373.6  436.78  5393.6  438.36
  5403.7  440.03  5463.9  441.77    5514  442.15  5534.1  443.33  5594.9  443.52
#Mann= 4 ,-1 , 0
  4527.4     .12       0  4891.1     .16       0  4972.3     .16       0
  5052.5     .12       0
Bank Sta=4972.3,5052.5
XS Rating Curve= 0 ,0
Exp/Cntr=0.3,0.1

Type RM Length L Ch R = 1 ,111291  ,587,587,587
BEGIN DESCRIPTION:
CANEY CREEK 149.0
END DESCRIPTION:
XS GIS Cut Line= 3
       3565270.5     10587954.83      3565881.64      10588663.2
      3566366.13     10588587.06
#Sta/Elev= 30
  3845.6  455.68  3891.8  451.03  3933.5  448.98  3947.7  446.34  4004.8   443.2
  4011.4  441.73  4039.9   439.2  4076.1  437.98  4117.8  434.11  4224.2  427.03
  4344.9  422.17  4363.1  422.18  4416.1  422.52  4474.7  421.27  4508.3  420.13
  4631.3  420.43  4678.3  419.35  4896.3  421.75  4971.4  421.14  4981.6  414.64
  5001.6     409  5021.5  414.87  5026.6  415.55  5032.2  420.67  5042.3  425.01
  5053.6  427.13  5062.5  429.49  5089.1  433.01  5143.5   437.6  5271.6  444.17
#Mann= 7 ,-1 , 0
  3845.6     .05       0  4363.1     .12       0  4474.7     .16       0
  4631.3     .16       0  4971.4     .12       0  5032.2     .16       0
  5053.6     .05       0
Bank Sta=4971.4,5032.2
XS Rating Curve= 0 ,0
Exp/Cntr=0.3,0.1

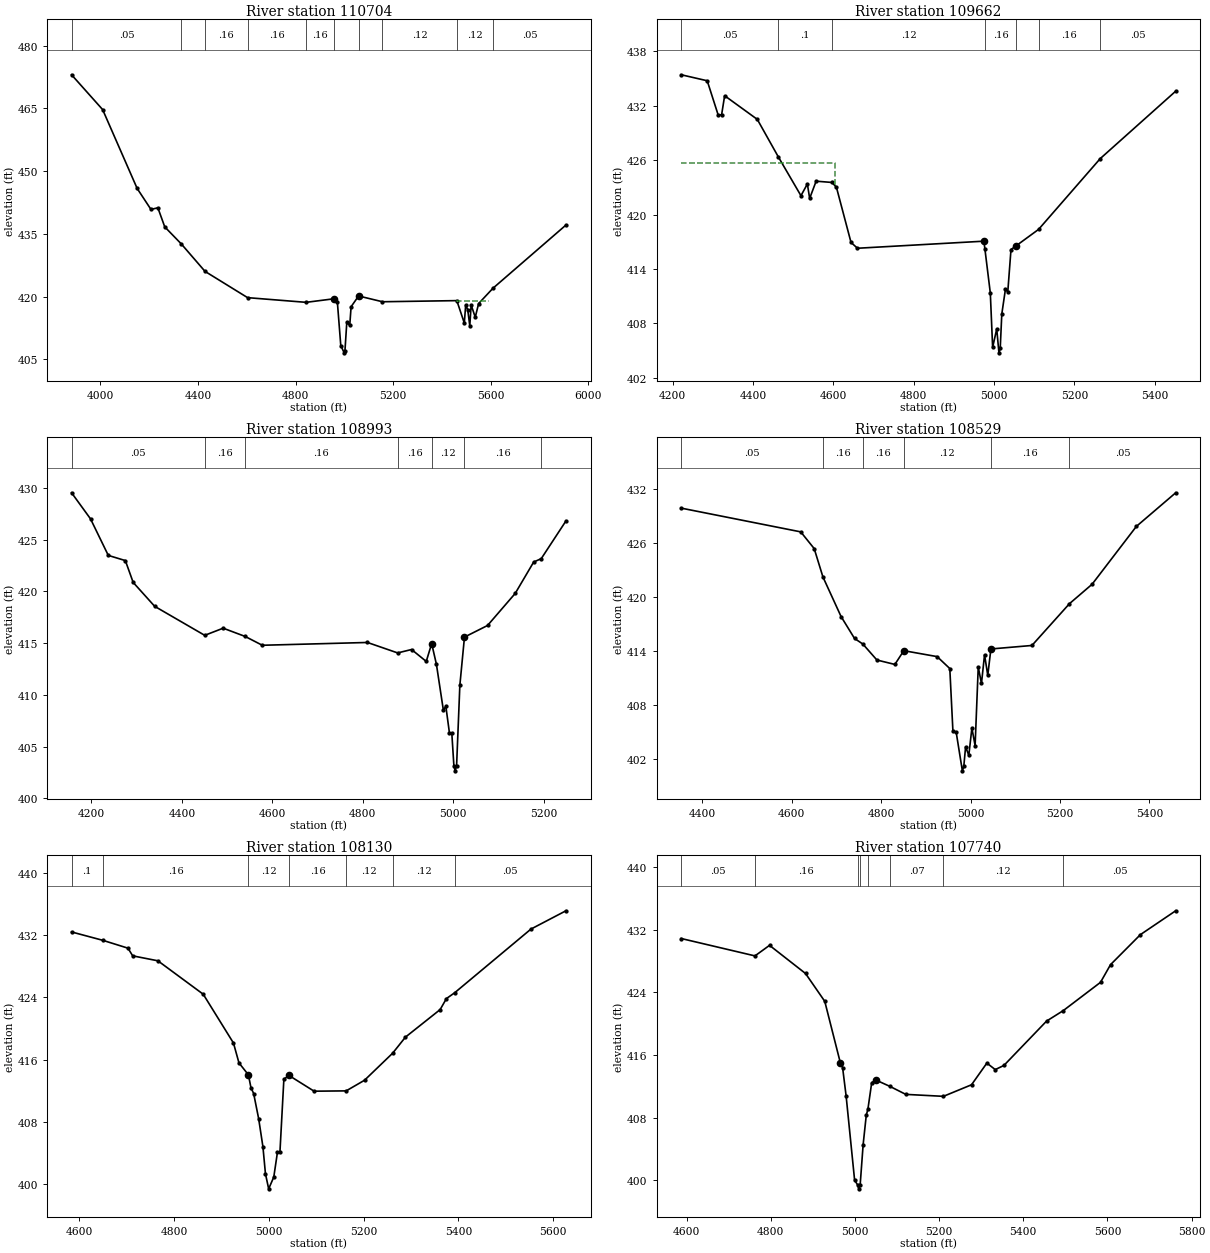
Type RM Length L Ch R = 1 ,110704  ,1042,1042,1042
BEGIN DESCRIPTION:
CANEY CREEK 148.0
END DESCRIPTION:
XS GIS Cut Line= 3
       3564949.6     10588060.18      3565749.61     10588860.19
      3566149.61     10589660.18
#Sta/Elev= 30
    3882  473.05  4009.3  464.72  4150.7  445.86  4207.3  440.84  4235.6  441.23
  4263.8  436.67  4331.6  432.59  4428.9  426.02  4603.3  419.74  4843.1  418.62
  4956.8  419.47    4971  418.77  4985.1  408.29    4999  406.54  5002.2  407.04
  5009.8  413.88  5021.8  413.09  5027.4  417.57  5058.1  420.14  5155.9  418.76
  5460.6  419.03  5491.3  413.66  5496.9  417.97  5505.3  416.86  5513.7  413.01
  5519.3  417.99  5536.1  415.06    5550  418.33  5608.7  421.99  5907.8  437.11
#Mann= 10 ,-1 , 0
    3882     .05       0  4331.6     .12       0  4428.9     .16       0
  4603.3     .16       0  4843.1     .16       0  4956.8     .12       0
  5058.1     .16       0  5155.9     .12       0  5460.6     .12       0
  5608.7     .05       0
#XS Ineff= 1 ,-1
 5463.07 5592.33  419.02
Permanent Ineff=
       F
Bank Sta=4956.8,5058.1
XS Rating Curve= 0 ,0
Exp/Cntr=0.3,0.1

Type RM Length L Ch R = 1 ,109662  ,669,669,669
BEGIN DESCRIPTION:
CANEY CREEK 146.0
END DESCRIPTION:
XS GIS Cut Line= 2
      3565041.36     10588642.37       3565638.6     10589718.79
#Sta/Elev= 30
  4221.3  435.42  4285.8  434.76  4313.2  430.97  4321.7  431.02  4329.2  433.11
  4410.5   430.5    4463  426.35  4519.2  422.08  4535.2  423.37  4540.9  421.78
    4557  423.68  4596.5  423.54  4607.6     423  4643.9  416.92    4660  416.28
  4974.7  417.06  4977.2  416.22  4990.7  411.35  4996.5  405.34  5006.7  407.38
  5012.2  404.74  5015.4  405.24  5019.3  409.02  5028.4  411.77  5034.2  411.46
  5042.2  416.14  5055.9  416.58  5110.9  418.36  5264.4  426.17  5452.3  433.61
#Mann= 7 ,-1 , 0
  4221.3     .05       0    4463      .1       0  4596.5     .12       0
  4977.2     .16       0  5055.9     .12       0  5110.9     .16       0
  5264.4     .05       0
#XS Ineff= 2 , 0
         4604.09  425.73
Permanent Ineff=
       F       F
Bank Sta=4974.7,5055.9
XS Rating Curve= 0 ,0
Exp/Cntr=0.3,0.1

Type RM Length L Ch R = 1 ,108993  ,464,464,464
BEGIN DESCRIPTION:
CANEY CREEK 145.0
END DESCRIPTION:
XS GIS Cut Line= 3
      3564849.62     10589010.22      3565099.61     10589810.19
      3565149.62     10590060.22
#Sta/Elev= 30
  4156.2  429.52  4198.1     427  4237.4  423.47  4275.1  422.97  4292.4  420.86
    4340  418.55  4450.6  415.75  4491.4  416.44  4540.1  415.64  4577.9  414.79
  4810.4  415.06  4877.2  414.05  4907.9  414.38  4940.4  413.23  4952.4  414.95
  4962.9  412.95  4978.1  408.56  4983.8  408.88  4991.7  406.31  4996.9  406.31
  5001.5  403.16  5004.3  402.66  5007.5  403.16  5014.7  410.93  5024.9  415.58
  5075.9   416.7  5137.1   419.8  5177.9  422.83  5194.7  423.16  5249.3   426.8
#Mann= 7 ,-1 , 0
  4156.2     .05       0  4450.6     .16       0  4540.1     .16       0
  4877.2     .16       0  4952.4     .12       0  5024.9     .16       0
  5194.7     .05       0
Bank Sta=4952.4,5024.9
XS Rating Curve= 0 ,0
Exp/Cntr=0.3,0.1

Type RM Length L Ch R = 1 ,108529  ,399,399,399
BEGIN DESCRIPTION:
CANEY CREEK 144.0
END DESCRIPTION:
XS GIS Cut Line= 3
      3564083.13     10589786.57      3564595.25     10589821.29
       3565020.6     10590233.62
#Sta/Elev= 30
    4353   429.9  4620.1  427.26  4650.2   425.4  4669.7  422.25  4710.3  417.84
  4740.4   415.4    4759  414.78  4790.5     413  4830.6  412.51  4850.6  414.04
  4925.2  413.38  4953.5  412.05  4960.5  405.05  4967.7  404.99  4981.6  400.67
  4984.8  401.17  4988.8  403.34    4996   402.4  5002.9  405.43  5010.1  403.47
  5017.1  412.22  5024.3  410.39  5031.2  413.59  5038.4  411.29  5045.4  414.23
  5137.2  414.62  5221.1  419.27  5271.7  421.43  5370.8  427.87  5458.7  431.61
#Mann= 6 ,-1 , 0
    4353     .05       0  4669.7     .16       0    4759     .16       0
  4850.6     .12       0  5045.4     .16       0  5221.1     .05       0
Bank Sta=4850.6,5045.4
XS Rating Curve= 0 ,0
Exp/Cntr=0.3,0.1

Type RM Length L Ch R = 1 ,108130  ,390,390,390
BEGIN DESCRIPTION:
CANEY CREEK 143.0
END DESCRIPTION:
XS GIS Cut Line= 2
      3564048.36     10589986.21      3565029.29     10590342.13
#Sta/Elev= 30
  4583.6  432.45  4649.6  431.37  4702.6  430.36  4712.6  429.37  4765.8  428.73
  4861.5  424.42  4925.3  418.13  4936.9  415.57  4956.8  414.03  4962.2  412.38
  4967.9  411.62  4978.5  408.37  4987.5  404.75  4992.8  401.28  4999.6  399.33
  5010.4  400.85  5018.1  404.03  5023.4  404.07  5031.7  413.47  5042.4  413.95
  5095.5  411.92  5163.2  411.96  5201.9  413.33  5261.3  416.82  5288.3  418.89
  5361.5  422.44  5374.8  423.86  5392.2  424.61  5553.2  432.82  5627.1  435.18
#Mann= 7 ,-1 , 0
  4583.6      .1       0  4649.6     .16       0  4956.8     .12       0
  5042.4     .16       0  5163.2     .12       0  5261.3     .12       0
  5392.2     .05       0
Bank Sta=4956.8,5042.4
XS Rating Curve= 0 ,0
Exp/Cntr=0.3,0.1

Type RM Length L Ch R = 1 ,107740  ,502,502,502
BEGIN DESCRIPTION:
CANEY CREEK 142.0
END DESCRIPTION:
XS GIS Cut Line= 3
      3563987.63     10590216.28      3564195.94     10590454.97
      3565042.32     10590593.86
#Sta/Elev= 30
  4587.6   430.9  4762.6  428.68  4797.2  430.03  4882.7  426.43  4928.4  422.87
  4965.7  414.95  4970.8  414.39  4979.1  410.79  4999.3     400  5006.5  399.39
  5009.2  398.89  5012.5  399.39  5019.6  404.56    5027   408.3  5030.9  409.08
  5039.9  412.46    5050   412.8  5083.3  411.99  5120.9  410.97  5210.3  410.72
  5277.1   412.2  5313.5  414.97  5333.4  414.14    5354  414.67  5455.3  420.34
  5495.2  421.69  5583.5   425.3  5607.3  427.56  5678.3   431.4  5762.1  434.45
#Mann= 8 ,-1 , 0
  4587.6     .05       0  4762.6     .16       0  5006.5     .07       0
  5012.5     .16       0  5030.9     .12       0  5083.3     .07       0
  5210.3     .12       0  5495.2     .05       0
Bank Sta=4965.7,5050
XS Rating Curve= 0 ,0
Exp/Cntr=0.3,0.1

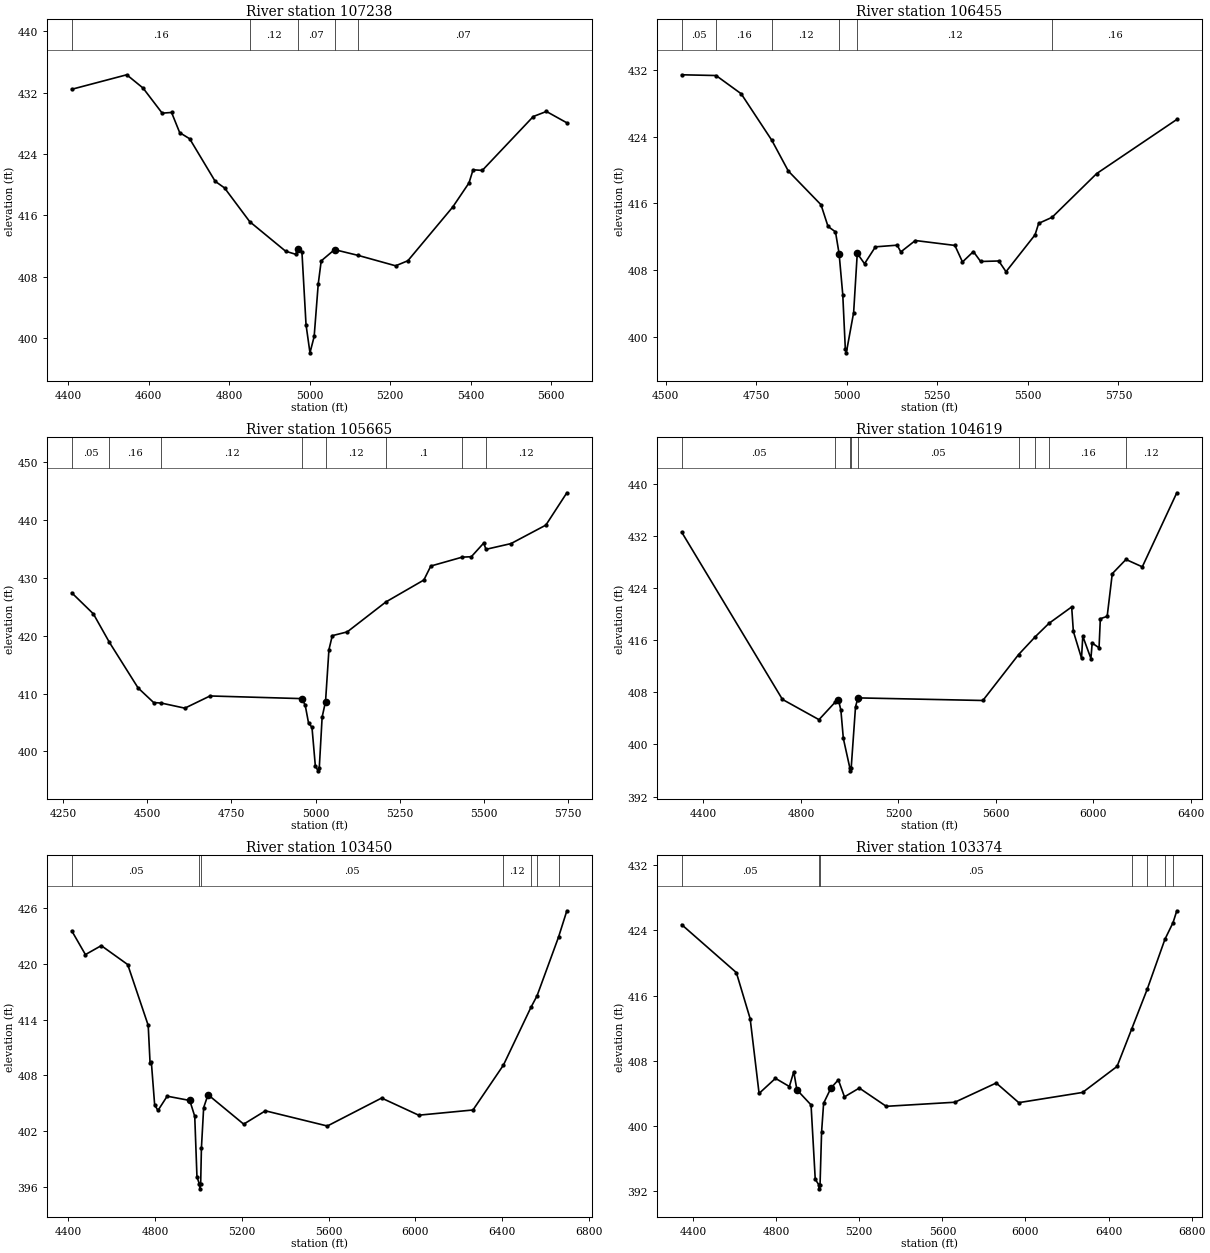
Type RM Length L Ch R = 1 ,107238  ,783,783,783
BEGIN DESCRIPTION:
CANEY CREEK 141.0
END DESCRIPTION:
XS GIS Cut Line= 2
      3563744.58     10591049.58      3564959.83     10590862.95
#Sta/Elev= 30
    4409  432.42  4545.6  434.31  4586.1  432.58  4633.6  429.31  4656.9   429.4
  4677.1  426.77  4701.9  425.97  4765.2  420.43  4788.4  419.57    4851  415.17
  4940.2  411.32  4965.2  410.92  4970.5  411.64  4980.7  411.17  4990.8  401.75
  5000.6  398.08    5011  400.21  5021.1  407.05  5028.5  410.06  5061.6  411.53
  5120.7  410.77  5213.3  409.42  5243.7  410.08    5355  417.07  5395.5  420.22
  5405.6  421.93  5428.5  421.85  5555.1  428.87  5587.7  429.53  5638.5  428.05
#Mann= 5 ,-1 , 0
    4409     .16       0    4851     .12       0  4970.5     .07       0
  5061.6     .12       0  5120.7     .07       0
Bank Sta=4970.5,5061.6
XS Rating Curve= 0 ,0
Exp/Cntr=0.3,0.1

Type RM Length L Ch R = 1 ,106455  ,790,790,790
BEGIN DESCRIPTION:
CANEY CREEK 140.0
END DESCRIPTION:
XS GIS Cut Line= 2
      3563825.67     10591371.85      3565190.34     10591449.98
#Sta/Elev= 30
  4544.4  431.47  4639.3  431.38  4708.6  429.19  4793.3  423.59  4838.8   419.9
    4929  415.85  4948.4  413.24    4969  412.59    4979  409.96  4989.1  405.04
  4996.1  398.55  4998.8  398.05  5019.1  402.89  5029.1     410  5049.2  408.76
  5079.2  410.79  5139.3  410.99  5149.3  410.18  5189.4  411.55  5298.6  410.96
  5319.6  408.97  5349.7  410.22  5369.7  409.03  5419.8  409.09  5439.8   407.8
  5519.9  412.23  5529.9  413.61    5567  414.34  5690.2   419.6  5911.3   426.1
#Mann= 6 ,-1 , 0
  4544.4     .05       0  4639.3     .16       0  4793.3     .12       0
    4979     .07       0  5029.1     .12       0    5567     .16       0
Bank Sta=4979,5029.1
XS Rating Curve= 0 ,0
Exp/Cntr=0.3,0.1

Type RM Length L Ch R = 1 ,105665  ,1046,1046,1046
BEGIN DESCRIPTION:
CANEY CREEK 138.0
END DESCRIPTION:
XS GIS Cut Line= 3
      3563830.94     10591726.03      3564398.62     10591981.23
      3565241.51     10592085.29
#Sta/Elev= 30
  4275.3  427.42  4339.6  423.78  4387.3  418.85  4472.5  410.97  4518.8  408.44
  4541.6  408.35  4611.5  407.47  4686.4  409.58  4959.2  409.12  4969.2     408
  4979.3  404.87  4989.4  404.16  4999.5  397.39  5007.8  396.63  5011.1  397.13
  5019.6  405.93  5029.7  408.62  5039.8  417.58  5049.8  420.01  5094.2  420.66
  5209.1  425.84  5321.9  429.63  5342.6  432.05  5436.1  433.59    5463  433.66
  5499.8  436.02  5506.6  434.94  5580.9  435.93  5684.6  439.13    5747  444.72
#Mann= 8 ,-1 , 0
  4275.3     .05       0  4387.3     .16       0  4541.6     .12       0
  4959.2     .07       0  5029.7     .12       0  5209.1      .1       0
  5436.1     .07       0  5506.6     .12       0
Bank Sta=4959.2,5029.7
XS Rating Curve= 0 ,0
Exp/Cntr=0.3,0.1

Type RM Length L Ch R = 1 ,104619  ,1169,1169,1169
BEGIN DESCRIPTION:
CANEY CREEK 137.0
END DESCRIPTION:
XS GIS Cut Line= 3
      3563256.13     10592524.92      3564176.25     10592498.88
      3565243.96     10592186.37
#Sta/Elev= 30
  4310.5  432.55  4724.1   406.9  4874.2  403.79  4941.8  406.52  4954.2  406.84
  4964.2  405.23  4974.2  400.92  5000.6  396.44  5003.3  395.94  5006.6  396.44
  5024.3  405.78  5032.4  406.87  5034.3  407.13  5547.1  406.73  5693.7  413.77
  5762.8  416.53  5818.5  418.56  5911.8  421.08  5918.7  417.33  5952.2  413.22
  5957.4  416.59  5990.8  413.17    5996  415.54  6024.2  414.81  6029.5  419.27
  6057.6  419.64  6078.5  426.18  6134.7  428.36  6201.8  427.23  6343.5  438.59
#Mann= 9 ,-1 , 0
  4310.5     .05       0  4941.8     .16       0  5000.6     .07       0
  5006.6     .16       0  5032.4     .05       0  5693.7     .08       0
  5762.8     .05       0  5818.5     .16       0  6134.7     .12       0
Bank Sta=4954.2,5034.3
XS Rating Curve= 0 ,0
Exp/Cntr=0.3,0.1

Type RM Length L Ch R = 1 ,103450  ,76,76,76
BEGIN DESCRIPTION:
Mapping XS c9b6cc2f
END DESCRIPTION:
XS GIS Cut Line= 4
      3563501.13     10592901.59      3563782.35     10593349.47
      3563949.02     10593309.54      3565218.64     10592364.26
#Sta/Elev= 30
  4415.7  423.52  4478.8  420.97  4551.9  421.93  4673.8   419.9  4768.3  413.38
  4776.9  409.36  4782.8  409.44  4798.1  404.83  4813.4  404.25  4855.8  405.78
    4960  405.32  4982.9  403.62  4993.1  397.15  5004.2  396.34  5006.9  395.84
  5010.2  396.34  5013.7  400.22    5024  404.55  5044.1  405.94  5208.6  402.78
  5308.7  404.21  5594.4  402.58  5844.6  405.58  6015.6  403.74  6265.9   404.3
  6406.2  409.11  6533.2  415.31  6561.2  416.54  6660.3  422.84  6698.8  425.67
#Mann= 7 ,-1 , 0
  4415.7     .05       0  5004.2    .035       0  5010.2     .05       0
  6406.2     .12       0  6533.2     .07       0  6561.2     .12       0
  6660.3     .07       0
Bank Sta=4960,5044.1
XS Rating Curve= 0 ,0
Exp/Cntr=0.3,0.1

Type RM Length L Ch R = 1 ,103374  ,339,339,339
BEGIN DESCRIPTION:
Mapping XS 33e430dd
END DESCRIPTION:
XS GIS Cut Line= 4
      3563494.61     10592921.54      3563801.88     10593407.19
       3563933.4     10593390.27      3565299.71     10592418.91
#Sta/Elev= 30
  4344.9  424.69  4608.1  418.81  4674.6  413.15  4717.5  403.99  4796.3  405.84
  4863.3  404.84  4884.5  406.65  4899.5  404.44  4967.7  402.58  4987.9  393.46
    5005  392.79  5007.8  392.29    5011  392.79  5018.4  399.25  5028.2  402.79
  5063.5  404.65  5099.1  405.66  5128.6  403.57    5200  404.65  5329.7  402.41
  5659.9  402.91  5859.2  405.27  5967.8  402.86  6274.8  404.11  6440.9   407.3
  6510.9  411.86  6585.7  416.74  6671.3  422.89  6710.5  424.94  6728.6  426.39
#Mann= 7 ,-1 , 0
  4344.9     .05       0    5005     .03       0    5011     .05       0
  6510.9     .07       0  6585.7     .12       0  6671.3     .07       0
  6710.5     .16       0
Bank Sta=4899.5,5063.5
XS Rating Curve= 0 ,0
Exp/Cntr=0.3,0.1