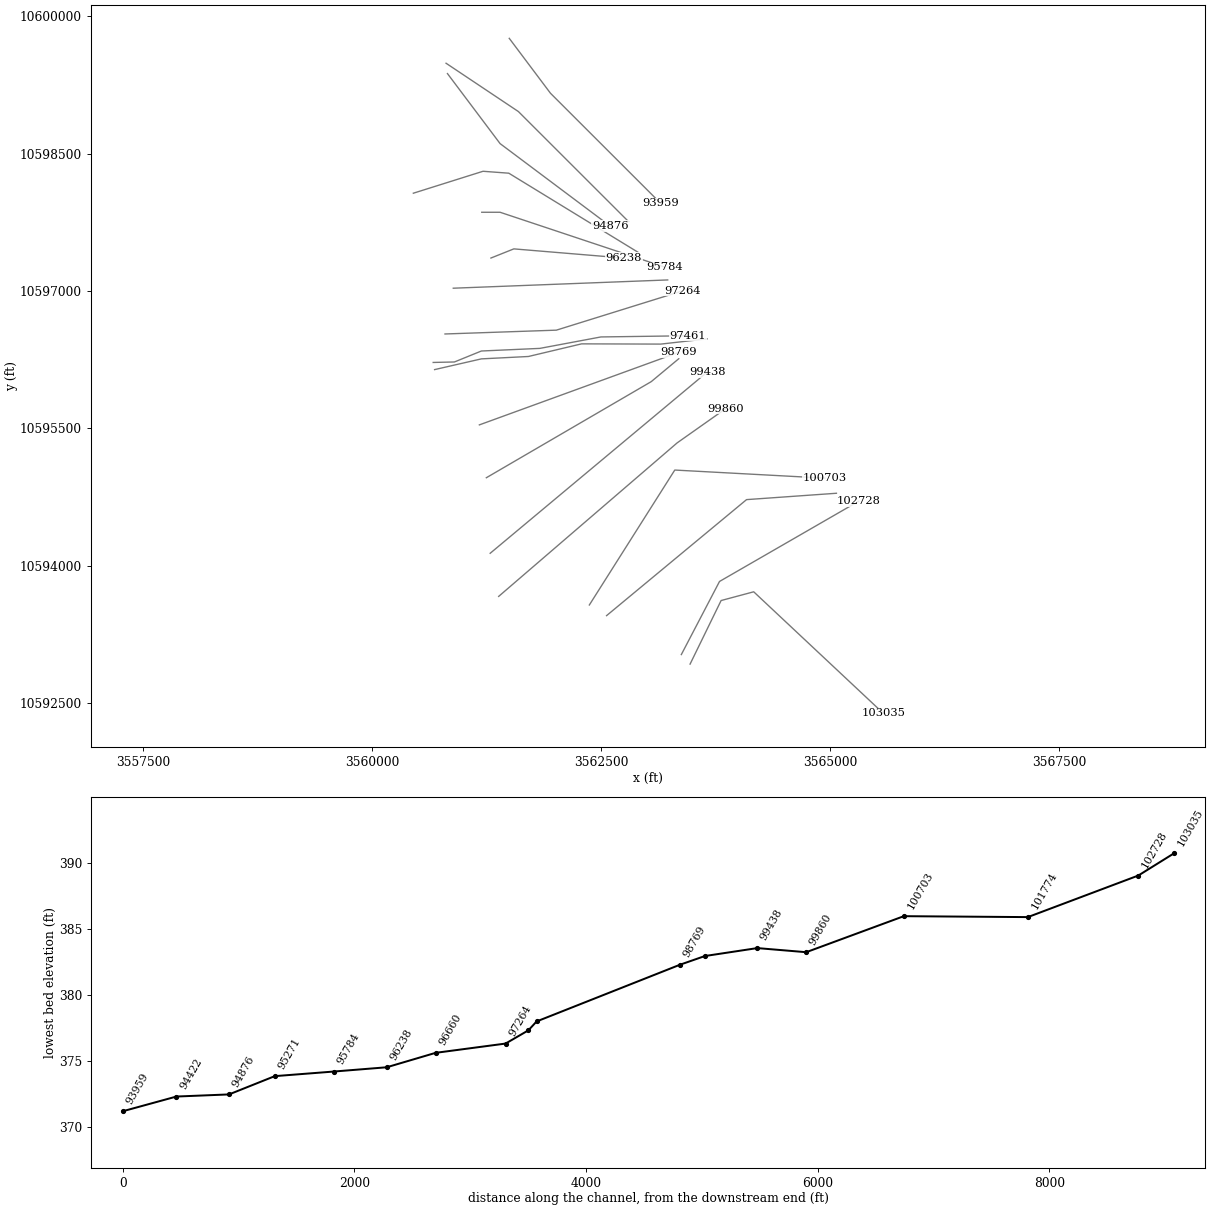
HEC-RAS study CANEY CREEK.prj: CANEY CREEK Base Level Engineering

--- CANEY CREEK.g01 (geometry) --- (continued)

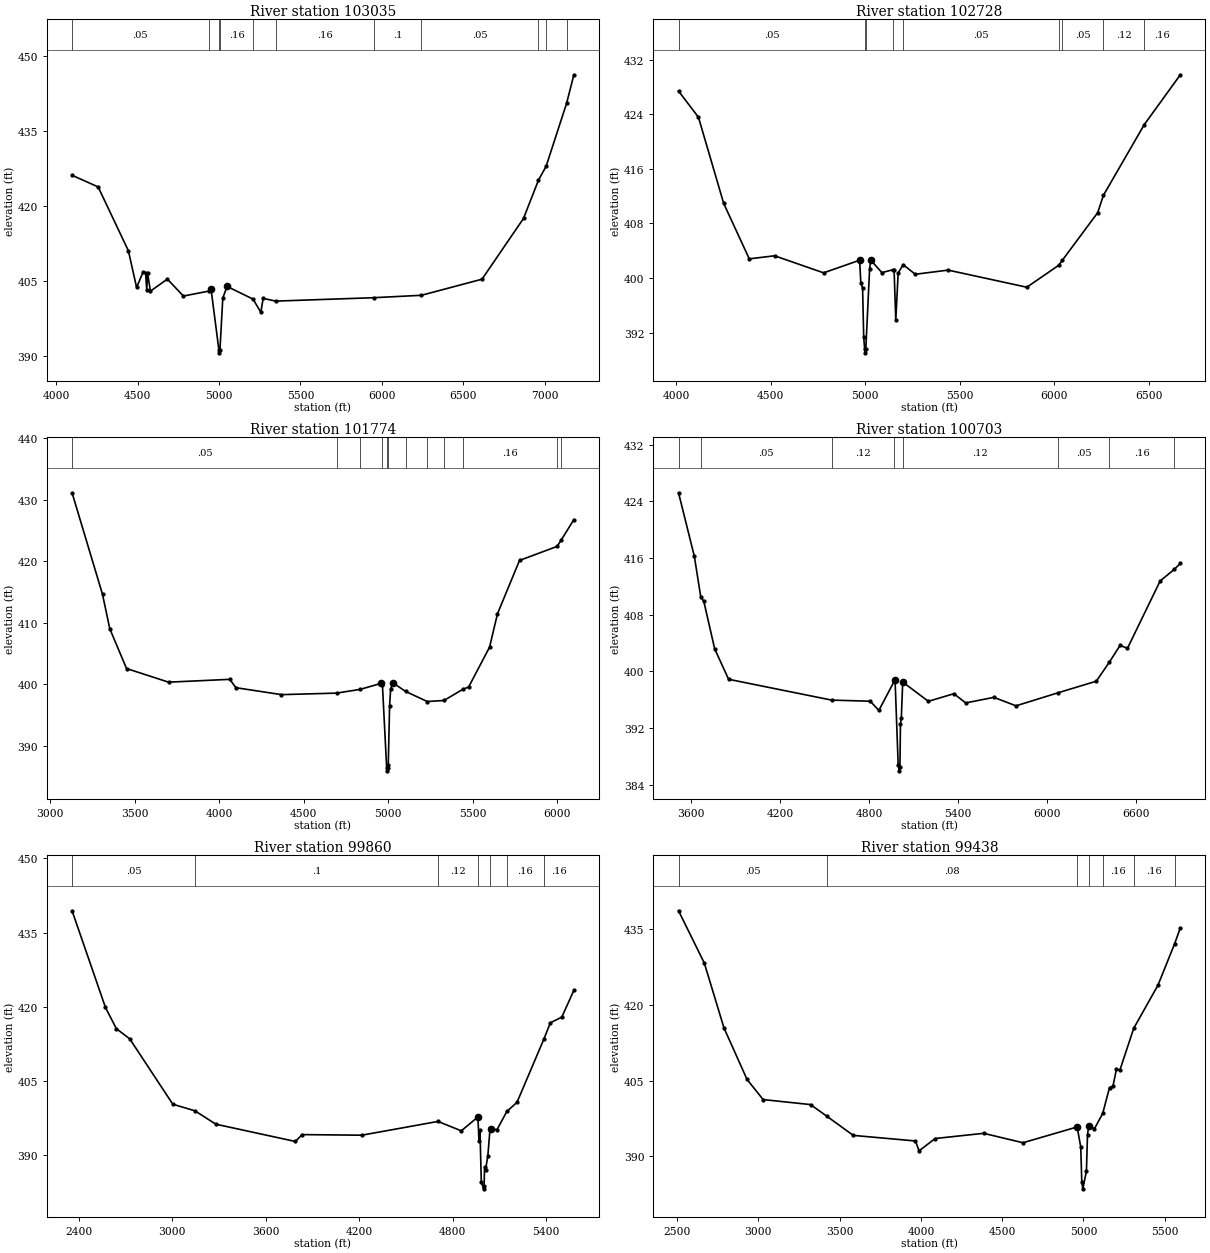
Type RM Length L Ch R = 1 ,103035  ,307,307,307
BEGIN DESCRIPTION:
CANEY CREEK 136.0
END DESCRIPTION:
XS GIS Cut Line= 4
      3563473.13     10592924.22      3563811.67     10593618.67
      3564167.57     10593714.15      3565582.53       10592386.
#Sta/Elev= 30
  4097.3  426.11  4257.3  423.79  4443.1  411.06  4493.7  403.73  4533.3   406.8
  4548.9  406.66  4555.8  403.25  4561.4  406.62  4578.3  402.99  4682.4   405.4
  4781.1  402.02  4935.2  402.99  4950.6  403.48  4999.3  391.19  5002.1  390.69
  5005.3  391.19    5023  401.62  5049.2  403.94    5209   401.4  5256.6  398.78
  5270.8  401.56  5347.9  401.01  5949.7  401.69  6242.8  402.17  6614.9  405.38
  6869.9  417.51  6961.8  425.15  7008.5  427.89  7134.6  440.49    7179  446.16
#Mann= 11 ,-1 , 0
  4097.3     .05       0  4935.2     .16       0  4999.3     .07       0
  5005.3     .16       0    5209     .05       0  5347.9     .16       0
  5949.7      .1       0  6242.8     .05       0  6961.8     .12       0
  7008.5     .05       0  7134.6     .16       0
Bank Sta=4950.6,5049.2
XS Rating Curve= 0 ,0
Exp/Cntr=0.3,0.1

Type RM Length L Ch R = 1 ,102728  ,954,954,954
BEGIN DESCRIPTION:
CANEY CREEK 135.0
END DESCRIPTION:
XS GIS Cut Line= 3
      3563377.65     10593028.41      3563794.31       10593827.
      3565313.41     10594703.74
#Sta/Elev= 30
  4012.7   427.4    4118  423.57  4251.6  410.93  4386.9   402.8  4520.8  403.25
  4780.2  400.75  4970.7   402.6  4977.3  399.23  4986.5  398.51  4992.2  391.41
  4997.4  389.52  5000.1  389.02  5003.4  389.52  5023.5  401.27  5029.6  402.63
  5088.4  400.78  5145.1  401.19  5153.1  401.19    5162  393.79  5174.6  400.71
  5200.9  401.96    5265  400.54  5439.1  401.15  5855.3  398.64  6024.6  401.87
  6042.3  402.56  6230.1  409.57  6260.4  412.11  6476.8  422.49  6667.4  429.79
#Mann= 9 ,-1 , 0
  4012.7     .05       0  4997.4     .03       0  5003.4     .05       0
  5145.1     .16       0  5200.9     .05       0  6024.6     .07       0
  6042.3     .05       0  6260.4     .12       0  6476.8     .16       0
Bank Sta=4970.7,5029.6
XS Rating Curve= 0 ,0
Exp/Cntr=0.3,0.1

Type RM Length L Ch R = 1 ,101774  ,1071,1071,1071
BEGIN DESCRIPTION:
Mapping XS 6f22017e
END DESCRIPTION:
XS GIS Cut Line= 3
      3562561.65     10593453.72      3564089.45      10594721.1
      3565070.35     10594790.54
#Sta/Elev= 30
  3129.7  431.13  3309.9  414.59  3352.8     409  3451.9  402.53  3700.5  400.31
  4062.6  400.77    4099  399.41  4368.6  398.28  4695.3  398.53  4834.2  399.14
  4958.5  400.12  4965.8   399.8  4990.7  386.38  4993.4  385.88  4996.7  386.38
  5000.2   386.8    5008  396.43  5014.5  399.26  5028.8  400.18  5103.1   398.8
  5230.8  397.16  5329.7  397.33  5439.6  399.12  5475.8  399.53  5599.3     406
  5646.2  411.43  5776.6  420.12  5998.8   422.4  6021.9  423.38  6098.1  426.76
#Mann= 12 ,-1 , 0
  3129.7     .05       0  4695.3     .07       0  4834.2     .12       0
  4965.8     .07       0  4990.7     .07       0  4996.7     .07       0
  5103.1     .12       0  5230.8     .07       0  5329.7     .05       0
  5439.6     .16       0  5998.8     .12       0  6021.9     .16       0
Bank Sta=4958.5,5028.8
XS Rating Curve= 0 ,0
Exp/Cntr=0.3,0.1

Type RM Length L Ch R = 1 ,100703  ,843,843,843
BEGIN DESCRIPTION:
CANEY CREEK 134.0
END DESCRIPTION:
XS GIS Cut Line= 3
      3562373.71     10593570.13      3563306.03     10595044.12
      3564945.65     10594955.64
#Sta/Elev= 30
    3514  425.22  3620.6  416.25  3663.8  410.55  3684.8  409.87  3757.8  403.18
  3851.8  398.88    4547  395.94  4808.1  395.78  4865.7  394.48  4969.2  398.59
  4975.1  398.84  4996.3  386.73  5004.7  385.95    5008  386.45  5011.6  392.56
  5017.5  393.47  5026.8  398.49  5199.8  395.77  5371.8  396.84    5452  395.54
  5642.2  396.33  5791.2  395.13  6072.9  396.96  6333.2  398.61  6420.8  401.29
  6493.5  403.66  6543.5  403.26  6763.9  412.76  6858.7   414.4  6900.1  415.24
#Mann= 8 ,-1 , 0
    3514     .16       0  3663.8     .05       0    4547     .12       0
  4969.2      .1       0  5026.8     .12       0  6072.9     .05       0
  6420.8     .16       0  6858.7     .12       0
Bank Sta=4975.1,5026.8
XS Rating Curve= 0 ,0
Exp/Cntr=0.3,0.1

Type RM Length L Ch R = 1 ,99860   ,422,422,422
BEGIN DESCRIPTION:
CANEY CREEK 133.0
END DESCRIPTION:
XS GIS Cut Line= 3
      3561384.12     10593663.89      3563332.07       10595341.
      3563862.73     10595715.58
#Sta/Elev= 30
  2358.2  439.42  2572.4  419.89  2642.6  415.59  2728.2  413.54  3004.7  400.33
  3146.2     399  3281.2  396.29  3791.4   392.8  3834.2  394.19  4217.1  394.07
  4706.4  396.85  4855.6  394.95  4962.4  397.75  4969.5  392.84  4975.7  395.07
  4984.3  384.63  4998.8  383.23  5002.1  383.73  5005.2  387.57  5011.4  387.08
  5026.1  389.85  5040.9  395.62    5048  395.42  5084.8  395.17    5148  398.86
  5213.3  400.71  5385.7  413.48  5427.5  416.79  5500.9  417.93  5578.2  423.35
#Mann= 7 ,-1 , 0
  2358.2     .05       0  3146.2      .1       0  4706.4     .12       0
  4962.4      .1       0  5040.9     .12       0    5148     .16       0
  5385.7     .16       0
Bank Sta=4962.4,5048
XS Rating Curve= 0 ,0
Exp/Cntr=0.3,0.1

Type RM Length L Ch R = 1 ,99438   ,453,453,453
BEGIN DESCRIPTION:
CANEY CREEK 132.0
END DESCRIPTION:
XS GIS Cut Line= 2
      3561291.41      10594134.8      3563659.44     10596113.95
#Sta/Elev= 30
  2509.4  438.68    2668  428.31    2789  415.44  2930.8  405.23  3029.7  401.24
  3321.2  400.25  3420.2  397.97  3584.1  394.14  3966.7  393.03  3988.8  391.07
  4087.7  393.52  4385.8  394.55  4627.8  392.68    4961  395.81  4983.1  391.85
  4989.6  384.92  4996.1  383.54  5018.2  387.09  5024.7  394.26  5032.5  396.01
  5067.7  395.47  5118.2   398.5  5160.1  403.62  5180.9  403.87    5203  407.28
  5223.8  407.07  5309.1  415.38  5458.1  423.92    5560   432.1  5595.6  435.28
#Mann= 7 ,-1 , 0
  2509.4     .05       0  3420.2     .08       0    4961     .07       0
  5032.5     .12       0  5118.2     .16       0  5309.1     .16       0
    5560     .12       0
Bank Sta=4961,5032.5
XS Rating Curve= 0 ,0
Exp/Cntr=0.3,0.1

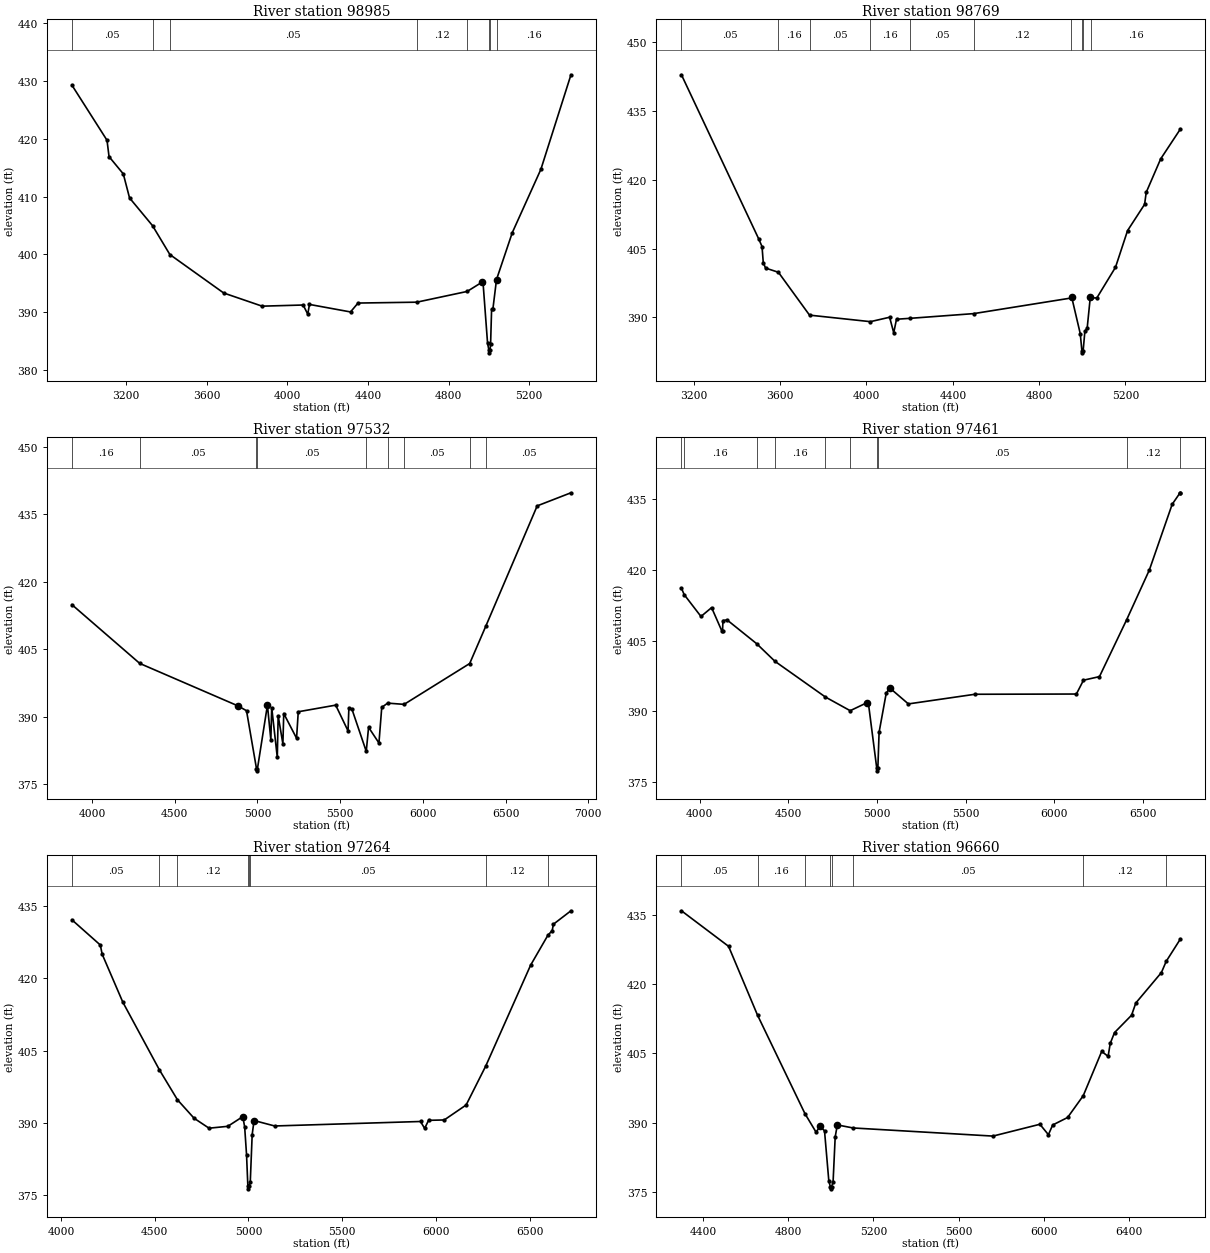
Type RM Length L Ch R = 1 ,98985   ,216,216,216
BEGIN DESCRIPTION:
CANEY CREEK 131.0
END DESCRIPTION:
XS GIS Cut Line= 3
      3561249.63      10594960.2      3563049.61     10596010.19
      3563349.65     10596260.22
#Sta/Elev= 30
  2932.5  429.28  3106.5  419.74  3116.5  416.91  3187.2  413.92  3218.2  409.76
  3332.1  404.96  3418.1  399.96    3685   393.3  3875.6  391.02    4079  391.22
  4101.8  389.64  4110.4  391.32  4313.9  390.02  4351.1  391.56  4642.4  391.71
  4892.2  393.57  4965.5  395.16  4971.3  394.95  4993.2  384.71  4999.7  383.44
  5002.4  382.94  5005.7  383.44  5008.5  384.53  5013.4  390.45  5019.6  390.45
  5037.8  395.63  5037.9  395.64  5115.9  403.74  5257.8  414.71  5406.9  431.08
#Mann= 8 ,-1 , 0
  2932.5     .05       0  3332.1     .16       0  3418.1     .05       0
  4642.4     .12       0  4892.2     .07       0  4999.7     .07       0
  5005.7     .07       0  5037.9     .16       0
Bank Sta=4965.5,5037.8
XS Rating Curve= 0 ,0
Exp/Cntr=0.3,0.1

Type RM Length L Ch R = 1 ,98769   ,1237,1237,1237
BEGIN DESCRIPTION:
CANEY CREEK 130.0
END DESCRIPTION:
XS GIS Cut Line= 2
      3561173.36     10595537.57      3563345.76     10596328.79
#Sta/Elev= 30
  3142.7  442.83  3500.6   407.1  3516.1  405.42  3521.8  401.91  3532.5  400.74
    3592  399.82  3736.1  390.49  4018.2  389.07  4107.2  390.03  4126.2  386.65
  4139.1   389.6  4203.7   389.8  4496.6  390.82  4947.2  394.21  4950.3   394.5
  4990.5  386.44  4997.9  382.78  5000.6  382.28  5003.9  382.78  5011.8  386.95
  5022.5  387.67  5036.8  394.34  5039.9  394.24  5067.3  394.24  5153.7  400.91
  5209.6   408.9  5288.5  414.61    5296  417.22    5363  424.51  5454.7  431.04
#Mann= 10 ,-1 , 0
  3142.7     .05       0    3592     .16       0  3736.1     .05       0
  4018.2     .16       0  4203.7     .05       0  4496.6     .12       0
  4947.2     .07       0  4997.9     .07       0  5003.9     .07       0
  5039.9     .16       0
Bank Sta=4950.3,5036.8
XS Rating Curve= 0 ,0
Exp/Cntr=0.3,0.1

Type RM Length L Ch R = 1 ,97532   ,71,71,71
BEGIN DESCRIPTION:
CANEY CREEK 128.0
END DESCRIPTION:
XS GIS Cut Line= 6
        3560685.     10596141.43      3561195.44     10596258.62
      3561708.46     10596284.66      3562289.19     10596422.68
      3563153.77     10596420.08      3563658.98     10596477.37
#Sta/Elev= 30
  3878.3   414.9  4288.5  401.85  4883.2  392.41  4933.9  391.35  4994.1   378.5
  4996.9     378  5000.1   378.5  5060.3  392.59    5081   384.9  5086.2  392.05
    5120  380.98  5125.2  390.25  5153.8  383.99    5159  390.73  5236.5  385.24
  5246.7  391.12  5473.1  392.59  5547.8  386.86  5552.8  391.97  5570.9  391.74
  5657.9  382.32  5671.8  387.67  5734.6  384.18  5751.5  392.09  5787.3  393.04
  5886.7  392.76  6283.2  401.83  6382.1  410.25  6691.3  436.84  6895.5  439.75
#Mann= 9 ,-1 , 0
  3878.3     .16       0  4288.5     .05       0  4994.1     .04       0
  5000.1     .05       0  5657.9     .12       0  5787.3     .08       0
  5886.7     .05       0  6283.2     .08       0  6382.1     .05       0
Bank Sta=4883.2,5060.3
XS Rating Curve= 0 ,0
Exp/Cntr=0.3,0.1

Type RM Length L Ch R = 1 ,97461   ,197,197,197
BEGIN DESCRIPTION:
CANEY CREEK 129.0
END DESCRIPTION:
XS GIS Cut Line= 6
      3560669.43     10596219.56      3560901.17     10596224.77
      3561195.44     10596344.56      3561833.46      10596373.2
      3562500.13      10596498.2      3563446.35     10596511.17
#Sta/Elev= 30
  3896.3  416.15  3911.4  414.79  4006.5  410.13  4066.5  412.01  4124.8     407
  4128.1     407  4130.5  409.25  4153.6   409.4  4320.9  404.34  4424.3  400.59
  4708.8  393.01  4848.5  390.11  4941.6  391.78  4951.6  391.58  4998.6  377.83
  5001.4  377.33  5004.6  377.83  5011.6  385.53  5051.7   393.8  5071.7  394.94
  5176.8  391.55  5552.4   393.6  6124.9  393.65    6165  396.59  6255.1  397.35
  6408.6  409.44  6536.6     420  6665.4  433.96  6708.5  436.32  6712.2  436.41
#Mann= 10 ,-1 , 0
  3896.3     .05       0  3911.4     .16       0  4320.9     .05       0
  4424.3     .16       0  4708.8     .12       0  4848.5     .05       0
  4998.6     .04       0  5004.6     .05       0  6408.6     .12       0
  6708.5     .16       0
Bank Sta=4941.6,5071.7
XS Rating Curve= 0 ,0
Exp/Cntr=0.3,0.1

Type RM Length L Ch R = 1 ,97264   ,604,604,604
BEGIN DESCRIPTION:
CANEY CREEK 127.0
END DESCRIPTION:
XS GIS Cut Line= 3
      3560798.31     10596530.61      3562013.61     10596572.28
       3563395.1     10597002.69
#Sta/Elev= 30
    4058  432.13  4209.4  426.91  4219.4     425  4329.5  415.06  4525.1  400.99
  4621.2   394.8  4709.7  390.98  4789.7  388.91  4889.8   389.3  4969.8  391.31
  4979.8  389.17  4989.8  383.42  4996.9  376.83  4999.6  376.33  5002.9  376.83
  5009.8  377.83  5019.9   387.6  5029.9   390.5  5139.9  389.37  5918.3   390.3
  5940.2  388.87  5961.3  390.54  6044.9  390.62  6161.6  393.72  6266.6  401.83
  6505.8  422.73  6597.5   428.9    6621  429.91  6627.4  431.22    6721  434.01
#Mann= 8 ,-1 , 0
    4058     .05       0  4525.1     .16       0  4621.2     .12       0
  4996.9     .07       0  5002.9     .12       0  5009.8     .05       0
  6266.6     .12       0  6597.5     .05       0
Bank Sta=4969.8,5029.9
XS Rating Curve= 0 ,0
Exp/Cntr=0.3,0.1

Type RM Length L Ch R = 1 ,96660   ,422,422,422
BEGIN DESCRIPTION:
CANEY CREEK 126.0
END DESCRIPTION:
XS GIS Cut Line= 2
      3560888.57     10597030.61      3563228.93     10597120.89
#Sta/Elev= 30
  4298.8  435.88    4520  428.18    4656  413.25  4878.5  391.92  4930.3  387.93
  4950.3  389.15  4970.3   388.2  4990.4  377.39  4997.4  376.13  5000.1  375.63
  5003.4  376.13  5010.4  377.03  5020.4  386.88  5030.4  389.48  5104.3  388.82
  5760.9  387.06  5981.1  389.62  6021.1  387.36  6041.1  389.46  6111.2  391.09
  6184.5   395.8  6271.3  405.41  6301.3  404.33  6311.3  407.14  6331.3  409.48
  6411.4  413.25  6431.4   415.9  6551.5   422.5  6573.9  424.92  6640.9  429.79
#Mann= 8 ,-1 , 0
  4298.8     .05       0    4656     .16       0  4878.5     .12       0
  4997.4     .07       0  5003.4     .12       0  5104.3     .05       0
  6184.5     .12       0  6573.9     .05       0
Bank Sta=4950.3,5030.4
XS Rating Curve= 0 ,0
Exp/Cntr=0.3,0.1

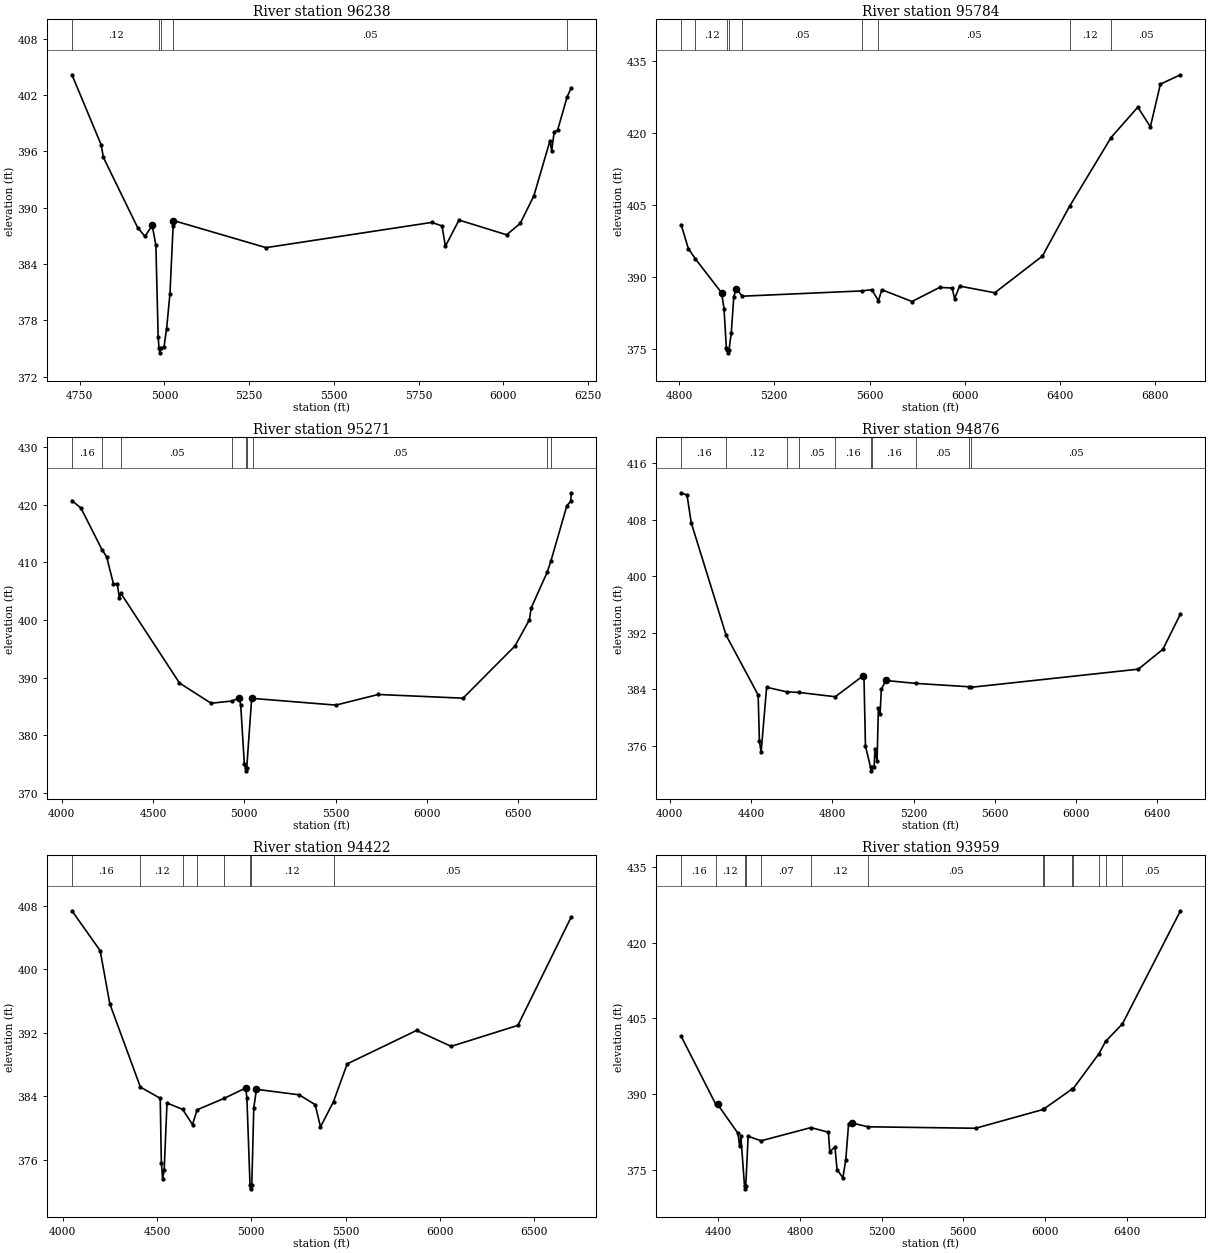
Type RM Length L Ch R = 1 ,96238   ,454,454,454
BEGIN DESCRIPTION:
CANEY CREEK 125.0
END DESCRIPTION:
XS GIS Cut Line= 3
      3561299.63      10597360.2      3561549.61     10597460.19
      3562749.62     10597360.19
#Sta/Elev= 30
  4727.1  404.17  4813.2  396.72    4820  395.36  4920.9  387.89  4942.5  386.95
    4964  388.12  4974.8  386.01  4981.5  376.28  4983.9  375.04  4986.7  374.54
  4989.9  375.04  4998.8  375.15  5006.4  377.12  5016.4  380.86  5025.6  388.02
  5026.4  388.64  5299.9  385.75  5789.1  388.44  5819.2  388.06  5829.2   385.9
  5869.3  388.69  6009.8  387.12    6050  388.33  6090.1  391.26  6137.8  397.14
  6142.8  396.06  6150.3   398.1  6160.4  398.28  6188.6  401.84  6200.5  402.77
#Mann= 5 ,-1 , 0
  4727.1     .12       0  4983.9     .07       0  4989.9     .12       0
  5025.6     .05       0  6188.6     .12       0
Bank Sta=4964,5026.4
XS Rating Curve= 0 ,0
Exp/Cntr=0.3,0.1

Type RM Length L Ch R = 1 ,95784   ,513,513,513
BEGIN DESCRIPTION:
CANEY CREEK 124.0
END DESCRIPTION:
XS GIS Cut Line= 3
      3561199.63     10597860.19      3561399.61     10597860.19
      3563199.56      10597260.2
#Sta/Elev= 30
  4808.8  400.95  4838.8  395.96  4868.7   393.8  4978.8  386.73  4988.8  383.42
  4998.8  375.13  5003.3  374.72    5006  374.22  5009.3  374.72  5019.3  378.36
  5029.9  385.96  5040.4  387.58  5065.5  386.03    5567  387.13  5609.6  387.38
  5637.5  385.08  5651.8  387.38  5778.3  384.92  5894.2  387.85  5946.9  387.74
  5957.5  385.49  5978.5  388.14  6126.1  386.74  6326.4   394.4  6440.2  404.76
  6614.7  419.11    6727  425.44  6779.7  421.34  6821.8  430.24  6906.1  432.19
#Mann= 9 ,-1 , 0
  4808.8     .05       0  4868.7     .12       0  5003.3     .07       0
  5009.3     .12       0  5065.5     .05       0    5567     .16       0
  5637.5     .05       0  6440.2     .12       0  6614.7     .05       0
Bank Sta=4978.8,5040.4
XS Rating Curve= 0 ,0
Exp/Cntr=0.3,0.1

Type RM Length L Ch R = 1 ,95271   ,395,395,395
BEGIN DESCRIPTION:
CANEY CREEK 123.0
END DESCRIPTION:
XS GIS Cut Line= 4
      3560452.92     10598068.33      3561213.33     10598307.91
      3561494.58     10598287.07      3562905.28     10597422.95
#Sta/Elev= 30
  4056.8  420.68  4105.8  419.42  4221.2   412.2  4246.7  410.97  4284.3  406.23
    4305  406.29  4316.6  403.81  4323.6  404.68  4645.5  389.09  4818.7  385.58
  4935.8  385.98  4970.7   386.5  4980.7  385.35  5000.7  375.06  5007.8  374.37
  5010.5  373.87  5013.8  374.37  5040.8  386.43  5046.5  386.42  5501.5  385.26
  5733.7   387.1    6198  386.46  6482.3   395.5  6561.6  400.05  6571.2   402.1
  6659.1  408.31  6679.4  410.25  6766.6  419.82  6787.9  420.58  6790.4  422.05
#Mann= 9 ,-1 , 0
  4056.8     .16       0  4221.2     .12       0  4323.6     .05       0
  4935.8     .16       0  5007.8     .07       0  5013.8     .16       0
  5046.5     .05       0  6659.1     .12       0  6679.4     .05       0
Bank Sta=4970.7,5040.8
XS Rating Curve= 0 ,0
Exp/Cntr=0.3,0.1

Type RM Length L Ch R = 1 ,94876   ,454,454,454
BEGIN DESCRIPTION:
CANEY CREEK 122.0
END DESCRIPTION:
XS GIS Cut Line= 3
      3560825.05      10599375.3      3561399.61     10598610.19
      3562599.59      10597710.2
#Sta/Elev= 30
  4056.7  411.82  4085.6  411.48  4106.4  407.56  4277.9  391.67  4435.5  383.22
  4441.7   376.7  4450.1  375.11  4477.2  384.31  4576.6  383.66  4634.2  383.59
  4814.9  382.97    4950  385.89  4956.2  385.79  4963.5     376  4988.7  372.99
  4991.4  372.49  4994.7  372.99  5006.2  373.05  5010.4  375.52  5020.8  373.85
  5027.1  381.37  5035.4  380.49  5041.6     384  5063.5  385.27  5210.5  384.86
  5474.7  384.38  5481.1   384.3  6306.2  386.87  6427.1  389.68  6513.5  394.68
#Mann= 10 ,-1 , 0
  4056.7     .16       0  4277.9     .12       0  4576.6     .16       0
  4634.2     .05       0  4814.9     .16       0  4988.7     .07       0
  4994.7     .16       0  5210.5     .05       0  5474.7     .08       0
  5481.1     .05       0
Bank Sta=4950,5063.5
XS Rating Curve= 0 ,0
Exp/Cntr=0.3,0.1

Type RM Length L Ch R = 1 ,94422   ,463,463,463
BEGIN DESCRIPTION:
CANEY CREEK 121.0
END DESCRIPTION:
XS GIS Cut Line= 3
      3560809.85     10599488.15      3561599.61     10598960.19
      3562799.58     10597760.22
#Sta/Elev= 30
  4048.9  407.34  4198.6  402.32  4249.6  395.63  4411.8  385.14  4516.9  383.73
  4522.9  375.64  4529.8  373.57  4537.9  374.73  4552.9  383.14  4635.7  382.33
  4688.1  380.43  4712.5  382.28  4855.5  383.72  4970.4  385.03  4976.4  383.79
  4992.9  372.83  4995.6  372.33  4998.9  372.83  5002.4  372.83    5013  382.54
  5027.2  384.86  5253.4  384.17  5338.3  382.93  5366.6  380.13  5435.8  383.32
    5508  388.06  5875.7  392.27  6059.5  390.27  6413.1  392.91  6695.9  406.56
#Mann= 8 ,-1 , 0
  4048.9     .16       0  4411.8     .12       0  4635.7     .05       0
  4712.5     .07       0  4855.5     .12       0  4992.9     .07       0
  4998.9     .12       0  5435.8     .05       0
Bank Sta=4970.4,5027.2
XS Rating Curve= 0 ,0
Exp/Cntr=0.3,0.1

Type RM Length L Ch R = 1 ,93959   ,516,516,516
BEGIN DESCRIPTION:
CANEY CREEK 120.0
END DESCRIPTION:
XS GIS Cut Line= 3
      3561499.59     10599760.22      3561949.61     10599160.19
      3563149.61     10597960.18
#Sta/Elev= 30
  4217.2  401.45    4387  387.95  4395.4  387.98  4495.4  382.23  4503.7  379.67
  4509.9  381.59  4527.8  371.72  4530.5  371.22  4533.8  371.72  4545.4  381.64
  4609.1  380.74  4853.2  383.35  4939.1  382.43  4945.4  378.55  4970.8  379.52
  4981.4  375.02  5009.7  373.42  5023.8  376.87  5037.9  384.14  5052.1  384.28
  5132.7  383.51  5660.2  383.22  5992.3  386.95  5997.5  387.12  6130.9  390.92
  6137.9  391.03  6264.4  397.97  6297.7  400.43  6379.9   403.9  6664.3   426.3
#Mann= 14 ,-1 , 0
  4217.2     .16       0    4387     .12       0  4527.8     .07       0
  4533.8     .12       0  4609.1     .07       0  4853.2     .12       0
  5132.7     .05       0  5992.3      .1       0  5997.5     .08       0
  6130.9     .05       0  6137.9      .1       0  6264.4     .05       0
  6297.7     .08       0  6379.9     .05       0
Bank Sta=4395.4,5052.1
XS Rating Curve= 0 ,0
Exp/Cntr=0.3,0.1