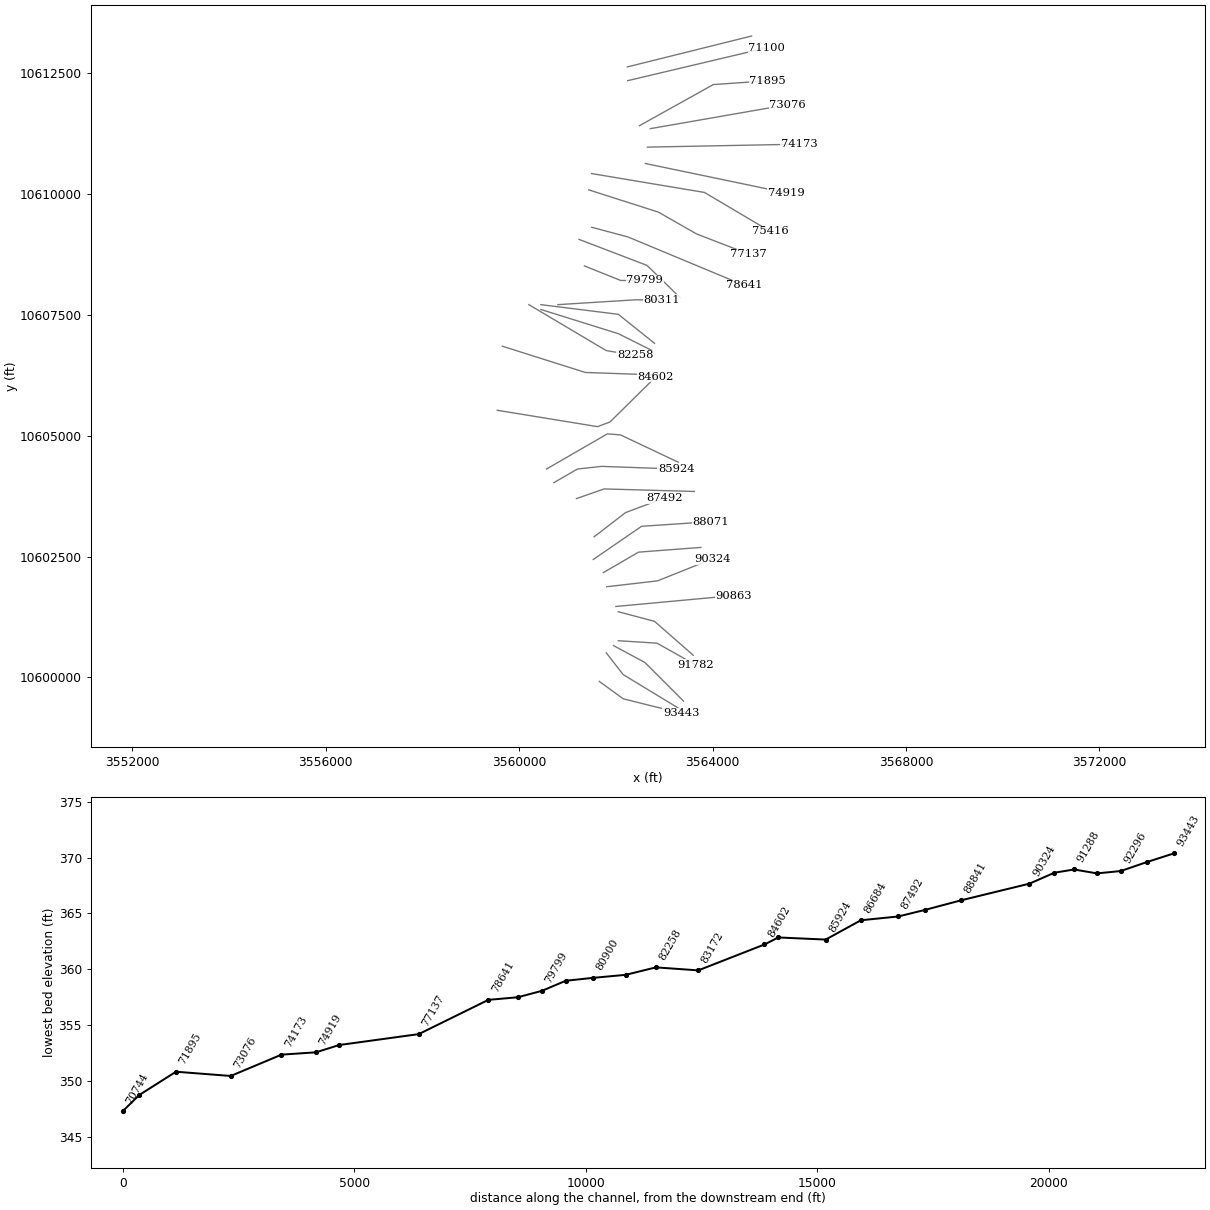
HEC-RAS study CANEY CREEK.prj: CANEY CREEK Base Level Engineering

--- CANEY CREEK.g01 (geometry) --- (continued)

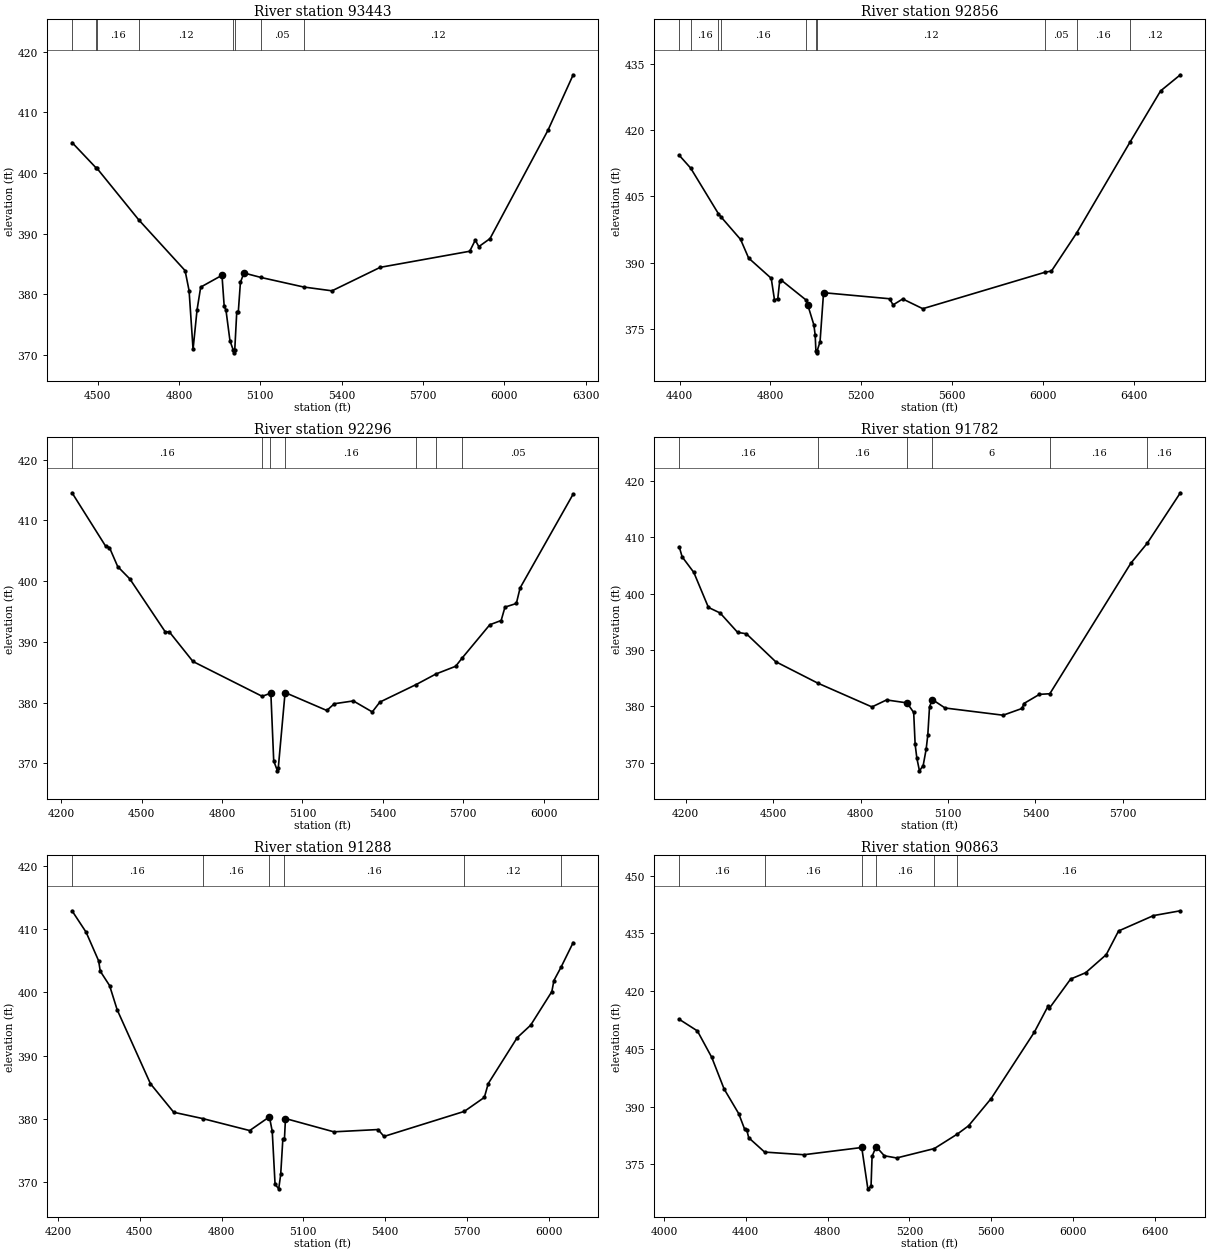
Type RM Length L Ch R = 1 ,93443   ,587,587,587
BEGIN DESCRIPTION:
CANEY CREEK 119.0
END DESCRIPTION:
XS GIS Cut Line= 3
      3561656.15     10599919.28      3562149.61     10599560.19
      3563349.59     10599260.19
#Sta/Elev= 30
    4406  405.03  4495.5  400.81  4497.3  400.81  4651.6   392.3  4822.7  383.92
  4837.4  380.63  4852.1  370.95  4866.8  377.45  4880.2   381.2  4958.7  383.15
  4966.8  378.07  4973.4   377.4  4988.1  372.37  4999.8  370.87  5002.5  370.37
  5005.8  370.87  5013.2  377.14  5018.9  377.14  5026.6  381.97  5039.5  383.53
  5102.6  382.79  5259.5  381.22  5364.2  380.59    5542  384.46  5871.8  387.11
  5892.4  388.95  5905.3  387.87  5946.6  389.19  6160.4  407.06  6253.2  416.19
#Mann= 8 ,-1 , 0
    4406     .16       0  4495.5     .12       0  4497.3     .16       0
  4651.6     .12       0  4999.8     .07       0  5005.8     .12       0
  5102.6     .05       0  5259.5     .12       0
Bank Sta=4958.7,5039.5
XS Rating Curve= 0 ,0
Exp/Cntr=0.3,0.1

Type RM Length L Ch R = 1 ,92856   ,560,560,560
BEGIN DESCRIPTION:
CANEY CREEK 118.0
END DESCRIPTION:
XS GIS Cut Line= 3
      3561799.63     10600510.16      3562149.61     10600060.19
      3563549.62     10599210.18
#Sta/Elev= 30
  4398.5  414.26  4448.8  411.37  4571.1  401.05  4581.7  400.38    4669  395.22
  4704.3  391.02  4803.9  386.44  4818.3  381.55  4832.8  381.83    4841  385.75
  4847.3  386.06  4956.7  381.56  4965.4  380.32  4991.8   375.9  4997.6  373.57
  5000.6  370.09  5003.4  369.59  5006.6  370.09    5019  372.12  5034.4  383.19
  5325.2  381.82  5340.7  380.43  5383.3  381.77  5471.6  379.57  6009.3   387.8
  6038.5  388.08  6149.3  396.67  6384.2   417.2  6519.2  428.81  6606.4  432.46
#Mann= 10 ,-1 , 0
  4398.5     .12       0  4448.8     .16       0  4571.1     .12       0
  4581.7     .16       0  4956.7     .12       0  5000.6     .07       0
  5006.6     .12       0  6009.3     .05       0  6149.3     .16       0
  6384.2     .12       0
Bank Sta=4965.4,5034.4
XS Rating Curve= 0 ,0
Exp/Cntr=0.3,0.1

Type RM Length L Ch R = 1 ,92296   ,514,514,514
BEGIN DESCRIPTION:
CANEY CREEK 117.0
END DESCRIPTION:
XS GIS Cut Line= 3
      3561949.59      10600660.2      3562599.61     10600310.19
      3563399.58     10599510.21
#Sta/Elev= 30
  4240.4  414.53  4365.4  405.77    4380  405.52  4410.8  402.39  4456.2  400.35
  4587.6  391.69  4603.9  391.62  4691.5  386.78  4949.7  381.05  4978.7  381.52
  4982.2  381.52  4992.8  370.42  5006.7  368.79  5009.9  369.29  5035.2  381.67
  5190.8  378.72  5219.1  379.83  5289.8  380.29  5360.5  378.48  5388.8   380.1
  5524.4  382.99  5598.4  384.73  5671.6  385.99  5694.9   387.3  5798.9  392.82
  5841.3  393.52  5855.5  395.72  5897.9  396.32    5912  398.88    6110  414.32
#Mann= 7 ,-1 , 0
  4240.4     .16       0  4949.7     .16       0  4978.7     .16       0
  5035.2     .16       0  5524.4     .16       0  5598.4     .12       0
  5694.9     .05       0
Bank Sta=4982.2,5035.2
XS Rating Curve= 0 ,0
Exp/Cntr=0.3,0.1

Type RM Length L Ch R = 1 ,91782   ,494,494,494
BEGIN DESCRIPTION:
CANEY CREEK 116.0
END DESCRIPTION:
XS GIS Cut Line= 3
      3562049.59     10600760.19      3562849.61     10600710.19
      3563649.64     10600260.17
#Sta/Elev= 30
  4177.6  408.35  4187.6  406.56  4227.7  403.79  4277.8  397.58  4317.9  396.59
    4378  393.15  4408.1   392.9  4508.3  387.96  4652.4  384.16  4838.9  379.92
    4889  381.16  4959.1  380.64  4982.1  378.94  4987.1  373.27  4992.9  370.86
  5001.9  368.58  5014.6   369.5  5024.8  372.39  5030.5  374.91  5036.5  379.98
  5046.4  381.22  5089.8  379.73    5289  378.45  5354.3  379.66    5360  380.52
  5413.6  382.15  5449.2  382.26  5727.2  405.42  5783.5  408.97  5897.1  417.92
#Mann= 6 ,-1 , 0
  4177.6     .16       0  4652.4     .16       0  4959.1     .12       0
  5046.4       6       0  5449.2     .16       0  5783.5     .16       0
Bank Sta=4959.1,5046.4
XS Rating Curve= 0 ,0
Exp/Cntr=0.3,0.1

Type RM Length L Ch R = 1 ,91288   ,425,425,425
BEGIN DESCRIPTION:
CANEY CREEK 115.0
END DESCRIPTION:
XS GIS Cut Line= 3
      3562049.62     10601360.18      3562799.61     10601160.19
       3563599.6     10600460.19
#Sta/Elev= 30
  4251.3  412.87    4303  409.48    4349  404.95  4354.8  403.33  4389.1  401.05
  4416.9  397.23  4539.1  385.54  4624.5  381.03  4731.1  380.03  4903.3  378.14
  4975.7  380.31  4986.1     378  4996.4  369.65  5009.8  368.93  5017.1  371.21
  5024.9  376.74  5030.8  376.74  5034.6  380.04  5212.1  377.94  5374.4   378.3
  5396.2  377.21    5691  381.17  5764.5  383.38  5778.7  385.56    5885  392.82
  5934.4  394.79  6012.2   400.1  6019.8  401.85  6045.4  403.91  6090.5  407.85
#Mann= 6 ,-1 , 0
  4251.3     .16       0  4731.1     .16       0  4975.7     .12       0
  5030.8     .16       0    5691     .12       0  6045.4     .16       0
Bank Sta=4975.7,5034.6
XS Rating Curve= 0 ,0
Exp/Cntr=0.3,0.1

Type RM Length L Ch R = 1 ,90863   ,539,539,539
BEGIN DESCRIPTION:
CANEY CREEK 114.0
END DESCRIPTION:
XS GIS Cut Line= 2
      3562001.23     10601468.77      3564440.41     10601694.46
#Sta/Elev= 30
  4074.5  412.69  4163.3  409.67  4233.6  402.79  4293.8   394.6  4365.2  388.19
  4394.2  384.15  4404.3  384.02  4414.3  381.91    4492  378.19  4683.7   377.5
  4966.7  379.38  4996.6  368.64  5012.2  369.33  5017.2  377.07    5037  379.62
  5077.1  377.23  5137.4  376.66  5321.4   379.1    5434  382.87  5488.9  385.02
  5599.4  392.11  5810.3  409.34  5878.2  416.19  5883.2  415.51  5987.7  423.14
  6061.3  424.79  6161.8  429.48    6222  435.63  6392.7  439.63  6524.1  440.88
#Mann= 6 ,-1 , 0
  4074.5     .16       0    4492     .16       0  4966.7     .12       0
    5037     .16       0  5321.4     .16       0    5434     .16       0
Bank Sta=4966.7,5037
XS Rating Curve= 0 ,0
Exp/Cntr=0.3,0.1

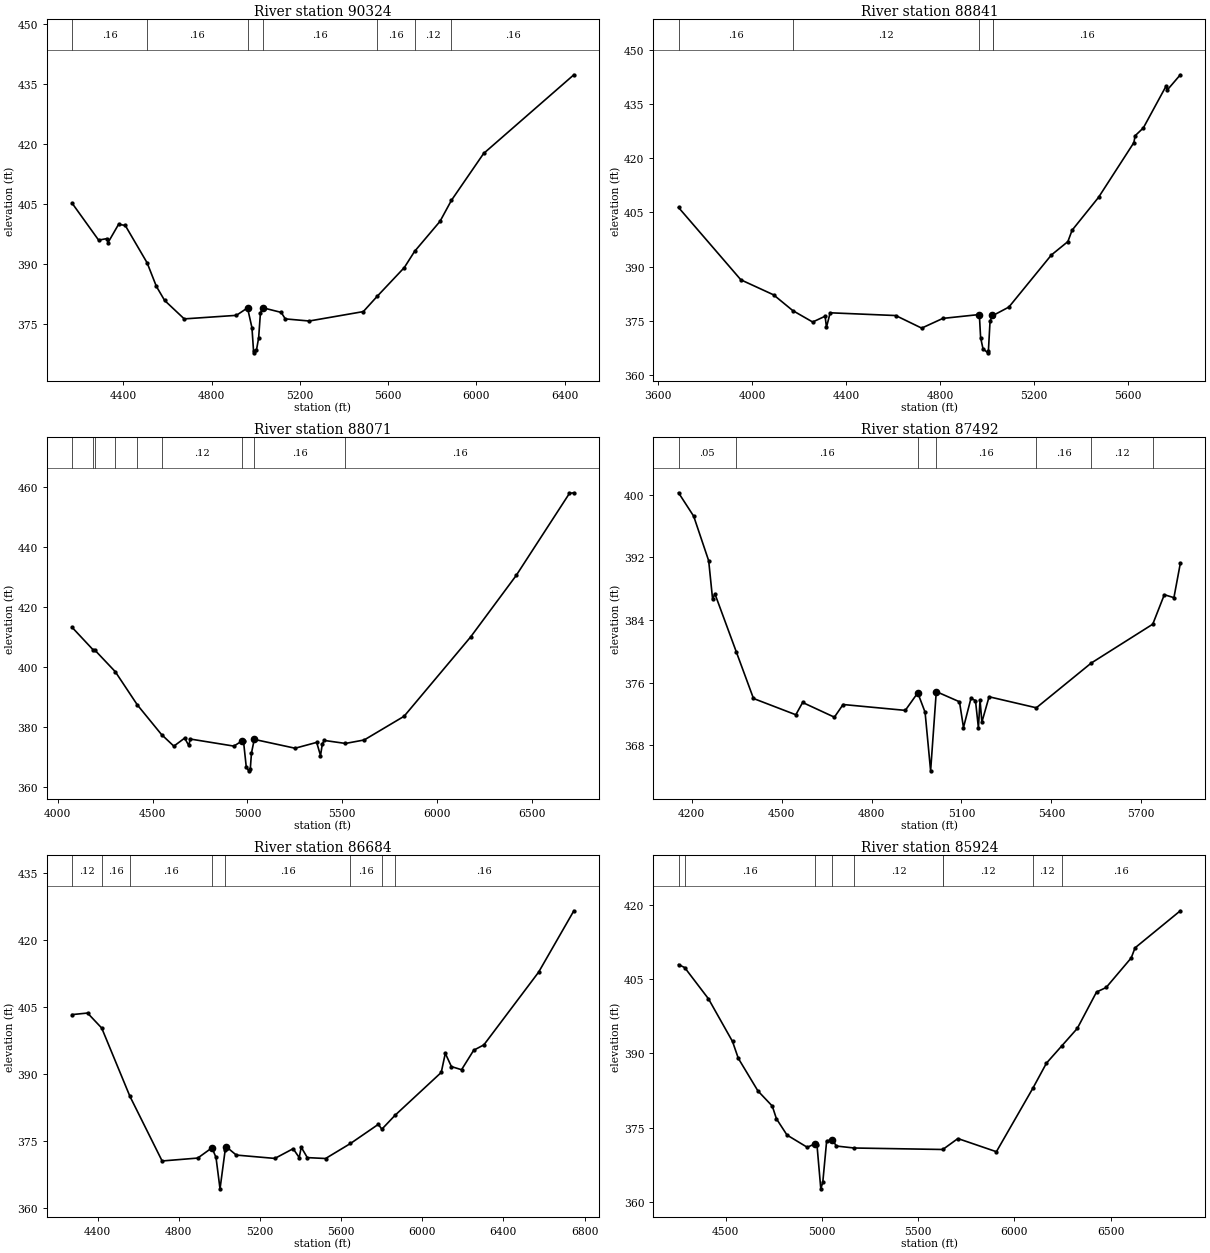
Type RM Length L Ch R = 1 ,90324   ,1483,1483,1483
BEGIN DESCRIPTION:
CANEY CREEK 113.0
END DESCRIPTION:
XS GIS Cut Line= 3
      3561810.22     10601876.75      3562860.57     10601998.28
      3563989.08     10602449.68
#Sta/Elev= 30
  4168.3  405.19  4288.5  395.92  4326.2   396.3  4331.2   395.3  4379.1  399.89
  4409.3  399.59  4508.2  390.23  4550.2  384.32  4587.6  380.79  4676.4  376.17
  4912.6  377.06    4963  378.93  4983.1  373.95  4990.2  368.16  4992.9  367.66
  5003.2  368.27  5013.3  371.38  5021.5   377.7  5033.4  378.94  5115.4   377.8
  5134.1  376.17  5242.5  375.64  5487.5     378  5550.3  381.83  5673.3  389.05
  5719.5  393.08  5834.9  400.63  5886.6   405.9  6032.4  417.64  6441.1  437.37
#Mann= 7 ,-1 , 0
  4168.3     .16       0  4508.2     .16       0    4963     .12       0
  5033.4     .16       0  5550.3     .16       0  5719.5     .12       0
  5886.6     .16       0
Bank Sta=4963,5033.4
XS Rating Curve= 0 ,0
Exp/Cntr=0.3,0.1

Type RM Length L Ch R = 1 ,88841   ,770,770,770
BEGIN DESCRIPTION:
CANEY CREEK 112.0
END DESCRIPTION:
XS GIS Cut Line= 3
      3561740.27     10602168.99      3562467.26     10602592.17
      3563756.59     10602689.68
#Sta/Elev= 30
  3687.9  406.38  3953.1  386.36  4092.1  382.21  4173.8  377.85  4258.4  374.69
  4311.3  376.29  4317.1  373.24  4332.8  377.24  4611.7  376.48    4722     373
  4812.2  375.69  4967.3  376.76  4972.7  370.34  4982.7  367.35  5002.5  366.16
  5005.8  366.66  5012.8   374.9  5022.8  376.52  5023.8  376.44    5093  378.83
  5273.6  393.23  5343.8  396.94  5361.8  400.09  5474.1  409.17  5624.6  424.34
  5629.8  426.23  5664.7  428.39  5761.3  439.95  5766.3  438.87  5822.1   443.1
#Mann= 5 ,-1 , 0
  3687.9     .16       0  4173.8     .12       0  4967.3     .12       0
  5023.8     .12       0  5023.8     .16       0
Bank Sta=4967.3,5022.8
XS Rating Curve= 0 ,0
Exp/Cntr=0.3,0.1

Type RM Length L Ch R = 1 ,88071   ,579,579,579
BEGIN DESCRIPTION:
CANEY CREEK 111.0
END DESCRIPTION:
XS GIS Cut Line= 3
      3561532.41     10602440.97      3562530.71     10603126.75
      3563962.97     10603222.24
#Sta/Elev= 30
  4075.2  413.24  4186.1  405.73  4196.8  405.53    4303  398.43  4419.8   387.3
  4546.9  377.44  4612.1  373.55  4668.9  376.24  4690.5   373.8  4698.7  375.93
  4928.7  373.57  4970.7  375.26  4979.5  375.12  4993.8  366.69  5006.3  365.31
  5015.4  366.08  5021.4  371.26  5036.3  375.81  5251.5  372.86  5365.4  374.81
  5385.5  370.41  5395.5  374.39  5405.5  375.46  5517.3  374.46    5616  375.62
  5826.5  383.54  6177.2  410.01  6417.8  430.57  6698.4  457.97  6721.8  458.17
#Mann= 9 ,-1 , 0
  4075.2      .1       0  4186.1     .05       0  4196.8      .1       0
    4303     .05       0  4419.8     .16       0  4546.9     .12       0
  4970.7     .12       0  5036.3     .16       0  5517.3     .16       0
Bank Sta=4970.7,5036.3
XS Rating Curve= 0 ,0
Exp/Cntr=0.3,0.1

Type RM Length L Ch R = 1 ,87492   ,808,808,808
BEGIN DESCRIPTION:
CANEY CREEK 110.0
END DESCRIPTION:
XS GIS Cut Line= 3
       3561549.6     10602910.18      3562199.61     10603410.19
      3562999.64      10603710.2
#Sta/Elev= 30
  4155.9  400.27  4206.4  397.28  4256.5  391.58  4269.5  386.69  4277.3  387.35
  4348.3  379.97    4406  373.97  4547.3  371.89    4570  373.46    4676  371.58
    4705   373.2  4912.6  372.45  4954.2  374.69  4978.6  372.22  4997.1  364.72
    5016  374.85  5093.4  373.55  5106.8  370.26  5131.7  373.98  5146.8  373.71
  5156.6  370.22    5162  373.78  5168.2  370.95  5192.2  374.19  5349.9  372.78
  5533.1   378.5  5738.4  383.47    5777  387.24    5809  386.86  5830.4  391.25
#Mann= 7 ,-1 , 0
  4155.9     .05       0  4348.3     .16       0  4954.2     .12       0
    5016     .16       0  5349.9     .16       0  5533.1     .12       0
  5738.4     .16       0
Bank Sta=4954.2,5016
XS Rating Curve= 0 ,0
Exp/Cntr=0.3,0.1

Type RM Length L Ch R = 1 ,86684   ,760,760,760
BEGIN DESCRIPTION:
CANEY CREEK 109.0
END DESCRIPTION:
XS GIS Cut Line= 3
      3561183.83     10603699.67      3561756.75     10603899.32
      3563623.11     10603847.24
#Sta/Elev= 30
  4273.7  403.33    4350  403.68  4419.9  400.32  4558.8  385.07  4717.6  370.61
  4893.3  371.26  4963.3  373.55  4983.3   371.4  5003.1  364.38  5028.5  373.05
  5033.5   373.8  5083.3  371.93  5273.4  371.18  5363.5  373.35  5393.5  371.37
  5403.5  373.68  5433.5  371.36  5523.5  371.16  5646.3  374.52  5783.6   378.8
  5800.9  377.71  5865.7  380.81  6093.7   390.4  6113.7  394.67  6143.8  391.71
  6193.8  391.01  6253.8  395.37  6303.8  396.56  6573.9  412.83  6747.5  426.54
#Mann= 8 ,-1 , 0
  4273.7     .12       0  4419.9     .16       0  4558.8     .16       0
  4963.3     .12       0  5028.5     .16       0  5646.3     .16       0
  5800.9     .12       0  5865.7     .16       0
Bank Sta=4963.3,5033.5
XS Rating Curve= 0 ,0
Exp/Cntr=0.3,0.1

Type RM Length L Ch R = 1 ,85924   ,1022,1022,1022
BEGIN DESCRIPTION:
CANEY CREEK 107.0
END DESCRIPTION:
XS GIS Cut Line= 4
      3560716.73     10604029.15        3561205.     10604311.26
      3561704.13     10604365.51       3563244.8     10604311.26
#Sta/Elev= 30
  4254.9  407.96  4286.7  407.36  4410.5  401.04  4535.4  392.42  4565.5  389.02
  4667.5  382.43  4742.1  379.37  4763.7   376.8  4818.6  373.52    4924  371.04
  4964.3  371.77  4974.3  371.54  4994.2  362.65  5004.5  363.97  5024.6  372.34
  5054.8  372.56  5074.9   371.3  5167.3   370.9  5628.1   370.6  5706.6  372.81
  5906.7  370.15  6096.8  383.02  6166.9  388.05  6245.5  391.49    6327  395.06
    6427  402.41  6477.1  403.33  6607.2   409.3  6627.2  411.34  6862.5  418.83
#Mann= 9 ,-1 , 0
  4254.9     .12       0  4286.7     .16       0  4964.3     .12       0
  5054.8     .16       0  5167.3     .12       0  5628.1     .05       0
  5628.1     .12       0  6096.8     .12       0  6245.5     .16       0
Bank Sta=4964.3,5054.8
XS Rating Curve= 0 ,0
Exp/Cntr=0.3,0.1

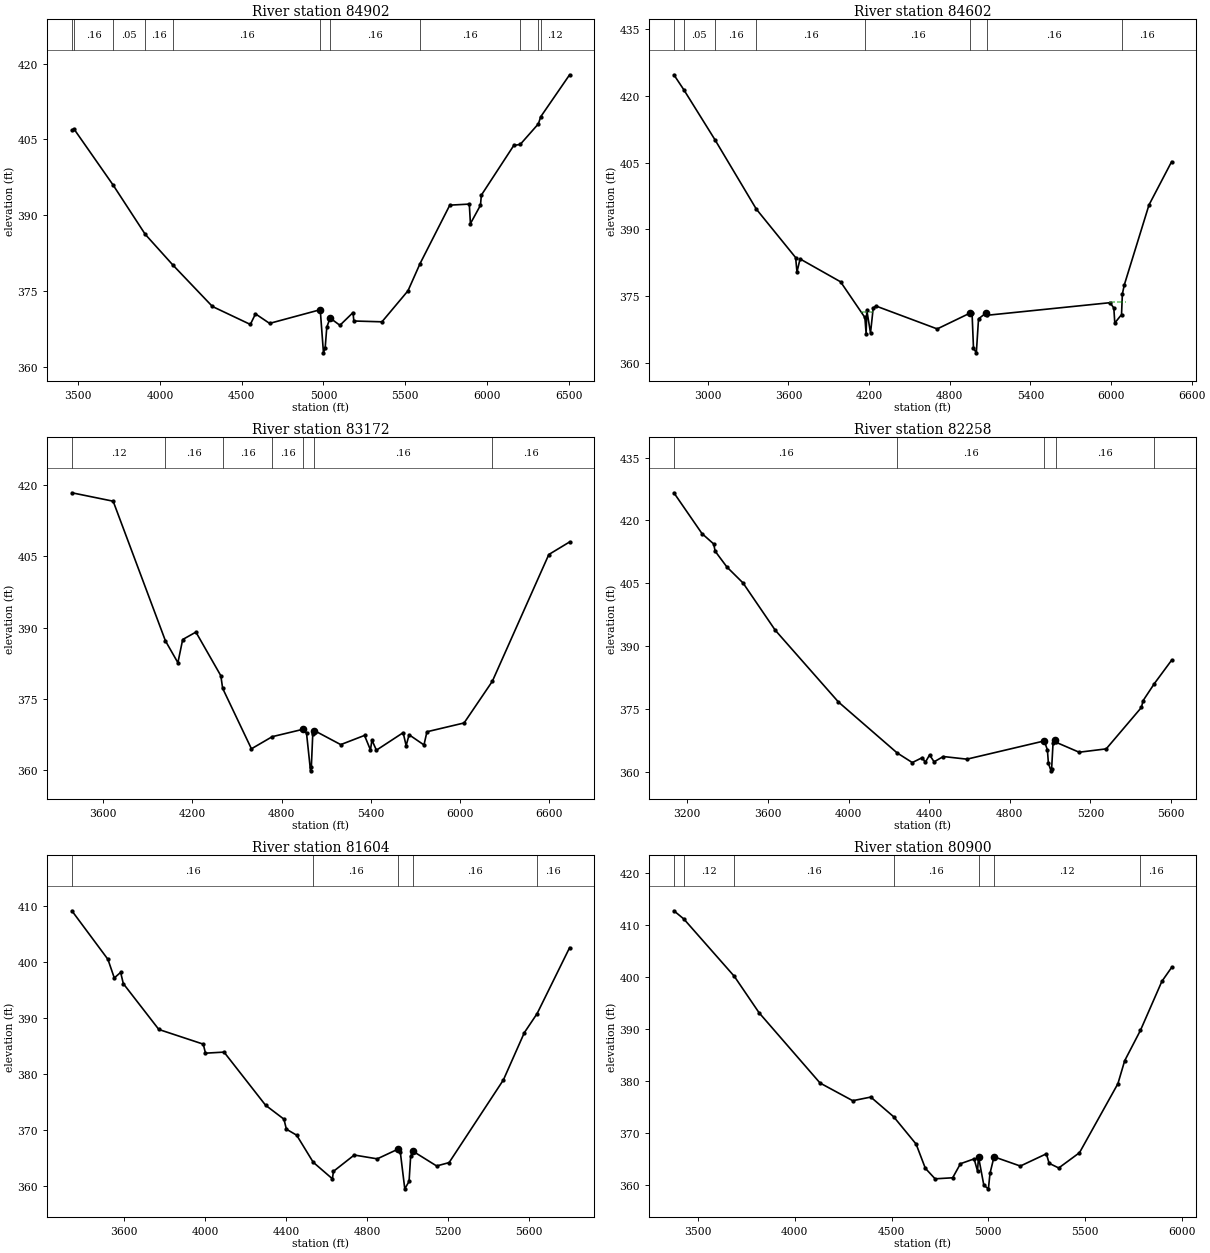
Type RM Length L Ch R = 1 ,84902   ,300,300,300
BEGIN DESCRIPTION:
CANEY CREEK 105.0
END DESCRIPTION:
XS GIS Cut Line= 4
       3560564.8     10604311.26      3561823.49     10605038.26
      3562094.76     10605016.55      3563288.33     10604452.32
#Sta/Elev= 30
  3460.4  406.81  3473.5  407.06  3713.7  395.95  3909.3  386.26    4078  380.21
  4320.5     372  4552.6  368.45  4584.1  370.54  4670.3  368.66  4980.3  371.36
  5000.1  362.84  5010.4  363.78  5020.4   367.9  5040.5  369.72  5100.7  368.28
  5180.9   370.8    5186  369.13    5358  368.97  5517.3   375.1  5591.1  380.47
  5773.2  392.02  5892.5  392.23  5899.4  388.37  5960.8     392  5966.3     394
  6164.8  403.82  6204.2  404.02  6315.4  408.09  6329.4  409.48  6506.3  417.78
#Mann= 11 ,-1 , 0
  3460.4     .12       0  3473.5     .16       0  3713.7     .05       0
  3909.3     .16       0    4078     .16       0  4980.3     .12       0
  5040.5     .16       0  5591.1     .16       0  6204.2     .12       0
  6315.4     .16       0  6329.4     .12       0
Bank Sta=4980.3,5040.5
XS Rating Curve= 0 ,0
Exp/Cntr=0.3,0.1

Type RM Length L Ch R = 1 ,84602   ,1430,1430,1430
BEGIN DESCRIPTION:
CANEY CREEK 104.0
END DESCRIPTION:
XS GIS Cut Line= 4
      3559545.55     10605526.06      3561620.23     10605187.51
       3561876.3       10605283.      3562822.02     10606215.71
#Sta/Elev= 30
  2747.1  424.75  2820.1  421.43  3052.8  410.14  3360.5  394.54    3653  383.64
  3663.1   380.4  3686.2  383.33  3987.4  378.19  4168.4  370.16  4177.7   366.5
  4182.8  371.81  4210.3  366.67  4230.5  372.32  4250.8  372.74  4706.7  367.59
  4953.5  371.19    4966  371.07  4976.6  363.25  4997.7  362.21  5014.1  369.86
  5069.4  371.16  5074.8  370.65  5992.6  373.49  6020.9  372.29    6028  368.92
  6078.1  370.81  6084.5  375.47  6098.7  377.48  6282.5  395.48  6450.8   405.2
#Mann= 8 ,-1 , 0
  2747.1     .12       0  2820.1     .05       0  3052.8     .16       0
  3360.5     .16       0  4168.4     .16       0  4953.5     .12       0
  5074.8     .16       0  6078.1     .16       0
#XS Ineff= 2 ,-1
 4147.73 4231.82  371.39 5990.91 6109.09  373.58
Permanent Ineff=
       F       F
Bank Sta=4953.5,5069.4
XS Rating Curve= 0 ,0
Exp/Cntr=0.3,0.1

Type RM Length L Ch R = 1 ,83172   ,914,914,914
BEGIN DESCRIPTION:
CANEY CREEK 103.0
END DESCRIPTION:
XS GIS Cut Line= 3
       3559653.4     10606850.31      3561367.76     10606307.79
      3562919.46     10606253.53
#Sta/Elev= 30
  3388.6  418.31  3666.6  416.54  4018.5   387.2  4102.4  382.61  4134.7  387.48
  4223.7  389.04  4391.5  379.87  4403.6  377.23  4597.4  364.52  4737.7  367.07
  4947.5  368.64  4968.5  367.75  4995.3  359.89  5000.8  360.73  5010.4  367.68
  5020.9  368.35  5198.6   365.4  5358.7  367.33  5398.7  364.28  5408.7  366.34
  5438.8  364.23  5618.9  367.91  5638.9  365.18  5658.9  367.47    5759  365.33
    5779   368.1  6029.1  369.95  6219.2   378.7  6599.5  405.34  6739.4  407.98
#Mann= 7 ,-1 , 0
  3388.6     .12       0  4018.5     .16       0  4403.6     .16       0
  4737.7     .16       0  4947.5     .12       0  5020.9     .16       0
  6219.2     .16       0
Bank Sta=4947.5,5020.9
XS Rating Curve= 0 ,0
Exp/Cntr=0.3,0.1

Type RM Length L Ch R = 1 ,82258   ,654,654,654
BEGIN DESCRIPTION:
CANEY CREEK 101.0
END DESCRIPTION:
XS GIS Cut Line= 3
      3560199.59      10607710.2      3561799.61     10606760.19
      3562399.63     10606660.18
#Sta/Elev= 30
  3133.6  426.62  3273.2  416.86  3331.3  414.38  3338.2  412.67  3396.7  408.88
  3476.6  405.07  3636.3  393.78    3950  376.61    4241  364.45  4316.3  362.14
  4366.4  363.33  4380.6  362.17    4402  363.96  4424.5  362.32  4470.3  363.58
  4587.2  362.95  4971.1  367.31  4986.6  365.16  4991.5  361.98  5004.3  360.16
  5007.5  360.66  5014.7  366.93  5022.3  367.46  5027.3  367.03  5143.9  364.61
  5278.3  365.41  5453.1  375.32  5460.7   376.9  5516.9     381  5602.7   386.6
#Mann= 5 ,-1 , 0
  3133.6     .16       0    4241     .16       0  4971.1     .12       0
  5027.3     .16       0  5516.9     .16       0
Bank Sta=4971.1,5022.3
XS Rating Curve= 0 ,0
Exp/Cntr=0.3,0.1

Type RM Length L Ch R = 1 ,81604   ,704,704,704
BEGIN DESCRIPTION:
CANEY CREEK 100.0
END DESCRIPTION:
XS GIS Cut Line= 3
      3560449.57      10607610.2      3562049.61     10607110.19
      3562749.64     10606760.17
#Sta/Elev= 30
  3341.5  409.09  3519.6  400.43  3551.1  397.11  3582.5   398.1  3595.6   396.1
  3771.1  387.92  3990.6   385.3  4001.6  383.69  4093.3  383.88  4298.6   374.4
  4389.2  371.92  4401.3  370.13  4452.1  369.06  4533.9  364.23  4628.6  361.28
  4633.9  362.61  4736.5  365.52  4850.2  364.84    4955  366.61  4963.9  366.11
  4986.2  359.49  5007.4  360.82  5015.2  365.26  5026.2  366.21  5143.6  363.57
  5205.1  364.17  5473.4  378.92  5576.9  387.35    5640  390.75  5800.5  402.51
#Mann= 5 ,-1 , 0
  3341.5     .16       0  4533.9     .16       0    4955     .12       0
  5026.2     .16       0    5640     .16       0
Bank Sta=4955,5026.2
XS Rating Curve= 0 ,0
Exp/Cntr=0.3,0.1

Type RM Length L Ch R = 1 ,80900   ,589,589,589
BEGIN DESCRIPTION:
CANEY CREEK 99.0
END DESCRIPTION:
XS GIS Cut Line= 3
      3560449.61     10607710.19      3562049.61     10607510.19
      3562799.59      10606910.2
#Sta/Elev= 30
  3374.9  412.79  3426.1  411.22  3687.4  400.16  3815.8  393.12  4130.7   379.6
  4299.5   376.2  4392.8   376.9    4511  373.11  4627.1  367.84  4674.9  363.17
  4725.3  361.15    4816  361.35  4856.3  364.06  4926.9  364.99  4944.5  362.65
  4949.6  365.39  4977.3  359.89  5000.7  359.22    5009  362.19  5029.8  365.39
  5165.8  363.61  5300.3  365.97  5314.7  364.14  5364.3  363.24  5471.6  366.18
  5670.1  379.47  5705.3  383.91  5786.9  389.77  5897.4  399.19  5947.8  401.87
#Mann= 7 ,-1 , 0
  3374.9     .16       0  3426.1     .12       0  3687.4     .16       0
    4511     .16       0  4949.6     .16       0  5029.8     .12       0
  5786.9     .16       0
Bank Sta=4949.6,5029.8
XS Rating Curve= 0 ,0
Exp/Cntr=0.3,0.1

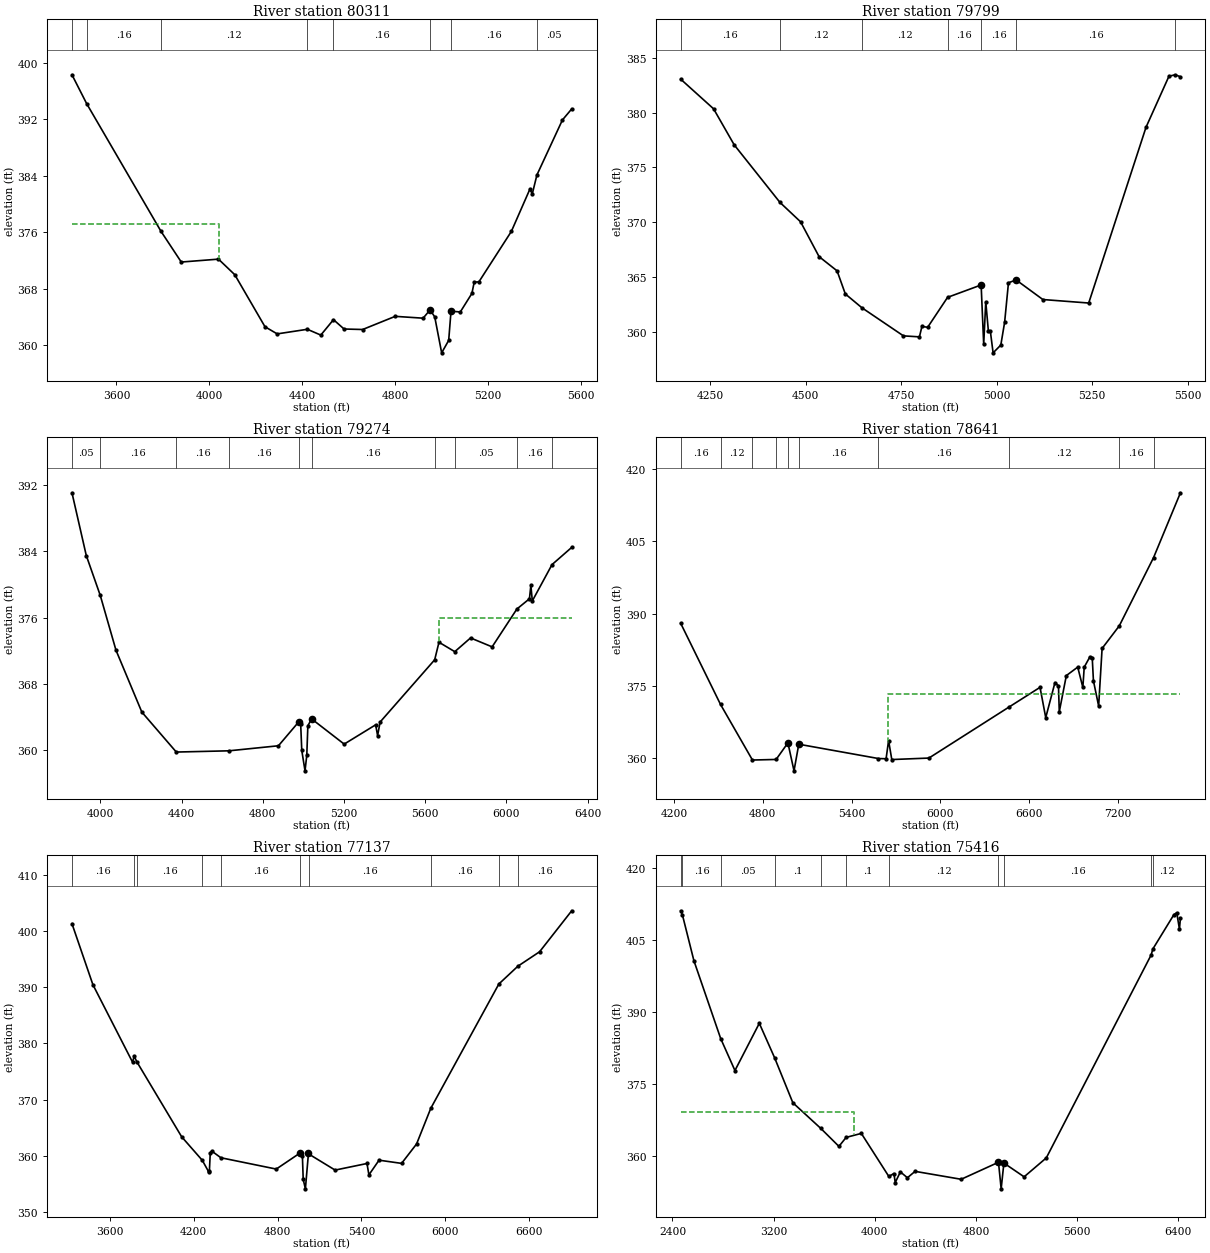
Type RM Length L Ch R = 1 ,80311   ,512,512,512
BEGIN DESCRIPTION:
CANEY CREEK 98.0
END DESCRIPTION:
XS GIS Cut Line= 3
      3560799.62     10607710.19      3562399.61     10607810.19
      3562949.59     10607810.19
#Sta/Elev= 30
  3408.6  398.28  3472.2  394.18  3792.4  376.13  3879.5   371.8  4039.8  372.21
    4110  370.01  4240.2  362.65  4292.8  361.64  4422.8  362.29  4480.7  361.47
  4535.3  363.65  4580.9  362.33    4661  362.26  4801.3  364.12  4921.5  363.86
  4951.6  365.04  4971.6  364.04  5001.4  358.96  5031.7  360.72  5041.7  364.85
  5081.7  364.74  5131.7  367.36  5141.7  368.97  5161.7  368.99  5301.7  376.13
  5381.7  382.12  5391.7  381.42  5411.8  384.11  5521.7  391.89  5561.7  393.45
#Mann= 8 ,-1 , 0
  3408.6     .12       0  3472.2     .16       0  3792.4     .12       0
  4422.8     .16       0  4535.3     .16       0  4951.6     .12       0
  5041.7     .16       0  5411.8     .05       0
#XS Ineff= 2 , 0
         4041.48  377.16
Permanent Ineff=
       F       F
Bank Sta=4951.6,5041.7
XS Rating Curve= 0 ,0
Exp/Cntr=0.3,0.1

Type RM Length L Ch R = 1 ,79799   ,525,525,525
BEGIN DESCRIPTION:
CANEY CREEK 97.0
END DESCRIPTION:
XS GIS Cut Line= 3
      3561349.64     10608510.18      3562099.61     10608210.19
      3562599.56     10608210.19
#Sta/Elev= 30
  4173.1  383.06  4259.2  380.35  4313.1  377.06  4432.9   371.8  4486.8  370.03
  4535.2  366.85  4582.3  365.55  4603.9  363.44  4647.2  362.18    4756  359.61
  4797.8  359.52  4804.5  360.48  4819.3  360.39  4871.5  363.13  4959.3  364.26
    4966  358.84  4971.4  362.73  4978.2  360.07  4983.3  360.07  4990.6  358.06
  5010.8  358.77  5020.8  360.86  5030.8  364.46  5050.8  364.72  5120.8  362.93
  5240.8  362.61  5390.8  378.67  5450.8  383.33  5467.3  383.46  5480.8  383.28
#Mann= 7 ,-1 , 0
  4173.1     .16       0  4432.9     .12       0  4647.2     .12       0
  4871.5     .16       0  4959.3     .16       0  5050.8     .16       0
  5467.3     .05       0
Bank Sta=4959.3,5050.8
XS Rating Curve= 0 ,0
Exp/Cntr=0.3,0.1

Type RM Length L Ch R = 1 ,79274   ,633,633,633
BEGIN DESCRIPTION:
CANEY CREEK 96.0
END DESCRIPTION:
XS GIS Cut Line= 3
      3561237.16     10609059.77      3562643.37     10608521.59
      3563328.13     10607854.16
#Sta/Elev= 30
  3860.3  391.08  3930.8   383.5  3999.8  378.67  4077.1  372.06  4204.5  364.58
  4374.3  359.75  4633.9   359.9  4877.5  360.51  4976.5  363.37    4987  363.16
  4992.4  359.95  5008.4  357.48  5017.1  359.36  5022.4  362.92  5040.7  363.76
  5201.3  360.71  5356.3  363.04    5366  361.74  5378.4  363.38  5647.2   370.9
  5668.3  373.02  5746.2  371.88  5823.9  373.54  5930.1  372.46    6052  377.03
    6114  378.27    6121   379.9  6128.1  378.01  6225.2   382.4  6322.2  384.48
#Mann= 10 ,-1 , 0
  3860.3     .05       0  3999.8     .16       0  4374.3     .16       0
  4633.9     .16       0  4976.5     .12       0  5040.7     .16       0
  5647.2     .16       0  5746.2     .05       0    6052     .16       0
  6225.2     .05       0
#XS Ineff= 2 , 0
                         5668.18          375.93
Permanent Ineff=
       F       F
Bank Sta=4976.5,5040.7
XS Rating Curve= 0 ,0
Exp/Cntr=0.3,0.1

Type RM Length L Ch R = 1 ,78641   ,1504,1504,1504
BEGIN DESCRIPTION:
CANEY CREEK 95.0
END DESCRIPTION:
XS GIS Cut Line= 3
      3561499.65     10609310.18      3562249.61     10609110.19
      3564649.64     10608110.17
#Sta/Elev= 30
  4245.7  387.96  4514.7  371.08  4730.5   359.5  4890.4  359.62  4970.1  363.07
  5011.3  357.25  5043.5  362.79  5581.9  359.81  5633.4  359.77  5650.2  363.55
  5671.9   359.6  5922.7  359.91  6466.5  370.58  6673.4  374.63  6711.9  368.33
  6774.2  375.62    6798  374.94  6803.4  369.55  6851.1  377.08    6928  378.84
  6962.7  374.61  6971.9  378.83  7010.3  380.99    7026  380.84  7034.2  375.99
  7069.4  370.74  7092.7  382.73  7208.8  387.43  7440.3  401.63  7621.9  415.13
#Mann= 10 ,-1 , 0
  4245.7     .16       0  4514.7     .12       0  4730.5     .16       0
  4890.4     .16       0  4970.1     .16       0  5043.5     .16       0
  5581.9     .16       0  6466.5     .12       0  7208.8     .16       0
  7440.3     .12       0
#XS Ineff= 2 , 0
         4197.73  347.37 5647.73          373.22
Permanent Ineff=
       F       F
Bank Sta=4970.1,5043.5
XS Rating Curve= 0 ,0
Exp/Cntr=0.3,0.1

Type RM Length L Ch R = 1 ,77137   ,1721,1721,1721
BEGIN DESCRIPTION:
Mapping XS 12263a88
END DESCRIPTION:
XS GIS Cut Line= 4
      3561436.81     10610084.08      3562877.74     10609624.02
      3563667.67     10609172.63      3564744.04     10608755.97
#Sta/Elev= 30
    3329  401.27  3478.9  390.43  3762.3  376.69  3774.7  377.73  3792.3  376.78
  4114.2  363.42  4261.9  359.24  4307.3   357.2  4312.6  357.36  4318.7  360.56
  4329.2  360.89  4394.9   359.7  4791.1  357.69  4962.4  360.56  4978.3  359.94
    4984  355.86  4999.6  354.18  5021.5  360.48    5028   360.3  5212.3  357.51
  5440.4  358.68  5454.2  356.66  5526.8  359.27    5688   358.7  5795.4  362.15
    5897  368.48  6384.3  390.56  6520.5  393.72  6675.7  396.28  6905.6  403.56
#Mann= 10 ,-1 , 0
    3329     .16       0  3774.7     .05       0  3792.3     .16       0
  4261.9     .16       0  4394.9     .16       0  4962.4     .12       0
    5028     .16       0    5897     .16       0  6384.3     .12       0
  6520.5     .16       0
Bank Sta=4962.4,5021.5
XS Rating Curve= 0 ,0
Exp/Cntr=0.3,0.1

Type RM Length L Ch R = 1 ,75416   ,497,497,497
BEGIN DESCRIPTION:
CANEY CREEK 94.0
END DESCRIPTION:
XS GIS Cut Line= 3
      3561496.45     10610420.96      3563831.53     10610030.33
      3565194.35     10609223.05
#Sta/Elev= 30
  2465.1  411.09  2478.6  410.25  2569.7  400.69  2781.5  384.48  2894.1  377.83
  3086.8  387.66  3207.5   380.5    3352  371.12  3573.4  365.77  3716.3  362.04
  3773.3  363.91  3893.4  364.74  4110.7  355.79  4151.4  356.39  4161.5  354.51
  4202.1  356.73  4257.8  355.51  4318.5  356.84  4682.8  355.19  4977.9  358.73
  4999.1   353.2  5020.7  358.57  5180.6   355.7    5356  359.64    6185  401.89
  6198.4  403.13  6364.6  410.27  6387.4  410.68  6408.8   407.3  6416.6  409.55
#Mann= 11 ,-1 , 0
  2465.1     .05       0  2478.6     .16       0  2781.5     .05       0
  3207.5      .1       0  3573.4      .1       0  3773.3      .1       0
  4110.7     .12       0  4977.9     .12       0  5020.7     .16       0
    6185     .16       0  6198.4     .12       0
#XS Ineff= 2 , 0
         3835.23  369.19
Permanent Ineff=
       F       F
Bank Sta=4977.9,5020.7
XS Rating Curve= 0 ,0
Exp/Cntr=0.3,0.1

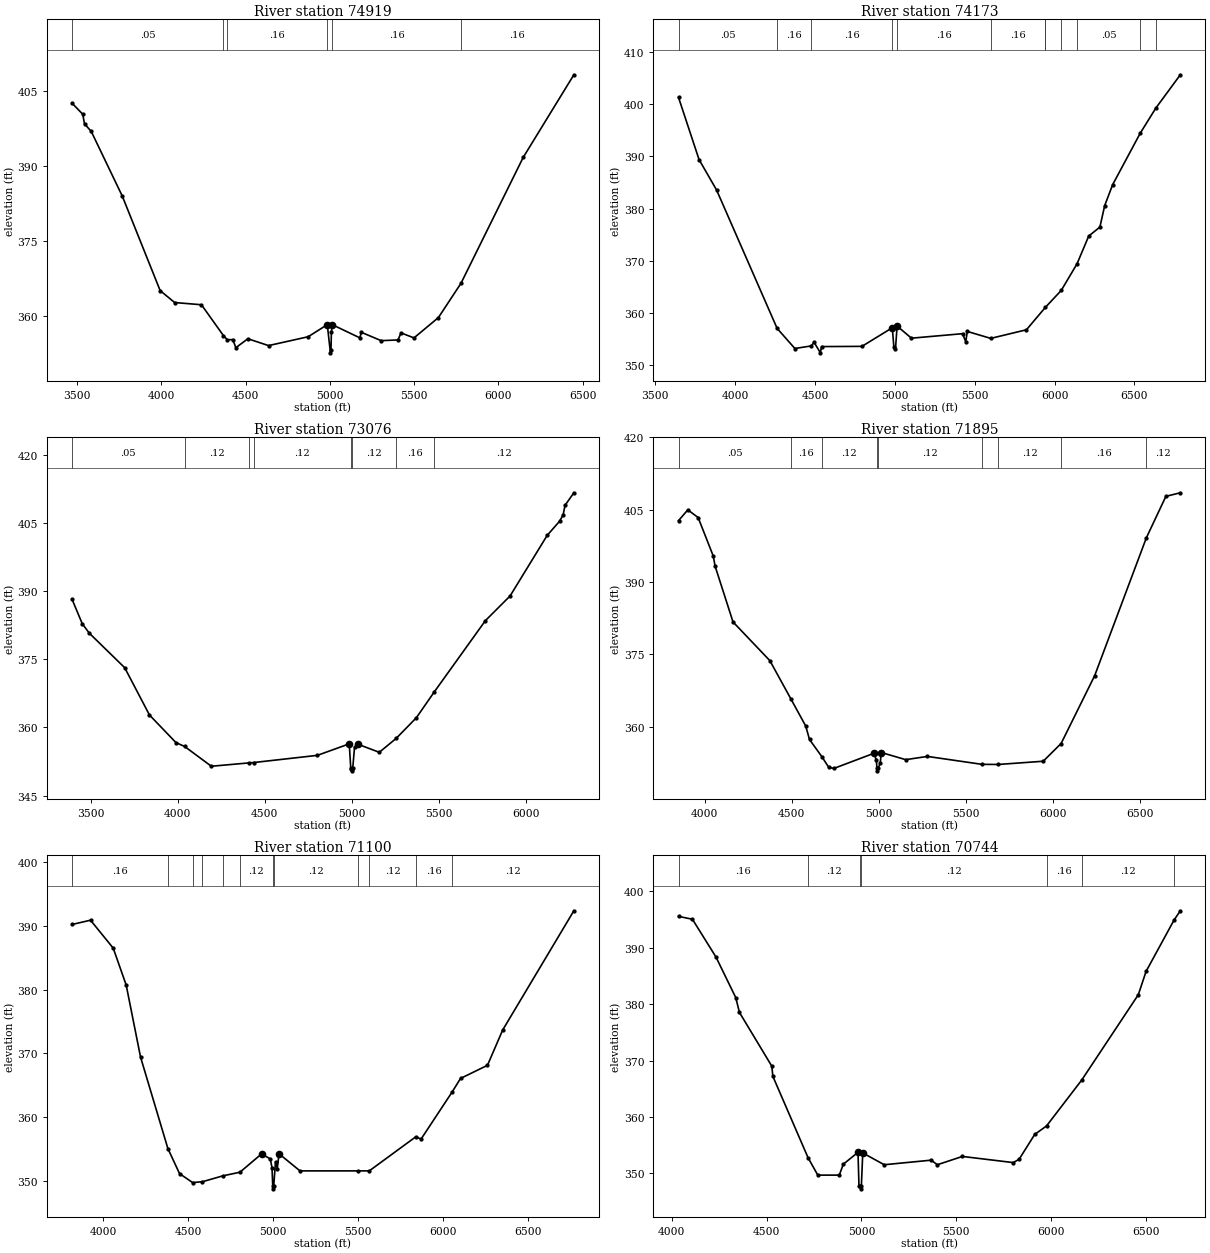
Type RM Length L Ch R = 1 ,74919   ,746,746,746
BEGIN DESCRIPTION:
CANEY CREEK 93.0
END DESCRIPTION:
XS GIS Cut Line= 2
      3562607.62     10610629.28       3565524.2     10610021.66
#Sta/Elev= 30
  3469.4  402.53  3532.7  400.32  3543.3  398.39  3583.1  396.89  3767.7  383.92
  3992.4  365.01  4078.5  362.62  4237.5  362.18  4367.9  356.01  4391.5  355.16
  4423.8   355.2  4441.8  353.58  4513.3  355.37  4635.9     354  4870.9  355.77
 4984.66  358.19  5003.4  352.55  5006.6  353.05  5009.1  356.67  5014.2  358.19
  5177.3  355.56  5187.5  356.65  5304.3  354.99  5404.4  355.13  5422.4  356.54
  5499.4  355.54  5644.4  359.61  5778.4  366.47  6147.7  391.67  6448.6  408.22
#Mann= 6 ,-1 , 0
  3469.4     .05       0  4367.9     .16       0  4391.5     .16       0
 4984.66     .12       0  5014.2     .16       0  5778.4     .16       0
Bank Sta=4984.66,5014.2
XS Rating Curve= 0 ,0
Exp/Cntr=0.3,0.1

Type RM Length L Ch R = 1 ,74173   ,1097,1097,1097
BEGIN DESCRIPTION:
CANEY CREEK 92.0
END DESCRIPTION:
XS GIS Cut Line= 2
      3562651.01     10610967.83      3565793.32     10611028.59
#Sta/Elev= 30
  3645.1  401.28  3773.7  389.37  3883.7  383.53  4262.5  357.03  4373.8  353.17
  4476.9  353.67  4493.9  354.37  4533.6  352.34  4540.9  353.54  4793.9  353.58
    4984  357.15    4994  353.39    5004  353.07    5014  357.47    5104  355.15
    5424  356.01    5444  354.48    5454  356.44  5600.5  355.11  5824.1  356.76
  5943.2  361.07  6042.1   364.3    6141   369.4  6214.2  374.72  6284.2  376.44
  6314.2  380.55  6364.2  384.57  6536.4  394.41  6635.3  399.28    6788  405.63
#Mann= 12 ,-1 , 0
  3645.1     .05       0  4262.5     .16       0  4476.9     .16       0
    4984     .12       0    5014     .16       0  5600.5     .16       0
  5943.2     .16       0  5943.2     .12       0  6042.1     .16       0
    6141     .05       0  6536.4     .16       0  6635.3      .1       0
Bank Sta=4984,5014
XS Rating Curve= 0 ,0
Exp/Cntr=0.3,0.1

Type RM Length L Ch R = 1 ,73076   ,1181,1181,1181
BEGIN DESCRIPTION:
CANEY CREEK 91.0
END DESCRIPTION:
XS GIS Cut Line= 2
      3562711.78     10611349.78      3565550.28     10611844.56
#Sta/Elev= 30
  3393.3  388.17    3452  382.79  3492.6  380.71  3695.6  373.12  3837.7  362.72
    3990  356.64  4039.4   355.8    4193  351.44  4409.9  352.18  4435.1  352.25
  4802.1  353.84  4984.8  356.37  4993.5  351.07  4995.6  350.93  4998.3  350.43
  5001.6  350.93  5005.1   351.1  5015.2  355.62  5035.5  356.27  5157.3  354.51
  5254.1  357.56  5370.5  362.13  5472.9  367.79  5766.4  383.47  5908.5  388.92
  6121.7  402.26  6192.7  405.36    6213  406.78  6224.1  408.87  6274.6  411.62
#Mann= 8 ,-1 , 0
  3393.3     .05       0  4039.4     .12       0  4409.9     .07       0
  4435.1     .12       0  4995.6     .07       0  5001.6     .12       0
  5254.1     .16       0  5472.9     .12       0
Bank Sta=4984.8,5035.5
XS Rating Curve= 0 ,0
Exp/Cntr=0.3,0.1

Type RM Length L Ch R = 1 ,71895   ,795,795,795
BEGIN DESCRIPTION:
CANEY CREEK 89.0
END DESCRIPTION:
XS GIS Cut Line= 3
      3562486.03     10611410.52      3564013.83     10612261.23
      3565142.35     10612339.36
#Sta/Elev= 30
  3850.4   402.7  3903.6  404.94    3963  403.34  4049.9  395.34  4060.2  393.27
  4163.1  381.69  4374.6  373.66  4495.6   365.7  4580.4   360.1  4602.1  357.31
  4673.3  353.73  4712.9  351.51  4742.7  351.32  4970.2  354.43  4986.2  353.04
  4988.9  351.31  4991.7  350.81  4994.9  351.31  5007.9  352.34  5013.7  354.61
  5154.3  353.13  5278.9   353.8  5591.4  352.16  5684.7  352.13  5943.3   352.8
  6046.1  356.48  6238.5  370.53  6535.6  399.16  6647.4  407.74  6730.3  408.48
#Mann= 9 ,-1 , 0
  3850.4     .05       0  4495.6     .16       0  4673.3     .12       0
  4988.9     .07       0  4994.9     .12       0  5591.4     .07       0
  5684.7     .12       0  6046.1     .16       0  6535.6     .12       0
Bank Sta=4970.2,5013.7
XS Rating Curve= 0 ,0
Exp/Cntr=0.3,0.1

Type RM Length L Ch R = 1 ,71100   ,356,356,356
BEGIN DESCRIPTION:
CANEY CREEK 88.0
END DESCRIPTION:
XS GIS Cut Line= 2
      3562243.84     10612341.95      3565118.89     10613022.52
#Sta/Elev= 30
  3816.5  390.24  3925.2  390.91  4058.8  386.52  4135.1  380.73  4219.7  369.41
  4380.6  355.05  4449.3  351.11  4526.5   349.7  4584.2  349.84  4704.2  350.76
  4804.9  351.33  4932.3  354.21  4983.7  353.42  4993.9  352.01  4997.9  349.22
  5000.6  348.72  5003.9  349.22  5014.5  352.99  5024.8  351.91    5035  354.23
  5158.4  351.54  5498.1  351.54  5566.5  351.54  5839.1  356.87  5871.7  356.55
  6052.6  363.86  6103.8  366.06  6262.3  368.12    6352  373.67    6771  392.39
#Mann= 12 ,-1 , 0
  3816.5     .16       0  4380.6     .12       0  4526.5     .05       0
  4584.2     .12       0  4704.2     .07       0  4804.9     .12       0
  4997.9     .07       0  5003.9     .12       0  5498.1     .07       0
  5566.5     .12       0  5839.1     .16       0  6052.6     .12       0
Bank Sta=4932.3,5035
XS Rating Curve= 0 ,0
Exp/Cntr=0.3,0.1

Type RM Length L Ch R = 1 ,70744   ,660,660,660
BEGIN DESCRIPTION:
CANEY CREEK 87.0
END DESCRIPTION:
XS GIS Cut Line= 2
      3562236.92     10612626.68      3564804.73     10613265.17
#Sta/Elev= 30
  4035.4  395.54  4108.6  395.03  4232.6  388.35    4337  381.16  4356.6  378.52
  4527.1  369.01  4532.8   367.2  4718.8  352.75  4769.8   349.7  4883.1   349.7
  4904.2  351.63  4981.7  353.74  4986.9  347.82  4993.5  347.77  4996.2  347.27
  4999.5  347.77  5006.8  353.63  5120.1  351.54  5367.5  352.35  5400.2  351.54
  5532.3  353.01  5800.2  351.92  5831.2   352.5  5913.6  356.91  5975.8  358.41
  6161.2  366.53  6459.7  381.65  6500.9   385.8  6648.7  394.91  6681.4  396.53
#Mann= 7 ,-1 , 0
  4035.4     .16       0  4718.8     .12       0  4993.5     .07       0
  4999.5     .12       0  5975.8     .16       0  6161.2     .12       0
  6648.7     .07       0
Bank Sta=4981.7,5006.8
XS Rating Curve= 0 ,0
Exp/Cntr=0.3,0.1