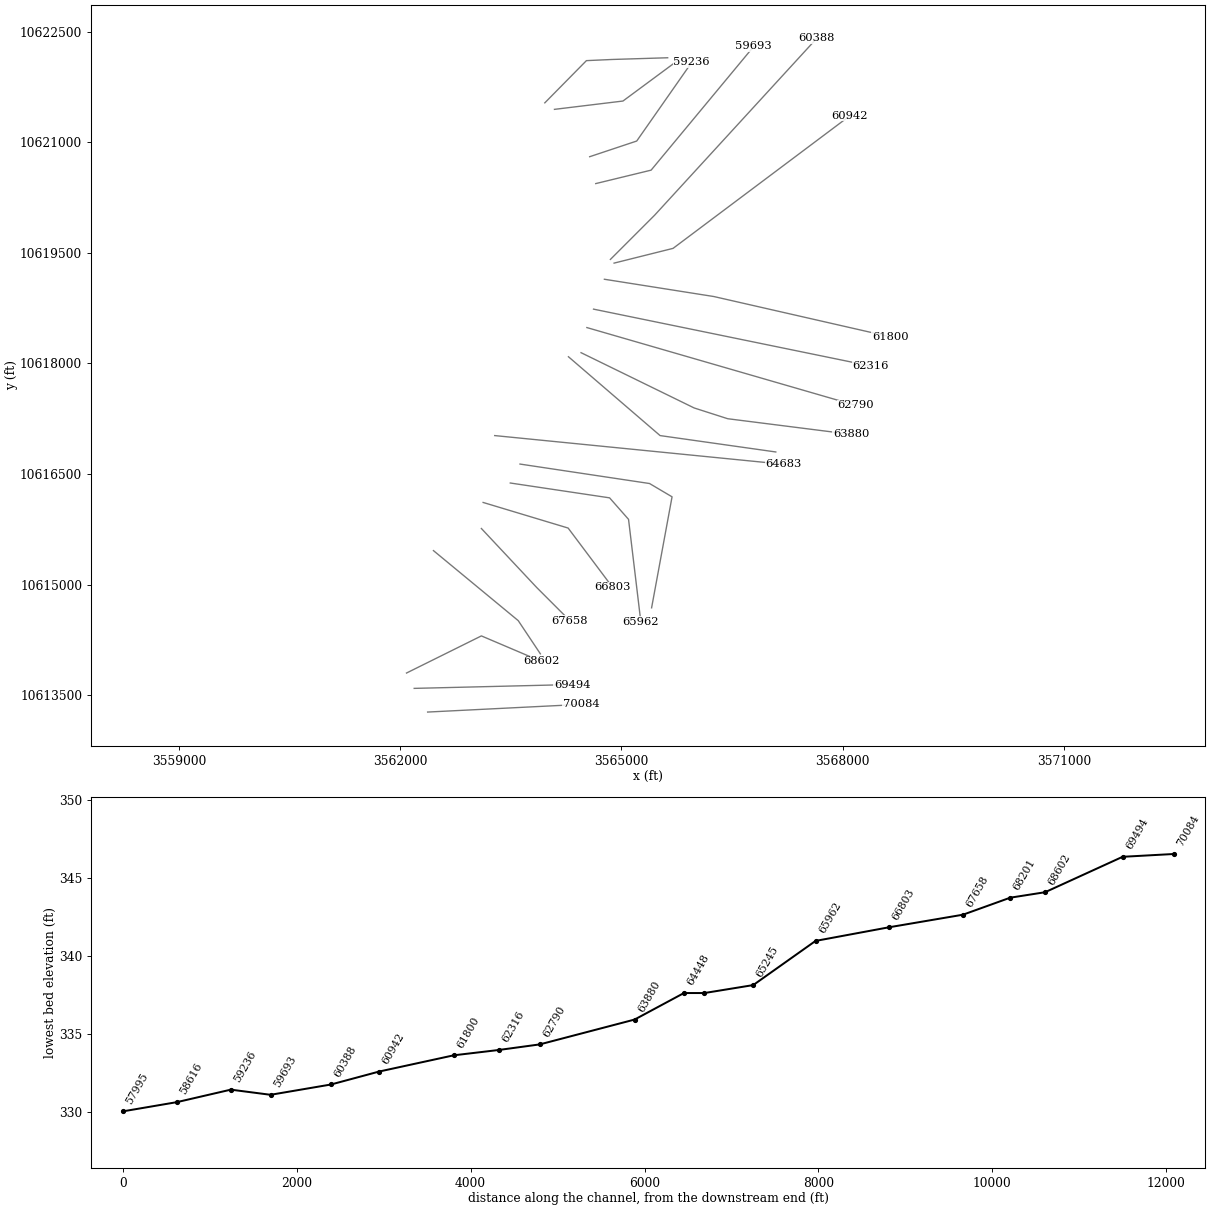
HEC-RAS study CANEY CREEK.prj: CANEY CREEK Base Level Engineering

--- CANEY CREEK.g01 (geometry) --- (continued)

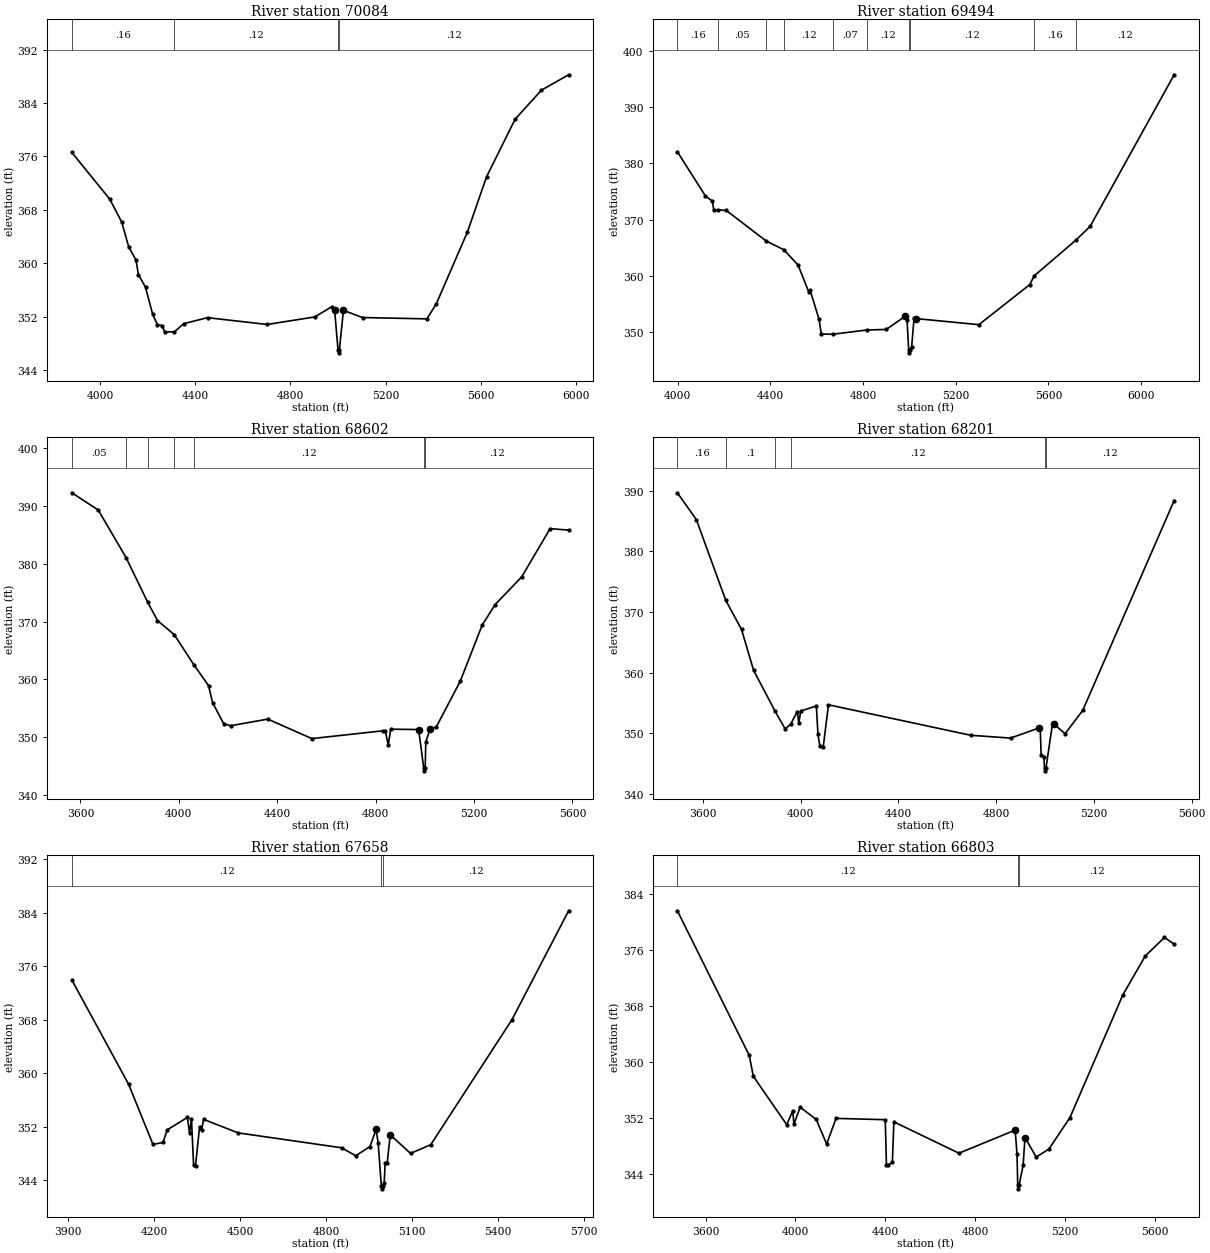
Type RM Length L Ch R = 1 ,70084   ,590,590,590
BEGIN DESCRIPTION:
CANEY CREEK 86.0
END DESCRIPTION:
XS GIS Cut Line= 2
      3562370.59     10613270.19      3564453.89     10613374.36
#Sta/Elev= 30
  3882.2  376.58  4041.4  369.59  4091.5  366.17  4121.5  362.39  4151.6  360.48
  4161.6  358.29  4191.6  356.38  4221.6  352.34  4241.7  350.78  4261.7  350.64
  4271.7   349.7    4313   349.7  4351.8  350.93  4451.9  351.83  4702.2  350.81
  4902.5  351.94  4972.6  353.45  4985.6  352.97  4999.6  347.06  5002.4  346.56
  5005.6  347.06  5022.6  352.92  5102.7  351.85  5373.1  351.65  5413.1  353.95
  5543.3  364.68  5623.4  372.93  5743.5  381.57  5853.7  385.91  5968.1  388.22
#Mann= 4 ,-1 , 0
  3882.2     .16       0    4313     .12       0  4999.6     .07       0
  5005.6     .12       0
Bank Sta=4985.6,5022.6
XS Rating Curve= 0 ,0
Exp/Cntr=0.3,0.1

Type RM Length L Ch R = 1 ,69494   ,892,892,892
BEGIN DESCRIPTION:
CANEY CREEK 85.0
END DESCRIPTION:
XS GIS Cut Line= 2
      3562188.24     10613591.37      3564332.41     10613643.46
#Sta/Elev= 30
  3998.2  382.07  4119.6   374.2  4149.6  373.31    4155  371.77  4173.5  371.76
  4209.6  371.64  4381.6  366.23  4458.2  364.67  4519.7  361.94    4566  357.12
    4571  357.53  4609.8  352.36  4619.8   349.7  4672.3   349.7  4816.9  350.43
  4899.8  350.53  4981.9  352.87  4989.9  352.12  4996.9  346.88  4999.6  346.38
  5002.9  346.88  5009.9   347.5  5019.9   352.5  5029.9  352.45    5300  351.38
    5520   358.5  5538.5  360.03  5718.3  366.36  5780.1  368.82    6143  395.72
#Mann= 10 ,-1 , 0
  3998.2     .16       0  4173.5     .05       0  4381.6     .16       0
  4458.2     .12       0  4672.3     .07       0  4816.9     .12       0
  4996.9     .07       0  5002.9     .12       0  5538.5     .16       0
  5718.3     .12       0
Bank Sta=4981.9,5029.9
XS Rating Curve= 0 ,0
Exp/Cntr=0.3,0.1

Type RM Length L Ch R = 1 ,68602   ,401,401,401
BEGIN DESCRIPTION:
CANEY CREEK 84.0
END DESCRIPTION:
XS GIS Cut Line= 3
      3562084.09     10613799.69      3563099.74     10614303.18
      3563915.18     10613956.18
#Sta/Elev= 30
  3564.8  392.32  3672.1  389.34    3786  381.03  3873.2  373.35  3913.1  370.17
  3981.5  367.71  4060.3  362.54  4120.5   358.9  4137.3  355.91  4182.2  352.29
  4210.2  351.93  4361.5  353.08  4540.9   349.7  4828.7  351.05  4839.5  350.97
  4851.2  348.59  4861.3  351.33  4974.8  351.27  4995.4  344.61  4998.2  344.11
  5001.4  344.61  5003.9  349.14  5022.1  351.43  5045.7  351.66  5143.8  359.63
  5232.9  369.36  5285.6  372.93  5393.8  377.74  5509.2   386.1  5584.6  385.85
#Mann= 7 ,-1 , 0
  3564.8     .05       0    3786     .16       0  3873.2     .12       0
  3981.5     .16       0  4060.3     .12       0  4995.4     .07       0
  5001.4     .12       0
Bank Sta=4974.8,5022.1
XS Rating Curve= 0 ,0
Exp/Cntr=0.3,0.1

Type RM Length L Ch R = 1 ,68201   ,543,543,543
BEGIN DESCRIPTION:
CANEY CREEK 83.0
END DESCRIPTION:
XS GIS Cut Line= 3
      3562449.58     10615460.21      3563599.61     10614510.19
       3563899.6      10614060.2
#Sta/Elev= 30
    3496  389.69  3573.9  385.25  3693.9  371.94  3758.5  367.12    3808  360.36
  3895.7  353.62    3937  350.69  3959.1  351.44  3986.5  353.54    3993  351.72
  4000.9  353.64  4064.7  354.48  4071.2  349.77    4079  347.87  4092.7  347.67
  4114.2  354.67  4696.5  349.63  4859.3  349.17    4974  350.82  4980.5  350.82
  4984.4   346.3  4995.2  346.09  4998.2  344.26    5001  343.76  5004.2  344.26
  5031.2  351.67  5037.3  351.47  5082.3  349.89  5154.4  353.74  5528.5  388.41
#Mann= 6 ,-1 , 0
    3496     .16       0  3693.9      .1       0  3895.7     .16       0
  3959.1     .12       0  4998.2     .07       0  5004.2     .12       0
Bank Sta=4974,5037.3
XS Rating Curve= 0 ,0
Exp/Cntr=0.3,0.1

Type RM Length L Ch R = 1 ,67658   ,855,855,855
BEGIN DESCRIPTION:
CANEY CREEK 82.0
END DESCRIPTION:
XS GIS Cut Line= 3
      3563099.62     10615760.17      3563849.61     10614960.19
      3564299.64     10614510.16
#Sta/Elev= 30
  3912.6  373.95  4110.6  358.34  4195.6  349.33  4230.8  349.61    4245  351.49
  4315.8  353.37  4323.1  351.04    4330  353.06  4337.3  346.28  4344.1  346.13
  4358.3  351.99  4365.1  351.45  4372.5  353.07  4492.6  351.05  4853.6  348.82
  4902.9  347.62  4952.7  349.01  4973.8  351.56  4981.1  349.59  4992.2  343.17
    4995  342.67  4998.2  343.17  5002.1  343.48  5005.7  346.56  5012.7  346.56
  5023.3  350.75    5094  347.98  5164.7  349.28  5447.6  367.98  5645.6  384.31
#Mann= 3 ,-1 , 0
  3912.6     .12       0  4992.2     .07       0  4998.2     .12       0
Bank Sta=4973.8,5023.3
XS Rating Curve= 0 ,0
Exp/Cntr=0.3,0.1

Type RM Length L Ch R = 1 ,66803   ,841,841,841
BEGIN DESCRIPTION:
CANEY CREEK 81.0
END DESCRIPTION:
XS GIS Cut Line= 3
      3563123.42     10616113.46      3564276.24     10615766.23
      3564880.39     10614960.69
#Sta/Elev= 30
  3474.4  381.64  3794.2  360.96  3812.5  357.96  3961.3  351.03  3987.9  353.02
  3993.2  351.12  4020.9  353.54  4092.2  351.79  4138.8  348.27  4180.6  351.94
  4399.6  351.75  4404.9  345.29  4410.4  345.24  4431.2  345.63  4437.9  351.44
  4727.7  346.96  4977.7  350.26  4985.9  346.83  4989.2  342.36    4992  341.86
  4995.2  342.36  5013.1  345.23  5021.4   349.2  5071.4  346.41  5127.7  347.54
  5221.4  352.05  5456.8   369.6  5556.8  375.18  5642.2  377.82  5685.3  376.86
#Mann= 3 ,-1 , 0
  3474.4     .12       0  4989.2     .07       0  4995.2     .12       0
Bank Sta=4977.7,5021.4
XS Rating Curve= 0 ,0
Exp/Cntr=0.3,0.1

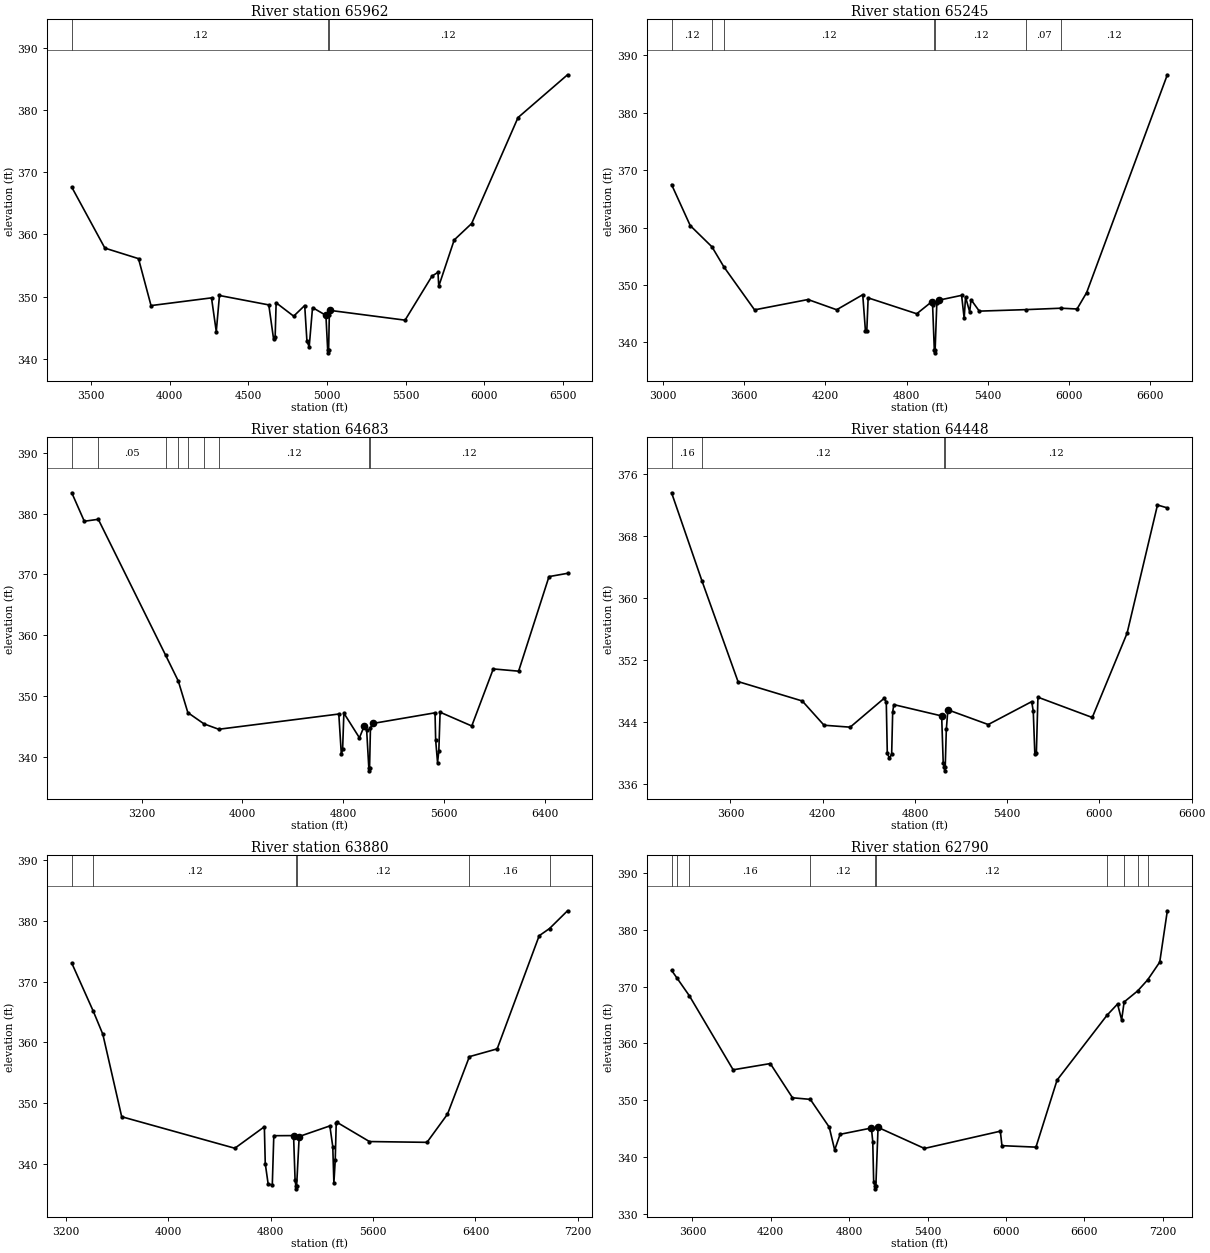
Type RM Length L Ch R = 1 ,65962   ,717,717,717
BEGIN DESCRIPTION:
CANEY CREEK 80.0
END DESCRIPTION:
XS GIS Cut Line= 4
      3563491.56     10616377.33      3564838.74     10616175.95
      3565095.69     10615884.28      3565262.35      10614495.4
#Sta/Elev= 30
  3378.7   367.6  3589.1  357.81  3802.7  356.12  3882.3  348.58  4266.5  349.82
  4296.8  344.41  4317.1   350.2  4630.5  348.69  4660.8  343.22  4670.9  343.57
  4677.2  349.03  4788.5  346.88  4858.7  348.59  4872.9  342.82  4887.2  341.97
  4908.4  348.26  4993.4  347.01  5004.6  341.49  5007.4  340.99  5010.6  341.49
  5015.1  347.11  5021.9   347.8  5496.3  346.24  5667.5  353.32  5705.4  353.92
  5710.4  351.69  5808.5  359.12  5919.3  361.76    6214  378.78  6528.4  385.65
#Mann= 3 ,-1 , 0
  3378.7     .12       0  5004.6     .07       0  5010.6     .12       0
Bank Sta=4993.4,5021.9
XS Rating Curve= 0 ,0
Exp/Cntr=0.3,0.1

Type RM Length L Ch R = 1 ,65245   ,562,562,562
BEGIN DESCRIPTION:
CANEY CREEK 79.0
END DESCRIPTION:
XS GIS Cut Line= 4
      3563623.42     10616634.29      3565380.41     10616370.39
      3565685.96     10616189.84      3565408.39     10614684.01
#Sta/Elev= 30
  3063.7  367.48  3201.4  360.34  3362.2  356.63  3450.2  353.14  3676.7  345.65
  4071.8  347.45  4283.4  345.67    4476  348.29  4495.8  342.04  4505.9  341.89
    4516  347.74  4875.2  344.97  4986.4  347.08  4992.2  346.49  5004.9  338.66
  5007.6  338.16  5010.9  338.66  5023.5  346.91  5036.9  347.33  5206.5  348.18
  5225.5  344.16  5235.6   347.9  5266.1   345.3  5276.3  347.42  5337.3  345.43
  5680.7  345.69  5941.9  345.94  6059.3   345.8  6130.4  348.66  6726.5  386.62
#Mann= 7 ,-1 , 0
  3063.7     .12       0  3362.2     .16       0  3450.2     .12       0
  5004.9     .07       0  5010.9     .12       0  5680.7     .07       0
  5941.9     .12       0
Bank Sta=4986.4,5036.9
XS Rating Curve= 0 ,0
Exp/Cntr=0.3,0.1

Type RM Length L Ch R = 1 ,64683   ,235,235,235
BEGIN DESCRIPTION:
CANEY CREEK 78.0
END DESCRIPTION:
XS GIS Cut Line= 2
      3563280.57     10617020.57      3567195.92     10616631.81
#Sta/Elev= 30
  2645.5  383.46    2745  378.77    2856  379.09  3391.1  356.67  3490.9  352.45
  3566.9  347.24  3695.5  345.38  3811.9   344.5  4764.9  347.01    4785  340.37
  4795.1  341.18  4805.1  347.16  4928.6  343.09  4965.9     345    4986  344.33
  5003.1  338.15  5005.8  337.65  5009.1  338.15  5016.1  344.74  5036.2  345.46
  5528.6  347.21  5533.7  342.68  5548.7     339  5558.8  340.96  5568.8  347.31
  5820.1  345.04  5990.9  354.44  6191.9  354.07  6433.1  369.65  6580.1  370.19
#Mann= 9 ,-1 , 0
  2645.5     .16       0    2856     .05       0  3391.1     .16       0
  3490.9     .05       0  3566.9     .12       0  3695.5     .05       0
  3811.9     .12       0  5003.1     .07       0  5009.1     .12       0
Bank Sta=4965.9,5036.2
XS Rating Curve= 0 ,0
Exp/Cntr=0.3,0.1

Type RM Length L Ch R = 1 ,64448   ,568,568,568
BEGIN DESCRIPTION:
CANEY CREEK 77.0
END DESCRIPTION:
XS GIS Cut Line= 3
      3564280.56     10618090.03      3565523.64     10617020.57
      3567093.07     10616798.35
#Sta/Elev= 30
  3216.8  373.56  3414.2  362.19  3648.9  349.18    4067  346.67  4208.5  343.54
  4378.6  343.29  4599.1  347.01  4613.4  346.54    4620  339.95  4634.2  339.26
  4648.5  339.84  4655.1  345.29  4662.8   346.2  4973.7  344.74  4983.8  338.67
  4990.9  338.15  4993.7  337.65  4996.9  338.15    5004  342.99  5014.1  345.53
  5276.7  343.63  5559.5  346.59  5569.6  345.35  5579.7  339.88  5589.8  339.95
  5599.9  347.16  5953.4  344.54  6179.8  355.42  6377.6  371.98  6441.7  371.61
#Mann= 4 ,-1 , 0
  3216.8     .16       0  3414.2     .12       0  4990.9     .07       0
  4996.9     .12       0
Bank Sta=4973.7,5014.1
XS Rating Curve= 0 ,0
Exp/Cntr=0.3,0.1

Type RM Length L Ch R = 1 ,63880   ,1090,1090,1090
BEGIN DESCRIPTION:
CANEY CREEK 76.0
END DESCRIPTION:
XS GIS Cut Line= 4
      3564451.54     10618145.12      3565986.29     10617395.11
      3566441.15     10617249.27      3568114.73     10617037.47
#Sta/Elev= 30
  3246.5  373.04  3414.9  365.12  3489.2  361.35  3636.5   347.8  4520.3  342.62
    4751  346.15  4758.1  340.09  4780.3   336.8    4813  336.54  4824.8  344.68
  4979.2   344.7  4991.1  337.33  4997.2  336.45  4999.9  335.95  5003.2  336.45
  5023.2  344.55  5262.7  346.29  5285.5  342.88  5294.2   336.9  5304.7  340.65
  5312.4   346.7  5317.6  346.89  5571.9  343.72  6021.5  343.59  6181.7  348.22
  6352.7  357.67  6569.8  358.95    6898  377.54  6978.7  378.72  7119.3  381.64
#Mann= 6 ,-1 , 0
  3246.5     .16       0  3414.9     .12       0  4997.2     .07       0
  5003.2     .12       0  6352.7     .16       0  6978.7     .05       0
Bank Sta=4979.2,5023.2
XS Rating Curve= 0 ,0
Exp/Cntr=0.3,0.1

Type RM Length L Ch R = 1 ,62790   ,474,474,474
BEGIN DESCRIPTION:
CANEY CREEK 75.0
END DESCRIPTION:
XS GIS Cut Line= 2
      3564530.59     10618485.84       3568175.5     10617430.55
#Sta/Elev= 30
  3440.8  372.87  3484.4  371.44  3577.1  368.38    3912  355.34  4196.4  356.44
  4366.3  350.41  4502.6  350.13  4647.4  345.24  4689.1  341.21  4730.7  343.97
  4970.2  345.08  4980.6  342.69  4987.6   335.6  4998.4  334.86  5001.1  334.36
  5004.4  334.86  5021.2  345.19  5376.2  341.48  5957.1  344.52  5969.6  341.97
  6229.8  341.71  6391.5  353.53  6773.8  364.96  6854.2  366.93  6885.7  364.15
  6904.8   367.3    7009  369.26  7084.3  371.18  7177.2  374.32  7235.4  383.37
#Mann= 10 ,-1 , 0
  3440.8     .16       0  3484.4     .12       0  3577.1     .16       0
  4502.6     .12       0  4998.4     .07       0  5004.4     .12       0
  6773.8     .16       0  6904.8     .05       0    7009     .12       0
  7084.3     .16       0
Bank Sta=4970.2,5021.2
XS Rating Curve= 0 ,0
Exp/Cntr=0.3,0.1

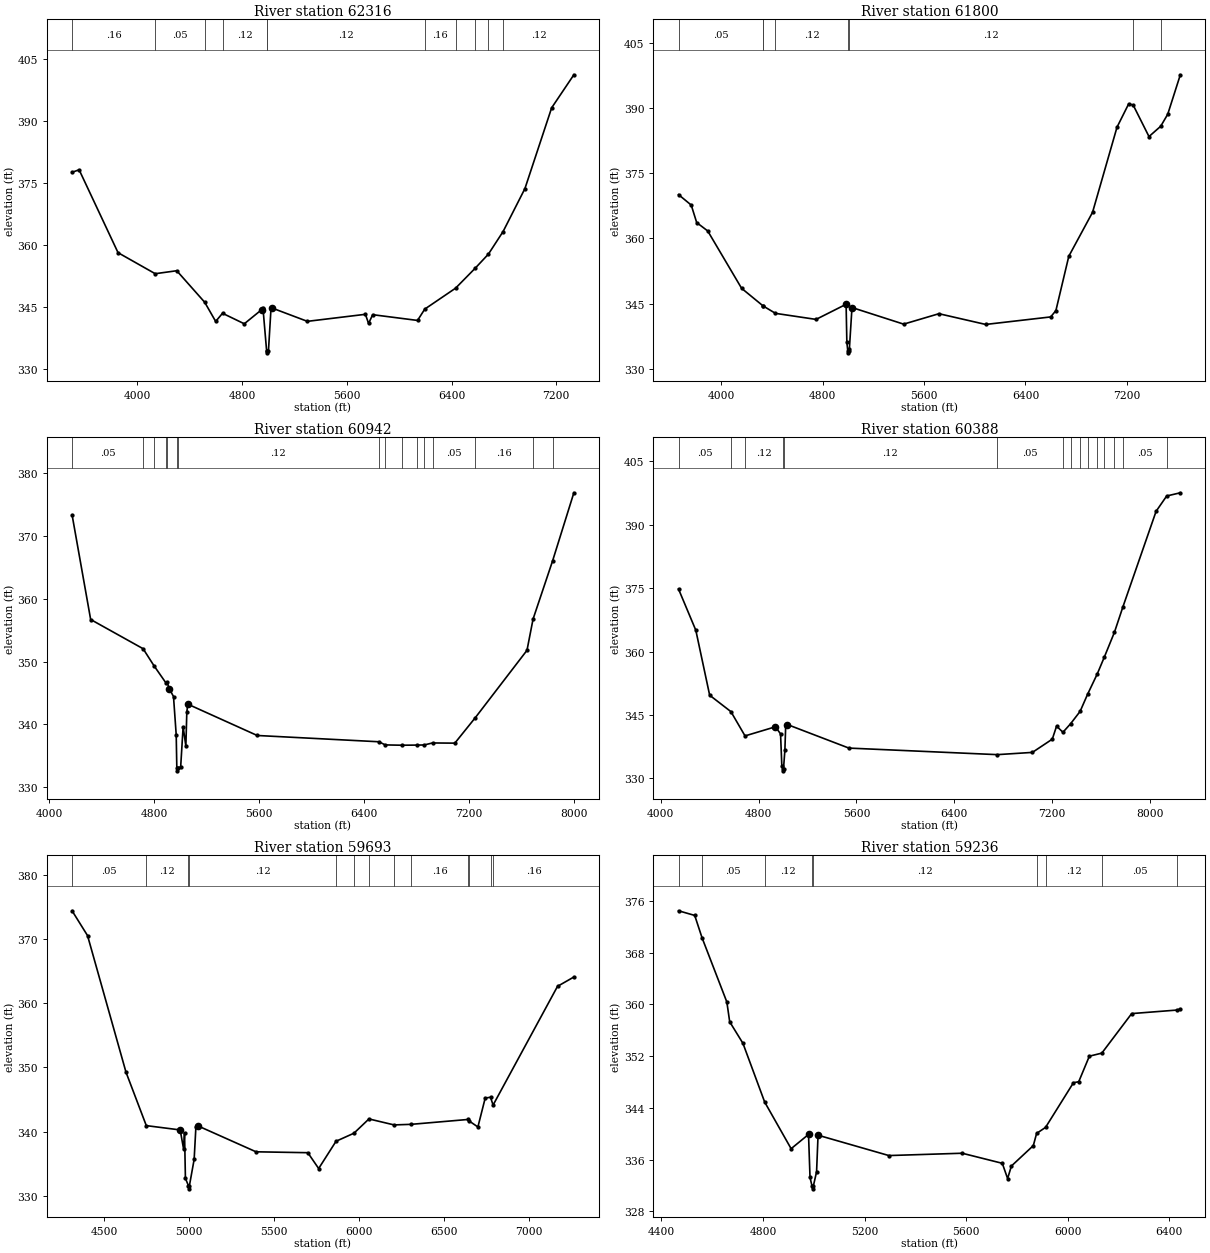
Type RM Length L Ch R = 1 ,62316   ,516,516,516
BEGIN DESCRIPTION:
CANEY CREEK 74.0
END DESCRIPTION:
XS GIS Cut Line= 2
      3564620.86     10618735.84      3568375.74     10617965.43
#Sta/Elev= 30
  3501.1  377.63    3555  378.23  3852.3   358.2  4136.3  353.12  4300.8  353.84
  4514.3  346.22  4598.1  341.59  4650.4  343.56  4816.7  341.02  4950.9  344.47
  4959.6  344.72  4987.2   334.5    4990     334  4993.2   334.5  5001.3  334.51
  5020.9   344.8  5031.1   344.8  5298.5  341.61  5741.9  343.31  5766.1  341.09
  5797.4  343.22    6140  341.83  6195.4  344.57  6430.9  349.63  6579.7  354.42
  6681.6  357.86  6793.8  363.32  6960.4  373.69  7164.6  393.21  7334.2  401.19
#Mann= 11 ,-1 , 0
  3501.1     .16       0  4136.3     .05       0  4514.3     .16       0
  4650.4     .12       0  4987.2     .07       0  4993.2     .12       0
  6195.4     .16       0  6430.9     .12       0  6579.7     .05       0
  6681.6     .16       0  6793.8     .12       0
Bank Sta=4950.9,5031.1
XS Rating Curve= 0 ,0
Exp/Cntr=0.3,0.1

Type RM Length L Ch R = 1 ,61800   ,858,858,858
BEGIN DESCRIPTION:
CANEY CREEK 73.0
END DESCRIPTION:
XS GIS Cut Line= 3
      3564768.19     10619141.23      3566252.59     10618906.85
      3568646.53     10618360.41
#Sta/Elev= 30
  3663.5  370.05  3763.7  367.64  3806.7  363.62  3893.7  361.69    4161   348.5
  4327.5  344.52  4329.6  344.46  4428.3  342.74  4748.2  341.35  4985.3  344.83
  4991.2  336.17  4998.3  334.16    5001  333.66  5004.3  334.16  5011.4  334.65
  5031.7  344.08  5439.2  340.26  5717.6  342.66  6086.4  340.19  6599.2  341.92
  6640.3  343.38  6742.1  355.88  6929.4  365.98  7122.4  385.56  7214.7  390.94
  7250.1  390.63  7374.6   383.4    7467  385.77  7522.4  388.53  7621.8  397.61
#Mann= 8 ,-1 , 0
  3663.5     .05       0  4327.5     .16       0  4329.6     .05       0
  4428.3     .12       0  4998.3     .07       0  5004.3     .12       0
  7250.1     .16       0    7467     .12       0
Bank Sta=4985.3,5031.7
XS Rating Curve= 0 ,0
Exp/Cntr=0.3,0.1

Type RM Length L Ch R = 1 ,60942   ,554,554,554
BEGIN DESCRIPTION:
CANEY CREEK 72.0
END DESCRIPTION:
XS GIS Cut Line= 3
      3564899.62     10619360.19      3565699.61     10619560.19
       3568099.6     10621360.19
#Sta/Elev= 30
  4175.5  373.39  4317.2  356.72  4716.8  352.07  4798.8  349.39  4893.7  346.54
  4899.2  346.75  4917.6  345.66  4948.6  344.45  4969.2  338.37  4973.9  333.12
  4976.7  332.62  4979.9  333.12  5003.2  333.22    5022  339.65  5042.8  336.56
  5050.1  341.97  5057.4  343.24  5586.6  338.25  6514.3  337.25  6562.3  336.75
  6686.8   336.7  6802.6  336.72  6859.3  336.74  6922.7  337.06  7092.8  337.03
  7249.1  341.09  7642.8  351.81  7689.2  356.79  7837.9  366.05  8000.1   376.9
#Mann= 16 ,-1 , 0
  4175.5     .05       0  4716.8     .16       0  4798.8     .05       0
  4893.7     .16       0  4899.2     .12       0  4973.9     .07       0
  4979.9     .12       0  6514.3     .05       0  6562.3     .12       0
  6686.8     .16       0  6802.6     .12       0  6859.3      .1       0
  6922.7     .05       0  7249.1     .16       0  7689.2     .08       0
  7837.9     .16       0
Bank Sta=4917.6,5057.4
XS Rating Curve= 0 ,0
Exp/Cntr=0.3,0.1

Type RM Length L Ch R = 1 ,60388   ,695,695,695
BEGIN DESCRIPTION:
CANEY CREEK 71.0
END DESCRIPTION:
XS GIS Cut Line= 3
       3564849.6     10619410.18      3565449.61     10620010.19
       3567649.6     10622410.18
#Sta/Elev= 30
  4145.2  374.77  4286.6  365.03  4399.8  349.67  4573.6  345.79  4689.1  340.05
  4937.2   342.2  4979.6  340.54  4990.2   332.9  4997.8  332.29  5000.6  331.79
  5003.8  332.29    5015  336.62  5021.8  342.55    5036  342.73  5538.5  337.17
  6752.2  335.62  7039.4  336.15  7202.2  339.28  7237.3  342.36  7289.5  340.91
  7352.3  342.94  7429.8  345.85  7490.3  349.85  7570.2  354.71  7628.4  358.72
  7710.6  364.56  7780.2  370.59  8051.3  393.16  8137.9  396.78  8249.5  397.54
#Mann= 15 ,-1 , 0
  4145.2     .05       0  4573.6     .16       0  4689.1     .12       0
  4997.8     .07       0  5003.8     .12       0  6752.2     .05       0
  7289.5     .08       0  7352.3     .05       0  7429.8     .16       0
  7490.3     .08       0  7570.2     .16       0  7628.4     .08       0
  7710.6     .16       0  7780.2     .05       0  8137.9     .16       0
Bank Sta=4937.2,5036
XS Rating Curve= 0 ,0
Exp/Cntr=0.3,0.1

Type RM Length L Ch R = 1 ,59693   ,457,457,457
BEGIN DESCRIPTION:
CANEY CREEK 70.0
END DESCRIPTION:
XS GIS Cut Line= 3
      3564651.05     10620438.98      3565401.89     10620621.26
      3566794.83      10622300.6
#Sta/Elev= 30
  4311.9  374.37    4403  370.51  4629.4  349.27    4749  340.96  4948.4  340.29
  4968.9  337.27  4974.1  339.81  4979.3  332.76  4996.9  331.63  4999.6  331.13
  5002.9  331.63  5030.7  335.71    5041  340.75  5051.3  340.94    5395  336.89
    5700  336.75  5763.8  334.29  5866.2  338.53  5971.5  339.78  6059.9     342
  6207.9  341.07  6308.5  341.16  6643.9  341.92  6651.7  341.65  6701.4  340.75
  6744.4  345.25  6775.6  345.37  6790.9  344.16  7170.2  362.62  7266.4  364.07
#Mann= 13 ,-1 , 0
  4311.9     .05       0    4749     .12       0  4996.9     .07       0
  5002.9     .12       0  5866.2     .16       0  5971.5     .12       0
  6059.9     .16       0  6207.9     .12       0  6308.5     .16       0
  6643.9     .05       0  6651.7     .08       0  6775.6     .05       0
  6790.9     .16       0
Bank Sta=4948.4,5051.3
XS Rating Curve= 0 ,0
Exp/Cntr=0.3,0.1

Type RM Length L Ch R = 1 ,59236   ,620,620,620
BEGIN DESCRIPTION:
CANEY CREEK 69.0
END DESCRIPTION:
XS GIS Cut Line= 3
      3564568.57     10620803.55      3565206.58     10621016.23
      3565953.09     10622083.91
#Sta/Elev= 30
  4467.9  374.49  4531.6  373.77  4560.3  370.33  4658.1  360.37  4669.3  357.31
  4721.4  353.98    4807  344.89  4911.1  337.67  4979.6  339.88  4985.5  333.22
    4993  331.96  4995.8  331.46    4999  331.96  5011.3   334.1  5017.1  339.76
  5295.9  336.61  5584.5  336.97  5742.4  335.41  5763.3  333.05  5778.2  334.99
  5864.5  338.15  5877.5  340.04  5912.7  340.97  6022.4  347.88  6043.3  348.04
  6085.1  351.99  6134.1  352.46  6251.7  358.58  6431.2  359.13  6443.2  359.29
#Mann= 9 ,-1 , 0
  4467.9     .16       0  4560.3     .05       0    4807     .12       0
    4993     .07       0    4999     .12       0  5877.5     .16       0
  5912.7     .12       0  6134.1     .05       0  6431.2     .08       0
Bank Sta=4979.6,5017.1
XS Rating Curve= 0 ,0
Exp/Cntr=0.3,0.1

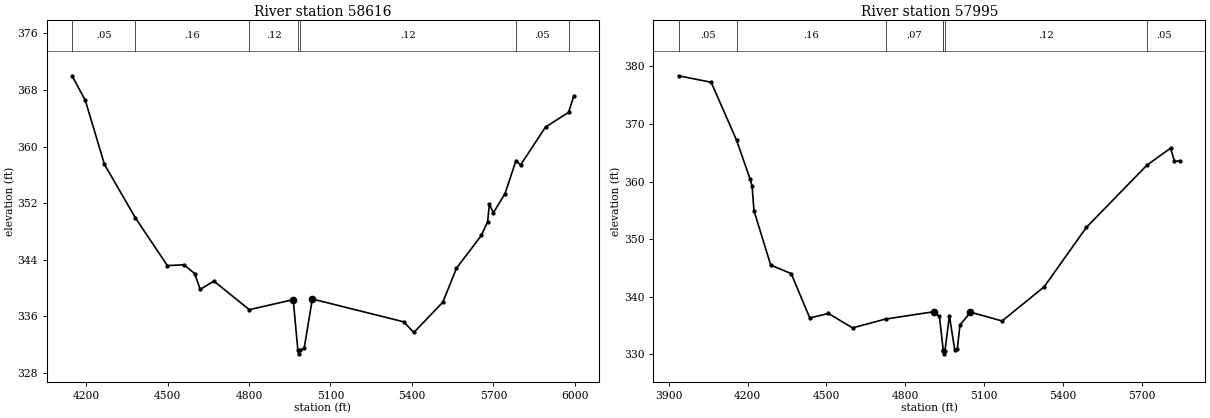
Type RM Length L Ch R = 1 ,58616   ,621,621,621
BEGIN DESCRIPTION:
CANEY CREEK 68.0
END DESCRIPTION:
XS GIS Cut Line= 3
      3564091.13     10621445.91      3565019.95     10621558.76
      3565753.46      10622101.3
#Sta/Elev= 30
  4148.3  370.01  4197.1  366.52  4267.7  357.46  4381.6   349.9  4499.3  343.15
  4560.8  343.26  4600.1     342  4620.2  339.77  4670.6  340.96    4801  336.91
  4962.7  338.33  4979.9  331.16  4982.6  330.66  4985.9  331.16    5003  331.43
  5033.2  338.42  5369.8  335.19  5406.9  333.68  5513.9  337.98    5564  342.78
  5655.8  347.42  5678.8  349.36  5685.1  351.88  5699.7  350.62  5742.8  353.33
  5783.3  358.02  5799.9  357.37    5892  362.76  5976.9  364.83  5996.3  367.18
#Mann= 7 ,-1 , 0
  4148.3     .05       0  4381.6     .16       0    4801     .12       0
  4979.9     .07       0  4985.9     .12       0  5783.3     .05       0
  5976.9     .08       0
Bank Sta=4962.7,5033.2
XS Rating Curve= 0 ,0
Exp/Cntr=0.3,0.1

Type RM Length L Ch R = 1 ,57995   ,118,118,118
BEGIN DESCRIPTION:
CANEY CREEK 67.0
END DESCRIPTION:
XS GIS Cut Line= 4
      3563960.13      10621534.3      3564524.38     10622106.88
      3564870.73      10622122.5      3565626.58     10622145.88
#Sta/Elev= 30
  3937.9  378.37  4061.9  377.24  4158.3  367.19  4210.4  360.36  4217.5  359.15
  4224.6  354.94  4288.2  345.48    4366  344.01  4436.7   336.3  4507.4  337.08
  4599.3  334.58  4724.5  336.11  4907.2  337.38  4929.2  336.56  4943.9  330.66
  4944.2  330.57    4947  330.07  4950.2  330.57  4967.2  336.68  4987.3  330.82
  4997.3   330.9  5007.3  335.06  5047.3  337.31  5167.4  335.78  5327.5  341.72
  5487.6  352.03  5717.7  362.84  5807.7   365.8  5822.5  363.49  5844.7  363.61
#Mann= 7 ,-1 , 0
  3937.9     .05       0  4158.3     .16       0  4724.5     .07       0
  4943.9     .12       0  4944.2     .07       0  4950.2     .12       0
  5717.7     .05       0
Bank Sta=4907.2,5047.3
XS Rating Curve= 0 ,0
Exp/Cntr=0.3,0.1