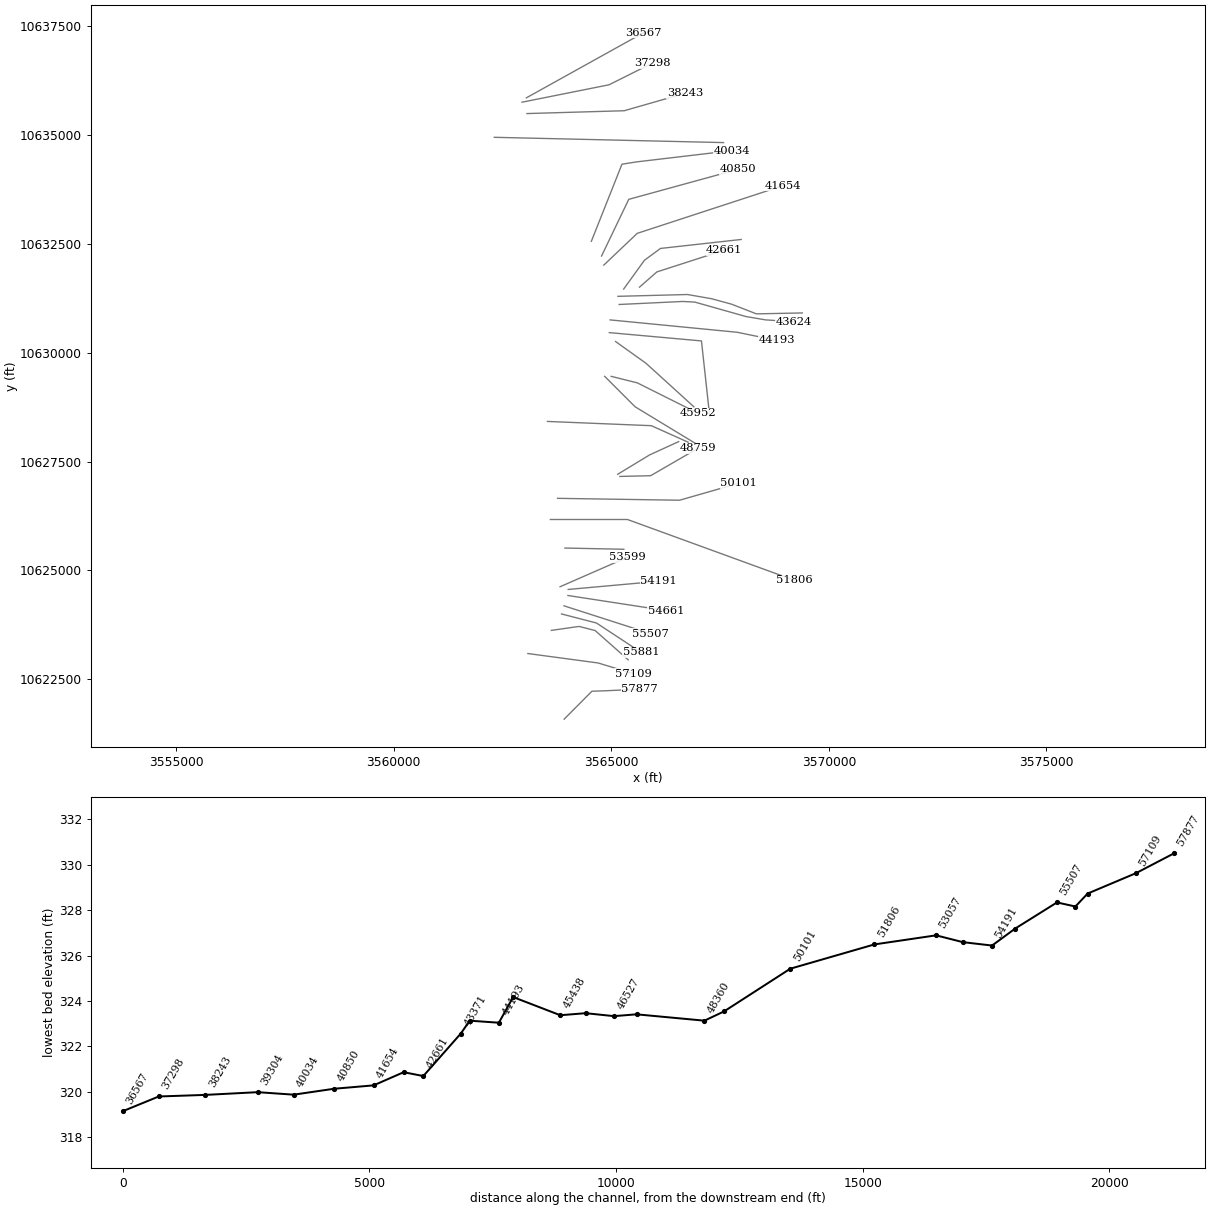
HEC-RAS study CANEY CREEK.prj: CANEY CREEK Base Level Engineering

--- CANEY CREEK.g01 (geometry) --- (continued)

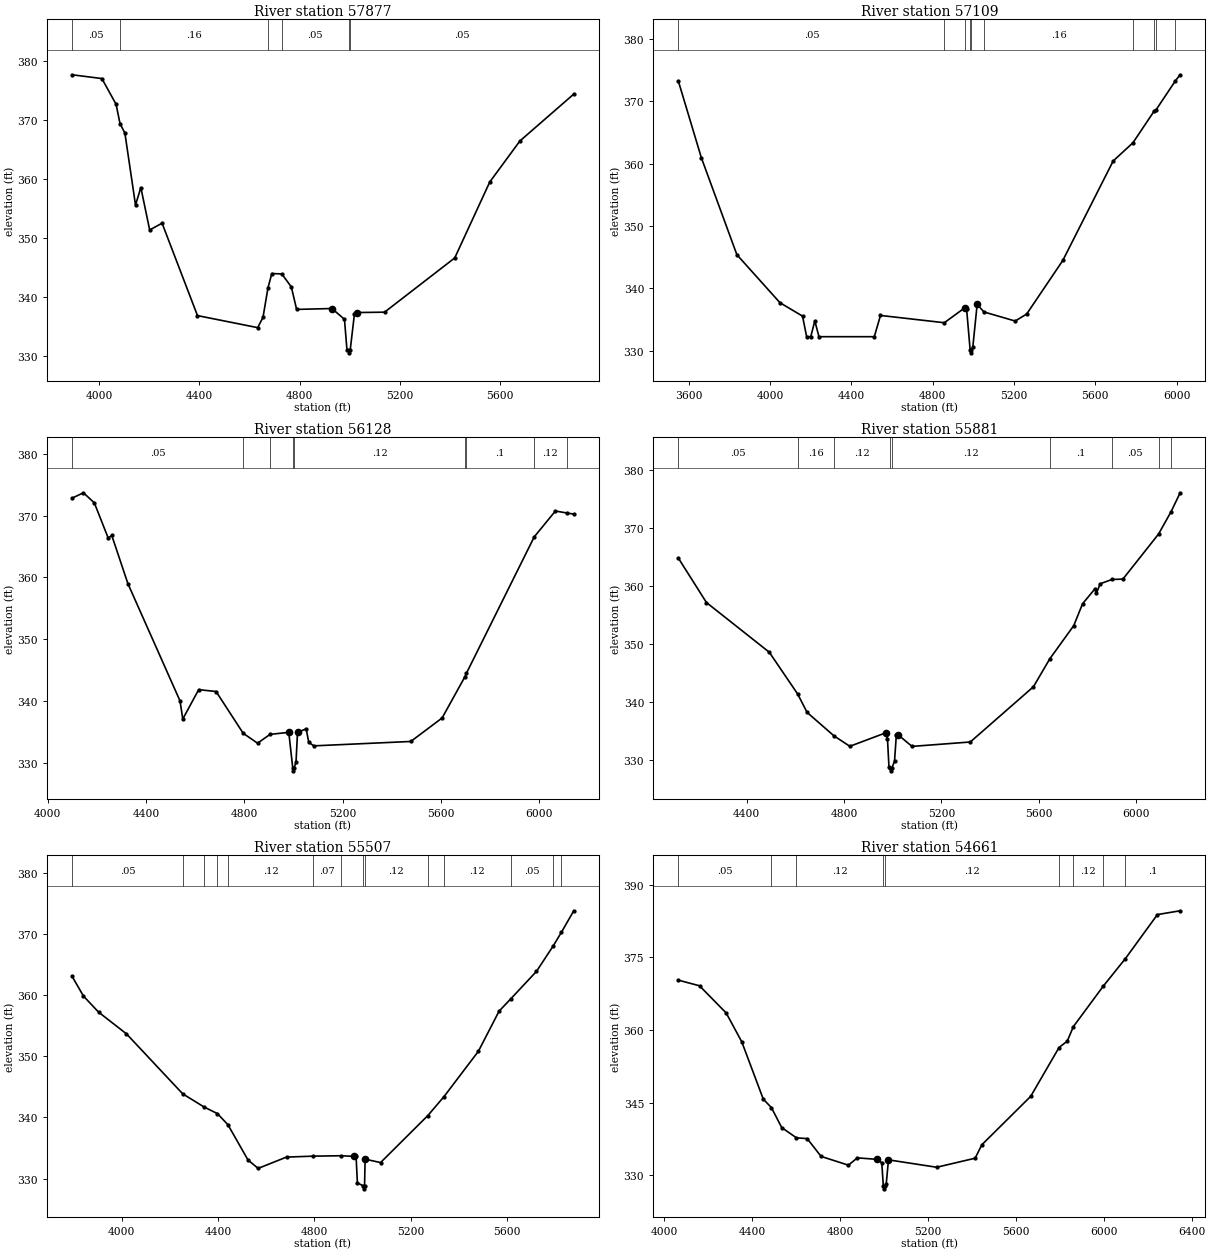
Type RM Length L Ch R = 1 ,57877   ,768,768,768
BEGIN DESCRIPTION:
CANEY CREEK 66.0
END DESCRIPTION:
XS GIS Cut Line= 4
      3563918.47     10621582.91      3564555.63     10622224.07
      3564857.71     10622234.48      3565654.61     10622270.94
#Sta/Elev= 30
  3891.4  377.62  4010.5  376.98  4067.1  372.63    4083  369.33  4102.4  367.74
  4144.8  355.55  4166.1  358.51  4201.4  351.32  4250.9  352.47  4392.3  336.81
  4632.8  334.77    4654  336.51  4673.9  341.51  4689.3  343.94  4729.1  343.87
  4767.1  341.68  4788.3  337.86  4929.4  338.01  4979.4  336.18  4989.4  331.02
  4996.4     331  4999.2   330.5  5002.4     331  5019.4  337.14  5029.4  337.33
  5139.5  337.39  5419.8  346.58    5560  359.47  5680.1   366.4  5895.3  374.35
#Mann= 6 ,-1 , 0
  3891.4     .05       0    4083     .16       0  4673.9     .08       0
  4729.1     .05       0  4996.4     .04       0  5002.4     .05       0
Bank Sta=4929.4,5029.4
XS Rating Curve= 0 ,0
Exp/Cntr=0.3,0.1

Type RM Length L Ch R = 1 ,57109   ,981,981,981
BEGIN DESCRIPTION:
CANEY CREEK 65.0
END DESCRIPTION:
XS GIS Cut Line= 3
      3563084.65     10623090.44       3564699.2     10622873.43
      3565502.15     10622630.38
#Sta/Elev= 30
  3549.7  373.18  3662.4  360.93  3837.2  345.37  4049.1  337.67  4160.1  335.52
  4180.3  332.22  4200.5  332.22  4220.6  334.76  4240.8  332.22  4513.2  332.22
  4543.5  335.63  4857.6  334.46  4957.2  336.83    4958  336.81  4967.3  336.64
  4984.5  330.13  4987.2  329.63  4990.5  330.13  4997.6   330.5  5019.1   337.4
  5052.5  336.19  5206.3  334.73  5262.8  335.86  5440.4  344.45  5688.2  360.41
  5785.5  363.33  5890.1  368.43    5900  368.66  5994.7  373.29  6017.7  374.24
#Mann= 10 ,-1 , 0
  3549.7     .05       0  4857.6     .16       0    4958     .12       0
  4984.5     .07       0  4990.5     .12       0  5052.5     .16       0
  5785.5      .1       0  5890.1     .05       0    5900      .1       0
  5994.7     .05       0
Bank Sta=4957.2,5019.1
XS Rating Curve= 0 ,0
Exp/Cntr=0.3,0.1

Type RM Length L Ch R = 1 ,56128   ,247,247,247
BEGIN DESCRIPTION:
CANEY CREEK 64.0
END DESCRIPTION:
XS GIS Cut Line= 4
      3563623.92     10623622.51      3564261.93     10623713.65
      3564630.86     10623618.16       3565390.4     10622945.43
#Sta/Elev= 30
  4099.5  372.83  4145.6   373.7  4190.1  372.07  4246.7  366.35  4260.9  366.81
  4326.5  359.01  4538.6  340.03  4549.7  337.11  4614.4  341.86  4685.1  341.56
  4795.3  334.81  4853.8   333.2  4904.7  334.63  4980.8  334.95  4996.8  329.23
  4999.6  328.73  5002.8  329.23  5010.2  330.14  5016.3  334.95  5051.5  335.52
    5062  333.34  5082.5  332.77  5476.9  333.48  5604.3  337.28  5697.2  343.96
  5702.9  344.49  5978.9  366.57  6064.9  370.75  6110.2  370.44  6139.7  370.25
#Mann= 9 ,-1 , 0
  4099.5     .05       0  4795.3     .16       0  4904.7     .12       0
  4996.8     .07       0  5002.8     .12       0  5697.2     .16       0
  5702.9      .1       0  5978.9     .12       0  6110.2      .1       0
Bank Sta=4980.8,5016.3
XS Rating Curve= 0 ,0
Exp/Cntr=0.3,0.1

Type RM Length L Ch R = 1 ,55881   ,374,374,374
BEGIN DESCRIPTION:
CANEY CREEK 63.0
END DESCRIPTION:
XS GIS Cut Line= 3
      3563858.28     10624000.11      3564661.24     10623791.78
      3565689.52     10623114.93
#Sta/Elev= 30
  4119.8  364.79  4234.8  357.16  4492.8   348.6  4609.4   341.4  4648.1  338.23
  4759.1  334.17  4823.7  332.39  4971.3  334.71  4978.4  333.63  4984.4  328.83
  4990.5  328.66  4993.3  328.16  4996.5  328.66  5007.3  329.82  5014.6  334.28
  5020.6  334.42  5079.1  332.37  5318.5  333.13  5577.8  342.65    5645  347.46
  5743.5  353.19  5779.6  356.95  5830.8  359.54  5836.8  358.78  5851.9  360.39
  5899.9  361.13  5945.3   361.2  6091.7  368.96  6143.1  372.81  6180.4  376.07
#Mann= 9 ,-1 , 0
  4119.8     .05       0  4609.4     .16       0  4759.1     .12       0
  4990.5     .07       0  4996.5     .12       0    5645      .1       0
  5899.9     .05       0  6091.7      .1       0  6143.1     .05       0
Bank Sta=4971.3,5020.6
XS Rating Curve= 0 ,0
Exp/Cntr=0.3,0.1

Type RM Length L Ch R = 1 ,55507   ,846,846,846
BEGIN DESCRIPTION:
CANEY CREEK 62.0
END DESCRIPTION:
XS GIS Cut Line= 2
      3563914.74     10624186.73      3565896.44     10623549.29
#Sta/Elev= 30
  3794.8  363.07  3841.9  359.85    3905  357.21  4020.5  353.67    4254  343.86
  4342.8  341.71  4398.1  340.63  4441.6  338.81  4524.7  333.06  4566.8  331.68
  4684.6  333.53    4795  333.68  4911.2  333.75  4965.9  333.64  4973.3  333.64
  4978.6  329.32  5002.4  328.84  5005.2  328.34  5008.4  328.84  5010.7  333.19
  5074.8  332.63  5271.1  340.32    5338  343.41  5480.7  350.82  5566.6  357.38
  5614.4  359.36  5721.8  363.88  5791.9  368.08  5824.9  370.25  5876.5  373.78
#Mann= 14 ,-1 , 0
  3794.8     .05       0    4254     .16       0  4342.8     .12       0
  4398.1     .16       0  4441.6     .12       0    4795     .07       0
  4911.2     .12       0  5002.4     .07       0  5008.4     .12       0
  5271.1      .1       0    5338     .12       0  5614.4     .05       0
  5791.9     .12       0  5824.9     .05       0
Bank Sta=4965.9,5010.7
XS Rating Curve= 0 ,0
Exp/Cntr=0.3,0.1

Type RM Length L Ch R = 1 ,54661   ,470,470,470
BEGIN DESCRIPTION:
CANEY CREEK 61.0
END DESCRIPTION:
XS GIS Cut Line= 2
      3564004.87     10624424.21      3566261.81     10624076.99
#Sta/Elev= 30
    4064  370.31  4159.9  369.15  4281.3  363.53  4352.1  357.58  4450.2  345.72
  4487.1  343.98  4534.2  339.84  4601.2  337.73    4650  337.57  4713.3  333.89
  4837.7  332.08  4878.2  333.59  4969.3  333.28  4989.5  332.57  4996.6  327.69
  4999.4  327.19  5002.6  327.69  5009.7  328.18  5019.9  333.18  5239.4  331.65
  5414.4  333.52  5444.8  336.29  5667.4  346.31  5796.2  356.39  5833.8  357.72
  5861.4  360.71  5997.6  369.08  6098.3  374.77  6244.1  383.87  6347.5  384.65
#Mann= 9 ,-1 , 0
    4064     .05       0  4487.1     .16       0  4601.2     .12       0
  4996.6     .07       0  5002.6     .12       0  5796.2     .05       0
  5861.4     .12       0  5997.6     .05       0  6098.3      .1       0
Bank Sta=4969.3,5019.9
XS Rating Curve= 0 ,0
Exp/Cntr=0.3,0.1

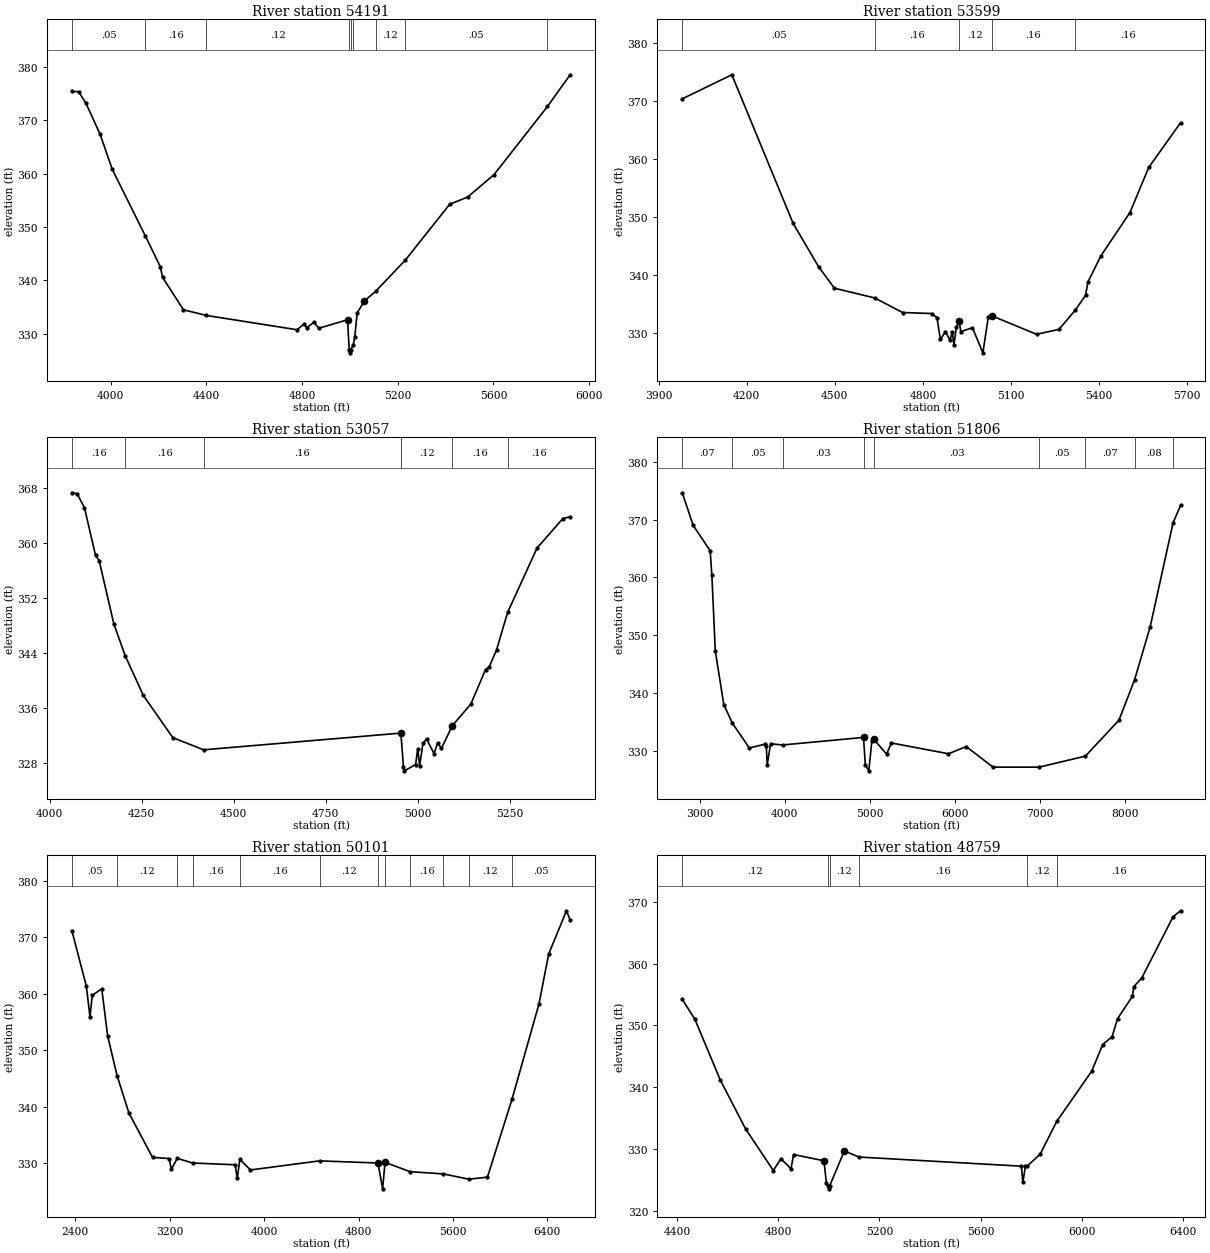
Type RM Length L Ch R = 1 ,54191   ,592,592,592
BEGIN DESCRIPTION:
CANEY CREEK 60.0
END DESCRIPTION:
XS GIS Cut Line= 2
      3564011.84     10624563.11       3566086.4     10624750.44
#Sta/Elev= 30
  3837.7  375.37  3865.7  375.33  3895.7  373.24    3956  367.33  4006.2  360.82
  4145.4  348.27    4207   342.6    4217  340.56    4304   334.5  4399.9  333.44
  4779.3  330.76  4809.4  331.88  4819.5  331.09  4849.6  332.19  4869.7  331.04
  4990.1  332.63  4997.2  326.94  4999.9  326.44  5003.2  326.94  5014.3  327.99
  5020.3  329.41  5030.3  333.89  5060.4  336.15  5107.1  337.93  5230.9  343.76
  5417.2  354.25  5492.2  355.61  5602.6   359.8    5826  372.57  5920.7   378.5
#Mann= 9 ,-1 , 0
  3837.7     .05       0  4145.4     .16       0  4399.9     .12       0
  4997.2     .07       0  5003.2     .12       0  5014.3     .16       0
  5107.1     .12       0  5230.9     .05       0    5826     .16       0
Bank Sta=4990.1,5060.4
XS Rating Curve= 0 ,0
Exp/Cntr=0.3,0.1

Type RM Length L Ch R = 1 ,53599   ,542,542,542
BEGIN DESCRIPTION:
CANEY CREEK 59.0
END DESCRIPTION:
XS GIS Cut Line= 2
      3563824.35     10624625.62      3565378.79     10625305.69
#Sta/Elev= 30
  3980.5  370.37  4149.3  374.52  4358.2  348.89  4444.7  341.44  4498.6  337.73
    4636  336.05  4730.9  333.54  4829.9  333.37  4847.9  332.65  4859.5  328.89
  4876.7  330.23  4892.2  328.78  4900.1  330.23  4905.6  327.95    4914     331
  4923.5  332.01  4928.9  330.24  4968.6  330.92  5004.3  326.59  5022.5  332.71
  5034.1  332.98  5186.9  329.79  5263.3  330.63  5318.4  333.92  5353.9   336.5
  5361.6  338.75  5406.1  343.31  5505.1  350.78  5568.9  358.54  5677.2  366.24
#Mann= 5 ,-1 , 0
  3980.5     .05       0    4636     .16       0  4923.5     .12       0
  5034.1     .16       0  5318.4     .16       0
Bank Sta=4923.5,5034.1
XS Rating Curve= 0 ,0
Exp/Cntr=0.3,0.1

Type RM Length L Ch R = 1 ,53057   ,1251,1251,1251
BEGIN DESCRIPTION:
CANEY CREEK 58.0
END DESCRIPTION:
XS GIS Cut Line= 2
      3563935.38     10625514.49       3565289.6     10625486.71
#Sta/Elev= 30
  4060.3  367.34  4074.5   367.2  4094.5  365.17  4124.5  358.24  4134.5  357.45
  4174.6  348.21  4205.8  343.56  4254.6  337.86  4334.6  331.72  4418.4  329.95
  4954.7  332.38  4961.7  327.39  4964.5  326.89  4994.7   327.8  5000.6   330.1
  5005.6  327.62  5014.7   330.9  5024.7  331.52  5044.7   329.4  5054.7  330.96
  5064.7  330.15  5094.7  333.47  5144.8   336.6  5184.8  341.62  5194.8     342
  5214.8  344.49  5244.8  349.93  5324.8   359.3  5394.8  363.58  5414.8  363.85
#Mann= 6 ,-1 , 0
  4060.3     .16       0  4205.8     .16       0  4418.4     .16       0
  4954.7     .12       0  5094.7     .16       0  5244.8     .16       0
Bank Sta=4954.7,5094.7
XS Rating Curve= 0 ,0
Exp/Cntr=0.3,0.1

Type RM Length L Ch R = 1 ,51806   ,1705,1705,1705
BEGIN DESCRIPTION:
CANEY CREEK 57.0
END DESCRIPTION:
XS GIS Cut Line= 3
      3563601.67     10626170.81      3565372.49     10626170.81
      3569209.26     10624773.26
#Sta/Elev= 30
  2796.7  374.66  2924.6  369.02  3124.6  364.62  3144.6  360.38  3184.6  347.27
  3284.6  337.97  3384.6  334.78  3584.6  330.45  3774.6  331.13  3784.6  330.74
  3794.6  327.49  3834.6  331.18  3974.6  330.97  4926.3  332.28  4947.6  327.51
  4988.7  326.49  5024.8  331.74  5050.1  331.92  5197.6  329.38  5253.4  331.32
  5924.7  329.45  6133.4  330.69  6448.2  327.13  6990.4  327.13  7533.1  329.04
  7927.6  335.26  8111.3  342.26  8294.7  351.45  8563.4  369.44  8650.9  372.46
#Mann= 9 ,-1 , 0
  2796.7     .07       0  3384.6     .05       0  3974.6     .03       0
  4926.3     .01       0  5050.1     .03       0  6990.4     .05       0
  7533.1     .07       0  8111.3     .08       0  8563.4     .12       0
Bank Sta=4926.3,5050.1
XS Rating Curve= 0 ,0
Exp/Cntr=0.3,0.1

Type RM Length L Ch R = 1 ,50101   ,1342,1342,1342
BEGIN DESCRIPTION:
CANEY CREEK 56.0
END DESCRIPTION:
XS GIS Cut Line= 3
      3563766.58     10626656.92      3566570.41     10626613.52
      3567933.27     10627004.15
#Sta/Elev= 30
  2370.8  371.19  2493.8  361.32  2523.8  355.94  2543.8  359.76  2623.9  360.89
  2673.9  352.51  2753.9  345.49  2853.9  338.87  3053.9     331  3193.9   330.8
  3213.9  328.89  3263.9  330.83  3393.2     330    3754  329.69    3772  327.27
    3794  330.65    3884  328.77  4469.5  330.38  4964.1     330  5003.9  325.42
  5024.1  330.12  5236.5  328.46  5517.4  328.07  5734.4  327.13  5891.9  327.49
    6100  341.29  6328.8   358.2  6410.9  367.06  6561.5  374.73  6592.7  373.12
#Mann= 12 ,-1 , 0
  2370.8     .05       0  2753.9     .12       0  3263.9     .12       0
  3393.2     .16       0    3794     .16       0  4469.5     .12       0
  4964.1      .1       0  5024.1     .12       0  5236.5     .16       0
  5517.4     .07       0  5734.4     .12       0    6100     .05       0
Bank Sta=4964.1,5024.1
XS Rating Curve= 0 ,0
Exp/Cntr=0.3,0.1

Type RM Length L Ch R = 1 ,48759   ,399,399,399
BEGIN DESCRIPTION:
CANEY CREEK 54.0
END DESCRIPTION:
XS GIS Cut Line= 3
      3565199.62     10627160.19      3565905.03     10627176.82
      3566999.59     10627810.18
#Sta/Elev= 30
  4420.4  354.24  4470.4     351  4570.4   341.2  4670.5  333.27  4780.5  326.51
  4810.5  328.42  4850.5  326.78  4860.5   329.1  4980.5  328.09  4990.5  324.47
  4997.5  324.04  5000.3  323.54  5003.5  324.04  5061.2  329.68  5119.2  328.69
  5761.3  327.21  5767.1  324.58  5777.1  327.16  5785.1  327.24  5835.9  329.18
  5901.7   334.5  6039.7  342.61  6082.8   346.9  6120.1  348.18  6141.6  351.11
  6200.5  354.73  6206.2   356.3  6237.8  357.72  6361.2  367.61  6390.6  368.58
#Mann= 6 ,-1 , 0
  4420.4     .12       0  4997.5     .07       0  5003.5     .12       0
  5119.2     .16       0  5785.1     .12       0  5901.7     .16       0
Bank Sta=4980.5,5061.2
XS Rating Curve= 0 ,0
Exp/Cntr=0.3,0.1

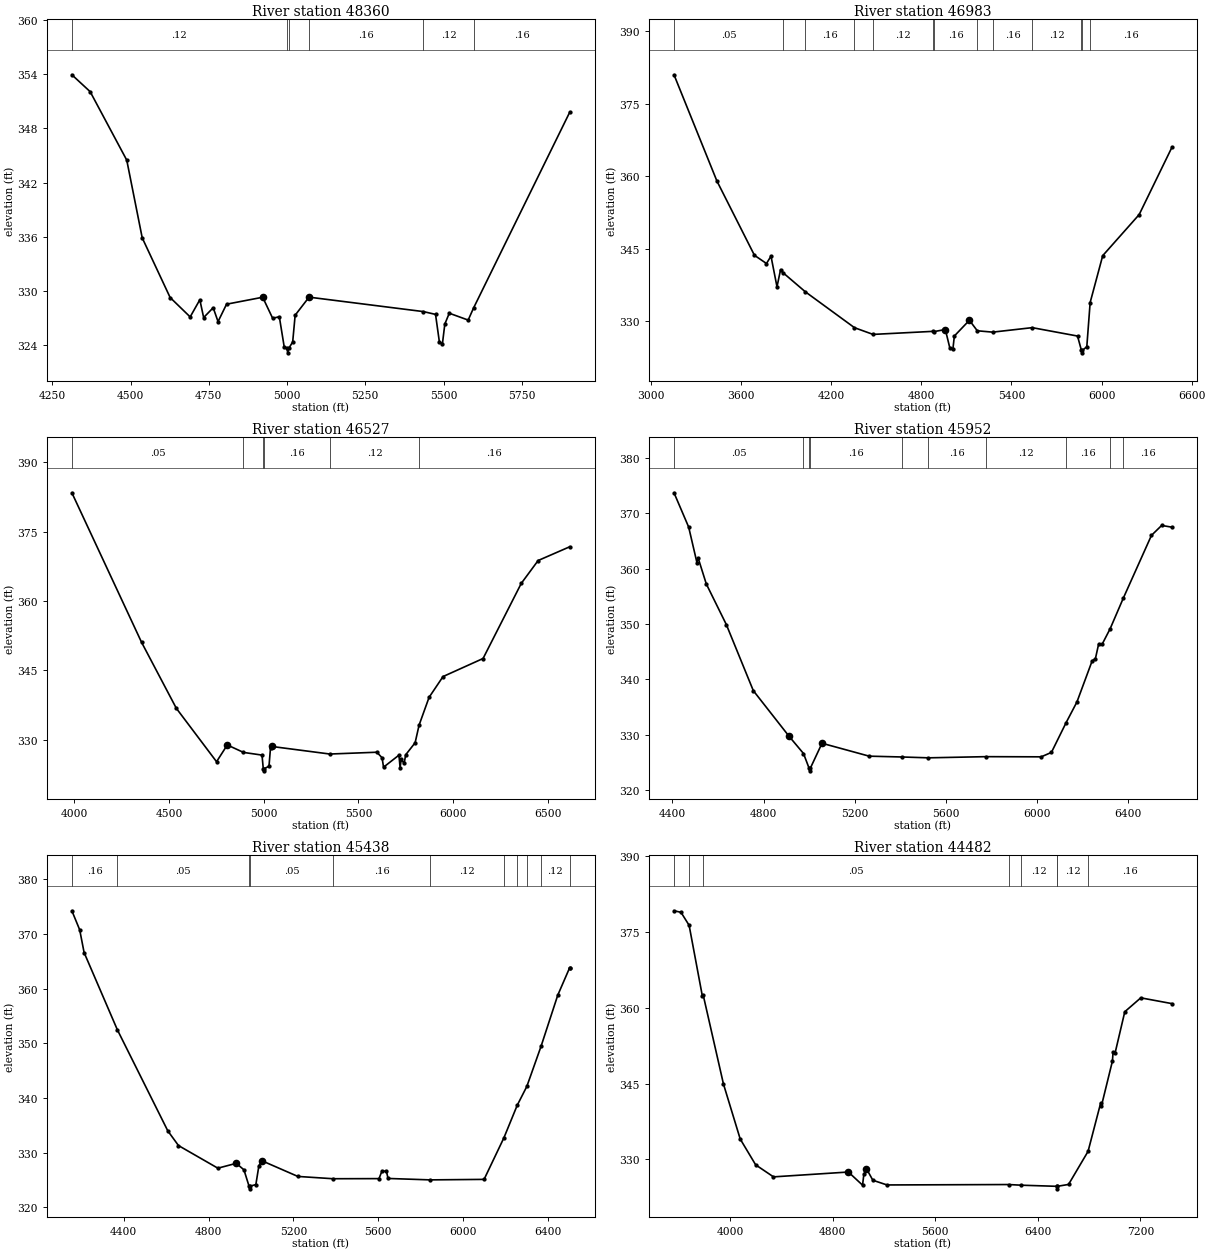
Type RM Length L Ch R = 1 ,48360   ,1377,1377,1377
BEGIN DESCRIPTION:
CANEY CREEK 53.0
END DESCRIPTION:
XS GIS Cut Line= 3
      3565149.64     10627210.21       3565884.2     10627655.99
      3566549.62     10627960.19
#Sta/Elev= 30
  4312.3  353.94  4370.7  352.07  4487.7  344.48  4537.1  335.87  4626.3  329.26
  4690.3  327.11  4721.2  329.01  4733.4  327.04  4763.9  328.13  4779.4  326.59
  4806.6  328.52 4922.05  329.29  4953.9  326.96  4975.2  327.13  4990.7  323.82
  4999.4  323.63  5002.2  323.13  5005.4  323.63  5017.9  324.33  5025.8   327.3
  5070.2   329.3  5435.6   327.7  5474.4  327.39  5486.6  324.36  5496.4  324.13
  5504.1  326.32  5518.3  327.52  5578.7  326.76  5595.8  328.09  5903.2  349.79
#Mann= 6 ,-1 , 0
  4312.3     .12       0  4999.4     .07       0  5005.4     .12       0
  5070.2     .16       0  5435.6     .12       0  5595.8     .16       0
Bank Sta=4922.05,5070.2
XS Rating Curve= 0 ,0
Exp/Cntr=0.3,0.1

Type RM Length L Ch R = 1 ,46983   ,456,456,456
BEGIN DESCRIPTION:
CANEY CREEK 52.0
END DESCRIPTION:
XS GIS Cut Line= 3
      3563534.37     10628424.14      3565921.54     10628326.48
      3566766.23     10627947.45
#Sta/Elev= 30
  3153.1  381.03  3438.6  359.03  3688.8  343.62  3768.9  341.92  3798.9  343.45
  3838.9  337.09  3862.7  340.66  3877.7  340.05    4028  336.05  4354.9  328.62
  4478.5  327.23  4875.8  327.86  4883.9  327.81  4959.8  328.24  4989.9   324.4
  5009.9  324.11  5019.9   326.9    5120  330.16  5172.7  327.98  5275.1   327.7
  5538.4  328.63  5840.1  326.89    5866  323.91  5868.7  323.41    5872  323.91
  5901.8  324.68  5924.1  333.84  6007.8  343.55  6250.5  352.06  6468.1  365.97
#Mann= 13 ,-1 , 0
  3153.1     .05       0  3877.7     .12       0    4028     .16       0
  4354.9     .07       0  4478.5     .12       0  4875.8     .05       0
  4883.9     .16       0  5172.7     .12       0  5275.1     .16       0
  5538.4     .12       0    5866     .07       0    5872     .12       0
  5924.1     .16       0
Bank Sta=4959.8,5120
XS Rating Curve= 0 ,0
Exp/Cntr=0.3,0.1

Type RM Length L Ch R = 1 ,46527   ,575,575,575
BEGIN DESCRIPTION:
CANEY CREEK 51.0
END DESCRIPTION:
XS GIS Cut Line= 3
      3564849.58     10629460.22      3565549.61     10628760.19
      3566949.59      10627910.2
#Sta/Elev= 30
  3987.1  383.38  4354.8   351.1  4538.7  336.82  4750.8   325.3  4807.4  328.92
  4892.9  327.31  4990.7  326.73  4997.3  323.83  5000.1  323.33  5003.3  323.83
  5027.5  324.31  5035.6  328.33    5043  328.59  5348.7  326.96  5597.1  327.35
  5624.5  326.14  5632.2  324.12  5713.6  326.72  5719.5  324.04  5725.8  325.84
  5740.8  324.92  5749.2   326.8  5798.9   329.4  5819.7  333.19  5872.6  339.21
  5946.2  343.69  6157.5  347.59  6359.1  363.81  6448.2  368.75  6614.9  371.72
#Mann= 6 ,-1 , 0
  3987.1     .05       0  4892.9     .16       0  4997.3     .07       0
  5003.3     .16       0  5348.7     .12       0  5819.7     .16       0
Bank Sta=4807.4,5043
XS Rating Curve= 0 ,0
Exp/Cntr=0.3,0.1

Type RM Length L Ch R = 1 ,45952   ,514,514,514
BEGIN DESCRIPTION:
CANEY CREEK 50.0
END DESCRIPTION:
XS GIS Cut Line= 3
      3564999.59     10629460.19      3565599.61     10629310.19
      3566999.58      10628610.2
#Sta/Elev= 30
    4407  373.68  4471.4  367.48  4507.5  361.08  4512.7  361.93  4548.7  357.21
  4636.4  349.89  4754.9  337.94  4912.1  329.68    4975  326.59  4999.3  323.96
    5002  323.46  5005.3  323.96  5056.2  328.44  5263.1  326.11  5408.6  325.96
  5522.9  325.81  5774.2  326.02  6017.7  325.99  6062.5  326.79  6127.1  332.18
  6174.3  335.89  6241.3  343.34  6255.3   343.7  6269.3  346.31  6286.1  346.42
  6320.1  349.13  6378.2  354.69  6501.3  365.99    6546  367.78  6590.7  367.47
#Mann= 10 ,-1 , 0
    4407     .05       0    4975     .16       0  4999.3     .07       0
  5005.3     .16       0  5408.6     .12       0  5522.9     .16       0
  5774.2     .12       0  6127.1     .16       0  6320.1     .12       0
  6378.2     .16       0
Bank Sta=4912.1,5056.2
XS Rating Curve= 0 ,0
Exp/Cntr=0.3,0.1

Type RM Length L Ch R = 1 ,45438   ,956,956,956
BEGIN DESCRIPTION:
CANEY CREEK 49.0
END DESCRIPTION:
XS GIS Cut Line= 3
      3565099.62     10630260.18      3565799.61     10629760.19
      3566899.59      10628760.2
#Sta/Elev= 30
  4155.7  374.26  4192.6  370.77  4213.4  366.61    4370  352.49  4607.9  333.98
  4658.3  331.29  4843.9  327.15 4930.68  328.04  4966.8  326.85  4990.8  323.87
  4993.5  323.37  4996.8  323.87    5023  324.15  5037.2  327.58  5051.4  328.51
    5221  325.64  5386.9  325.22  5603.5  325.24  5617.7  326.65  5638.6  326.58
    5646  325.27  5844.2  325.01  6098.8   325.1  6192.4  332.72    6255  338.66
  6300.3  342.11  6367.4  349.46  6446.1  358.81  6501.7  363.79  6502.5  363.79
#Mann= 11 ,-1 , 0
  4155.7     .16       0    4370     .05       0  4990.8     .03       0
  4996.8     .05       0  5386.9     .16       0  5844.2     .12       0
  6192.4     .16       0    6255     .12       0  6300.3     .16       0
  6367.4     .12       0  6501.7     .16       0
Bank Sta=4930.68,5051.4
XS Rating Curve= 0 ,0
Exp/Cntr=0.3,0.1

Type RM Length L Ch R = 1 ,44482   ,289,289,289
BEGIN DESCRIPTION:
CANEY CREEK 48.0
END DESCRIPTION:
XS GIS Cut Line= 3
      3564955.41     10630465.15      3567073.45     10630274.18
      3567264.42     10628529.43
#Sta/Elev= 30
  3563.5  379.23  3617.9  378.93  3681.4  376.35  3784.7  362.33  3790.5  362.62
  3949.3  344.91  4079.8  334.03  4200.3  328.92  4339.2  326.54  4923.2   327.5
  5033.6   324.9  5043.7  327.02  5063.8  328.17    5114  325.87  5224.4  324.94
  6173.6  325.02  6271.8  324.89  6546.2  324.67    6549  324.17  6552.2  324.67
  6639.8  325.04    6792  331.59  6890.9  341.22  6895.9  340.56  6981.8  349.45
  6987.2  351.25  7001.9  350.98  7078.4  359.24  7203.1  361.99  7445.3  360.85
#Mann= 8 ,-1 , 0
  3563.5     .05       0  3681.4     .16       0  3790.5     .05       0
  6173.6      .1       0  6271.8     .12       0  6546.2     .03       0
  6552.2     .12       0    6792     .16       0
Bank Sta=4923.2,5063.8
XS Rating Curve= 0 ,0
Exp/Cntr=0.3,0.1

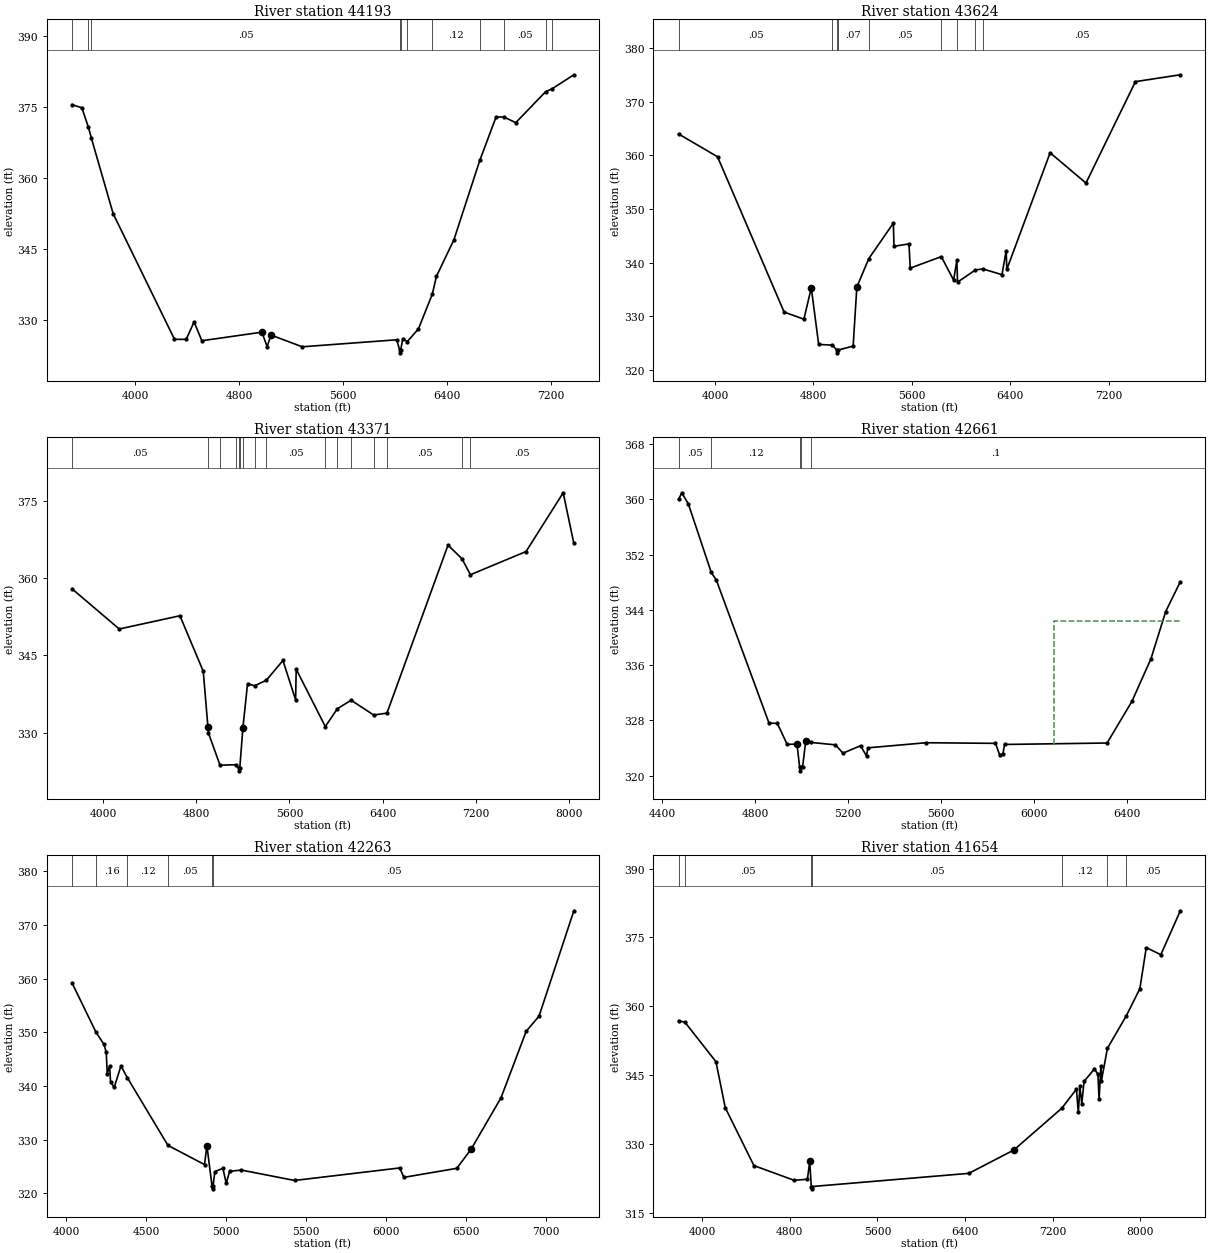
Type RM Length L Ch R = 1 ,44193   ,591,591,591
BEGIN DESCRIPTION:
CANEY CREEK 47.0
END DESCRIPTION:
XS GIS Cut Line= 3
       3564974.5      10630757.4       3567898.1     10630472.68
      3568806.18     10630285.52
#Sta/Elev= 30
  3513.6   375.5  3589.1  374.83    3640  370.67    3663  368.35  3830.2  352.44
  4302.4   325.9  4392.9  325.89  4453.1  329.58  4513.4   325.6  4975.6  327.41
  5015.8  324.35  5045.9   326.8  5286.2  324.32    6014   325.8  6037.6  323.54
  6040.4  323.04  6043.6  323.54  6060.7  325.98  6095.9  325.43  6181.3  328.11
  6288.5  335.48  6319.4  339.19  6454.4  346.94  6654.3  363.76  6779.3   372.9
  6840.6  372.88  6930.7  371.68    7160  378.22  7208.8  378.82  7378.2  381.81
#Mann= 11 ,-1 , 0
  3513.6     .05       0    3640     .16       0    3663     .05       0
  6037.6     .03       0  6043.6     .05       0  6095.9     .16       0
  6288.5     .12       0  6654.3     .16       0  6840.6     .05       0
    7160     .16       0  7208.8     .05       0
Bank Sta=4975.6,5045.9
XS Rating Curve= 0 ,0
Exp/Cntr=0.3,0.1

Type RM Length L Ch R = 1 ,43624   ,182,182,182
BEGIN DESCRIPTION:
CANEY CREEK 46.0
END DESCRIPTION:
XS GIS Cut Line= 6
       3565182.8     10631111.57      3566641.16     10631181.01
      3566918.94     10631167.12      3568099.49     10630833.79
      3568550.88      10630757.4      3569203.63     10630715.74
#Sta/Elev= 30
    3704  364.01    4021  359.75  4561.9  330.75  4722.7  329.41  4782.8  335.27
  4842.9   324.7  4953.4  324.57  4990.9  323.63  4993.6  323.13  4996.9  323.63
    5123  324.39  5153.1  335.42  5250.3  340.73  5449.9  347.35    5455  343.03
  5576.7  343.47  5587.3  338.95  5839.4   341.1  5939.9   336.7  5965.9  340.48
  5971.5  336.33  6116.8  338.61  6177.2   338.8  6332.7  337.73  6366.7   342.2
  6371.9  338.72  6723.9  360.49  7015.2  354.84  7417.3  373.78  7782.1  375.06
#Mann= 9 ,-1 , 0
    3704     .05       0  4953.4     .07       0  4990.9     .07       0
  4996.9     .07       0  5250.3     .05       0  5839.4     .12       0
  5965.9     .05       0  6116.8     .16       0  6177.2     .05       0
Bank Sta=4782.8,5153.1
XS Rating Curve= 0 ,0
Exp/Cntr=0.3,0.1

Type RM Length L Ch R = 1 ,43371   ,759,759,759
BEGIN DESCRIPTION:
CANEY CREEK 45.0
END DESCRIPTION:
XS GIS Cut Line= 6
      3565155.01     10631299.07      3566752.27     10631340.73
      3567307.82     10631243.51      3567766.16     10631118.51
       3568335.6     10630896.29      3569391.14     10630917.12
#Sta/Elev= 30
  3735.4  357.88  4140.4  350.09  4660.9  352.66  4861.1  341.88  4901.1  331.05
  4905.8  329.88  5004.8  323.66  5138.4  323.74  5168.1  323.06  5170.9  322.56
  5174.1  323.06  5201.1  330.85  5202.8  331.24  5241.1  339.49  5301.8  339.07
  5402.2  340.14  5544.7  343.98  5653.4  336.34  5658.5  342.29  5908.2  331.15
  6011.8  334.62  6129.7  336.26  6322.8   333.4    6437  333.76  6961.2  366.36
  7080.6  363.74  7153.3  360.62  7630.9  365.13  7949.2  376.53  8040.9   366.7
#Mann= 16 ,-1 , 0
  3735.4     .05       0  4905.8     .07       0  5004.8     .05       0
  5138.4     .07       0  5168.1     .07       0  5174.1     .07       0
  5202.8     .05       0  5301.8     .07       0  5402.2     .05       0
  5908.2      .1       0  6011.8     .08       0  6129.7     .05       0
  6322.8     .08       0    6437     .05       0  7080.6     .08       0
  7153.3     .05       0
Bank Sta=4901.1,5201.1
XS Rating Curve= 0 ,0
Exp/Cntr=0.3,0.1

Type RM Length L Ch R = 1 ,42661   ,398,398,398
BEGIN DESCRIPTION:
CANEY CREEK 44.0
END DESCRIPTION:
XS GIS Cut Line= 3
      3565649.61     10631510.19      3566049.61     10631860.19
      3567599.65      10632360.2
#Sta/Elev= 30
  4470.2  359.99    4484  360.96  4512.4  359.36  4611.1  349.42    4633  348.31
  4859.8   327.6  4895.4  327.57  4937.6  324.53  4980.3  324.55  4991.6  321.19
  4994.3  320.69  4997.6  321.19  5004.3  321.27  5017.7  324.96  5039.5  324.81
  5145.9  324.45    5178  323.25  5253.9  324.33  5279.4  322.84  5285.4  324.02
  5535.7  324.76  5834.7  324.67  5852.8  322.98  5866.7  323.16  5873.8  324.51
  6315.1  324.72    6422  330.75  6504.3  336.95  6567.3  343.75  6630.4  348.08
#Mann= 5 ,-1 , 0
  4470.2     .05       0  4611.1     .12       0  4991.6     .07       0
  4997.6     .12       0  5039.5      .1       0
#XS Ineff= 2 , 0
                         6086.36           342.4
Permanent Ineff=
       F       F
Bank Sta=4980.3,5017.7
XS Rating Curve= 0 ,0
Exp/Cntr=0.3,0.1

Type RM Length L Ch R = 1 ,42263   ,609,609,609
BEGIN DESCRIPTION:
CANEY CREEK 43.0
END DESCRIPTION:
XS GIS Cut Line= 4
      3565286.16     10631466.53      3565763.57     10632128.41
       3566132.5     10632399.67      3567986.28     10632605.65
#Sta/Elev= 30
  4036.4   359.2  4186.1  350.03  4235.5  347.78  4250.2  346.31  4256.3  342.29
    4271  343.75  4277.2  340.82  4299.8  339.74  4342.2  343.74  4381.9  341.57
  4636.3  328.95  4865.1  325.38  4879.7  328.93  4912.2  321.36    4915  320.86
  4918.2  321.36  4929.9  324.08    4980  324.68  5000.9  321.88  5021.7  324.12
  5094.9  324.36  5428.2  322.42    6086  324.75  6112.4     323  6443.2  324.68
  6533.8  328.29  6719.9  337.82  6877.1  350.19  6957.6  353.02  7175.6  372.65
#Mann= 6 ,-1 , 0
  4036.4     .05       0  4186.1     .16       0  4381.9     .12       0
  4636.3     .05       0  4912.2     .03       0  4918.2     .05       0
Bank Sta=4879.7,6533.8
XS Rating Curve= 0 ,0
Exp/Cntr=0.3,0.1

Type RM Length L Ch R = 1 ,41654   ,804,804,804
BEGIN DESCRIPTION:
CANEY CREEK 42.0
END DESCRIPTION:
XS GIS Cut Line= 3
      3564829.95     10632017.38      3565598.16     10632746.52
       3568944.5     10633840.27
#Sta/Elev= 30
  3784.5  356.89  3844.4  356.51  4125.9  347.96  4210.8  337.95  4472.5  325.34
  4840.2  322.13  4960.9  322.37  4981.9  326.26    4996  320.78  4998.8  320.28
    5002  320.78  6433.8  323.65  6844.1  328.72  7281.8  337.82  7415.9  341.97
  7433.2  336.91  7447.8  342.58  7464.8   338.8  7485.8  343.67  7580.6  346.41
  7612.4  345.18  7622.6   339.8  7639.1  346.93  7644.3  343.81  7698.7  350.86
  7871.9  357.98  7994.9  363.85  8053.4   372.8  8186.2  371.25  8364.2  380.81
#Mann= 7 ,-1 , 0
  3784.5     .12       0  3844.4     .05       0    4996     .03       0
    5002     .05       0  7281.8     .12       0  7698.7     .16       0
  7871.9     .05       0
Bank Sta=4981.9,6844.1
XS Rating Curve= 0 ,0
Exp/Cntr=0.3,0.1

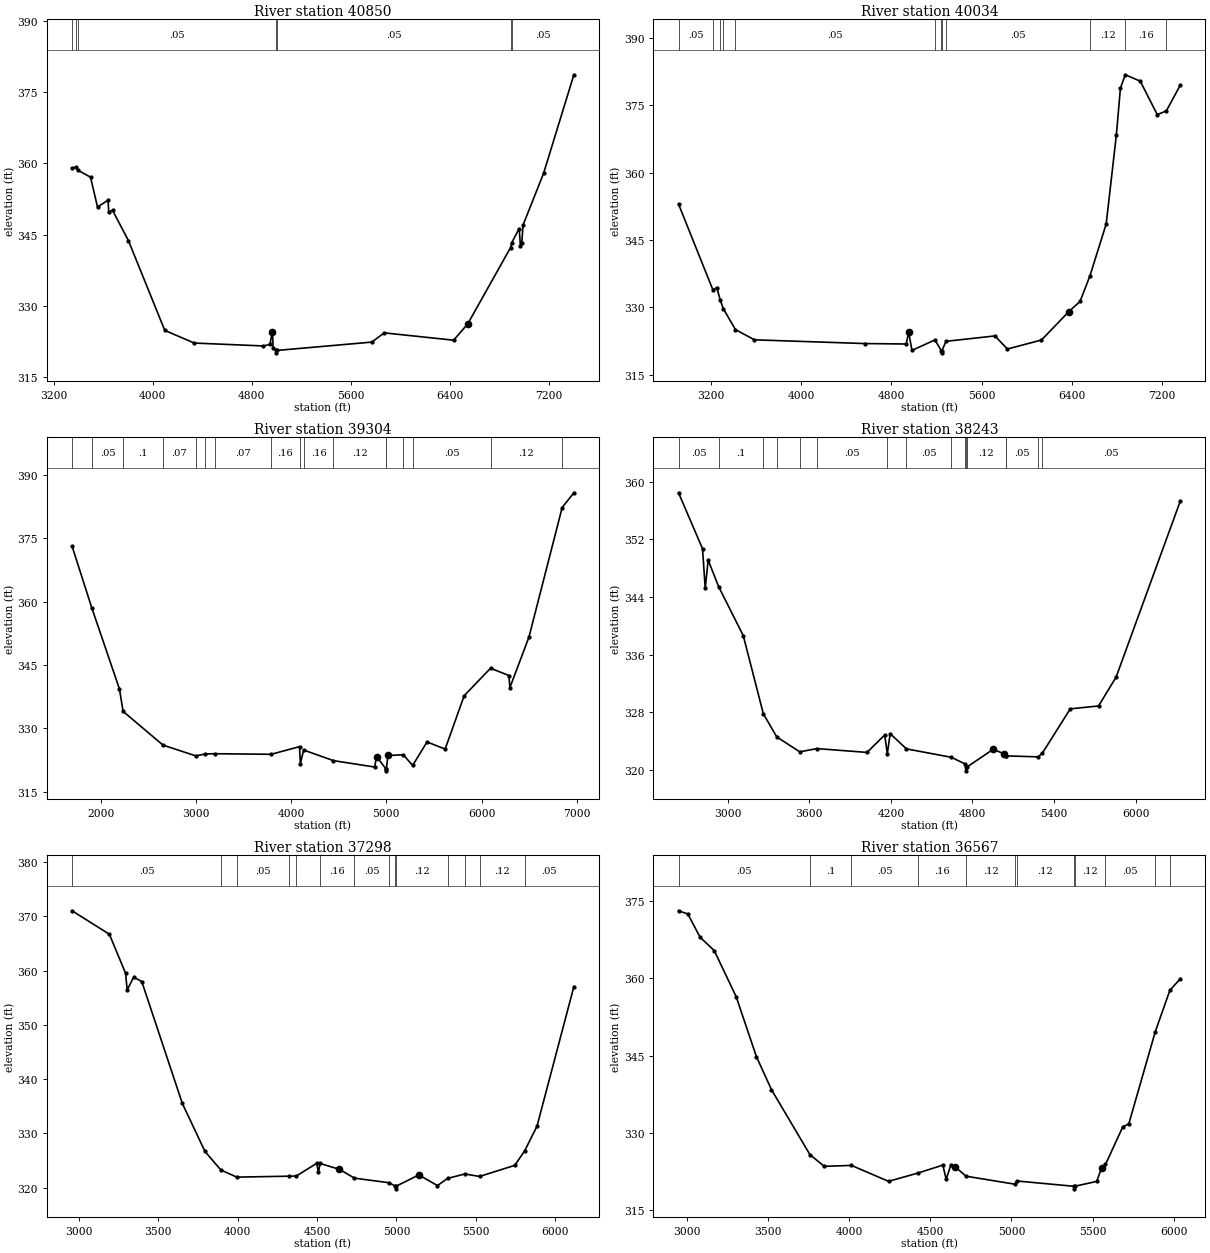
Type RM Length L Ch R = 1 ,40850   ,816,816,816
BEGIN DESCRIPTION:
CANEY CREEK 41.0
END DESCRIPTION:
XS GIS Cut Line= 3
      3564777.84     10632225.67      3565402.85     10633527.77
      3567915.21     10634217.69
#Sta/Elev= 30
    3349  359.01  3377.6  359.14  3395.3  358.57    3498  357.08  3554.4   350.8
  3639.4  352.25    3645  349.79  3675.7  350.11  3803.5  343.76  4097.2  324.85
  4335.5  322.19  4892.7  321.58  4945.5  321.89 4965.91  324.58  4971.9  321.22
  4994.4  320.63  4997.1  320.13  5000.4  320.63  5767.7  322.39  5868.5  324.33
  6428.5  322.79  6542.5  326.23  6888.1  342.29    6898  343.34  6957.3  346.28
  6967.7   342.6  6978.6  343.28  6988.5     347  7154.4   357.9  7398.7  378.63
#Mann= 7 ,-1 , 0
    3349     .05       0  3377.6     .08       0  3395.3     .05       0
  4994.4    .035       0  5000.4     .05       0  6888.1     .12       0
    6898     .05       0
Bank Sta=4965.91,6542.5
XS Rating Curve= 0 ,0
Exp/Cntr=0.3,0.1

Type RM Length L Ch R = 1 ,40034   ,730,730,730
BEGIN DESCRIPTION:
CANEY CREEK 40.0
END DESCRIPTION:
XS GIS Cut Line= 4
      3564543.47     10632564.23       3565246.6     10634335.06
      3565572.12     10634387.14      3567772.68     10634647.57
#Sta/Elev= 30
  2911.2  353.02    3216   333.9  3251.2  334.42    3281  331.63    3309  329.68
  3416.2  325.05  3584.7  322.77  4562.8  321.94    4931  321.84 4952.27  324.52
  4981.6  320.41  5185.2  322.75  5241.4  320.37  5244.1  319.87  5247.4  320.37
  5284.3  322.44  5717.6  323.64  5828.4  320.72  6130.5  322.73  6372.2  329.03
  6472.9  331.34  6559.5  336.96  6704.5  348.59  6795.1  368.51  6830.8  378.87
  6873.8  381.84  7006.6  380.42  7157.6  372.96  7238.1  373.79  7362.1  379.55
#Mann= 12 ,-1 , 0
  2911.2     .05       0    3216     .16       0    3281     .05       0
    3309     .16       0  3416.2     .05       0  5185.2      .1       0
  5241.4     .03       0  5247.4      .1       0  5284.3     .05       0
  6559.5     .12       0  6873.8     .16       0  7238.1     .05       0
Bank Sta=4952.27,6372.2
XS Rating Curve= 0 ,0
Exp/Cntr=0.3,0.1

Type RM Length L Ch R = 1 ,39304   ,1061,1061,1061
BEGIN DESCRIPTION:
CANEY CREEK 39.0
END DESCRIPTION:
XS GIS Cut Line= 2
      3562312.29     10634953.44      3567581.39     10634831.91
#Sta/Elev= 30
  1699.1   373.1  1906.3   358.5  2196.6  339.35    2235  334.04  2654.3  326.06
  2998.3  323.52  3097.4  323.96  3196.4  324.03  3790.8  323.89  4087.9   325.7
  4097.1   321.7  4131.2   324.9    4445  322.39  4877.3  320.88  4897.3  323.35
  4994.3  320.48    4997  319.98  5000.3  320.48  5017.3  323.61  5177.5  323.79
  5276.5  321.26  5427.4  326.81  5617.5  325.12  5817.5  337.74  6094.5  344.24
  6287.6  342.51  6297.6  339.65  6497.7  351.59  6846.8  382.23  6969.6  385.72
#Mann= 17 ,-1 , 0
  1699.1      .1       0  1906.3     .05       0    2235      .1       0
  2654.3     .07       0  2998.3      .1       0  3097.4     .05       0
  3196.4     .07       0  3790.8     .16       0  4087.9     .12       0
  4131.2     .16       0    4445     .12       0  4994.3     .07       0
  5000.3     .12       0  5177.5     .16       0  5276.5     .05       0
  6094.5     .12       0  6846.8     .16       0
Bank Sta=4897.3,5017.3
XS Rating Curve= 0 ,0
Exp/Cntr=0.3,0.1

Type RM Length L Ch R = 1 ,38243   ,945,945,945
BEGIN DESCRIPTION:
CANEY CREEK 38.0
END DESCRIPTION:
XS GIS Cut Line= 3
      3563063.22     10635498.94      3565298.41     10635564.05
      3566698.13     10635965.52
#Sta/Elev= 30
  2637.5  358.48    2814  350.71    2834   345.2  2855.5  349.13  2932.9  345.43
  3114.1  338.62  3261.3   327.8  3360.2  324.57  3529.4   322.5    3655  322.95
  4024.5  322.42  4154.5  324.84    4174  322.23  4194.6  325.03  4314.3  322.91
  4645.4  321.74  4744.3  320.83  4751.8  320.36  4754.5  319.86  4757.8  320.36
  4951.6  322.84  5030.9  322.25  5045.8  321.95  5048.4  321.94  5283.7   321.8
    5315  322.33  5519.9  328.47    5728  328.87  5857.5  332.89  6329.8  357.34
#Mann= 16 ,-1 , 0
  2637.5     .05       0  2932.9      .1       0  3261.3     .05       0
  3360.2     .12       0  3529.4     .16       0    3655     .05       0
    4174     .16       0  4314.3     .05       0  4645.4     .16       0
  4744.3     .12       0  4751.8     .07       0  4757.8     .12       0
  5045.8     .16       0  5048.4     .05       0  5283.7     .16       0
    5315     .05       0
Bank Sta=4951.6,5030.9
XS Rating Curve= 0 ,0
Exp/Cntr=0.3,0.1

Type RM Length L Ch R = 1 ,37298   ,731,731,731
BEGIN DESCRIPTION:
CANEY CREEK 36.0
END DESCRIPTION:
XS GIS Cut Line= 3
      3562949.56     10635760.18      3564949.61     10636160.19
      3565949.62     10636660.19
#Sta/Elev= 30
  2958.5  371.02  3193.1   366.7  3295.1  359.52  3305.3  356.44  3346.1  358.78
  3397.1  357.99    3652  335.55  3794.8  326.68  3894.9  323.26    3995  321.95
  4323.1  322.12  4369.3  322.15  4498.5   324.5  4508.6  322.83  4519.5  324.46
  4641.2  323.38  4735.6  321.76  4951.4  320.92  4992.6  320.29  4995.4  319.79
  4998.6  320.29  5140.7  322.35  5258.1  320.39  5321.4  321.71  5429.8  322.53
  5522.9  322.07  5744.4  324.12  5806.3  326.77  5884.2  331.33  6116.2  357.04
#Mann= 14 ,-1 , 0
  2958.5     .05       0  3894.9     .16       0    3995     .05       0
  4323.1     .16       0  4369.3     .05       0  4519.5     .16       0
  4735.6     .05       0  4951.4     .12       0  4992.6     .07       0
  4998.6     .12       0  5321.4     .05       0  5429.8     .07       0
  5522.9     .12       0  5806.3     .05       0
Bank Sta=4641.2,5140.7
XS Rating Curve= 0 ,0
Exp/Cntr=0.3,0.1

Type RM Length L Ch R = 1 ,36567   ,764,764,764
BEGIN DESCRIPTION:
CANEY CREEK 35.0
END DESCRIPTION:
XS GIS Cut Line= 3
      3563049.58     10635860.17      3564849.61     10636860.19
      3565749.59     10637360.18
#Sta/Elev= 30
  2950.5  373.14  3007.7  372.52  3083.2     368  3170.2  365.41  3305.2  356.46
  3429.9  344.82  3522.5   338.4  3759.4  325.78  3847.4  323.51  4014.5  323.69
  4243.2   320.6  4423.9   322.2 4577.27  323.75  4597.8  321.01  4627.6  323.83
    4655  323.35  4720.7  321.59  5023.2  320.03  5031.6  320.67    5383  319.64
  5385.8  319.14    5389  319.64  5524.4  320.58  5554.2  323.16  5578.5  323.87
  5684.6  331.15  5722.3  331.78  5884.7  349.63  5974.5  357.66  6039.2  359.96
#Mann= 12 ,-1 , 0
  2950.5     .05       0  3759.4      .1       0  4014.5     .05       0
  4423.9     .16       0  4720.7     .12       0  5023.2     .07       0
  5031.6     .12       0    5383     .07       0    5389     .12       0
  5578.5     .05       0  5884.7     .08       0  5974.5     .05       0
Bank Sta=4655,5554.2
XS Rating Curve= 0 ,0
Exp/Cntr=0.3,0.1