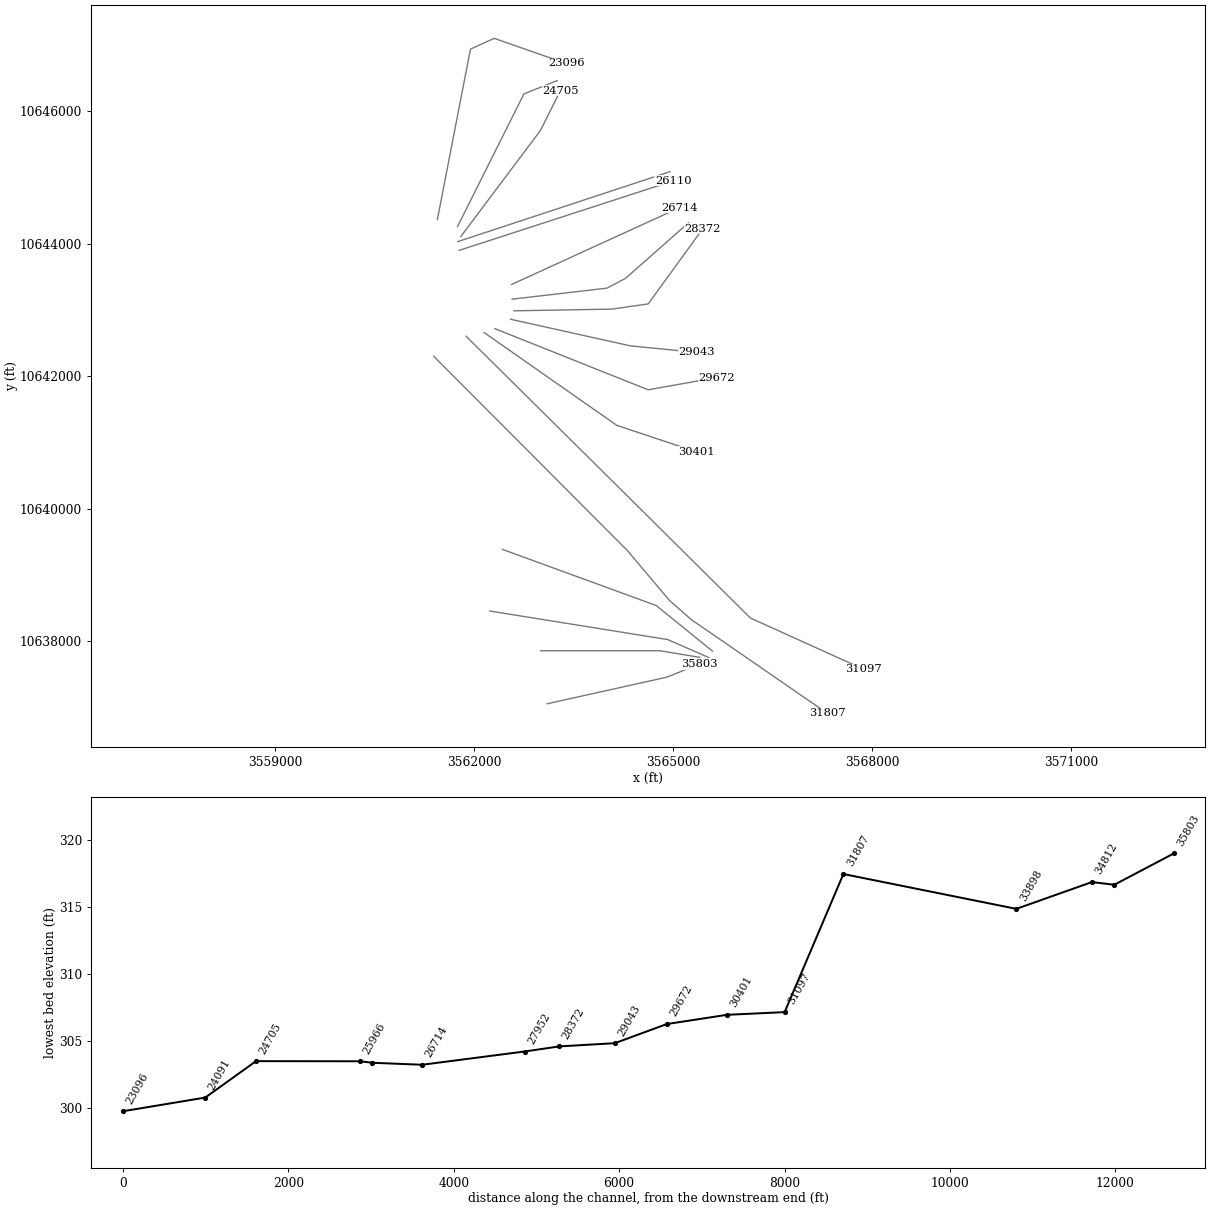
HEC-RAS study CANEY CREEK.prj: CANEY CREEK Base Level Engineering

--- CANEY CREEK.g01 (geometry) --- (continued)

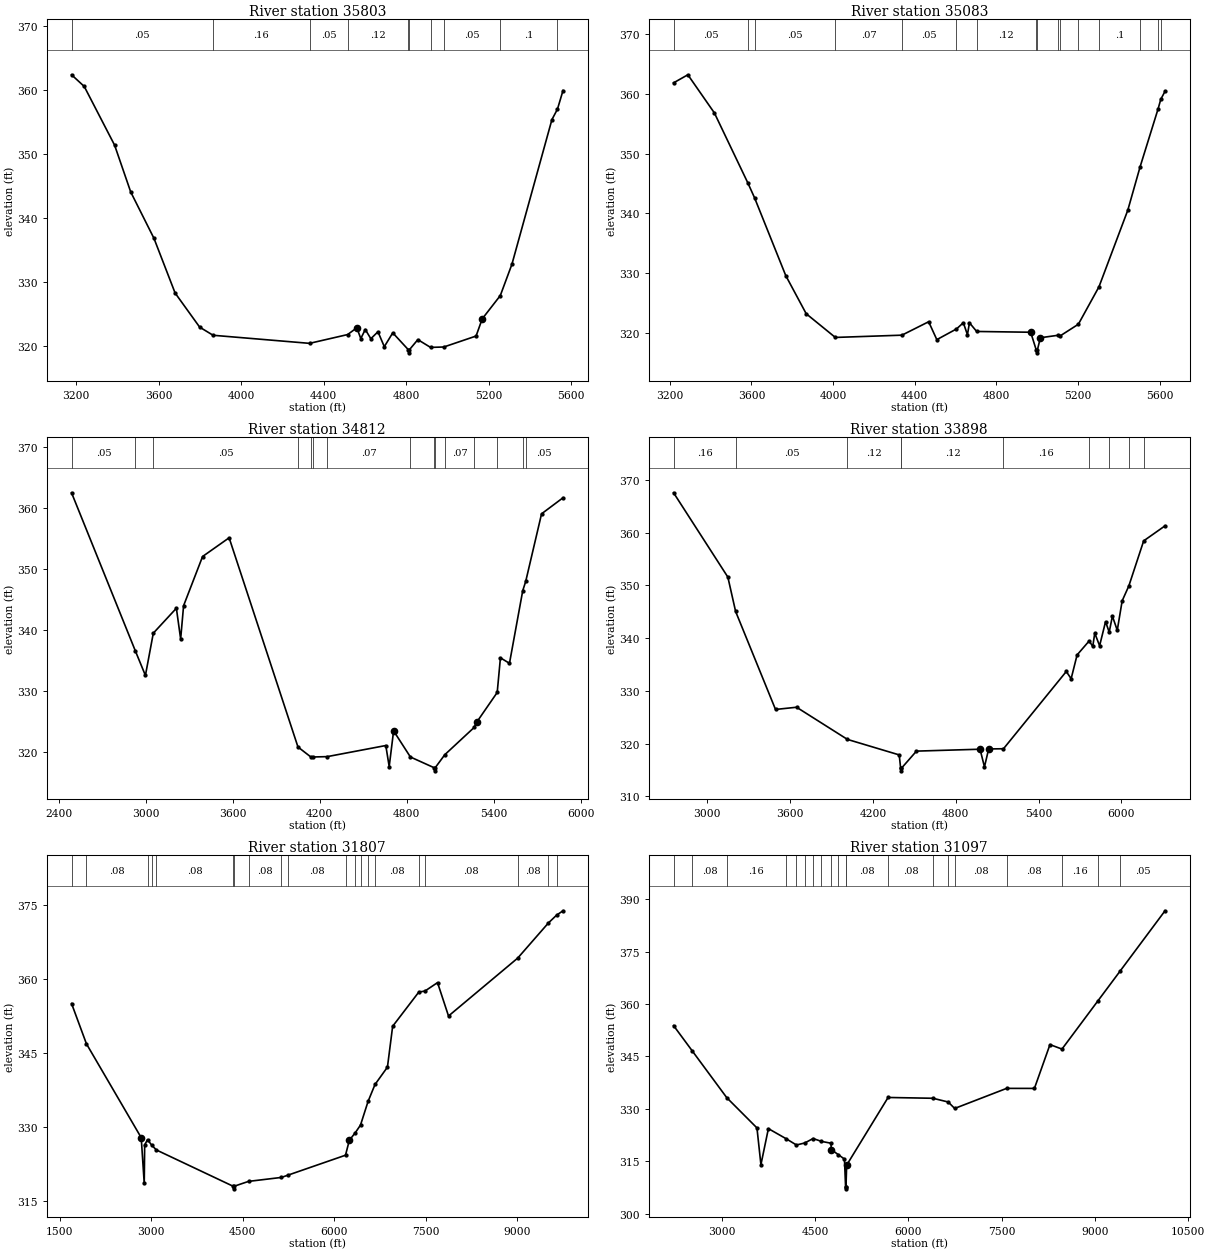
Type RM Length L Ch R = 1 ,35803   ,720,720,720
BEGIN DESCRIPTION:
CANEY CREEK 34.0
END DESCRIPTION:
XS GIS Cut Line= 3
       3563099.6     10637060.19      3564899.61     10637460.19
      3565399.58     10637660.18
#Sta/Elev= 30
  3178.2  362.36  3239.7  360.54  3386.9  351.38    3465  344.08  3577.7  336.85
  3680.2  328.32  3799.2     323  3864.3  321.73  4331.9  320.47  4516.5  321.84
  4561.1   322.9  4580.3  321.22  4602.1  322.63    4629  321.19  4663.6  322.28
  4694.3  319.95  4735.3  322.11  4810.4  319.49  4813.1  318.99  4816.4  319.49
  4856.9  321.05  4918.4  319.84  4982.6   319.9  5139.2  321.61  5168.9  324.29
  5256.6  327.92  5312.9   332.8  5506.8  355.36  5533.8  357.01  5560.6   359.9
#Mann= 10 ,-1 , 0
  3178.2     .05       0  3864.3     .16       0  4331.9     .05       0
  4516.5     .12       0  4810.4     .04       0  4816.4     .12       0
  4918.4     .08       0  4982.6     .05       0  5256.6      .1       0
  5533.8     .16       0
Bank Sta=4561.1,5168.9
XS Rating Curve= 0 ,0
Exp/Cntr=0.3,0.1

Type RM Length L Ch R = 1 ,35083   ,271,271,271
BEGIN DESCRIPTION:
CANEY CREEK 33.0
END DESCRIPTION:
XS GIS Cut Line= 3
      3562999.63     10637860.19      3564799.61     10637860.19
      3565399.65     10637760.18
#Sta/Elev= 30
  3218.5  361.88  3288.5  363.23  3418.5  356.84  3582.1  345.14  3615.4  342.62
  3768.5  329.57  3868.5   323.2  4011.2  319.23  4337.4  319.61  4468.5  321.86
  4508.5  318.86  4604.8  320.65  4638.5  321.69  4658.5  319.69  4668.5  321.68
  4703.8  320.23  4968.5   320.1  4995.5  317.15  4998.2  316.65  5001.5  317.15
    5016  319.18  5100.2  319.58  5110.7  319.44  5202.1  321.44  5303.1  327.71
  5444.3  340.54    5505  347.85  5593.3  357.57    5606  359.12  5626.8  360.46
#Mann= 16 ,-1 , 0
  3218.5     .05       0  3582.1     .16       0  3615.4     .05       0
  4011.2     .07       0  4337.4     .05       0  4604.8     .07       0
  4703.8     .12       0  4995.5     .07       0  5001.5     .12       0
  5100.2     .07       0  5110.7     .12       0  5202.1     .08       0
  5303.1      .1       0    5505     .05       0  5593.3     .16       0
    5606     .05       0
Bank Sta=4968.5,5016
XS Rating Curve= 0 ,0
Exp/Cntr=0.3,0.1

Type RM Length L Ch R = 1 ,34812   ,914,914,914
BEGIN DESCRIPTION:
CANEY CREEK 32.0
END DESCRIPTION:
XS GIS Cut Line= 3
       3562236.7     10638459.18      3564917.22     10638028.63
      3565534.94     10637757.94
#Sta/Elev= 30
  2488.4  362.44  2929.1  336.47  2997.8  332.49  3052.2  339.42  3211.3  343.51
  3240.8  338.47  3261.1  343.93    3392  351.99  3575.1  355.06  4049.9  320.76
  4141.1  319.08  4150.8  319.12  4251.6  319.18  4655.6     321    4679  317.55
  4709.4   323.4  4825.3  319.12    4990  317.35  4992.8  316.85    4996  317.35
  5062.3  319.49  5265.2  323.97  5281.7   324.8  5423.9   329.7  5446.1  335.38
  5508.5  334.48    5600  346.39  5620.6  347.92  5729.8  358.99  5877.7  361.62
#Mann= 15 ,-1 , 0
  2488.4     .05       0  2929.1     .16       0  3052.2     .05       0
  4049.9     .12       0  4141.1     .05       0  4150.8     .12       0
  4251.6     .07       0  4825.3     .12       0    4990     .07       0
    4996     .12       0  5062.3     .07       0  5265.2     .05       0
  5423.9      .1       0    5600     .16       0  5620.6     .05       0
Bank Sta=4709.4,5281.7
XS Rating Curve= 0 ,0
Exp/Cntr=0.3,0.1

Type RM Length L Ch R = 1 ,33898   ,2091,2091,2091
BEGIN DESCRIPTION:
CANEY CREEK 30.0
END DESCRIPTION:
XS GIS Cut Line= 3
      3562424.16     10639389.74      3564743.61     10638542.52
      3565590.75     10637855.09
#Sta/Elev= 30
  2755.2  367.58  3148.5  351.59  3204.6  345.08  3493.7  326.49  3646.4  326.91
  4014.8  320.81  4389.9  317.87  4400.2  315.35    4403  314.85  4406.2  315.35
  4514.8  318.59  4975.4  318.95  5007.4   315.6  5037.9     319  5145.3  319.04
  5600.2  333.69  5635.4  332.32  5678.5  336.83  5765.9  339.48    5792  338.44
  5806.4  340.96  5841.6  338.57  5884.7  343.14  5911.1  341.15  5934.3  344.19
  5969.5   341.5    6005  347.09  6053.4  349.92  6160.8  358.46  6315.5  361.31
#Mann= 10 ,-1 , 0
  2755.2     .16       0  3204.6     .05       0  4014.8     .12       0
  4400.2     .07       0  4406.2     .12       0  5145.3     .16       0
  5765.9     .05       0  5911.1      .1       0  6053.4     .16       0
  6160.8     .05       0
Bank Sta=4975.4,5037.9
XS Rating Curve= 0 ,0
Exp/Cntr=0.3,0.1

Type RM Length L Ch R = 1 ,31807   ,710,710,710
BEGIN DESCRIPTION:
CANEY CREEK 29.0
END DESCRIPTION:
XS GIS Cut Line= 6
      3561388.78      10642303.6      3564312.42     10639367.81
      3564944.36     10638617.81      3565276.31     10638326.66
      3565791.93      10637972.5       3567323.2     10636915.19
#Sta/Elev= 30
    1694  354.98  1937.8  346.82  2835.4  327.81  2884.9  318.54    2892  326.33
  2938.4  327.42  3008.7  326.27  3084.4  325.32  4345.7  317.95  4348.4  317.45
  4351.7  317.95    4594  318.96  5131.6  319.76  5234.6   320.2  6182.4  324.26
  6245.1  327.28  6343.5  328.83  6428.1  330.36  6552.2  335.16  6665.7  338.58
  6869.5   342.1  6954.9  350.37  7383.5   357.3  7483.4   357.5  7690.1  359.21
  7870.1  352.45  9003.9  364.18  9507.9  371.31  9641.4  372.88  9745.9  373.76
#Mann= 20 ,-1 , 0
    1694     .08       0  1937.8     .08       0  2938.4     .08       0
  3008.7     .05       0  3084.4     .08       0  4345.7     .07       0
  4351.7     .08       0    4594     .08       0  5131.6     .05       0
  5234.6     .08       0  6182.4     .08       0  6343.5     .05       0
  6428.1      .1       0  6552.2     .05       0  6665.7     .08       0
  7383.5     .05       0  7483.4     .08       0  9003.9     .08       0
  9507.9     .08       0  9641.4     .08       0
Bank Sta=2835.4,6245.1
XS Rating Curve= 0 ,0
Exp/Cntr=0.3,0.1

Type RM Length L Ch R = 1 ,31097   ,696,696,696
BEGIN DESCRIPTION:
CANEY CREEK 28.0
END DESCRIPTION:
XS GIS Cut Line= 4
       3561877.6     10642604.66      3564308.56     10640195.83
      3566162.38     10638354.16       3567863.8     10637583.31
#Sta/Elev= 30
  2223.6  353.82    2528  346.49  3079.6   333.2  3564.6  324.56  3628.3  314.06
  3748.4  324.36  4030.1  321.51  4199.5  319.68  4333.5  320.26  4467.5  321.53
  4601.5  320.71  4754.8  320.19  4759.7  318.36  4869.5  316.96  4971.8  315.65
    4990  307.64  4992.7  307.14    4996  307.64  5007.1  313.92  5673.4  333.27
    6395  333.04  6640.4  331.97  6744.2  330.13  7579.5  335.87  8026.5  335.86
  8276.6  348.39  8469.7  347.11  9051.5  360.99  9410.2  369.55 10126.9  386.66
#Mann= 20 ,-1 , 0
  2223.6     .08       0    2528     .08       0  3079.6     .16       0
  4030.1     .16       0  4199.5     .16       0  4333.5     .16       0
  4467.5     .05       0  4601.5     .08       0  4754.8     .16       0
  4869.5     .08       0    4990     .07       0    4996     .08       0
  5673.4     .08       0    6395     .16       0  6640.4     .16       0
  6744.2     .08       0  7579.5     .08       0  8469.7     .16       0
  9051.5     .05       0  9410.2     .05       0
Bank Sta=4759.7,5007.1
XS Rating Curve= 0 ,0
Exp/Cntr=0.3,0.1

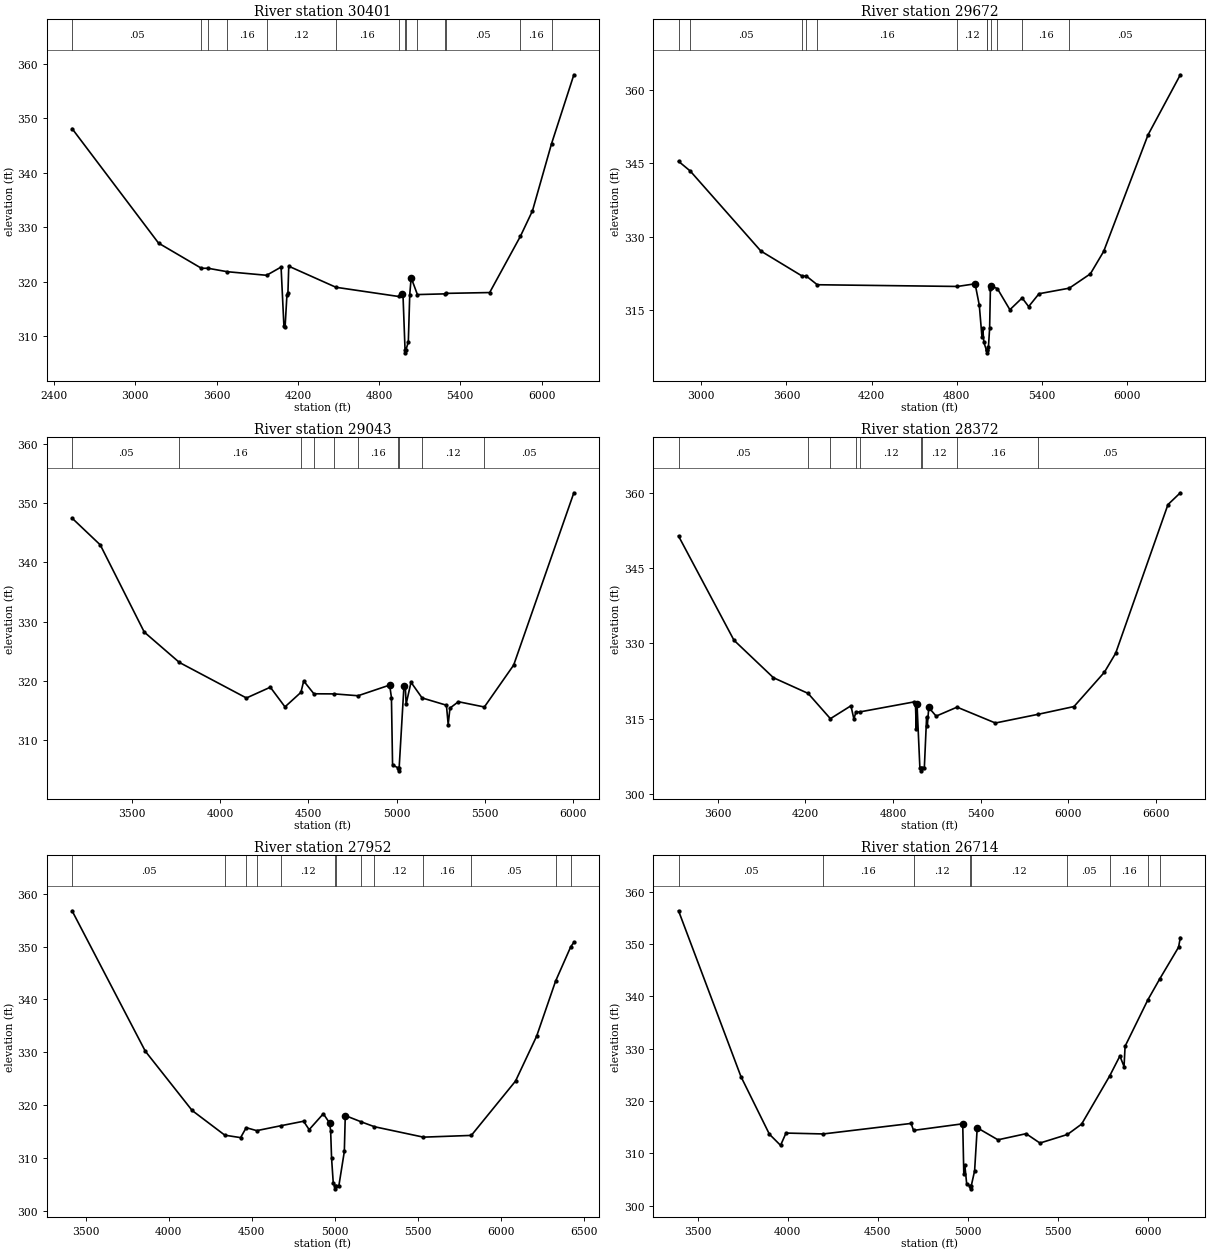
Type RM Length L Ch R = 1 ,30401   ,729,729,729
BEGIN DESCRIPTION:
CANEY CREEK 27.0
END DESCRIPTION:
XS GIS Cut Line= 3
      3562149.61     10642660.18      3564149.61     10641260.19
      3565349.59     10640860.19
#Sta/Elev= 30
  2532.6  348.12  3171.3  327.09  3487.9  322.47  3536.8  322.47  3678.2  321.84
  3969.5  321.18  4076.3  322.69  4097.2  311.91  4105.9  311.68  4119.4  317.48
  4126.9  317.88    4133  322.85  4481.5  318.98  4943.9  317.29  4970.9  317.76
  4976.5  317.76    4992  307.44  4994.7  306.94    4998  307.44  5016.1  308.93
  5026.6  317.61  5037.1  320.73  5083.3  317.64  5285.6  317.77  5294.7  317.86
  5616.9  318.01  5843.5  328.32  5933.1  333.02  6073.9  345.34  6238.8     358
#Mann= 14 ,-1 , 0
  2532.6     .05       0  3487.9     .16       0  3536.8     .12       0
  3678.2     .16       0  3969.5     .12       0  4481.5     .16       0
  4943.9     .12       0    4992     .07       0    4998     .12       0
  5083.3     .16       0  5285.6     .12       0  5294.7     .05       0
  5843.5     .16       0  6073.9     .05       0
Bank Sta=4970.9,5037.1
XS Rating Curve= 0 ,0
Exp/Cntr=0.3,0.1

Type RM Length L Ch R = 1 ,29672   ,629,629,629
BEGIN DESCRIPTION:
CANEY CREEK 26.0
END DESCRIPTION:
XS GIS Cut Line= 3
      3562311.56     10642718.67      3564622.76     10641796.36
      3565653.55     10641980.81
#Sta/Elev= 30
  2839.8  345.43    2922  343.45  3420.1  327.07  3712.1  321.93  3739.1  321.98
  3817.3  320.18  4804.8  319.83  4929.3  320.37  4958.9     316  4977.8  309.48
  4983.2  311.31  4991.1   308.4  5009.8  306.75  5012.6  306.25  5015.8  306.75
  5023.4  307.46  5031.7  311.24  5037.1  319.27  5039.4  319.46  5044.9  319.91
  5086.3  319.39  5174.5  315.07  5260.9  317.48  5306.6  315.71  5379.6  318.34
    5593  319.48  5741.6  322.41  5835.3     327  6147.9  350.84  6375.4  363.13
#Mann= 12 ,-1 , 0
  2839.8     .16       0    2922     .05       0  3712.1     .16       0
  3739.1     .12       0  3817.3     .16       0  4804.8     .12       0
  5009.8     .07       0  5015.8     .12       0  5039.4     .16       0
  5086.3     .12       0  5260.9     .16       0    5593     .05       0
Bank Sta=4929.3,5044.9
XS Rating Curve= 0 ,0
Exp/Cntr=0.3,0.1

Type RM Length L Ch R = 1 ,29043   ,671,671,671
BEGIN DESCRIPTION:
CANEY CREEK 25.0
END DESCRIPTION:
XS GIS Cut Line= 3
      3562549.56      10642860.2      3564349.61     10642460.19
      3565349.57     10642360.19
#Sta/Elev= 30
  3157.9  347.49    3318  342.97  3567.7  328.25  3767.2  323.12  4147.8  317.12
  4283.5  318.94  4366.7  315.62  4457.2  318.07    4473  319.99  4530.9  317.83
  4647.7  317.81  4781.5   317.5  4960.9   319.3  4971.1   317.2  4977.5  305.81
  5008.9  305.32  5011.7  304.82  5014.9  305.32  5042.1  319.11  5049.6  319.18
  5054.6  316.12  5082.3  319.77  5145.1  317.13  5283.3   315.9  5293.3  312.64
  5303.4  315.41  5351.1  316.49  5498.7   315.6  5665.1  322.68  6006.8  351.77
#Mann= 10 ,-1 , 0
  3157.9     .05       0  3767.2     .16       0  4457.2     .12       0
  4530.9     .16       0  4647.7     .12       0  4781.5     .16       0
  5008.9     .07       0  5014.9     .16       0  5145.1     .12       0
  5498.7     .05       0
Bank Sta=4960.9,5042.1
XS Rating Curve= 0 ,0
Exp/Cntr=0.3,0.1

Type RM Length L Ch R = 1 ,28372   ,420,420,420
BEGIN DESCRIPTION:
CANEY CREEK 24.0
END DESCRIPTION:
XS GIS Cut Line= 4
      3562600.34     10642987.78      3564076.07     10643013.83
      3564622.94     10643091.95      3565447.61     10644229.12
#Sta/Elev= 30
  3332.9  351.36  3712.2   330.6  3982.3  323.13  4219.3  320.01  4371.8  314.97
  4512.4  317.54  4532.4  314.94  4546.9  316.27  4577.1  316.34  4943.8  318.31
  4953.9  317.87  4959.4  312.97  4964.5  317.89  4984.2  305.11  4991.3  305.08
    4994  304.58  4997.3  305.08  5014.5  305.12  5030.1  315.29  5035.2   313.6
  5044.8   317.2  5095.3  315.48  5238.5  317.27  5500.8  314.11  5795.6  315.86
  6038.5  317.39  6246.1  324.21  6323.4     328  6681.4  357.63    6766  359.98
#Mann= 9 ,-1 , 0
  3332.9     .05       0  4219.3     .16       0  4371.8     .12       0
  4546.9     .16       0  4577.1     .12       0  4991.3     .07       0
  4997.3     .12       0  5238.5     .16       0  5795.6     .05       0
Bank Sta=4964.5,5044.8
XS Rating Curve= 0 ,0
Exp/Cntr=0.3,0.1

Type RM Length L Ch R = 1 ,27952   ,1238,1238,1238
BEGIN DESCRIPTION:
CANEY CREEK 23.0
END DESCRIPTION:
XS GIS Cut Line= 4
      3562571.24      10643163.6      3564001.76     10643330.26
      3564279.54     10643476.09      3565230.28      10644315.8
#Sta/Elev= 30
  3417.6  356.76  3858.7  330.22  4140.8  319.01  4337.8  314.34  4432.8  313.88
  4466.4  315.76    4530   315.2  4675.3  316.13  4812.1  316.98  4845.6  315.39
  4930.9  318.39  4968.3  316.67    4975  315.22  4980.6  310.03  4990.9  305.24
  4999.7   304.7  5002.4   304.2  5005.7   304.7  5024.8  304.82  5057.5  311.26
  5063.2  318.05  5160.4  316.85  5239.1  315.94  5533.8  313.97  5822.4   314.3
  6088.6  324.57  6215.7  333.05    6330  343.47  6421.5  349.98    6440  350.78
#Mann= 13 ,-1 , 0
  3417.6     .05       0  4337.8     .16       0  4466.4     .12       0
    4530     .16       0  4675.3     .12       0  4999.7     .07       0
  5005.7     .12       0  5160.4     .16       0  5239.1     .12       0
  5533.8     .16       0  5822.4     .05       0    6330     .08       0
  6421.5     .05       0
Bank Sta=4968.3,5063.2
XS Rating Curve= 0 ,0
Exp/Cntr=0.3,0.1

Type RM Length L Ch R = 1 ,26714   ,604,604,604
BEGIN DESCRIPTION:
CANEY CREEK 22.0
END DESCRIPTION:
XS GIS Cut Line= 2
      3562564.29     10643385.83      3565098.62     10644545.37
#Sta/Elev= 30
  3393.8  356.35  3740.6  324.65  3898.5  313.65  3960.5  311.52  3990.6  313.87
  4197.4   313.7  4685.5  315.71  4699.1  314.38  4972.2  315.64  4978.2  306.07
  4983.7  307.82  4994.2  304.16  5013.2  303.71    5016  303.21  5019.2  303.71
  5038.2  306.65  5052.7  314.88  5167.8  312.58  5324.1  313.75  5401.1  311.96
    5554   313.6  5632.5  315.58  5788.3  324.78  5845.2   328.6  5868.2  326.57
    5874  330.46  6000.6  339.34  6065.8  343.29  6170.9  349.38  6180.8  351.24
#Mann= 9 ,-1 , 0
  3393.8     .05       0  4197.4     .16       0  4699.1     .12       0
  5013.2     .07       0  5019.2     .12       0    5554     .05       0
  5788.3     .16       0  6000.6     .05       0  6065.8     .16       0
Bank Sta=4972.2,5052.7
XS Rating Curve= 0 ,0
Exp/Cntr=0.3,0.1

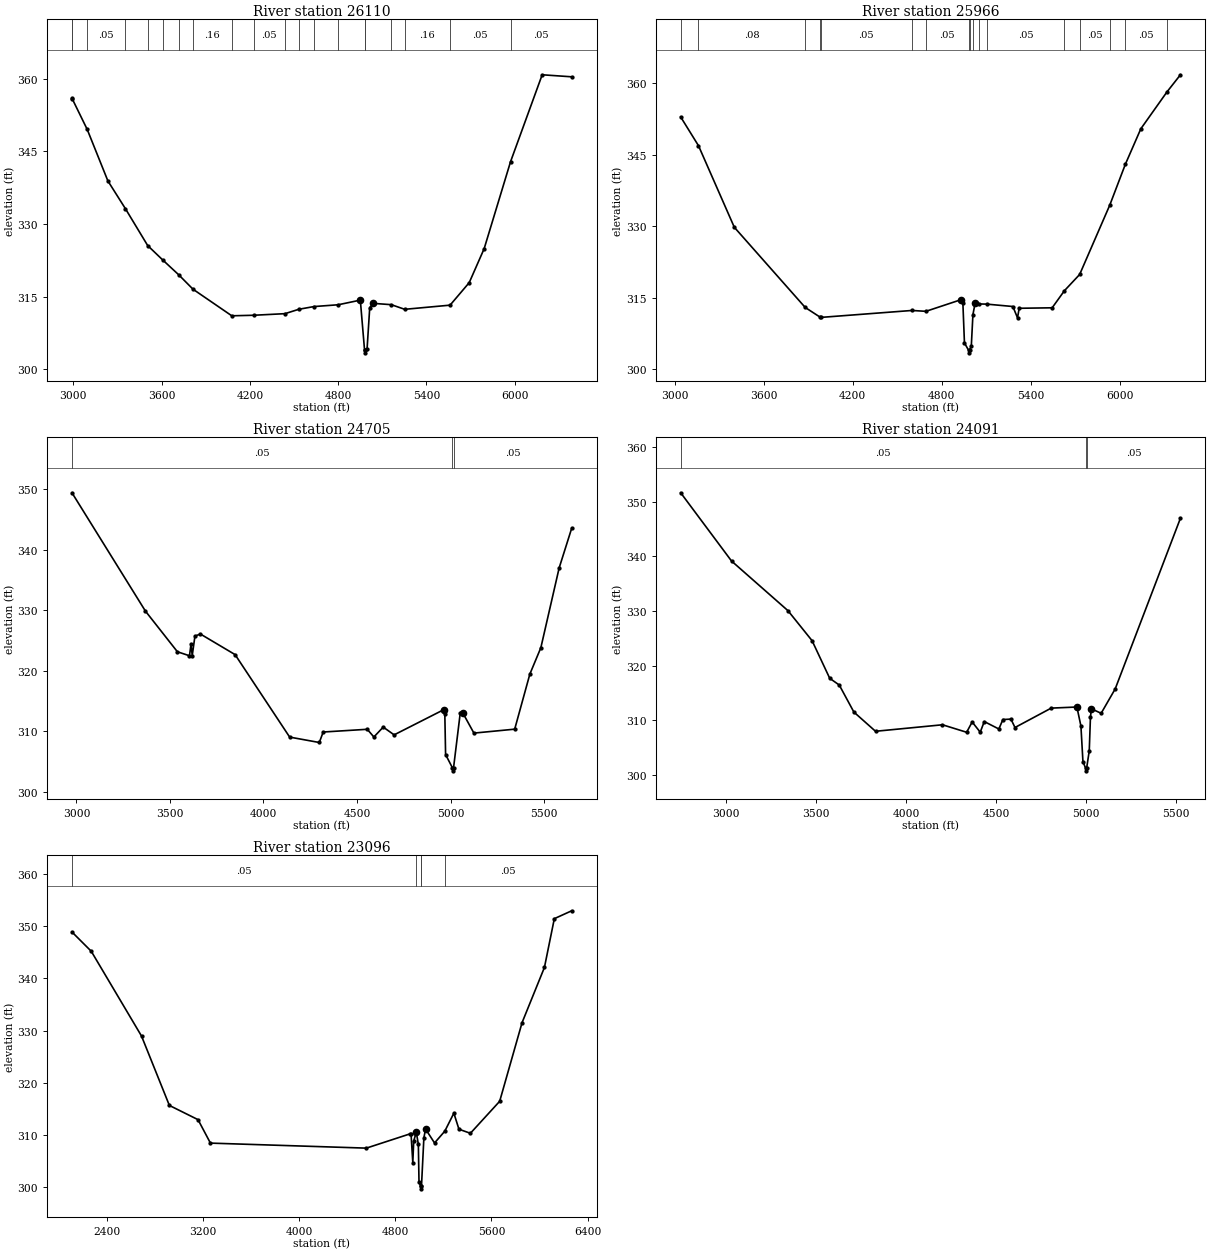
Type RM Length L Ch R = 1 ,26110   ,144,144,144
BEGIN DESCRIPTION:
CANEY CREEK 21.0
END DESCRIPTION:
XS GIS Cut Line= 2
       3561772.6     10643899.71      3565001.81     10644948.33
#Sta/Elev= 30
  2991.6  356.06  2993.6  355.88  3095.3  349.55  3235.8   338.9  3354.9  333.16
  3506.1  325.54  3608.8  322.55  3716.1  319.52  3814.2  316.51  4077.4  311.02
  4225.1  311.13  4438.7  311.46  4533.2  312.37  4635.9  312.93  4799.9   313.3
  4950.7  314.26  4979.6  303.86  4982.4  303.36  4985.6  303.86  4996.6  304.19
  5014.6  312.71  5038.7  313.59  5161.2  313.32  5252.2  312.36  5560.4  313.22
  5690.6  317.88  5792.1  324.91  5971.2  342.88  6186.2  360.86  6386.8  360.44
#Mann= 20 ,-1 , 0
  2991.6     .05       0  2993.6     .08       0  3095.3     .05       0
  3354.9     .08       0  3506.1     .05       0  3608.8     .16       0
  3716.1     .08       0  3814.2     .16       0  4077.4     .08       0
  4225.1     .05       0  4438.7     .08       0  4533.2     .05       0
  4635.9     .16       0  4799.9     .08       0  4979.6     .07       0
  4985.6     .16       0  5161.2     .05       0  5252.2     .16       0
  5560.4     .05       0  5971.2     .05       0
Bank Sta=4950.7,5038.7
XS Rating Curve= 0 ,0
Exp/Cntr=0.3,0.1

Type RM Length L Ch R = 1 ,25966   ,1261,1261,1261
BEGIN DESCRIPTION:
CANEY CREEK 20.0
END DESCRIPTION:
XS GIS Cut Line= 2
      3561751.73     10644031.64       3564953.2     10645087.22
#Sta/Elev= 30
  3039.8  352.96  3159.9  346.93  3401.6  329.81  3879.8  312.99  3982.6  310.91
  3983.2   310.9  4599.7  312.36  4693.9  312.18  4931.5  314.63  4943.4  313.86
  4953.9  305.55  4982.5  303.97  4985.3  303.47  4988.5  303.97  5000.2  304.92
  5011.1   311.5  5026.7  314.02  5049.5  313.73  5104.8  313.69  5280.4  313.19
  5311.9  310.82  5323.1  312.82  5545.5  312.92  5628.1   316.5    5731  319.91
  5934.3  334.47  6039.5  343.05  6143.7  350.48  6319.9  358.21  6410.8  361.81
#Mann= 17 ,-1 , 0
  3039.8     .05       0  3159.9     .08       0  3879.8     .05       0
  3982.6     .08       0  3983.2     .05       0  4599.7     .08       0
  4693.9     .05       0  4982.5     .04       0  4988.5     .05       0
  5011.1     .08       0  5049.5     .16       0  5104.8     .05       0
  5628.1     .08       0    5731     .05       0  5934.3     .08       0
  6039.5     .05       0  6319.9     .08       0
Bank Sta=4931.5,5026.7
XS Rating Curve= 0 ,0
Exp/Cntr=0.3,0.1

Type RM Length L Ch R = 1 ,24705   ,614,614,614
BEGIN DESCRIPTION:
CANEY CREEK 19.0
END DESCRIPTION:
XS GIS Cut Line= 3
      3561799.62     10644110.21      3562999.61     10645710.19
      3563299.61     10646310.19
#Sta/Elev= 30
  2976.4  349.39  3369.1  329.85  3539.9  323.14  3604.5  322.48  3612.8  324.44
  3619.1   322.5  3633.7  325.73  3662.8  326.07  3848.2  322.67  4139.9  309.05
  4298.2  308.16  4319.1  309.89  4554.5  310.34  4589.9  309.07  4639.9   310.7
  4698.2  309.42  4962.8  313.57  4969.1  312.85  4973.2  306.17  5009.7  303.98
  5012.5  303.48  5015.7  303.98  5051.8   313.1  5065.8  313.01  5124.5  309.71
  5342.5  310.36  5423.6  319.46  5482.3  323.81  5580.1  336.98  5647.2  343.54
#Mann= 3 ,-1 , 0
  2976.4     .05       0  5009.7     .03       0  5015.7     .05       0
Bank Sta=4962.8,5065.8
XS Rating Curve= 0 ,0
Exp/Cntr=0.3,0.1

Type RM Length L Ch R = 1 ,24091   ,995,995,995
BEGIN DESCRIPTION:
CANEY CREEK 18.0
END DESCRIPTION:
XS GIS Cut Line= 3
       3561749.6     10644260.17      3562749.61     10646260.19
      3563249.61     10646460.19
#Sta/Elev= 30
  2748.5  351.65  3030.8  339.16  3343.9  330.08    3478  324.58  3575.9   317.7
    3629  316.46    3710  311.52  3830.2     308    4202  309.19  4336.1  307.82
  4366.9   309.7  4411.6  307.83    4434  309.78    4515  308.42  4537.4  310.15
  4582.1  310.23  4604.5  308.69  4805.7  312.24  4948.3  312.44  4970.6  308.97
  4981.8  302.46  4996.4  301.26  4999.1  300.76  5002.4  301.26  5016.9  304.42
  5023.6  310.66    5029  312.11  5082.9  311.29    5161  315.76  5523.1  346.99
#Mann= 3 ,-1 , 0
  2748.5     .05       0  4996.4     .03       0  5002.4     .05       0
Bank Sta=4948.3,5029
XS Rating Curve= 0 ,0
Exp/Cntr=0.3,0.1

Type RM Length L Ch R = 1 ,23096   ,450,450,450
BEGIN DESCRIPTION:
CANEY CREEK 17.0
END DESCRIPTION:
XS GIS Cut Line= 4
       3561444.8       10644364.      3561943.92     10646935.57
      3562301.99     10647098.33      3563385.83     10646718.99
#Sta/Elev= 30
  2107.3  348.89  2267.6  345.21  2686.4  328.98  2918.4   315.7  3156.9  312.98
  3260.3  308.49  4558.4  307.53  4922.3  310.26  4930.8  310.22  4945.4  304.76
  4952.8  308.86    4971  310.33  4974.8  310.53  4991.5  308.28    4997     301
  5011.6  300.24  5014.3  299.74  5017.6  300.24  5037.6  309.51  5051.7  311.18
  5126.3  308.52  5211.7  310.77  5287.2  314.22  5329.6  311.15  5424.9  310.37
  5668.6  316.49  5855.1  331.54  6041.3   342.1  6123.8  351.44  6268.5  352.95
#Mann= 5 ,-1 , 0
  2107.3     .05       0    4971     .16       0  5011.6     .07       0
  5017.6     .16       0  5211.7     .05       0
Bank Sta=4974.8,5051.7
XS Rating Curve= 0 ,0
Exp/Cntr=0.3,0.1