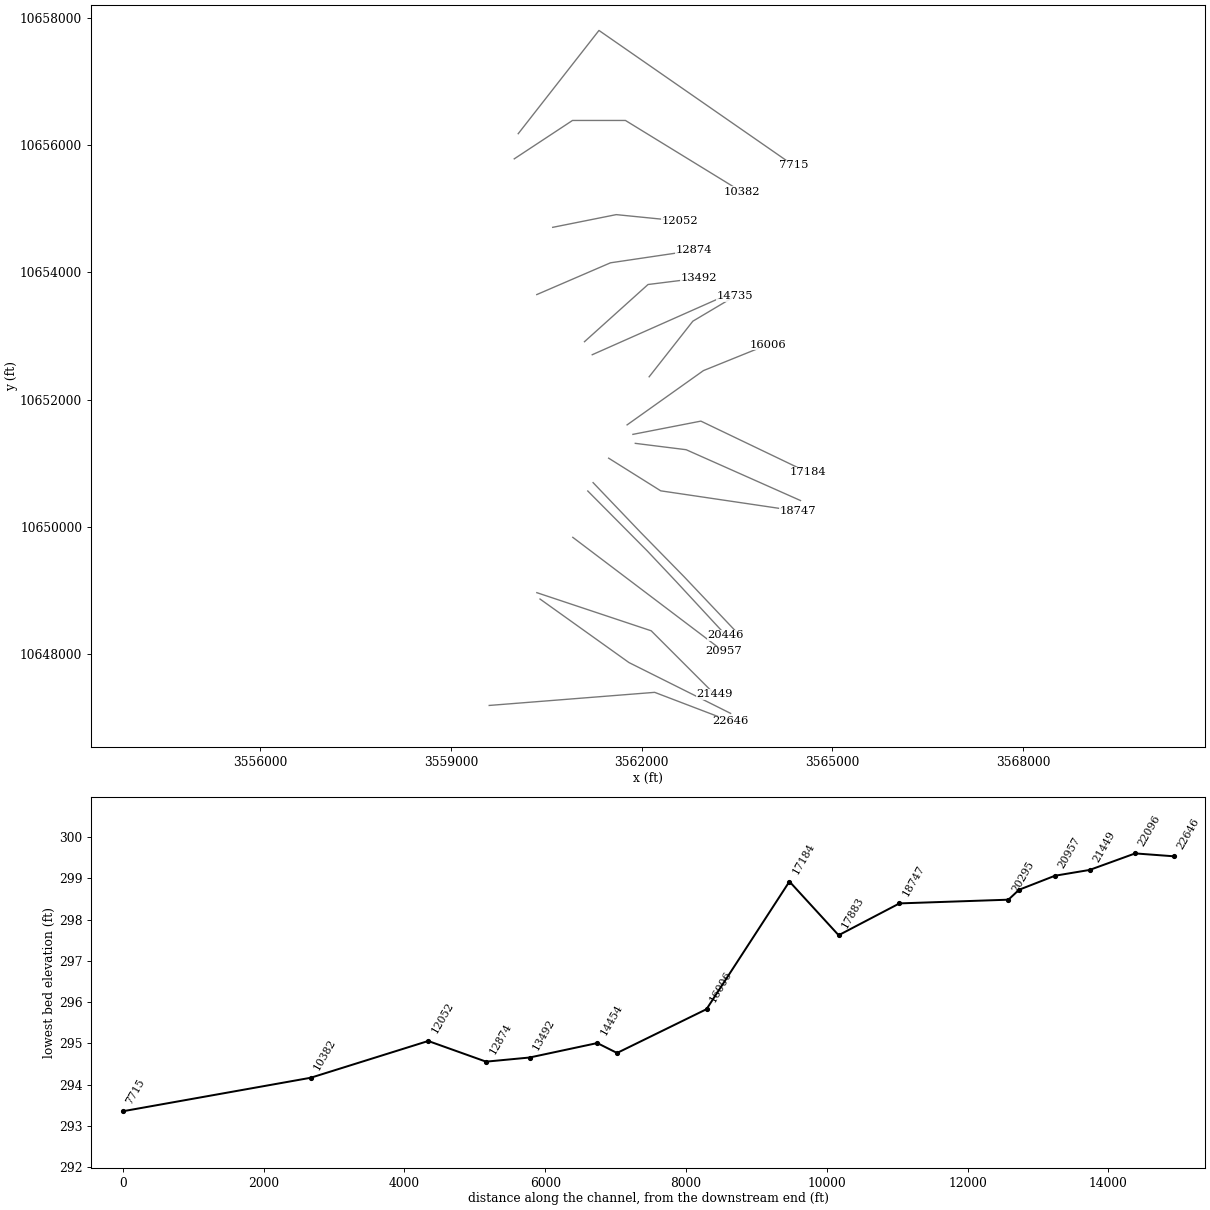
HEC-RAS study CANEY CREEK.prj: CANEY CREEK Base Level Engineering

--- CANEY CREEK.g01 (geometry) --- (continued)

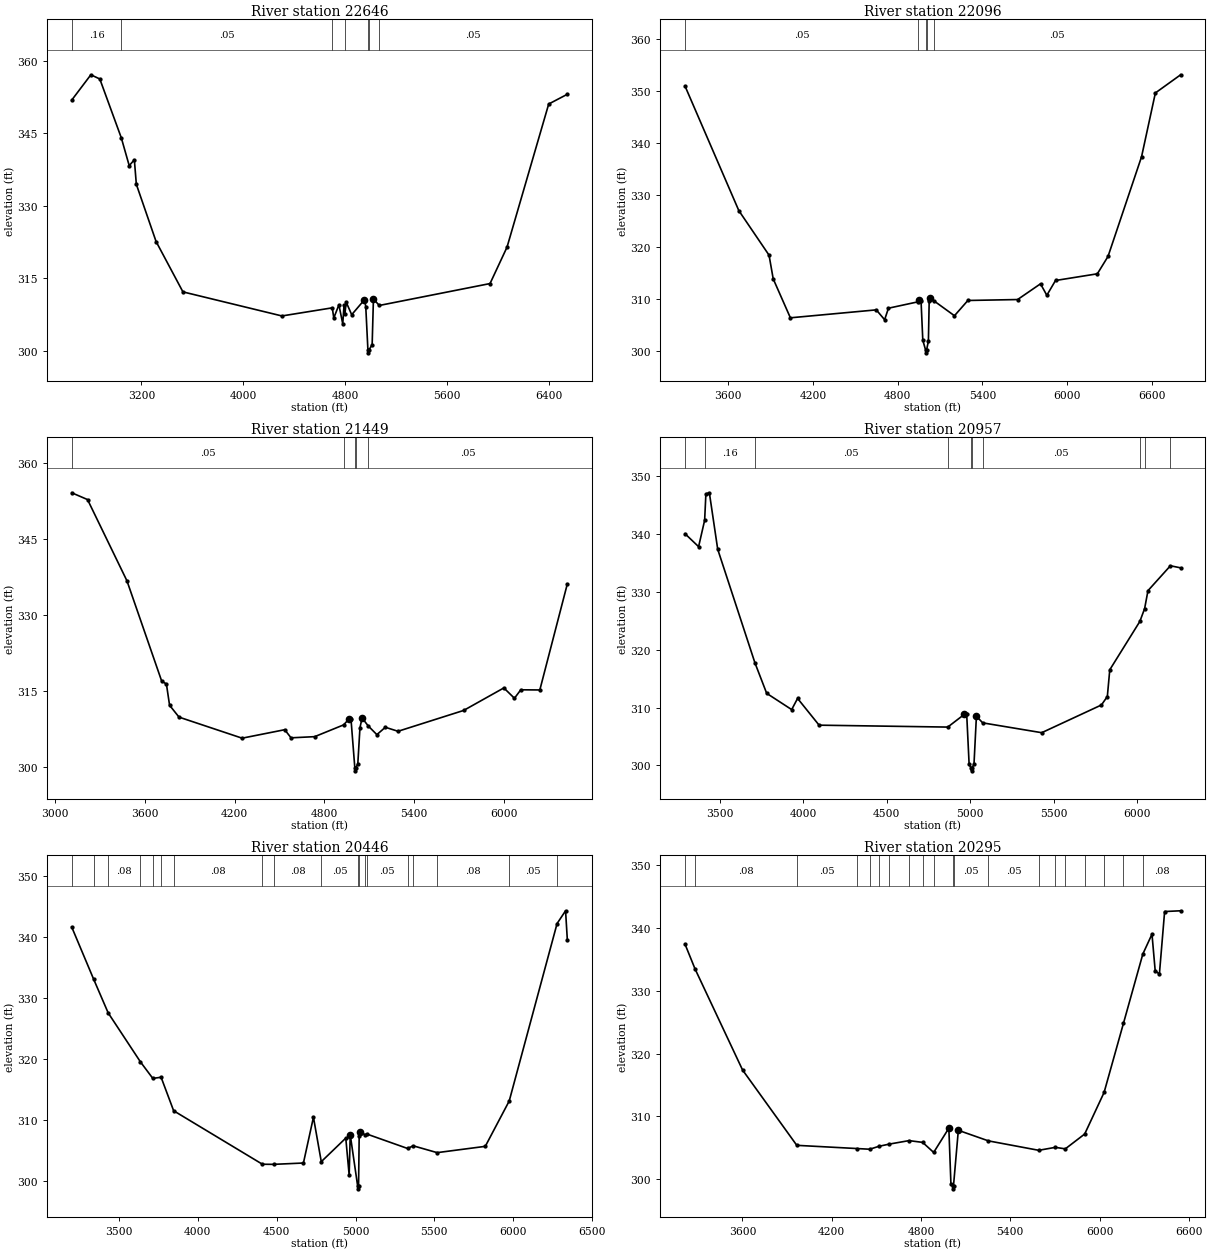
Type RM Length L Ch R = 1 ,22646   ,550,550,550
BEGIN DESCRIPTION:
Mapping XS a1266f67
END DESCRIPTION:
XS GIS Cut Line= 3
      3559600.18     10647185.14      3562204.34      10647391.3
       3563396.3     10646936.19
#Sta/Elev= 30
  2654.1  351.82    2804  357.05  2874.2  356.18  3042.8  344.01  3104.9  338.25
  3145.1  339.47  3160.8  334.39  3315.6  322.56  3526.3  312.14  4302.8  307.16
    4698  308.84  4709.9  306.74  4750.1  309.46  4780.2  305.52  4790.2  309.35
    4797  307.53    4807  310.02  4850.4  307.42  4950.7  310.52  4960.7  309.11
  4977.8  300.03  4980.5  299.53  4983.8  300.03  5010.9  301.23  5020.9  310.67
  5066.9  309.33  5935.7  313.86    6069  321.39    6396     351  6542.3  353.02
#Mann= 7 ,-1 , 0
  2654.1     .16       0  3042.8     .05       0    4698     .16       0
    4797     .12       0  4977.8     .07       0  4983.8     .12       0
  5066.9     .05       0
Bank Sta=4950.7,5020.9
XS Rating Curve= 0 ,0
Exp/Cntr=0.3,0.1

Type RM Length L Ch R = 1 ,22096   ,647,647,647
BEGIN DESCRIPTION:
CANEY CREEK 16.0
END DESCRIPTION:
XS GIS Cut Line= 3
      3560399.63     10648860.18      3561799.61     10647860.19
      3563399.61     10647060.19
#Sta/Elev= 30
  3294.7  350.99  3675.6     327  3889.5  318.42    3919  313.85  4040.6  306.35
  4648.9  307.88  4707.9  305.98    4735   308.2  4942.4  309.42  4951.2  309.77
    4966   309.5  4978.3  302.02  4998.6   300.1  5001.4   299.6  5004.6   300.1
  5017.9  301.85  5023.5  309.63  5029.1  310.22    5055  309.66  5202.4  306.75
  5297.4  309.69  5649.6  309.87  5811.7   312.9  5856.5  310.69    5918  313.54
  6214.2  314.83  6289.7  318.17  6527.3  337.39  6625.1  349.68    6804  353.18
#Mann= 5 ,-1 , 0
  3294.7     .05       0  4942.4     .16       0  4998.6     .07       0
  5004.6     .16       0    5055     .05       0
Bank Sta=4951.2,5029.1
XS Rating Curve= 0 ,0
Exp/Cntr=0.3,0.1

Type RM Length L Ch R = 1 ,21449   ,492,492,492
BEGIN DESCRIPTION:
CANEY CREEK 15.0
END DESCRIPTION:
XS GIS Cut Line= 3
       3560349.6     10648960.19      3562149.61     10648360.19
      3563149.61     10647360.18
#Sta/Elev= 30
  3111.2  354.03  3216.6  352.69  3480.1  336.66    3712   316.9  3743.7  316.32
  3764.8  312.13    3828  309.79  4249.6  305.64  4534.2  307.31  4576.4  305.71
  4734.5  305.94  4927.6  308.26  4966.4  309.51    4977  309.43  5002.9   299.7
  5005.7   299.2  5008.9   299.7  5022.7  300.62  5036.9  307.67    5051  309.63
  5092.9  308.03    5150  306.34  5206.6  307.79  5291.4     307  5729.8  311.11
  5998.5  315.55  6069.2  313.51  6111.7  315.18  6238.9  315.15  6422.8  336.07
#Mann= 5 ,-1 , 0
  3111.2     .05       0  4927.6     .16       0  5002.9     .07       0
  5008.9     .16       0  5092.9     .05       0
Bank Sta=4966.4,5051
XS Rating Curve= 0 ,0
Exp/Cntr=0.3,0.1

Type RM Length L Ch R = 1 ,20957   ,511,511,511
BEGIN DESCRIPTION:
CANEY CREEK 14.0
END DESCRIPTION:
XS GIS Cut Line= 2
      3560915.58       10649831.      3563283.66     10648039.32
#Sta/Elev= 30
    3291  340.02  3372.2  337.79  3408.4  342.35  3415.9  346.91  3436.7   347.1
  3486.7  337.34  3709.7  317.72  3780.1  312.45  3929.9  309.64  3965.3  311.57
  4094.2  306.95  4865.1  306.62  4964.1  308.81  4978.6  308.85  4993.2  300.16
  5004.7  299.56  5007.5  299.06  5010.7  299.56  5022.3   300.2  5036.8   308.5
  5074.4  307.35  5428.1  305.65  5785.9  310.44  5821.3   311.9  5835.9  316.52
  6016.1  324.87  6044.7  327.09  6064.8  330.19  6199.2  334.49  6260.5  334.13
#Mann= 10 ,-1 , 0
    3291     .05       0  3408.4     .16       0  3709.7     .05       0
  4865.1     .16       0  5004.7     .07       0  5010.7     .16       0
  5074.4     .05       0  6016.1     .08       0  6044.7     .05       0
  6199.2     .16       0
Bank Sta=4964.1,5036.8
XS Rating Curve= 0 ,0
Exp/Cntr=0.3,0.1

Type RM Length L Ch R = 1 ,20446   ,151,151,151
BEGIN DESCRIPTION:
CANEY CREEK 13.0
END DESCRIPTION:
XS GIS Cut Line= 4
       3561151.7     10650560.17      3562089.22     10649615.71
      3562547.55      10649129.6      3563324.94     10648289.74
#Sta/Elev= 30
  3200.2  341.59  3338.4   333.1  3431.2  327.54    3636  319.51  3714.3  316.81
  3766.8     317  3846.4  311.51  4409.3  302.75  4479.9  302.73  4669.6  302.95
  4733.1  310.45  4782.8  303.17  4938.2  307.03  4959.7  300.96  4966.5  307.58
  5013.3  299.22  5016.1  298.72  5019.3  299.22  5023.2  307.38  5030.5  308.11
  5062.8  307.52  5071.4   307.7  5330.3  305.33  5365.6  305.77  5517.7  304.65
    5823  305.68  5974.8  313.11  6278.4  342.18  6332.2  344.27  6343.5  339.47
#Mann= 19 ,-1 , 0
  3200.2     .08       0  3338.4     .05       0  3431.2     .08       0
    3636     .05       0  3714.3     .08       0  3766.8     .05       0
  3846.4     .08       0  4409.3     .05       0  4479.9     .08       0
  4782.8     .05       0  5013.3     .03       0  5019.3     .05       0
  5062.8     .08       0  5071.4     .05       0  5330.3     .08       0
  5365.6     .05       0  5517.7     .08       0  5974.8     .05       0
  6278.4     .08       0
Bank Sta=4966.5,5030.5
XS Rating Curve= 0 ,0
Exp/Cntr=0.3,0.1

Type RM Length L Ch R = 1 ,20295   ,1548,1548,1548
BEGIN DESCRIPTION:
CANEY CREEK 12.0
END DESCRIPTION:
XS GIS Cut Line= 4
      3561235.07     10650692.07      3561985.05     10649907.38
      3562665.61     10649212.93      3563540.64     10648289.29
#Sta/Elev= 30
  3214.5  337.39  3281.3  333.48  3601.1  317.38  3965.4   305.4  4369.2  304.89
  4455.3  304.78  4516.4  305.24  4587.5   305.6  4719.7  306.15    4811  305.87
  4885.1  304.27  4987.1  308.13  5001.2  299.18  5012.4  298.98  5015.1  298.48
  5018.4  298.98  5050.8  307.79  5252.9  306.11    5591  304.61  5702.8  305.08
  5769.7  304.84  5899.9   307.2  6030.2  313.81  6160.4  324.81  6290.6  335.83
  6352.1  338.99  6373.5   333.2  6401.8  332.62    6437  342.59  6544.6  342.71
#Mann= 20 ,-1 , 0
  3214.5     .05       0  3281.3     .08       0  3965.4     .05       0
  4369.2     .16       0  4455.3     .05       0  4516.4     .16       0
  4587.5     .08       0  4719.7     .08       0    4811     .16       0
  4885.1     .05       0  5012.4     .04       0  5018.4     .05       0
  5252.9     .05       0    5591     .08       0  5702.8     .12       0
  5769.7     .05       0  5899.9     .05       0  6030.2     .08       0
  6160.4     .05       0  6290.6     .08       0
Bank Sta=4987.1,5050.8
XS Rating Curve= 0 ,0
Exp/Cntr=0.3,0.1

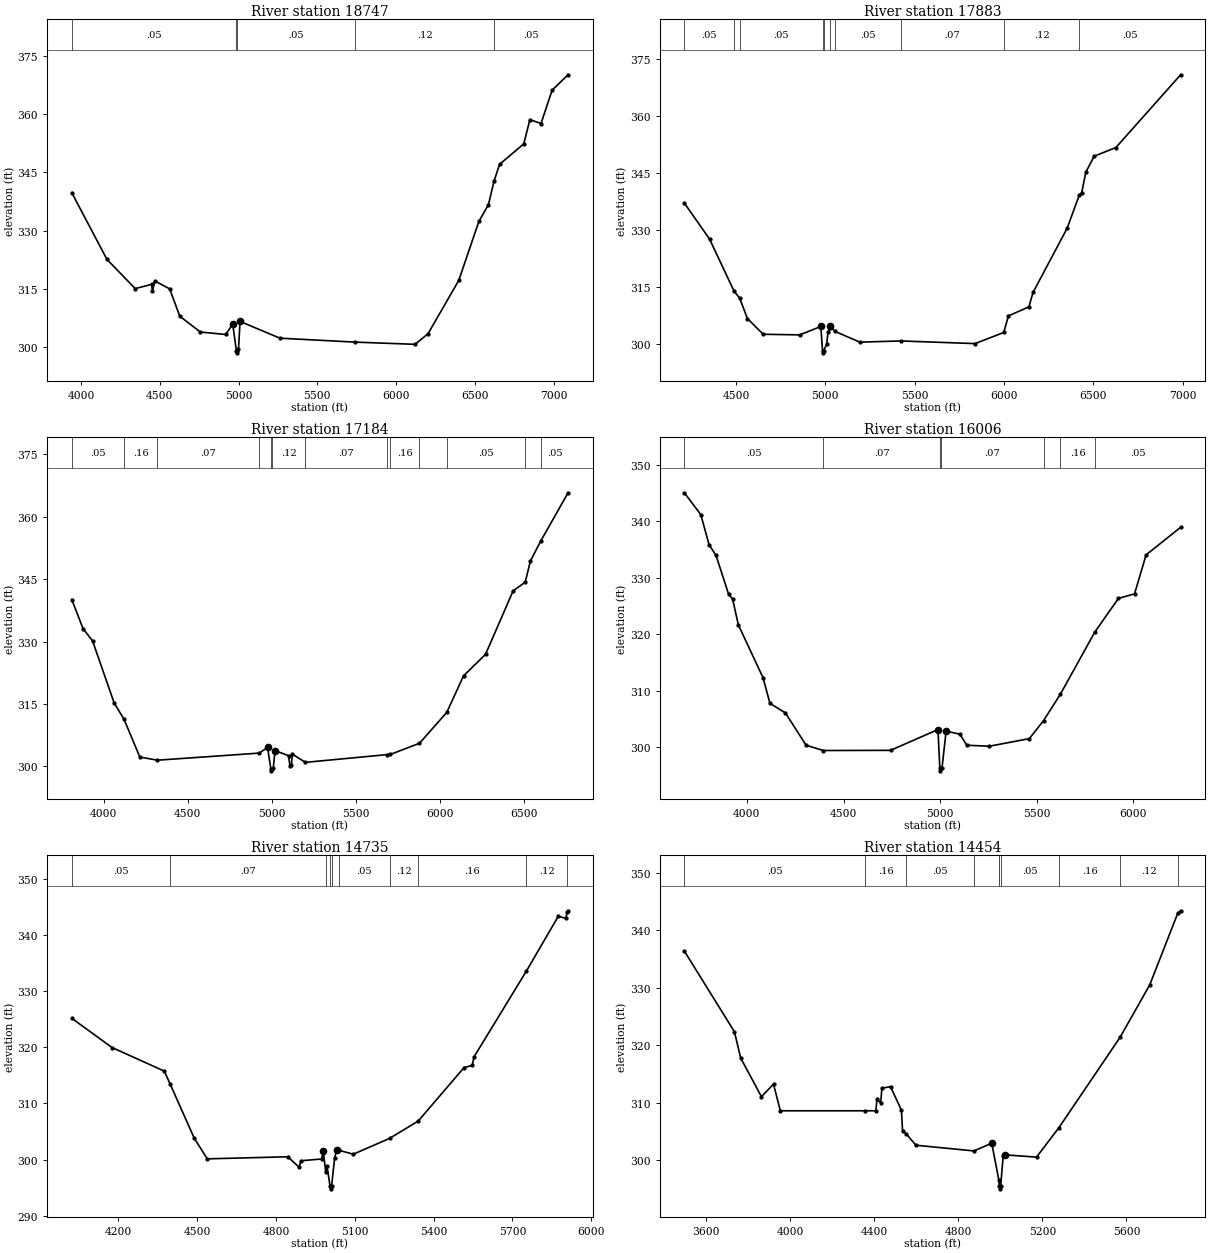
Type RM Length L Ch R = 1 ,18747   ,864,864,864
BEGIN DESCRIPTION:
CANEY CREEK 11.0
END DESCRIPTION:
XS GIS Cut Line= 3
      3561480.19     10651076.86      3562299.66     10650562.96
      3564459.38     10650243.51
#Sta/Elev= 30
  3941.6  339.76  4164.9  322.53  4344.1  314.99  4447.8  316.08  4453.7  314.37
    4469  316.97  4563.2  314.91  4626.9  307.86  4757.7  303.77  4918.9  303.13
  4963.2  305.84  4986.7  298.89  4989.4  298.39  4992.7  298.89  4999.8   299.3
  5009.9   306.5  5262.6  302.18    5740  301.16  6120.3  300.59  6202.8   303.3
  6398.5  317.12  6526.2  332.37  6586.9  336.69  6622.1  342.76  6657.6  347.11
  6810.8  352.38  6849.7  358.64  6920.5  357.65  6991.2  366.27  7092.1  370.24
#Mann= 5 ,-1 , 0
  3941.6     .05       0  4986.7     .03       0  4992.7     .05       0
    5740     .12       0  6622.1     .05       0
Bank Sta=4963.2,5009.9
XS Rating Curve= 0 ,0
Exp/Cntr=0.3,0.1

Type RM Length L Ch R = 1 ,17883   ,699,699,699
BEGIN DESCRIPTION:
CANEY CREEK 10.0
END DESCRIPTION:
XS GIS Cut Line= 3
      3561899.56     10651310.19      3562699.61     10651210.19
      3564499.57     10650410.21
#Sta/Elev= 30
  4211.4  337.06  4352.5  327.57  4489.5  313.86  4521.2  311.99  4564.2  306.65
  4652.3  302.51  4856.4  302.35  4974.8  304.56  4984.4  298.12  4987.2  297.62
  4990.4  298.12  5007.6  299.91  5015.2  303.16  5024.7  304.24  5026.6  304.71
  5055.2  303.25  5192.8  300.44  5423.9  300.75  5837.7  300.05  5998.1  302.99
  6024.4  307.35  6138.7  309.73  6161.9  313.52  6352.7  330.43  6420.5  339.14
  6434.1  339.78  6457.4  345.21  6503.9  349.39  6625.6  351.69  6987.4  370.84
#Mann= 10 ,-1 , 0
  4211.4     .05       0  4489.5     .16       0  4521.2     .05       0
  4984.4     .03       0  4990.4     .05       0  5024.7     .16       0
  5055.2     .05       0  5423.9     .07       0  5998.1     .12       0
  6420.5     .05       0
Bank Sta=4974.8,5026.6
XS Rating Curve= 0 ,0
Exp/Cntr=0.3,0.1

Type RM Length L Ch R = 1 ,17184   ,1178,1178,1178
BEGIN DESCRIPTION:
CANEY CREEK 9.0
END DESCRIPTION:
XS GIS Cut Line= 3
      3561862.12     10651451.84       3562931.6     10651660.18
      3564611.58      10650854.9
#Sta/Elev= 30
  3810.8  340.09  3877.5  333.12  3934.3  330.15  4062.9  315.23  4120.7  311.39
  4215.8  302.23  4320.7  301.48  4924.7  303.18  4975.8  304.53    4995  299.42
  4997.7  298.92    5001  299.42  5009.5  299.59  5020.2  303.77  5100.2  302.57
  5108.9  300.05  5117.3  300.31  5122.8  302.94  5200.8  300.96  5685.2  302.81
  5706.2  302.86  5879.5  305.55  6041.7  312.96  6141.9  321.77  6272.3  326.91
  6436.5  342.17  6508.5  344.26  6539.4  349.35  6600.9  354.15  6763.4  365.75
#Mann= 13 ,-1 , 0
  3810.8     .05       0  4120.7     .16       0  4320.7     .07       0
  4924.7     .12       0    4995     .07       0    5001     .12       0
  5200.8     .07       0  5685.2     .12       0  5706.2     .16       0
  5879.5     .12       0  6041.7     .05       0  6508.5     .08       0
  6600.9     .05       0
Bank Sta=4975.8,5020.2
XS Rating Curve= 0 ,0
Exp/Cntr=0.3,0.1

Type RM Length L Ch R = 1 ,16006   ,1271,1271,1271
BEGIN DESCRIPTION:
CANEY CREEK 8.0
END DESCRIPTION:
XS GIS Cut Line= 3
      3561770.37     10651600.97      3562971.79     10652455.15
      3563985.15     10652864.66
#Sta/Elev= 30
  3676.7  345.07  3761.7  341.21  3804.7  335.87  3840.4  333.99  3905.5  327.12
  3926.4  326.25    3956  321.69  4083.9  312.31  4119.5  307.78  4199.5  306.09
  4306.5  300.37  4395.2  299.43  4743.2  299.46  4988.6  303.14  4998.3  296.33
  5001.1  295.83  5004.3  296.33  5009.9  296.42  5030.8  302.86  5102.2  302.32
  5137.8  300.36  5254.3  300.19  5461.3  301.53  5534.6  304.71  5621.7  309.39
  5799.9   320.4  5922.3  326.37  6005.5  327.17  6065.3  334.08  6243.8  338.95
#Mann= 7 ,-1 , 0
  3676.7     .05       0  4395.2     .07       0  4998.3     .07       0
  5004.3     .07       0  5534.6     .05       0  5621.7     .16       0
  5799.9     .05       0
Bank Sta=4988.6,5030.8
XS Rating Curve= 0 ,0
Exp/Cntr=0.3,0.1

Type RM Length L Ch R = 1 ,14735   ,281,281,281
BEGIN DESCRIPTION:
CANEY CREEK 7.0
END DESCRIPTION:
XS GIS Cut Line= 3
      3562117.63     10652357.94      3562805.12     10653232.93
      3563471.79     10653628.77
#Sta/Elev= 30
  4023.5  325.19  4176.5  319.98  4375.4  315.77  4396.8  313.56  4489.3  303.81
    4539  300.12  4845.4  300.49  4888.7  298.61  4895.1  299.78  4973.7  300.09
  4980.2  301.56  4989.6  297.76  4994.5  298.83    5006  295.27  5008.7  294.77
    5012  295.27  5023.4  300.23    5031  301.65  5038.4  301.66  5094.6  300.95
  5232.7  303.77  5341.5  306.86  5516.1  316.41  5547.4  316.78  5553.2  318.26
  5752.4  333.56  5874.2  343.37  5903.9  343.02  5907.4  344.15  5911.6  344.37
#Mann= 10 ,-1 , 0
  4023.5     .05       0  4396.8     .07       0  4989.6     .12       0
    5006     .07       0    5012     .12       0  5038.4     .05       0
  5232.7     .12       0  5341.5     .16       0  5752.4     .12       0
  5907.4     .16       0
Bank Sta=4980.2,5031
XS Rating Curve= 0 ,0
Exp/Cntr=0.3,0.1

Type RM Length L Ch R = 1 ,14454   ,962,962,962
BEGIN DESCRIPTION:
CANEY CREEK 6.0
END DESCRIPTION:
XS GIS Cut Line= 2
      3561221.76     10652705.14      3563381.48     10653663.48
#Sta/Elev= 30
  3495.2  336.41  3733.5  322.37  3763.7  317.77  3862.2  311.06  3919.7  313.23
  3952.3   308.6  4353.8   308.6    4407   308.6  4412.4  310.63  4430.2  309.96
  4435.7  312.54  4476.8  312.79  4528.8  308.71  4534.2  305.08  4552.9  304.53
  4597.8   302.6  4874.3  301.61  4958.8  302.96  4992.1  296.63  4995.2  295.51
    4998  295.01  5001.2  295.51  5013.5  300.78  5021.5  300.93    5172  300.53
  5278.4  305.65    5570   321.4  5711.3  330.54  5844.1  342.96    5858  343.42
#Mann= 10 ,-1 , 0
  3495.2     .05       0  4353.8     .16       0  4552.9     .05       0
  4874.3     .07       0  4992.1     .05       0  4995.2     .03       0
  5001.2     .05       0  5278.4     .16       0    5570     .12       0
  5844.1     .16       0
Bank Sta=4958.8,5021.5
XS Rating Curve= 0 ,0
Exp/Cntr=0.3,0.1

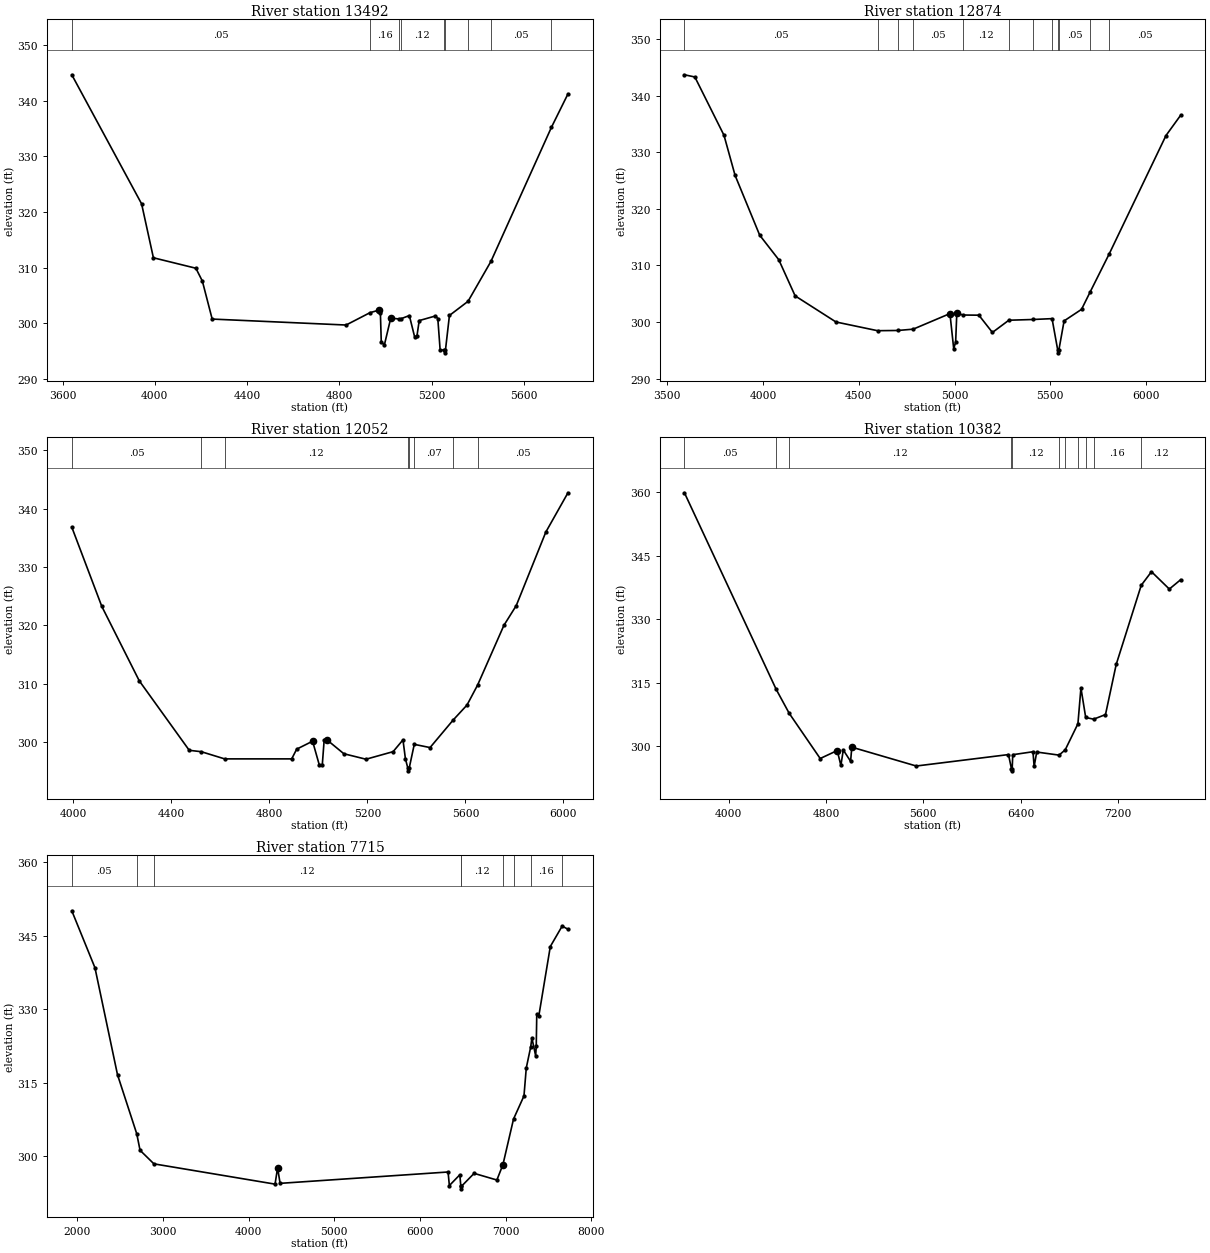
Type RM Length L Ch R = 1 ,13492   ,618,618,618
BEGIN DESCRIPTION:
CANEY CREEK 5.0
END DESCRIPTION:
XS GIS Cut Line= 3
      3561099.63      10652910.2      3562099.61     10653810.19
      3562899.64     10653910.19
#Sta/Elev= 30
  3639.8  344.65  3942.5  321.45  3993.7  311.75  4177.9  309.87    4206  307.56
  4248.6  300.73  4829.3  299.66  4932.9  301.88 4970.17  302.32    4978  301.87
  4981.8  296.65  4995.2  296.06  5022.9  300.89  5060.4  300.75  5065.7  300.77
  5103.6  301.36  5126.2  297.58  5136.3  297.62  5146.4  300.46  5216.9  301.29
    5227  300.83  5237.1  295.18  5254.2  295.16    5257  294.66  5260.2  295.16
  5277.4  301.38  5358.1  303.92  5457.3  311.09    5720  335.23  5791.4  341.21
#Mann= 9 ,-1 , 0
  3639.8     .05       0  4932.9     .16       0  5060.4     .07       0
  5065.7     .12       0  5254.2     .07       0  5260.2     .12       0
  5358.1     .07       0  5457.3     .05       0    5720     .16       0
Bank Sta=4970.17,5022.9
XS Rating Curve= 0 ,0
Exp/Cntr=0.3,0.1

Type RM Length L Ch R = 1 ,12874   ,822,822,822
BEGIN DESCRIPTION:
CANEY CREEK 4.0
END DESCRIPTION:
XS GIS Cut Line= 3
      3560348.98     10653651.78      3561508.68     10654151.77
      3562821.16     10654346.21
#Sta/Elev= 30
  3590.4  343.67  3644.8  343.28  3796.8  332.99  3854.7  325.91  3983.2  315.34
  4082.7  311.01  4168.2  304.62  4381.3  300.01  4598.4  298.47  4704.4  298.51
  4784.2  298.74 4976.14  301.49  4995.8  295.31  5005.9  296.42    5012  301.56
  5045.4  301.24  5127.2  301.21  5197.9  298.16  5283.6  300.32  5409.6  300.45
  5509.1   300.6  5538.7  295.06  5541.4  294.56  5544.7  295.06    5572   300.2
    5663  302.24    5708  305.31  5807.4  312.03  6103.8  332.94  6180.1  336.51
#Mann= 12 ,-1 , 0
  3590.4     .05       0  4598.4     .07       0  4704.4     .12       0
  4784.2     .05       0  5045.4     .12       0  5283.6     .16       0
  5409.6     .12       0  5509.1     .05       0  5538.7     .03       0
  5544.7     .05       0    5708      .1       0  5807.4     .05       0
Bank Sta=4976.14,5012
XS Rating Curve= 0 ,0
Exp/Cntr=0.3,0.1

Type RM Length L Ch R = 1 ,12052   ,1670,1670,1670
BEGIN DESCRIPTION:
CANEY CREEK 3.0
END DESCRIPTION:
XS GIS Cut Line= 3
       3560599.6     10654710.19      3561599.61     10654910.19
      3562599.61     10654810.19
#Sta/Elev= 30
  3993.5  336.84  4115.9  323.26  4268.9  310.49  4472.8  298.58    4522  298.34
  4617.2  297.11  4890.9  297.11  4911.3  298.78 4976.14  300.14  5003.1  296.13
  5015.8  296.11  5023.4  300.34  5033.4  300.42  5103.8  297.99  5194.2  297.05
  5304.8  298.35    5345  300.37    5355  297.12  5364.6  295.56  5367.3  295.06
  5370.6  295.56  5391.1   299.6  5455.5  299.05  5549.8  303.77  5606.3  306.34
  5649.6  309.77    5757  320.01  5807.3  323.39  5927.9  335.99  6018.3  342.73
#Mann= 8 ,-1 , 0
  3993.5     .05       0    4522     .16       0  4617.2     .12       0
  5364.6     .07       0  5370.6     .12       0  5391.1     .07       0
  5549.8     .12       0  5649.6     .05       0
Bank Sta=4976.14,5033.4
XS Rating Curve= 0 ,0
Exp/Cntr=0.3,0.1

Type RM Length L Ch R = 1 ,10382   ,2667,2667,2667
BEGIN DESCRIPTION:
CANEY CREEK 2.0
END DESCRIPTION:
XS GIS Cut Line= 4
      3559994.29     10655788.13      3560910.94     10656392.28
      3561744.27     10656392.28      3563576.11      10655268.2
#Sta/Elev= 30
  3635.4  359.84  4390.3  313.39  4497.1  307.75  4751.9  297.08  4891.9  298.96
  4921.9  295.46  4941.9  299.08  5001.9  296.42  5011.9  299.76  5541.9  295.31
  6300.3  298.01  6324.7  294.67  6327.5  294.17  6330.7  294.67  6335.5  297.98
  6501.7  298.68  6511.3   295.2  6532.6  298.61  6716.4  297.88  6766.9  299.13
  6871.3  305.28  6896.1  313.75  6935.3  306.77  7000.6  306.37  7098.1  307.46
  7186.1  319.29    7392  337.99  7476.2   341.2  7623.1   337.1  7715.8   339.3
#Mann= 11 ,-1 , 0
  3635.4     .05       0  4390.3     .16       0  4497.1     .12       0
  6324.7     .07       0  6330.7     .12       0  6716.4     .16       0
  6766.9     .12       0  6871.3     .16       0  6935.3      .1       0
  7000.6     .16       0    7392     .12       0
Bank Sta=4891.9,5011.9
XS Rating Curve= 0 ,0
Exp/Cntr=0.3,0.1

Type RM Length L Ch R = 1 ,7715    ,0,0,0
BEGIN DESCRIPTION:
CANEY CREEK 1.0
END DESCRIPTION:
XS GIS Cut Line= 3
      3560056.77     10656183.95      3561327.61     10657808.95
      3564389.24     10655684.55
#Sta/Elev= 30
  1937.4  350.13  2207.7   338.5  2470.9  316.65  2695.4   304.6    2734  301.23
  2895.8  298.46  4309.1  294.32  4338.8  297.65  4367.9  294.48    6328   296.8
  6342.9  294.03  6465.1  296.23    6477  293.86  6479.7  293.36    6483  293.86
  6631.8  296.52  6897.4  295.16    6968   298.3  7091.8  307.62  7213.5  312.33
  7240.5  318.05  7291.9  322.32    7306  324.16  7349.9  320.52  7356.7  322.51
  7362.8     329  7386.4  328.63  7520.8  342.83  7659.2  347.01  7726.8  346.36
#Mann= 9 ,-1 , 0
  1937.4     .05       0  2695.4     .16       0  2895.8     .12       0
    6477     .07       0    6483     .12       0    6968     .16       0
  7091.8     .05       0  7291.9     .16       0  7659.2     .05       0
Bank Sta=4338.8,6968
XS Rating Curve= 0 ,0
Exp/Cntr=0.3,0.1

Chan Stop Cuts=-1
Use User Specified Reach Order=0
Composite Channel Slope=5