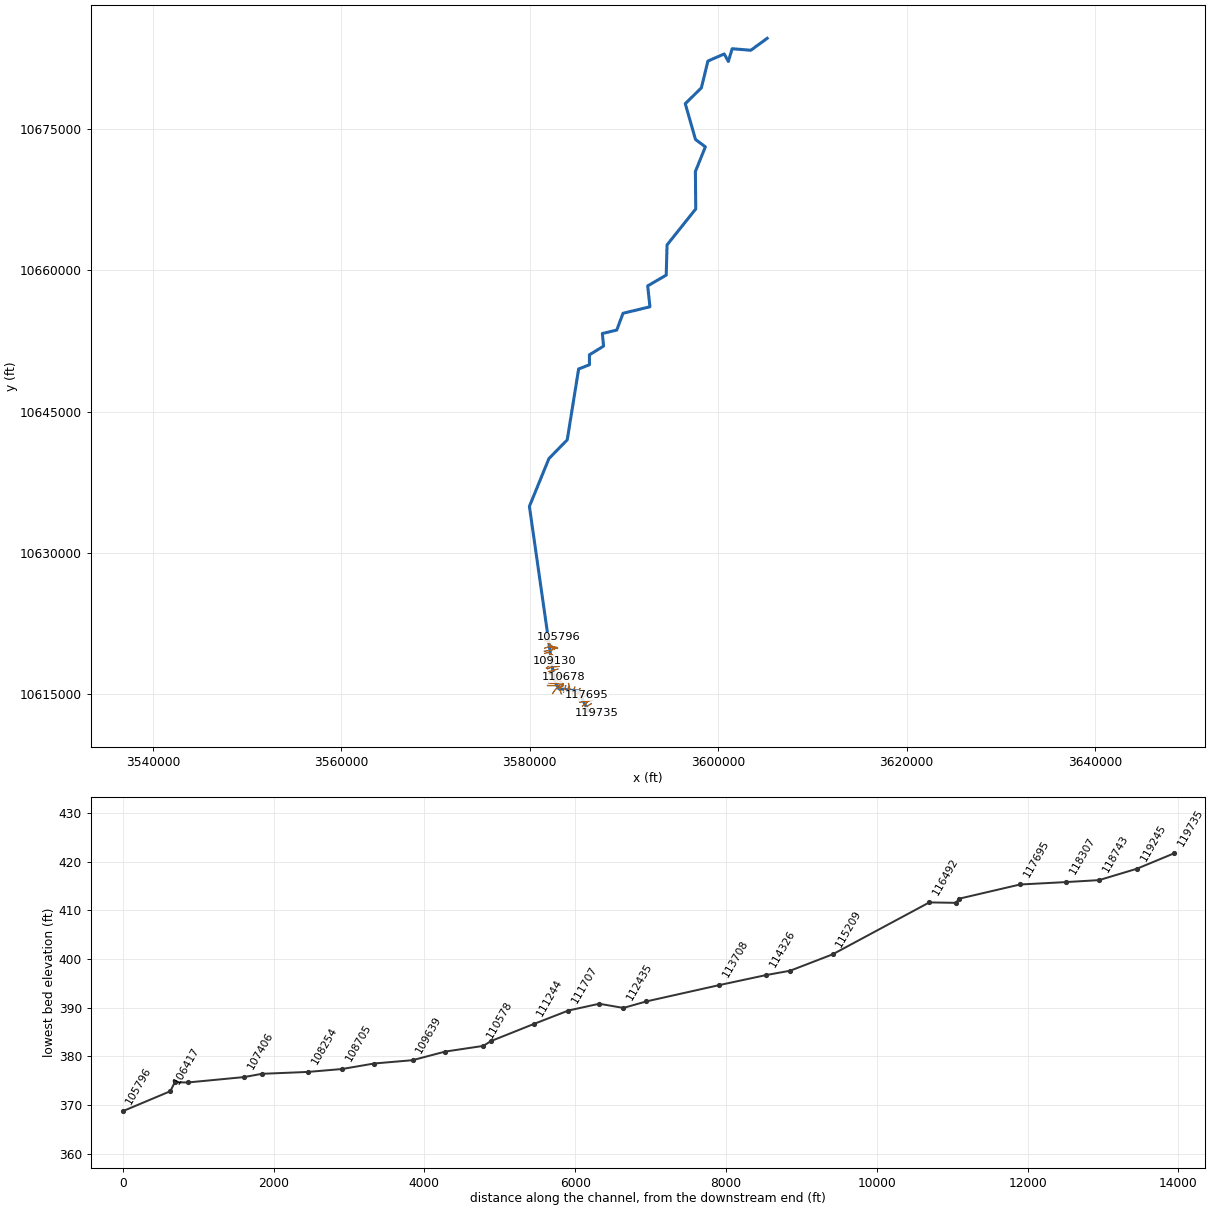
--- COTTONWOOD CREEK.prj (project) ---

Proj Title=COTTONWOOD CREEK Base Level Engineering
Current Plan=p01
Default Exp/Contr=0.3,0.1
English Units
Geom File=g01
Flow File=f01
Plan File=p01
Y Axis Title=Elevation
X Axis Title(PF)=Main Channel Distance
X Axis Title(XS)=Station
BEGIN DESCRIPTION:
COTTONWOOD CREEK
END DESCRIPTION:
DSS Export Rating Curves= 0
DSS Export Rating Curve Sorted= 0
DSS Export Volume Flow Curves= 0
DXF OffsetX= 0
DXF OffsetY= 0
DXF ScaleX= 1
DXF ScaleY= 10

--- COTTONWOOD CREEK.p01 (plan) ---

Plan Title=Multiple Run
Short Identifier=Multiple
Geom File=g01
Flow File=f01
Subcritical Flow
K Sum by GR= 0
Std Step Tol= 0.01
Critical Tol= 0.01
Num of Std Step Trials= 20
Max Error Tol= 0.3
Flow Tol Ratio= 0.001
Split Flow NTrial= 30
Split Flow Tol= 0.02
Split Flow Ratio= 0.02
Log Output Level= 0
Friction Slope Method= 1
Unsteady Friction Slope Method= 2
Unsteady Bridges Friction Slope Method= 1
Parabolic Critical Depth
Global Vel Dist=  1 , 1 , 1
Global Log Level= 0
CheckData=True
Encroach Param= -1, 0, 0, 0
BEGIN DESCRIPTION:
Multiple Run
END DESCRIPTION:

--- COTTONWOOD CREEK.f01 (steady flow) ---

Flow Title=Multiple
Program Version=4.10
Number of Profiles= 7
Profile Names=10-year,25-year,50-year,1pct_min,100-year,1pct_plu,500-year
River Rch & RM=COTTONWOOD CREEK,Reach-1         ,119735
    1400    1914    2337    2082    2816    3808    4073
River Rch & RM=COTTONWOOD CREEK,Reach-1         ,112435
    2884    4097    5132    4679    6328    8557    9593
River Rch & RM=COTTONWOOD CREEK,Reach-1         ,111244
    2884    4097    5132    4679    6328    8557    9593
River Rch & RM=COTTONWOOD CREEK,Reach-1         ,106494
    3794    5462    6902    6344    8580   11603   13220
River Rch & RM=COTTONWOOD CREEK,Reach-1         ,105052
    4850    7034    8933    8242   11147   15075   17311
River Rch & RM=COTTONWOOD CREEK,Reach-1         ,104444
    4850    7034    8933    8242   11147   15075   17311
River Rch & RM=COTTONWOOD CREEK,Reach-1         ,101805
    4850    7034    8933    8242   11147   15075   17311
River Rch & RM=COTTONWOOD CREEK,Reach-1         ,98458
    5542    8056   10243    9459   12792   17299   19894
River Rch & RM=COTTONWOOD CREEK,Reach-1         ,92346
    6001    8723   11093   10239   13848   18727   21521
River Rch & RM=COTTONWOOD CREEK,Reach-1         ,92244
    6001    8723   11093   10239   13848   18727   21521
River Rch & RM=COTTONWOOD CREEK,Reach-1         ,91200
    6001    8723   11093   10239   13848   18727   21521
River Rch & RM=COTTONWOOD CREEK,Reach-1         ,87771
    6332    9216   11729   10833   14650   19812   22795
River Rch & RM=COTTONWOOD CREEK,Reach-1         ,85260
    6703    9779   12466   11530   15593   21088   24334
River Rch & RM=COTTONWOOD CREEK,Reach-1         ,82284
    6948   10136   12919   11946   16155   21848   25195
River Rch & RM=COTTONWOOD CREEK,Reach-1         ,75717
   11319   16782   21629   20202   27321   36948   43462
River Rch & RM=COTTONWOOD CREEK,Reach-1         ,71501
   12101   17961   23166   21650   29279   39596   46628
River Rch & RM=COTTONWOOD CREEK,Reach-1         ,68837
   12277   18219   23498   21957   29694   40158   47276
River Rch & RM=COTTONWOOD CREEK,Reach-1         ,65764
   12277   18219   23498   21957   29694   40158   47276
River Rch & RM=COTTONWOOD CREEK,Reach-1         ,63711
   12312   18226   23498   21957   29694   40158   47276
River Rch & RM=COTTONWOOD CREEK,Reach-1         ,58872
   12541   18535   23836   22201   30024   40604   47492
River Rch & RM=COTTONWOOD CREEK,Reach-1         ,51226
   13418   19830   25499   23743   32110   43425   50758
River Rch & RM=COTTONWOOD CREEK,Reach-1         ,46532
   13545   20001   25705   23921   32350   43750   51072
River Rch & RM=COTTONWOOD CREEK,Reach-1         ,45000
   13545   20001   25705   23921   32350   43750   51072
River Rch & RM=COTTONWOOD CREEK,Reach-1         ,41384
   14061   20754   26665   24803   33543   45363   52907
River Rch & RM=COTTONWOOD CREEK,Reach-1         ,34504
   14257   21049   27050   25165   34032   46025   53696
River Rch & RM=COTTONWOOD CREEK,Reach-1         ,29726
   14257   21049   27050   25165   34032   46025   53696
River Rch & RM=COTTONWOOD CREEK,Reach-1         ,22708
   14257   21049   27050   25165   34032   46025   53696
Boundary for River Rch & Prof#=COTTONWOOD CREEK,Reach-1         , 1
Up Type= 0
Dn Type= 3
Dn Slope=0.003
Boundary for River Rch & Prof#=COTTONWOOD CREEK,Reach-1         , 2
Up Type= 0
Dn Type= 3
Dn Slope=0.003
Boundary for River Rch & Prof#=COTTONWOOD CREEK,Reach-1         , 3
Up Type= 0
Dn Type= 3
Dn Slope=0.003
Boundary for River Rch & Prof#=COTTONWOOD CREEK,Reach-1         , 4
Up Type= 0
Dn Type= 3
Dn Slope=0.003
Boundary for River Rch & Prof#=COTTONWOOD CREEK,Reach-1         , 5
Up Type= 0
Dn Type= 3
Dn Slope=0.003
Boundary for River Rch & Prof#=COTTONWOOD CREEK,Reach-1         , 6
Up Type= 0
Dn Type= 3
Dn Slope=0.003
Boundary for River Rch & Prof#=COTTONWOOD CREEK,Reach-1         , 7
Up Type= 0
Dn Type= 3
Dn Slope=0.003
DSS Import GetInterval= 0
DSS Import GetPeak= 0
DSS Import FillOption= 0

--- COTTONWOOD CREEK.g01 (geometry) ---

Geom Title=Existing Conditions
Program Version=4.10

River Reach=COTTONWOOD CREEK,Reach-1
Reach XY= 30
       3586191.5     10613197.55      3585182.25       10615306.
      3583071.25       10615553.       3582599.5       10616420.
      3579960.25       10634931.      3582032.75       10640009.
        3583976.       10642002.        3585186.       10649532.
       3586334.5       10649977.        3586330.       10651031.
      3587834.25       10651958.      3587701.75       10653300.
      3589229.75       10653660.        3589897.       10655445.
        3592754.       10656138.      3592515.75       10658357.
      3594482.25       10659503.      3594571.25       10662715.
       3597616.5       10666532.        3597580.       10670514.
        3598639.       10673131.       3597592.5       10673912.
        3596505.       10677713.        3598219.       10679410.
       3598905.5       10682246.       3600639.5       10683001.
        3601078.       10682203.      3601480.75       10683558.
       3603462.5       10683394.       3605199.5       10684661.

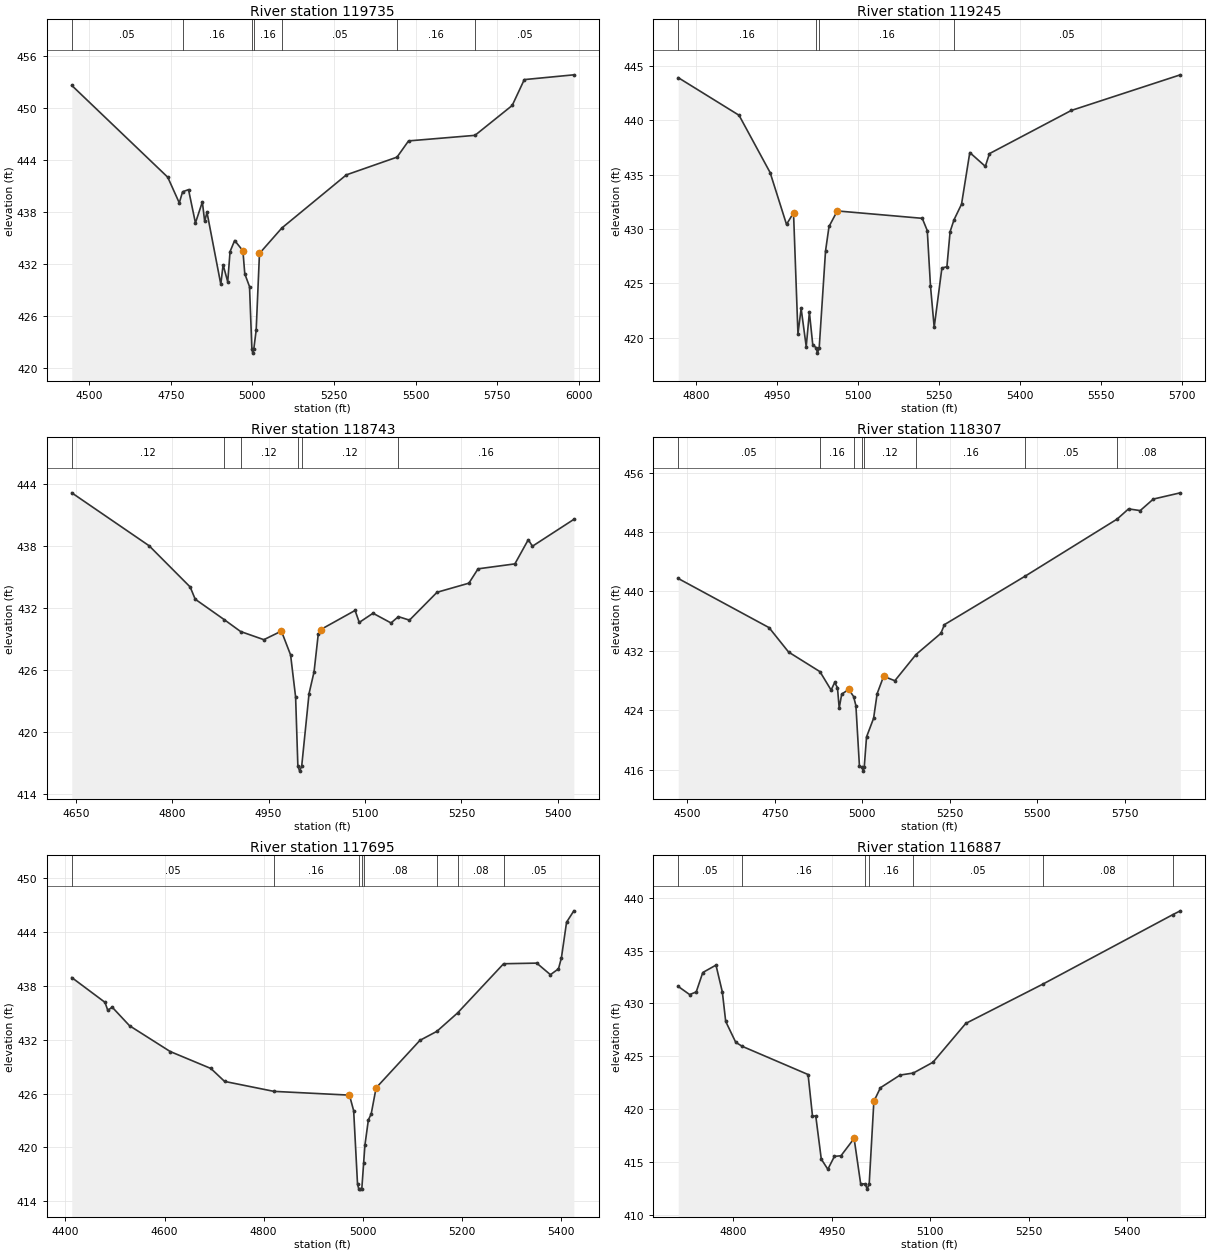
Type RM Length L Ch R = 1 ,119735  ,490,490,490
BEGIN DESCRIPTION:
COTTONWOOD CREEK 166.0
END DESCRIPTION:
XS GIS Cut Line= 4
      3585787.38     10612936.31        3586152.     10613302.66
       3586219.7     10613314.82      3587125.24     10613016.44
#Sta/Elev= 30
  4446.3  452.56  4740.5  441.99  4775.9  439.03    4786  440.31  4804.2  440.56
  4825.4  436.72  4846.6  439.14  4853.7  436.91  4860.8  437.95  4903.2  429.65
  4910.2  431.91  4924.4  429.94  4931.5  433.42  4945.6   434.7  4970.9  433.52
  4976.7  430.86  4991.2  429.39  4998.4  422.23  5001.1  421.73  5004.4  422.23
  5011.6  424.37  5021.7  433.21  5090.3  436.14  5288.1  442.26  5443.3   444.3
  5478.7  446.17  5682.3  446.81  5796.4  450.25  5833.5  453.23  5985.4  453.78
#Mann= 7 ,-1 , 0
  4446.3     .05       0    4786     .16       0  4998.4     .07       0
  5004.4     .16       0  5090.3     .05       0  5443.3     .16       0
  5682.3     .05       0
Bank Sta=4970.9,5021.7
XS Rating Curve= 0 ,0
Exp/Cntr=0.3,0.1

Type RM Length L Ch R = 1 ,119245  ,502,502,502
BEGIN DESCRIPTION:
COTTONWOOD CREEK 165.0
END DESCRIPTION:
XS GIS Cut Line= 2
      3585739.21     10613464.97      3586524.68     10613964.02
#Sta/Elev= 30
  4766.9  443.92  4879.6  440.46  4937.2  435.19  4967.6  430.42  4980.6  431.49
  4988.8  420.35  4994.7  422.69  5004.1  419.18    5010  422.34  5016.2  419.37
  5022.2  419.08    5025  418.58  5028.2  419.08  5039.9  427.97  5046.4  430.23
  5061.7  431.66  5219.2  430.98  5228.5  429.85  5234.4  424.78  5241.3  420.96
  5255.6  426.41  5264.9  426.53  5270.8  429.75    5278  430.84    5292  432.28
  5307.3  437.03  5336.1  435.76  5343.7  436.93  5495.3   440.9  5697.5  444.18
#Mann= 4 ,-1 , 0
  4766.9     .16       0  5022.2     .07       0  5028.2     .16       0
    5278     .05       0
Bank Sta=4980.6,5061.7
XS Rating Curve= 0 ,0
Exp/Cntr=0.3,0.1

Type RM Length L Ch R = 1 ,118743  ,436,436,436
BEGIN DESCRIPTION:
COTTONWOOD CREEK 164.0
END DESCRIPTION:
XS GIS Cut Line= 3
      3585599.59     10613710.17      3585899.61     10613960.19
      3586199.57     10614210.16
#Sta/Elev= 30
  4643.8  443.19  4764.2  438.06    4828  434.07  4835.8  432.89  4881.2   430.9
  4906.4  429.76  4942.6  428.97  4969.9   429.8  4984.2  427.49    4992  423.41
  4995.5  416.74  4998.3  416.24  5001.5  416.74  5012.9  423.75  5020.7  425.86
  5027.2   429.5  5031.1  429.95  5084.5   431.8    5091  430.64  5112.4  431.53
  5140.4  430.59  5151.9   431.2  5169.1  430.86    5212  433.56  5261.5  434.44
  5275.8  435.83  5333.1  436.31  5353.9  438.65  5360.4  438.02  5424.8  440.62
#Mann= 6 ,-1 , 0
  4643.8     .12       0  4881.2     .16       0  4906.4     .12       0
  4995.5     .07       0  5001.5     .12       0  5151.9     .16       0
Bank Sta=4969.9,5031.1
XS Rating Curve= 0 ,0
Exp/Cntr=0.3,0.1

Type RM Length L Ch R = 1 ,118307  ,612,612,612
BEGIN DESCRIPTION:
COTTONWOOD CREEK 163.0
END DESCRIPTION:
XS GIS Cut Line= 2
      3585287.83     10614115.99      3586705.85     10614332.82
#Sta/Elev= 30
  4473.9  441.75  4733.4  435.14  4789.3  431.85  4878.8  429.22  4910.7  426.74
  4920.8  427.76  4928.8  427.08  4933.8  424.32    4941   426.2  4961.3  426.83
  4974.9  425.87  4981.5  424.65  4991.6  416.53  4999.3  416.34  5002.1  415.84
  5005.3  416.34  5011.9  420.44  5032.1  422.95  5042.2  426.26  5060.7  428.59
  5092.8     428  5153.2  431.52  5224.3  434.37  5234.4  435.54    5466  442.09
  5727.9  449.74  5760.5  451.11  5793.8  450.88  5831.3  452.43  5908.4  453.27
#Mann= 8 ,-1 , 0
  4473.9     .05       0  4878.8     .16       0  4974.9     .12       0
  4999.3     .07       0  5005.3     .12       0  5153.2     .16       0
    5466     .05       0  5727.9     .08       0
Bank Sta=4961.3,5060.7
XS Rating Curve= 0 ,0
Exp/Cntr=0.3,0.1

Type RM Length L Ch R = 1 ,117695  ,808,808,808
BEGIN DESCRIPTION:
COTTONWOOD CREEK 162.0
END DESCRIPTION:
XS GIS Cut Line= 2
      3585157.61     10614402.46      3586051.72      10614879.9
#Sta/Elev= 30
  4412.7  438.93  4479.7  436.17  4485.4  435.28  4494.3  435.63  4529.3  433.56
  4611.5  430.68  4693.6  428.79  4721.2  427.35  4820.8  426.24  4973.3  425.82
  4981.8  424.08  4989.6  415.88  4992.2  415.35    4995  415.34  4998.2  415.35
  5001.9  418.22  5004.5  420.24  5011.5  423.06  5017.2  423.73  5027.1  426.63
  5115.6  431.93  5149.7  432.93  5191.5  434.98  5284.5  440.47  5351.4  440.54
    5379  439.25  5395.3   439.9  5401.2  441.13  5411.6   445.1  5426.3  446.37
#Mann= 8 ,-1 , 0
  4412.7     .05       0  4820.8     .16       0  4992.2     .07       0
  4998.2     .16       0  5001.9     .08       0  5149.7     .05       0
  5191.5     .08       0  5284.5     .05       0
Bank Sta=4973.3,5027.1
XS Rating Curve= 0 ,0
Exp/Cntr=0.3,0.1

Type RM Length L Ch R = 1 ,116887  ,43,43,43
BEGIN DESCRIPTION:
COTTONWOOD CREEK 161.0
END DESCRIPTION:
XS GIS Cut Line= 4
      3585012.25     10614950.19      3585217.99     10614964.51
      3585361.22       10614958.       3585776.2     10614970.97
#Sta/Elev= 30
  4716.2  431.61  4733.6  430.84  4743.6  431.09  4753.6  432.93  4773.7  433.63
  4783.4  431.08  4788.5   428.3  4803.8  426.32  4813.7  425.94    4914  423.27
  4920.7  419.34  4925.7  419.34  4934.1  415.26  4944.1   414.3  4954.1  415.52
  4964.1  415.58  4984.1  417.22  4994.1  412.92  5001.1  412.92  5003.9  412.42
  5007.1  412.92  5014.2  420.73  5024.2  422.02  5054.2  423.22  5074.2  423.41
  5104.2  424.43  5154.2  428.11  5271.9  431.84  5469.6  438.41    5481  438.77
#Mann= 7 ,-1 , 0
  4716.2     .05       0  4813.7     .16       0  5001.1     .07       0
  5007.1     .16       0  5074.2     .05       0  5271.9     .08       0
  5469.6      .1       0
Bank Sta=4984.1,5014.2
XS Rating Curve= 0 ,0
Exp/Cntr=0.3,0.1

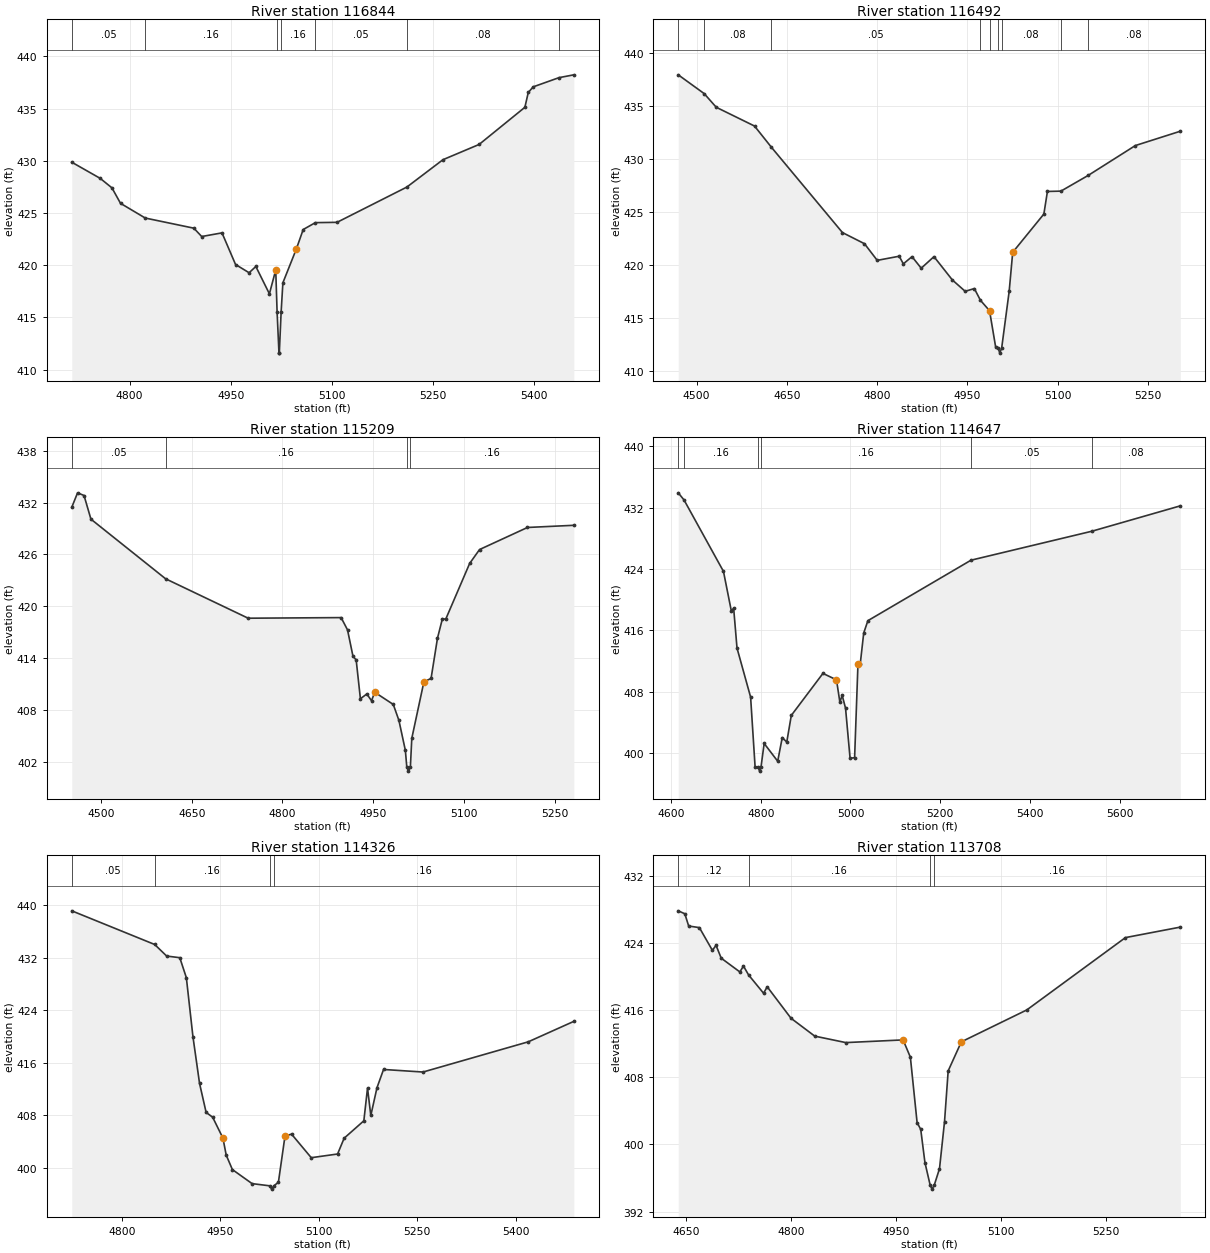
Type RM Length L Ch R = 1 ,116844  ,352,352,352
BEGIN DESCRIPTION:
COTTONWOOD CREEK 160.0
END DESCRIPTION:
XS GIS Cut Line= 2
      3585007.52     10614980.14      3585749.64      10615040.9
#Sta/Elev= 30
  4714.3  429.86  4756.5  428.31  4773.9   427.4  4786.6  425.92  4823.3  424.51
  4895.3  423.54    4907  422.74  4937.1  423.09  4957.2  420.06  4977.3  419.27
  4987.3  419.87  5007.4  417.25  5016.8  419.54  5018.8  415.52  5021.6  411.57
  5022.1  411.57  5024.8  415.52  5027.4  418.31  5047.5  421.57  5057.5  423.41
  5075.6  424.07  5107.7   424.1  5211.3  427.48  5264.8   430.1  5318.4  431.56
  5386.3  435.12  5391.3  436.54  5398.7  437.08  5436.9  437.96  5458.9  438.23
#Mann= 7 ,-1 , 0
  4714.3     .05       0  4823.3     .16       0  5018.8     .07       0
  5024.8     .16       0  5075.6     .05       0  5211.3     .08       0
  5436.9     .05       0
Bank Sta=5016.8,5047.5
XS Rating Curve= 0 ,0
Exp/Cntr=0.3,0.1

Type RM Length L Ch R = 1 ,116492  ,1283,1283,1283
BEGIN DESCRIPTION:
COTTONWOOD CREEK 159.0
END DESCRIPTION:
XS GIS Cut Line= 2
      3584890.29     10614862.94      3585333.02     10615570.43
#Sta/Elev= 30
  4469.4  437.91  4512.5  436.14  4532.6  434.85  4596.2  433.08  4624.4  431.07
  4742.4  423.03    4779  421.98  4800.2  420.41  4836.7   420.8  4843.6  420.08
    4858  420.76  4873.3  419.67  4894.5  420.76  4925.1  418.56  4946.4  417.49
  4961.6  417.75  4971.8  416.64  4986.9  415.66    4997  412.25  5001.1  412.16
  5003.9  411.66  5007.1  412.16  5019.5  417.48  5025.4  421.17  5077.2  424.78
  5083.1  426.91  5105.5  426.94  5150.8  428.42  5229.3  431.24    5304  432.59
#Mann= 9 ,-1 , 0
  4469.4     .16       0  4512.5     .08       0  4624.4     .05       0
  4971.8     .16       0  4986.9     .08       0  5001.1     .07       0
  5007.1     .08       0  5105.5     .05       0  5150.8     .08       0
Bank Sta=4986.9,5025.4
XS Rating Curve= 0 ,0
Exp/Cntr=0.3,0.1

Type RM Length L Ch R = 1 ,115209  ,562,562,562
BEGIN DESCRIPTION:
COTTONWOOD CREEK 158.0
END DESCRIPTION:
XS GIS Cut Line= 2
      3584495.35     10614941.12      3584777.46     10615722.34
#Sta/Elev= 30
  4451.4  431.45    4461  433.12  4471.7  432.81  4483.1  430.08  4606.7  423.19
  4743.2  418.64    4897  418.71  4907.6  417.29  4916.6  414.25  4921.9  413.82
  4928.9  409.34  4939.5  409.89  4947.3  409.11  4952.6  410.09  4983.3  408.68
  4992.6  406.84  5003.3  403.37  5005.6  401.48  5008.4  400.98  5011.6  401.48
  5013.9  404.76    5034  411.31  5045.8  411.68  5056.4  416.33  5064.6  418.59
    5070  418.52  5109.6  424.96    5126  426.57  5205.3  429.12    5282  429.37
#Mann= 4 ,-1 , 0
  4451.4     .05       0  4606.7     .16       0  5005.6     .07       0
  5011.6     .16       0
Bank Sta=4952.6,5034
XS Rating Curve= 0 ,0
Exp/Cntr=0.3,0.1

Type RM Length L Ch R = 1 ,114647  ,321,321,321
BEGIN DESCRIPTION:
COTTONWOOD CREEK 157.0
END DESCRIPTION:
XS GIS Cut Line= 3
      3584199.61     10615110.16      3584249.61     10615510.19
      3584099.62     10616210.16
#Sta/Elev= 30
  4616.2  433.93  4629.1     433    4717  423.68  4734.6   418.5  4739.7  418.88
  4747.2  413.67  4777.5  407.28  4787.5  398.17  4794.6  398.12  4797.4  397.62
  4800.6  398.12  4807.7  401.23  4837.9  398.91    4848     402  4858.1  401.41
  4868.2  404.89  4938.7  410.37  4968.9  409.53  4976.5   406.6  4981.5  407.53
  4989.1  405.82  4999.2  399.29  5009.3  399.38  5016.8  411.64  5021.9  411.64
  5029.6  415.64  5038.9  417.25  5268.7  425.14  5538.1  428.92  5735.2  432.23
#Mann= 6 ,-1 , 0
  4616.2     .05       0  4629.1     .16       0  4794.6     .07       0
  4800.6     .16       0  5268.7     .05       0  5538.1     .08       0
Bank Sta=4968.9,5016.8
XS Rating Curve= 0 ,0
Exp/Cntr=0.3,0.1

Type RM Length L Ch R = 1 ,114326  ,618,618,618
BEGIN DESCRIPTION:
COTTONWOOD CREEK 156.0
END DESCRIPTION:
XS GIS Cut Line= 2
      3584135.09     10614975.83      3584100.37     10615739.64
#Sta/Elev= 30
  4723.7  439.12    4850  433.99  4868.2  432.23  4888.2  431.98  4898.2  428.93
  4908.2  419.97  4918.3  412.82  4928.3  408.41  4938.3  407.67  4953.9  404.49
  4958.9   401.9  4968.3   399.7  4998.3  397.56  5025.4  397.22  5028.1  396.72
  5031.4  397.22  5038.4  397.77  5048.4   404.8  5058.4   405.1  5088.4  401.51
  5128.5  402.07  5138.5  404.48  5168.5  407.13  5174.1  412.12  5179.1  407.94
  5188.5  412.17  5198.5  414.95  5258.6  414.56  5418.8  419.16  5488.3  422.28
#Mann= 4 ,-1 , 0
  4723.7     .05       0    4850     .16       0  5025.4     .07       0
  5031.4     .16       0
Bank Sta=4953.9,5048.4
XS Rating Curve= 0 ,0
Exp/Cntr=0.3,0.1

Type RM Length L Ch R = 1 ,113708  ,968,968,968
BEGIN DESCRIPTION:
COTTONWOOD CREEK 155.0
END DESCRIPTION:
XS GIS Cut Line= 2
      3583620.48     10615181.12      3583815.79     10615871.21
#Sta/Elev= 30
  4638.5  427.83  4647.9  427.48  4653.4  426.02  4668.7  425.83  4687.3  423.12
  4692.5  423.72  4699.9  422.19  4726.5  420.55  4731.7  421.25    4739  420.19
  4760.4  418.01  4765.6  418.78  4799.6  415.03  4833.5   412.9  4877.9  412.13
  4959.7  412.45  4970.1  410.39  4979.7   402.6  4984.9  401.79  4990.9  397.84
  4998.3  395.17    5001  394.67  5004.3  395.17  5011.7   397.1  5018.9  402.72
  5024.1  408.76  5042.9  412.22  5136.4  416.02  5277.3  424.64  5355.7  425.89
#Mann= 4 ,-1 , 0
  4638.5     .12       0    4739     .16       0  4998.3     .07       0
  5004.3     .16       0
Bank Sta=4959.7,5042.9
XS Rating Curve= 0 ,0
Exp/Cntr=0.3,0.1

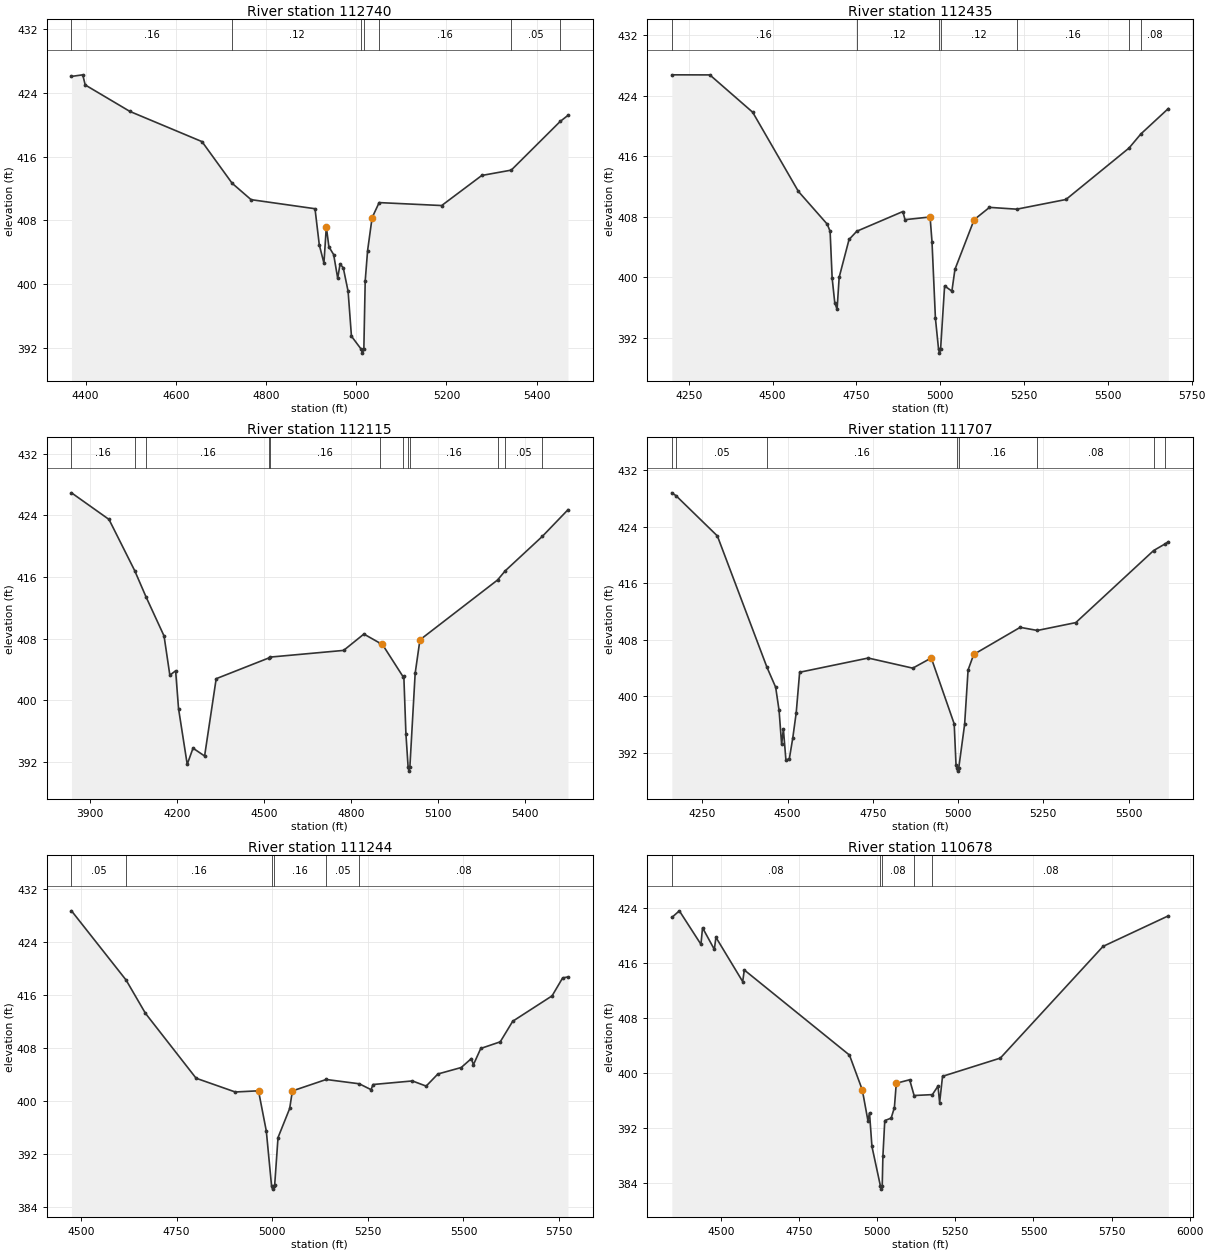
Type RM Length L Ch R = 1 ,112740  ,305,305,305
BEGIN DESCRIPTION:
COTTONWOOD CREEK 154.0
END DESCRIPTION:
XS GIS Cut Line= 4
       3583355.7     10615024.88      3583164.75     10615463.21
      3583260.23     10615723.63       3583568.4     10615879.88
#Sta/Elev= 30
  4368.6  426.07  4393.6  426.27    4399     425  4498.2  421.67    4658  417.88
  4724.8  412.65  4766.8  410.59  4908.6  409.45  4918.1  404.91  4928.4  402.62
  4933.7  407.17  4939.4  404.67    4950  403.68  4958.9  400.72  4964.2  402.51
  4971.3  402.02    4982  399.07  4989.4  393.44  5010.9  391.81  5013.7  391.31
  5016.9  391.81  5019.9  400.36  5025.2  404.18  5035.2  408.32  5050.8  410.22
  5189.5  409.85  5278.5  413.63  5343.8   414.3  5452.4  420.42  5469.6  421.18
#Mann= 7 ,-1 , 0
  4368.6     .16       0  4724.8     .12       0  5010.9     .07       0
  5016.9     .12       0  5050.8     .16       0  5343.8     .05       0
  5452.4     .08       0
Bank Sta=4933.7,5035.2
XS Rating Curve= 0 ,0
Exp/Cntr=0.3,0.1

Type RM Length L Ch R = 1 ,112435  ,320,320,320
BEGIN DESCRIPTION:
COTTONWOOD CREEK 153.0
END DESCRIPTION:
XS GIS Cut Line= 3
      3582426.91     10615055.23      3582756.76     10615515.29
      3583555.01     10615962.14
#Sta/Elev= 30
  4199.5  426.78  4312.9  426.77  4440.7  421.83    4577  411.36    4663  407.03
  4671.6  406.08  4677.7  399.89  4685.5  396.63  4692.4  395.76  4698.6     400
  4728.1     405  4751.1  406.09  4888.7   408.7  4894.9  407.62  4969.8  407.98
  4975.5  404.71  4985.7  394.58  4995.1  390.47  4997.8  389.97  5001.1  390.47
  5013.1  398.86  5034.8  398.17  5043.9  401.04  5101.2  407.62    5147  409.25
  5228.4  409.01    5375  410.29  5563.3   417.1  5598.5  418.96  5680.4  422.32
#Mann= 7 ,-1 , 0
  4199.5     .16       0  4751.1     .12       0  4995.1     .07       0
  5001.1     .12       0  5228.4     .16       0  5563.3     .05       0
  5598.5     .08       0
#XS Ineff= 1 ,-1
 4649.43 4880.57   407.3
Permanent Ineff=
       F
Bank Sta=4969.8,5101.2
XS Rating Curve= 0 ,0
Exp/Cntr=0.3,0.1

Type RM Length L Ch R = 1 ,112115  ,408,408,408
BEGIN DESCRIPTION:
COTTONWOOD CREEK 152.0
END DESCRIPTION:
XS GIS Cut Line= 3
      3581880.07      10615892.9      3582952.07     10615879.88
      3583554.99     10616101.09
#Sta/Elev= 30
  3835.4  426.93  3964.9  423.48  4053.6  416.84  4092.2  413.48    4155  408.36
    4175  403.28    4195  403.84    4205  398.94    4235  391.71    4255  393.81
    4295  392.79    4335  402.82  4518.1  405.53  4520.8  405.62    4775  406.49
    4845  408.61    4901  407.42  4907.5  407.35  4979.9   403.1  4982.9  403.14
  4990.1  395.68  4997.7  391.33  5000.5  390.83  5003.7  391.33    5022  403.51
  5038.5  407.86  5306.4  415.62  5332.9  416.81  5461.1  421.28  5549.7  424.74
#Mann= 12 ,-1 , 0
  3835.4     .16       0  4053.6     .05       0  4092.2     .16       0
  4518.1     .12       0  4520.8     .16       0    4901     .12       0
  4979.9     .16       0  4997.7     .07       0  5003.7     .16       0
  5306.4     .08       0  5332.9     .05       0  5461.1     .08       0
#XS Ineff= 1 ,-1
 4156.93 4694.89  406.17
Permanent Ineff=
       F
Bank Sta=4907.5,5038.5
XS Rating Curve= 0 ,0
Exp/Cntr=0.3,0.1

Type RM Length L Ch R = 1 ,111707  ,463,463,463
BEGIN DESCRIPTION:
Mapping XS 22c14912
END DESCRIPTION:
XS GIS Cut Line= 3
      3581986.66     10616177.77      3582743.59     10616101.39
      3583426.14     10616233.04
#Sta/Elev= 30
  4160.8  428.79    4173  428.39  4294.4  422.69  4439.8  404.12  4465.3   401.3
  4475.3  398.02  4482.8  393.22  4487.9   395.4  4495.4  390.98  4505.5  391.22
  4515.5  394.14  4525.6  397.72  4535.6  403.42  4736.7  405.43  4867.3     404
  4921.6  405.44  4988.8  396.12  4994.2  390.24  4996.3  389.94    4999  389.44
  5002.3  389.94  5019.4  396.07  5029.5  403.74    5046  405.94  5182.3  409.77
  5232.7  409.33  5345.3  410.44  5573.6  420.63  5606.1  421.54  5616.7  421.87
#Mann= 8 ,-1 , 0
  4160.8     .08       0    4173     .05       0  4439.8     .16       0
  4996.3     .07       0  5002.3     .16       0  5232.7     .08       0
  5573.6     .05       0  5606.1     .08       0
Bank Sta=4921.6,5046
XS Rating Curve= 0 ,0
Exp/Cntr=0.3,0.1

Type RM Length L Ch R = 1 ,111244  ,566,566,566
BEGIN DESCRIPTION:
COTTONWOOD CREEK 151.0
END DESCRIPTION:
XS GIS Cut Line= 2
      3582099.96     10616586.76      3583373.36     10616336.77
#Sta/Elev= 30
  4475.5  428.71  4618.3  418.24  4668.8  413.22  4801.2  403.41  4903.6  401.33
  4964.3  401.51  4984.7  395.43  4998.4  387.15  5001.1  386.65  5004.4  387.15
  5006.5   387.2  5015.3  394.44  5045.8  398.84  5052.8  401.49  5141.2  403.22
  5227.8  402.57  5258.5  401.68  5263.6  402.46  5366.5     403  5402.5  402.22
  5433.1  404.05  5494.2  405.03  5520.8  406.39  5525.9  405.44  5545.2  407.91
  5596.1  408.91  5628.7  412.02  5731.6  415.86  5759.2  418.57  5773.2  418.72
#Mann= 6 ,-1 , 0
  4475.5     .05       0  4618.3     .16       0  4998.4     .07       0
  5004.4     .16       0  5141.2     .05       0  5227.8     .08       0
Bank Sta=4964.3,5052.8
XS Rating Curve= 0 ,0
Exp/Cntr=0.3,0.1

Type RM Length L Ch R = 1 ,110678  ,100,100,100
BEGIN DESCRIPTION:
COTTONWOOD CREEK 150.0
END DESCRIPTION:
XS GIS Cut Line= 2
      3582006.22     10617146.65      3583553.01      10616789.9
#Sta/Elev= 30
  4343.7  422.64  4367.7  423.61  4436.8  418.74  4441.9  421.15  4479.6     418
  4484.7  419.76  4570.3  413.32  4575.4  415.01  4911.6  402.64  4952.7  397.57
  4970.6  393.12  4975.7  394.23  4983.5  389.35  5010.4  383.65  5013.1  383.15
  5016.4  383.65  5018.5   387.9  5024.5  393.11    5045  393.48  5055.3  395.01
  5061.3  398.54  5104.1  399.05  5118.3  396.76  5176.7  396.89  5194.7  398.13
  5199.9  395.72  5209.2  399.55    5394   402.2  5722.4  418.44  5931.1  422.88
#Mann= 5 ,-1 , 0
  4343.7     .08       0  5010.4     .07       0  5016.4     .08       0
  5118.3     .16       0  5176.7     .08       0
Bank Sta=4952.7,5061.3
XS Rating Curve= 0 ,0
Exp/Cntr=0.3,0.1

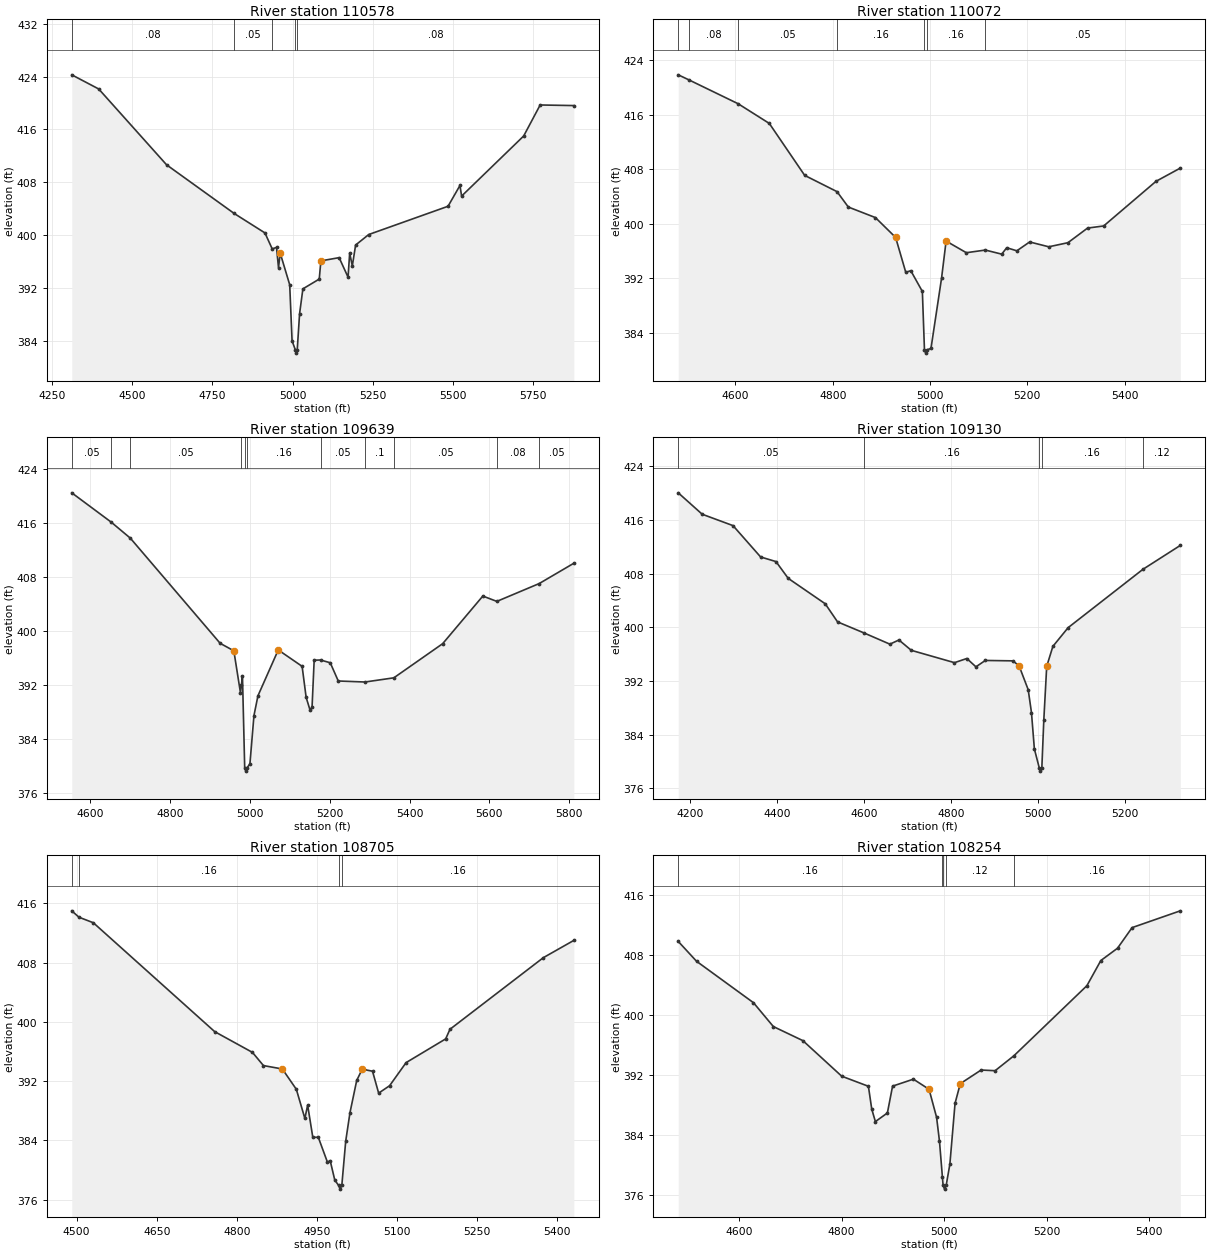
Type RM Length L Ch R = 1 ,110578  ,506,506,506
BEGIN DESCRIPTION:
COTTONWOOD CREEK 149.0
END DESCRIPTION:
XS GIS Cut Line= 2
       3581998.4     10617253.42      3583521.78     10616894.06
#Sta/Elev= 30
  4311.7  424.26  4395.7  422.12  4607.3  410.65  4818.1  403.29  4913.9  400.35
  4936.6  397.93    4950  398.16  4956.2  395.09  4961.4  397.31  4991.1  392.51
  4998.5  384.03  5008.6  382.67  5011.4  382.17  5014.6  382.67  5021.9  388.13
  5032.2  391.89  5083.2  393.37  5088.3  396.12  5145.2  396.61    5173  393.66
  5178.1  397.31  5186.3  395.36  5196.6  398.52  5237.6  400.11  5484.7  404.38
  5521.9  407.53    5527  405.92  5720.5  415.01  5771.9   419.7  5876.9  419.61
#Mann= 5 ,-1 , 0
  4311.7     .08       0  4818.1     .05       0  4936.6     .08       0
  5008.6     .07       0  5014.6     .08       0
Bank Sta=4961.4,5088.3
XS Rating Curve= 0 ,0
Exp/Cntr=0.3,0.1

Type RM Length L Ch R = 1 ,110072  ,433,433,433
BEGIN DESCRIPTION:
COTTONWOOD CREEK 148.0
END DESCRIPTION:
XS GIS Cut Line= 2
      3581989.29     10617370.69      3582983.21     10617648.46
#Sta/Elev= 30
  4482.5  421.88  4504.1  421.15  4605.7  417.63  4669.7  414.74  4742.4  407.11
  4808.9  404.72  4832.1  402.46  4887.8  400.91  4929.3     398  4950.2  392.87
  4960.5  393.11  4984.3  390.06  4988.6   381.5  4991.4     381  4994.6   381.5
    5002  381.69  5023.7  391.98  5033.1  397.46  5074.7  395.75  5113.7  396.14
  5147.4  395.54  5157.7  396.48  5178.5  396.03  5204.8  397.33  5244.1  396.62
  5283.5  397.22  5323.9  399.37    5357  399.68  5464.6  406.24  5514.5  408.18
#Mann= 7 ,-1 , 0
  4482.5     .05       0  4504.1     .08       0  4605.7     .05       0
  4808.9     .16       0  4988.6     .07       0  4994.6     .16       0
  5113.7     .05       0
Bank Sta=4929.3,5033.1
XS Rating Curve= 0 ,0
Exp/Cntr=0.3,0.1

Type RM Length L Ch R = 1 ,109639  ,509,509,509
BEGIN DESCRIPTION:
COTTONWOOD CREEK 147.0
END DESCRIPTION:
XS GIS Cut Line= 3
      3581911.14     10617657.13      3582236.71     10617839.44
      3583116.25     10617939.09
#Sta/Elev= 30
  4553.5  420.45  4652.1  416.12  4700.2  413.74  4925.4  398.16  4959.7  397.05
  4976.3  390.83  4978.7  392.01  4981.3  393.29  4986.9  379.73  4989.7  379.23
  4992.9  379.73    5000  380.31  5010.1  387.46  5020.1  390.39    5071  397.18
  5130.8  394.75  5140.9  390.15  5150.6  388.28  5155.7  388.69    5161  395.66
  5176.9  395.69  5201.3  395.28  5221.4  392.58  5288.5  392.43  5360.7  393.05
  5483.1  398.11  5583.7  405.16  5618.8  404.37  5724.9  407.01  5811.8  410.02
#Mann= 11 ,-1 , 0
  4553.5     .05       0  4652.1     .08       0  4700.2     .05       0
  4978.7     .16       0  4986.9     .07       0  4992.9     .16       0
  5176.9     .05       0  5288.5      .1       0  5360.7     .05       0
  5618.8     .08       0  5724.9     .05       0
Bank Sta=4959.7,5071
XS Rating Curve= 0 ,0
Exp/Cntr=0.3,0.1

Type RM Length L Ch R = 1 ,109130  ,425,425,425
BEGIN DESCRIPTION:
COTTONWOOD CREEK 146.0
END DESCRIPTION:
XS GIS Cut Line= 2
       3581772.3     10617739.61      3582631.68     10618512.19
#Sta/Elev= 30
  4172.2  420.04  4227.3  416.85  4298.3  415.15  4361.8  410.48  4397.2  409.79
  4425.3  407.29  4510.5   403.5  4538.9   400.8  4599.1  399.17  4659.3  397.48
  4680.2   398.1  4708.6  396.56    4808  394.72  4836.4  395.34  4857.4   394.1
    4879  395.05  4942.6  394.99  4956.8  394.23  4977.7  390.69  4985.2  387.29
  4991.9  381.86  5003.1  379.05  5005.9  378.55  5009.1  379.05  5013.6  386.13
  5020.3  394.17  5034.5  397.15  5069.6  399.94  5241.6  408.63  5327.8   412.2
#Mann= 5 ,-1 , 0
  4172.2     .05       0  4599.1     .16       0  5003.1     .07       0
  5009.1     .16       0  5241.6     .12       0
Bank Sta=4956.8,5020.3
XS Rating Curve= 0 ,0
Exp/Cntr=0.3,0.1

Type RM Length L Ch R = 1 ,108705  ,451,451,451
BEGIN DESCRIPTION:
COTTONWOOD CREEK 145.0
END DESCRIPTION:
XS GIS Cut Line= 2
      3581570.31     10618414.38      3582485.37     10618631.22
#Sta/Elev= 30
  4490.8  414.99  4504.2  414.13  4531.2  413.38  4758.5  398.68  4829.2  395.88
  4849.8   394.1  4885.2  393.64  4911.4   390.9  4927.4  386.96  4932.6  388.76
  4942.3   384.4  4952.5  384.43  4969.7  381.05  4974.8  381.27  4983.4  378.65
  4990.6  377.92  4993.4  377.42  4996.6  377.92  5003.9   383.9  5011.9  387.75
  5024.5  392.09  5034.8  393.61  5054.1  393.34  5065.6  390.38  5086.1  391.38
    5117   394.5  5191.1   397.7  5199.2     399  5373.9  408.66  5431.2     411
#Mann= 4 ,-1 , 0
  4490.8     .05       0  4504.2     .16       0  4990.6     .07       0
  4996.6     .16       0
Bank Sta=4885.2,5034.8
XS Rating Curve= 0 ,0
Exp/Cntr=0.3,0.1

Type RM Length L Ch R = 1 ,108254  ,613,613,613
BEGIN DESCRIPTION:
COTTONWOOD CREEK 144.0
END DESCRIPTION:
XS GIS Cut Line= 3
      3581583.38      10618748.6      3581913.21     10618917.85
      3582512.19     10618813.68
#Sta/Elev= 30
  4481.6  409.87  4517.3  407.22  4628.3  401.69    4667  398.51  4724.6  396.63
  4800.2  391.89  4852.3  390.54  4858.8   387.5  4865.9  385.83  4889.3  386.98
  4899.4  390.56    4940  391.49  4970.5  390.14  4985.2   386.4  4990.8  383.24
  4996.6   378.4  4997.9  377.32  5000.7  376.82  5003.9  377.32  5011.1  380.15
  5021.2  388.27  5031.4  390.89    5072  392.71  5099.3  392.62  5135.9  394.61
  5278.2  403.96  5305.4  407.32  5337.9  408.96  5366.3  411.71  5460.3  413.95
#Mann= 5 ,-1 , 0
  4481.6     .16       0  4996.6     .12       0  4997.9     .07       0
  5003.9     .12       0  5135.9     .16       0
Bank Sta=4970.5,5031.4
XS Rating Curve= 0 ,0
Exp/Cntr=0.3,0.1

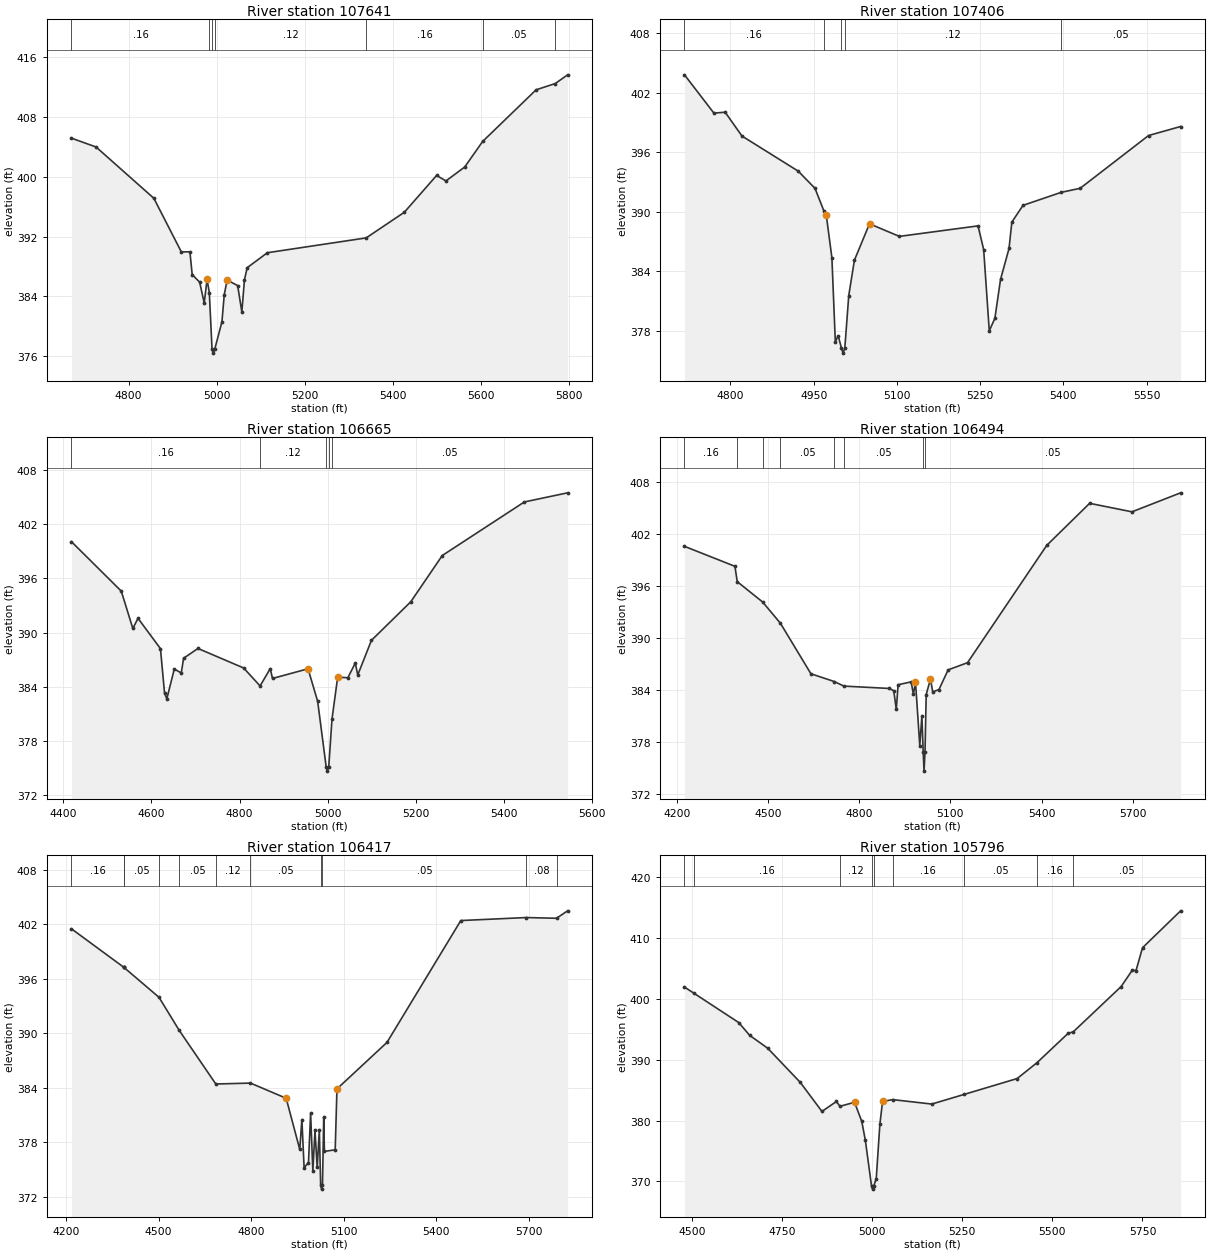
Type RM Length L Ch R = 1 ,107641  ,235,235,235
BEGIN DESCRIPTION:
COTTONWOOD CREEK 143.0
END DESCRIPTION:
XS GIS Cut Line= 3
      3581599.61     10619310.19      3581949.61     10619410.19
      3582599.59      10619010.2
#Sta/Elev= 30
  4670.1  405.14    4726  403.96  4857.3  397.11  4919.7  389.95  4939.2  389.96
  4944.4  386.92  4961.3  385.91  4971.7  383.13  4978.2  386.28  4983.3  384.51
  4989.5  376.93  4992.2  376.43  4995.5  376.93    5012  380.62  5017.2  384.22
  5023.7  386.19  5047.7  385.45  5057.2  381.93  5063.1  386.21  5069.3  387.84
  5115.2  389.84  5339.7  391.82  5426.3  395.24  5499.7  400.16    5521  399.43
  5563.6  401.29  5604.3   404.7  5725.8   411.6  5769.5  412.44  5797.3   413.6
#Mann= 7 ,-1 , 0
  4670.1     .16       0  4983.3     .12       0  4989.5     .07       0
  4995.5     .12       0  5339.7     .16       0  5604.3     .05       0
  5769.5     .16       0
Bank Sta=4978.2,5023.7
XS Rating Curve= 0 ,0
Exp/Cntr=0.3,0.1

Type RM Length L Ch R = 1 ,107406  ,741,741,741
BEGIN DESCRIPTION:
COTTONWOOD CREEK 142.0
END DESCRIPTION:
XS GIS Cut Line= 2
       3581547.3     10619541.47      3582430.05     10619684.69
#Sta/Elev= 30
  4717.1  403.82  4770.1  399.96  4790.4  400.05  4820.7  397.65  4922.1  394.11
  4952.4  392.37  4968.2  390.12  4972.7  389.66  4982.8  385.38    4989  376.89
  4994.1  377.52  5000.1  376.26  5002.9  375.76  5006.1  376.26  5013.2  381.57
  5023.4  385.13  5050.6   388.8  5104.4  387.53  5246.2  388.59  5256.4   386.2
  5266.5  378.01  5276.6  379.27  5286.8  383.19  5302.1  386.31  5307.2  388.97
  5327.3  390.66  5396.1  391.97  5430.4  392.38  5553.6   397.7  5611.4  398.61
#Mann= 5 ,-1 , 0
  4717.1     .16       0  4968.2     .12       0  5000.1     .07       0
  5006.1     .12       0  5396.1     .05       0
Bank Sta=4972.7,5050.6
XS Rating Curve= 0 ,0
Exp/Cntr=0.3,0.1

Type RM Length L Ch R = 1 ,106665  ,179,179,179
BEGIN DESCRIPTION:
COTTONWOOD CREEK 141.0
END DESCRIPTION:
XS GIS Cut Line= 4
      3581586.31     10619872.19      3582088.92     10620025.84
      3582187.88     10619981.57       3582622.8     10619749.79
#Sta/Elev= 30
  4418.3  400.06  4531.4  394.59  4557.7  390.45  4569.4  391.58  4620.4  388.22
  4629.7   383.3  4634.9  382.66  4651.8  385.96  4667.7  385.53    4673  387.16
  4705.7  388.24  4809.3  386.08  4846.7  384.09  4869.7  386.01  4874.9  384.92
  4955.6  385.99  4977.5  382.38  4996.7  375.16  4999.4  374.66  5002.7  375.16
    5010  380.42  5022.9  385.06  5046.1     385  5062.9  386.63  5068.5   385.3
  5099.6  389.14    5189  393.41  5260.5  398.53  5446.9  404.46  5545.1  405.47
#Mann= 5 ,-1 , 0
  4418.3     .16       0  4846.7     .12       0  4996.7     .07       0
  5002.7     .12       0    5010     .05       0
Bank Sta=4955.6,5022.9
XS Rating Curve= 0 ,0
Exp/Cntr=0.3,0.1

Type RM Length L Ch R = 1 ,106494  ,58,58,58
BEGIN DESCRIPTION:
COTTONWOOD CREEK 140.0
END DESCRIPTION:
XS GIS Cut Line= 6
       3581612.4     10620648.23      3581781.63      10620624.8
      3582107.15     10620205.53      3582260.79     10620072.72
      3582531.63      10619934.7       3582934.9     10619830.59
#Sta/Elev= 30
  4225.4  400.58  4391.3  398.28  4398.9  396.51  4482.6  394.16    4541  391.71
  4641.3  385.89  4717.8     385  4749.8  384.47  4899.2   384.2  4913.7  383.94
    4922   381.8    4928  384.63    4971  384.96  4978.3  383.52  4985.2  384.96
  4999.3  377.61  5006.2  381.04  5010.5  376.89  5013.3  374.67  5016.5  376.89
  5020.4  383.49  5034.5   385.3  5041.8   383.8  5062.3  384.07  5092.5  386.34
  5156.3  387.17  5416.8  400.69    5558  405.54  5697.2  404.56  5857.2  406.75
#Mann= 8 ,-1 , 0
  4225.4     .16       0  4398.9     .05       0  4482.6     .08       0
    4541     .05       0  4717.8     .16       0  4749.8     .05       0
  5010.5    .035       0  5016.5     .05       0
Bank Sta=4985.2,5034.5
XS Rating Curve= 0 ,0
Exp/Cntr=0.3,0.1

Type RM Length L Ch R = 1 ,106417  ,632,632,632
BEGIN DESCRIPTION:
Mapping XS 994855a3
END DESCRIPTION:
XS GIS Cut Line= 6
      3581614.93     10620689.91      3581846.73     10620640.42
      3581922.25     10620580.53      3582130.59     10620244.59
      3582409.23     10620051.88      3582930.06     10619932.09
#Sta/Elev= 30
  4217.7  401.51  4386.4   397.3  4387.4  397.27  4387.5  397.27  4501.5  393.97
  4566.8  390.34  4685.6  384.43    4798  384.53  4913.7  382.86  4957.7  377.23
  4964.6  380.52  4971.8  375.23    4986  375.77  4992.9   381.2  5000.1  374.89
  5007.1  379.32  5014.3  375.25  5021.2   379.4  5025.4  373.36  5028.2  372.86
  5031.4  373.36  5035.4  380.81  5037.6  377.01  5072.6  377.19  5078.3  383.89
  5240.5  389.01  5479.8  402.42  5691.7  402.75  5790.1  402.67  5825.9  403.49
#Mann= 12 ,-1 , 0
  4217.7     .16       0  4386.4     .12       0  4387.4     .16       0
  4387.5     .05       0  4501.5      .1       0  4566.8     .05       0
  4685.6     .12       0    4798     .05       0  5025.4    .035       0
  5031.4     .05       0  5691.7     .08       0  5790.1     .05       0
Bank Sta=4913.7,5078.3
XS Rating Curve= 0 ,0
Exp/Cntr=0.3,0.1

Type RM Length L Ch R = 1 ,105796  ,531,531,531
BEGIN DESCRIPTION:
COTTONWOOD CREEK 139.0
END DESCRIPTION:
XS GIS Cut Line= 3
      3581699.64     10620760.19      3582249.61     10620810.19
      3583049.65      10621010.2
#Sta/Elev= 30
  4478.9  401.92  4505.3   400.9  4629.5  396.09  4659.6     394  4709.8  391.88
  4800.2  386.27  4860.4   381.5  4900.6  383.13  4910.3  382.34  4950.8     383
  4970.9  379.86  4980.9  376.74    4998  369.24  5000.8  368.74    5004  369.24
  5011.1  370.48  5021.1  379.36  5028.6  383.13  5056.6  383.44  5165.1  382.71
  5254.8  384.29  5402.2   386.9  5456.8  389.48  5543.9  394.34  5557.7  394.56
  5690.8  402.01  5721.8   404.7  5732.1  404.64  5750.1  408.38  5855.8  414.44
#Mann= 9 ,-1 , 0
  4478.9     .12       0  4505.3     .16       0  4910.3     .12       0
    4998     .07       0    5004     .12       0  5056.6     .16       0
  5254.8     .05       0  5456.8     .16       0  5557.7     .05       0
Bank Sta=4950.8,5028.6
XS Rating Curve= 0 ,0
Exp/Cntr=0.3,0.1