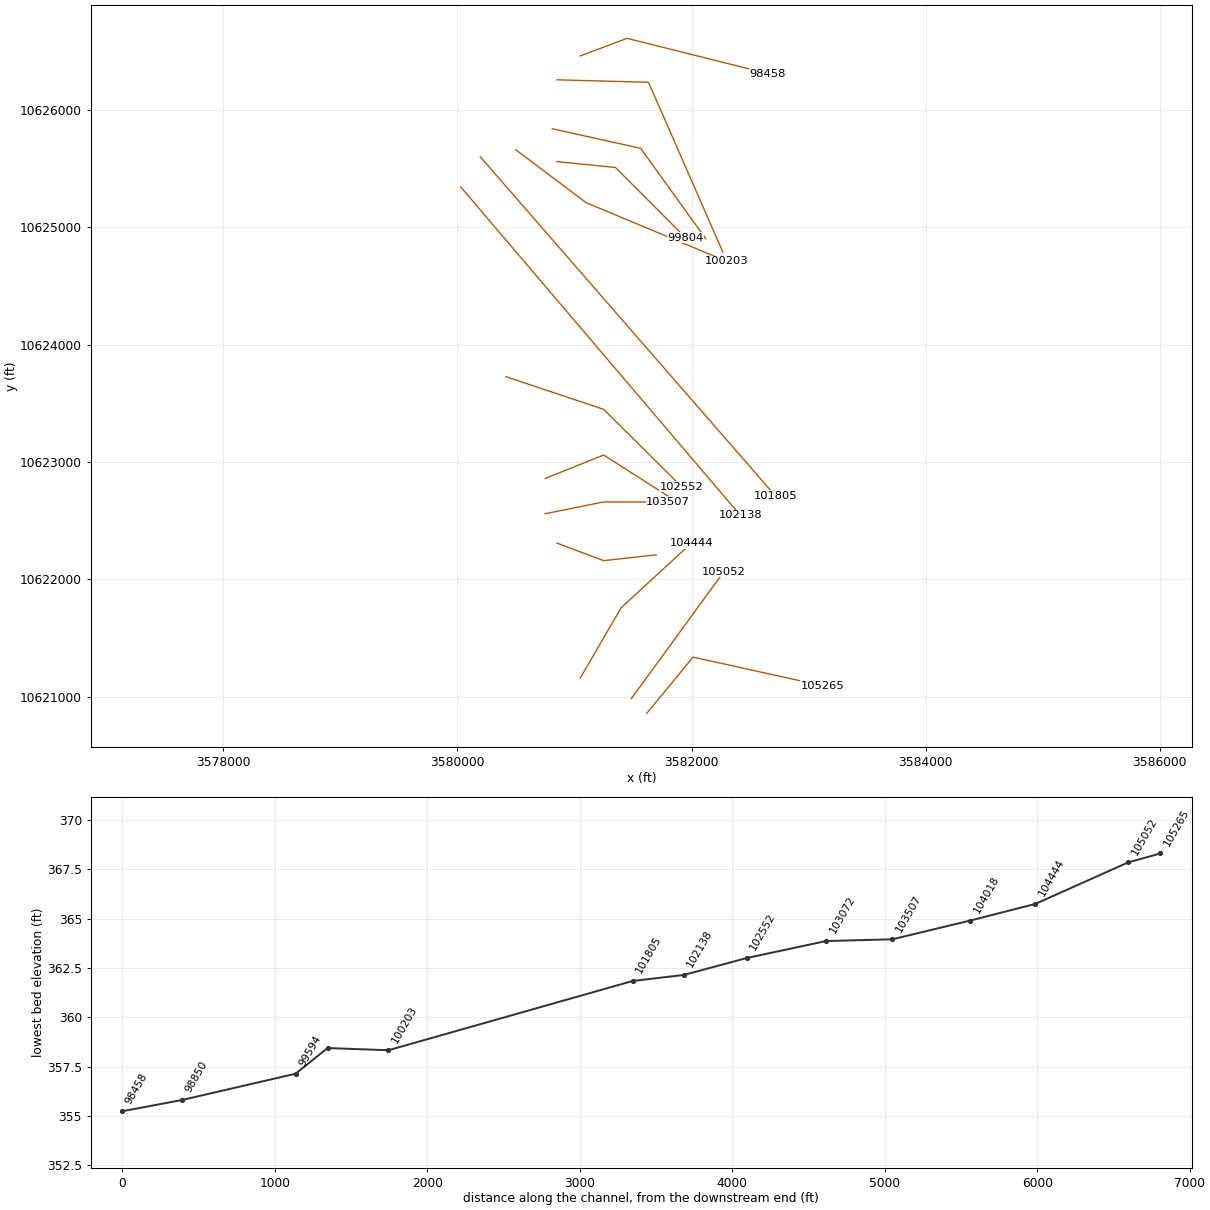
HEC-RAS study COTTONWOOD CREEK.prj: COTTONWOOD CREEK Base Level Engineering

--- COTTONWOOD CREEK.g01 (geometry) --- (continued)

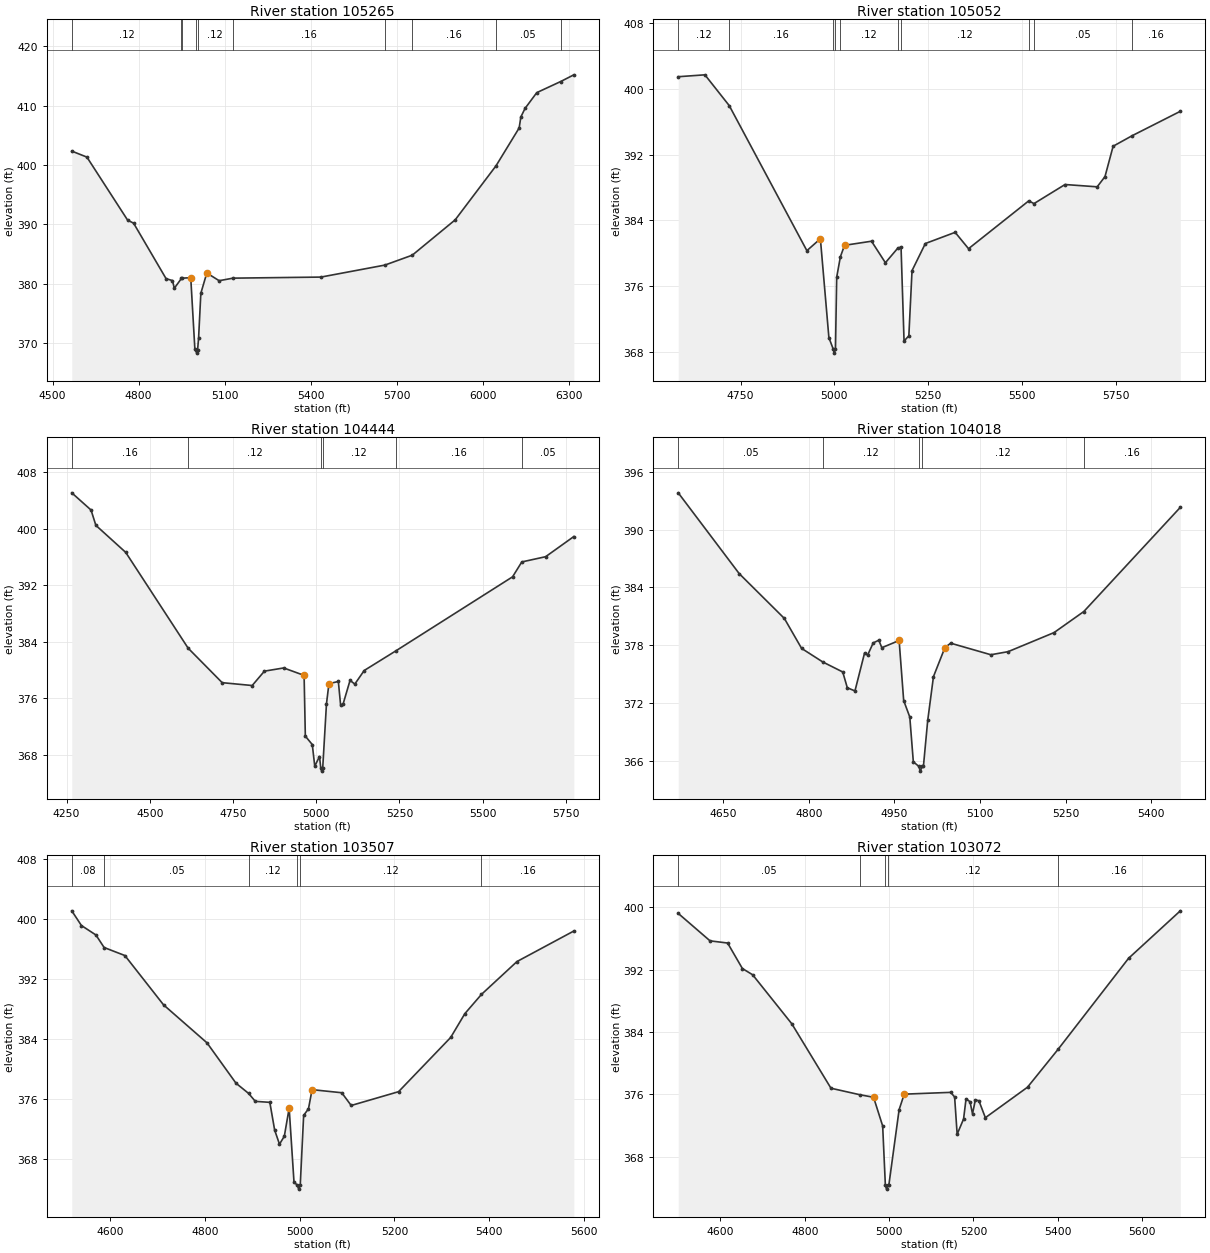
Type RM Length L Ch R = 1 ,105265  ,213,213,213
BEGIN DESCRIPTION:
COTTONWOOD CREEK 138.0
END DESCRIPTION:
XS GIS Cut Line= 3
      3581617.16     10620859.17      3582013.03     10621338.37
      3583115.86     10621095.61
#Sta/Elev= 30
  4567.1  402.33  4619.9  401.32  4761.9   390.7  4782.7  390.19    4896  380.84
  4918.2  380.52  4924.7  379.23  4949.7  380.89  4950.5  380.92    4982  381.01
  4996.4  368.95  4999.8   368.8  5002.6   368.3  5005.8   368.8  5009.4  370.89
  5017.2  378.38    5038   381.8    5081   380.5  5129.4  380.93    5436  381.11
  5658.9  383.13  5754.5   384.8  5904.1  390.75  6046.6  399.86  6127.2  406.23
  6133.1  408.08  6147.7  409.52  6188.6  412.18  6271.5  414.04  6317.9  415.18
#Mann= 10 ,-1 , 0
  4567.1     .12       0  4949.7     .16       0  4950.5     .12       0
  4999.8     .07       0  5005.8     .12       0  5129.4     .16       0
  5658.9     .05       0  5754.5     .16       0  6046.6     .05       0
  6271.5     .16       0
Bank Sta=4982,5038
XS Rating Curve= 0 ,0
Exp/Cntr=0.3,0.1

Type RM Length L Ch R = 1 ,105052  ,608,608,608
BEGIN DESCRIPTION:
COTTONWOOD CREEK 137.0
END DESCRIPTION:
XS GIS Cut Line= 2
      3581485.28     10620984.24       3582274.9     10622064.77
#Sta/Elev= 30
  4583.8  401.48  4654.9  401.71  4719.8  397.96  4926.7  380.31  4962.7  381.76
  4985.4  369.72  4996.9  368.34  4999.6  367.84  5002.9  368.34  5006.2  377.09
  5016.1  379.58  5027.1  380.96    5099  381.46    5136  378.84  5168.7   380.6
  5177.7  380.76  5185.7  369.31  5198.5  369.95    5207  377.88  5242.5  381.18
  5321.9  382.54  5357.6  380.55  5518.1  386.37  5532.1  386.04  5614.8  388.36
  5700.5  388.08  5721.3  389.32    5743  393.02  5793.7   394.3  5922.1  397.27
#Mann= 10 ,-1 , 0
  4583.8     .12       0  4719.8     .16       0  4996.9     .07       0
  5002.9     .16       0  5016.1     .12       0  5168.7     .16       0
  5177.7     .12       0  5518.1     .07       0  5532.1     .05       0
  5793.7     .16       0
Bank Sta=4962.7,5027.1
XS Rating Curve= 0 ,0
Exp/Cntr=0.3,0.1

Type RM Length L Ch R = 1 ,104444  ,426,426,426
BEGIN DESCRIPTION:
COTTONWOOD CREEK 136.0
END DESCRIPTION:
XS GIS Cut Line= 3
      3581049.59     10621160.15      3581399.61     10621760.19
      3581999.61     10622310.19
#Sta/Elev= 30
  4265.5  405.04  4323.4  402.61  4337.9  400.45  4427.6  396.63  4615.2   383.1
  4717.5  378.23  4807.6  377.83  4844.4  379.86  4902.3  380.31  4963.6  379.26
  4967.3  370.68  4988.2  369.49  4995.6  366.44  5009.8   367.8  5013.6  366.24
  5016.3  365.74  5019.6  366.24  5030.8  375.24  5038.2  378.09  5066.5   378.4
  5073.3  375.08  5080.7  375.21  5101.7  378.56  5115.9  378.03  5144.2  379.95
  5238.5   382.7    5590  393.18  5617.7  395.28  5689.3  396.02  5774.1  398.87
#Mann= 6 ,-1 , 0
  4265.5     .16       0  4615.2     .12       0  5013.6     .07       0
  5019.6     .12       0  5238.5     .16       0  5617.7     .05       0
Bank Sta=4963.6,5038.2
XS Rating Curve= 0 ,0
Exp/Cntr=0.3,0.1

Type RM Length L Ch R = 1 ,104018  ,511,511,511
BEGIN DESCRIPTION:
COTTONWOOD CREEK 135.0
END DESCRIPTION:
XS GIS Cut Line= 3
      3580849.65     10622310.17      3581249.61     10622160.19
      3581699.58     10622210.19
#Sta/Elev= 30
  4571.2  393.81    4678  385.42  4757.2  380.76  4787.4  377.65  4824.5  376.24
  4859.5   375.2  4867.5  373.56  4880.9  373.23  4897.8  377.18  4903.1  376.95
  4912.9  378.22  4922.7   378.5    4928  377.72  4958.3  378.47  4966.3  372.23
    4977  370.52  4983.2  365.87  4992.7   365.4  4995.4   364.9  4998.7   365.4
  5000.9   365.4  5008.4  370.16  5018.5  374.72  5038.6  377.74  5048.7  378.19
  5119.1  376.99  5149.3  377.31  5229.8  379.29    5282  381.48  5451.1   392.3
#Mann= 5 ,-1 , 0
  4571.2     .05       0  4824.5     .12       0  4992.7     .07       0
  4998.7     .12       0    5282     .16       0
Bank Sta=4958.3,5038.6
XS Rating Curve= 0 ,0
Exp/Cntr=0.3,0.1

Type RM Length L Ch R = 1 ,103507  ,435,435,435
BEGIN DESCRIPTION:
COTTONWOOD CREEK 134.0
END DESCRIPTION:
XS GIS Cut Line= 3
      3580749.64      10622560.2      3581249.61     10622660.19
      3581799.64     10622660.19
#Sta/Elev= 30
  4518.8  401.05  4539.2  399.09  4569.8  397.83  4587.1  396.16  4630.9  395.09
  4712.5  388.52  4804.3  383.45  4865.5  378.07  4892.1  376.71  4906.3  375.65
  4936.9  375.52  4947.1  371.82  4957.3  369.94  4967.5     371  4977.7  374.74
  4987.9  364.92  4995.1  364.45  4997.8  363.95  5001.1  364.45  5008.3  373.78
  5018.5  374.66  5026.1  377.21  5088.7   376.8  5108.7   375.1  5208.7  376.94
  5318.7  384.17  5348.7  387.35  5383.7  389.91  5458.7  394.29  5578.7  398.36
#Mann= 6 ,-1 , 0
  4518.8     .08       0  4587.1     .05       0  4892.1     .12       0
  4995.1     .07       0  5001.1     .12       0  5383.7     .16       0
Bank Sta=4977.7,5026.1
XS Rating Curve= 0 ,0
Exp/Cntr=0.3,0.1

Type RM Length L Ch R = 1 ,103072  ,520,520,520
BEGIN DESCRIPTION:
COTTONWOOD CREEK 133.0
END DESCRIPTION:
XS GIS Cut Line= 3
      3580749.61     10622860.19      3581249.61     10623060.19
      3581799.58     10622710.21
#Sta/Elev= 30
    4500  399.22  4575.4   395.7  4617.1  395.42  4652.1  392.15  4676.4  391.35
  4769.3  385.06  4862.1   376.8  4930.2  375.97  4963.1  375.64  4984.7  371.96
  4991.1  364.36  4993.8  363.86  4997.1  364.36  4999.5  364.43  5023.7  374.05
  5035.8  376.04    5146  376.27  5155.3  375.68  5161.3   370.9  5176.5  372.85
  5182.4  375.44  5191.8  375.07  5197.7  373.52  5204.5  375.31  5212.9  375.19
  5228.2  373.02  5328.1  376.93  5400.9  381.81  5567.7  393.46  5690.4  399.55
#Mann= 5 ,-1 , 0
    4500     .05       0  4930.2     .12       0  4991.1     .07       0
  4997.1     .12       0  5400.9     .16       0
Bank Sta=4963.1,5035.8
XS Rating Curve= 0 ,0
Exp/Cntr=0.3,0.1

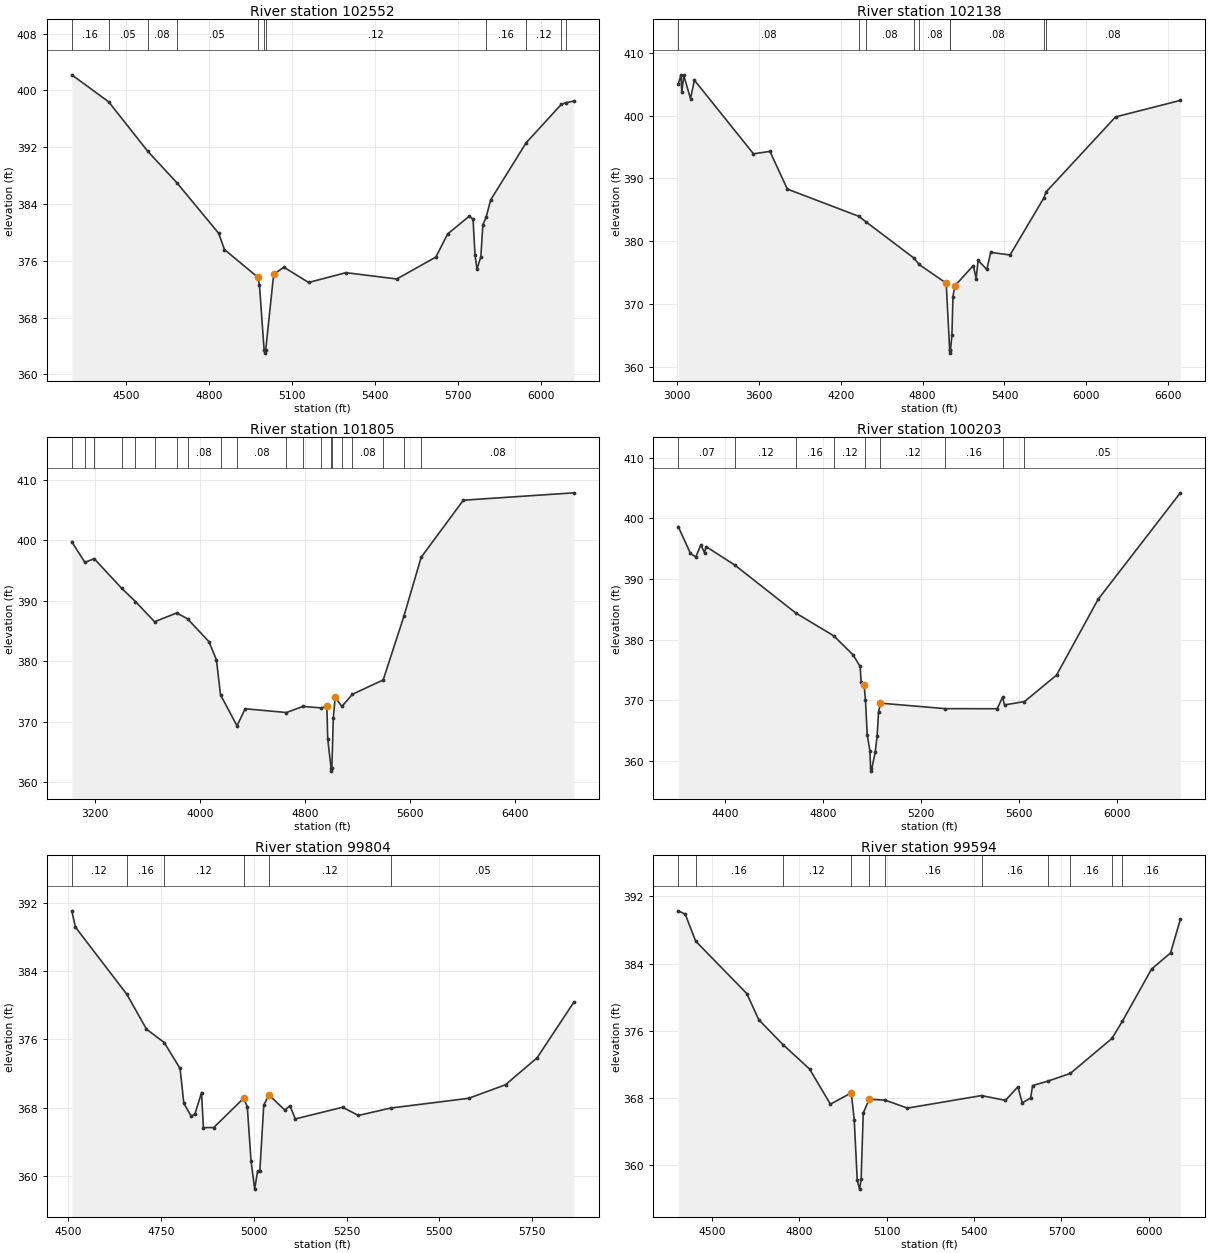
Type RM Length L Ch R = 1 ,102552  ,414,414,414
BEGIN DESCRIPTION:
COTTONWOOD CREEK 132.0
END DESCRIPTION:
XS GIS Cut Line= 3
      3580415.78     10623727.27      3581249.14     10623449.48
       3581915.2     10622790.36
#Sta/Elev= 30
  4304.7  402.19  4438.1  398.39  4578.7  391.46  4684.4  387.01  4835.8  379.88
  4856.9  377.58  4977.4  373.69  4983.4  372.59  5000.1   363.5  5002.8     363
  5006.1   363.5  5034.7  374.08  5071.6   375.1  5161.2  372.95  5296.1  374.33
  5479.9  373.44  5621.4  376.53  5663.8  379.78  5741.6  382.27  5755.7  381.87
  5762.8  376.86  5769.9  374.83    5784   376.6  5791.1  381.06  5802.9  382.11
  5819.4  384.58  5947.7  392.62  6074.8  398.03  6092.5  398.27  6120.2   398.5
#Mann= 11 ,-1 , 0
  4304.7     .16       0  4438.1     .05       0  4578.7     .08       0
  4684.4     .05       0  4977.4     .12       0  5000.1     .07       0
  5006.1     .12       0  5802.9     .16       0  5947.7     .12       0
  6074.8     .16       0  6092.5     .12       0
Bank Sta=4977.4,5034.7
XS Rating Curve= 0 ,0
Exp/Cntr=0.3,0.1

Type RM Length L Ch R = 1 ,102138  ,333,333,333
BEGIN DESCRIPTION:
COTTONWOOD CREEK 131.0
END DESCRIPTION:
XS GIS Cut Line= 2
      3580027.65     10625345.28       3582415.6     10622547.76
#Sta/Elev= 30
    3010  405.01  3029.7  406.52  3036.3  403.72  3050.5  406.42  3099.9  402.73
  3128.5  405.67  3561.1  393.93  3681.8  394.31  3809.2   388.3  4330.7  383.98
  4385.2  383.08  4738.9  377.26  4774.2  376.28    4973   373.3  4998.5  362.64
  5001.3  362.14  5004.5  362.64  5015.1   365.1  5022.4  371.15  5036.7  372.87
  5171.7  376.11  5192.6  374.03  5206.8  376.94  5270.5  375.48  5299.1  378.21
  5440.7  377.79  5688.5  386.89  5705.2  387.85  6213.6  399.81  6688.1  402.44
#Mann= 9 ,-1 , 0
    3010     .08       0  4330.7     .05       0  4385.2     .08       0
  4738.9     .05       0  4774.2     .08       0  4998.5     .07       0
  5004.5     .08       0  5688.5     .12       0  5705.2     .08       0
Bank Sta=4973,5036.7
XS Rating Curve= 0 ,0
Exp/Cntr=0.3,0.1

Type RM Length L Ch R = 1 ,101805  ,1602,1602,1602
BEGIN DESCRIPTION:
COTTONWOOD CREEK 130.0
END DESCRIPTION:
XS GIS Cut Line= 2
      3580194.31     10625602.23       3582714.1     10622714.54
#Sta/Elev= 30
  3020.3  399.76  3120.3  396.36  3191.5  396.96  3400.7  392.08  3506.7  389.87
  3652.4  386.54  3821.8  387.99  3904.1  387.02  4067.5  383.24  4124.5  380.24
  4155.8  374.45  4281.6  369.33  4343.8  372.15  4659.2  371.53    4785  372.54
  4924.8  372.29  4967.5  372.55  4974.1  367.15  4999.6  362.34  5002.3  361.84
  5005.6  362.34  5016.8  370.69  5031.1  374.03  5082.3  372.53  5162.5  374.55
  5397.4  376.91    5555  387.41  5687.2  397.19  6009.2  406.63  6852.8  407.85
#Mann= 20 ,-1 , 0
  3020.3     .12       0  3120.3     .08       0  3191.5     .16       0
  3400.7     .08       0  3506.7     .16       0  3652.4     .08       0
  3821.8     .12       0  3904.1     .08       0  4155.8     .05       0
  4281.6     .08       0  4659.2     .05       0    4785     .05       0
  4924.8     .05       0  4999.6     .03       0  5005.6     .05       0
  5082.3     .05       0  5162.5     .08       0  5397.4     .16       0
    5555     .16       0  5687.2     .08       0
Bank Sta=4967.5,5031.1
XS Rating Curve= 0 ,0
Exp/Cntr=0.3,0.1

Type RM Length L Ch R = 1 ,100203  ,399,399,399
BEGIN DESCRIPTION:
COTTONWOOD CREEK 127.0
END DESCRIPTION:
XS GIS Cut Line= 3
      3580499.64     10625660.17      3581099.61     10625210.19
      3582299.64     10624710.17
#Sta/Elev= 30
  4207.6  398.64  4257.6  394.22  4279.4  393.65  4300.3  395.66  4314.9  394.31
  4321.1  395.36  4439.3  392.29  4688.4  384.38  4841.8  380.66  4921.1  377.52
  4950.3   375.6  4954.4  373.01  4966.8  372.47  4972.2  370.01  4979.2  364.31
  4990.1   361.7    4993  358.83  4995.8  358.33  5011.7  361.43  5019.9   364.2
  5025.3  368.05  5033.4  369.54  5298.5  368.63  5510.1  368.62  5531.7  370.53
  5539.9  369.25  5621.3   369.8  5752.2  374.16  5921.7  386.64  6257.6  404.22
#Mann= 9 ,-1 , 0
  4207.6     .07       0  4439.3     .12       0  4688.4     .16       0
  4841.8     .12       0  4972.2      .1       0  5033.4     .12       0
  5298.5     .16       0  5531.7     .16       0  5621.3     .05       0
Bank Sta=4966.8,5033.4
XS Rating Curve= 0 ,0
Exp/Cntr=0.3,0.1

Type RM Length L Ch R = 1 ,99804   ,210,210,210
BEGIN DESCRIPTION:
COTTONWOOD CREEK 126.0
END DESCRIPTION:
XS GIS Cut Line= 3
      3580849.64     10625560.19      3581349.61     10625510.19
      3581949.62     10624910.18
#Sta/Elev= 30
  4510.7  391.07  4520.7  389.15  4658.9  381.28  4711.7   377.2  4759.4  375.63
  4802.1  372.59  4812.2  368.52  4832.3  366.96  4842.3  367.28  4859.9  369.76
  4864.9  365.65  4892.6  365.66    4973  369.09    4983  368.11  4993.1  361.74
  5002.9  358.44  5010.6  360.52  5016.7  360.52  5027.3  368.29  5041.4  369.49
  5083.9  367.71    5098  368.21  5112.2  366.67  5239.4  368.04  5281.9  367.08
  5369.3  367.95  5578.8  369.09  5677.8  370.68  5762.7  373.83  5861.7  380.36
#Mann= 6 ,-1 , 0
  4510.7     .12       0  4658.9     .16       0  4759.4     .12       0
    4973      .1       0  5041.4     .12       0  5369.3     .05       0
Bank Sta=4973,5041.4
XS Rating Curve= 0 ,0
Exp/Cntr=0.3,0.1

Type RM Length L Ch R = 1 ,99594   ,744,744,744
BEGIN DESCRIPTION:
COTTONWOOD CREEK 125.0
END DESCRIPTION:
XS GIS Cut Line= 3
      3580809.73       10625840.      3581564.97     10625673.32
      3582121.26     10624903.87
#Sta/Elev= 30
    4385  390.28  4408.9  389.89  4444.9  386.67  4620.4  380.42  4661.4  377.31
  4744.4  374.35  4835.5  371.45  4907.2  367.26  4978.8   368.6  4989.1  365.34
  4999.3  358.18  5007.2  357.14  5012.6  358.32  5019.8   366.2  5040.3  367.84
  5094.6  367.74  5171.7  366.79  5425.7  368.28  5507.8  367.71  5550.7  369.33
  5565.4  367.41  5594.2  367.99    5601  369.47  5652.6  369.99  5730.5  370.92
  5873.2  375.08    5909  377.13  6009.4  383.35  6074.4  385.27  6107.9  389.25
#Mann= 11 ,-1 , 0
    4385     .12       0  4444.9     .16       0  4744.4     .12       0
  4978.8      .1       0  5040.3     .12       0  5094.6     .16       0
  5425.7     .16       0  5652.6      .1       0  5730.5     .16       0
  5873.2     .05       0    5909     .16       0
#XS Ineff= 1 ,-1
 5548.86 5611.36  369.22
Permanent Ineff=
       F
Bank Sta=4978.8,5040.3
XS Rating Curve= 0 ,0
Exp/Cntr=0.3,0.1

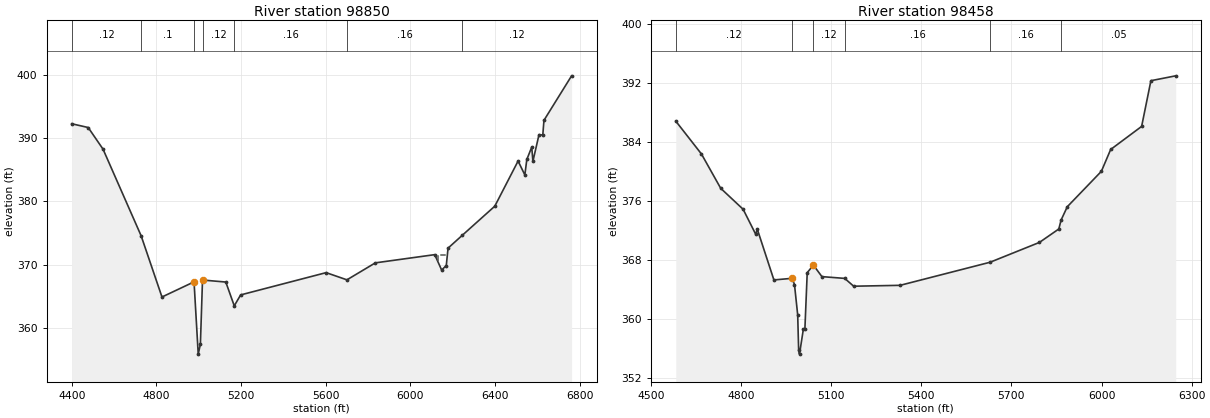
Type RM Length L Ch R = 1 ,98850   ,392,392,392
BEGIN DESCRIPTION:
COTTONWOOD CREEK 124.0
END DESCRIPTION:
XS GIS Cut Line= 3
       3580851.4     10626256.66      3581632.68     10626235.82
      3582268.11     10624787.87
#Sta/Elev= 30
  4399.7  392.31  4477.9  391.71    4548  388.28    4728  374.56  4826.5  364.86
  4978.1  367.26  4997.9  355.81  5008.1  357.37  5018.1  367.55  5128.2  367.23
  5168.2  363.46  5198.3  365.19  5602.4  368.72  5700.7  367.58  5835.1  370.27
  6115.7  371.57  6148.4  369.13  6170.3  369.85  6178.6   372.6  6246.7  374.66
  6399.6  379.25  6509.6   386.4  6541.6   384.2  6550.9  386.65  6574.2  388.61
  6579.7  386.36  6608.5  390.58  6626.4  390.52  6631.9  392.85  6762.5   399.9
#Mann= 7 ,-1 , 0
  4399.7     .12       0    4728      .1       0  4978.1      .1       0
  5018.1     .12       0  5168.2     .16       0  5700.7     .16       0
  6246.7     .12       0
#XS Ineff= 1 ,-1
 6129.22 6180.46  371.51
Permanent Ineff=
       F
Bank Sta=4978.1,5018.1
XS Rating Curve= 0 ,0
Exp/Cntr=0.3,0.1

Type RM Length L Ch R = 1 ,98458   ,449,449,449
BEGIN DESCRIPTION:
COTTONWOOD CREEK 123.0
END DESCRIPTION:
XS GIS Cut Line= 3
      3581049.57     10626460.17      3581449.61     10626610.19
      3582649.63     10626310.18
#Sta/Elev= 30
  4582.7  386.84  4668.2  382.38  4732.3  377.73    4807  374.88  4848.9  371.49
  4854.2  372.17  4909.4   365.3  4969.9  365.52  4977.9  364.68  4988.6  360.55
  4991.8  355.74  4994.6  355.24  5007.3  358.59  5012.5  358.59  5020.3  366.29
  5040.9  367.31  5069.2  365.75  5145.1  365.51  5174.9  364.45  5329.5  364.57
    5629   367.7  5793.3  370.39  5857.8  372.21  5865.5  373.43  5886.1  375.23
  5999.5  380.03  6030.4  382.99  6133.5  386.12  6164.4  392.32  6246.9  392.98
#Mann= 6 ,-1 , 0
  4582.7     .12       0  4969.9      .1       0  5040.9     .12       0
  5145.1     .16       0    5629     .16       0  5865.5     .05       0
Bank Sta=4969.9,5040.9
XS Rating Curve= 0 ,0
Exp/Cntr=0.3,0.1