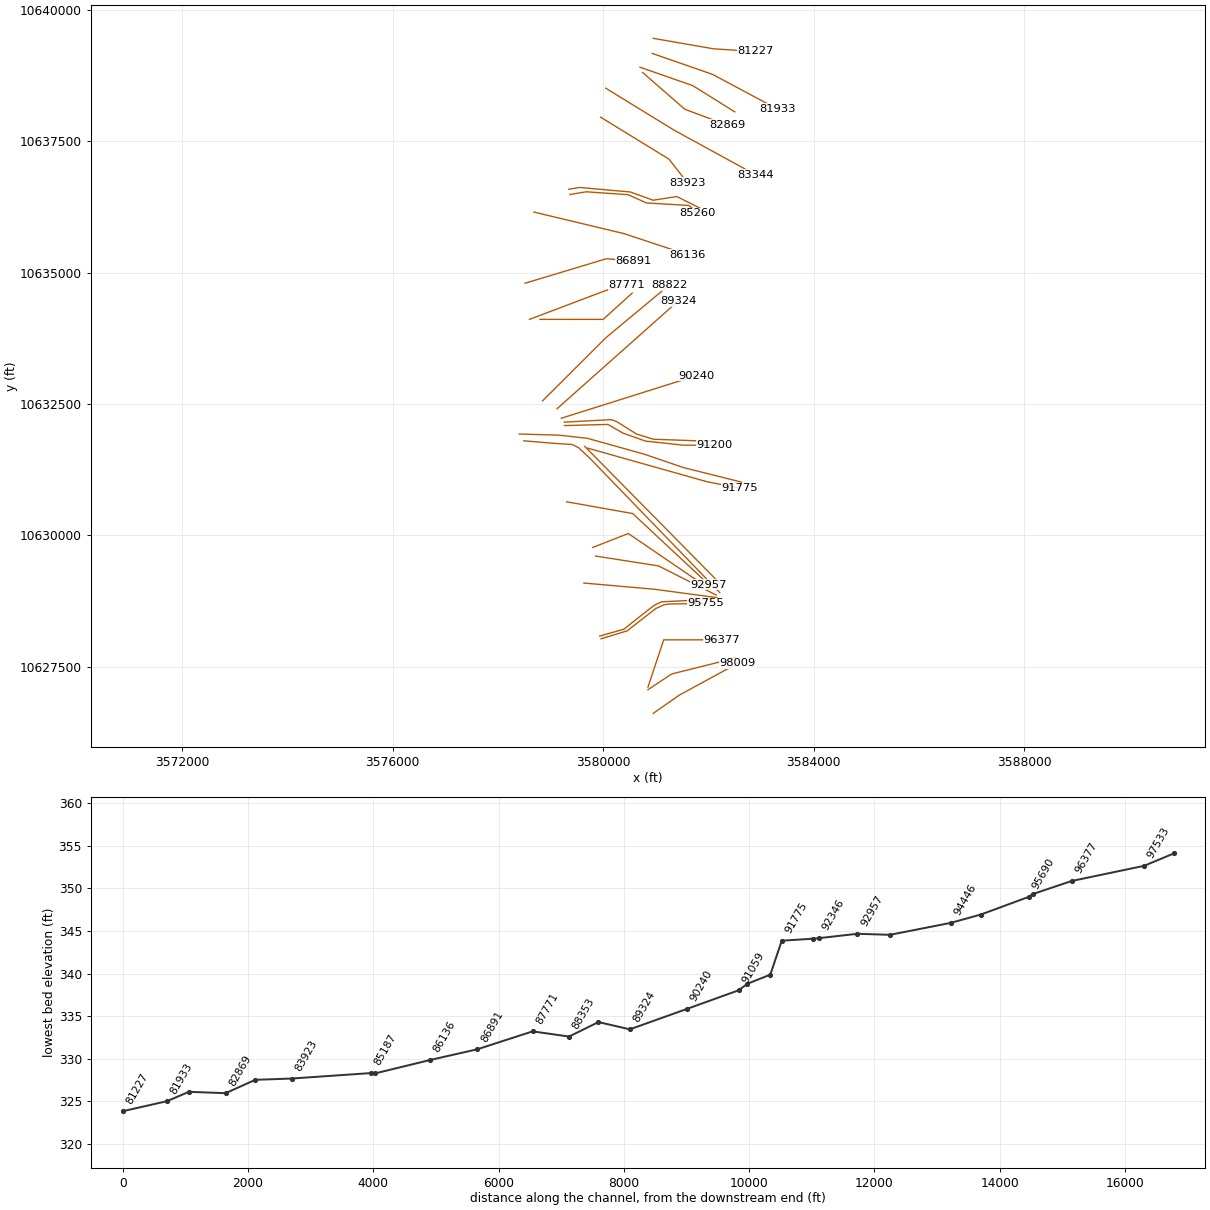
HEC-RAS study COTTONWOOD CREEK.prj: COTTONWOOD CREEK Base Level Engineering

--- COTTONWOOD CREEK.g01 (geometry) --- (continued)

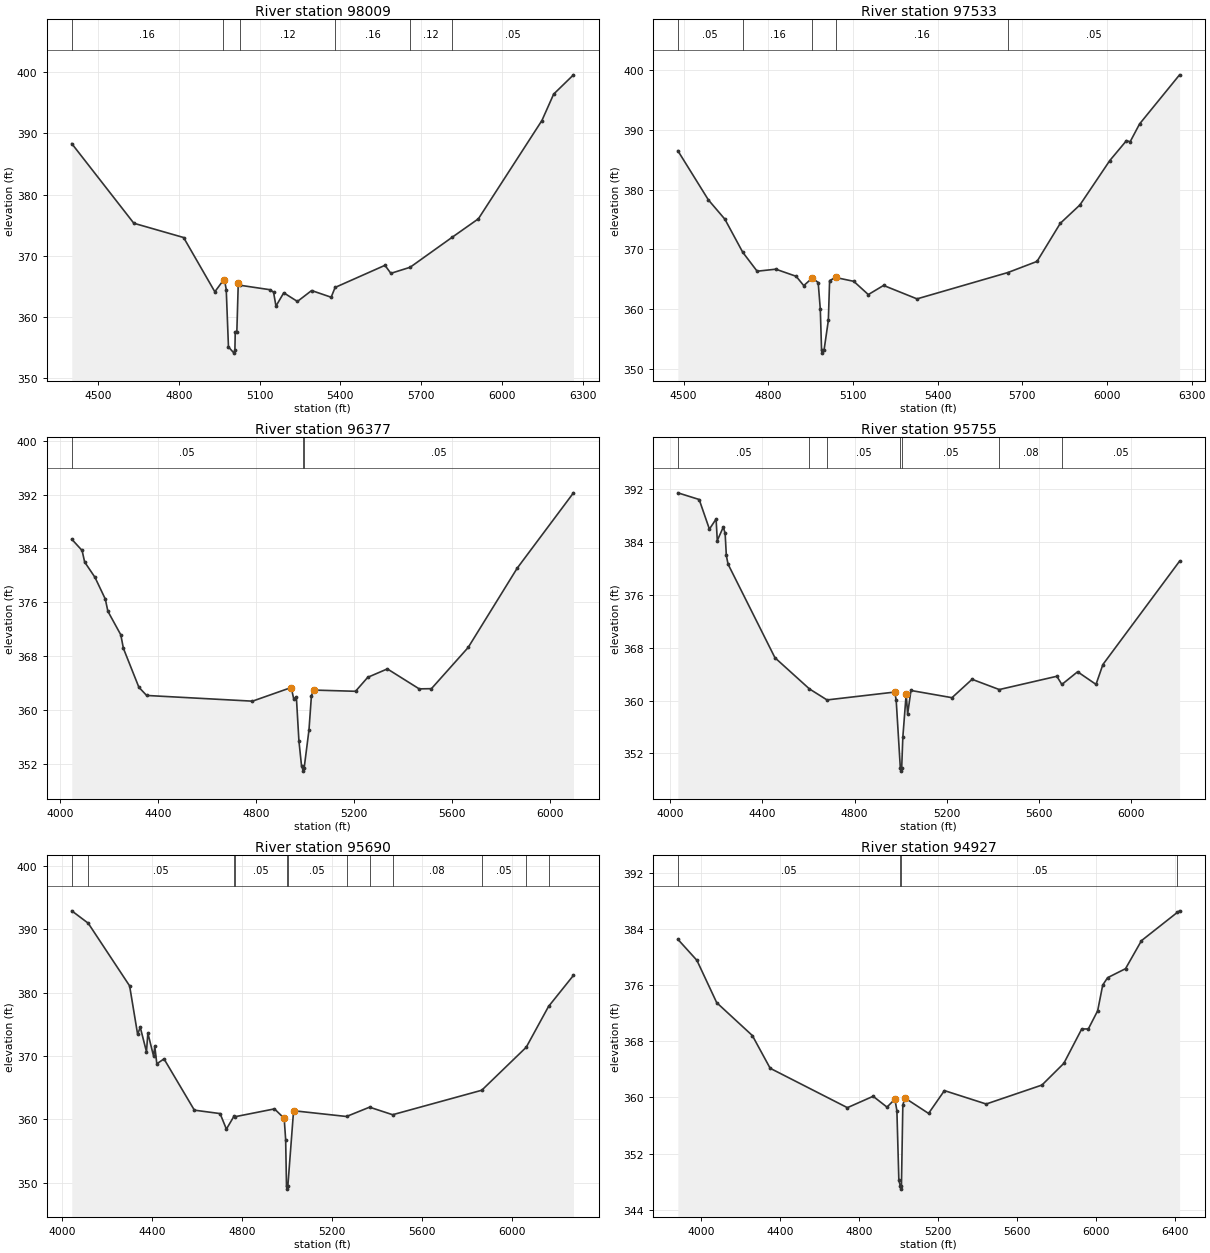
Type RM Length L Ch R = 1 ,98009   ,476,476,476
BEGIN DESCRIPTION:
COTTONWOOD CREEK 122.0
END DESCRIPTION:
XS GIS Cut Line= 3
      3580949.64     10626610.21      3581449.61     10626960.19
      3582549.62     10627560.19
#Sta/Elev= 30
  4402.3  388.33  4632.9  375.32  4817.7  372.99  4933.7  364.13  4963.3  365.89
  4969.4  366.11    4976   364.5  4984.3  355.12  5004.9  354.11  5008.2  354.61
  5009.5  357.61  5015.4  357.61  5020.7  365.52  5026.4   365.2  5137.9  364.47
  5151.7  364.07  5160.7  361.79  5189.6  363.96  5240.4  362.55  5293.1  364.33
  5365.7  363.24  5380.4  364.84  5565.5  368.45  5587.4  367.14  5658.9  368.13
  5814.1     373  5912.5  376.05  6148.4   392.1    6192  396.41  6265.6  399.56
#Mann= 6 ,-1 , 0
  4402.3     .16       0  4963.3      .1       0  5026.4     .12       0
  5380.4     .16       0  5658.9     .12       0  5814.1     .05       0
Bank Sta=4969.4,5020.7
XS Rating Curve= 0 ,0
Exp/Cntr=0.3,0.1

Type RM Length L Ch R = 1 ,97533   ,1156,1156,1156
BEGIN DESCRIPTION:
COTTONWOOD CREEK 121.0
END DESCRIPTION:
XS GIS Cut Line= 3
      3580849.59     10627060.18      3581299.61     10627360.19
      3582499.63     10627660.19
#Sta/Elev= 30
  4479.5  386.53  4587.7   378.3  4646.3  375.06  4709.4  369.54  4760.5  366.36
  4826.6   366.7  4898.7  365.51  4925.7  363.95  4955.8  365.22  4976.8  364.47
  4984.3     360  4988.8  353.15  4991.6  352.65  4997.8  353.22  5012.8  358.12
  5017.3  364.79  5038.4  365.31  5102.8  364.67  5154.4  362.45  5208.5  363.98
    5327  361.73  5649.1  366.14  5752.2     368  5834.7  374.38  5904.2  377.45
  6009.9  384.87  6069.2  388.22  6082.1  388.02  6115.6  391.01  6257.3  399.23
#Mann= 5 ,-1 , 0
  4479.5     .05       0  4709.4     .16       0  4955.8     .12       0
  5038.4     .16       0  5649.1     .05       0
Bank Sta=4955.8,5038.4
XS Rating Curve= 0 ,0
Exp/Cntr=0.3,0.1

Type RM Length L Ch R = 1 ,96377   ,622,622,622
BEGIN DESCRIPTION:
COTTONWOOD CREEK 120.0
END DESCRIPTION:
XS GIS Cut Line= 3
      3580849.61     10627110.18      3581149.61     10628010.19
      3582249.62     10628010.19
#Sta/Elev= 30
  4046.6  385.38  4088.8   383.7  4099.3  381.98  4141.5   379.7  4183.6  376.47
  4194.2  374.65  4246.9  371.15  4257.4  369.15  4320.7  363.35  4352.3  362.13
  4784.5  361.28  4942.6  363.31  4953.1   361.6  4963.7  361.93  4974.2  355.37
  4984.8  351.68  4989.7  351.37  4992.4  350.87  4995.7  351.37  5015.3     357
  5025.3  362.12  5035.3  362.93  5205.3  362.75  5255.3  364.83  5335.3  366.08
  5465.3  363.11  5515.3  363.14  5665.3  369.27  5865.3  381.06  6095.3  392.28
#Mann= 3 ,-1 , 0
  4046.6     .05       0  4989.7     .03       0  4995.7     .05       0
Bank Sta=4942.6,5035.3
XS Rating Curve= 0 ,0
Exp/Cntr=0.3,0.1

Type RM Length L Ch R = 1 ,95755   ,65,65,65
BEGIN DESCRIPTION:
COTTONWOOD CREEK 119.0
END DESCRIPTION:
XS GIS Cut Line= 6
      3579959.42     10628029.13      3580455.92      10628181.9
      3580997.59     10628605.51      3581157.31     10628678.42
      3581264.95     10628692.31      3581952.48     10628702.73
#Sta/Elev= 30
  4032.2  391.43  4124.9  390.42  4169.4  385.94  4198.4  387.47  4203.6  384.21
  4229.7  386.25  4237.7   385.3  4242.9  381.95  4250.4  380.64  4454.2  366.48
  4603.8  361.77  4680.3   360.1  4974.4  361.29  4980.8  360.09  4998.8  349.83
  5001.5  349.33  5004.8  349.83  5009.7  354.45  5024.2  360.98  5030.6  357.97
    5045  361.53  5223.3  360.44  5310.6  363.22  5428.7  361.67  5678.9  363.68
  5700.6  362.44    5769  364.36    5849  362.45    5879  365.46    6212  381.09
#Mann= 7 ,-1 , 0
  4032.2     .05       0  4603.8     .16       0  4680.3     .05       0
  4998.8     .04       0  5004.8     .05       0  5428.7     .08       0
  5700.6     .05       0
Bank Sta=4974.4,5024.2
XS Rating Curve= 0 ,0
Exp/Cntr=0.3,0.1

Type RM Length L Ch R = 1 ,95690   ,763,763,763
BEGIN DESCRIPTION:
COTTONWOOD CREEK 118.0
END DESCRIPTION:
XS GIS Cut Line= 6
      3579935.09      10628081.2      3580393.42     10628213.15
      3580896.89     10628612.45       3580983.7     10628674.95
       3581108.7     10628733.98      3581969.82     10628775.65
#Sta/Elev= 30
  4044.2  392.91  4117.2  390.96  4301.1  381.07  4336.6  373.45  4348.4  374.53
  4375.9  370.69  4382.2  373.61  4407.6  369.97  4412.9  371.52  4421.9  368.77
  4453.8  369.55  4588.6  361.46  4702.8  360.92  4730.8  358.47  4764.3  360.49
  4768.5  360.42  4944.3  361.66  4987.4  360.17  4993.9  356.83  4997.7   349.5
  5000.4     349  5003.7   349.5  5029.1  361.37  5264.1  360.46  5366.5  361.93
    5469  360.74  5864.5   364.6  6062.2  371.39  6161.1  377.82  6271.9  382.73
#Mann= 12 ,-1 , 0
  4044.2     .08       0  4117.2     .05       0  4764.3     .12       0
  4768.5     .05       0  4997.7     .04       0  5003.7     .05       0
  5264.1     .08       0  5366.5     .05       0    5469     .08       0
  5864.5     .05       0  6062.2     .08       0  6161.1     .05       0
Bank Sta=4987.4,5029.1
XS Rating Curve= 0 ,0
Exp/Cntr=0.3,0.1

Type RM Length L Ch R = 1 ,94927   ,481,481,481
BEGIN DESCRIPTION:
COTTONWOOD CREEK 117.0
END DESCRIPTION:
XS GIS Cut Line= 3
      3579633.31     10629091.08      3580973.61     10628973.02
      3582161.12      10628813.3
#Sta/Elev= 30
  3881.3  382.51    3978  379.51  4078.4  373.48  4259.1   368.8  4349.4  364.14
  4740.9  358.53  4871.4  360.15  4941.7  358.61  4981.8  359.74  4991.9  358.09
  5001.9  348.16    5009  347.43  5011.7  346.93    5015  347.43    5022  358.89
    5032  359.92  5152.5  357.71  5232.8  360.96  5444.7  359.05  5727.3  361.75
  5838.2  364.84  5929.1  369.74  5962.5  369.74  6009.8  372.33  6035.4  375.99
  6060.2  377.04    6151  378.32  6231.8  382.31  6413.3  386.33    6425  386.56
#Mann= 4 ,-1 , 0
  3881.3     .05       0    5009     .03       0    5015     .05       0
  6413.3     .08       0
Bank Sta=4981.8,5032
XS Rating Curve= 0 ,0
Exp/Cntr=0.3,0.1

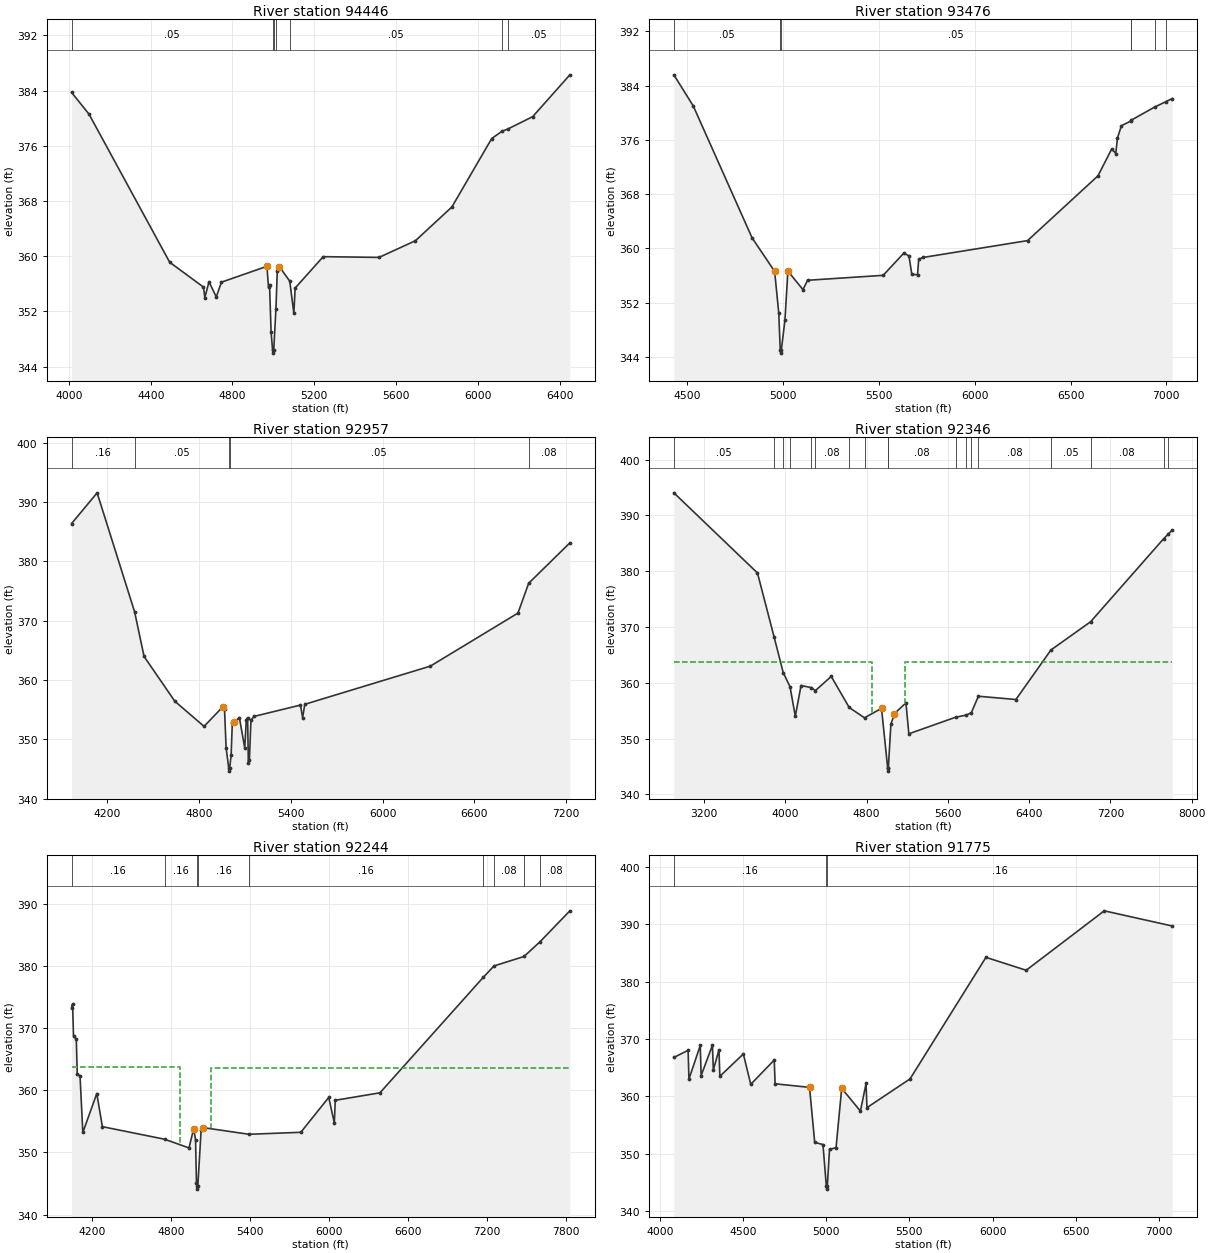
Type RM Length L Ch R = 1 ,94446   ,970,970,970
BEGIN DESCRIPTION:
COTTONWOOD CREEK 116.0
END DESCRIPTION:
XS GIS Cut Line= 3
      3579855.51     10629604.97      3581049.99     10629417.46
      3582145.91     10628862.57
#Sta/Elev= 30
    4013  383.73  4098.1  380.59  4492.9  359.12  4658.2  355.52    4665  354.01
  4685.2  356.29  4720.8  354.09    4746  356.23  4968.7  358.53  4976.3  355.48
  4981.3  355.89  4988.9  349.08    4996  346.45  4998.8  345.95    5002  346.45
  5012.7  352.41  5019.3  357.84  5029.4  358.48  5080.2  356.38  5100.3  351.73
  5106.6  355.38  5243.9  359.93  5516.8  359.82    5695  362.24  5873.3  367.13
  6068.2  377.05  6118.4   378.1  6145.9  378.41  6268.7  380.22  6450.5  386.28
#Mann= 7 ,-1 , 0
    4013     .05       0    4996     .03       0    5002     .05       0
  5012.7     .16       0  5080.2     .05       0  6118.4      .1       0
  6145.9     .05       0
Bank Sta=4968.7,5029.4
XS Rating Curve= 0 ,0
Exp/Cntr=0.3,0.1

Type RM Length L Ch R = 1 ,93476   ,519,519,519
BEGIN DESCRIPTION:
COTTONWOOD CREEK 115.0
END DESCRIPTION:
XS GIS Cut Line= 3
      3579799.97     10629768.15      3580477.08     10630033.78
      3582023.93     10628976.51
#Sta/Elev= 30
  4429.4  385.58  4530.9  380.97  4837.3  361.56  4955.4   356.6  4976.9  350.43
  4984.6  345.05  4987.3  344.55  4990.6  345.05  5009.1  349.43  5024.4  356.65
  5103.1  353.91  5127.2  355.29  5521.8  356.02  5629.4  359.29  5656.5  358.89
  5671.4  356.16  5701.2  356.11  5707.3  358.38  5729.1  358.65  6275.5  361.14
  6643.2  370.69    6715  374.67    6736  373.98  6744.9  376.28  6765.8  378.09
  6815.2  378.77  6816.5  378.89  6938.4  380.82  6996.6  381.61  7030.4  382.08
#Mann= 7 ,-1 , 0
  4429.4     .05       0  4984.6     .03       0  4990.6     .05       0
  6815.2     .08       0  6816.5      .1       0  6938.4     .08       0
  6996.6     .05       0
Bank Sta=4955.4,5024.4
XS Rating Curve= 0 ,0
Exp/Cntr=0.3,0.1

Type RM Length L Ch R = 1 ,92957   ,611,611,611
BEGIN DESCRIPTION:
COTTONWOOD CREEK 114.0
END DESCRIPTION:
XS GIS Cut Line= 3
      3579305.25     10630637.94      3580560.41     10630413.99
      3582008.35      10629059.8
#Sta/Elev= 30
  3967.1  386.38  4134.1  391.56  4379.3  371.49    4441  363.99  4641.9  356.45
  4833.3  352.21  4956.8  355.54    4967  355.11  4977.2  348.65  4994.5  345.17
  4997.2  344.67  5000.5  345.17  5010.1  347.33  5017.8   352.8    5028  352.89
    5064  353.69  5099.1  348.58  5109.2  353.26  5117.8  353.68  5122.9  345.96
  5129.5  346.58  5139.7  353.24    5160  353.89  5463.4   355.8  5477.6  353.69
  5491.7  355.93  6312.4  362.36  6885.4   371.3  6954.8  376.31  7224.6  383.13
#Mann= 5 ,-1 , 0
  3967.1     .16       0  4379.3     .05       0  4994.5     .03       0
  5000.5     .05       0  6954.8     .08       0
Bank Sta=4956.8,5028
XS Rating Curve= 0 ,0
Exp/Cntr=0.3,0.1

Type RM Length L Ch R = 1 ,92346   ,102,102,102
BEGIN DESCRIPTION:
COTTONWOOD CREEK 113.0
END DESCRIPTION:
XS GIS Cut Line= 6
      3578491.86     10631798.44      3579075.23     10631749.83
      3579408.56     10631728.99      3579533.56     10631666.49
      3579741.89     10631472.05      3582214.14     10628909.52
#Sta/Elev= 30
  2903.4  394.06  3726.1  379.69  3889.9  368.21  3979.9  361.81  4046.5   359.3
  4098.6     354  4155.2  359.51  4255.4  359.14  4296.2   358.6  4452.3  361.14
  4629.1  355.57  4779.7  353.72  4947.3  355.42  5008.1  344.66  5010.8  344.16
  5014.1  344.66  5039.4  352.55  5074.6  354.49  5187.8   356.4  5216.1  350.85
  5675.5  353.82  5781.6  354.21  5830.9  354.63    5901  357.59  6269.8     357
  6614.9  365.88  7005.5  370.95    7724  385.83  7766.9  386.61  7808.2  387.37
#Mann= 18 ,-1 , 0
  2903.4     .05       0  3889.9     .08       0  3979.9     .12       0
  4046.5     .08       0  4255.4     .16       0  4296.2     .08       0
  4629.1     .05       0  4779.7     .08       0  5008.1     .07       0
  5014.1     .08       0  5675.5     .05       0  5781.6     .08       0
  5830.9     .05       0    5901     .08       0  6614.9     .05       0
  7005.5     .08       0    7724     .05       0  7766.9     .08       0
#XS Ineff= 2 , 0
       0    4850  363.73    5180       0  363.73
Permanent Ineff=
       T       T
Bank Sta=4947.3,5074.6
XS Rating Curve= 0 ,0
Exp/Cntr=0.3,0.1

Type RM Length L Ch R = 1 ,92244   ,495,495,495
BEGIN DESCRIPTION:
COTTONWOOD CREEK 112.0
END DESCRIPTION:
XS GIS Cut Line= 2
      3579650.28     10631691.56      3582303.12     10628995.31
#Sta/Elev= 30
    4045  373.34  4052.6  373.91  4059.7  368.77  4080.8  368.28    4088  362.59
  4109.1  362.36  4130.4  353.22  4236.4   359.5  4278.8  354.16  4751.7  352.13
  4936.5  350.73  4971.9  353.85    4986  352.06    4993  345.11  4997.2  344.59
  4999.9  344.09  5003.2  344.59  5028.5  353.66  5042.6  354.01  5391.9  352.93
  5785.1  353.25  5997.1  358.87  6039.5  354.76  6046.7  358.41  6386.1  359.62
  7169.6  378.22  7251.8  380.07  7479.6  381.59  7601.2  383.97  7827.5  388.95
#Mann= 9 ,-1 , 0
    4045     .16       0  4751.7     .16       0  4997.2     .03       0
  5003.2     .16       0  5391.9     .16       0  7169.6     .05       0
  7251.8     .08       0  7479.6     .05       0  7601.2     .08       0
#XS Ineff= 2 , 0
       0    4870  363.78    5100       0  363.65
Permanent Ineff=
       T       T
Bank Sta=4971.9,5042.6
XS Rating Curve= 0 ,0
Exp/Cntr=0.5,0.3

Type RM Length L Ch R = 1 ,91775   ,183,183,183
BEGIN DESCRIPTION:
COTTONWOOD CREEK 111.0
END DESCRIPTION:
XS GIS Cut Line= 3
      3579705.41     10631659.19      3581976.27     10631018.56
      3582598.66     10630898.77
#Sta/Elev= 30
  4085.2  366.79  4170.6  368.03  4175.7  363.03  4243.7  368.87  4248.9  363.64
  4316.9  368.92  4322.1  364.61  4356.1  368.13  4361.3   363.5  4502.5   367.4
  4546.9  362.11  4688.1  366.34  4693.3   362.2    4900  361.58  4931.2     352
  4980.9  351.62  5000.9  344.36  5003.7  343.86  5006.9  344.36  5020.1  350.78
  5059.3  351.08  5093.3  361.41  5205.7  357.45  5239.7  362.26  5244.9  358.05
  5503.7  363.05  5959.8  384.22  6201.6  381.97  6670.6  392.32  7078.5  389.68
#Mann= 3 ,-1 , 0
  4085.2     .16       0  5000.9     .03       0  5006.9     .16       0
Bank Sta=4900,5093.3
XS Rating Curve= 0 ,0
Exp/Cntr=0.5,0.3

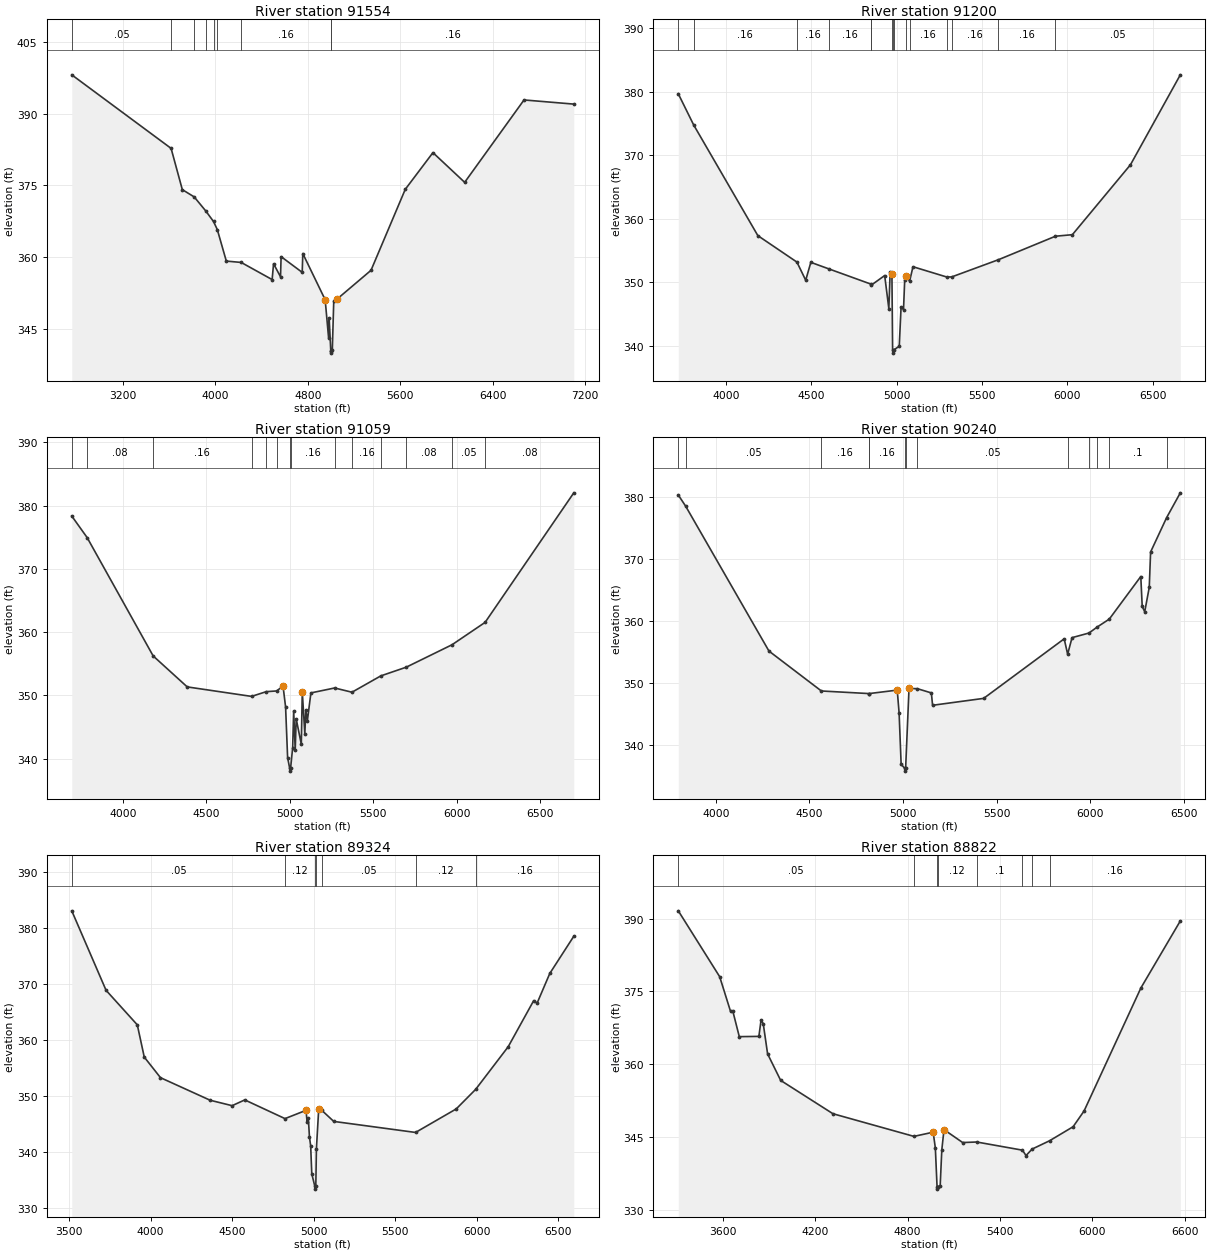
Type RM Length L Ch R = 1 ,91554   ,366,366,366
BEGIN DESCRIPTION:
COTTONWOOD CREEK 110.0
END DESCRIPTION:
XS GIS Cut Line= 6
      3578404.69     10631928.21      3579155.52     10631906.51
       3579702.4     10631845.75      3580787.47     10631541.93
      3581520.97     10631290.19      3582626.16     10631012.76
#Sta/Elev= 30
    2757  398.14  3616.4  382.74  3713.5   374.1  3816.3  372.58  3916.3  369.64
  3983.3  367.43  4016.3  365.73  4094.2  359.14  4222.8  358.86  4490.6  355.27
    4503  358.59  4563.1  355.85  4568.3  360.07  4750.8  356.78    4756  360.72
  4949.5  351.05  4978.9  343.12  4984.1  347.23  4997.9  340.37  5000.6  339.87
  5003.9  340.37  5011.2  340.44  5023.8  350.82  5052.7  351.19  5346.1  357.21
  5642.3  374.16  5881.9  381.85  6156.5  375.63    6670  392.88  7100.6  392.01
#Mann= 9 ,-1 , 0
    2757     .05       0  3616.4     .08       0  3816.3     .05       0
  3916.3     .08       0  3983.3     .05       0  4016.3     .08       0
  4222.8     .16       0  4997.9     .03       0  5003.9     .16       0
Bank Sta=4949.5,5052.7
XS Rating Curve= 0 ,0
Exp/Cntr=0.5,0.3

Type RM Length L Ch R = 1 ,91200   ,141,141,141
BEGIN DESCRIPTION:
COTTONWOOD CREEK 109.0
END DESCRIPTION:
XS GIS Cut Line= 6
      3579264.07     10632088.81      3580088.68     10632110.51
      3580375.14     10631945.57      3580800.49     10631793.67
      3581520.97     10631715.54      3582111.25     10631715.54
#Sta/Elev= 30
  3722.5  379.68  3812.7  374.76  4188.2  357.32  4416.9  353.15  4468.3  350.29
  4498.3  353.11  4602.7  352.09  4847.8   349.7  4850.6  349.49  4930.5  351.03
  4954.8  345.83  4962.5   351.6  4972.9   351.2  4976.9   339.3  4979.6   338.8
  4982.9   339.3  5015.8  339.88  5026.5   346.1  5040.7  345.65  5047.8  350.38
  5055.9  350.93  5076.6  350.16  5096.1  352.42  5292.5  350.81  5322.5  350.81
  5596.6  353.53  5930.2  357.23    6029  357.47  6369.2   368.5  6660.8  382.67
#Mann= 15 ,-1 , 0
  3722.5     .08       0  3812.7     .16       0  4416.9     .16       0
  4602.7     .16       0  4847.8     .08       0  4850.6     .16       0
  4972.9     .05       0  4976.9     .04       0  4982.9     .07       0
  5055.9     .16       0  5076.6     .16       0  5292.5     .08       0
  5322.5     .16       0  5596.6     .16       0  5930.2     .05       0
Bank Sta=4972.9,5055.9
XS Rating Curve= 0 ,0
Exp/Cntr=0.5,0.3

Type RM Length L Ch R = 1 ,91059   ,819,819,819
BEGIN DESCRIPTION:
COTTONWOOD CREEK 108.0
END DESCRIPTION:
XS GIS Cut Line= 6
      3579259.74     10632153.91      3580158.13     10632201.65
      3580266.63     10632158.25      3580631.22     10631928.21
      3580956.74     10631828.39      3582172.06     10631784.98
#Sta/Elev= 30
    3694  378.34    3786  374.94  4181.5  356.23  4385.3  351.34  4770.4  349.84
  4858.8  350.59  4920.9   350.7  4959.1  351.48  4974.4  348.16  4986.5  340.16
  4998.5  338.53  5001.2  338.03  5004.5  338.53  5016.7  341.75  5022.7  347.56
    5032  341.39  5037.9  346.29  5068.4  342.29  5074.3  350.54  5089.6  343.97
  5095.5  347.71  5104.8  346.01    5126  350.39    5268  351.17  5371.8   350.5
  5544.5  353.08  5697.2  354.46  5970.9     358  6169.1  361.54  6700.1  382.01
#Mann= 14 ,-1 , 0
    3694     .05       0    3786     .08       0  4181.5     .16       0
  4770.4     .16       0  4858.8     .16       0  4920.9     .05       0
  4998.5     .04       0  5004.5     .16       0    5268     .16       0
  5371.8     .16       0  5544.5     .16       0  5697.2     .08       0
  5970.9     .05       0  6169.1     .08       0
Bank Sta=4959.1,5074.3
XS Rating Curve= 0 ,0
Exp/Cntr=0.3,0.1

Type RM Length L Ch R = 1 ,90240   ,916,916,916
BEGIN DESCRIPTION:
COTTONWOOD CREEK 107.0
END DESCRIPTION:
XS GIS Cut Line= 2
      3579204.96     10632228.84      3581760.83     10633035.68
#Sta/Elev= 30
  3799.7  380.27  3839.3  378.46  4283.8  355.17  4563.6  348.75  4819.2  348.33
  4820.4  348.34  4968.6  348.89  4978.6   345.2  4989.5  336.94  5007.5  336.36
  5010.3  335.86  5013.5  336.36  5031.5  349.15    5076  349.12  5150.8  348.44
  5157.3  346.45    5430  347.56  5859.9  357.14  5878.4  354.67  5901.9  357.33
  5992.3  358.07  6034.8  359.01  6100.7  360.31  6268.9  367.16  6276.5  362.34
  6289.9   361.5  6314.1  365.42  6321.3  371.11  6406.8  376.63  6479.9  380.62
#Mann= 13 ,-1 , 0
  3799.7     .08       0  3839.3     .05       0  4563.6     .16       0
  4819.2     .12       0  4820.4     .16       0  5007.5     .07       0
  5013.5     .16       0    5076     .05       0  5878.4     .16       0
  5992.3     .05       0  6034.8     .16       0  6100.7      .1       0
  6406.8     .16       0
Bank Sta=4968.6,5031.5
XS Rating Curve= 0 ,0
Exp/Cntr=0.3,0.1

Type RM Length L Ch R = 1 ,89324   ,502,502,502
BEGIN DESCRIPTION:
COTTONWOOD CREEK 106.0
END DESCRIPTION:
XS GIS Cut Line= 2
      3579123.31     10632409.19      3581420.48     10634456.52
#Sta/Elev= 30
  3517.4  383.14  3727.6  368.95  3919.1  362.78  3961.7  357.03  4061.2  353.35
  4365.6  349.32  4500.2  348.35  4577.9  349.38  4824.4  346.04  4953.3  347.52
    4960  345.39  4967.5  346.07  4974.2  342.79  4981.8  341.16  4988.5   336.2
  5007.2  333.95  5009.9  333.45  5013.2  333.95  5016.9  340.64  5031.1  347.82
  5050.7   347.5  5123.1  345.54  5624.6  343.57  5873.9  347.77  5992.9  351.26
  6192.4  358.87  6348.8  367.11  6369.7  366.66  6447.4  371.96  6594.5   378.6
#Mann= 7 ,-1 , 0
  3517.4     .05       0  4824.4     .12       0  5007.2     .07       0
  5013.2     .12       0  5050.7     .05       0  5624.6     .12       0
  5992.9     .16       0
Bank Sta=4953.3,5031.1
XS Rating Curve= 0 ,0
Exp/Cntr=0.3,0.1

Type RM Length L Ch R = 1 ,88822   ,469,469,469
BEGIN DESCRIPTION:
COTTONWOOD CREEK 105.0
END DESCRIPTION:
XS GIS Cut Line= 3
      3578849.62      10632560.2      3580049.61     10633760.19
      3581249.62      10634760.2
#Sta/Elev= 30
  3311.8  391.59  3580.5  378.03  3651.2  370.87  3665.3     371  3707.8  365.69
    3835  365.74  3849.2   369.1  3863.3  368.36  3891.6  362.14  3976.5  356.68
  4315.9  349.82  4841.5  345.16  4966.4  346.02  4980.6  342.78  4991.7   334.8
  4994.4   334.3  4997.7   334.8  5012.1  335.04  5022.5  342.38  5036.8  346.55
  5157.9  343.89  5249.3     344  5546.1  342.32  5569.2  341.21  5608.5  342.54
  5722.3  344.26  5875.1  347.15  5946.1  350.39  6315.1  375.72  6570.9  389.51
#Mann= 8 ,-1 , 0
  3311.8     .05       0  4841.5     .12       0  4991.7     .07       0
  4997.7     .12       0  5249.3      .1       0  5546.1     .16       0
  5608.5     .12       0  5722.3     .16       0
Bank Sta=4966.4,5036.8
XS Rating Curve= 0 ,0
Exp/Cntr=0.3,0.1

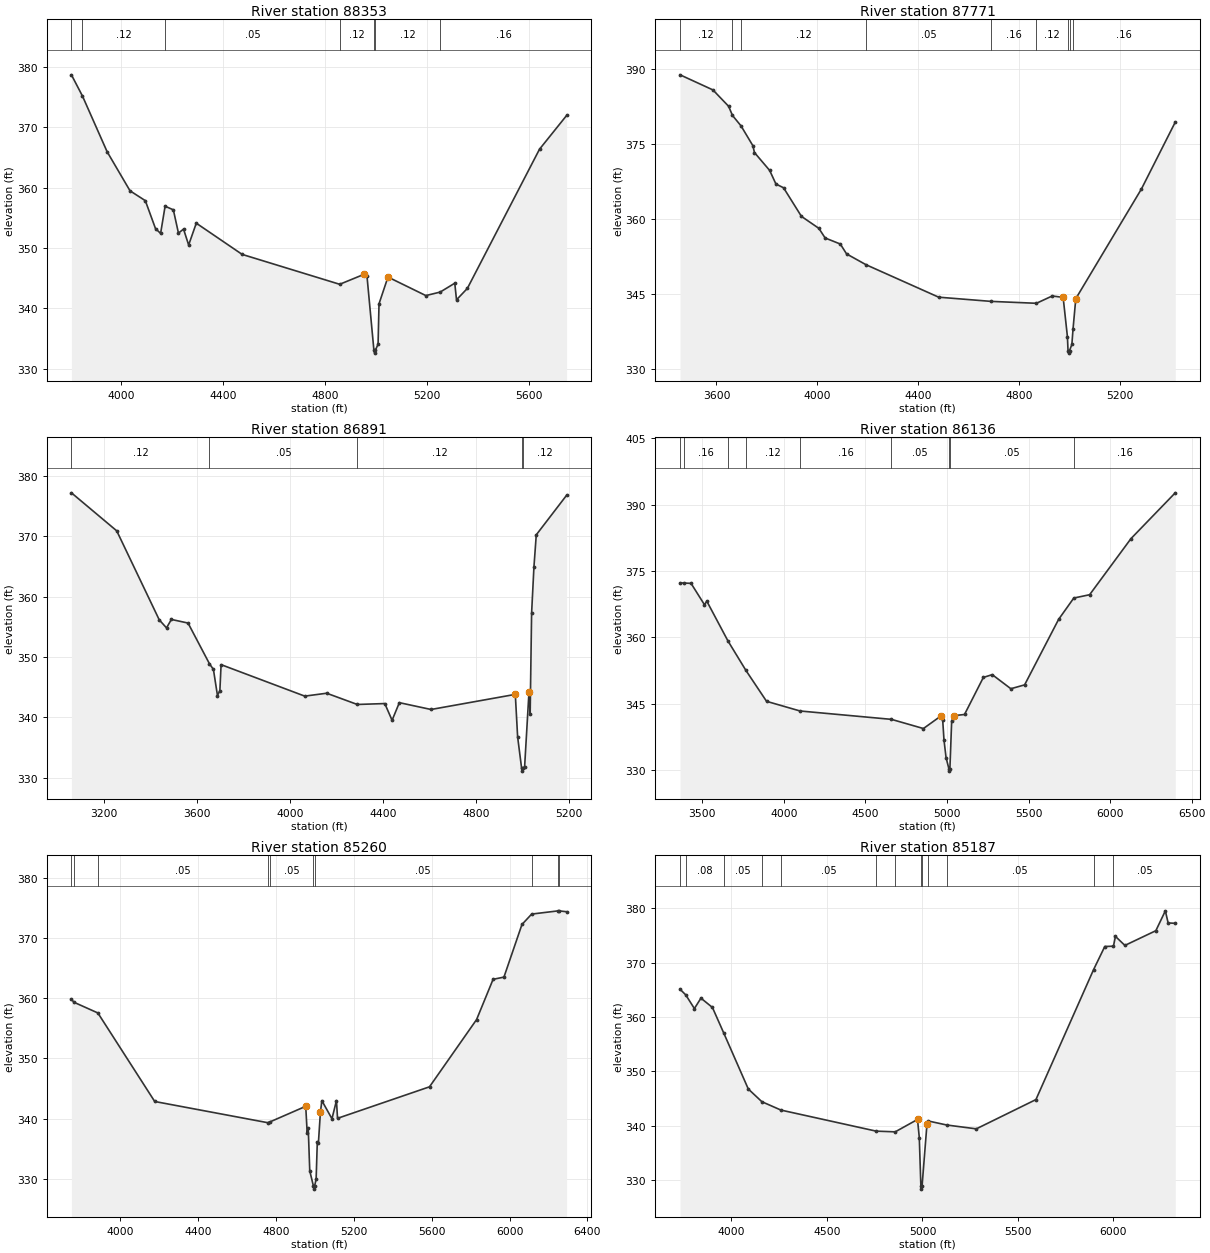
Type RM Length L Ch R = 1 ,88353   ,582,582,582
BEGIN DESCRIPTION:
COTTONWOOD CREEK 104.0
END DESCRIPTION:
XS GIS Cut Line= 3
      3578799.59     10634110.19      3579999.61     10634110.19
       3580549.6     10634610.18
#Sta/Elev= 30
    3805  378.69  3848.4  375.17    3945  365.96    4035  359.48    4095  357.85
    4135  353.22    4155  352.43  4172.6  356.93    4205  356.33    4225  352.48
    4245  353.14    4265  350.51    4295  354.12    4475  348.95  4857.8     344
    4955  345.68    4965  345.31    4992   333.1  4994.8   332.6    4998   333.1
  5008.4  334.07  5012.1  340.77  5047.2   345.2  5195.9  342.13    5252  342.71
  5309.4  344.18  5316.2  341.43  5358.8  343.32  5641.9  366.37  5748.3  371.96
#Mann= 7 ,-1 , 0
    3805     .16       0  3848.4     .12       0  4172.6     .05       0
  4857.8     .12       0    4992     .07       0    4998     .12       0
    5252     .16       0
Bank Sta=4955,5047.2
XS Rating Curve= 0 ,0
Exp/Cntr=0.3,0.1

Type RM Length L Ch R = 1 ,87771   ,880,880,880
BEGIN DESCRIPTION:
COTTONWOOD CREEK 103.0
END DESCRIPTION:
XS GIS Cut Line= 3
      3578599.65      10634110.2      3580049.61     10634660.19
      3580449.64      10634760.2
#Sta/Elev= 30
  3455.7  388.77  3585.9  385.76  3648.2  382.49  3663.4  380.67  3697.6  378.56
  3744.4  374.62  3750.7  373.25    3811  369.68  3835.8  366.97    3866  366.22
  3936.9  360.51    4006  358.12  4030.8   356.2    4091  354.99  4115.8  353.02
  4192.9  350.86  4480.9  344.38  4688.6  343.54  4868.5  343.16  4931.1  344.62
  4974.4  344.34  4991.4  336.46  4993.7  333.71  4996.5  333.21  4999.7  333.71
    5009  334.95  5013.5  337.98  5024.5  344.08  5284.8  365.99  5418.8  379.32
#Mann= 9 ,-1 , 0
  3455.7     .12       0  3663.4     .16       0  3697.6     .12       0
  4192.9     .05       0  4688.6     .16       0  4868.5     .12       0
  4993.7     .07       0  4999.7     .12       0  5013.5     .16       0
Bank Sta=4974.4,5024.5
XS Rating Curve= 0 ,0
Exp/Cntr=0.3,0.1

Type RM Length L Ch R = 1 ,86891   ,755,755,755
BEGIN DESCRIPTION:
COTTONWOOD CREEK 101.0
END DESCRIPTION:
XS GIS Cut Line= 3
      3578517.43     10634798.97      3580059.08     10635264.24
      3580579.89     10635222.57
#Sta/Elev= 30
  3058.7  377.16  3253.8  370.87    3437  356.14  3468.3  354.81  3489.2  356.21
    3561  355.61  3653.3  348.87  3670.3  347.94  3687.7  343.62  3698.1  344.44
  3703.3  348.73  4063.7  343.52  4158.1     344  4289.9  342.14  4408.4  342.29
  4439.8  339.52  4471.1  342.44  4607.6  341.31  4970.5  343.81  4980.5  336.78
  4997.6  331.61  5000.4  331.11  5003.6  331.61  5010.6  331.82  5029.5  344.23
  5034.5  340.61  5040.7  357.25  5050.8  364.92  5060.8  370.21  5191.5  376.76
#Mann= 5 ,-1 , 0
  3058.7     .12       0  3653.3     .05       0  4289.9     .12       0
  4997.6     .07       0  5003.6     .12       0
Bank Sta=4970.5,5029.5
XS Rating Curve= 0 ,0
Exp/Cntr=0.3,0.1

Type RM Length L Ch R = 1 ,86136   ,876,876,876
BEGIN DESCRIPTION:
COTTONWOOD CREEK 100.0
END DESCRIPTION:
XS GIS Cut Line= 3
      3578684.04     10636153.14      3580392.41      10635743.4
      3581606.16     10635341.13
#Sta/Elev= 30
    3364  372.31  3388.3  372.29  3431.4  372.21  3513.7  367.39  3527.9   368.2
  3657.6  359.22  3767.8  352.57  3894.2   345.6  4099.4  343.42  4659.8  341.53
  4855.8  339.46  4963.7  342.31    4974  341.36  4981.8   336.9  4994.5  332.92
  5012.1  330.35  5014.9  329.85  5018.1  330.35    5029  341.19    5046  342.38
  5107.7  342.63  5223.2  350.99  5277.6  351.62  5391.8  348.44  5476.1  349.31
  5684.4  364.08  5777.5   368.9  5874.6  369.65  6128.1  382.31  6399.5  392.64
#Mann= 9 ,-1 , 0
    3364     .05       0  3388.3     .16       0  3657.6     .05       0
  3767.8     .12       0  4099.4     .16       0  4659.8     .05       0
  5012.1     .03       0  5018.1     .05       0  5777.5     .16       0
Bank Sta=4963.7,5046
XS Rating Curve= 0 ,0
Exp/Cntr=0.3,0.1

Type RM Length L Ch R = 1 ,85260   ,73,73,73
BEGIN DESCRIPTION:
COTTONWOOD CREEK 99.0
END DESCRIPTION:
XS GIS Cut Line= 6
      3579367.35     10636487.22      3579679.85      10636539.3
      3580474.12     10636482.88      3580821.34     10636326.63
      3581628.63     10636278.89      3581797.93     10636126.95
#Sta/Elev= 30
  3748.4  359.87  3760.6  359.36  3884.3  357.57  4176.5  342.85  4756.7  339.33
  4768.2  339.45  4952.6  342.05    4960  337.68  4965.5  338.38  4973.3  331.32
  4992.2  328.78  4994.9  328.28  4998.2  328.78  5006.1  329.97  5012.1  336.16
  5017.6   335.9    5028  341.04  5035.5  342.99  5087.4  339.98  5110.5     343
    5116  340.05  5588.7  345.29  5830.7  356.47  5915.5  363.16  5971.3  363.53
  6063.9  372.28  6113.8  374.01  6251.6  374.55  6251.8  374.55  6293.4   374.4
#Mann= 10 ,-1 , 0
  3748.4     .05       0  3760.6     .08       0  3884.3     .05       0
  4756.7     .08       0  4768.2     .05       0  4992.2     .04       0
  4998.2     .05       0  6113.8     .08       0  6251.6     .05       0
  6251.8     .08       0
Bank Sta=4952.6,5028
XS Rating Curve= 0 ,0
Exp/Cntr=0.3,0.1

Type RM Length L Ch R = 1 ,85187   ,1264,1264,1264
BEGIN DESCRIPTION:
COTTONWOOD CREEK 98.0
END DESCRIPTION:
XS GIS Cut Line= 6
      3579345.68     10636587.05      3579549.64     10636621.77
      3580517.52     10636534.96      3580947.21     10636378.71
       3581398.6     10636448.16      3581832.61     10636231.16
#Sta/Elev= 30
  3731.1  365.12  3761.1  364.07  3806.1  361.56  3840.4  363.48  3900.6  361.76
  3960.4  357.01  4088.3  346.75  4159.3  344.41    4259  342.87  4757.5  338.99
  4857.5  338.86  4974.1  341.14  4983.4  337.81  4991.8  328.81  4994.5  328.31
  4997.8  328.81  5023.8  340.37  5028.9  340.87  5126.6  340.12  5281.9  339.41
    5594   344.8  5895.5  368.71  5954.4  372.99  5999.8  373.05  6010.3  374.85
  6059.7  373.19  6221.7   375.9  6271.5  379.56    6286  377.33  6323.3  377.26
#Mann= 13 ,-1 , 0
  3731.1     .05       0  3761.1     .08       0  3960.4     .05       0
  4159.3     .08       0    4259     .05       0  4757.5     .08       0
  4857.5     .05       0  4991.8     .04       0  4997.8     .05       0
  5028.9     .16       0  5126.6     .05       0  5895.5     .08       0
  5999.8     .05       0
Bank Sta=4974.1,5023.8
XS Rating Curve= 0 ,0
Exp/Cntr=0.3,0.1

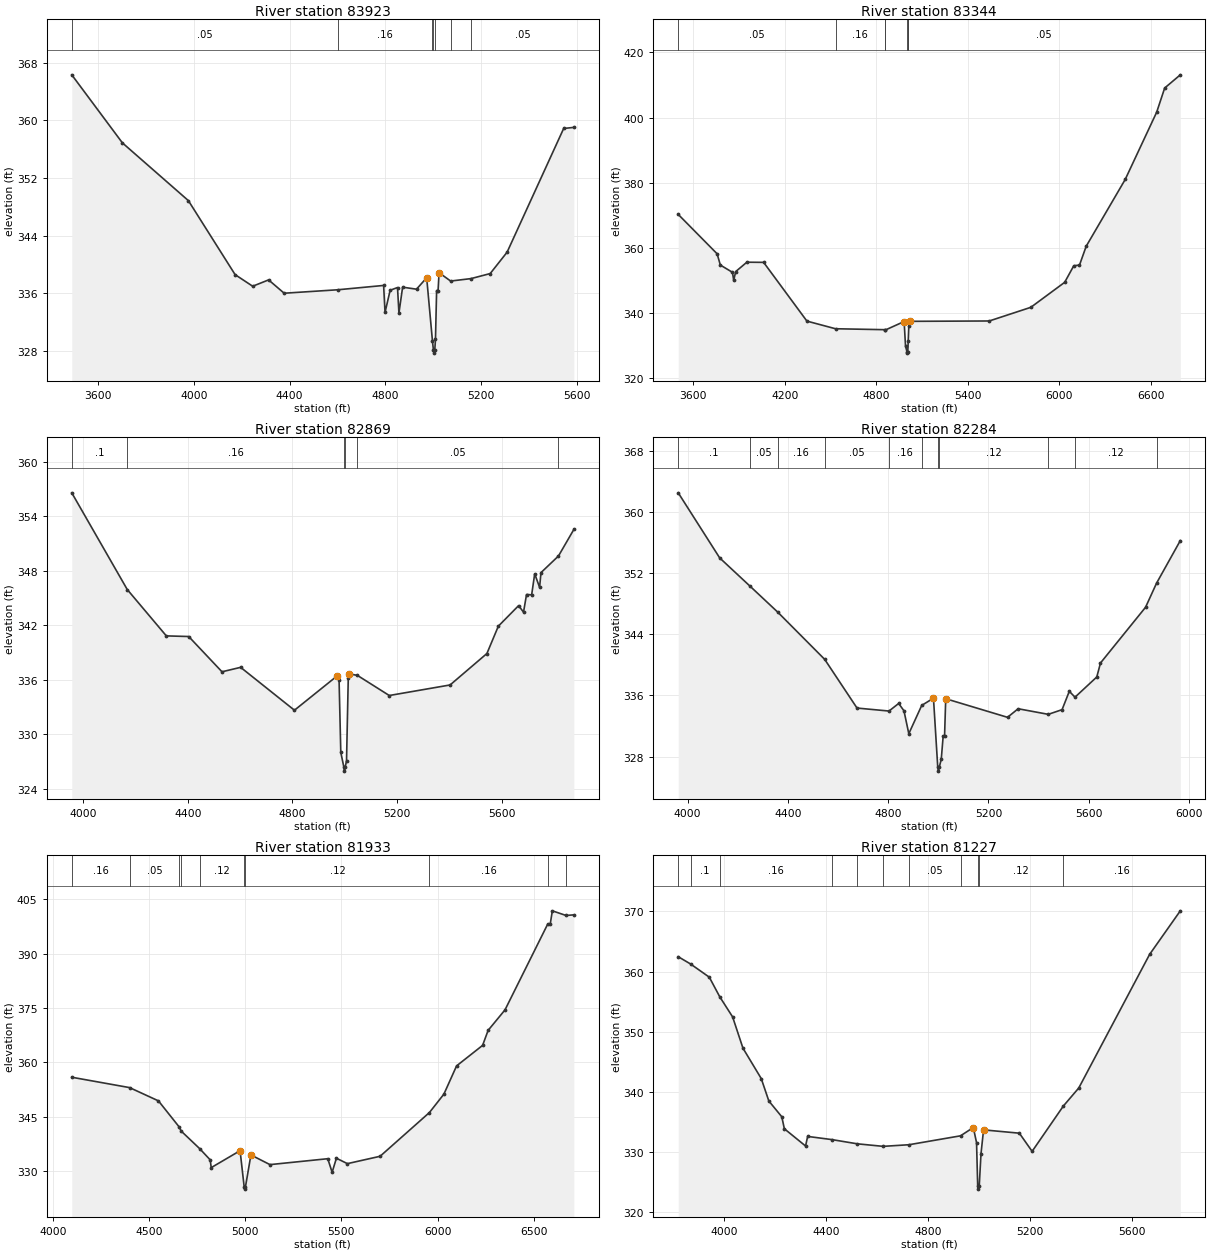
Type RM Length L Ch R = 1 ,83923   ,579,579,579
BEGIN DESCRIPTION:
COTTONWOOD CREEK 97.0
END DESCRIPTION:
XS GIS Cut Line= 3
      3579949.61     10637960.19      3581249.61     10637160.19
       3581599.6      10636710.2
#Sta/Elev= 30
  3490.3  366.32  3701.7  356.87  3977.2  348.85  4172.4  338.57  4245.8  336.96
  4312.2  337.84  4377.2  335.99  4601.6  336.47  4792.5  337.07  4798.4  333.32
  4819.7   336.4  4850.5  336.78  4856.4  333.24  4871.8  336.83  4929.8  336.55
  4972.3  338.14  4996.3  329.39  5000.2  328.17  5002.9  327.67  5006.2  328.17
    5009  329.57  5013.8  336.36  5019.9  336.36    5024  338.84  5072.3  337.68
  5157.4  338.02  5237.5  338.72  5308.1  341.69  5544.3  358.87  5586.8  359.02
#Mann= 7 ,-1 , 0
  3490.3     .05       0  4601.6     .16       0  4996.3     .12       0
  5000.2     .07       0  5006.2     .12       0  5072.3     .16       0
  5157.4     .05       0
Bank Sta=4972.3,5024
XS Rating Curve= 0 ,0
Exp/Cntr=0.3,0.1

Type RM Length L Ch R = 1 ,83344   ,475,475,475
BEGIN DESCRIPTION:
COTTONWOOD CREEK 96.0
END DESCRIPTION:
XS GIS Cut Line= 3
      3580049.59      10638510.2      3581349.61     10637710.19
      3582899.59      10636860.2
#Sta/Elev= 30
  3501.3  370.19  3756.3  358.08  3777.6  354.61  3856.9  352.38  3865.3  349.92
  3878.2   352.6  3951.5  355.49  4061.6  355.44  4345.6  337.37  4533.2  335.02
    4857  334.73    4861  334.65  4983.4  337.24  4992.5  329.77  5001.6  328.02
  5004.4  327.52  5007.6  328.02  5010.3  331.24  5014.2  335.89    5020   337.3
    5542  337.41  5814.7  341.61  6036.8   349.3  6096.5   354.4    6134   354.6
    6178   360.4  6433.9  380.94  6640.5  401.64  6692.9  409.07  6795.5  413.13
#Mann= 7 ,-1 , 0
  3501.3     .05       0  4533.2     .16       0    4857     .12       0
    4861     .16       0  5001.6     .07       0  5007.6     .16       0
  5010.3     .05       0
Bank Sta=4983.4,5020
XS Rating Curve= 0 ,0
Exp/Cntr=0.3,0.1

Type RM Length L Ch R = 1 ,82869   ,585,585,585
BEGIN DESCRIPTION:
COTTONWOOD CREEK 95.0
END DESCRIPTION:
XS GIS Cut Line= 3
      3580749.61     10638810.19      3581549.61     10638110.19
      3582349.59      10637810.2
#Sta/Elev= 30
  3957.3  356.57  4169.2  345.93  4318.4  340.83  4403.9  340.76    4531  336.88
  4602.2  337.37  4807.7  332.65  4970.5  336.42  4978.1  335.98  4984.7  328.01
    4996  326.45  4998.7  325.95    5002  326.45  5006.6   327.1  5013.2  336.16
    5017  336.66  5048.3  336.48  5169.8  334.27  5402.1  335.43  5542.7  338.89
  5586.4   341.9  5663.8  344.16  5682.5  343.44    5694  345.38  5713.6  345.35
  5725.2  347.66  5743.9  346.17  5749.2  347.79    5816  349.62  5874.7  352.54
#Mann= 6 ,-1 , 0
  3957.3      .1       0  4169.2     .16       0    4996     .07       0
    5002     .16       0  5048.3     .05       0    5816     .12       0
Bank Sta=4970.5,5017
XS Rating Curve= 0 ,0
Exp/Cntr=0.3,0.1

Type RM Length L Ch R = 1 ,82284   ,351,351,351
BEGIN DESCRIPTION:
COTTONWOOD CREEK 94.0
END DESCRIPTION:
XS GIS Cut Line= 3
      3580699.62     10638910.18      3581699.61     10638560.19
      3582499.64     10638060.17
#Sta/Elev= 30
  3962.4  362.47  4127.7  353.97  4248.6  350.28  4358.8   346.9  4546.7  340.71
  4675.6  334.35  4803.1  333.96  4841.8  334.95  4862.9  333.99  4882.2     331
  4933.8   334.7  4980.6  335.64  4997.7  326.61  5000.4  326.11  5003.7  326.61
  5011.7  327.67  5019.2  330.65  5024.8  330.65  5029.5  335.57    5276  333.14
  5318.4  334.26  5438.6  333.53  5493.6  334.14  5522.5  336.54  5545.2  335.77
  5632.1  338.41  5646.9  340.24  5826.7  347.52  5870.6  350.67  5965.3  356.23
#Mann= 11 ,-1 , 0
  3962.4      .1       0  4248.6     .05       0  4358.8     .16       0
  4546.7     .05       0  4803.1     .16       0  4933.8     .12       0
  4997.7     .07       0  5003.7     .12       0  5438.6     .16       0
  5545.2     .12       0  5870.6     .16       0
Bank Sta=4980.6,5029.5
XS Rating Curve= 0 ,0
Exp/Cntr=0.3,0.1

Type RM Length L Ch R = 1 ,81933   ,706,706,706
BEGIN DESCRIPTION:
COTTONWOOD CREEK 93.0
END DESCRIPTION:
XS GIS Cut Line= 3
      3580929.83     10639173.86      3582075.68     10638774.55
      3583307.95     10638115.02
#Sta/Elev= 30
  4097.7  355.87  4398.5  353.01  4548.5  349.35  4656.6  342.14  4666.3  341.04
  4762.8  336.18  4817.6  333.08  4822.9  330.94    4973  335.61  4994.6  325.51
  4997.4  325.01  5000.6  325.51  5029.4  334.44  5128.4  331.77    5429   333.4
  5451.7  329.66    5474  333.53  5531.1  332.04  5701.2  334.07  5957.8  346.14
  6033.1  351.22  6098.9     359  6234.3  364.66    6263   368.8  6350.8  374.45
  6572.5  398.07  6586.4  398.26    6597  401.77  6668.1  400.49  6708.8  400.66
#Mann= 10 ,-1 , 0
  4097.7     .16       0  4398.5     .05       0  4656.6     .16       0
  4666.3     .05       0  4762.8     .12       0  4994.6     .07       0
  5000.6     .12       0  5957.8     .16       0  6572.5     .05       0
  6668.1     .08       0
Bank Sta=4973,5029.4
XS Rating Curve= 0 ,0
Exp/Cntr=0.3,0.1

Type RM Length L Ch R = 1 ,81227   ,637,637,637
BEGIN DESCRIPTION:
COTTONWOOD CREEK 92.0
END DESCRIPTION:
XS GIS Cut Line= 3
      3580949.59     10639460.19      3582099.61     10639260.19
      3582899.56     10639210.19
#Sta/Elev= 30
  3820.8  362.46  3868.9  361.26  3942.6  359.06  3983.6   355.8    4034  352.46
  4074.6  347.26  4146.3  342.21  4176.1  338.48  4226.8  335.86    4237  333.86
  4320.1     331  4328.3  332.59  4422.2  332.07  4523.3  331.36  4624.4  330.94
  4725.5  331.21  4927.7  332.69  4977.9  334.07  4990.6  331.55  4995.1  324.33
  4997.9  323.83  5001.1  324.33  5008.1  329.75  5018.1  333.68  5158.4  333.13
  5208.5  330.11  5330.9  337.64  5391.4  340.64  5669.4  362.86  5789.6  370.09
#Mann= 11 ,-1 , 0
  3820.8     .05       0  3868.9      .1       0  3983.6     .16       0
  4422.2      .1       0  4523.3     .05       0  4624.4     .16       0
  4725.5     .05       0  4927.7     .12       0  4995.1     .07       0
  5001.1     .12       0  5330.9     .16       0
Bank Sta=4977.9,5018.1
XS Rating Curve= 0 ,0
Exp/Cntr=0.3,0.1