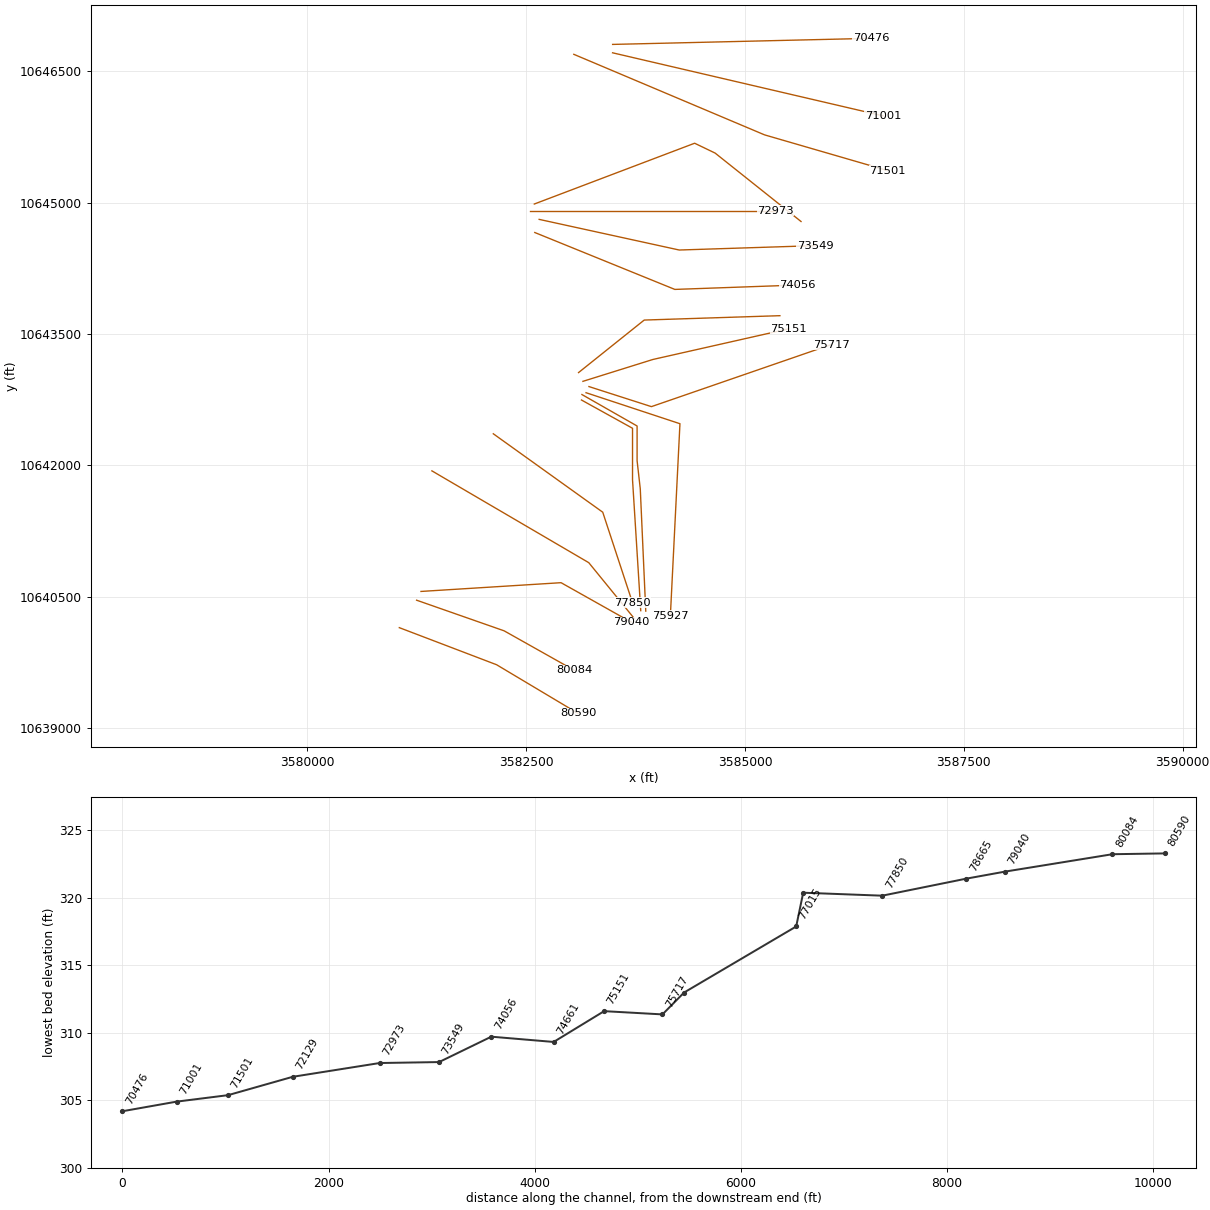
HEC-RAS study COTTONWOOD CREEK.prj: COTTONWOOD CREEK Base Level Engineering

--- COTTONWOOD CREEK.g01 (geometry) --- (continued)

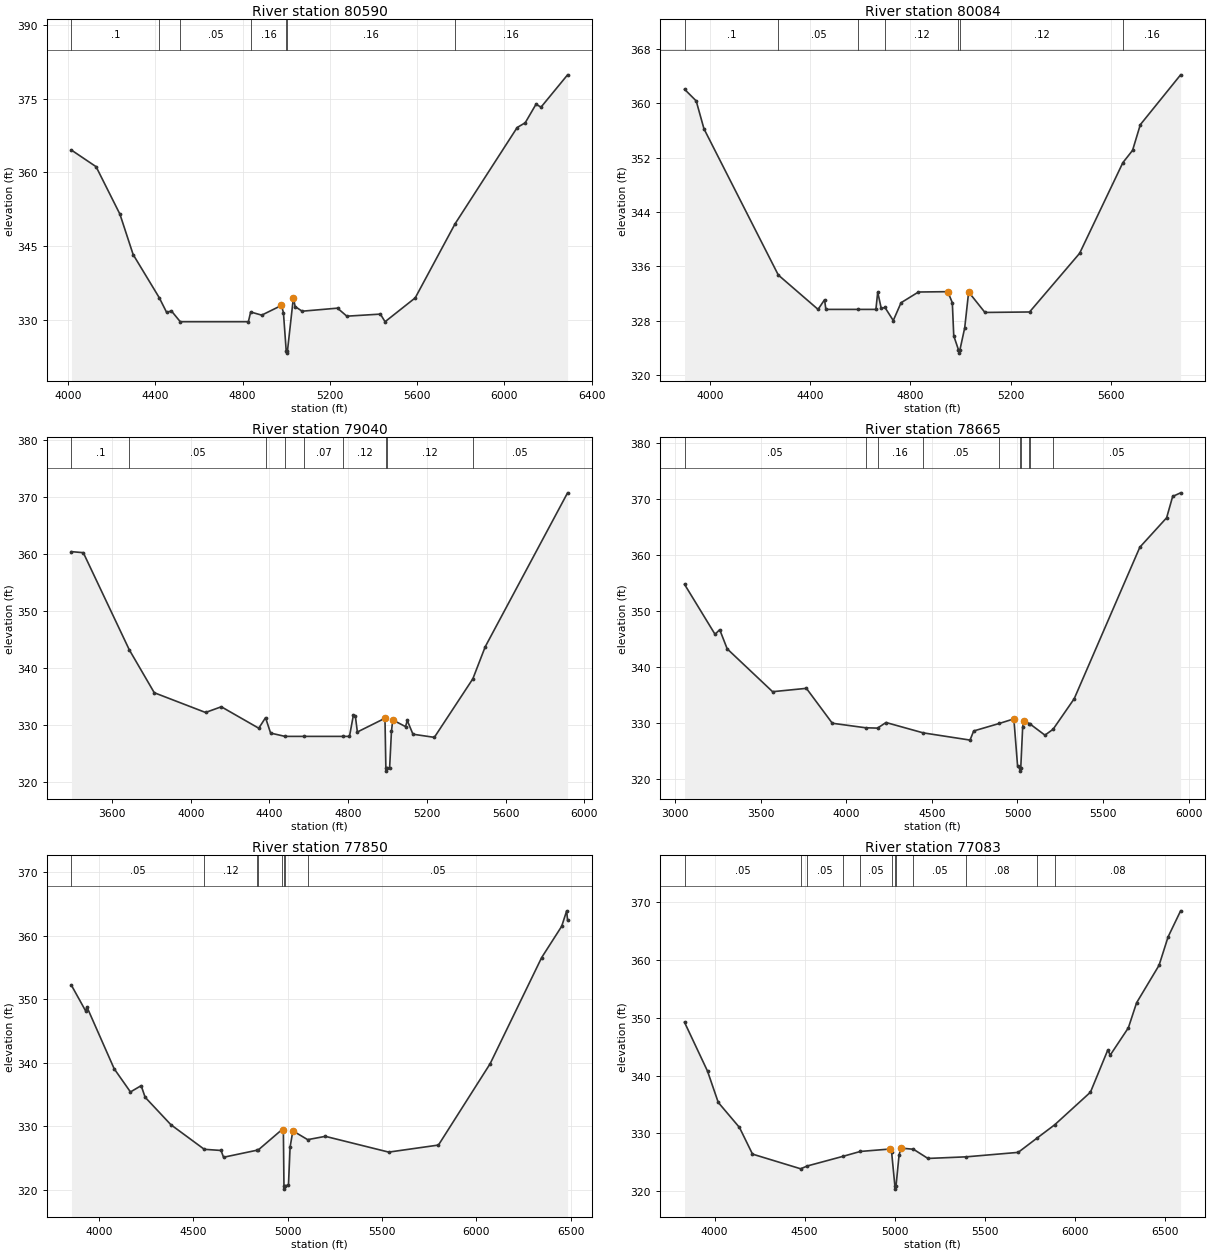
Type RM Length L Ch R = 1 ,80590   ,506,506,506
BEGIN DESCRIPTION:
COTTONWOOD CREEK 91.0
END DESCRIPTION:
XS GIS Cut Line= 3
      3581052.25     10640146.51      3582163.36      10639722.9
      3583093.92     10639167.34
#Sta/Elev= 30
  4016.3  364.54  4129.1  361.17  4238.2  351.53  4298.9  343.31  4418.5  334.54
  4452.3  331.56  4474.1  331.86  4514.8  329.66  4826.8  329.66  4837.3  331.64
  4887.9     331  4978.2  332.97  4987.4  331.52    5000  323.78  5002.7  323.28
    5006  323.78    5033  334.56  5040.9  332.75    5073   331.8  5235.1  332.42
  5277.9  330.79  5431.6  331.21    5453  329.66  5591.2  334.51  5773.7  349.56
  6058.2  369.13  6095.2   370.1  6144.4  373.85  6167.7  373.28  6289.2  379.84
#Mann= 7 ,-1 , 0
  4016.3      .1       0  4418.5     .16       0  4514.8     .05       0
  4837.3     .16       0    5000     .07       0    5006     .16       0
  5773.7     .16       0
Bank Sta=4978.2,5033
XS Rating Curve= 0 ,0
Exp/Cntr=0.3,0.1

Type RM Length L Ch R = 1 ,80084   ,1044,1044,1044
BEGIN DESCRIPTION:
COTTONWOOD CREEK 90.0
END DESCRIPTION:
XS GIS Cut Line= 3
      3581249.57      10640460.2      3582249.61     10640110.19
      3583049.61     10639660.19
#Sta/Elev= 30
  3899.3  362.08  3945.9  360.36  3976.9  356.25  4273.2  334.72  4431.7  329.66
  4457.5  331.08  4462.8  329.66  4592.1  329.66  4662.2  329.66  4669.4   332.2
  4683.4  329.82  4698.4  329.94  4731.4  328.02  4762.4  330.64  4831.7  332.22
  4948.6  332.27  4966.8  330.64  4972.5  325.77  4991.2  323.72  4993.9  323.22
  4997.2  323.72  5016.2  326.95  5031.8  332.22  5096.8  329.21  5274.7  329.28
  5474.2  337.92  5646.6  351.27  5685.2  353.08  5716.1  356.86  5876.7   364.2
#Mann= 7 ,-1 , 0
  3899.3      .1       0  4273.2     .05       0  4592.1     .16       0
  4698.4     .12       0  4991.2     .07       0  4997.2     .12       0
  5646.6     .16       0
Bank Sta=4948.6,5031.8
XS Rating Curve= 0 ,0
Exp/Cntr=0.3,0.1

Type RM Length L Ch R = 1 ,79040   ,375,375,375
BEGIN DESCRIPTION:
COTTONWOOD CREEK 89.0
END DESCRIPTION:
XS GIS Cut Line= 3
      3581299.65     10640560.19      3582899.61     10640660.19
      3583699.65     10640210.17
#Sta/Elev= 30
  3393.8   360.4  3453.9  360.22  3687.7  343.19  3814.6  335.67  4075.1  332.21
  4155.2  333.21  4345.6  329.45  4379.9   331.3  4405.7   328.6  4478.8  328.02
  4577.7  328.02  4775.5  328.02  4806.5  328.02  4826.5  331.76  4836.6  331.51
  4846.6  328.79  4986.9   331.2  4991.4  322.43  4994.1  321.93  4997.4  322.43
  5010.6  322.56  5019.8   328.9  5026.5   330.9  5091.5  329.73  5100.1  330.81
  5129.1   328.4  5237.8  327.85  5433.5  338.12  5496.3  343.73  5914.8  370.71
#Mann= 9 ,-1 , 0
  3393.8      .1       0  3687.7     .05       0  4379.9     .07       0
  4478.8     .12       0  4577.7     .07       0  4775.5     .12       0
  4991.4     .07       0  4997.4     .12       0  5433.5     .05       0
Bank Sta=4986.9,5026.5
XS Rating Curve= 0 ,0
Exp/Cntr=0.3,0.1

Type RM Length L Ch R = 1 ,78665   ,815,815,815
BEGIN DESCRIPTION:
COTTONWOOD CREEK 88.0
END DESCRIPTION:
XS GIS Cut Line= 3
       3581424.4     10641937.51      3583216.11     10640888.88
       3583735.8     10640251.38
#Sta/Elev= 30
  3054.8  354.81  3233.2  345.87  3260.5   346.7  3304.2  343.27  3569.5  335.61
    3767  336.21  3918.3  329.97  4113.1  329.16  4182.4   329.1  4232.2   330.1
  4449.4  328.25    4723  326.96  4744.4  328.59  4893.8  329.93  4979.1  330.75
  5000.6   322.4  5013.3  321.91    5016  321.41  5019.3  321.91  5030.6  329.34
  5037.8  330.45  5068.8  329.91  5075.7  329.79  5160.7  327.84  5208.4   328.9
  5331.6  334.35  5715.1  361.44  5871.6   366.7  5906.8  370.51  5953.3  371.16
#Mann= 10 ,-1 , 0
  3054.8     .05       0  4113.1     .12       0  4182.4     .16       0
  4449.4     .05       0  4893.8     .12       0  5013.3     .07       0
  5019.3     .12       0  5068.8     .16       0  5075.7     .12       0
  5208.4     .05       0
Bank Sta=4979.1,5037.8
XS Rating Curve= 0 ,0
Exp/Cntr=0.3,0.1

Type RM Length L Ch R = 1 ,77850   ,767,767,767
BEGIN DESCRIPTION:
COTTONWOOD CREEK 87.0
END DESCRIPTION:
XS GIS Cut Line= 3
      3582125.81     10642361.12      3583375.83     10641465.27
       3583716.1     10640430.57
#Sta/Elev= 30
  3855.6  352.19  3931.2  348.14  3937.3   348.8  4081.7  339.08  4167.9  335.43
  4224.7  336.42  4245.6   334.6    4382  330.28    4559  326.41  4647.7  326.23
  4660.8  325.16  4836.6  326.26  4845.9  326.34  4971.2  329.53  4977.7  329.48
  4980.8  320.65  4983.6  320.15  4986.8  320.65  5004.7  320.81  5013.3  326.77
    5028  329.31  5106.4  327.93    5200  328.45  5535.7  325.97  5798.9  327.08
  6072.6  339.87  6345.4  356.56  6451.5  361.48  6477.9  363.91  6482.7  362.41
#Mann= 8 ,-1 , 0
  3855.6     .05       0    4559     .12       0  4836.6     .16       0
  4845.9     .05       0  4971.2     .16       0  4980.8     .07       0
  4986.8     .16       0  5106.4     .05       0
Bank Sta=4977.7,5028
XS Rating Curve= 0 ,0
Exp/Cntr=0.3,0.1

Type RM Length L Ch R = 1 ,77083   ,68,68,68
BEGIN DESCRIPTION:
COTTONWOOD CREEK 86.0
END DESCRIPTION:
XS GIS Cut Line= 5
      3583132.77     10642746.95      3583716.11     10642424.03
      3583716.11     10641996.95      3583716.11     10641835.49
      3583809.86     10640340.72
#Sta/Elev= 30
  3833.4  349.25  3961.1  340.79  4020.6  335.38  4138.4  331.04  4210.7  326.43
    4478  323.89  4515.1  324.38  4711.2  326.03  4809.2  326.89    4974  327.31
  4982.9  326.72    5001  320.87  5003.7  320.37    5007  320.87    5024  326.23
    5034  327.47  5103.9  327.27  5184.2  325.68  5397.5  325.96  5685.2  326.73
  5789.5   329.2  5887.5   331.5    6086  337.14  6182.1  344.43  6196.2  343.58
  6296.4  348.28  6342.1  352.62  6466.7   359.1  6516.8  364.01  6586.4  368.53
#Mann= 12 ,-1 , 0
  3833.4     .05       0    4478     .08       0  4515.1     .05       0
  4711.2     .08       0  4809.2     .05       0  4982.9     .16       0
    5001     .07       0    5007     .16       0  5103.9     .05       0
  5397.5     .08       0  5789.5     .05       0  5887.5     .08       0
Bank Sta=4974,5034
XS Rating Curve= 0 ,0
Exp/Cntr=0.3,0.1

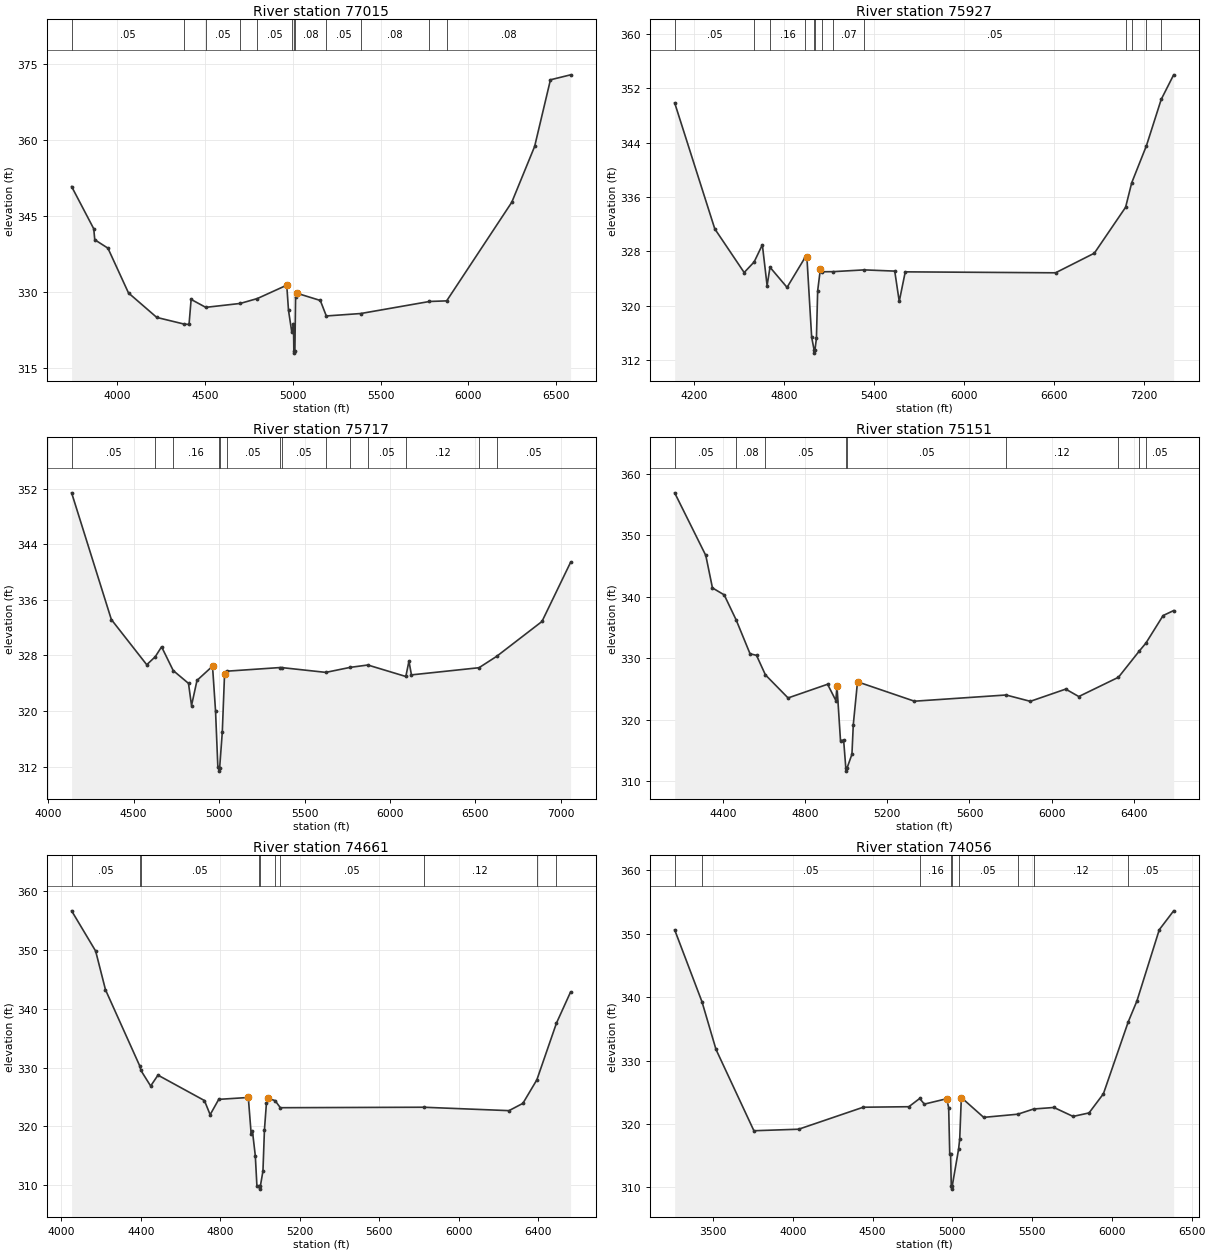
Type RM Length L Ch R = 1 ,77015   ,1088,1088,1088
BEGIN DESCRIPTION:
COTTONWOOD CREEK 85.0
END DESCRIPTION:
XS GIS Cut Line= 5
      3583138.02     10642809.43      3583768.19     10642450.08
      3583768.19     10642054.24      3583804.65     10641731.33
      3583867.15     10640335.45
#Sta/Elev= 30
  3739.2  350.77  3865.4  342.42  3871.1  340.26  3946.1   338.6  4063.4  329.75
  4224.5  324.92  4379.8  323.61  4408.4  323.53  4420.2  328.48  4503.5  326.91
  4699.7  327.68  4797.7  328.65  4965.2  331.29  4975.2  326.31  4994.1  321.99
  5003.6  323.68  5005.6  318.37  5008.4  317.87  5011.6  318.37  5015.5  328.91
  5025.6  329.67  5156.4  328.27  5190.6  325.21  5386.6  325.69  5778.5  328.07
  5876.5  328.19  6247.6  347.67  6377.8  358.69  6467.9  371.85  6582.7  372.83
#Mann= 12 ,-1 , 0
  3739.2     .05       0  4379.8     .08       0  4503.5     .05       0
  4699.7     .08       0  4797.7     .05       0  4994.1     .08       0
  5005.6     .07       0  5011.6     .08       0  5190.6     .05       0
  5386.6     .08       0  5778.5     .05       0  5876.5     .08       0
Bank Sta=4965.2,5025.6
XS Rating Curve= 0 ,0
Exp/Cntr=0.3,0.1

Type RM Length L Ch R = 1 ,75927   ,210,210,210
BEGIN DESCRIPTION:
Mapping XS 3e256e22
END DESCRIPTION:
XS GIS Cut Line= 3
      3583184.89     10642830.27      3584257.77     10642476.12
      3584148.44     10640284.27
#Sta/Elev= 30
  4071.3  349.87  4338.5   331.3  4534.3  324.86  4600.8  326.42  4655.5  328.95
  4687.1  322.93  4706.4  325.64    4820  322.67  4939.3  327.05  4952.2  327.13
    4984  315.33    5000  313.48  5002.7  312.98    5006  313.48  5015.7  315.14
    5024  322.16  5042.2  325.41  5051.9  324.97  5128.6  324.99  5334.1  325.25
  5537.5  325.07  5567.5   320.6  5607.6  324.96  6608.8  324.82  6867.3  327.71
  7075.6  334.48  7116.2  338.08  7214.5  343.56  7312.9  350.38  7395.7     354
#Mann= 13 ,-1 , 0
  4071.3     .05       0  4600.8     .08       0  4706.4     .16       0
  4939.3     .12       0    5000     .07       0    5006     .12       0
  5051.9     .05       0  5128.6     .07       0  5334.1     .05       0
  7075.6     .12       0  7116.2     .05       0  7214.5     .16       0
  7312.9     .05       0
Bank Sta=4952.2,5042.2
XS Rating Curve= 0 ,0
Exp/Cntr=0.3,0.1

Type RM Length L Ch R = 1 ,75717   ,566,566,566
BEGIN DESCRIPTION:
COTTONWOOD CREEK 84.0
END DESCRIPTION:
XS GIS Cut Line= 3
      3583218.28     10642900.38      3583931.82     10642671.21
      3585983.88     10643379.54
#Sta/Elev= 30
  4136.9  351.38  4369.4  333.16  4576.6  326.66  4626.4  327.81  4663.4  329.24
  4731.6  325.82    4821  323.98  4838.7  320.79  4870.8  324.41  4961.6  326.45
  4979.2  320.03  4992.8  311.94  4997.4  311.86  5000.1  311.36  5003.4  311.86
  5018.7  316.95  5032.1  325.37  5043.7  325.73  5354.1  326.25  5365.7  326.25
  5624.7  325.56  5767.2  326.28  5870.5  326.62  6092.9  324.97  6111.2  327.18
  6125.7   325.2  6521.1  326.23  6624.2  327.86  6889.7  332.88  7057.2  341.39
#Mann= 14 ,-1 , 0
  4136.9     .05       0  4626.4     .08       0  4731.6     .16       0
  4997.4     .07       0  5003.4     .16       0  5043.7     .05       0
  5354.1     .16       0  5365.7     .05       0  5624.7     .16       0
  5767.2     .07       0  5870.5     .05       0  6092.9     .12       0
  6521.1     .16       0  6624.2     .05       0
Bank Sta=4961.6,5032.1
XS Rating Curve= 0 ,0
Exp/Cntr=0.3,0.1

Type RM Length L Ch R = 1 ,75151   ,490,490,490
BEGIN DESCRIPTION:
COTTONWOOD CREEK 83.0
END DESCRIPTION:
XS GIS Cut Line= 3
      3583149.63      10642960.2      3583949.61     10643210.19
      3585499.65      10643560.2
#Sta/Elev= 30
  4166.1  356.93  4317.5  346.73  4349.9  341.44    4407  340.31  4465.7  336.19
  4532.8  330.71  4564.2  330.46  4607.5  327.28  4717.7  323.52  4909.9  325.75
  4950.3  323.09  4955.5  325.48  4972.8  316.55    4988  316.67  4998.6   312.1
  5001.4   311.6  5004.6   312.1  5028.4  314.35    5035  319.19  5055.5  326.15
  5332.3  322.99    5778     324  5896.1  322.97  6068.2  324.96  6131.9  323.75
  6324.9  326.89  6425.4  331.13  6458.3  332.45    6542  336.94  6593.3  337.75
#Mann= 9 ,-1 , 0
  4166.1     .05       0  4465.7     .08       0  4607.5     .05       0
  4998.6     .03       0  5004.6     .05       0    5778     .12       0
  6324.9     .05       0  6425.4     .16       0  6458.3     .05       0
Bank Sta=4955.5,5055.5
XS Rating Curve= 0 ,0
Exp/Cntr=0.3,0.1

Type RM Length L Ch R = 1 ,74661   ,605,605,605
BEGIN DESCRIPTION:
COTTONWOOD CREEK 82.0
END DESCRIPTION:
XS GIS Cut Line= 3
      3583099.58     10643060.17      3583849.61     10643660.19
       3585399.6     10643710.19
#Sta/Elev= 30
  4051.8  356.66  4172.7  349.82  4222.3  343.23  4395.2  330.24  4400.8   329.5
  4449.6  326.86  4486.4  328.71  4720.2  324.39    4749  321.98  4792.2  324.59
  4941.1  324.91  4955.5   318.7  4961.9  319.19  4976.3     315  4984.3  309.93
  4995.7  309.82  4998.4  309.32  5001.7  309.82  5014.8   312.4  5022.3  319.42
  5032.3  323.95  5042.3  324.76    5076  324.37  5102.3  323.17  5823.8  323.25
    6253  322.67    6323  323.91  6393.3  327.91  6492.1  337.57  6563.1  342.86
#Mann= 10 ,-1 , 0
  4051.8     .05       0  4395.2     .08       0  4400.8     .05       0
  4995.7     .03       0  5001.7     .05       0    5076     .16       0
  5102.3     .05       0  5823.8     .12       0  6393.3     .16       0
  6492.1     .05       0
Bank Sta=4941.1,5042.3
XS Rating Curve= 0 ,0
Exp/Cntr=0.3,0.1

Type RM Length L Ch R = 1 ,74056   ,507,507,507
BEGIN DESCRIPTION:
COTTONWOOD CREEK 81.0
END DESCRIPTION:
XS GIS Cut Line= 3
      3582599.61     10644660.19      3584199.61     10644010.19
      3585599.63     10644060.19
#Sta/Elev= 30
  3259.2  350.61  3430.6  339.25  3518.2  331.75  3755.9  318.92  4036.3  319.16
  4441.3  322.63  4727.1  322.71  4795.2  324.01  4824.3  323.12  4964.6  323.97
  4976.8  322.55  4983.5  315.29  4988.7  315.29  4993.2  310.21  4995.9  309.71
  4999.2  310.21    5039  316.02  5046.2  317.67  5056.2  324.16  5196.3  321.03
  5410.5  321.53  5509.3  322.35  5636.6  322.59  5756.7  321.18  5856.7  321.73
  5946.8  324.75  6102.5   336.1  6156.9  339.39    6297  350.63  6387.1  353.61
#Mann= 9 ,-1 , 0
  3259.2     .08       0  3430.6     .05       0  4795.2     .16       0
  4993.2     .07       0  4999.2     .16       0    5039     .05       0
  5410.5     .07       0  5509.3     .12       0  6102.5     .05       0
Bank Sta=4964.6,5056.2
XS Rating Curve= 0 ,0
Exp/Cntr=0.3,0.1

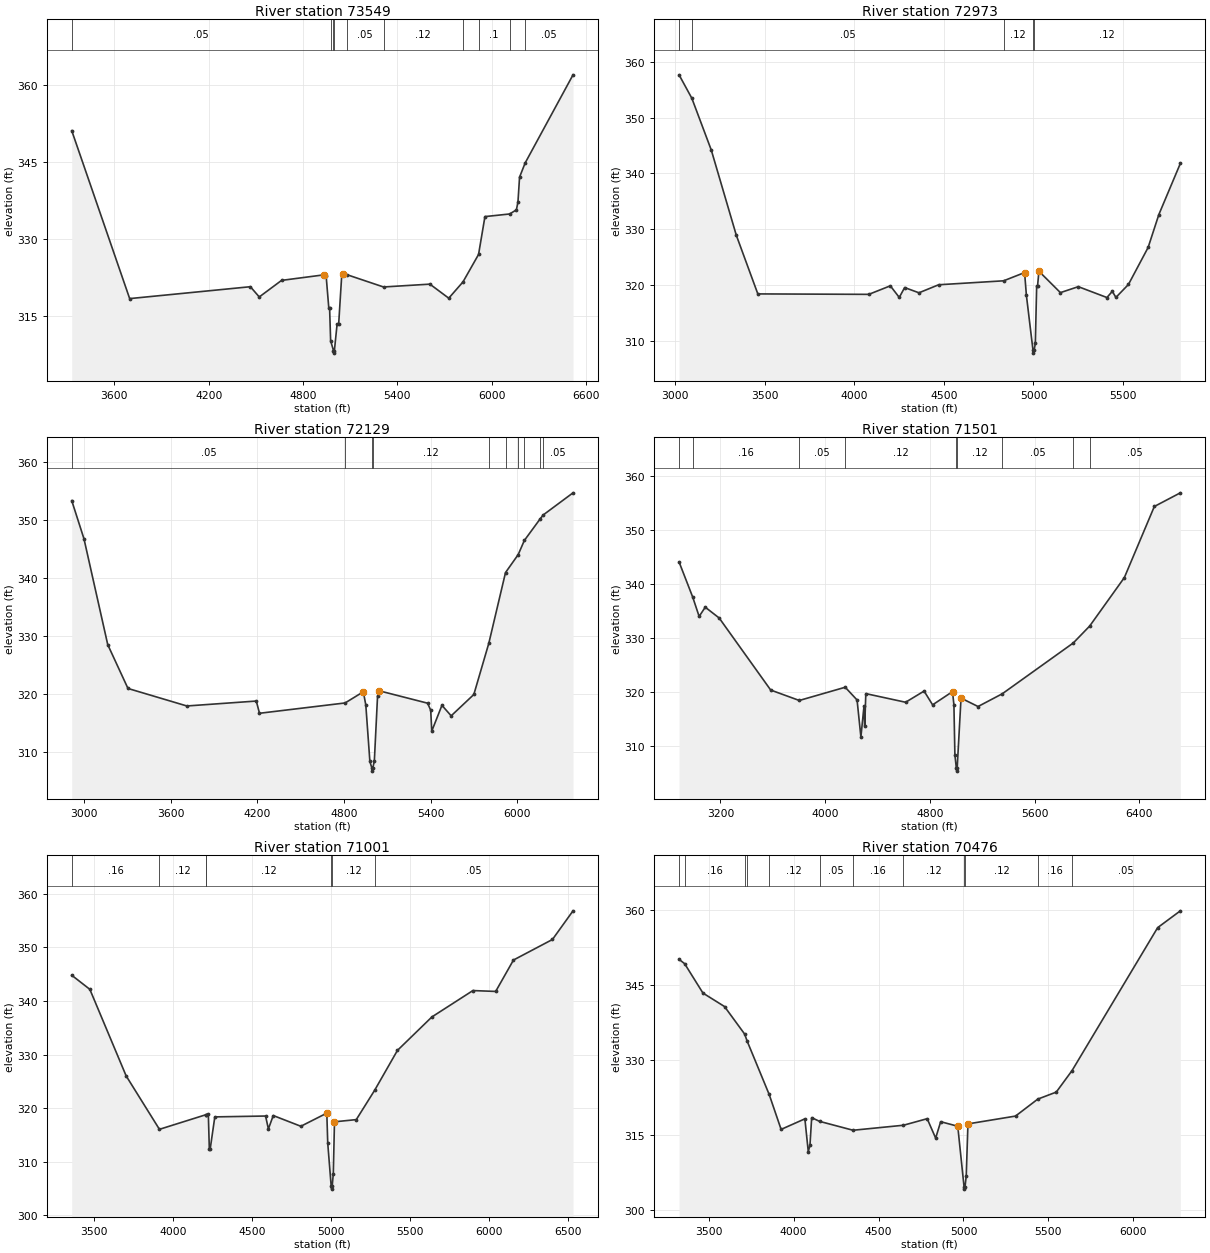
Type RM Length L Ch R = 1 ,73549   ,576,576,576
BEGIN DESCRIPTION:
COTTONWOOD CREEK 80.0
END DESCRIPTION:
XS GIS Cut Line= 3
      3582649.62     10644810.19      3584249.61     10644460.19
      3585799.58     10644510.19
#Sta/Elev= 30
  3328.7  351.08  3697.2  318.43  4464.9  320.74  4521.6  318.75  4663.4  321.97
  4935.8  323.06  4947.1  322.78    4964  316.54    4969  316.54  4975.5  310.25
  4993.5  308.33  4996.3  307.83  4999.5  308.33  5016.5  313.43  5026.6  313.45
  5046.6  323.23  5056.6  323.23  5077.2   323.1  5311.8  320.69  5606.9  321.24
  5726.9  318.51  5817.5  321.68  5916.4  327.01    5957  334.37  6114.1  334.88
  6157.1  335.68  6167.1  337.23  6177.2  342.04    6213  344.81  6517.3  361.93
#Mann= 10 ,-1 , 0
  3328.7     .05       0  4975.5     .16       0  4993.5     .07       0
  4999.5     .16       0  5077.2     .05       0  5311.8     .12       0
  5817.5     .07       0  5916.4      .1       0  6114.1     .16       0
    6213     .05       0
Bank Sta=4935.8,5056.6
XS Rating Curve= 0 ,0
Exp/Cntr=0.3,0.1

Type RM Length L Ch R = 1 ,72973   ,844,844,844
BEGIN DESCRIPTION:
COTTONWOOD CREEK 79.0
END DESCRIPTION:
XS GIS Cut Line= 3
      3582549.61     10644910.19      3584549.61     10644910.19
      3585349.61     10644910.19
#Sta/Elev= 30
  3020.4  357.67  3091.9  353.46  3200.4  344.18  3340.4  328.88  3460.4  318.38
  4080.4   318.3  4200.4  319.83  4250.4  317.75  4280.4  319.52  4360.4  318.58
  4470.4  320.02  4833.3  320.73  4950.4  322.21  4960.4  318.15  4997.4  308.26
  5000.1  307.76  5003.4  308.26  5010.4   309.5  5017.9  319.83  5022.9  319.83
  5030.4  322.45  5150.4  318.61  5250.4  319.68  5410.4  317.73  5440.4  318.85
  5460.4  317.75  5530.4  320.07  5640.4  326.71  5700.4  332.62  5820.4  341.78
#Mann= 5 ,-1 , 0
  3020.4     .08       0  3091.9     .05       0  4833.3     .12       0
  4997.4     .07       0  5003.4     .12       0
Bank Sta=4950.4,5030.4
XS Rating Curve= 0 ,0
Exp/Cntr=0.3,0.1

Type RM Length L Ch R = 1 ,72129   ,628,628,628
BEGIN DESCRIPTION:
COTTONWOOD CREEK 78.0
END DESCRIPTION:
XS GIS Cut Line= 4
      3582593.92     10644985.66      3584425.53     10645680.11
       3584659.9     10645567.26      3585640.83     10644785.99
#Sta/Elev= 30
  2913.8  353.41  2998.6  346.82  3163.4  328.55  3303.5     321  3711.3  317.98
  4192.5  318.83  4214.6  316.72  4807.7   318.5  4934.1  320.43  4951.2  318.14
  4979.4  308.41  4993.5  307.24  4996.2  306.74  4999.5  307.24  5010.4  308.53
  5032.5  319.67  5041.7  320.61  5379.3  318.46  5400.9  317.24  5408.1  313.64
  5478.6  318.09  5542.6  316.28  5699.6  319.96  5803.4   328.8    5919  340.99
  6007.1   344.1  6049.5  346.53  6157.1  350.19  6180.1  350.93  6386.8  354.75
#Mann= 10 ,-1 , 0
  2913.8     .05       0  4807.7     .12       0  4993.5     .07       0
  4999.5     .12       0  5803.4     .16       0    5919     .05       0
  6007.1     .16       0  6049.5     .05       0  6157.1     .16       0
  6180.1     .05       0
Bank Sta=4934.1,5041.7
XS Rating Curve= 0 ,0
Exp/Cntr=0.3,0.1

Type RM Length L Ch R = 1 ,71501   ,500,500,500
BEGIN DESCRIPTION:
COTTONWOOD CREEK 77.0
END DESCRIPTION:
XS GIS Cut Line= 3
      3583045.31     10646695.74      3585224.14      10645775.6
       3586630.4     10645367.61
#Sta/Elev= 30
  2884.1  344.14  2988.9  337.59  3037.5  334.04  3084.2  335.75  3190.6  333.75
  3584.2   320.4  3802.6  318.47  4153.4  320.92    4244  318.56  4273.2   311.7
  4296.9  317.44  4302.3  313.73  4310.8  319.74  4614.7  318.14  4755.9  320.21
    4821  317.66    4973  320.11  4983.8  317.65  4991.2  308.41  5002.5  305.88
  5005.3  305.38  5008.5  305.88  5038.1  318.91  5168.1  317.35  5353.1  319.71
  5895.4  329.12  6020.9  332.26  6285.8  341.24  6514.8  354.41  6713.5  356.94
#Mann= 9 ,-1 , 0
  2884.1     .05       0  2988.9     .16       0  3802.6     .05       0
  4153.4     .12       0  5002.5     .07       0  5008.5     .12       0
  5353.1     .05       0  5895.4     .12       0  6020.9     .05       0
Bank Sta=4973,5038.1
XS Rating Curve= 0 ,0
Exp/Cntr=0.3,0.1

Type RM Length L Ch R = 1 ,71001   ,525,525,525
BEGIN DESCRIPTION:
COTTONWOOD CREEK 75.0
END DESCRIPTION:
XS GIS Cut Line= 2
      3583488.03      10646713.1       3586576.5     10645993.03
#Sta/Elev= 30
  3358.8  344.81  3473.4  342.18  3703.2  326.02  3913.6  316.06    4206  318.77
  4210.6   318.8    4223  318.83  4229.3  312.37  4234.4  312.33    4264  318.38
  4585.1  318.54  4602.9  316.13  4633.7  318.63  4808.2  316.63  4972.5  319.08
  4978.4  313.47  5000.3   305.4  5003.1   304.9  5006.3   305.4  5013.6  307.79
    5021  317.46  5158.9  317.87    5275  323.34  5419.4  330.79  5637.3  337.03
  5896.7  341.95  6040.8  341.79  6153.4  347.65  6399.8  351.48  6530.1  356.83
#Mann= 7 ,-1 , 0
  3358.8     .16       0  3913.6     .12       0    4206     .16       0
  4210.6     .12       0  5000.3     .07       0  5006.3     .12       0
    5275     .05       0
Bank Sta=4972.5,5021
XS Rating Curve= 0 ,0
Exp/Cntr=0.3,0.1

Type RM Length L Ch R = 1 ,70476   ,733,733,733
BEGIN DESCRIPTION:
COTTONWOOD CREEK 74.0
END DESCRIPTION:
XS GIS Cut Line= 2
       3583488.8     10646808.84      3586440.18     10646878.29
#Sta/Elev= 30
    3325  350.09  3357.9  349.22  3465.8  343.35  3592.8  340.66  3711.3  335.16
  3725.9  333.77  3855.5  323.12    3926  316.12    4066  318.23    4086  311.67
    4096  312.98    4106  318.47  4152.1  317.73  4349.8  315.95  4646.5  316.95
  4786.2  318.26  4836.2  314.38  4865.7  317.66  4966.3  316.75  5003.3  304.69
    5006  304.19  5009.3  304.69  5016.3  306.86  5026.3  317.22  5306.4  318.78
  5437.5  322.17  5546.4  323.57  5639.4  327.87  6143.5  356.42  6277.2  359.78
#Mann= 12 ,-1 , 0
    3325     .12       0  3357.9     .16       0  3711.3     .12       0
  3725.9     .16       0  3855.5     .12       0  4152.1     .05       0
  4349.8     .16       0  4646.5     .12       0  5003.3     .07       0
  5009.3     .12       0  5437.5     .16       0  5639.4     .05       0
Bank Sta=4966.3,5026.3
XS Rating Curve= 0 ,0
Exp/Cntr=0.3,0.1