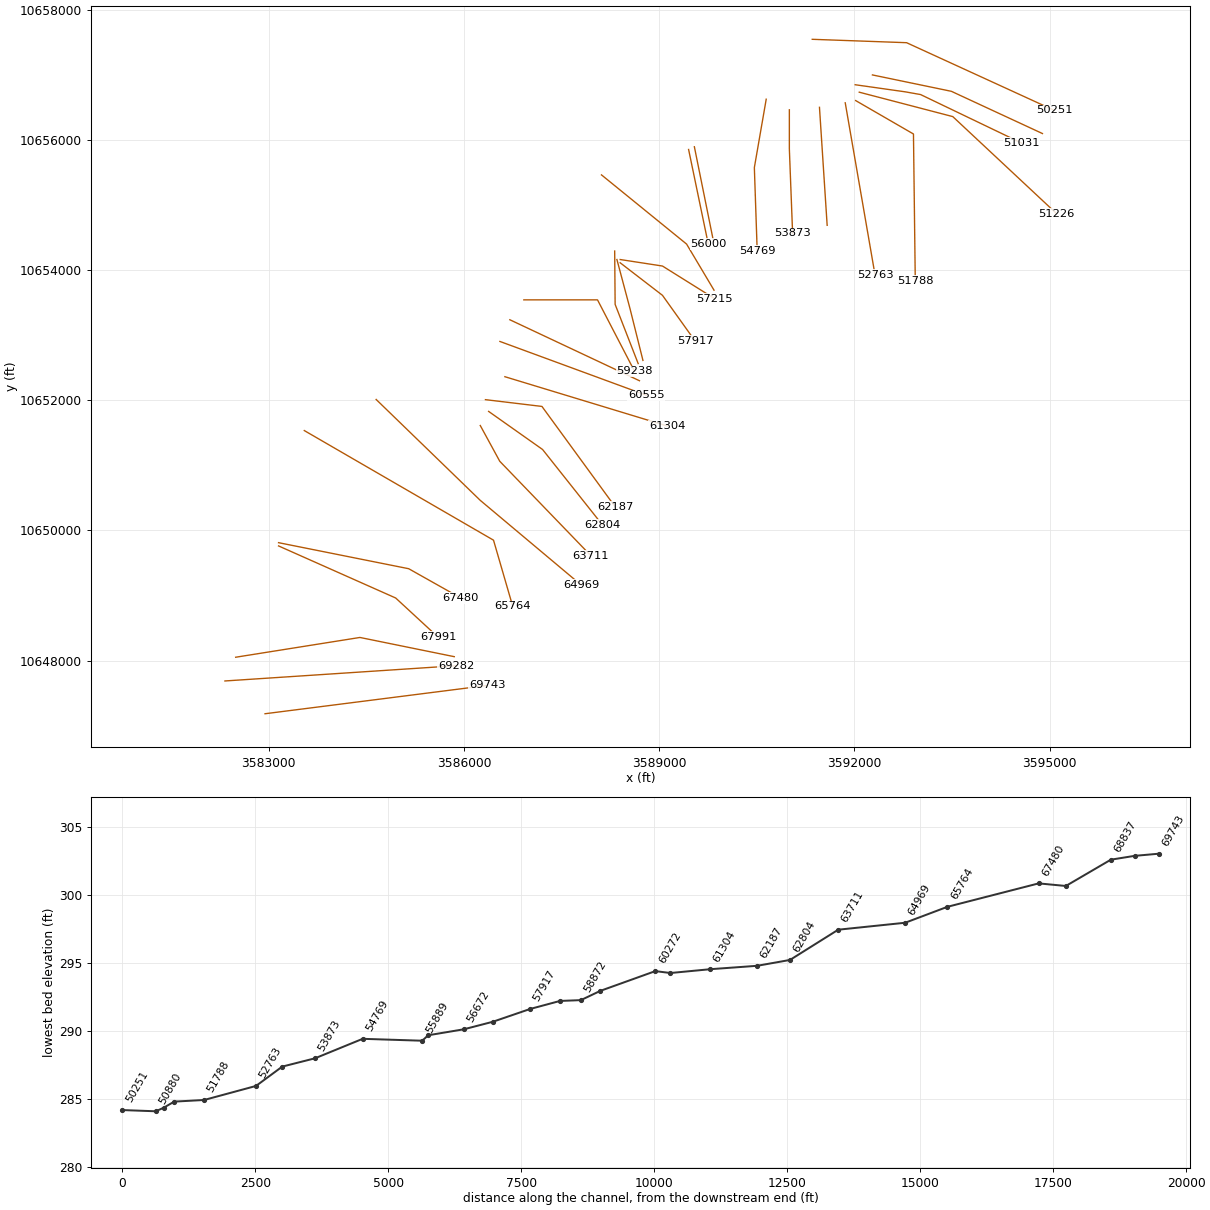
HEC-RAS study COTTONWOOD CREEK.prj: COTTONWOOD CREEK Base Level Engineering

--- COTTONWOOD CREEK.g01 (geometry) --- (continued)

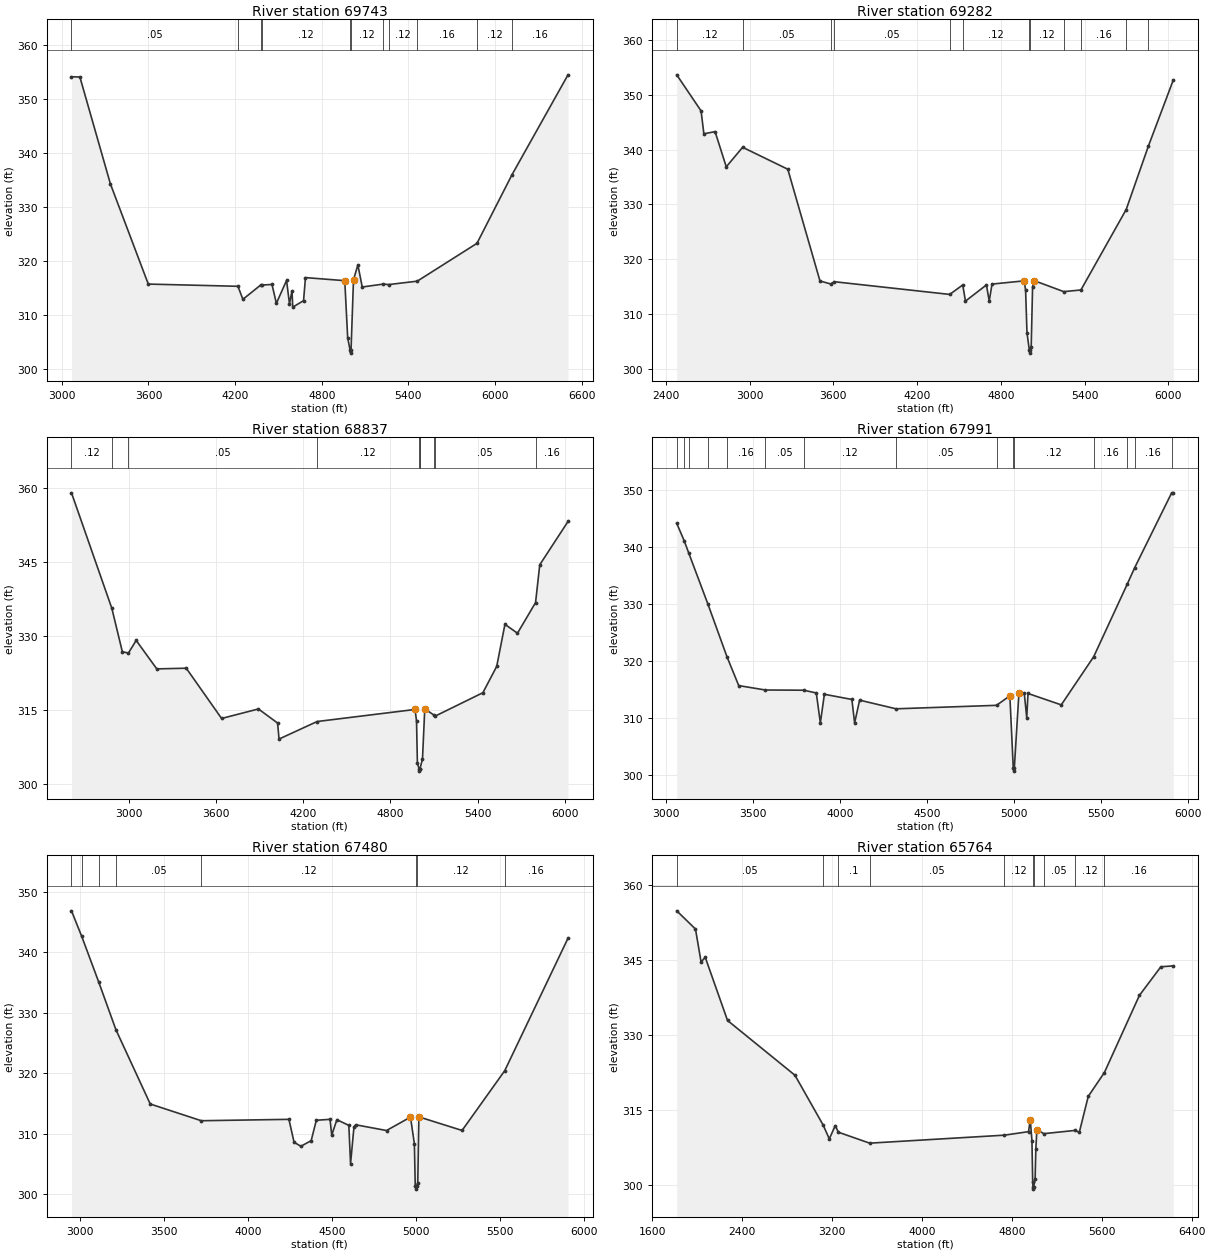
Type RM Length L Ch R = 1 ,69743   ,461,461,461
BEGIN DESCRIPTION:
COTTONWOOD CREEK 73.0
END DESCRIPTION:
XS GIS Cut Line= 2
      3582941.92     10647182.11      3586353.42     10647616.14
#Sta/Elev= 30
  3066.8  354.17    3125  354.11  3336.6  334.31  3598.7  315.79  4219.7  315.38
    4254  312.97  4376.1  315.59  4385.9  315.61  4455.6  315.72  4485.8  312.22
  4556.4  316.46  4576.6  312.15  4594.2  314.56  4599.2  311.52  4674.1  312.72
  4687.4  316.99  4959.6  316.42  4979.8  305.84  4996.9  303.51  4999.7  303.01
  5002.9  303.51  5020.1  316.62  5050.4  319.33  5080.6  315.25  5226.1  315.79
  5263.8   315.7  5461.7  316.33  5875.3  323.33  6117.9  336.03  6505.8  354.52
#Mann= 11 ,-1 , 0
  3066.8     .05       0  4219.7     .12       0  4376.1     .16       0
  4385.9     .12       0  4996.9     .07       0  5002.9     .12       0
  5226.1     .05       0  5263.8     .12       0  5461.7     .16       0
  5875.3     .12       0  6117.9     .16       0
Bank Sta=4959.6,5020.1
XS Rating Curve= 0 ,0
Exp/Cntr=0.3,0.1

Type RM Length L Ch R = 1 ,69282   ,445,445,445
BEGIN DESCRIPTION:
COTTONWOOD CREEK 72.0
END DESCRIPTION:
XS GIS Cut Line= 2
      3582325.61     10647685.58      3585875.28     10647919.91
#Sta/Elev= 30
  2477.5  353.67  2651.9  347.08  2671.9   342.9  2752.1   343.3  2832.3  336.87
  2949.6  340.44  3273.2  336.43  3503.7  316.03  3580.5  315.48  3606.6  315.89
  4433.1  313.57  4526.7   315.3    4546  312.35  4696.3   315.3  4716.4  312.35
  4736.4  315.46  4966.9  316.05  4976.9  314.38  4986.9  306.56    5004  303.35
  5006.7  302.85    5010  303.35    5017  303.88    5027  314.96  5037.1   316.1
  5250.4  314.08  5373.2  314.38  5697.6  329.07  5856.4  340.63  6034.9  352.71
#Mann= 12 ,-1 , 0
  2477.5     .12       0  2949.6     .05       0  3580.5     .16       0
  3606.6     .05       0  4433.1      .1       0  4526.7     .12       0
    5004     .07       0    5010     .12       0  5250.4     .05       0
  5373.2     .16       0  5697.6     .05       0  5856.4     .16       0
Bank Sta=4966.9,5037.1
XS Rating Curve= 0 ,0
Exp/Cntr=0.3,0.1

Type RM Length L Ch R = 1 ,68837   ,846,846,846
BEGIN DESCRIPTION:
COTTONWOOD CREEK 71.0
END DESCRIPTION:
XS GIS Cut Line= 3
       3582490.5     10648050.16      3584400.25     10648353.98
      3585849.95     10648058.83
#Sta/Elev= 30
  2607.3  359.11  2884.8  335.63  2956.6  326.85  2998.4  326.54  3051.9  329.13
  3193.7  323.34  3396.2  323.48  3639.2  313.27  3892.4   315.2    4024  312.34
  4034.1  309.09  4296.1  312.65    4969   315.1  4979.2  312.75  4985.2  304.17
  4996.6  303.07  4999.4  302.57  5002.6  303.07  5003.1  303.09  5020.1  305.02
  5035.8  315.22  5097.8  313.98  5104.9  313.71  5435.3   318.5  5530.3  323.84
    5587  332.39  5673.2  330.59  5797.4  336.81  5826.3  344.49  6020.5  353.29
#Mann= 10 ,-1 , 0
  2607.3     .12       0  2884.8     .16       0  2998.4     .05       0
  4296.1     .12       0  4996.6     .07       0  5002.6     .12       0
  5003.1     .05       0  5097.8     .12       0  5104.9     .05       0
  5797.4     .16       0
Bank Sta=4969,5035.8
XS Rating Curve= 0 ,0
Exp/Cntr=0.3,0.1

Type RM Length L Ch R = 1 ,67991   ,511,511,511
BEGIN DESCRIPTION:
COTTONWOOD CREEK 70.0
END DESCRIPTION:
XS GIS Cut Line= 3
      3583149.56     10649760.21      3584949.61     10648960.19
       3585599.6      10648360.2
#Sta/Elev= 30
  3059.4   344.1    3102  341.06  3127.9  338.93  3238.1  329.98  3348.3  320.69
  3415.8  315.64  3568.7  314.87  3789.1  314.83  3861.7  314.35    3885  309.09
  3908.2  314.12  4066.2  313.21    4082  309.09  4110.7  313.09  4320.1  311.57
  4897.9  312.18  4974.5  313.85  4994.1  301.14  4996.8  300.64  5000.1  301.14
  5026.5   314.3  5057.3   314.3  5071.5     310  5078.8  314.26  5269.9  312.26
  5456.3   320.7  5648.8   333.4  5692.4  336.34  5904.7  349.45  5913.8  349.45
#Mann= 15 ,-1 , 0
  3059.4     .16       0    3102     .12       0  3127.9     .16       0
  3238.1     .12       0  3348.3     .16       0  3568.7     .05       0
  3789.1     .12       0  4320.1     .05       0  4897.9     .12       0
  4994.1     .07       0  5000.1     .12       0  5456.3     .16       0
  5648.8     .05       0  5692.4     .16       0  5904.7     .05       0
Bank Sta=4974.5,5026.5
XS Rating Curve= 0 ,0
Exp/Cntr=0.3,0.1

Type RM Length L Ch R = 1 ,67480   ,1716,1716,1716
BEGIN DESCRIPTION:
COTTONWOOD CREEK 69.0
END DESCRIPTION:
XS GIS Cut Line= 3
      3583149.65     10649810.18      3585149.61     10649410.19
      3585949.57     10648960.21
#Sta/Elev= 30
  2947.6  346.89  3008.7  342.65  3110.4  335.06  3212.1  327.22  3416.7  314.92
  3720.6  312.15  4242.7  312.38  4273.3  308.59  4314.1  307.92  4375.3  308.86
  4405.9  312.23  4487.5  312.38  4497.7  309.76  4528.3  312.32  4599.6  311.38
  4609.8  305.03  4630.2  311.15  4640.4  311.48    4824  310.53  4966.8  312.75
    4990  308.33  4995.1  301.41  4997.9  301.33  5000.6  300.83  5003.9  301.33
  5010.1  301.89  5016.8  312.79    5274  310.54  5528.1  320.43    5905  342.36
#Mann= 8 ,-1 , 0
  2947.6     .16       0  3008.7     .12       0  3110.4     .16       0
  3212.1     .05       0  3720.6     .12       0  4997.9     .07       0
  5003.9     .12       0  5528.1     .16       0
Bank Sta=4966.8,5016.8
XS Rating Curve= 0 ,0
Exp/Cntr=0.3,0.1

Type RM Length L Ch R = 1 ,65764   ,795,795,795
BEGIN DESCRIPTION:
COTTONWOOD CREEK 68.0
END DESCRIPTION:
XS GIS Cut Line= 3
      3583545.22     10651532.51       3586453.2     10649848.48
        3586748.     10648834.05
#Sta/Elev= 30
  1819.6   354.8  1986.4  351.15  2036.1  344.57  2073.4  345.48  2271.4  332.86
  2871.2   321.9  3122.1  311.93  3176.8  309.16  3229.9  311.83  3257.2   310.5
  3535.7  308.31  4735.1  309.91  4948.8  310.61  4964.6  312.98  4979.4  308.79
  4986.1  300.44  4988.9  299.61  4991.6  299.11  4994.9  299.61  5007.6   301.2
  5014.1  307.21  5023.4  310.98  5086.1  310.21  5358.7  310.85  5401.1  310.52
  5480.2  317.67  5623.8  322.44  5935.4  337.88  6125.9   343.6  6236.4  343.79
#Mann= 10 ,-1 , 0
  1819.6     .05       0  3122.1     .08       0  3257.2      .1       0
  3535.7     .05       0  4735.1     .12       0  4988.9     .07       0
  4994.9     .12       0  5086.1     .05       0  5358.7     .12       0
  5623.8     .16       0
Bank Sta=4964.6,5023.4
XS Rating Curve= 0 ,0
Exp/Cntr=0.3,0.1

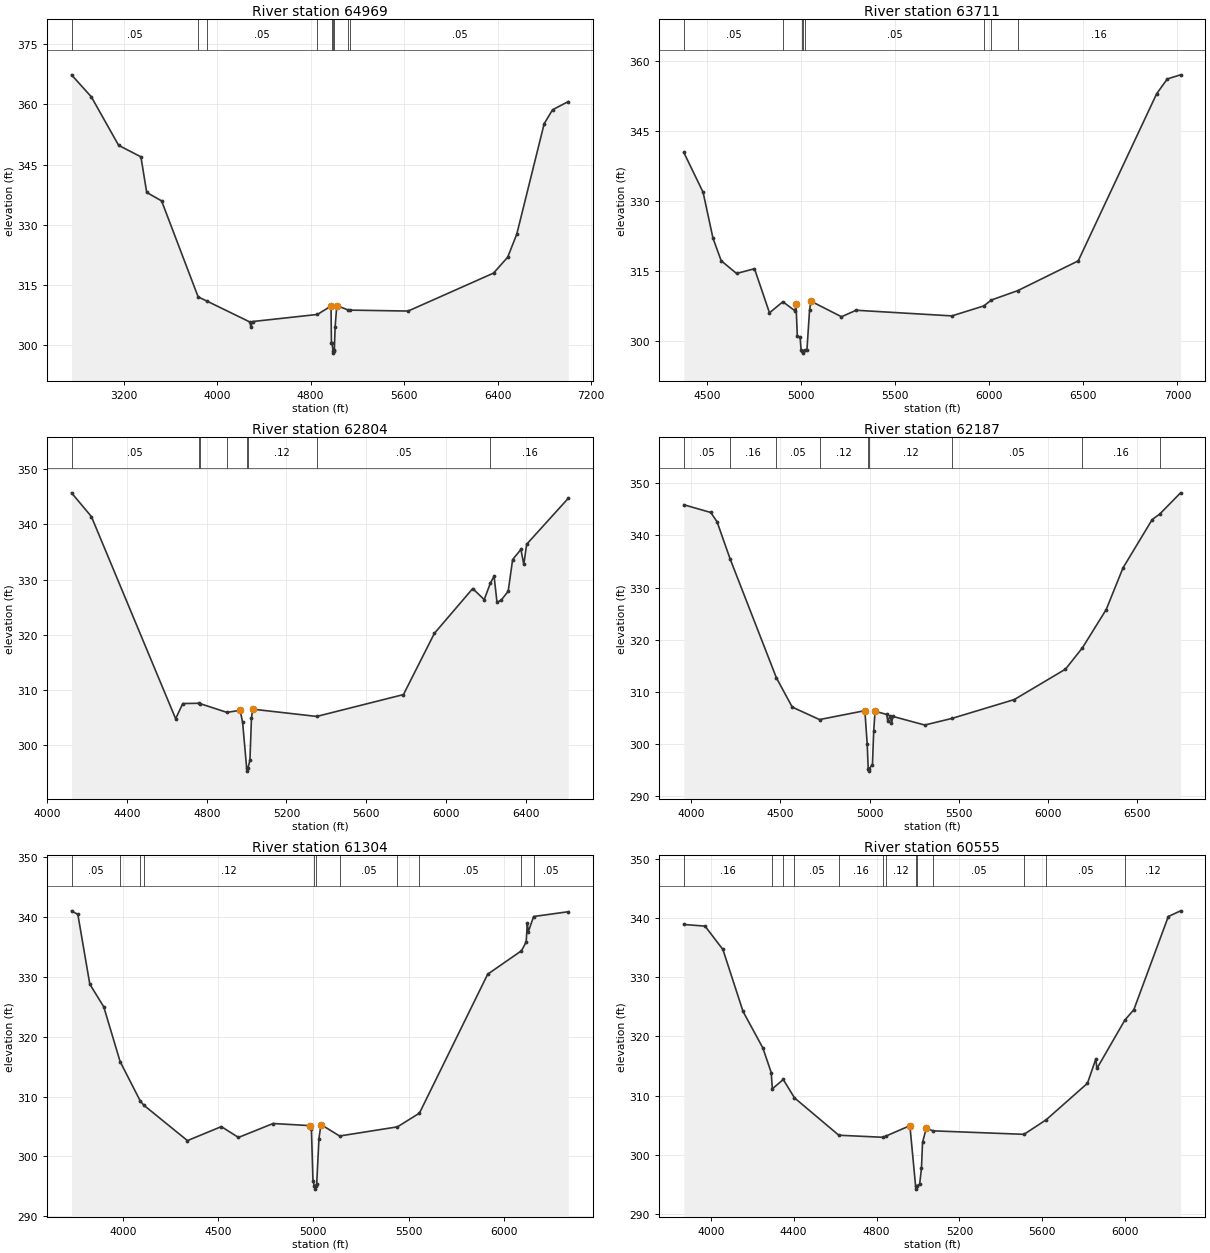
Type RM Length L Ch R = 1 ,64969   ,1258,1258,1258
BEGIN DESCRIPTION:
COTTONWOOD CREEK 67.0
END DESCRIPTION:
XS GIS Cut Line= 3
      3584649.64     10652010.16      3586249.61     10650460.19
      3587799.59      10649160.2
#Sta/Elev= 30
    2754  367.38  2923.6  361.89  3157.2  349.79    3348  346.92  3397.4  338.04
  3524.8  335.93  3837.7  311.97  3910.3  310.96  4281.6  305.69  4288.5  304.35
  4302.7  305.82  4858.4  307.59  4974.6   309.7  4978.1  300.39  4983.2  300.39
  4992.3  298.44  4995.1  297.94  4998.3  298.44  5003.1  298.79  5009.6  304.42
  5023.9  309.82  5116.8  308.75  5140.5  308.67  5634.2  308.44  6365.2  317.91
  6486.2  321.87  6564.3  327.66  6798.4  355.18    6870  358.66  7004.6  360.71
#Mann= 9 ,-1 , 0
    2754     .05       0  3837.7     .16       0  3910.3     .05       0
  4858.4     .12       0  4983.2     .16       0  4992.3     .07       0
  4998.3     .16       0  5116.8     .12       0  5140.5     .05       0
Bank Sta=4974.6,5023.9
XS Rating Curve= 0 ,0
Exp/Cntr=0.3,0.1

Type RM Length L Ch R = 1 ,63711   ,907,907,907
BEGIN DESCRIPTION:
COTTONWOOD CREEK 66.0
END DESCRIPTION:
XS GIS Cut Line= 3
      3586249.62     10651610.16      3586549.61     10651060.19
      3587949.59     10649610.21
#Sta/Elev= 30
  4374.7   340.4  4477.2  331.87  4529.9  322.03  4573.5  317.21  4655.2  314.48
  4750.6   315.5  4830.3  306.06  4901.5  308.43  4965.6   306.5  4971.3     308
  4978.4     301  4993.1  300.86  4998.3  298.16  5005.2  297.93    5008  297.43
  5011.2  297.93  5019.9  298.08  5029.3     298  5043.5  306.66  5050.7  308.55
  5213.3  305.22  5291.2  306.61  5800.3   305.4  5969.9  307.53  6010.4   308.8
  6150.7  310.81  6472.3  317.18  6889.5  352.96  6946.1  356.13  7016.7  357.01
#Mann= 8 ,-1 , 0
  4374.7     .05       0  4901.5     .16       0  5005.2     .07       0
  5011.2     .16       0  5019.9     .05       0  5969.9     .16       0
  6010.4     .05       0  6150.7     .16       0
Bank Sta=4971.3,5050.7
XS Rating Curve= 0 ,0
Exp/Cntr=0.3,0.1

Type RM Length L Ch R = 1 ,62804   ,617,617,617
BEGIN DESCRIPTION:
COTTONWOOD CREEK 65.0
END DESCRIPTION:
XS GIS Cut Line= 3
      3586378.05     10651826.79      3587207.05     10651241.71
      3588126.26     10650084.03
#Sta/Elev= 30
  4121.5  345.74  4221.3  341.43  4644.1  304.72  4679.8  307.48  4761.9  307.53
  4765.6  307.48  4900.9  305.88  4967.9  306.24  4980.2  304.07  5000.6  295.71
  5003.4  295.21  5006.6  295.71  5016.9  297.18  5024.6  304.84  5030.7  306.46
  5351.9  305.14  5787.3  309.11  5942.6  320.23  6134.9  328.36  6192.6  326.35
  6224.1   329.4  6242.2   330.6  6256.7  325.88  6277.5  326.24  6312.9  327.87
  6335.2  333.62  6376.8  335.47  6391.2  332.74  6405.7  336.41  6614.4  344.75
#Mann= 8 ,-1 , 0
  4121.5     .05       0  4761.9     .16       0  4765.6     .05       0
  4900.9     .12       0  5000.6     .07       0  5006.6     .12       0
  5351.9     .05       0  6224.1     .16       0
Bank Sta=4967.9,5030.7
XS Rating Curve= 0 ,0
Exp/Cntr=0.3,0.1

Type RM Length L Ch R = 1 ,62187   ,883,883,883
BEGIN DESCRIPTION:
COTTONWOOD CREEK 64.0
END DESCRIPTION:
XS GIS Cut Line= 3
      3586329.44     10652007.34      3587197.51     10651903.17
      3588322.51      10650361.5
#Sta/Elev= 30
  3959.7  345.87  4110.9  344.39  4145.9  342.61  4219.1  335.48  4478.3  312.68
  4567.2  307.06  4719.8  304.67  4973.9  306.38  4987.1  299.93  4992.6  295.28
  4995.3  294.78  4998.6  295.28  5016.4  296.02  5023.4  302.46  5031.1  306.27
    5096  305.65  5102.2  304.45  5116.8  305.38    5123  303.97  5131.5  305.27
  5309.2  303.62  5461.5  304.89  5811.2  308.51  6097.8  314.34  6192.9  318.45
  6325.7  325.76  6419.9  333.76  6583.2  343.02  6626.1   344.1  6742.5  348.16
#Mann= 9 ,-1 , 0
  3959.7     .05       0  4219.1     .16       0  4478.3     .05       0
  4719.8     .12       0  4992.6     .07       0  4998.6     .12       0
  5461.5     .05       0  6192.9     .16       0  6626.1     .05       0
Bank Sta=4973.9,5031.1
XS Rating Curve= 0 ,0
Exp/Cntr=0.3,0.1

Type RM Length L Ch R = 1 ,61304   ,749,749,749
BEGIN DESCRIPTION:
COTTONWOOD CREEK 63.0
END DESCRIPTION:
XS GIS Cut Line= 2
      3586627.71     10652359.94      3589120.83     10651602.98
#Sta/Elev= 30
  3731.3  341.05  3764.6  340.45  3827.3  328.79  3900.5     325  3986.3  315.85
  4090.9  309.33  4109.8  308.58  4339.4  302.64  4517.1  304.98    4607  303.17
  4788.8   305.5  4984.5  305.14  4989.7   304.5  4997.8  295.93  5005.3  295.03
    5008  294.53  5011.3  295.03  5017.4  295.44  5029.2  302.99  5039.6  305.33
  5137.5  303.41  5440.9  304.94  5556.1  307.23  5914.2  330.46  6091.5  334.38
  6116.1  335.85    6122  339.03  6127.2  337.54  6155.1   340.1  6336.8   340.9
#Mann= 11 ,-1 , 0
  3731.3     .05       0  3986.3     .16       0  4090.9     .05       0
  4109.8     .12       0  5005.3     .07       0  5011.3     .12       0
  5137.5     .05       0  5440.9     .16       0  5556.1     .05       0
  6091.5     .08       0  6155.1     .05       0
Bank Sta=4984.5,5039.6
XS Rating Curve= 0 ,0
Exp/Cntr=0.3,0.1

Type RM Length L Ch R = 1 ,60555   ,283,283,283
BEGIN DESCRIPTION:
COTTONWOOD CREEK 62.0
END DESCRIPTION:
XS GIS Cut Line= 2
      3586551.37     10652901.59      3588801.32     10652075.22
#Sta/Elev= 30
  3870.2  338.88  3972.7   338.6  4058.8  334.66    4156  324.21  4251.8  318.04
    4292   313.9  4297.3  311.16    4350  312.74  4404.2  309.64  4618.1  303.34
    4832  302.99  4843.7  303.17  4961.1  304.95  4988.6  294.75  4991.3  294.25
  4994.6  294.75  5008.2  295.11  5016.8  297.74  5022.1  302.14  5040.2  304.52
    5072  304.08  5511.6  303.49  5618.5  305.94  5817.8   312.1  5858.1  316.19
  5863.5   314.6  5998.3  322.76  6041.6  324.51  6207.9  340.22  6267.1  341.18
#Mann= 13 ,-1 , 0
  3870.2     .16       0  4297.3     .12       0    4350     .16       0
  4404.2     .05       0  4618.1     .16       0    4832     .05       0
  4843.7     .12       0  4988.6     .07       0  4994.6     .12       0
    5072     .05       0  5511.6     .16       0  5618.5     .05       0
  5998.3     .12       0
Bank Sta=4961.1,5040.2
XS Rating Curve= 0 ,0
Exp/Cntr=0.3,0.1

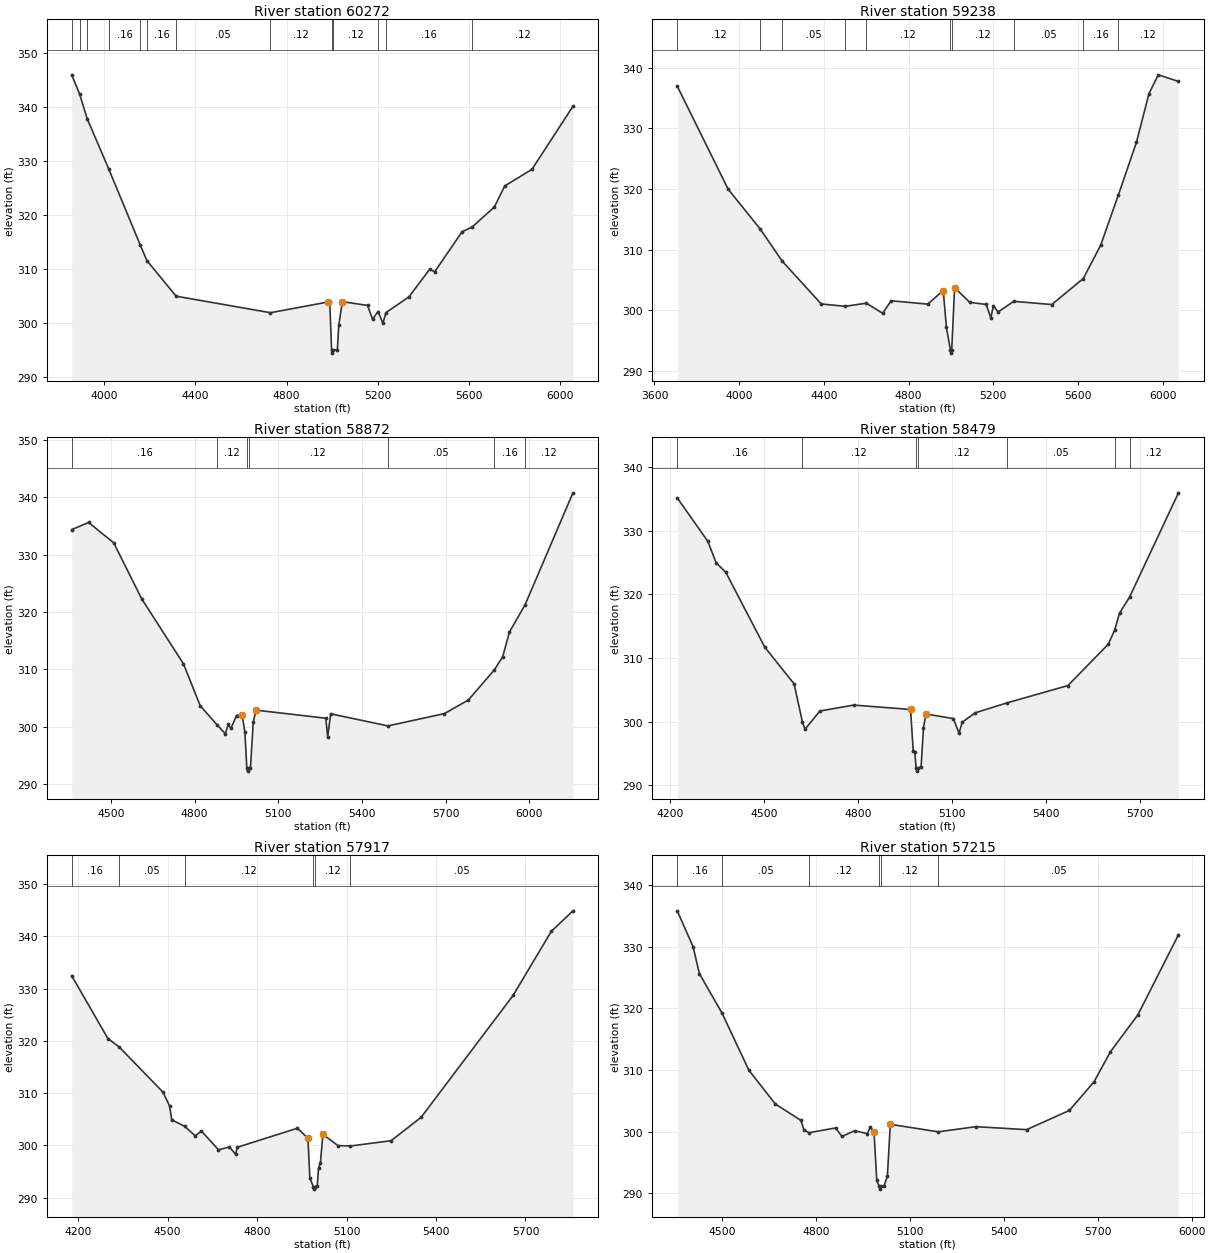
Type RM Length L Ch R = 1 ,60272   ,1034,1034,1034
BEGIN DESCRIPTION:
COTTONWOOD CREEK 61.0
END DESCRIPTION:
XS GIS Cut Line= 2
      3586704.16     10653234.92      3588695.91     10652298.03
#Sta/Elev= 30
  3856.5   345.9  3891.8  342.27  3924.5  337.76  4018.4  328.54  4157.5   314.4
  4186.4  311.53  4314.9  304.93  4729.4  301.87  4983.9  303.87  4989.7  303.78
  4997.8  294.89  5000.5  294.39  5003.8  294.89  5022.9  295.04  5029.5  299.64
    5045  303.92  5155.5  303.22  5177.6  300.68  5201.7  302.09  5222.9  299.94
  5236.8   301.9  5336.9  304.79  5428.1  309.89  5450.9  309.47  5570.4  316.84
  5614.7  317.72  5712.7  321.45  5758.3  325.34  5877.8  328.41  6057.6  340.08
#Mann= 13 ,-1 , 0
  3856.5     .05       0  3891.8     .16       0  3924.5     .12       0
  4018.4     .16       0  4157.5     .05       0  4186.4     .16       0
  4314.9     .05       0  4729.4     .12       0  4997.8     .07       0
  5003.8     .12       0  5201.7     .05       0  5236.8     .16       0
  5614.7     .12       0
Bank Sta=4983.9,5045
XS Rating Curve= 0 ,0
Exp/Cntr=0.3,0.1

Type RM Length L Ch R = 1 ,59238   ,366,366,366
BEGIN DESCRIPTION:
COTTONWOOD CREEK 60.0
END DESCRIPTION:
XS GIS Cut Line= 3
       3586919.4     10653540.48      3588051.35     10653540.48
      3588620.32     10652444.19
#Sta/Elev= 30
  3707.7  336.96  3947.9  319.98    4099  313.42  4204.4  308.07  4387.9  301.04
  4501.2  300.66  4600.2  301.17  4677.9  299.51  4717.9  301.57  4890.4  301.02
  4963.9  303.25  4978.9  297.19    4998  293.44  5000.8  292.94    5004  293.44
  5017.5  303.73  5089.5  301.31  5166.7  300.97  5188.8  298.74  5200.5  300.74
  5223.1  299.72  5296.7  301.48  5476.4  300.95  5625.4  305.24  5707.5  310.74
  5790.4  318.95  5876.5   327.7  5935.3  335.71  5979.6  338.82  6074.8  337.73
#Mann= 10 ,-1 , 0
  3707.7     .12       0    4099     .16       0  4204.4     .05       0
  4501.2     .16       0  4600.2     .12       0    4998     .07       0
    5004     .12       0  5296.7     .05       0  5625.4     .16       0
  5790.4     .12       0
Bank Sta=4963.9,5017.5
XS Rating Curve= 0 ,0
Exp/Cntr=0.3,0.1

Type RM Length L Ch R = 1 ,58872   ,393,393,393
BEGIN DESCRIPTION:
COTTONWOOD CREEK 59.0
END DESCRIPTION:
XS GIS Cut Line= 3
      3588315.24     10654290.52      3588322.19     10653471.04
      3588676.34     10652561.36
#Sta/Elev= 30
  4360.1  334.39  4420.4  335.64  4510.4   332.1  4610.4  322.35  4760.4  310.98
  4820.4  303.66  4882.2  300.27  4910.5  298.76  4920.5   300.4  4930.5  299.72
  4950.5  301.95  4970.5   302.1  4980.5  299.05  4987.5  292.76  4990.2  292.26
  4993.5  292.76  5000.5  292.88  5010.5  300.88  5020.5   302.9  5270.4  301.49
  5277.1  298.23  5287.8  302.26    5493  300.15  5695.6   302.3  5781.5  304.68
  5874.7  309.96  5903.9  312.19  5928.4  316.53  5984.6  321.31  6155.8  340.81
#Mann= 7 ,-1 , 0
  4360.1     .16       0  4882.2     .12       0  4987.5     .07       0
  4993.5     .12       0    5493     .05       0  5874.7     .16       0
  5984.6     .12       0
Bank Sta=4970.5,5020.5
XS Rating Curve= 0 ,0
Exp/Cntr=0.3,0.1

Type RM Length L Ch R = 1 ,58479   ,562,562,562
BEGIN DESCRIPTION:
COTTONWOOD CREEK 58.0
END DESCRIPTION:
XS GIS Cut Line= 3
      3588349.61     10654160.19      3588549.61     10653410.19
       3588749.6     10652610.21
#Sta/Elev= 30
  4223.6  335.17  4321.3  328.34  4347.8  324.97  4378.8  323.46    4503  311.71
  4596.8  305.92  4623.6  299.89  4631.8  298.79    4679  301.65    4787  302.59
  4968.8   301.9  4977.2  295.44  4982.3  295.28  4986.5   292.7  4989.2   292.2
  4992.5   292.7  5002.4  292.88  5010.1  299.02  5017.8  301.19  5105.5  300.46
  5123.5  298.18  5133.8  299.89    5175  301.37  5275.7  302.92  5471.4  305.66
  5600.2  312.16  5620.7  314.39  5636.3  317.06  5668.3  319.58  5824.4  335.97
#Mann= 7 ,-1 , 0
  4223.6     .16       0  4623.6     .12       0  4986.5     .07       0
  4992.5     .12       0  5275.7     .05       0  5620.7     .16       0
  5668.3     .12       0
Bank Sta=4968.8,5017.8
XS Rating Curve= 0 ,0
Exp/Cntr=0.3,0.1

Type RM Length L Ch R = 1 ,57917   ,702,702,702
BEGIN DESCRIPTION:
COTTONWOOD CREEK 57.0
END DESCRIPTION:
XS GIS Cut Line= 3
      3588399.64     10654110.16      3589049.61     10653610.19
      3589549.64     10652910.15
#Sta/Elev= 30
  4178.8  332.45  4300.2  320.43  4337.2  318.87    4485  310.16  4506.8  307.54
    4514  304.89  4557.2  303.64  4592.9  301.81  4613.7  302.73  4670.8  299.14
  4707.1  299.68  4727.9  298.32  4734.2  299.63  4935.4  303.27  4970.7  301.35
  4977.1  293.74  4988.6  292.11  4991.3  291.61  4994.6  292.11  5001.9  292.16
  5006.2  295.66  5012.3  296.56  5020.9  302.09  5071.3  299.95  5113.2  299.87
  5249.5  300.88  5350.3  305.37  5658.7  328.72  5786.5  340.95  5859.1  344.89
#Mann= 6 ,-1 , 0
  4178.8     .16       0  4337.2     .05       0  4557.2     .12       0
  4988.6     .07       0  4994.6     .12       0  5113.2     .05       0
Bank Sta=4970.7,5020.9
XS Rating Curve= 0 ,0
Exp/Cntr=0.3,0.1

Type RM Length L Ch R = 1 ,57215   ,543,543,543
BEGIN DESCRIPTION:
COTTONWOOD CREEK 56.0
END DESCRIPTION:
XS GIS Cut Line= 3
      3588399.61     10654160.19      3589049.61     10654060.19
      3589849.57     10653560.21
#Sta/Elev= 30
  4356.9  335.79  4407.5  329.97  4427.7   325.6  4499.9  319.21  4585.8  309.94
  4670.5  304.46  4751.5  301.83  4761.6  300.33  4776.8  299.81  4862.8  300.59
    4883  299.21  4923.5  300.14    4964  299.67  4974.1  300.79  4985.5  299.87
  4994.3  292.07  5001.4  291.17  5004.2  290.67  5007.4  291.17  5017.5  291.22
  5028.1  292.77  5037.5  301.18  5190.9  299.96  5311.1   300.8  5472.7  300.31
  5609.5  303.43  5688.5  308.09  5740.4  312.93  5828.2  318.92  5957.9  331.91
#Mann= 6 ,-1 , 0
  4356.9     .16       0  4499.9     .05       0  4776.8     .12       0
  5001.4     .07       0  5007.4     .12       0  5190.9     .05       0
Bank Sta=4985.5,5037.5
XS Rating Curve= 0 ,0
Exp/Cntr=0.3,0.1

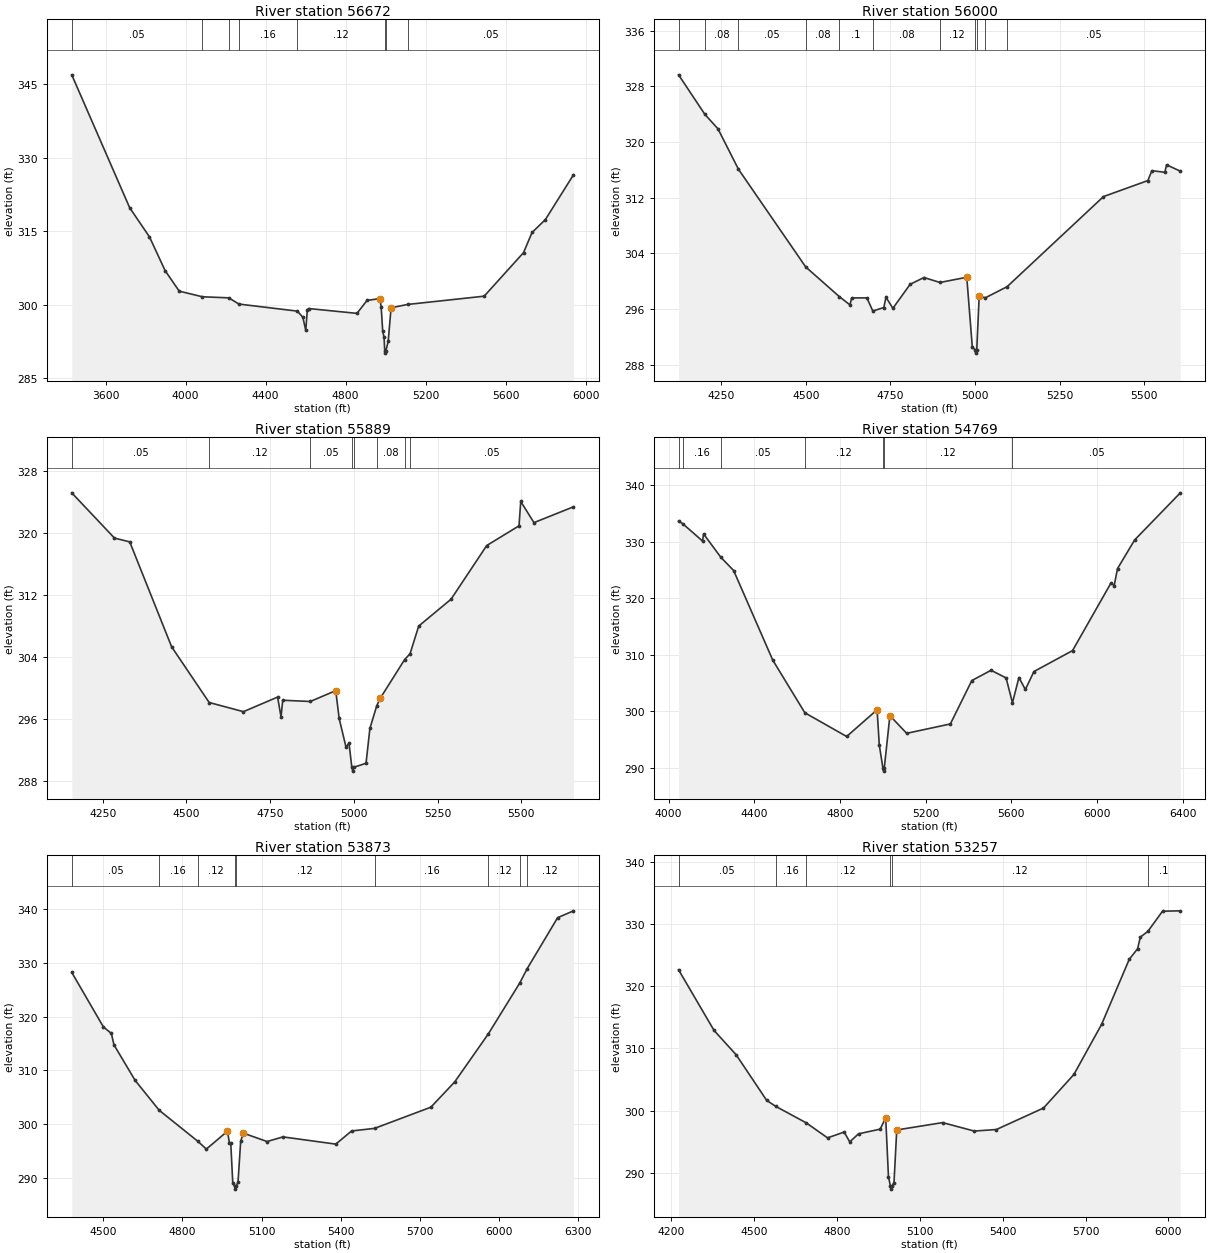
Type RM Length L Ch R = 1 ,56672   ,672,672,672
BEGIN DESCRIPTION:
COTTONWOOD CREEK 55.0
END DESCRIPTION:
XS GIS Cut Line= 3
      3588112.75     10655460.21      3589420.06     10654397.69
      3589841.94     10653689.35
#Sta/Elev= 30
  3430.7  346.96  3720.3  319.82  3819.4  313.86  3897.7  306.96  3968.1  302.78
  4084.2  301.63  4215.9  301.41  4266.6  300.14  4558.9   298.7  4586.5  297.43
  4600.9  294.78  4608.8  298.94  4615.3  299.23    4857  298.24  4907.7   300.9
  4971.6  301.25    4978  299.57  4985.9  294.55  4992.4  293.38  4995.8  290.62
  4998.6  290.12  5001.8  290.62  5013.2  292.54  5027.6  299.38  5109.8  300.06
  5493.1  301.75  5689.8  310.64  5732.6  314.76  5799.1  317.39  5939.8  326.55
#Mann= 8 ,-1 , 0
  3430.7     .05       0  4084.2     .16       0  4215.9     .05       0
  4266.6     .16       0  4558.9     .12       0  4995.8     .07       0
  5001.8     .12       0  5109.8     .05       0
Bank Sta=4971.6,5027.6
XS Rating Curve= 0 ,0
Exp/Cntr=0.3,0.1

Type RM Length L Ch R = 1 ,56000   ,111,111,111
BEGIN DESCRIPTION:
COTTONWOOD CREEK 54.0
END DESCRIPTION:
XS GIS Cut Line= 2
      3589451.31     10655850.81       3589753.4     10654397.68
#Sta/Elev= 30
  4123.2  329.66  4201.1  323.97  4239.5  321.92  4300.4  316.09  4499.1  302.07
  4598.4  297.81  4630.1  296.61  4635.2  297.61  4680.2  297.62  4697.8  295.73
  4730.3  296.23  4736.7  297.71  4757.1  296.12  4808.2  299.57    4849  300.54
  4896.5  299.83  4975.7  300.58    4992  290.59  4999.2  290.18    5002  289.68
  5005.2  290.18  5012.4  297.89  5030.7  297.63  5095.1  299.23  5380.1  312.17
  5511.5  314.47  5523.1  315.89  5561.6  315.66  5566.7  316.73  5607.4  315.82
#Mann= 11 ,-1 , 0
  4123.2     .05       0  4201.1     .08       0  4300.4     .05       0
  4499.1     .08       0  4598.4      .1       0  4697.8     .08       0
  4896.5     .12       0  4999.2     .07       0  5005.2     .12       0
  5030.7     .08       0  5095.1     .05       0
Bank Sta=4975.7,5012.4
XS Rating Curve= 0 ,0
Exp/Cntr=0.3,0.1

Type RM Length L Ch R = 1 ,55889   ,1120,1120,1120
BEGIN DESCRIPTION:
COTTONWOOD CREEK 53.0
END DESCRIPTION:
XS GIS Cut Line= 2
      3589539.84     10655892.52      3589836.57     10654424.51
#Sta/Elev= 30
  4157.7  325.13  4285.2   319.3  4330.8  318.81  4455.9  305.29  4567.9  298.12
  4670.2  296.94  4772.2  298.82  4782.4  296.26  4787.5  298.41  4869.7  298.25
  4945.7  299.65  4955.9  296.06  4976.3  292.38  4985.3  292.87  4993.7  289.78
  4996.4  289.28  4999.7  289.78  5036.1  290.29  5047.7  294.78  5068.2  297.71
  5078.3  298.65  5151.2  303.64  5167.5   304.4  5193.4  307.97  5289.8  311.42
  5396.4  318.34  5492.8  320.88  5497.9  324.02  5537.4  321.29  5655.4  323.33
#Mann= 8 ,-1 , 0
  4157.7     .05       0  4567.9     .12       0  4869.7     .05       0
  4993.7     .04       0  4999.7     .05       0  5068.2     .08       0
  5151.2     .12       0  5167.5     .05       0
Bank Sta=4945.7,5078.3
XS Rating Curve= 0 ,0
Exp/Cntr=0.3,0.1

Type RM Length L Ch R = 1 ,54769   ,896,896,896
BEGIN DESCRIPTION:
COTTONWOOD CREEK 52.0
END DESCRIPTION:
XS GIS Cut Line= 3
      3590644.02      10656623.4      3590461.73     10655573.04
      3590505.13     10654297.03
#Sta/Elev= 30
  4046.5  333.69  4065.1  333.24  4158.2  330.15  4163.2   331.4  4243.8  327.27
  4303.5  324.93  4486.2  309.07    4636  299.75  4831.3  295.55  4973.4  300.28
  4983.7  294.03  5000.8  289.92  5003.6  289.42  5006.8  289.92  5033.2  299.24
  5111.5  296.11  5315.5  297.77  5415.6  305.45  5505.6  307.27  5575.7  305.92
  5605.4  301.52  5635.7  305.98  5665.7  303.87  5705.8  307.05  5885.9  310.75
    6066  322.75  6080.4  322.24    6096  325.27    6176  330.34  6389.3  338.68
#Mann= 7 ,-1 , 0
  4046.5     .12       0  4065.1     .16       0  4243.8     .05       0
    4636     .12       0  5000.8     .07       0  5006.8     .12       0
  5605.4     .05       0
Bank Sta=4973.4,5033.2
XS Rating Curve= 0 ,0
Exp/Cntr=0.3,0.1

Type RM Length L Ch R = 1 ,53873   ,616,616,616
BEGIN DESCRIPTION:
COTTONWOOD CREEK 51.0
END DESCRIPTION:
XS GIS Cut Line= 3
      3590999.61     10656460.19      3590999.61     10655860.19
      3591049.61     10654560.15
#Sta/Elev= 30
  4380.6   328.2  4500.6  318.07  4530.6  316.88  4540.6  314.75  4620.6  308.17
  4711.9  302.62  4857.2  296.91  4890.6  295.42  4970.6  298.74  4978.1   296.5
  4983.1   296.5  4990.6  289.18  4997.6  288.49  5000.4  287.99  5003.6  288.49
  5010.6  289.33  5020.6  296.84  5030.6  298.38  5120.7  296.82  5180.8  297.68
  5380.9  296.34  5440.9  298.78  5527.8  299.26  5741.2  303.19  5831.2  307.86
  5959.2  316.81    6078  326.23    6106  328.88  6221.5  338.35  6281.6  339.62
#Mann= 9 ,-1 , 0
  4380.6     .05       0  4711.9     .16       0  4857.2     .12       0
  4997.6     .07       0  5003.6     .12       0  5527.8     .16       0
  5959.2     .12       0    6078     .16       0    6106     .12       0
Bank Sta=4970.6,5030.6
XS Rating Curve= 0 ,0
Exp/Cntr=0.3,0.1

Type RM Length L Ch R = 1 ,53257   ,494,494,494
BEGIN DESCRIPTION:
COTTONWOOD CREEK 50.0
END DESCRIPTION:
XS GIS Cut Line= 2
      3591462.46     10656498.36      3591580.52      10654685.8
#Sta/Elev= 30
  4226.6  322.62    4355  312.88  4435.2  308.96  4545.4  301.65  4577.8  300.69
  4688.4  298.04  4765.9  295.62    4826  296.55  4846.1  294.97  4878.1  296.27
  4956.3  297.02  4976.4  298.84  4986.4  289.38  4993.4  287.88  4996.2  287.38
  4999.4  287.88  5006.4  288.42  5016.4  296.89  5182.3  298.07    5297  296.71
  5377.2  296.96  5547.6  300.41  5657.8  305.81    5758  313.86  5858.2  324.32
  5888.3  326.01  5898.3  327.88  5925.5   328.8  5978.5  332.04    6043   332.1
#Mann= 6 ,-1 , 0
  4226.6     .05       0  4577.8     .16       0  4688.4     .12       0
  4993.4     .07       0  4999.4     .12       0  5925.5      .1       0
Bank Sta=4976.4,5016.4
XS Rating Curve= 0 ,0
Exp/Cntr=0.3,0.1

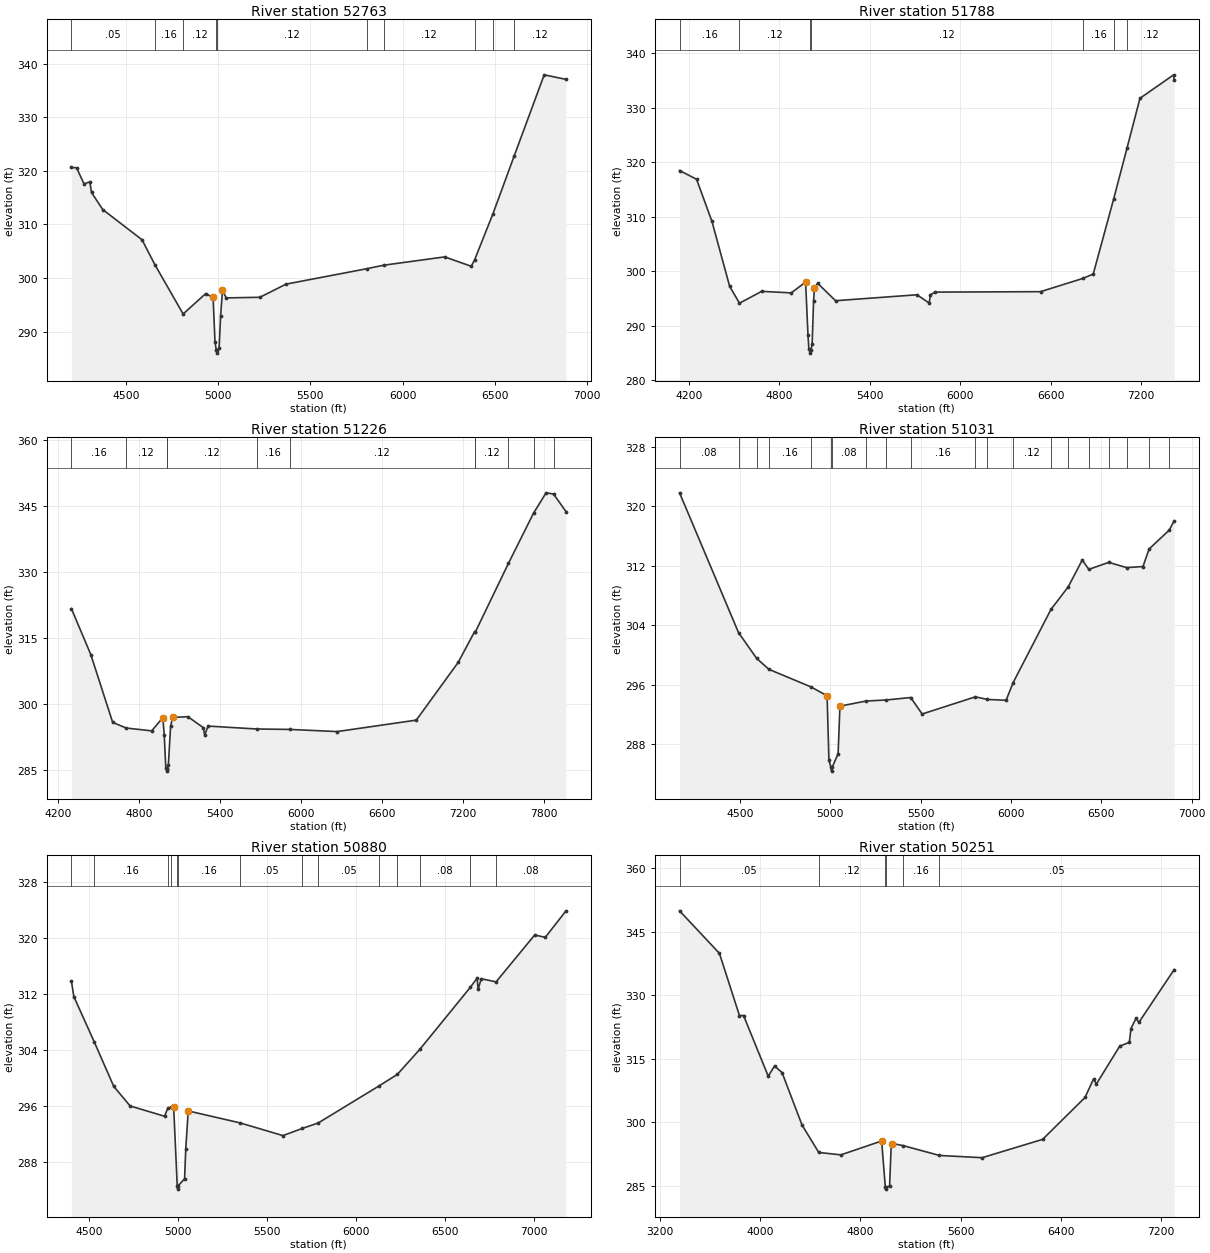
Type RM Length L Ch R = 1 ,52763   ,975,975,975
BEGIN DESCRIPTION:
COTTONWOOD CREEK 49.0
END DESCRIPTION:
XS GIS Cut Line= 2
      3591858.29     10656567.81      3592316.34     10653923.59
#Sta/Elev= 30
  4203.1  320.64  4231.1  320.59  4271.7  317.57    4303  317.97  4312.3  315.97
  4373.2  312.78  4586.3  307.14  4656.6  302.45  4809.4  293.27  4931.4  297.07
    4972  296.36  4982.2  288.13  4989.3  286.46  4992.1  285.96  4995.3  286.46
  5004.6  286.92  5012.6  292.85  5022.8  297.69  5043.1  296.28  5225.7  296.39
  5367.8  298.85    5806  301.73  5896.6  302.38  6228.7  303.94  6372.6  302.18
  6390.9  303.39  6489.7  311.93  6606.2  322.85  6768.4  337.95  6886.7   337.1
#Mann= 10 ,-1 , 0
  4203.1     .05       0  4656.6     .16       0  4809.4     .12       0
  4989.3     .07       0  4995.3     .12       0    5806     .16       0
  5896.6     .12       0  6390.9     .05       0  6489.7     .16       0
  6606.2     .12       0
Bank Sta=4972,5022.8
XS Rating Curve= 0 ,0
Exp/Cntr=0.3,0.1

Type RM Length L Ch R = 1 ,51788   ,562,562,562
BEGIN DESCRIPTION:
COTTONWOOD CREEK 48.0
END DESCRIPTION:
XS GIS Cut Line= 3
      3592018.02     10656602.49      3592906.91      10656088.6
      3592934.67     10653833.42
#Sta/Elev= 30
  4137.7  318.48  4250.7  316.87  4352.7  309.13  4470.3  297.19  4535.5   294.1
  4682.4  296.28  4878.8     296  4974.2  297.98    4990  288.28  4995.8  285.73
  5002.7  285.43  5005.5  284.93  5008.7  285.43  5017.4  286.52  5027.3  294.58
  5033.1  296.96  5054.6  297.75  5172.9  294.56  5712.9  295.65    5794  294.14
  5802.9  295.65  5832.9  296.14    6533  296.22  6815.9  298.67    6883  299.47
  7018.3  313.24  7107.8  322.68    7193  331.75  7416.6  336.06  7419.8  335.09
#Mann= 7 ,-1 , 0
  4137.7     .16       0  4535.5     .12       0  5002.7     .07       0
  5008.7     .12       0  6815.9     .16       0  7018.3     .08       0
  7107.8     .12       0
Bank Sta=4974.2,5033.1
XS Rating Curve= 0 ,0
Exp/Cntr=0.3,0.1

Type RM Length L Ch R = 1 ,51226   ,195,195,195
BEGIN DESCRIPTION:
Mapping XS 86af0265
END DESCRIPTION:
XS GIS Cut Line= 3
      3592073.57     10656730.96      3593511.08     10656355.96
      3595104.75     10654866.45
#Sta/Elev= 30
  4297.8  321.71  4441.5  311.29  4603.7  295.89    4703   294.6  4893.1  293.95
  4975.8  296.95  4986.1  293.07  4997.9  285.48  5003.8  285.31  5006.5  284.81
  5009.8  285.31  5017.1  286.31  5033.2  294.98  5048.1  297.01  5161.8  297.17
  5276.1  294.67  5285.8     293  5311.4  295.04  5670.7  294.38  5917.1  294.28
  6267.6  293.79  6854.8  296.39  7165.9  309.52  7287.4  316.49  7293.8  316.47
  7538.1  331.98    7724  343.38  7817.1     348  7872.3  347.73  7964.8  343.75
#Mann= 11 ,-1 , 0
  4297.8     .16       0    4703     .12       0  5003.8     .07       0
  5009.8     .12       0  5670.7     .16       0  5917.1     .12       0
  7287.4     .16       0  7293.8     .12       0  7538.1     .16       0
    7724     .12       0  7872.3     .16       0
Bank Sta=4975.8,5048.1
XS Rating Curve= 0 ,0
Exp/Cntr=0.3,0.1

Type RM Length L Ch R = 1 ,51031   ,151,151,151
BEGIN DESCRIPTION:
COTTONWOOD CREEK 47.0
END DESCRIPTION:
XS GIS Cut Line= 4
       3592011.1     10656845.54      3592781.91     10656736.17
      3593016.29     10656694.51      3594568.35     10655949.72
#Sta/Elev= 30
    4165   321.8  4491.5     303    4592  299.53  4659.7  298.06  4893.5  295.69
  4981.8   294.5    4992  285.82  5003.7  284.87  5006.5  284.37  5009.7  284.87
  5042.8  286.71  5052.9  293.11  5198.4   293.8  5310.2  293.94  5444.7  294.27
    5508  292.05  5802.3  294.36  5869.5  294.01  5972.8   293.9  6011.8  296.28
  6221.4  306.13  6316.9  309.16  6394.3  312.76  6430.9   311.5  6540.6  312.45
  6640.4  311.74  6730.6  311.89  6764.3  314.24  6876.1  316.79  6903.1  318.04
#Mann= 20 ,-1 , 0
    4165     .08       0  4491.5     .05       0    4592     .08       0
  4659.7     .16       0  4893.5     .05       0  5003.7     .07       0
  5009.7     .08       0  5198.4     .05       0  5310.2     .16       0
  5444.7     .16       0  5802.3     .16       0  5869.5     .12       0
  6011.8     .12       0  6221.4     .16       0  6316.9     .05       0
  6430.9     .16       0  6540.6     .05       0  6640.4     .16       0
  6764.3     .05       0  6876.1     .12       0
Bank Sta=4981.8,5052.9
XS Rating Curve= 0 ,0
Exp/Cntr=0.3,0.1

Type RM Length L Ch R = 1 ,50880   ,629,629,629
BEGIN DESCRIPTION:
COTTONWOOD CREEK 46.0
END DESCRIPTION:
XS GIS Cut Line= 3
       3592276.3     10656996.18      3593489.44     10656744.43
      3594889.17     10656095.57
#Sta/Elev= 30
  4400.4   313.8    4414  311.59  4528.6  305.13  4638.7  298.76  4730.6  295.97
  4924.6   294.5  4942.2  295.64  4961.7  295.76  4975.7  295.76  4995.6   284.6
  4998.3   284.1  5001.6   284.6    5037  285.58  5043.6  289.84  5057.4  295.26
  5348.1  293.56    5590  291.74  5700.1  292.77  5789.1  293.55    6130  298.82
  6233.5  300.47  6360.7  304.07  6643.4  312.88  6682.5  314.22    6688  312.61
  6705.4  314.13  6788.9  313.68  7006.3  320.38  7065.6  320.03  7182.2  323.82
#Mann= 14 ,-1 , 0
  4400.4     .05       0  4528.6     .16       0  4942.2     .05       0
  4961.7     .16       0  4995.6     .07       0  5001.6     .16       0
  5348.1     .05       0  5700.1     .08       0  5789.1     .05       0
    6130     .08       0  6233.5     .05       0  6360.7     .08       0
  6643.4     .05       0  6788.9     .08       0
Bank Sta=4975.7,5057.4
XS Rating Curve= 0 ,0
Exp/Cntr=0.3,0.1

Type RM Length L Ch R = 1 ,50251   ,2546,2546,2546
BEGIN DESCRIPTION:
Mapping XS 68b384c8
END DESCRIPTION:
XS GIS Cut Line= 3
      3591351.34     10657543.46      3592801.01     10657491.38
      3595074.94     10656449.88
#Sta/Elev= 30
  3354.5   349.9    3673  339.86  3833.1  325.18  3865.8  325.18  4063.2  310.85
  4113.3  313.26  4173.3  311.72  4333.4  299.31  4466.8  292.85  4643.6  292.28
  4969.1  295.56  4998.5  284.69  5001.3  284.19  5004.5  284.69  5032.6  284.86
  5045.5   294.5  5055.6  294.94  5138.9  294.48  5431.2  292.14  5771.5  291.61
  6255.4  295.94    6594  305.83  6662.4  310.21  6684.4  308.99  6871.4  317.95
  6948.4  318.85  6961.1  322.11  7001.6  324.52  7024.6  323.57  7306.2  336.02
#Mann= 6 ,-1 , 0
  3354.5     .05       0  4466.8     .12       0  4998.5     .07       0
  5004.5     .12       0  5138.9     .16       0  5431.2     .05       0
Bank Sta=4969.1,5055.6
XS Rating Curve= 0 ,0
Exp/Cntr=0.3,0.1