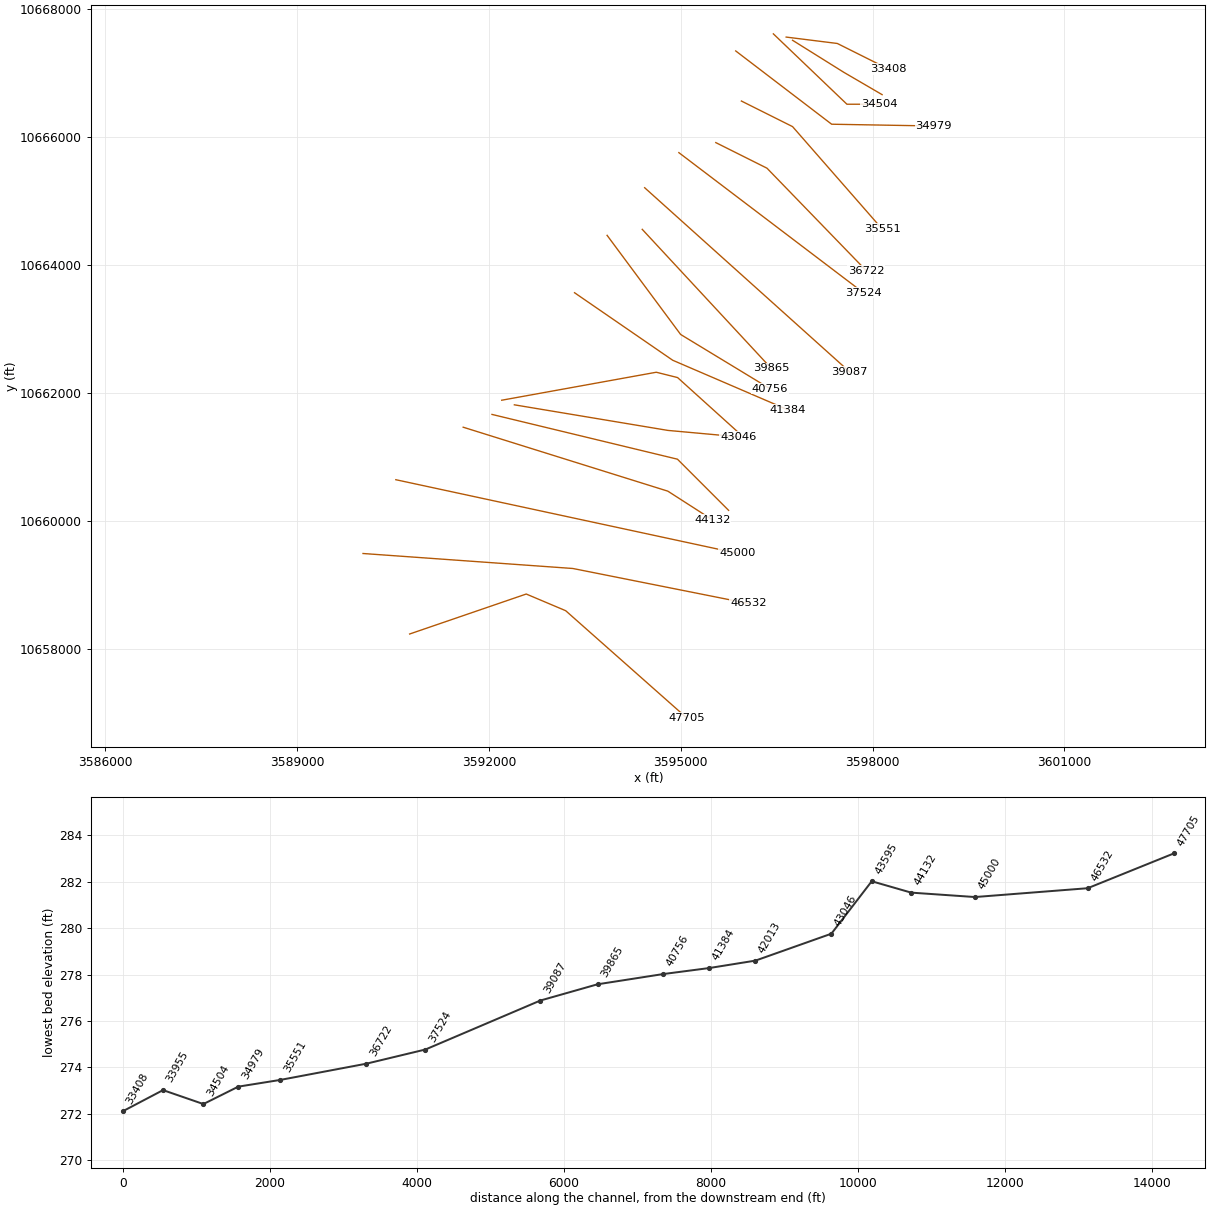
HEC-RAS study COTTONWOOD CREEK.prj: COTTONWOOD CREEK Base Level Engineering

--- COTTONWOOD CREEK.g01 (geometry) --- (continued)

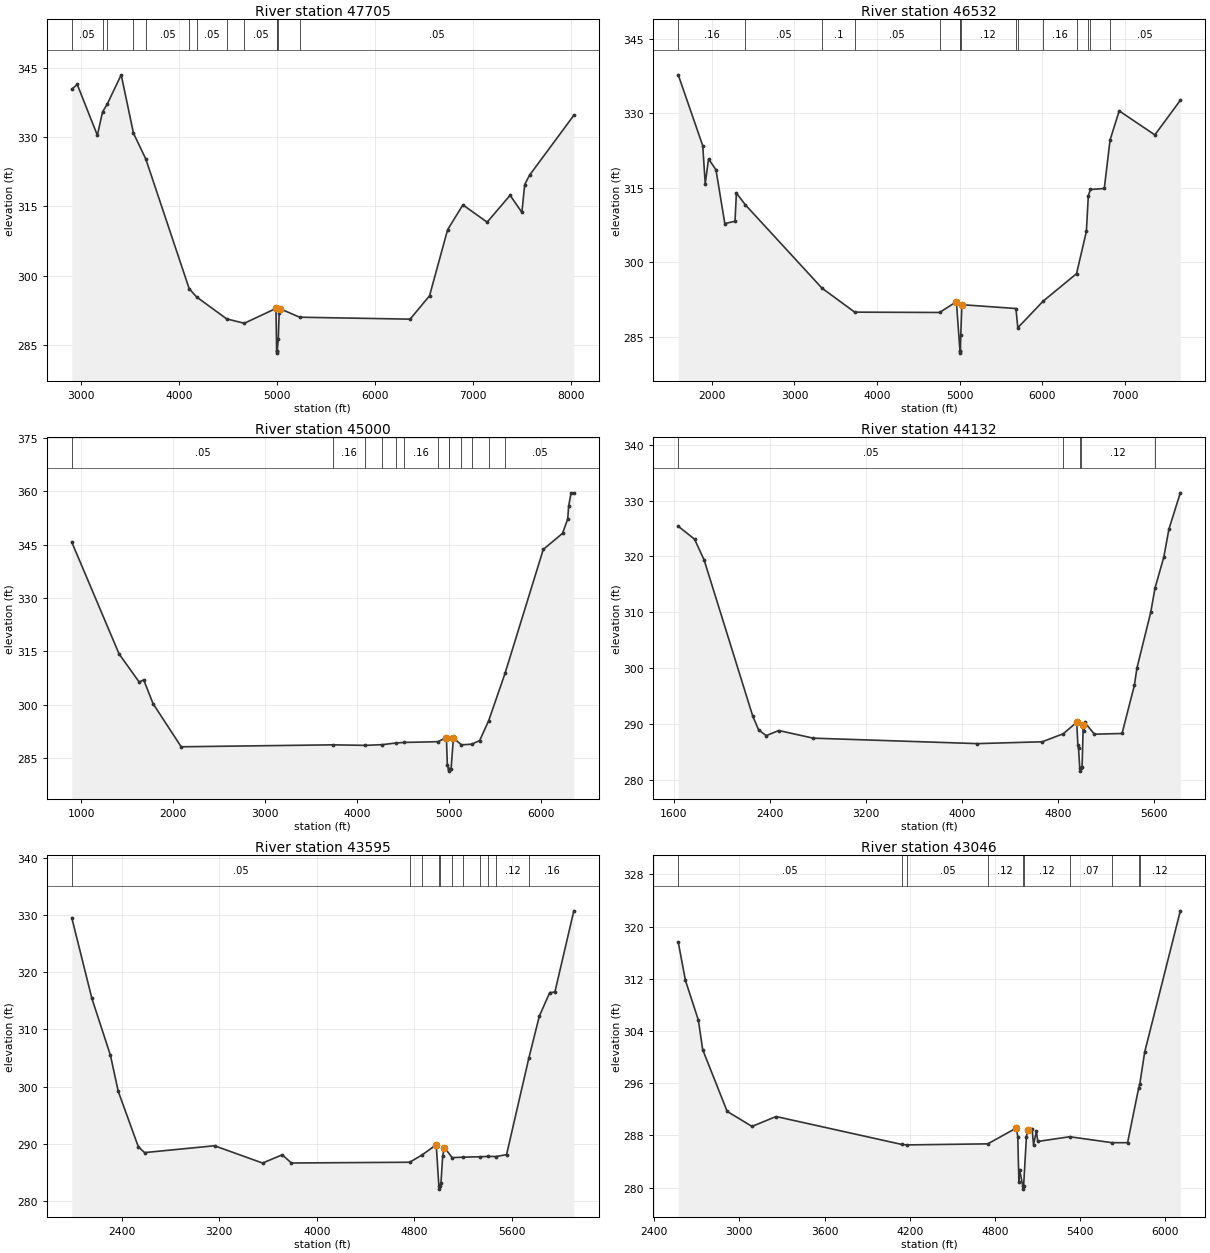
Type RM Length L Ch R = 1 ,47705   ,1173,1173,1173
BEGIN DESCRIPTION:
COTTONWOOD CREEK 45.0
END DESCRIPTION:
XS GIS Cut Line= 4
      3590762.41     10658226.83      3592585.35     10658851.84
      3593201.67     10658591.42      3595094.03     10656916.07
#Sta/Elev= 30
  2906.7  340.39  2962.6  341.42    3168   330.4  3220.3  335.45  3268.2  337.14
  3411.2   343.5  3536.3  330.86  3662.3  325.26  4104.7  297.19    4180   295.4
    4488  290.63  4667.5  289.69  4990.4   292.9  4997.4  283.72  5000.2  283.22
  5003.4  283.72    5014  286.18    5023  291.85    5035  292.81  5232.5     291
  6359.3  290.58  6557.6  295.64  6742.2  309.96    6898  315.33  7145.6  311.59
  7379.8  317.41  7500.2  313.71  7528.7  319.74    7578  321.75  8030.3  334.74
#Mann= 13 ,-1 , 0
  2906.7     .05       0  3220.3     .16       0  3268.2     .05       0
  3536.3      .1       0  3662.3     .05       0  4104.7      .1       0
    4180     .05       0    4488     .16       0  4667.5     .05       0
  4997.4     .03       0  5003.4     .05       0    5014     .16       0
  5232.5     .05       0
Bank Sta=4990.4,5035
XS Rating Curve= 0 ,0
Exp/Cntr=0.3,0.1

Type RM Length L Ch R = 1 ,46532   ,1532,1532,1532
BEGIN DESCRIPTION:
COTTONWOOD CREEK 44.0
END DESCRIPTION:
XS GIS Cut Line= 3
      3590033.25     10659485.52      3593314.52     10659251.15
      3596056.13     10658704.56
#Sta/Elev= 30
    1591  337.79  1888.1   323.5  1918.2  315.86  1958.3  320.84  2048.5  318.66
  2155.5  307.82  2279.1  308.29  2295.8  313.97  2405.8  311.58  3333.7  294.81
  3729.9  289.98  4759.2  289.91  4962.3  292.08  5005.2  282.22  5007.9  281.72
  5011.2  282.22  5015.5  285.42  5028.6  291.48  5683.9  290.71  5706.6  286.83
  6011.6  292.16  6418.4  297.73  6537.7  306.24  6561.3  313.45  6587.5  314.69
  6754.6  314.89  6825.1  324.68  6935.4  330.53  7367.4  325.69  7676.2  332.65
#Mann= 15 ,-1 , 0
    1591     .16       0  2405.8     .05       0  3333.7      .1       0
  3729.9     .05       0  4759.2     .16       0  5005.2     .07       0
  5011.2     .16       0  5015.5     .12       0  5683.9     .16       0
  5706.6     .12       0  6011.6     .16       0  6418.4      .1       0
  6561.3     .15       0  6587.5      .1       0  6825.1     .05       0
Bank Sta=4962.3,5028.6
XS Rating Curve= 0 ,0
Exp/Cntr=0.3,0.1

Type RM Length L Ch R = 1 ,45000   ,868,868,868
BEGIN DESCRIPTION:
COTTONWOOD CREEK 43.0
END DESCRIPTION:
XS GIS Cut Line= 2
      3590546.12     10660639.32      3595884.63     10659489.15
#Sta/Elev= 30
   894.4  345.69  1409.4  314.25  1627.8  306.37  1677.1     307  1777.7  300.34
  2084.6  288.18  3738.3  288.73  4088.1  288.58  4272.4  288.78  4421.3  289.25
  4510.6   289.4  4878.1  289.62  4969.3  290.77  4979.5  283.11  4993.1  281.84
  4995.8  281.34  4999.1  281.84  5020.4  282.02  5045.4  290.65  5132.8  288.73
  5244.6  288.91    5331  289.94  5428.7  295.49  5607.1  308.83  6022.9  343.64
  6232.2  348.15  6288.9  352.22  6299.1  355.85  6325.7  359.54  6355.4  359.36
#Mann= 13 ,-1 , 0
   894.4     .05       0  3738.3     .16       0  4088.1     .05       0
  4272.4     .16       0  4421.3     .05       0  4510.6     .16       0
  4878.1     .12       0  4993.1     .07       0  4999.1     .12       0
  5132.8     .16       0  5244.6     .05       0  5428.7     .16       0
  5607.1     .05       0
Bank Sta=4969.3,5045.4
XS Rating Curve= 0 ,0
Exp/Cntr=0.3,0.1

Type RM Length L Ch R = 1 ,44132   ,537,537,537
BEGIN DESCRIPTION:
COTTONWOOD CREEK 42.0
END DESCRIPTION:
XS GIS Cut Line= 3
      3591599.64     10661460.18      3594799.61     10660460.19
      3595499.57     10660010.21
#Sta/Elev= 30
    1636  325.42  1772.2   323.1  1852.3  319.34  2257.8  291.34  2306.5  288.91
  2369.4  287.89  2474.1  288.81  2760.7  287.44  4128.9  286.46  4669.6  286.79
  4845.2  288.23  4957.1  290.29  4967.1  286.17  4972.3   285.6    4983  282.03
  4985.7  281.53    4989  282.03  5002.1  282.31  5011.4  289.79  5017.3  288.65
  5024.2  290.25  5105.1  288.15    5335  288.28    5438  296.92  5459.2  300.01
  5574.1  309.99  5610.2  314.36    5683  319.89  5725.6  324.88  5820.7  331.41
#Mann= 5 ,-1 , 0
    1636     .05       0  4845.2     .12       0    4983     .07       0
    4989     .12       0  5610.2     .16       0
Bank Sta=4957.1,5011.4
XS Rating Curve= 0 ,0
Exp/Cntr=0.3,0.1

Type RM Length L Ch R = 1 ,43595   ,549,549,549
BEGIN DESCRIPTION:
COTTONWOOD CREEK 41.0
END DESCRIPTION:
XS GIS Cut Line= 3
      3592049.65     10661660.18      3594949.61     10660960.19
       3595749.6      10660160.2
#Sta/Elev= 30
  1991.7  329.57  2156.3  315.45  2308.4  305.49  2372.3  299.17  2536.9  289.46
  2588.3  288.42  3161.5  289.62  3555.3  286.59  3716.2  288.03  3791.9   286.6
  4761.2  286.73  4863.9  288.03  4978.5  289.79  5000.2  282.52    5003  282.02
  5006.2  282.52  5017.4   283.1  5031.5  287.87  5045.7  289.31  5108.9  287.54
  5200.8  287.62  5334.3  287.69  5400.2  287.75  5467.7  287.73  5554.8  288.06
  5738.2  305.04  5823.5  312.33  5908.3  316.45  5950.8  316.55  6106.3  330.78
#Mann= 11 ,-1 , 0
  1991.7     .05       0  4761.2     .16       0  4863.9     .12       0
  5000.2     .07       0  5006.2     .12       0  5108.9     .16       0
  5200.8     .07       0  5334.3     .12       0  5400.2     .07       0
  5467.7     .12       0  5738.2     .16       0
Bank Sta=4978.5,5045.7
XS Rating Curve= 0 ,0
Exp/Cntr=0.3,0.1

Type RM Length L Ch R = 1 ,43046   ,1033,1033,1033
BEGIN DESCRIPTION:
COTTONWOOD CREEK 40.0
END DESCRIPTION:
XS GIS Cut Line= 3
      3592399.63     10661810.19      3594799.61     10661410.19
      3595899.59     10661310.19
#Sta/Elev= 30
  2568.9  317.62  2619.6  311.76  2710.8  305.66  2741.2  301.14  2913.6  291.68
  3088.5  289.37  3258.3  290.89  4144.2  286.61  4180.3  286.54  4749.8   286.7
  4951.3  289.13  4961.4   287.8    4969  280.85  4974.1  282.76  4996.5  280.26
  4999.2  279.76  5002.5  280.26  5022.1  287.79  5032.1  288.75  5062.2  289.05
  5072.3  286.58  5092.4  288.64  5102.4  287.07  5326.8  287.79  5625.9  286.88
    5735  286.88  5813.1  295.26  5821.5  295.94  5855.5  300.77  6106.5  322.42
#Mann= 10 ,-1 , 0
  2568.9     .05       0  4144.2     .16       0  4180.3     .05       0
  4749.8     .12       0  4996.5     .07       0  5002.5     .12       0
  5326.8     .07       0  5625.9     .12       0  5813.1     .16       0
  5821.5     .12       0
Bank Sta=4951.3,5032.1
XS Rating Curve= 0 ,0
Exp/Cntr=0.3,0.1

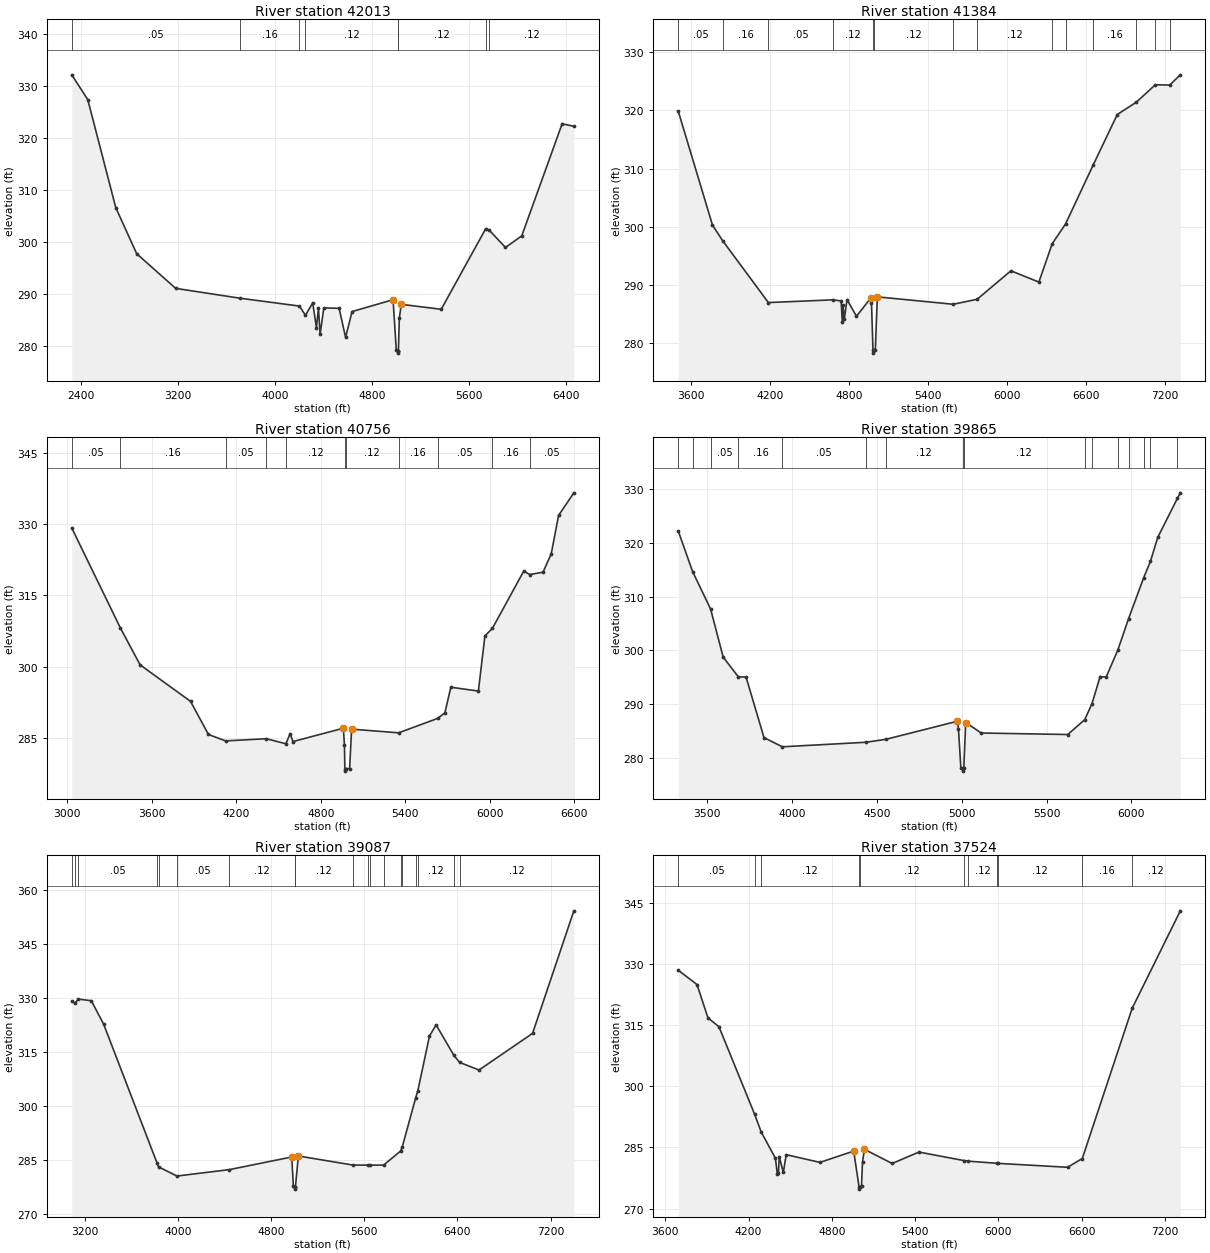
Type RM Length L Ch R = 1 ,42013   ,629,629,629
BEGIN DESCRIPTION:
COTTONWOOD CREEK 39.0
END DESCRIPTION:
XS GIS Cut Line= 4
      3592201.89     10661882.11       3594618.6     10662319.61
      3594951.93     10662236.28      3595950.96     10661334.38
#Sta/Elev= 30
  2322.1  332.11  2454.3  327.34  2685.6  306.56  2858.4  297.71    3180  291.05
  3713.3  289.15  4201.9  287.65  4251.5  285.86  4311.6  288.27  4342.1   283.5
  4358.8  287.29  4372.6  282.21  4403.1  287.29  4529.4  287.22  4582.9  281.64
  4636.4  286.59    4975  288.87  5001.6   279.2  5013.2   279.1    5016   278.6
  5019.2   279.1  5026.5   285.3  5042.9  287.98  5372.4  287.03    5740  302.52
  5769.8  302.22    5903  298.91  6037.5  301.15  6370.8  322.69  6467.6  322.22
#Mann= 8 ,-1 , 0
  2322.1     .05       0  3713.3     .16       0  4201.9     .05       0
  4251.5     .12       0  5013.2     .07       0  5019.2     .12       0
    5740     .16       0  5769.8     .12       0
Bank Sta=4975,5042.9
XS Rating Curve= 0 ,0
Exp/Cntr=0.3,0.1

Type RM Length L Ch R = 1 ,41384   ,628,628,628
BEGIN DESCRIPTION:
COTTONWOOD CREEK 38.0
END DESCRIPTION:
XS GIS Cut Line= 3
      3593340.81     10663562.68      3594875.54     10662507.11
      3596665.88     10661736.85
#Sta/Elev= 30
  3505.9  319.88  3765.8  300.29  3843.1   297.6  4190.4  286.97  4679.2  287.44
  4742.6  287.25  4751.4  283.65  4757.5  286.57  4766.3  284.06  4787.3  287.49
    4859  284.61  4966.5  287.72    4973  286.97  4984.5  278.78  4987.2  278.28
  4990.5  278.78  5002.4  278.88  5017.3  287.95  5593.4  286.68  5774.7  287.53
  6031.5  292.43  6243.9  290.49  6344.7  297.07  6446.3  300.48    6655  310.56
  6839.1  319.29  6984.4  321.42  7127.7   324.4  7237.3  324.35  7317.6  326.11
#Mann= 14 ,-1 , 0
  3505.9     .05       0  3843.1     .16       0  4190.4     .05       0
  4679.2     .12       0  4984.5     .07       0  4990.5     .12       0
  5593.4     .16       0  5774.7     .12       0  6344.7     .16       0
  6446.3     .12       0    6655     .16       0  6984.4     .05       0
  7127.7     .16       0  7237.3     .12       0
Bank Sta=4966.5,5017.3
XS Rating Curve= 0 ,0
Exp/Cntr=0.3,0.1

Type RM Length L Ch R = 1 ,40756   ,891,891,891
BEGIN DESCRIPTION:
COTTONWOOD CREEK 37.0
END DESCRIPTION:
XS GIS Cut Line= 3
      3593849.64     10664460.15      3594999.61     10662910.19
       3596399.6     10662060.19
#Sta/Elev= 30
  3031.1  329.17  3377.2   308.1  3516.7  300.38  3875.1   292.7  4002.3  285.73
  4124.5  284.38  4413.7  284.84  4552.9  283.78  4582.4   285.9  4603.2  284.24
  4961.1  287.05  4968.8  283.52  4971.7  278.52  4974.4  278.02  4977.7  278.52
  5005.6  278.57  5019.6  286.85  5353.7  286.08  5630.1   289.1  5682.1  290.25
  5724.8  295.67  5920.6  294.87    5967  306.46  6020.8  308.09  6242.3  320.07
  6287.1  319.38  6379.9  319.88  6438.1  323.72  6490.4  331.81  6598.9  336.57
#Mann= 11 ,-1 , 0
  3031.1     .05       0  3377.2     .16       0  4124.5     .05       0
  4413.7     .16       0  4552.9     .12       0  4971.7     .07       0
  4977.7     .12       0  5353.7     .16       0  5630.1     .05       0
  6020.8     .16       0  6287.1     .05       0
Bank Sta=4961.1,5019.6
XS Rating Curve= 0 ,0
Exp/Cntr=0.3,0.1

Type RM Length L Ch R = 1 ,39865   ,778,778,778
BEGIN DESCRIPTION:
COTTONWOOD CREEK 36.0
END DESCRIPTION:
XS GIS Cut Line= 2
      3594398.95      10664554.1      3596412.29     10662384.56
#Sta/Elev= 30
  3328.2   322.2  3412.9  314.65    3519  307.69    3593  298.77  3682.9  295.08
  3727.9  295.06  3833.9   283.8  3942.4   282.1  4433.8  282.94  4552.4  283.49
  4972.9  286.84  4980.2  285.46  4994.4  278.11  5005.6  278.08  5008.3  277.58
  5011.6  278.08  5022.8  286.61  5114.6  284.66  5624.3  284.38  5724.5  287.13
  5767.5  290.13  5815.3  295.14  5850.5  295.03  5919.4  300.05  5982.7  305.88
  6071.3  313.44  6111.8  316.54  6154.9     321  6271.3  328.28    6288  329.28
#Mann= 16 ,-1 , 0
  3328.2     .05       0  3412.9     .12       0    3519     .05       0
  3682.9     .16       0  3942.4     .05       0  4433.8     .16       0
  4552.4     .12       0  5005.6     .07       0  5011.6     .12       0
  5724.5     .16       0  5767.5     .05       0  5919.4     .12       0
  5982.7     .05       0  6071.3     .16       0  6111.8     .05       0
  6271.3     .12       0
Bank Sta=4972.9,5022.8
XS Rating Curve= 0 ,0
Exp/Cntr=0.3,0.1

Type RM Length L Ch R = 1 ,39087   ,1563,1563,1563
BEGIN DESCRIPTION:
COTTONWOOD CREEK 34.0
END DESCRIPTION:
XS GIS Cut Line= 2
      3594437.06     10665204.58      3597643.56     10662324.27
#Sta/Elev= 30
  3088.7  329.11  3114.6  328.62  3146.2  329.73  3256.3  329.29  3362.4  322.76
  3819.8  284.22  3833.6  283.08  3991.3  280.52  4442.2  282.31    4977  285.82
  4991.2  277.63  5002.4  277.38  5005.2  276.88  5008.4  277.38  5033.8   286.1
  5504.7  283.56  5627.8  283.56  5645.3  283.56  5765.7  283.56  5911.1  287.47
  5926.5  288.68  6041.4  302.32  6059.8  304.28  6159.6  319.47  6216.4  322.58
  6369.7  314.05  6417.9  312.14  6584.9  310.01  7044.6  320.21  7398.9  354.29
#Mann= 19 ,-1 , 0
  3088.7     .05       0  3114.6     .16       0  3146.2     .05       0
  3819.8     .16       0  3833.6     .12       0  3991.3     .05       0
  4442.2     .12       0  5002.4     .07       0  5008.4     .12       0
  5504.7     .07       0  5627.8      .1       0  5645.3     .12       0
  5765.7      .1       0  5911.1     .16       0  5926.5     .12       0
  6041.4     .16       0  6059.8     .12       0  6369.7     .16       0
  6417.9     .12       0
Bank Sta=4977,5033.8
XS Rating Curve= 0 ,0
Exp/Cntr=0.3,0.1

Type RM Length L Ch R = 1 ,37524   ,802,802,802
BEGIN DESCRIPTION:
COTTONWOOD CREEK 32.0
END DESCRIPTION:
XS GIS Cut Line= 2
      3594971.79     10665753.18      3597853.72     10663565.69
#Sta/Elev= 30
  3693.6  328.47    3829  324.95  3907.9  316.77  3986.9  314.62  4243.4  293.19
  4291.9  288.77  4393.9  282.34  4407.1   278.6  4415.4  278.76  4421.7  282.76
  4450.8  278.85  4471.6  283.22  4714.9  281.33  4958.2   284.1  4996.9  275.27
  4999.6  274.77  5002.9  275.27  5014.4  275.62  5021.6  281.48  5035.2  284.54
  5235.1  281.06  5428.3  283.86  5750.5  281.79  5783.7  281.63  5988.8  281.11
  5996.8  281.09  6499.4  280.13  6605.4  282.28  6964.8  319.13  7311.7  343.04
#Mann= 11 ,-1 , 0
  3693.6     .05       0  4243.4     .16       0  4291.9     .12       0
  4996.9     .07       0  5002.9     .12       0  5750.5     .16       0
  5783.7     .12       0  5988.8     .16       0  5996.8     .12       0
  6605.4     .16       0  6964.8     .12       0
Bank Sta=4958.2,5035.2
XS Rating Curve= 0 ,0
Exp/Cntr=0.3,0.1

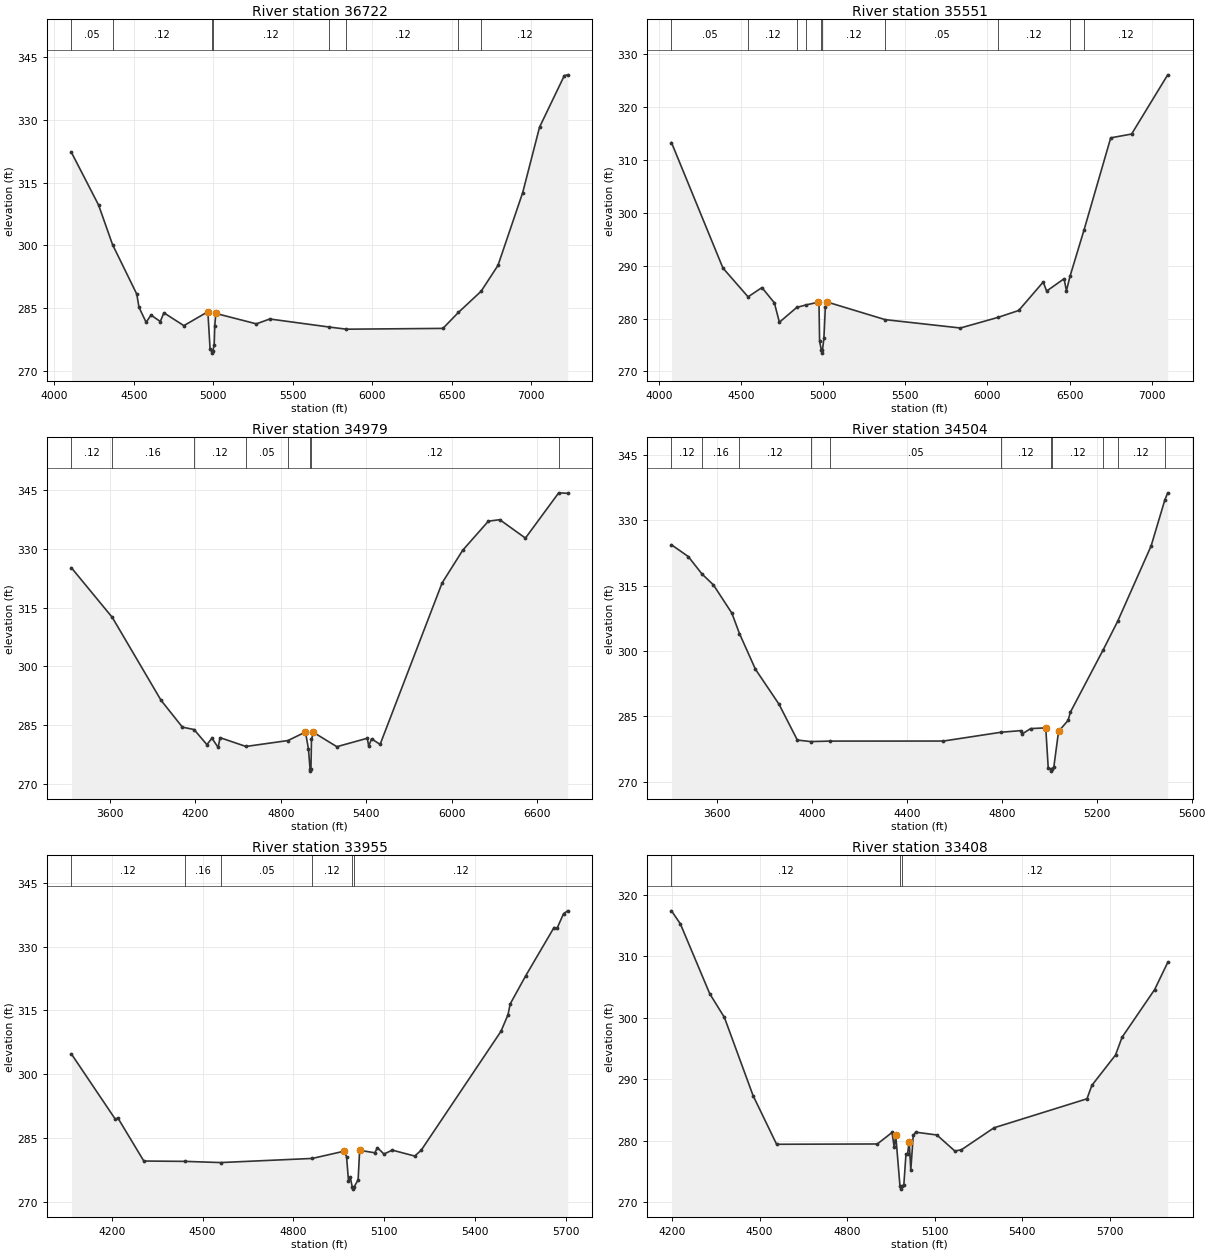
Type RM Length L Ch R = 1 ,36722   ,1171,1171,1171
BEGIN DESCRIPTION:
COTTONWOOD CREEK 30.0
END DESCRIPTION:
XS GIS Cut Line= 3
      3595549.62     10665910.18      3596349.61     10665510.19
      3597899.62     10663910.18
#Sta/Elev= 30
  4108.5  322.19    4279  309.61    4367  300.13  4519.4  288.28  4533.3  285.14
  4578.1  281.54  4608.8  283.27  4667.5  281.73  4689.9  283.81  4815.6  280.74
  4966.6  284.07  4980.6  275.17  4991.5  274.66  4994.3  274.16  4997.5  274.66
  5006.4  276.12    5010   280.7    5017  283.66  5271.6  281.17  5356.5  282.33
  5731.1   280.4  5838.6  279.89  6445.6  280.08    6543   283.9  6685.9  288.97
  6792.1  295.17  6947.7  312.61  7053.7  328.27  7209.4  340.59  7230.6  340.78
#Mann= 8 ,-1 , 0
  4108.5     .05       0    4367     .12       0  4991.5     .07       0
  4997.5     .12       0  5731.1     .16       0  5838.6     .12       0
    6543     .16       0  6685.9     .12       0
Bank Sta=4966.6,5017
XS Rating Curve= 0 ,0
Exp/Cntr=0.3,0.1

Type RM Length L Ch R = 1 ,35551   ,572,572,572
BEGIN DESCRIPTION:
COTTONWOOD CREEK 28.0
END DESCRIPTION:
XS GIS Cut Line= 3
      3595949.64     10666560.17      3596749.61     10666160.19
      3598149.59     10664560.21
#Sta/Elev= 30
  4076.9  313.26  4389.9  289.55    4543   284.1  4627.5  285.85    4703  282.97
  4733.7   279.3  4839.8  282.11  4897.4  282.58  4968.5  283.07  4974.6  283.07
  4978.4  275.71  4989.6  273.96  4992.4  273.46  4995.6  273.96  5004.5  276.25
  5013.5  282.19  5021.1  283.15  5377.5  279.79  5835.5  278.21  6062.8   280.2
  6190.4  281.52  6339.5   286.9  6360.3  285.19  6466.6  287.52  6480.9  285.24
  6502.4  287.95  6588.3  296.77  6750.4  314.15  6877.6  314.87  7097.3  326.06
#Mann= 10 ,-1 , 0
  4076.9     .05       0    4543     .12       0  4839.8     .05       0
  4897.4     .12       0  4989.6     .07       0  4995.6     .12       0
  5377.5     .05       0  6062.8     .12       0  6502.4     .16       0
  6588.3     .12       0
Bank Sta=4968.5,5021.1
XS Rating Curve= 0 ,0
Exp/Cntr=0.3,0.1

Type RM Length L Ch R = 1 ,34979   ,475,475,475
BEGIN DESCRIPTION:
COTTONWOOD CREEK 27.0
END DESCRIPTION:
XS GIS Cut Line= 3
       3595860.7     10667343.44      3597360.69     10666197.61
      3598956.29     10666169.86
#Sta/Elev= 30
  3330.2  325.17  3616.8  312.49  3958.8   291.3    4109  284.42  4190.7  283.81
  4280.8  279.95  4316.2  281.59  4359.8  279.24  4373.3  281.73  4554.9  279.48
  4849.5  280.99  4972.8  283.17  4993.7  278.86  5005.2  273.67  5007.9  273.17
  5011.2  273.67  5015.1  281.31    5029  283.08  5193.2  279.42  5406.7  281.58
  5416.7  279.54  5436.7  281.45  5496.7     280    5932  321.31  6076.8  329.68
  6256.8  337.11  6336.8  337.49  6516.9  332.78  6750.5  344.36  6813.6  344.24
#Mann= 8 ,-1 , 0
  3330.2     .12       0  3616.8     .16       0  4190.7     .12       0
  4554.9     .05       0  4849.5     .12       0  5005.2     .07       0
  5011.2     .12       0  6750.5     .16       0
Bank Sta=4972.8,5029
XS Rating Curve= 0 ,0
Exp/Cntr=0.3,0.1

Type RM Length L Ch R = 1 ,34504   ,549,549,549
BEGIN DESCRIPTION:
COTTONWOOD CREEK 26.0
END DESCRIPTION:
XS GIS Cut Line= 3
      3596449.59      10667610.2      3597599.61     10666510.19
       3598099.6     10666510.19
#Sta/Elev= 30
  3407.6  324.41  3478.2  321.72  3536.1  317.71  3584.5  315.19  3662.2   308.7
    3694  304.03  3761.3  295.84  3860.3  287.83    3938  279.56  3994.5  279.21
  4077.2  279.32  4553.5  279.33  4796.2  281.35  4878.7  281.72  4885.9  280.96
  4921.2  282.19    4985  282.36  4995.5  273.11    5006  272.92  5008.8  272.42
    5012  272.92    5019  273.34    5039  281.56    5079  284.06    5089  285.98
  5227.2   300.3  5288.1  306.84    5429  324.14  5486.9  334.71    5499  336.35
#Mann= 11 ,-1 , 0
  3407.6     .12       0  3536.1     .16       0    3694     .12       0
  3994.5     .07       0  4077.2     .05       0  4796.2     .12       0
    5006     .07       0    5012     .12       0  5227.2     .16       0
  5288.1     .12       0  5486.9     .05       0
Bank Sta=4985,5039
XS Rating Curve= 0 ,0
Exp/Cntr=0.3,0.1

Type RM Length L Ch R = 1 ,33955   ,547,547,547
BEGIN DESCRIPTION:
COTTONWOOD CREEK 25.0
END DESCRIPTION:
XS GIS Cut Line= 3
      3596749.58     10667510.21      3597549.61     10667010.19
      3598149.65     10666660.17
#Sta/Elev= 30
  4067.2  304.75  4211.7  289.47  4220.5  289.72    4306  279.62    4442  279.54
  4559.2  279.26  4862.1  280.23  4966.4  281.92  4975.3  280.66  4981.7  274.95
  4987.6  275.79  4994.1  273.52  4996.8  273.02  5000.1  273.52  5013.5  275.21
  5018.5  282.14  5068.5  281.56  5077.2  282.76  5098.7  281.27  5126.4  282.18
  5200.4  280.79  5221.9  282.18  5485.3  310.12  5508.4  314.03  5515.5  316.53
  5566.3  323.09  5660.2  334.48  5670.1  334.27  5691.6  337.73  5705.3   338.4
#Mann= 6 ,-1 , 0
  4067.2     .12       0    4442     .16       0  4559.2     .05       0
  4862.1     .12       0  4994.1     .07       0  5000.1     .12       0
Bank Sta=4966.4,5018.5
XS Rating Curve= 0 ,0
Exp/Cntr=0.3,0.1

Type RM Length L Ch R = 1 ,33408   ,694,694,694
BEGIN DESCRIPTION:
COTTONWOOD CREEK 24.0
END DESCRIPTION:
XS GIS Cut Line= 3
      3596649.57     10667560.19      3597449.61     10667460.19
      3598249.61     10667060.19
#Sta/Elev= 30
    4198   317.4  4228.3  315.29  4329.1  303.91  4379.4  300.05  4477.7  287.32
  4558.3  279.41  4903.5  279.46  4953.9  281.33  4961.4  278.91  4966.5  280.93
  4981.1  272.61  4983.9  272.11  4987.1  272.61  4994.2  272.72  5001.7  277.82
  5007.1  277.82  5012.7  279.86  5018.2  275.22  5026.6  280.87    5035  281.38
  5107.7  280.92  5169.2  278.31  5191.5  278.51  5303.3  282.09    5622  286.81
  5638.8     289  5719.8  293.93  5742.2  296.82    5854  304.59  5898.7     309
#Mann= 3 ,-1 , 0
    4198     .12       0  4981.1     .07       0  4987.1     .12       0
Bank Sta=4966.5,5012.7
XS Rating Curve= 0 ,0
Exp/Cntr=0.3,0.1