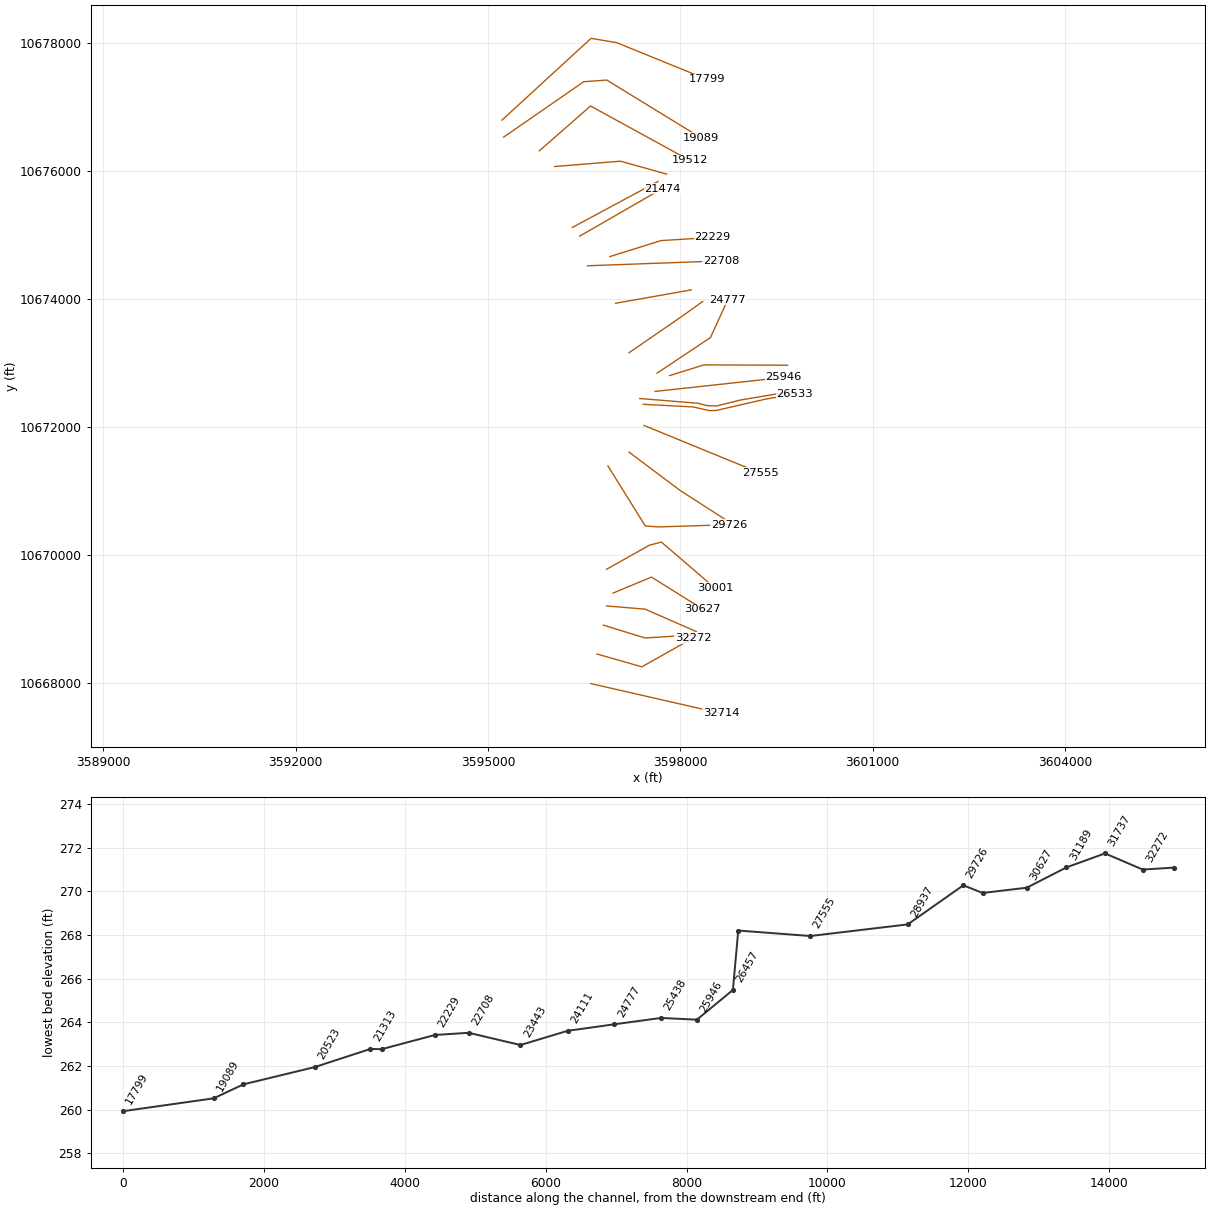
HEC-RAS study COTTONWOOD CREEK.prj: COTTONWOOD CREEK Base Level Engineering

--- COTTONWOOD CREEK.g01 (geometry) --- (continued)

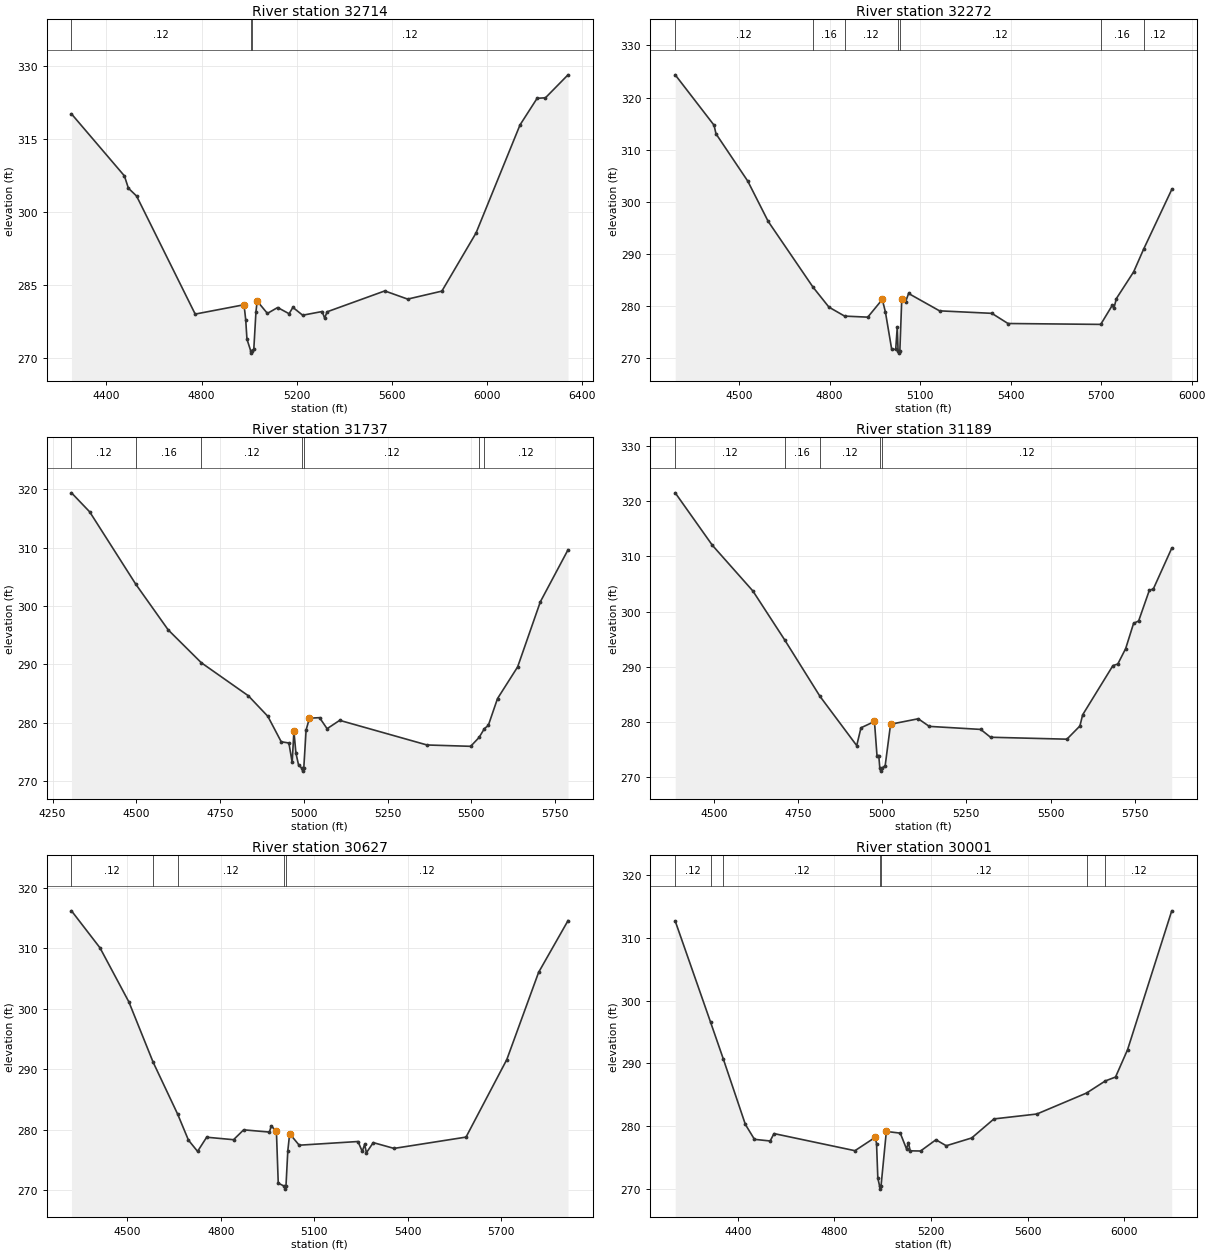
Type RM Length L Ch R = 1 ,32714   ,442,442,442
BEGIN DESCRIPTION:
COTTONWOOD CREEK 23.0
END DESCRIPTION:
XS GIS Cut Line= 2
      3596603.04     10667998.79      3598636.16     10667533.87
#Sta/Elev= 30
  4253.9  320.23  4476.1   307.5  4492.9  304.97  4527.4  303.35  4773.5   279.1
  4978.7  281.02  4985.8  277.88  4990.9  273.95  5006.5  271.58  5009.2  271.08
  5012.5  271.58  5019.7  271.91  5028.8  279.63  5033.9  281.77  5076.8  279.24
  5119.8  280.45  5167.9  279.18  5183.9  280.48  5224.9  278.87    5307  279.63
  5317.2  278.26  5327.5  279.57  5569.8  283.86    5666  282.18  5809.6  283.82
  5953.2  295.77  6137.9  317.97  6209.7  323.44  6244.7  323.54  6339.5  328.26
#Mann= 3 ,-1 , 0
  4253.9     .12       0  5006.5     .07       0  5012.5     .12       0
Bank Sta=4978.7,5033.9
XS Rating Curve= 0 ,0
Exp/Cntr=0.3,0.1

Type RM Length L Ch R = 1 ,32272   ,535,535,535
BEGIN DESCRIPTION:
COTTONWOOD CREEK 22.0
END DESCRIPTION:
XS GIS Cut Line= 3
      3596699.62     10668460.19      3597399.61     10668260.19
      3598199.62      10668710.2
#Sta/Elev= 30
  4288.1  324.36  4416.8   314.7  4423.3  313.05  4528.6  303.98  4596.2  296.26
  4744.8  283.65  4797.7  279.81  4849.6  278.09  4926.4  277.89  4974.5  281.28
  4984.9  278.87  5005.7  271.72    5019  271.71  5024.1  275.95  5026.8  271.49
  5029.6  270.99  5032.8  271.49  5039.1  281.43  5051.5   280.8  5061.7  282.43
  5164.3   279.1  5337.7  278.62  5391.2  276.67  5698.6   276.5  5736.7  280.14
  5742.4  279.62  5750.4  281.45  5807.8  286.58  5840.8  290.93    5934  302.37
#Mann= 7 ,-1 , 0
  4288.1     .12       0  4744.8     .16       0  4849.6     .12       0
  5026.8     .07       0  5032.8     .12       0  5698.6     .16       0
  5840.8     .12       0
Bank Sta=4974.5,5039.1
XS Rating Curve= 0 ,0
Exp/Cntr=0.3,0.1

Type RM Length L Ch R = 1 ,31737   ,548,548,548
BEGIN DESCRIPTION:
COTTONWOOD CREEK 21.0
END DESCRIPTION:
XS GIS Cut Line= 3
      3596799.61     10668910.19      3597449.61     10668710.19
      3598249.57     10668760.19
#Sta/Elev= 30
  4306.6  319.41  4360.9  316.15  4498.5  303.75    4595  295.94    4694   290.3
  4834.3  284.64  4892.5  281.12  4932.4  276.76  4955.3  276.55  4965.1  273.22
  4970.3  278.57  4976.2  274.85  4984.1   272.8  4993.7  272.23  4996.4  271.73
  4999.7  272.23  5006.7   278.8  5016.7   280.8  5046.8  280.89  5069.3     279
  5106.9  280.43  5367.4  276.21  5497.7  275.98  5522.8   277.5  5538.9  279.03
  5550.3  279.55  5577.8  284.16  5637.9  289.59  5705.6  300.74  5788.2  309.65
#Mann= 7 ,-1 , 0
  4306.6     .12       0  4498.5     .16       0    4694     .12       0
  4993.7     .07       0  4999.7     .12       0  5522.8     .16       0
  5538.9     .12       0
Bank Sta=4970.3,5016.7
XS Rating Curve= 0 ,0
Exp/Cntr=0.3,0.1

Type RM Length L Ch R = 1 ,31189   ,562,562,562
BEGIN DESCRIPTION:
COTTONWOOD CREEK 20.0
END DESCRIPTION:
XS GIS Cut Line= 3
      3596849.64     10669210.19      3597449.61     10669160.19
      3598249.65     10668810.17
#Sta/Elev= 30
  4384.9  321.53  4495.2  312.03  4615.7  303.74    4710  294.89  4815.1  284.64
  4924.2  275.72  4936.8  278.94  4976.9  280.09  4984.4  273.92  4989.7  273.92
  4992.9  271.59  4995.7  271.09  4998.9  271.59  5008.8   272.1  5024.8  279.59
    5107  280.58  5139.8   279.2  5292.6  278.65  5321.8  277.23  5548.7  276.88
  5587.3  279.27  5595.5   281.3  5685.5  290.22  5699.9   290.5  5723.3   293.3
  5746.7  297.85  5761.9  298.32  5793.5  303.84  5805.6  304.12  5860.2   311.5
#Mann= 5 ,-1 , 0
  4384.9     .12       0    4710     .16       0  4815.1     .12       0
  4992.9     .07       0  4998.9     .12       0
Bank Sta=4976.9,5024.8
XS Rating Curve= 0 ,0
Exp/Cntr=0.3,0.1

Type RM Length L Ch R = 1 ,30627   ,626,626,626
BEGIN DESCRIPTION:
COTTONWOOD CREEK 19.0
END DESCRIPTION:
XS GIS Cut Line= 3
      3596949.64      10669410.2      3597549.61     10669660.19
      3598349.64     10669160.17
#Sta/Elev= 30
  4320.5  316.16    4412  310.04  4504.6  301.11  4582.5  291.14  4661.4  282.53
  4695.8  278.26  4725.1   276.4  4754.3  278.74  4840.5  278.33    4873  279.96
  4955.8  279.59  4961.3   280.6  4978.1  279.74    4984  271.15  5002.8  270.66
  5005.6  270.16  5008.8  270.66  5014.7  276.49  5020.6  279.32  5051.2  277.42
  5239.9  278.03  5253.5   276.4  5261.2  277.54    5267  276.18  5288.9  277.85
  5355.5  276.89  5586.6  278.76  5717.5  291.58  5819.5  305.99  5913.9  314.54
#Mann= 5 ,-1 , 0
  4320.5     .12       0  4582.5     .16       0  4661.4     .12       0
  5002.8     .07       0  5008.8     .12       0
Bank Sta=4978.1,5020.6
XS Rating Curve= 0 ,0
Exp/Cntr=0.3,0.1

Type RM Length L Ch R = 1 ,30001   ,275,275,275
BEGIN DESCRIPTION:
COTTONWOOD CREEK 18.0
END DESCRIPTION:
XS GIS Cut Line= 4
      3596850.94     10669782.86      3597517.58     10670157.85
      3597705.08     10670206.46      3598538.43     10669491.18
#Sta/Elev= 30
  4140.3  312.68  4287.1  296.51  4339.1  290.73    4431  280.23  4468.6  277.86
  4533.6   277.6  4549.5  278.78  4884.8  276.05  4969.2  278.19  4974.3  277.18
  4979.6  271.68  4986.9  270.42  4989.7  269.92  4992.9  270.42  5014.9  279.12
  5072.6  278.85  5098.6  276.32  5106.1  277.35  5113.8  276.03  5156.6     276
  5220.3  277.79    5263  276.84  5368.4  278.08  5460.7  281.12  5638.4   281.9
  5844.4  285.25  5922.1  287.18  5964.3   287.8  6014.2  292.17  6197.1  314.31
#Mann= 7 ,-1 , 0
  4140.3     .12       0  4287.1     .16       0  4339.1     .12       0
  4986.9     .07       0  4992.9     .12       0  5844.4     .16       0
  5922.1     .12       0
Bank Sta=4969.2,5014.9
XS Rating Curve= 0 ,0
Exp/Cntr=0.3,0.1

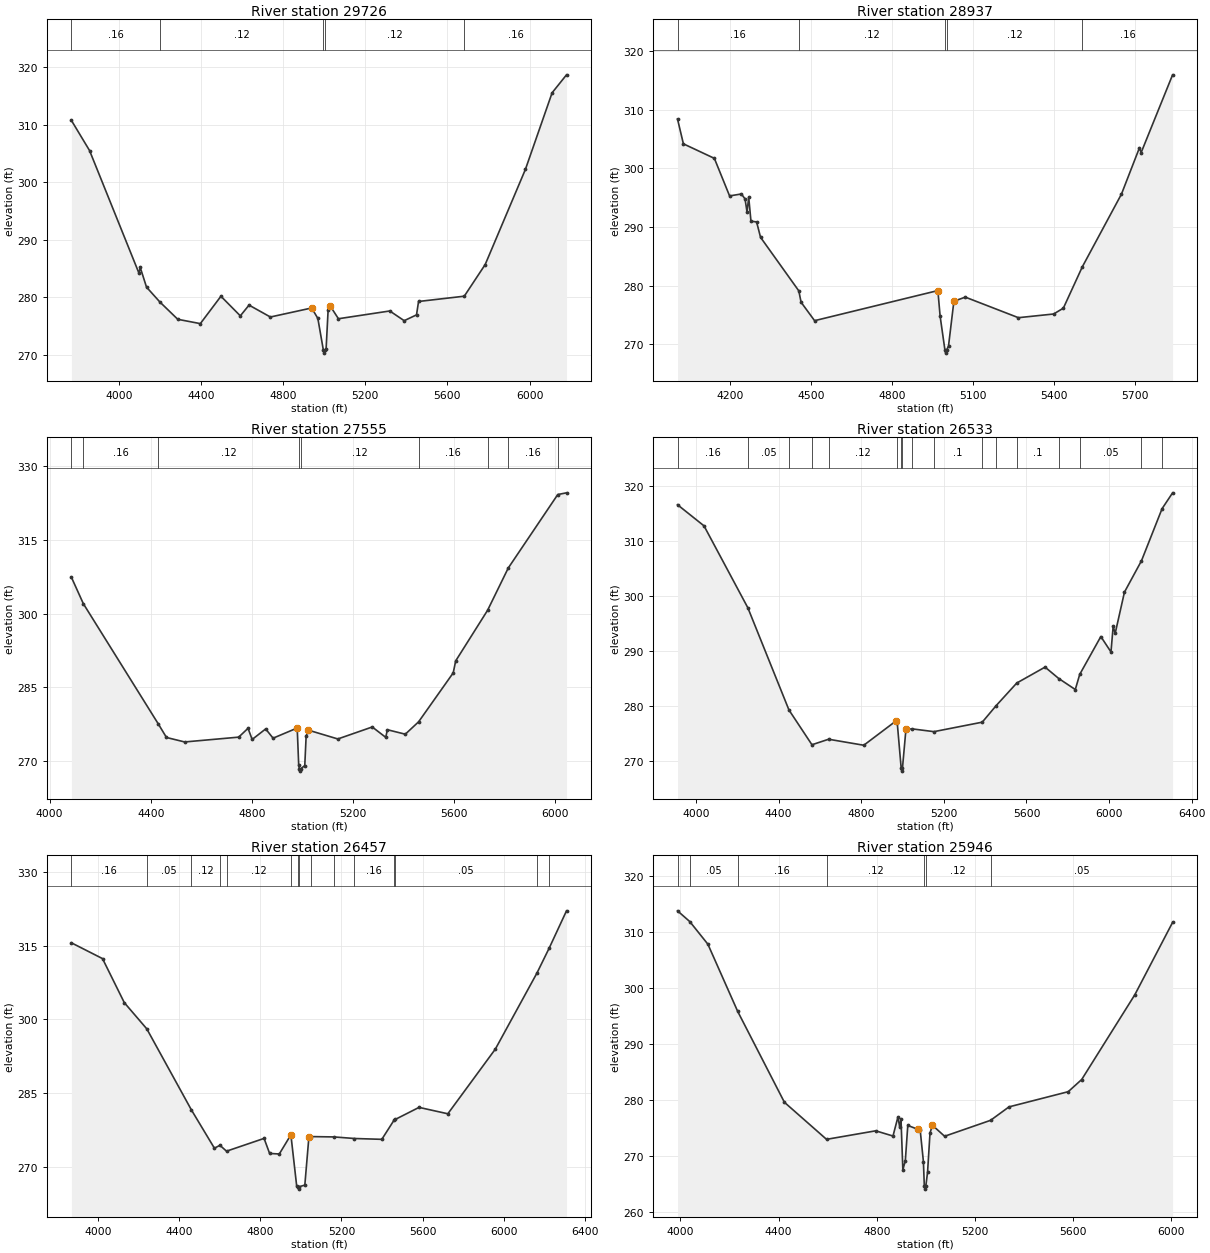
Type RM Length L Ch R = 1 ,29726   ,789,789,789
BEGIN DESCRIPTION:
COTTONWOOD CREEK 17.0
END DESCRIPTION:
XS GIS Cut Line= 4
      3596870.73     10671394.44      3597454.04     10670456.98
      3597669.32     10670443.09      3598759.62     10670477.82
#Sta/Elev= 30
  3769.3  310.73  3857.5   305.5  4098.3  284.16  4104.2  285.19  4134.9  281.75
    4200  279.16  4287.2  276.15    4397   275.4  4497.3  280.16  4591.7  276.75
  4634.2  278.62  4738.1  276.55  4939.1  278.12  4969.2  276.31  4996.2  270.77
    4999  270.27  5002.2  270.77  5009.3  270.91  5019.3  277.82  5029.3  278.47
  5069.4  276.25  5319.5   277.6  5389.6  275.91  5449.6  276.92  5459.6  279.25
  5682.2  280.17    5784  285.67  5979.9  302.22  6109.9  315.54    6180  318.66
#Mann= 5 ,-1 , 0
  3769.3     .16       0    4200     .12       0  4996.2     .07       0
  5002.2     .12       0  5682.2     .16       0
Bank Sta=4939.1,5029.3
XS Rating Curve= 0 ,0
Exp/Cntr=0.3,0.1

Type RM Length L Ch R = 1 ,28937   ,1382,1382,1382
BEGIN DESCRIPTION:
COTTONWOOD CREEK 16.0
END DESCRIPTION:
XS GIS Cut Line= 3
      3597199.64     10671610.17      3597999.61     10671010.19
      3598699.58     10670560.21
#Sta/Elev= 30
  4006.9  308.45  4028.7  304.21  4143.3  301.73  4199.6  295.32  4243.3  295.65
  4256.9   294.8  4264.2  292.56  4270.4  295.11  4278.7     291  4299.6  290.88
  4314.2  288.25  4455.8  279.11  4464.2  277.17  4514.2  274.02  4970.4  279.16
  4978.7   274.8  4996.6  268.98  4999.3  268.48  5002.6  268.98  5009.8   269.7
  5029.7  277.34  5071.9  278.04  5268.4  274.53  5398.8  275.16  5434.8  276.16
  5504.9  283.21  5649.8  295.63  5716.5  303.55  5722.5   302.7    5839  315.99
#Mann= 5 ,-1 , 0
  4006.9     .16       0  4455.8     .12       0  4996.6     .07       0
  5002.6     .12       0  5504.9     .16       0
Bank Sta=4970.4,5029.7
XS Rating Curve= 0 ,0
Exp/Cntr=0.3,0.1

Type RM Length L Ch R = 1 ,27555   ,1022,1022,1022
BEGIN DESCRIPTION:
COTTONWOOD CREEK 15.0
END DESCRIPTION:
XS GIS Cut Line= 2
      3597433.25     10672026.41      3599245.19     10671283.58
#Sta/Elev= 30
  4086.2  307.42  4133.4  302.04  4430.2  277.53  4462.2   274.8  4534.2  273.89
  4747.7  274.87  4784.8  276.67  4801.1   274.4  4854.5  276.54  4883.9  274.66
  4979.3  276.73  4985.2  269.18  4987.6  268.45  4990.4  267.95  4993.6  268.45
  5009.2  269.08  5014.6  275.04  5022.5  276.31    5140   274.5  5276.1  276.94
  5329.5  274.83    5336  276.38  5406.9  275.47  5459.6     278  5596.4  287.96
  5606.2   290.4  5732.2  300.69  5814.2  309.32  6009.9  324.27  6044.5  324.62
#Mann= 9 ,-1 , 0
  4086.2     .05       0  4133.4     .16       0  4430.2     .12       0
  4987.6     .07       0  4993.6     .12       0  5459.6     .16       0
  5732.2     .12       0  5814.2     .16       0  6009.9     .12       0
Bank Sta=4979.3,5022.5
XS Rating Curve= 0 ,0
Exp/Cntr=0.3,0.1

Type RM Length L Ch R = 1 ,26533   ,76,76,76
BEGIN DESCRIPTION:
COTTONWOOD CREEK 14.0
END DESCRIPTION:
XS GIS Cut Line= 6
      3597421.56     10672356.29      3598200.22     10672314.62
      3598455.43     10672257.33       3598559.6     10672259.94
      3599333.03     10672437.02      3599783.58     10672515.15
#Sta/Elev= 30
  3910.1  316.58  4038.5  312.74  4250.8  297.86  4449.9   279.3  4561.2  272.99
  4641.9  273.99  4812.2   272.9  4966.4  277.26  4974.5  276.87  4993.4   268.7
  4996.1   268.2  4999.4   268.7  5016.4  275.81    5047  275.87  5152.1  275.37
  5385.9  277.09  5452.7  280.07  5553.1   284.2  5690.1  287.09  5756.3  285.02
  5836.5  283.02    5858  285.77  5960.2  292.64  6009.3  289.84  6019.9  294.49
  6029.6  293.21  6074.6  300.71    6157   306.4  6256.7  315.86  6307.7  318.74
#Mann= 17 ,-1 , 0
  3910.1     .16       0  4250.8     .05       0  4449.9     .12       0
  4561.2     .05       0  4641.9     .12       0  4974.5     .07       0
  4993.4     .07       0  4999.4     .07       0    5047     .12       0
  5152.1      .1       0  5385.9     .16       0  5452.7     .05       0
  5553.1      .1       0  5756.3     .16       0    5858     .05       0
    6157     .16       0  6256.7     .05       0
Bank Sta=4966.4,5016.4
XS Rating Curve= 0 ,0
Exp/Cntr=0.3,0.1

Type RM Length L Ch R = 1 ,26457   ,511,511,511
BEGIN DESCRIPTION:
COTTONWOOD CREEK 13.0
END DESCRIPTION:
XS GIS Cut Line= 6
      3597366.84     10672446.57      3598280.95     10672371.91
      3598416.37     10672335.46      3598567.41     10672330.25
      3598931.99     10672421.39      3599776.51     10672564.31
#Sta/Elev= 30
  3868.8  315.59  4022.1  312.38  4129.5  303.42  4240.4  298.09  4460.3   281.6
  4573.9   273.8    4601   274.4  4633.5   273.2  4818.7   275.8    4846  272.74
  4893.7  272.63  4950.9  276.53  4979.6  266.06  4986.6  265.98  4989.4  265.48
  4992.6  265.98  5019.6   266.3  5039.6  276.05  5049.3  276.17  5163.5   276.1
  5264.5  275.78  5399.2  275.61  5460.4  279.57  5466.4  279.68  5582.7  282.11
  5724.7  280.81  5958.9  293.97  6164.3  309.46  6224.8  314.55  6309.8   322.1
#Mann= 15 ,-1 , 0
  3868.8     .16       0  4240.4     .05       0  4460.3     .12       0
    4601     .05       0  4633.5     .12       0  4950.9     .07       0
  4986.6     .07       0  4992.6     .07       0  5049.3     .12       0
  5163.5      .1       0  5264.5     .16       0  5460.4      .1       0
  5466.4     .05       0  6164.3     .16       0  6224.8     .05       0
Bank Sta=4950.9,5039.6
XS Rating Curve= 0 ,0
Exp/Cntr=0.3,0.1

Type RM Length L Ch R = 1 ,25946   ,508,508,508
BEGIN DESCRIPTION:
COTTONWOOD CREEK 12.0
END DESCRIPTION:
XS GIS Cut Line= 2
       3597606.5     10672556.81      3599612.53     10672775.37
#Sta/Elev= 30
  3987.9  313.76    4038  311.84  4111.7  307.81  4233.1  295.83  4423.6  279.61
  4595.3     273  4795.8  274.52  4866.2  273.59  4886.3  276.98  4893.8  275.15
  4898.8  276.64  4906.4  267.57  4916.5   269.2  4926.5  275.48  4966.8   274.8
  4976.8  274.74  4990.2  269.03  4993.9  264.62  4996.7  264.12  4999.9  264.62
    5007   267.1  5017.1  274.15  5027.1   275.5  5076.6  273.55  5263.8  276.39
    5339  278.79  5580.4   281.5  5635.3  283.67    5852   298.8  6005.8   311.7
#Mann= 7 ,-1 , 0
  3987.9     .16       0    4038     .05       0  4233.1     .16       0
  4595.3     .12       0  4993.9     .07       0  4999.9     .12       0
  5263.8     .05       0
Bank Sta=4966.8,5027.1
XS Rating Curve= 0 ,0
Exp/Cntr=0.3,0.1

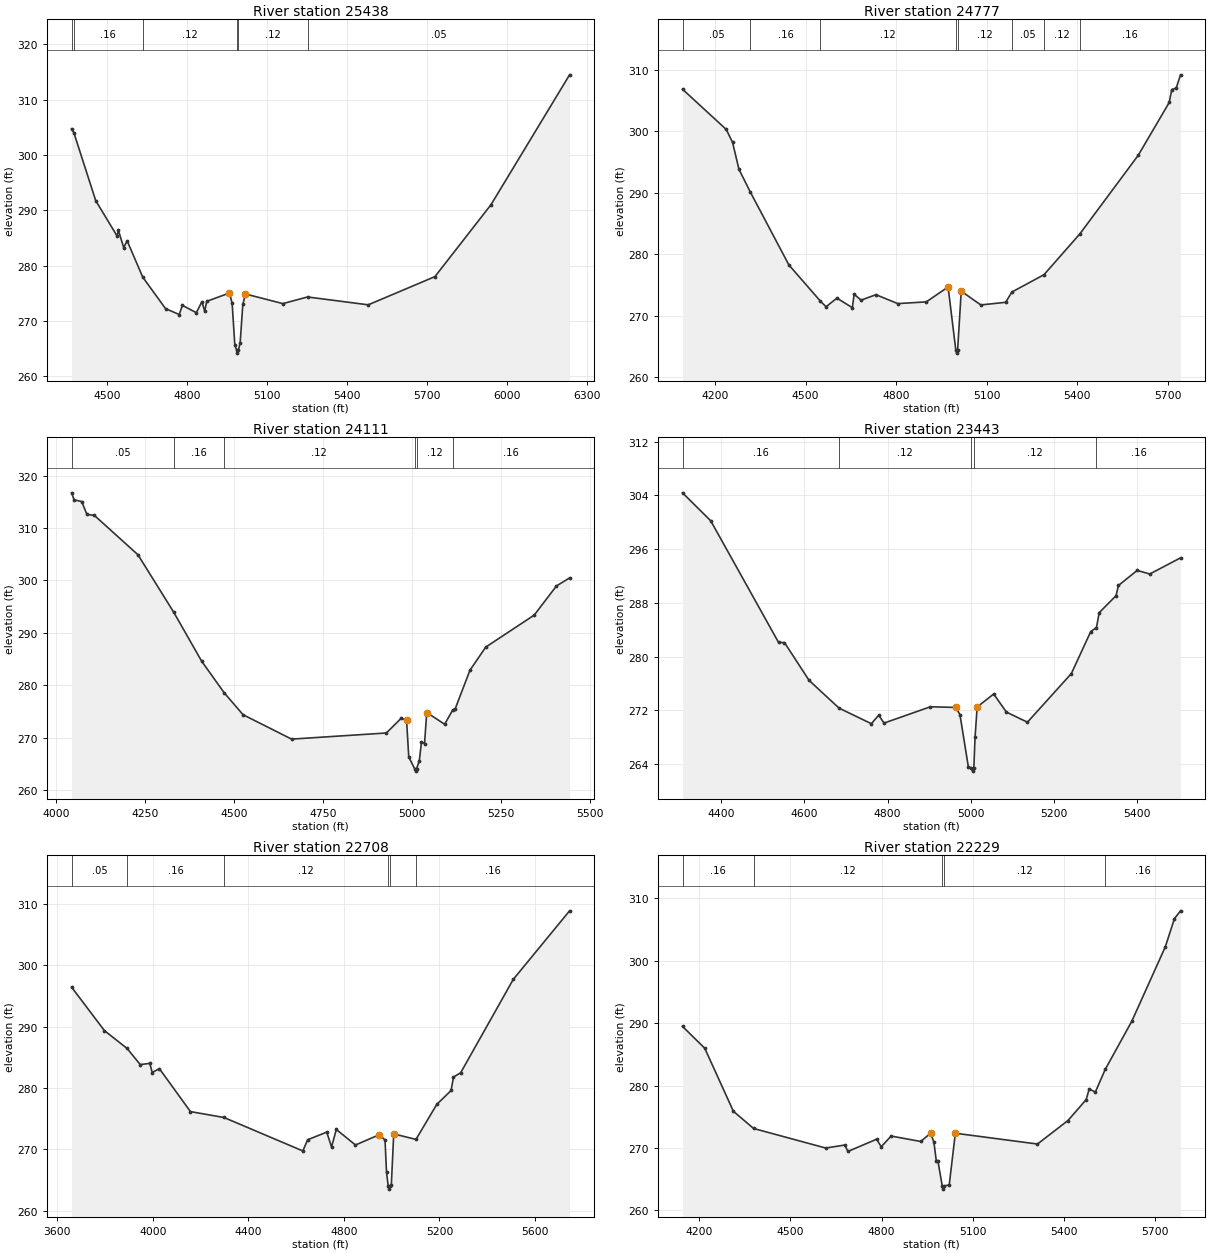
Type RM Length L Ch R = 1 ,25438   ,661,661,661
BEGIN DESCRIPTION:
COTTONWOOD CREEK 11.0
END DESCRIPTION:
XS GIS Cut Line= 3
      3597833.08     10672804.22      3598369.49     10672970.87
      3599674.18     10672965.66
#Sta/Elev= 30
  4367.9  304.75  4376.7  304.01  4458.5  291.75  4538.4  285.38  4543.6  286.37
  4563.2  283.28  4576.2   284.5  4634.6  277.94  4720.3  272.23  4771.5  271.18
  4783.1  272.83  4835.5  271.51  4856.4  273.49  4866.9  271.78  4874.4  273.56
  4959.7  275.07  4969.7  273.22  4979.7  265.71  4986.7   264.7  4989.5   264.2
  4992.7   264.7  4999.7  266.03  5009.7     273  5019.7  274.89  5159.7  273.15
  5252.3  274.35  5479.7  272.93  5729.7  278.03  5939.7  291.02  6234.3   314.5
#Mann= 6 ,-1 , 0
  4367.9     .05       0  4376.7     .16       0  4634.6     .12       0
  4986.7     .07       0  4992.7     .12       0  5252.3     .05       0
Bank Sta=4959.7,5019.7
XS Rating Curve= 0 ,0
Exp/Cntr=0.3,0.1

Type RM Length L Ch R = 1 ,24777   ,666,666,666
BEGIN DESCRIPTION:
COTTONWOOD CREEK 10.0
END DESCRIPTION:
XS GIS Cut Line= 3
      3597637.71     10672842.39      3598471.06     10673397.96
      3598741.18     10673986.69
#Sta/Elev= 30
  4092.2  306.86  4237.1  300.31  4258.1  298.19  4279.1  293.83  4317.3  290.08
  4444.4  278.27  4549.1  272.36  4567.6  271.46  4603.6  272.86  4654.7  271.31
  4660.7   273.5  4683.4  272.53  4732.8  273.42    4805  271.97  4899.7  272.25
  4971.8  274.68  4997.3  264.41    5000  263.91  5003.3  264.41  5015.3     274
    5080  271.75  5162.2  272.18  5183.3  273.86  5289.5  276.68  5407.9   283.3
  5601.3  296.09  5704.3  304.72  5712.3  306.79  5727.3  307.06  5741.5   309.2
#Mann= 8 ,-1 , 0
  4092.2     .05       0  4317.3     .16       0  4549.1     .12       0
  4997.3     .07       0  5003.3     .12       0  5183.3     .05       0
  5289.5     .12       0  5407.9     .16       0
Bank Sta=4971.8,5015.3
XS Rating Curve= 0 ,0
Exp/Cntr=0.3,0.1

Type RM Length L Ch R = 1 ,24111   ,668,668,668
BEGIN DESCRIPTION:
COTTONWOOD CREEK 9.0
END DESCRIPTION:
XS GIS Cut Line= 3
      3597199.62      10673160.2      3597999.61     10673710.19
      3598349.59     10673960.17
#Sta/Elev= 30
  4042.6  316.73    4050  315.38    4071  315.07  4085.9   312.6  4106.8  312.42
  4229.3  304.91  4329.6  293.98  4408.6  284.59  4471.7  278.58    4525  274.38
  4661.5  269.72  4928.2  270.89  4970.1  273.72    4985  273.32  4991.1  266.31
  5007.4  264.11  5010.1  263.61  5013.4  264.11  5020.8  265.61  5026.9  269.16
  5035.5  268.88  5041.7   274.8  5092.1  272.56  5114.9   275.3  5121.6  275.48
  5163.3  282.87  5207.6  287.28    5344  293.39  5406.7  298.96  5443.5  300.48
#Mann= 6 ,-1 , 0
  4042.6     .05       0  4329.6     .16       0  4471.7     .12       0
  5007.4     .07       0  5013.4     .12       0  5114.9     .16       0
Bank Sta=4985,5041.7
XS Rating Curve= 0 ,0
Exp/Cntr=0.3,0.1

Type RM Length L Ch R = 1 ,23443   ,735,735,735
BEGIN DESCRIPTION:
COTTONWOOD CREEK 8.0
END DESCRIPTION:
XS GIS Cut Line= 2
       3596991.9     10673932.68      3598172.45     10674141.01
#Sta/Elev= 30
  4306.5  304.38  4374.3  300.23  4537.7  282.12    4552  282.09  4611.3  276.46
  4683.5  272.33  4761.1  270.02  4778.8  271.29  4791.6  270.11  4903.3  272.54
  4964.2  272.44  4974.4  271.37  4994.7  263.55  5001.8  263.46  5004.6  262.96
  5007.8  263.46  5010.7  267.98  5015.8  272.51  5055.6  274.44  5086.1  271.75
  5136.8  270.24  5242.5  277.48  5289.2  283.73    5303  284.33  5309.5  286.54
  5350.1  289.07  5355.9  290.59  5400.9  292.83  5431.3   292.3  5505.3   294.7
#Mann= 5 ,-1 , 0
  4306.5     .16       0  4683.5     .12       0  5001.8     .07       0
  5007.8     .12       0    5303     .16       0
Bank Sta=4964.2,5015.8
XS Rating Curve= 0 ,0
Exp/Cntr=0.3,0.1

Type RM Length L Ch R = 1 ,22708   ,479,479,479
BEGIN DESCRIPTION:
COTTONWOOD CREEK 7.0
END DESCRIPTION:
XS GIS Cut Line= 2
      3596552.34     10674517.17      3598635.14     10674593.54
#Sta/Elev= 30
  3660.3  296.43  3797.7  289.35  3892.6  286.44  3947.8  283.81  3987.8  284.01
  3997.8  282.52  4027.8  283.15  4157.9  276.15  4298.2  275.19  4628.2  269.74
  4648.2  271.56  4728.3  272.81  4748.3  270.38  4768.3  273.24  4848.4  270.71
  4948.4  272.39  4972.1  271.52  4978.5  266.23  4985.5  264.02  4988.2  263.52
  4991.5  264.02  4998.5  264.18  5008.5  272.52  5101.7  271.62  5188.6  277.32
  5248.7  279.59  5258.6  281.78  5288.7  282.48  5508.8  297.69  5744.5  308.86
#Mann= 6 ,-1 , 0
  3660.3     .05       0  3892.6     .16       0  4298.2     .12       0
  4985.5     .07       0  4991.5     .12       0  5101.7     .16       0
Bank Sta=4948.4,5008.5
XS Rating Curve= 0 ,0
Exp/Cntr=0.3,0.1

Type RM Length L Ch R = 1 ,22229   ,755,755,755
BEGIN DESCRIPTION:
COTTONWOOD CREEK 6.0
END DESCRIPTION:
XS GIS Cut Line= 3
      3596899.61     10674660.19      3597699.61     10674910.19
       3598499.6     10674960.19
#Sta/Elev= 30
  4144.6  289.48  4217.9  285.97  4312.2  275.88  4378.7  273.13  4616.1     270
  4678.9  270.48  4689.4  269.46  4783.7  271.41  4798.9   270.2  4831.4  271.92
  4928.8  271.05  4961.3  272.36  4972.3  270.96  4980.1  267.99  4985.3  267.99
  4999.8  263.92  5002.5  263.42  5005.8  263.92  5022.8   264.1  5042.9  272.37
  5313.4  270.64  5413.6   274.4  5473.7  277.75  5483.7  279.47  5503.8  278.95
  5536.3  282.58    5624  290.31  5734.2  302.21  5764.3  306.73  5784.3  307.98
#Mann= 5 ,-1 , 0
  4144.6     .16       0  4378.7     .12       0  4999.8     .07       0
  5005.8     .12       0  5536.3     .16       0
Bank Sta=4961.3,5042.9
XS Rating Curve= 0 ,0
Exp/Cntr=0.3,0.1

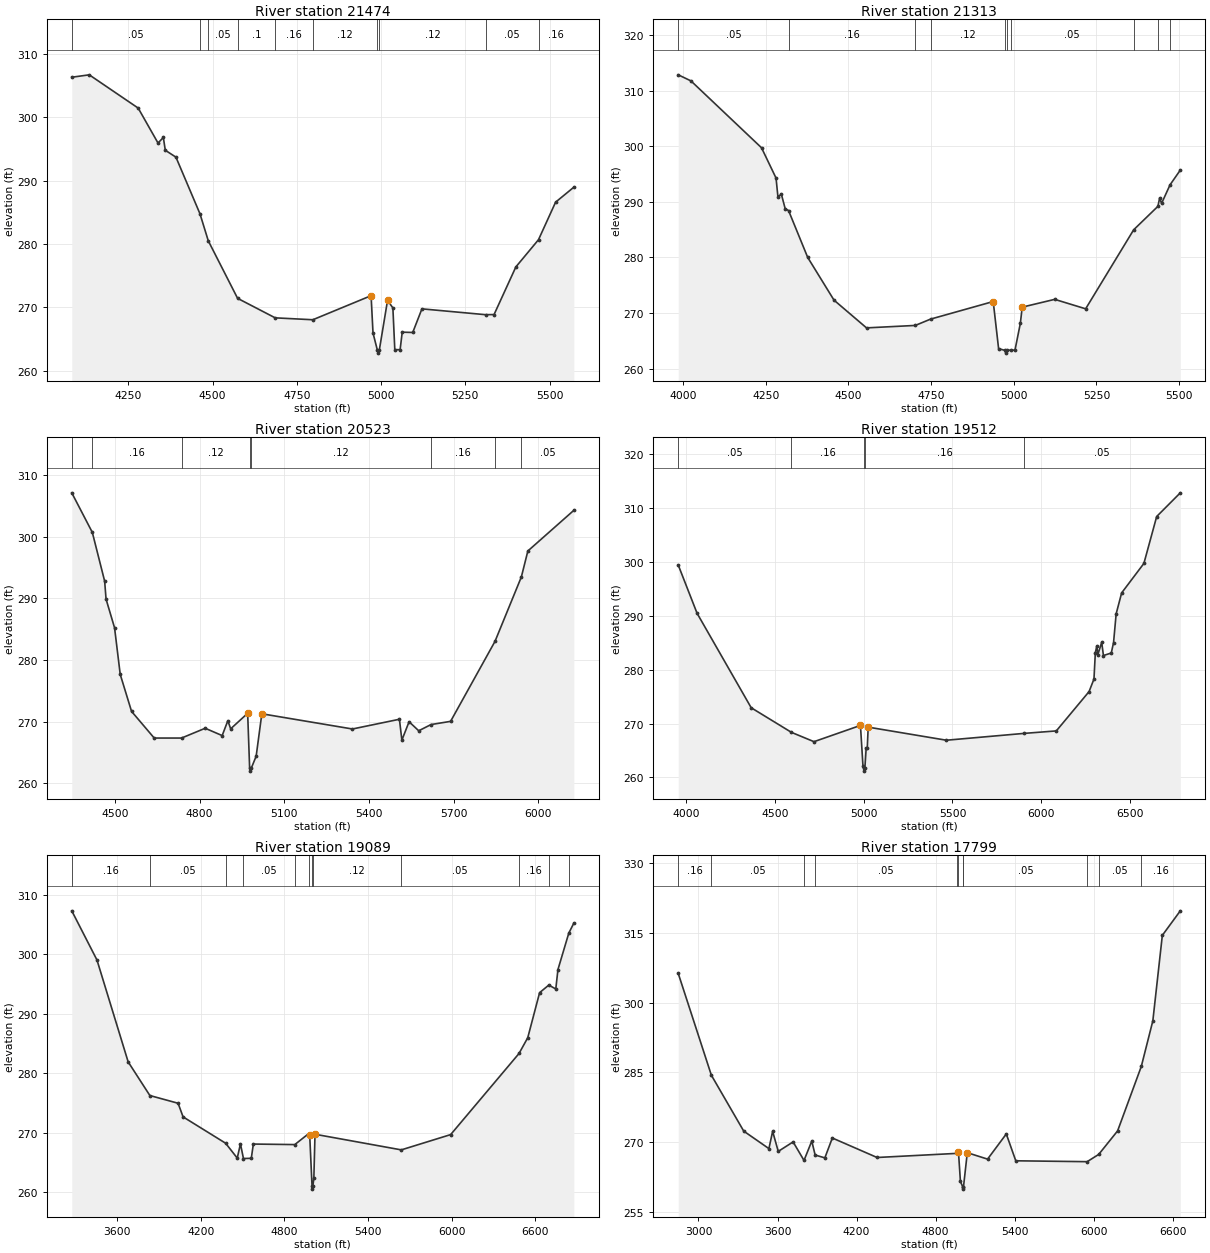
Type RM Length L Ch R = 1 ,21474   ,161,161,161
BEGIN DESCRIPTION:
COTTONWOOD CREEK 5.0
END DESCRIPTION:
XS GIS Cut Line= 2
      3596429.45     10674979.39      3597721.16     10675722.48
#Sta/Elev= 30
  4081.9  306.33  4133.8  306.71    4279  301.46  4337.9  295.94  4353.7  296.82
  4359.5   294.8  4391.1  293.71  4462.4  284.77  4487.1   280.5  4574.1  271.42
  4685.7  268.34  4797.4  268.04  4970.3  271.84    4976  265.95  4988.8  263.27
  4991.6  262.77  4994.8  263.27  5019.2  271.11    5035   269.9  5040.7  263.31
  5056.5  263.32  5062.7  266.08  5093.9  266.03  5121.2  269.76  5309.9  268.84
  5335.3  268.86    5400  276.38  5467.2  280.68  5517.9   286.6  5572.1  288.97
#Mann= 10 ,-1 , 0
  4081.9     .05       0  4462.4      .1       0  4487.1     .05       0
  4574.1      .1       0  4685.7     .16       0  4797.4     .12       0
  4988.8     .07       0  4994.8     .12       0  5309.9     .05       0
  5467.2     .16       0
Bank Sta=4970.3,5019.2
XS Rating Curve= 0 ,0
Exp/Cntr=0.3,0.1

Type RM Length L Ch R = 1 ,21313   ,790,790,790
BEGIN DESCRIPTION:
COTTONWOOD CREEK 4.0
END DESCRIPTION:
XS GIS Cut Line= 2
      3596314.88     10675114.82      3597651.71     10675833.58
#Sta/Elev= 30
  3985.8  312.83  4024.2  311.74  4237.6  299.71  4281.5  294.26  4287.1  290.93
  4297.7  291.33  4309.1  288.76  4319.3  288.42  4377.2  279.99  4456.7  272.31
    4555  267.32  4702.4  267.76  4748.8   268.9    4938  272.06  4954.3  263.58
  4973.2  263.28  4975.9  262.78  4979.2  263.28  4990.7  263.32  5003.8  263.32
    5020  268.13  5025.7  271.05  5123.9  272.45  5217.4  270.75  5362.6  284.96
  5435.9  289.18  5441.2   290.7  5446.9   289.7  5472.6  293.05  5503.6   295.7
#Mann= 10 ,-1 , 0
  3985.8     .05       0  4319.3     .16       0  4702.4     .07       0
  4748.8     .12       0  4973.2    .035       0  4979.2     .12       0
  4990.7     .05       0  5362.6     .16       0  5435.9     .05       0
  5472.6     .16       0
Bank Sta=4938,5025.7
XS Rating Curve= 0 ,0
Exp/Cntr=0.3,0.1

Type RM Length L Ch R = 1 ,20523   ,1011,1011,1011
BEGIN DESCRIPTION:
COTTONWOOD CREEK 3.0
END DESCRIPTION:
XS GIS Cut Line= 3
      3596038.46     10676065.78      3597066.19     10676149.11
      3597786.51     10675948.26
#Sta/Elev= 30
  4347.2  307.13    4420  300.71  4463.7  292.79  4468.7  289.87  4498.8  285.22
  4518.9  277.65    4559  271.65  4639.3  267.32  4736.1  267.32  4819.9  268.91
  4880.1  267.72  4900.2  270.14  4910.2  268.82  4970.4  271.34  4977.4  262.45
  4980.2  261.95  4983.4  262.45  5000.5  264.37  5020.6  271.26  5341.6  268.79
  5508.1  270.37  5516.8  266.98  5542.3  269.97  5576.5   268.5    5620  269.51
  5689.4  270.03  5846.8  283.02  5940.1  293.47  5963.2  297.69  6126.1  304.29
#Mann= 8 ,-1 , 0
  4347.2     .05       0    4420     .16       0  4736.1     .12       0
  4977.4     .07       0  4983.4     .12       0    5620     .16       0
  5846.8      .1       0  5940.1     .05       0
Bank Sta=4970.4,5020.6
XS Rating Curve= 0 ,0
Exp/Cntr=0.3,0.1

Type RM Length L Ch R = 1 ,19512   ,423,423,423
BEGIN DESCRIPTION:
COTTONWOOD CREEK 2.0
END DESCRIPTION:
XS GIS Cut Line= 3
      3595799.63     10676310.21      3596599.61     10677010.19
      3598149.65     10676160.17
#Sta/Elev= 30
  3953.7  299.44    4060  290.47  4365.1  272.93  4592.1  268.36  4719.1  266.63
  4981.1  269.65  4995.3  262.09  4999.9  261.66  5002.7  261.16  5005.9  261.66
  5013.4  265.47  5019.5  265.47  5024.7  269.33  5465.5   266.9  5904.2  268.17
  6085.4  268.63  6270.2  275.94  6297.7  278.27  6305.4  283.16  6313.8  284.41
  6319.5   282.8  6341.3  285.08  6351.1  282.63  6395.3   283.1  6408.1  285.04
  6422.8  290.38  6453.7  294.26  6579.2  299.74  6651.3  308.45  6784.5  312.85
#Mann= 5 ,-1 , 0
  3953.7     .05       0  4592.1     .16       0  4999.9     .07       0
  5005.9     .16       0  5904.2     .05       0
Bank Sta=4981.1,5024.7
XS Rating Curve= 0 ,0
Exp/Cntr=0.3,0.1

Type RM Length L Ch R = 1 ,19089   ,1290,1290,1290
BEGIN DESCRIPTION:
Mapping XS 9e9e8347
END DESCRIPTION:
XS GIS Cut Line= 4
       3595243.3     10676524.13      3596493.28      10677388.7
      3596852.65     10677414.74      3598320.16     10676514.46
#Sta/Elev= 30
  3275.2  307.32    3456  299.05  3679.7  281.92  3835.5  276.26  4037.9  274.96
  4073.7  272.67  4378.9  268.24  4462.3  265.74  4485.3  268.13  4506.8  265.67
    4563   265.7  4577.9   268.1  4875.1  268.01    4974  269.84  4981.9  269.69
  4998.9  261.02  5001.7  260.52  5004.9  261.02  5011.9  262.41  5020.1  269.75
  5639.2  267.12  5993.3  269.69  6483.7  283.33  6546.3  285.98  6631.4  293.56
  6697.3  294.83  6747.5  294.18  6762.9  297.44  6840.6  303.56    6877  305.26
#Mann= 12 ,-1 , 0
  3275.2     .16       0  3835.5     .05       0  4378.9     .16       0
  4506.8     .05       0  4875.1     .16       0    4974     .12       0
  4998.9     .07       0  5004.9     .12       0  5639.2     .05       0
  6483.7     .16       0  6697.3     .05       0  6840.6     .16       0
Bank Sta=4981.9,5020.1
XS Rating Curve= 0 ,0
Exp/Cntr=0.3,0.1

Type RM Length L Ch R = 1 ,17799   ,0,0,0
BEGIN DESCRIPTION:
COTTONWOOD CREEK 1.0
END DESCRIPTION:
XS GIS Cut Line= 4
      3595217.26     10676789.76      3596607.86     10678065.78
       3597008.9     10677998.07      3598414.86     10677425.27
#Sta/Elev= 30
  2846.2   306.3  3097.8  284.41  3343.5   272.4  3534.7  268.64    3563  272.35
  3605.6  268.04  3718.4  270.08  3801.2   266.1  3860.2  270.26  3885.7  267.26
  3959.5  266.65  4016.2  270.92  4355.9  266.73  4966.1  267.62  4974.2  267.85
  4988.8  261.58  5006.1  260.43  5008.9  259.93  5012.1  260.43    5041  267.76
    5195  266.38  5337.1  271.79  5409.2  266.02  5951.2  265.83  6039.1   267.4
  6182.3  272.45  6362.1  286.29  6449.8   296.1  6521.9  314.48  6658.4  319.75
#Mann= 11 ,-1 , 0
  2846.2     .16       0  3097.8     .05       0  3801.2     .16       0
  3885.7     .05       0  4966.1     .12       0  4974.2     .05       0
  5006.1     .03       0  5012.1     .05       0  5951.2     .16       0
  6039.1     .05       0  6362.1     .16       0
Bank Sta=4974.2,5041
XS Rating Curve= 0 ,0
Exp/Cntr=0.3,0.1

Chan Stop Cuts=-1
Use User Specified Reach Order=0
Composite Channel Slope=5