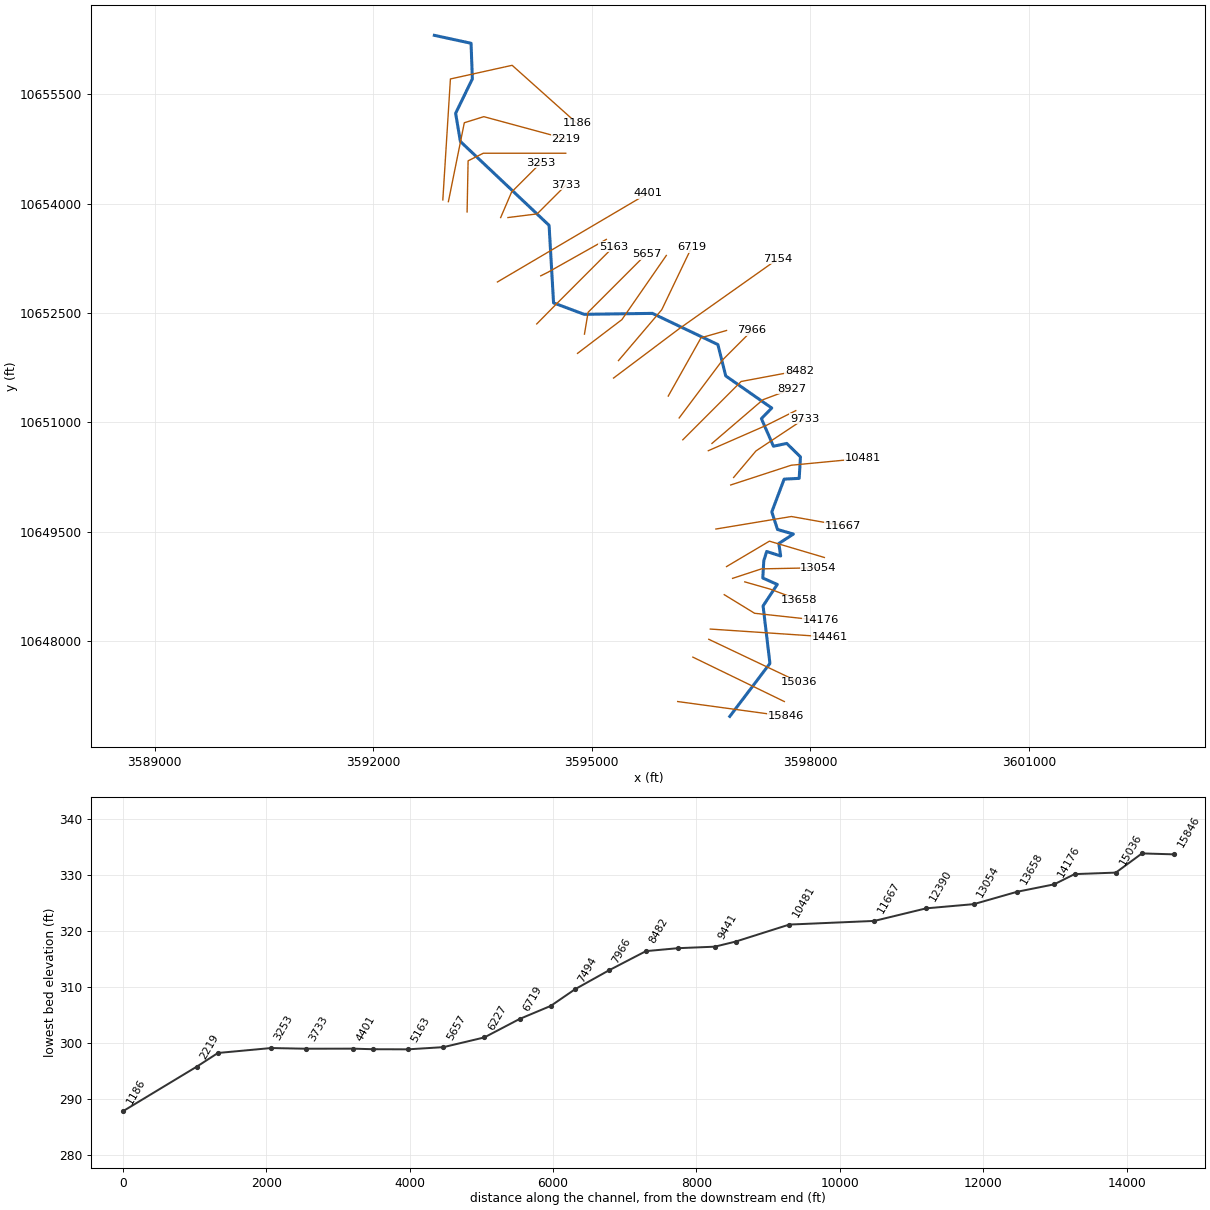
--- COX CREEK.prj (project) ---

Proj Title=COX CREEK Base Level Engineering
Current Plan=p01
Default Exp/Contr=0.3,0.1
English Units
Geom File=g01
Flow File=f01
Plan File=p01
BEGIN DESCRIPTION:
COX CREEK
END DESCRIPTION:

--- COX CREEK.p01 (plan) ---

Plan Title=Multiple Run
Short Identifier=Multiple
Geom File=g01
Flow File=f01
Subcritical Flow
K Sum by GR= 0
Std Step Tol= 0.01
Critical Tol= 0.01
Num of Std Step Trials= 20
Max Error Tol= 0.3
Flow Tol Ratio= 0.001
Split Flow NTrial= 30
Split Flow Tol= 0.02
Split Flow Ratio= 0.02
Log Output Level= 0
Friction Slope Method= 1
Unsteady Friction Slope Method= 2
Unsteady Bridges Friction Slope Method= 1
Parabolic Critical Depth
Global Vel Dist=  1 , 1 , 1
Global Log Level= 0
CheckData=True
Encroach Param= -1, 0, 0, 0
BEGIN DESCRIPTION:
Multiple Run
END DESCRIPTION:

--- COX CREEK.f01 (steady flow) ---

Flow Title=Multiple
Number of Profiles=7
Profile Names=10-year,25-year,50-year,1pct_min,100-year,1pct_plu,500-year
River Rch & RM= COX CREEK,Reach-1,15846
    2305    3251    4051    3678    4974    6726    7475
River Rch & RM= COX CREEK,Reach-1,12390
    2942    4195    5267    4813    6508    8802    9913
River Rch & RM= COX CREEK,Reach-1,5657
    3091    4401    5518    5034    6807    9206   10333
River Rch & RM= COX CREEK,Reach-1,1186
    3686    5286    6660    6101    8251   11159   12632
Boundary for River Rch & Prof#=COX CREEK,Reach-1,1
Up Type=0
Dn Type=3
Dn Slope=0.005
Boundary for River Rch & Prof#=COX CREEK,Reach-1,2
Up Type=0
Dn Type=3
Dn Slope=0.005
Boundary for River Rch & Prof#=COX CREEK,Reach-1,3
Up Type=0
Dn Type=3
Dn Slope=0.005
Boundary for River Rch & Prof#=COX CREEK,Reach-1,4
Up Type=0
Dn Type=3
Dn Slope=0.005
Boundary for River Rch & Prof#=COX CREEK,Reach-1,5
Up Type=0
Dn Type=3
Dn Slope=0.005
Boundary for River Rch & Prof#=COX CREEK,Reach-1,6
Up Type=0
Dn Type=3
Dn Slope=0.005
Boundary for River Rch & Prof#=COX CREEK,Reach-1,7
Up Type=0
Dn Type=3
Dn Slope=0.005

--- COX CREEK.g01 (geometry) ---

Geom Title=Existing Conditions

River Reach=COX CREEK,Reach-1
Reach XY= 30
      3596894.25     10646964.00      3597445.00     10647691.00
      3597351.00     10648480.00      3597545.75     10648775.00
      3597347.00     10648863.00      3597360.75     10649100.00
      3597400.75     10649227.00      3597592.50     10649165.00
      3597567.00     10649337.00      3597767.25     10649466.00
      3597549.25     10649529.00      3597470.75     10649770.00
      3597640.16     10650220.25      3597846.75     10650230.67
      3597864.04     10650525.51      3597676.11     10650710.19
      3597493.16     10650671.57      3597327.95     10651050.39
      3597469.66     10651196.23      3596838.74     10651636.39
      3596730.62     10652066.98      3595832.25     10652495.00
      3594895.25     10652482.00      3594475.50     10652639.00
      3594414.25     10653703.00      3593196.58     10654854.45
      3593131.48     10655240.74      3593361.12     10655713.19
      3593343.25     10656202.00      3592839.50     10656311.00

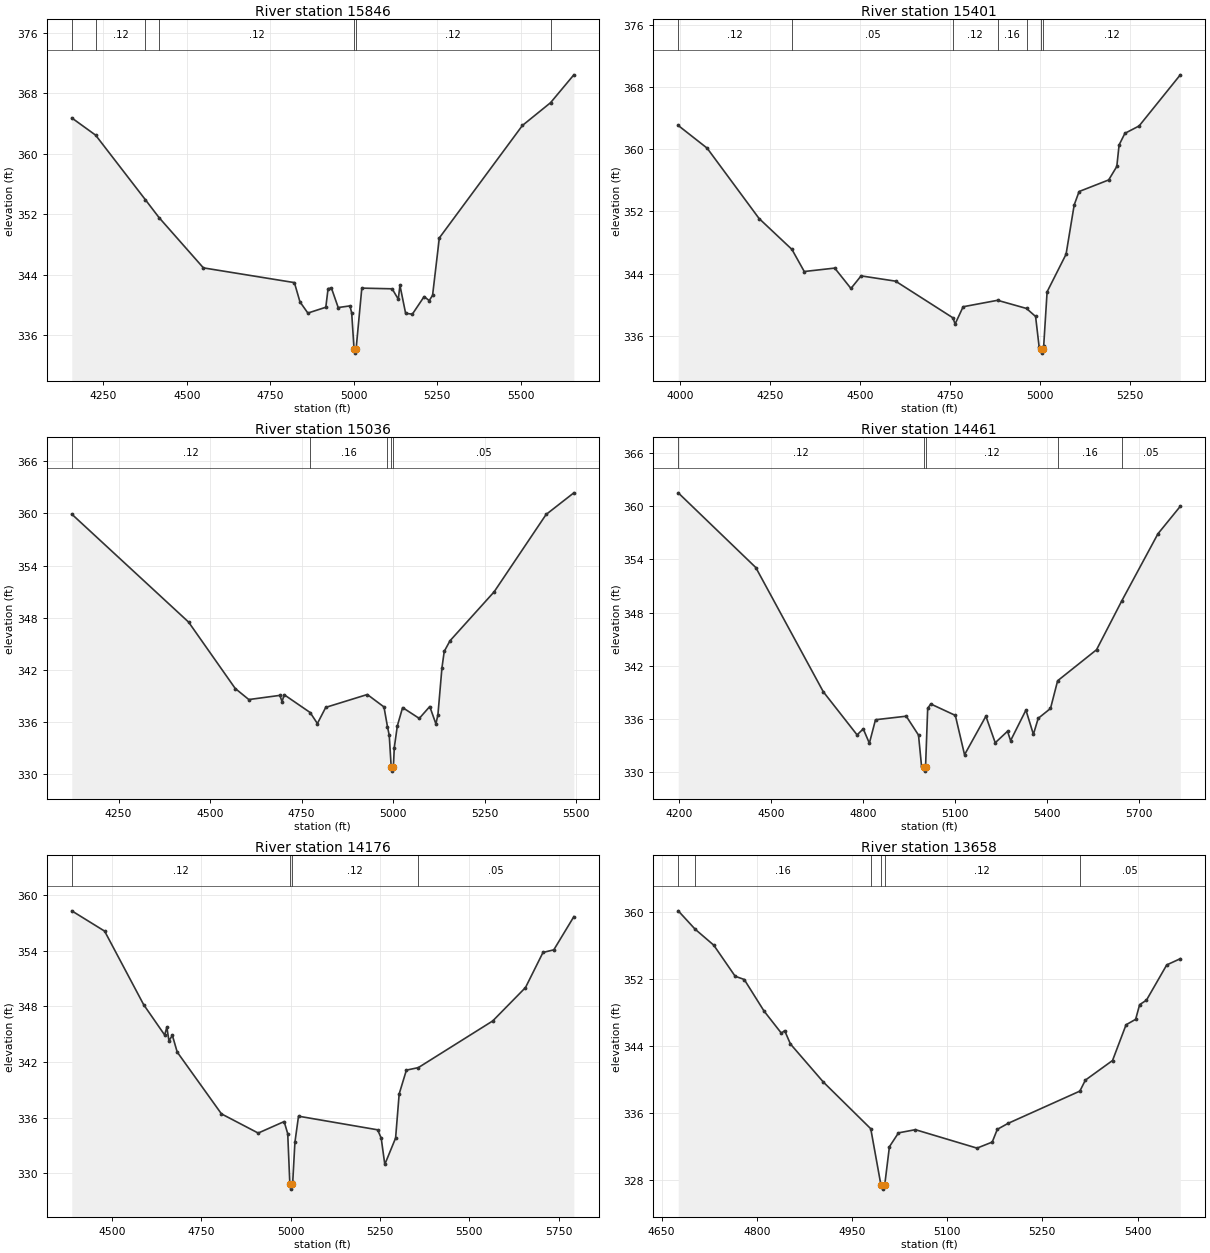
Type RM Length L Ch R = 1,15846,445,445,445
BEGIN DESCRIPTION:
COX CREEK 26.0
END DESCRIPTION:
XS GIS Cut Line= 2
      3596179.10     10647167.72      3597668.72     10646964.59
#Sta/Elev= 30
  4155.3  364.74  4226.7  362.46  4376.0  353.90  4416.5  351.56  4549.4  344.90
  4821.9  342.95  4838.6  340.40  4862.3  338.92  4916.0  339.69  4922.8  342.16
  4932.9  342.22  4953.1  339.65  4988.3  339.87  4993.5  338.93  5000.6  334.12
  5003.3  333.62  5006.6  334.12  5023.8  342.22  5114.6  342.13  5133.0  340.76
  5138.0  342.58  5155.0  338.88  5175.2  338.78  5210.4  341.10  5225.6  340.57
  5235.7  341.27  5255.9  348.86  5504.7  363.74  5588.9  366.75  5658.7  370.44
#Mann=7,-1,0
  4155.3    0.16       0  4226.7    0.12       0  4376.0    0.16       0
  4416.5    0.12       0  5000.6    0.07       0  5006.6    0.12       0
  5588.9    0.05       0
Bank Sta=5000.6,5006.6
Exp/Cntr=0.3,0.1

Type RM Length L Ch R = 1,15401,365,365,365
BEGIN DESCRIPTION:
Mapping XS 636d9e67
END DESCRIPTION:
XS GIS Cut Line= 2
      3596387.43     10647777.10      3597642.63     10647167.72
#Sta/Elev= 30
  3993.9  363.05  4074.1  360.14  4218.6  351.09  4309.9  347.12  4344.1  344.28
  4428.8  344.72  4473.9  342.10  4502.1  343.72  4597.9  343.04  4757.2  338.33
  4763.3  337.53  4785.6  339.75  4881.4  340.58  4961.8  339.53  4987.0  338.50
  4996.8  334.62  5001.0  334.29  5003.8  333.79  5007.0  334.29  5009.6  334.77
  5019.0  341.67  5071.7  346.50  5094.3  352.84  5107.9  354.56  5190.1  356.05
  5212.7  357.78  5219.1  360.55  5235.2  362.04  5274.7  362.99  5389.2  369.56
#Mann=7,-1,0
  3993.9    0.12       0  4309.9    0.05       0  4757.2    0.12       0
  4881.4    0.16       0  4961.8    0.12       0  5001.0    0.07       0
  5007.0    0.12       0
Bank Sta=5001,5007
Exp/Cntr=0.3,0.1

Type RM Length L Ch R = 1,15036,575,575,575
BEGIN DESCRIPTION:
COX CREEK 25.0
END DESCRIPTION:
XS GIS Cut Line= 2
      3596606.13     10648021.91      3597845.17     10647433.63
#Sta/Elev= 30
  4122.1  359.92  4441.2  347.51  4568.7  339.87  4605.8  338.60  4690.5  339.08
  4696.7  338.35  4702.2  339.16  4773.3  337.11  4793.1  335.84  4815.9  337.70
  4929.5  339.18  4975.0  337.75  4984.5  335.49  4989.4  334.48  4994.7  330.87
  4997.4  330.37  5000.7  330.87  5003.2  333.08  5011.5  335.57  5025.9  337.68
  5071.4  336.43  5100.1  337.80  5116.9  335.80  5122.4  336.86  5133.3  342.22
  5139.6  344.14  5155.4  345.36  5276.0  350.99  5417.9  359.88  5493.7  362.37
#Mann=5,-1,0
  4122.1    0.12       0  4773.3    0.16       0  4984.5    0.05       0
  4994.7    0.03       0  5000.7    0.05       0
Bank Sta=4994.7,5000.7
Exp/Cntr=0.3,0.1

Type RM Length L Ch R = 1,14461,285,285,285
BEGIN DESCRIPTION:
COX CREEK 24.0
END DESCRIPTION:
XS GIS Cut Line= 2
      3596627.00     10648162.52      3598262.45     10648053.14
#Sta/Elev= 30
  4196.4  361.51  4449.6  353.08  4670.1  339.05  4780.3  334.19  4800.4  334.87
  4820.4  333.25  4840.4  335.90  4940.7  336.30  4980.8  334.17  4990.8  330.64
  4997.8  330.60  5000.5  330.10  5003.8  330.60  5010.8  337.19  5020.8  337.68
  5101.0  336.39  5131.1  331.95  5200.8  336.30  5231.3  333.30  5271.4  334.60
  5281.4  333.54  5331.5  336.99  5355.9  334.25  5371.6  336.06  5411.7  337.17
  5435.0  340.30  5562.0  343.80  5644.0  349.29  5762.5  356.89  5835.5  359.99
#Mann=5,-1,0
  4196.4    0.12       0  4997.8    0.07       0  5003.8    0.12       0
  5435.0    0.16       0  5644.0    0.05       0
Bank Sta=4997.8,5003.8
Exp/Cntr=0.3,0.1

Type RM Length L Ch R = 1,14176,518,518,518
BEGIN DESCRIPTION:
COX CREEK 23.0
END DESCRIPTION:
XS GIS Cut Line= 3
      3596818.02     10648634.27      3597234.69     10648379.05
      3598145.42     10648280.17
#Sta/Elev= 30
  4387.6  358.31  4479.5  356.12  4588.8  348.18  4647.5  344.91  4653.6  345.75
  4659.5  344.28  4669.0  344.88  4682.6  343.07  4806.4  336.40  4909.2  334.33
  4981.8  335.57  4991.8  334.26  4997.8  328.78  5000.5  328.28  5003.8  328.78
  5005.8  329.03  5011.9  333.33  5022.0  336.15  5243.3  334.68  5253.3  333.79
  5263.4  330.95  5293.6  333.79  5303.6  338.55  5323.8  341.12  5357.1  341.39
  5565.4  346.43  5657.0  350.03  5706.0  353.82  5736.2  354.10  5792.3  357.68
#Mann=4,-1,0
  4387.6    0.12       0  4997.8    0.07       0  5003.8    0.12       0
  5357.1    0.05       0
Bank Sta=4997.8,5003.8
Exp/Cntr=0.3,0.1

Type RM Length L Ch R = 1,13658,604,604,604
BEGIN DESCRIPTION:
COX CREEK 22.0
END DESCRIPTION:
XS GIS Cut Line= 3
      3597099.65     10648810.18      3597449.61     10648710.19
      3597849.65     10648560.17
#Sta/Elev= 30
  4676.2  360.14  4702.8  357.95  4732.1  356.05  4765.9  352.34  4780.2  351.95
  4811.4  348.19  4838.7  345.55  4843.9  345.85  4853.0  344.26  4905.0  339.71
  4979.6  334.15  4995.6  327.45  4998.3  326.95  5001.6  327.45  5009.0  332.01
  5023.3  333.66  5049.9  334.04  5147.0  331.84  5171.0  332.56  5179.0  334.08
  5195.9  334.79  5309.1  338.64  5317.8  339.95  5360.6  342.29  5381.9  346.55
  5397.0  347.20  5403.3  348.95  5414.0  349.48  5446.0  353.69  5467.4  354.43
#Mann=6,-1,0
  4676.2    0.12       0  4702.8    0.16       0  4979.6    0.12       0
  4995.6    0.07       0  5001.6    0.12       0  5309.1    0.05       0
Bank Sta=4995.6,5001.6
Exp/Cntr=0.3,0.1

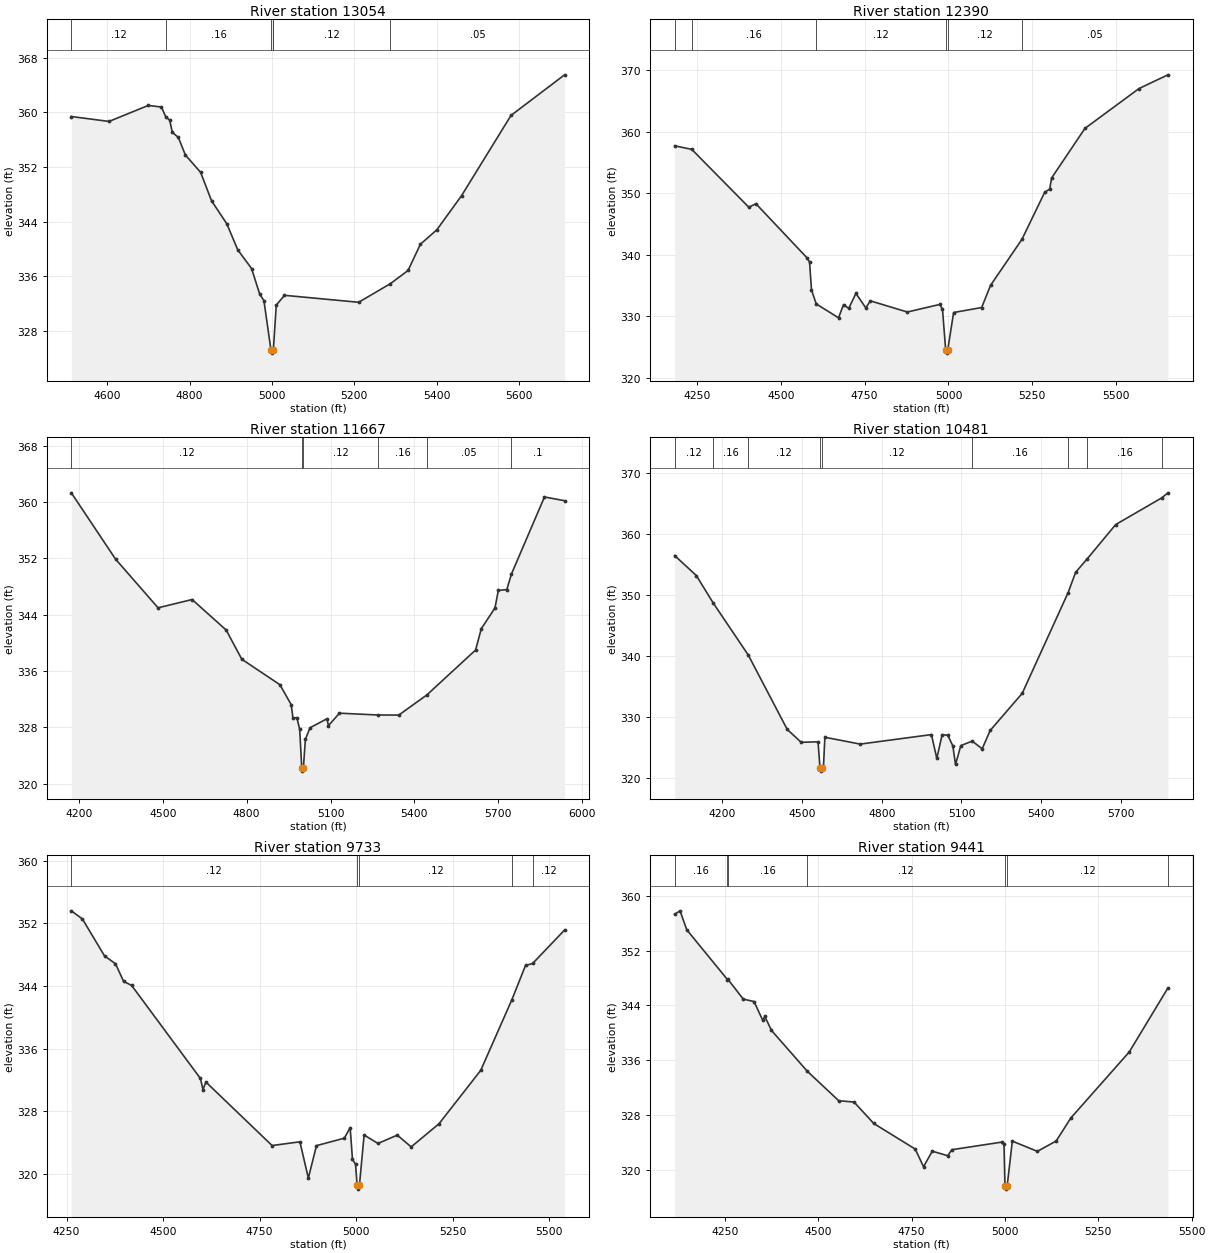
Type RM Length L Ch R = 1,13054,664,664,664
BEGIN DESCRIPTION:
COX CREEK 21.0
END DESCRIPTION:
XS GIS Cut Line= 3
      3596932.65     10648858.24      3597328.44     10648988.43
      3598109.73     10649004.05
#Sta/Elev= 30
  4512.9  359.37  4604.4  358.65  4699.8  360.99  4731.6  360.76  4742.7  359.28
  4751.8  358.86  4758.1  357.07  4772.9  356.31  4789.9  353.74  4827.0  351.20
  4853.5  347.04  4890.6  343.67  4917.1  339.87  4950.7  337.13  4970.7  333.34
  4980.7  332.45  4997.7  325.25  5000.5  324.75  5003.7  325.25  5003.9  325.44
  5010.7  331.77  5030.7  333.21  5210.8  332.19  5287.8  334.91  5330.8  336.84
  5360.8  340.68  5400.8  342.80  5460.8  347.79  5580.9  359.53  5711.0  365.47
#Mann=6,-1,0
  4512.9    0.12       0  4742.7    0.16       0  4997.7    0.07       0
  5003.7    0.16       0  5003.9    0.12       0  5287.8    0.05       0
Bank Sta=4997.7,5003.7
Exp/Cntr=0.3,0.1

Type RM Length L Ch R = 1,12390,723,723,723
BEGIN DESCRIPTION:
COX CREEK 20.0
END DESCRIPTION:
XS GIS Cut Line= 3
      3596849.23     10649019.66      3597437.81     10649368.64
      3598192.18     10649144.93
#Sta/Elev= 30
  4183.3  357.74  4234.3  357.16  4404.3  347.75  4425.7  348.31  4579.0  339.45
  4585.6  338.82  4591.4  334.28  4605.5  332.01  4672.0  329.75  4686.9  331.89
  4702.5  331.28  4723.9  333.72  4753.4  331.36  4766.8  332.51  4877.2  330.69
  4973.7  331.92  4982.1  331.16  4991.6  324.50  4994.3  324.00  4997.6  324.50
  5015.3  330.61  5098.9  331.42  5125.4  335.03  5219.1  342.52  5286.7  350.15
  5302.0  350.71  5307.5  352.50  5406.9  360.57  5568.3  367.06  5654.4  369.29
#Mann=6,-1,0
  4183.3     0.1       0  4234.3    0.16       0  4605.5    0.12       0
  4991.6    0.07       0  4997.6    0.12       0  5219.1    0.05       0
Bank Sta=4991.6,4997.6
Exp/Cntr=0.3,0.1

Type RM Length L Ch R = 1,11667,1186,1186,1186
BEGIN DESCRIPTION:
COX CREEK 19.0
END DESCRIPTION:
XS GIS Cut Line= 3
      3596703.47     10649535.31      3597739.90     10649707.18
      3598443.00     10649582.18
#Sta/Elev= 30
  4172.7  361.33  4331.0  351.90  4483.0  344.98  4604.8  346.16  4726.7  341.82
  4782.6  337.67  4918.9  334.05  4959.4  331.21  4965.6  329.31  4979.7  329.36
  4989.8  327.69  4997.0  322.26  4999.7  321.76  5003.0  322.26  5010.1  326.27
  5026.5  327.92  5087.5  329.21  5092.6  328.22  5131.8  330.00  5270.8  329.74
  5344.3  329.73  5444.0  332.57  5619.1  338.98  5639.5  342.01  5688.4  344.96
  5700.4  347.46  5730.8  347.57  5747.4  349.79  5865.5  360.74  5937.4  360.21
#Mann=6,-1,0
  4172.7    0.12       0  4997.0    0.07       0  5003.0    0.12       0
  5270.8    0.16       0  5444.0    0.05       0  5747.4     0.1       0
Bank Sta=4997,5003
Exp/Cntr=0.3,0.1

Type RM Length L Ch R = 1,10481,748,748,748
BEGIN DESCRIPTION:
COX CREEK 18.0
END DESCRIPTION:
XS GIS Cut Line= 3
      3596906.87     10650139.95      3597736.69     10650410.78
      3598715.22     10650504.46
#Sta/Elev= 30
  4020.8  356.51  4102.4  353.22  4165.7  348.73  4297.8  340.17  4444.4  327.95
  4497.0  325.84  4560.2  325.93  4567.7  321.61  4570.4  321.11  4573.7  321.61
  4580.8  321.94  4586.0  326.67  4718.9  325.55  4987.0  327.11  5007.1  323.20
  5027.2  327.09  5048.6  327.00  5067.4  325.26  5077.5  322.20  5097.5  325.30
  5140.3  326.04  5177.9  324.78  5208.0  327.79  5328.6  333.89  5501.1  350.41
  5529.5  353.76  5573.5  355.99  5680.2  361.60  5854.5  366.01  5876.7  366.81
#Mann=9,-1,0
  4020.8    0.12       0  4165.7    0.16       0  4297.8    0.12       0
  4567.7    0.07       0  4573.7    0.12       0  5140.3    0.16       0
  5501.1    0.05       0  5573.5    0.16       0  5854.5    0.05       0
Bank Sta=4567.7,4573.7
Exp/Cntr=0.3,0.1

Type RM Length L Ch R = 1,9733,292,292,292
BEGIN DESCRIPTION:
COX CREEK 17.0
END DESCRIPTION:
XS GIS Cut Line= 3
      3596946.52     10650242.80      3597253.79     10650607.35
      3597920.42     10651050.04
#Sta/Elev= 30
  4262.4  353.59  4291.1  352.55  4348.3  347.84  4376.7  346.84  4397.7  344.59
  4418.5  344.07  4596.6  332.20  4603.2  330.79  4610.9  331.74  4782.2  323.64
  4854.2  324.12  4876.0  319.49  4897.1  323.63  4969.2  324.58  4984.3  325.92
  4990.3  321.88  4998.2  321.26  5002.3  318.58  5005.1  318.08  5008.3  318.58
  5020.4  324.98  5056.4  323.91  5106.3  324.97  5142.3  323.47  5214.3  326.42
  5322.4  333.24  5403.1  342.26  5438.3  346.62  5456.7  346.87  5539.4  351.14
#Mann=5,-1,0
  4262.4    0.12       0  5002.3    0.07       0  5008.3    0.12       0
  5403.1    0.16       0  5456.7    0.12       0
Bank Sta=5002.3,5008.3
Exp/Cntr=0.3,0.1

Type RM Length L Ch R = 1,9441,514,514,514
BEGIN DESCRIPTION:
COX CREEK 16.0
END DESCRIPTION:
XS GIS Cut Line= 3
      3596599.64     10650610.20      3597399.61     10650960.19
      3597799.61     10651160.19
#Sta/Elev= 30
  4116.0  357.31  4130.4  357.82  4148.3  355.06  4257.3  347.78  4258.9  347.79
  4299.6  344.93  4328.4  344.57  4351.8  341.83  4357.3  342.40  4375.2  340.35
  4471.2  334.38  4555.3  330.08  4596.2  329.89  4648.9  326.76  4760.0  323.02
  4782.2  320.44  4805.6  322.71  4846.9  322.05  4858.2  322.93  4992.0  324.04
  4997.6  323.70  5000.2  317.67  5002.9  317.17  5006.2  317.67  5019.9  324.18
  5087.0  322.69  5137.3  324.20  5176.5  327.56  5333.0  337.21  5436.4  346.55
#Mann=7,-1,0
  4116.0    0.16       0  4257.3    0.12       0  4258.9    0.16       0
  4471.2    0.12       0  5000.2    0.07       0  5006.2    0.12       0
  5436.4    0.16       0
Bank Sta=5000.2,5006.2
Exp/Cntr=0.3,0.1

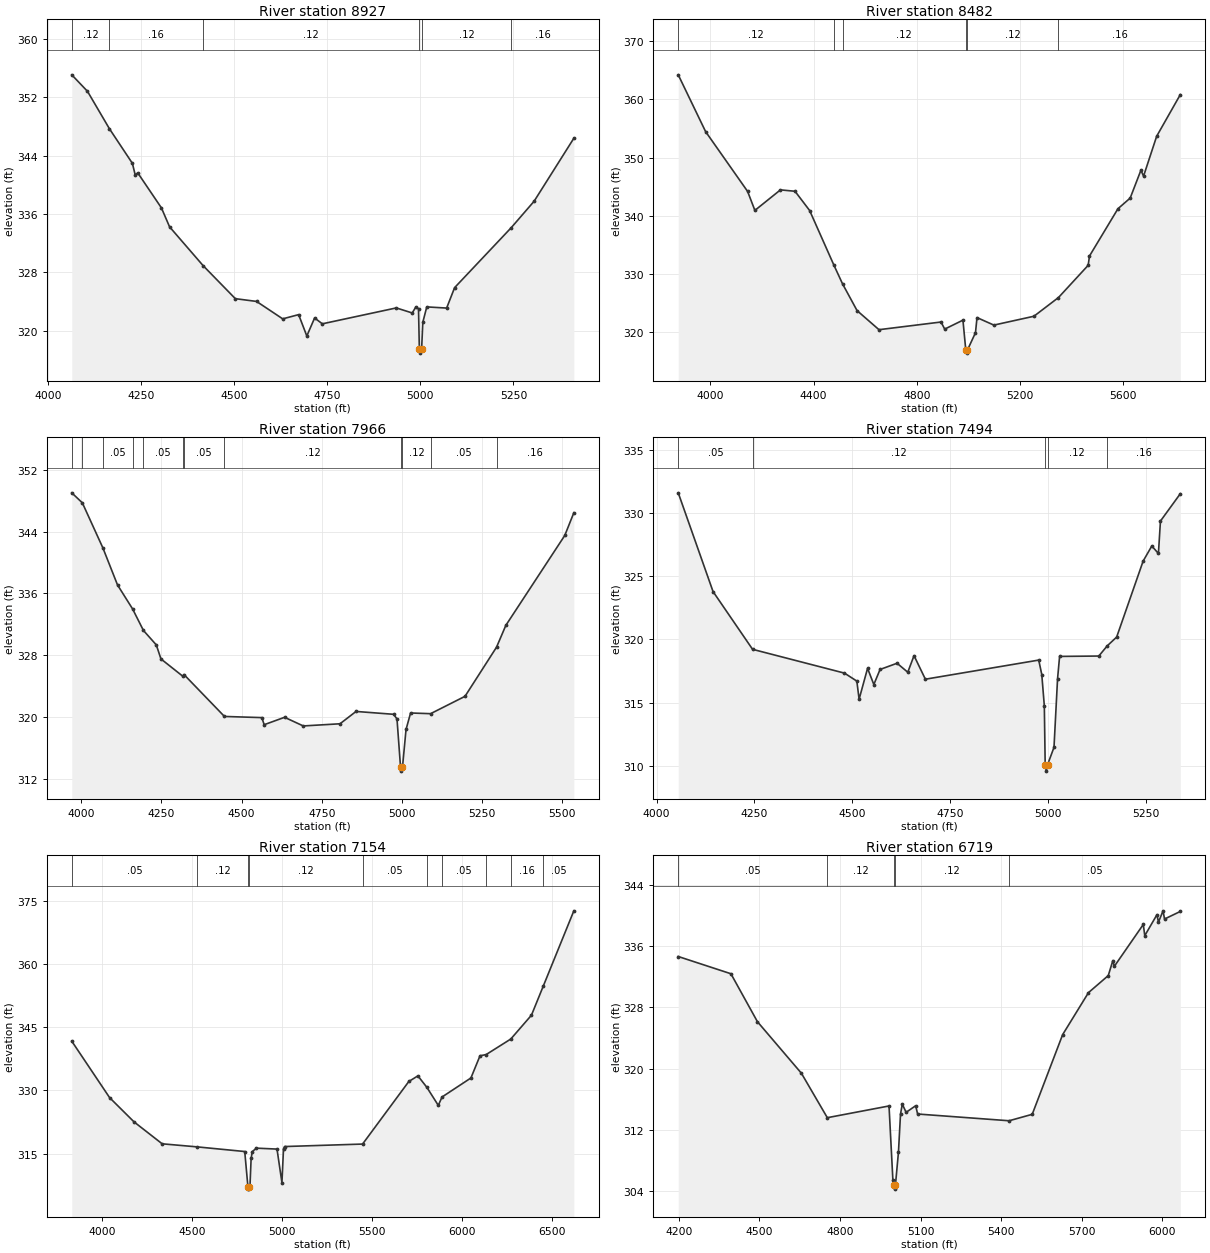
Type RM Length L Ch R = 1,8927,445,445,445
BEGIN DESCRIPTION:
COX CREEK 15.0
END DESCRIPTION:
XS GIS Cut Line= 3
      3596649.65     10650710.22      3597349.61     10651310.19
      3597749.60     10651460.19
#Sta/Elev= 30
  4063.2  355.07  4105.4  352.81  4164.2  347.69  4226.1  342.93  4233.8  341.31
  4240.4  341.63  4304.1  336.82  4326.0  334.22  4416.3  328.89  4502.7  324.37
  4559.8  323.99  4630.0  321.60  4672.8  322.18  4694.8  319.25  4715.7  321.72
  4736.5  320.92  4935.2  323.10  4978.0  322.41  4987.8  323.23  4994.9  323.00
  4997.2  317.40  5000.0  316.90  5003.2  317.40  5006.5  321.14  5017.1  323.24
  5070.5  323.08  5091.9  325.88  5244.3  334.12  5305.5  337.73  5412.3  346.37
#Mann=6,-1,0
  4063.2    0.12       0  4164.2    0.16       0  4416.3    0.12       0
  4997.2    0.07       0  5003.2    0.12       0  5244.3    0.16       0
Bank Sta=4997.2,5003.2
Exp/Cntr=0.3,0.1

Type RM Length L Ch R = 1,8482,516,516,516
BEGIN DESCRIPTION:
COX CREEK 14.0
END DESCRIPTION:
XS GIS Cut Line= 3
      3596249.62     10650760.20      3597049.61     10651560.19
      3597849.62     10651710.19
#Sta/Elev= 30
  3875.6  364.23  3981.6  354.47  4144.3  344.19  4172.6  340.92  4271.6  344.45
  4328.1  344.21  4384.7  340.90  4478.0  331.58  4512.1  328.30  4568.5  323.69
  4653.4  320.41  4893.8  321.73  4908.0  320.51  4978.7  322.05  4989.8  316.88
  4992.6  316.38  4995.8  316.88  5027.3  319.89  5033.2  322.49  5098.5  321.20
  5253.7  322.72  5348.9  325.94  5463.9  331.48  5469.0  333.08  5579.3  341.21
  5626.7  343.04  5668.3  347.83  5678.5  346.81  5729.3  353.67  5820.9  360.83
#Mann=6,-1,0
  3875.6    0.12       0  4478.0    0.16       0  4512.1    0.12       0
  4989.8    0.07       0  4995.8    0.12       0  5348.9    0.16       0
Bank Sta=4989.8,4995.8
Exp/Cntr=0.3,0.1

Type RM Length L Ch R = 1,7966,472,472,472
BEGIN DESCRIPTION:
COX CREEK 13.0
END DESCRIPTION:
XS GIS Cut Line= 3
      3596199.60     10651060.18      3596799.61     10651860.19
      3597199.61     10652260.19
#Sta/Elev= 30
  3970.2  349.05  4003.2  347.75  4067.4  341.89  4112.9  337.10  4159.9  333.99
  4193.7  331.20  4233.8  329.33  4248.3  327.51  4316.6  325.26  4320.0  325.49
  4446.3  320.05  4562.9  319.90  4570.2  318.98  4633.8  319.94  4692.1  318.82
  4806.7  319.10  4856.7  320.70  4973.7  320.33  4984.4  319.73  4995.5  313.46
  4998.2  312.96  5001.5  313.46  5012.6  318.36  5026.8  320.50  5089.2  320.41
  5196.5  322.66  5294.9  329.04  5323.8  331.86  5507.6  343.52  5535.9  346.47
#Mann=12,-1,0
  3970.2    0.05       0  4003.2    0.12       0  4067.4    0.05       0
  4159.9    0.16       0  4193.7    0.05       0  4316.6    0.16       0
  4320.0    0.05       0  4446.3    0.12       0  4995.5    0.07       0
  5001.5    0.12       0  5089.2    0.05       0  5294.9    0.16       0
Bank Sta=4995.5,5001.5
Exp/Cntr=0.3,0.1

Type RM Length L Ch R = 1,7494,340,340,340
BEGIN DESCRIPTION:
COX CREEK 12.0
END DESCRIPTION:
XS GIS Cut Line= 3
      3596049.62     10651360.22      3596499.61     10652160.19
      3596849.65     10652260.20
#Sta/Elev= 30
  4055.3  331.58  4144.2  323.78  4245.1  319.22  4479.8  317.34  4511.3  316.71
  4517.1  315.28  4538.7  317.72  4554.7  316.44  4570.6  317.63  4614.0  318.12
  4641.4  317.41  4657.3  318.72  4686.3  316.86  4975.7  318.37  4983.5  317.23
  4990.0  314.75  4992.2  310.10  4995.0  309.60  4998.2  310.10  5014.7  311.48
  5023.8  316.90  5029.0  318.66  5129.1  318.69  5150.5  319.49  5174.7  320.19
  5242.3  326.19  5264.4  327.38  5281.3  326.79  5286.5  329.35  5337.2  331.51
#Mann=5,-1,0
  4055.3    0.05       0  4245.1    0.12       0  4992.2    0.07       0
  4998.2    0.12       0  5150.5    0.16       0
Bank Sta=4992.2,4998.2
Exp/Cntr=0.3,0.1

Type RM Length L Ch R = 1,7154,435,435,435
BEGIN DESCRIPTION:
COX CREEK 11.0
END DESCRIPTION:
XS GIS Cut Line= 3
      3595298.95     10651607.37      3596199.97     10652284.44
      3597554.12     10653242.76
#Sta/Elev= 30
  3833.3  341.68  4043.3  328.30  4178.7  322.56  4334.9  317.36  4529.3  316.63
  4793.1  315.53  4810.9  307.12  4813.7  306.62  4816.9  307.12  4822.2  307.38
  4828.5  313.88  4834.8  315.50  4857.7  316.33  4972.2  316.11  4999.5  308.16
  5008.2  316.16  5014.3  316.71  5447.0  317.30  5703.6  332.13  5754.0  333.46
  5803.9  330.73  5867.2  326.46  5887.8  328.45  6048.2  332.96  6098.6  338.22
  6132.8  338.51  6269.4  342.19  6384.1  347.84  6449.1  354.67  6619.3  372.57
#Mann=10,-1,0
  3833.3    0.05       0  4529.3    0.12       0  4810.9    0.07       0
  4816.9    0.12       0  5447.0    0.05       0  5803.9    0.12       0
  5887.8    0.05       0  6132.8    0.12       0  6269.4    0.16       0
  6449.1    0.05       0
Bank Sta=4810.9,4816.9
Exp/Cntr=0.3,0.1

Type RM Length L Ch R = 1,6719,492,492,492
BEGIN DESCRIPTION:
COX CREEK 10.0
END DESCRIPTION:
XS GIS Cut Line= 3
      3595366.64     10651846.94      3595960.38     10652544.85
      3596371.84     10653404.22
#Sta/Elev= 30
  4198.1  334.64  4394.2  332.39  4493.0  326.13  4656.6  319.41  4753.1  313.61
  4982.8  315.14  4997.1  305.53  5000.6  304.79  5003.4  304.29  5006.6  304.79
  5017.9  309.10  5025.6  314.09  5032.2  315.37  5046.5  314.31  5082.0  315.17
  5089.3  314.09  5429.8  313.21  5515.9  314.05  5629.2  324.45  5725.4  329.93
  5799.0  332.15  5816.1  334.11  5821.6  333.36  5929.4  338.82  5934.9  337.36
  5980.3  340.10  5985.8  339.12  6002.9  340.60  6008.5  339.53  6067.2  340.52
#Mann=5,-1,0
  4198.1    0.05       0  4753.1    0.12       0  5000.6    0.07       0
  5006.6    0.12       0  5429.8    0.05       0
Bank Sta=5000.6,5006.6
Exp/Cntr=0.3,0.1

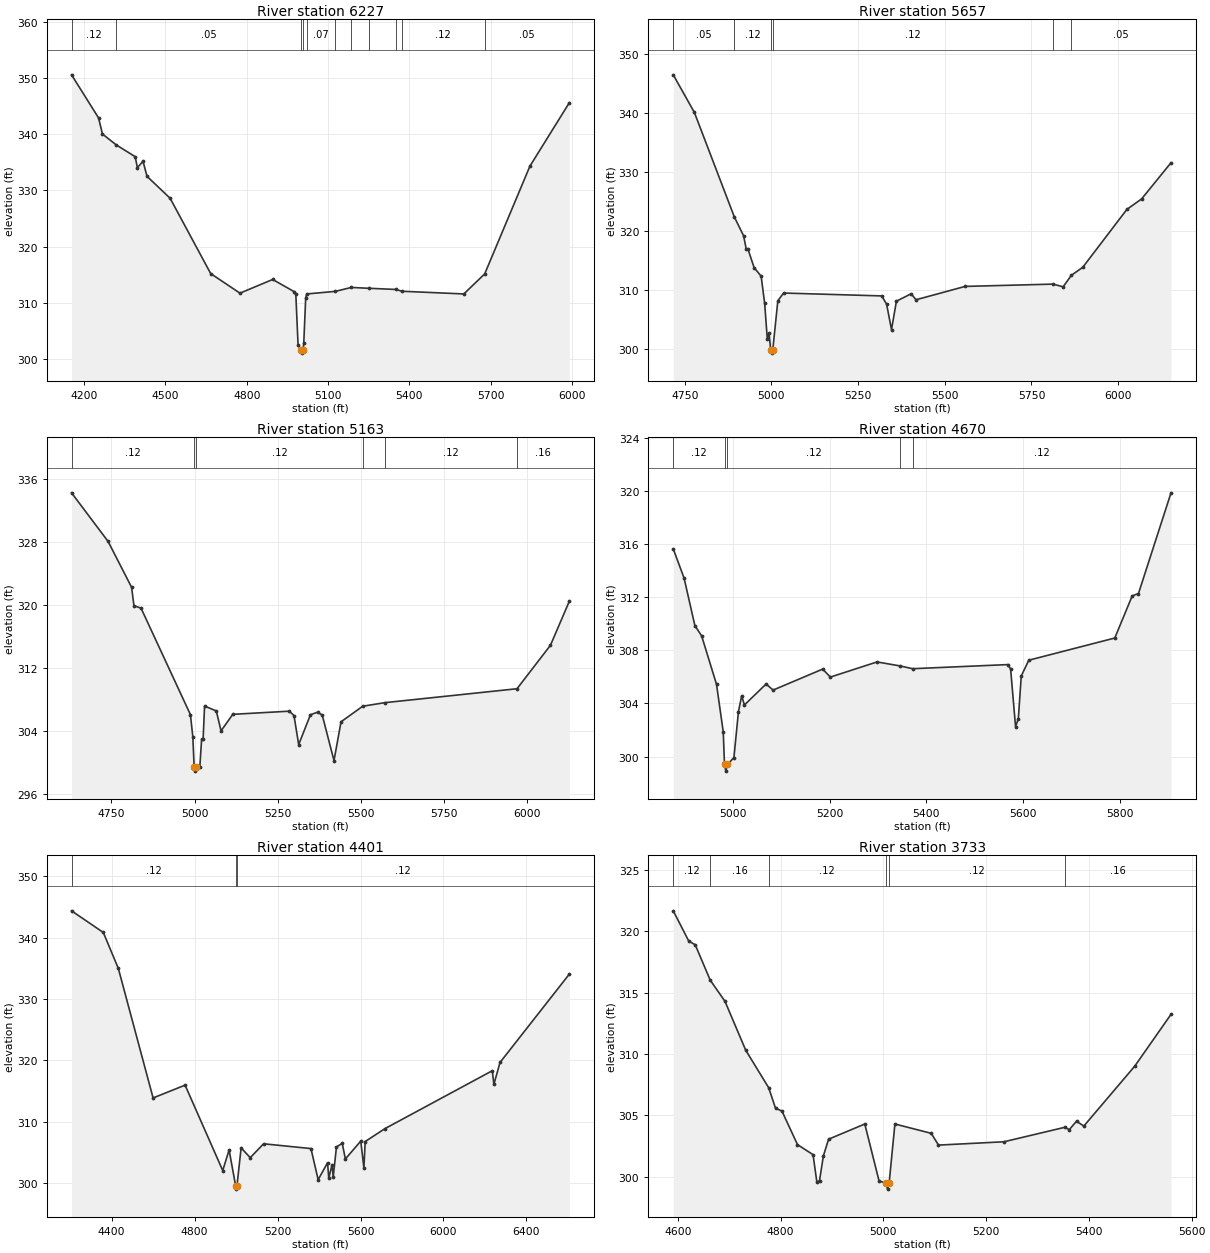
Type RM Length L Ch R = 1,6227,570,570,570
BEGIN DESCRIPTION:
COX CREEK 9.0
END DESCRIPTION:
XS GIS Cut Line= 3
      3594804.16     10651945.92      3595413.51     10652409.44
      3596022.90     10653289.67
#Sta/Elev= 30
  4153.6  350.61  4253.1  342.94  4267.6  340.06  4318.1  338.13  4388.3  336.02
  4396.5  334.06  4417.3  335.20  4431.9  332.52  4517.2  328.61  4666.9  315.18
  4774.9  311.69  4895.6  314.13  4974.4  311.97  4980.9  311.52  4989.2  302.48
  5001.1  301.50  5003.8  301.00  5007.1  301.50  5010.2  302.74  5017.4  310.87
  5021.3  311.55  5127.1  312.01  5185.8  312.71  5249.7  312.56  5350.3  312.35
  5372.3  312.03  5600.7  311.55  5677.8  315.13  5844.5  334.33  5989.8  345.63
#Mann=11,-1,0
  4153.6    0.12       0  4318.1    0.05       0  5001.1    0.03       0
  5007.1    0.05       0  5021.3    0.07       0  5127.1    0.12       0
  5185.8    0.07       0  5249.7    0.12       0  5350.3    0.07       0
  5372.3    0.12       0  5677.8    0.05       0
Bank Sta=5001.1,5007.1
Exp/Cntr=0.3,0.1

Type RM Length L Ch R = 1,5657,494,494,494
BEGIN DESCRIPTION:
COX CREEK 8.0
END DESCRIPTION:
XS GIS Cut Line= 3
      3594899.60     10652210.16      3594949.61     10652510.19
      3595749.58     10653310.16
#Sta/Elev= 30
  4717.0  346.41  4777.9  340.04  4893.2  322.33  4919.8  319.15  4927.4  316.93
  4932.5  316.88  4950.2  313.75  4970.5  312.30  4980.6  307.70  4988.2  301.67
  4993.3  302.70  4997.9  299.77  5000.6  299.27  5003.9  299.77  5018.6  308.14
  5035.3  309.45  5318.2  308.96  5332.3  307.56  5346.4  303.26  5360.6  308.07
  5403.0  309.32  5417.2  308.31  5558.6  310.57  5812.5  310.96  5841.4  310.50
  5865.3  312.46  5898.0  313.81  6025.3  323.62  6067.7  325.39  6152.5  331.52
#Mann=6,-1,0
  4717.0    0.05       0  4893.2    0.12       0  4997.9    0.07       0
  5003.9    0.12       0  5812.5    0.16       0  5865.3    0.05       0
Bank Sta=4997.9,5003.9
Exp/Cntr=0.3,0.1

Type RM Length L Ch R = 1,5163,493,493,493
BEGIN DESCRIPTION:
COX CREEK 7.0
END DESCRIPTION:
XS GIS Cut Line= 3
      3594244.59     10652350.01      3594522.07     10652631.50
      3595299.62     10653410.20
#Sta/Elev= 30
  4630.5  334.21  4740.3  328.04  4811.0  322.21  4818.0  319.88  4839.3  319.57
  4987.7  306.05  4994.9  303.24  4998.9  299.38  5001.6  298.88  5004.9  299.38
  5016.0  299.45  5021.3  302.91  5025.8  302.91  5030.2  307.14  5065.5  306.52
  5079.7  303.99  5115.0  306.09  5284.7  306.49  5298.9  305.94  5313.0  302.25
  5348.4  306.04  5369.6  306.36  5383.7  306.01  5419.1  300.22  5440.3  305.14
  5505.5  307.12  5571.7  307.57  5969.1  309.34  6069.6  314.86  6126.2  320.44
#Mann=6,-1,0
  4630.5    0.12       0  4998.9    0.07       0  5004.9    0.12       0
  5505.5    0.16       0  5571.7    0.12       0  5969.1    0.16       0
Bank Sta=4998.9,5004.9
Exp/Cntr=0.3,0.1

Type RM Length L Ch R = 1,4670,269,269,269
BEGIN DESCRIPTION:
COX CREEK 6.0
END DESCRIPTION:
XS GIS Cut Line= 3
      3594299.60     10653010.18      3594399.61     10653060.19
      3595199.62     10653510.19
#Sta/Elev= 30
  4876.3  315.63  4898.7  313.43  4921.0  309.86  4935.0  309.08  4965.8  305.43
  4979.7  301.86  4982.3  299.40  4985.1  298.90  4988.3  299.40  5001.8  299.92
  5011.1  303.36  5017.8  304.57  5023.5  303.88  5068.4  305.46  5082.8  305.00
  5185.4  306.58  5201.3  305.98  5297.9  307.12  5345.4  306.82  5371.3  306.61
  5568.5  306.92  5574.2  306.59  5584.4  302.25  5590.2  302.85  5596.2  306.06
  5611.8  307.25  5789.7  308.92  5825.7  312.09  5838.7  312.27  5906.0  319.85
#Mann=5,-1,0
  4876.3    0.12       0  4982.3    0.07       0  4988.3    0.12       0
  5345.4    0.16       0  5371.3    0.12       0
Bank Sta=4982.3,4988.3
Exp/Cntr=0.3,0.1

Type RM Length L Ch R = 1,4401,668,668,668
BEGIN DESCRIPTION:
COX CREEK 5.0
END DESCRIPTION:
XS GIS Cut Line= 2
      3593705.15     10652925.91      3595772.89     10654144.68
#Sta/Elev= 30
  4206.6  344.36  4359.8  340.83  4432.3  334.96  4599.8  313.86  4754.1  315.95
  4935.6  302.03  4966.3  305.38  4998.1  299.50  5000.9  299.00  5004.1  299.50
  5024.3  305.72  5068.3  304.13  5132.7  306.39  5361.0  305.61  5395.8  300.54
  5441.1  303.31  5446.9  300.79  5462.6  302.98  5468.4  300.99  5484.0  305.87
  5511.9  306.46  5527.0  303.92  5601.2  306.83  5616.3  302.46  5622.6  306.76
  5718.3  308.87  6235.5  318.30  6243.1  316.07  6272.6  319.64  6606.8  334.04
#Mann=3,-1,0
  4206.6    0.12       0  4998.1    0.07       0  5004.1    0.12       0
Bank Sta=4998.1,5004.1
Exp/Cntr=0.3,0.1

Type RM Length L Ch R = 1,3733,480,480,480
BEGIN DESCRIPTION:
COX CREEK 4.0
END DESCRIPTION:
XS GIS Cut Line= 3
      3593849.64     10653810.19      3594249.61     10653860.19
      3594649.64     10654260.22
#Sta/Elev= 30
  4591.0  321.68  4621.2  319.21  4633.8  318.91  4662.9  316.03  4691.7  314.30
  4732.1  310.31  4776.7  307.26  4790.0  305.59  4802.6  305.35  4832.8  302.62
  4863.1  301.80  4870.6  299.54  4875.7  299.69  4883.2  301.70  4893.3  303.06
  4963.8  304.30  4991.6  299.65  5005.2  299.49  5008.0  298.99  5011.2  299.49
  5022.4  304.30  5093.1  303.54  5107.2  302.58  5234.5  302.85  5353.0  304.03
  5361.8  303.84  5375.9  304.53  5390.1  304.13  5489.1  309.01  5559.8  313.24
#Mann=6,-1,0
  4591.0    0.12       0  4662.9    0.16       0  4776.7    0.12       0
  5005.2    0.07       0  5011.2    0.12       0  5353.0    0.16       0
Bank Sta=5005.2,5011.2
Exp/Cntr=0.3,0.1

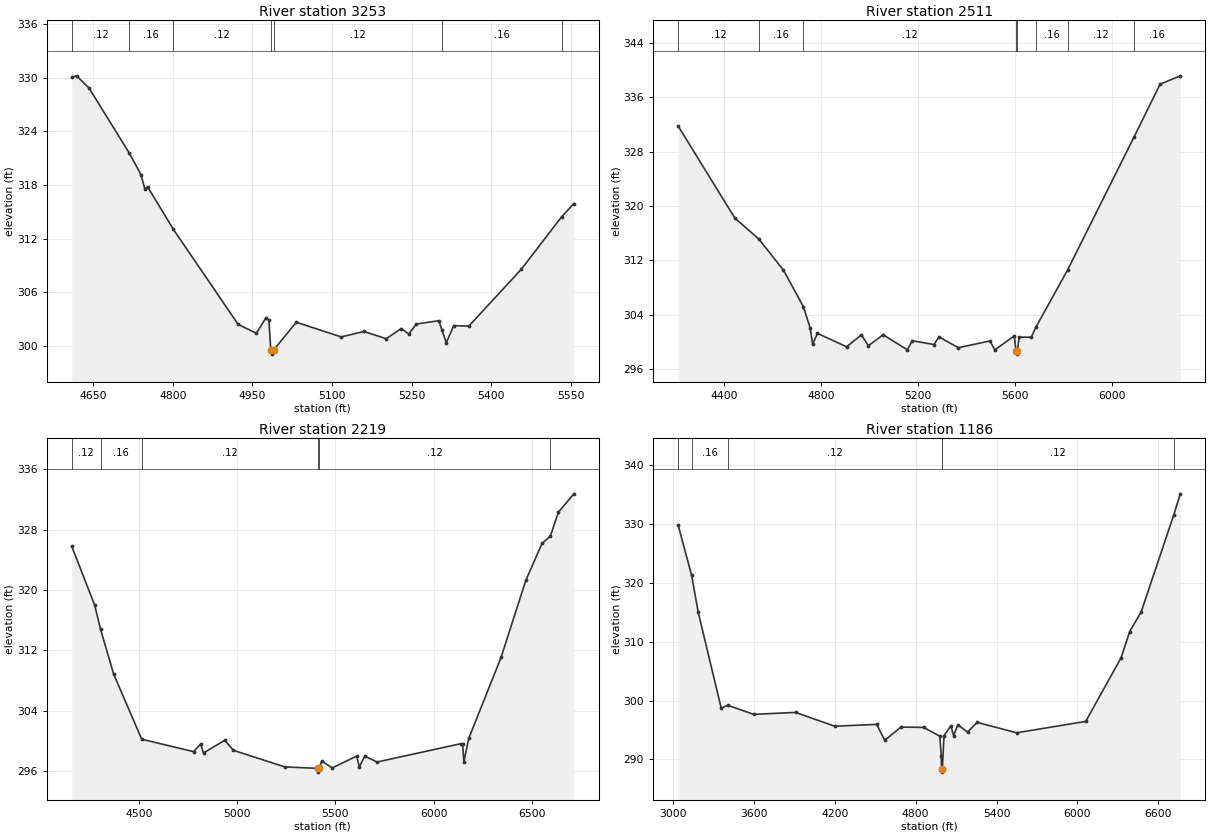
Type RM Length L Ch R = 1,3253,742,742,742
BEGIN DESCRIPTION:
COX CREEK 3.0
END DESCRIPTION:
XS GIS Cut Line= 3
      3593749.61     10653810.20      3593899.61     10654160.19
      3594299.63     10654560.21
#Sta/Elev= 30
  4609.5  330.06  4618.6  330.19  4642.1  328.82  4717.4  321.61  4740.0  319.15
  4747.3  317.55  4752.7  317.77  4801.2  313.03  4923.2  302.43  4957.6  301.44
  4975.8  303.20  4981.2  302.87  4984.6  299.61  4987.3  299.11  4990.6  299.61
  5032.7  302.67  5117.6  301.03  5160.0  301.64  5202.4  300.83  5230.7  301.97
  5244.8  301.35  5259.0  302.47  5301.4  302.84  5307.3  301.82  5315.5  300.40
  5329.7  302.29  5358.0  302.24  5457.0  308.59  5532.9  314.44  5556.0  315.92
#Mann=7,-1,0
  4609.5    0.12       0  4717.4    0.16       0  4801.2    0.12       0
  4984.6    0.07       0  4990.6    0.12       0  5307.3    0.16       0
  5532.9    0.12       0
Bank Sta=4984.6,4990.6
Exp/Cntr=0.3,0.1

Type RM Length L Ch R = 1,2511,292,292,292
BEGIN DESCRIPTION:
COX CREEK 2.0
END DESCRIPTION:
XS GIS Cut Line= 4
      3593288.85     10653887.19      3593302.74     10654588.60
      3593511.08     10654692.77      3594643.00     10654692.77
#Sta/Elev= 30
  4212.8  331.72  4445.8  318.22  4544.8  315.13  4645.9  310.57  4727.8  305.22
  4755.9  302.04  4765.9  299.68  4785.9  301.28  4905.9  299.31  4966.8  301.06
  4995.4  299.47  5056.2  301.08  5155.8  298.86  5175.8  300.20  5265.8  299.64
  5285.8  300.77  5365.8  299.17  5495.8  300.17  5515.8  298.85  5595.8  300.91
  5602.8  298.73  5605.6  298.23  5608.8  298.73  5615.8  300.73  5665.8  300.71
  5685.0  302.20  5815.5  310.61  6089.5  330.19  6195.8  337.89  6279.2  339.12
#Mann=8,-1,0
  4212.8    0.12       0  4544.8    0.16       0  4727.8    0.12       0
  5602.8    0.07       0  5608.8    0.12       0  5685.0    0.16       0
  5815.5    0.12       0  6089.5    0.16       0
Bank Sta=5602.8,5608.8
Exp/Cntr=0.3,0.1

Type RM Length L Ch R = 1,2219,1033,1033,1033
BEGIN DESCRIPTION:
Mapping XS 5d65035b
END DESCRIPTION:
XS GIS Cut Line= 4
      3593032.11     10654028.00      3593250.86     10655111.38
      3593518.23     10655194.72      3594645.64     10654889.45
#Sta/Elev= 30
  4159.3  325.79  4275.9  317.99  4305.7  314.78  4372.4  308.83  4515.1  300.19
  4778.5  298.54  4814.4  299.54  4829.3  298.36  4936.9  300.05  4981.5  298.71
  5242.9  296.51  5410.4  296.32  5413.2  295.82  5416.4  296.32  5430.8  297.29
  5483.7  296.38  5608.2  297.95  5621.5  296.52  5649.6  297.95  5711.8  297.16
  6136.5  299.59  6146.9  299.56  6153.5  297.19  6178.0  300.29  6342.4  311.04
  6468.1  321.27  6551.0  326.19  6593.3  327.16  6633.8  330.32  6712.6  332.77
#Mann=6,-1,0
  4159.3    0.12       0  4305.7    0.16       0  4515.1    0.12       0
  5410.4    0.07       0  5416.4    0.12       0  6593.3    0.16       0
Bank Sta=5410.4,5416.4
Exp/Cntr=0.3,0.1

Type RM Length L Ch R = 1,1186,0,0,0
BEGIN DESCRIPTION:
COX CREEK 1.0
END DESCRIPTION:
XS GIS Cut Line= 4
      3592955.72     10654052.32      3593059.89     10655712.08
      3593907.11     10655899.58      3594794.90     10655105.42
#Sta/Elev= 30
  3040.4  329.79  3139.6  321.30  3188.6  315.01  3358.9  298.74  3408.3  299.20
  3599.4  297.67  3910.0  298.00  4200.5  295.65  4511.2  295.97  4571.3  293.26
  4691.5  295.51  4859.3  295.45  4979.7  293.96  4989.9  290.62  4992.3  288.35
  4995.0  287.85  4998.3  288.35  5010.4  294.05  5061.6  295.72  5082.1  294.03
  5112.8  295.90  5185.1  294.66  5256.2  296.30  5549.5  294.54  6061.0  296.47
  6323.4  307.30  6387.0  311.74  6472.2  315.08  6713.2  331.53  6762.3  335.15
#Mann=6,-1,0
  3040.4    0.12       0  3139.6    0.16       0  3408.3    0.12       0
  4992.3    0.07       0  4998.3    0.12       0  6713.2    0.16       0
Bank Sta=4992.3,4998.3
Exp/Cntr=0.3,0.1

Chan Stop Cuts=-1