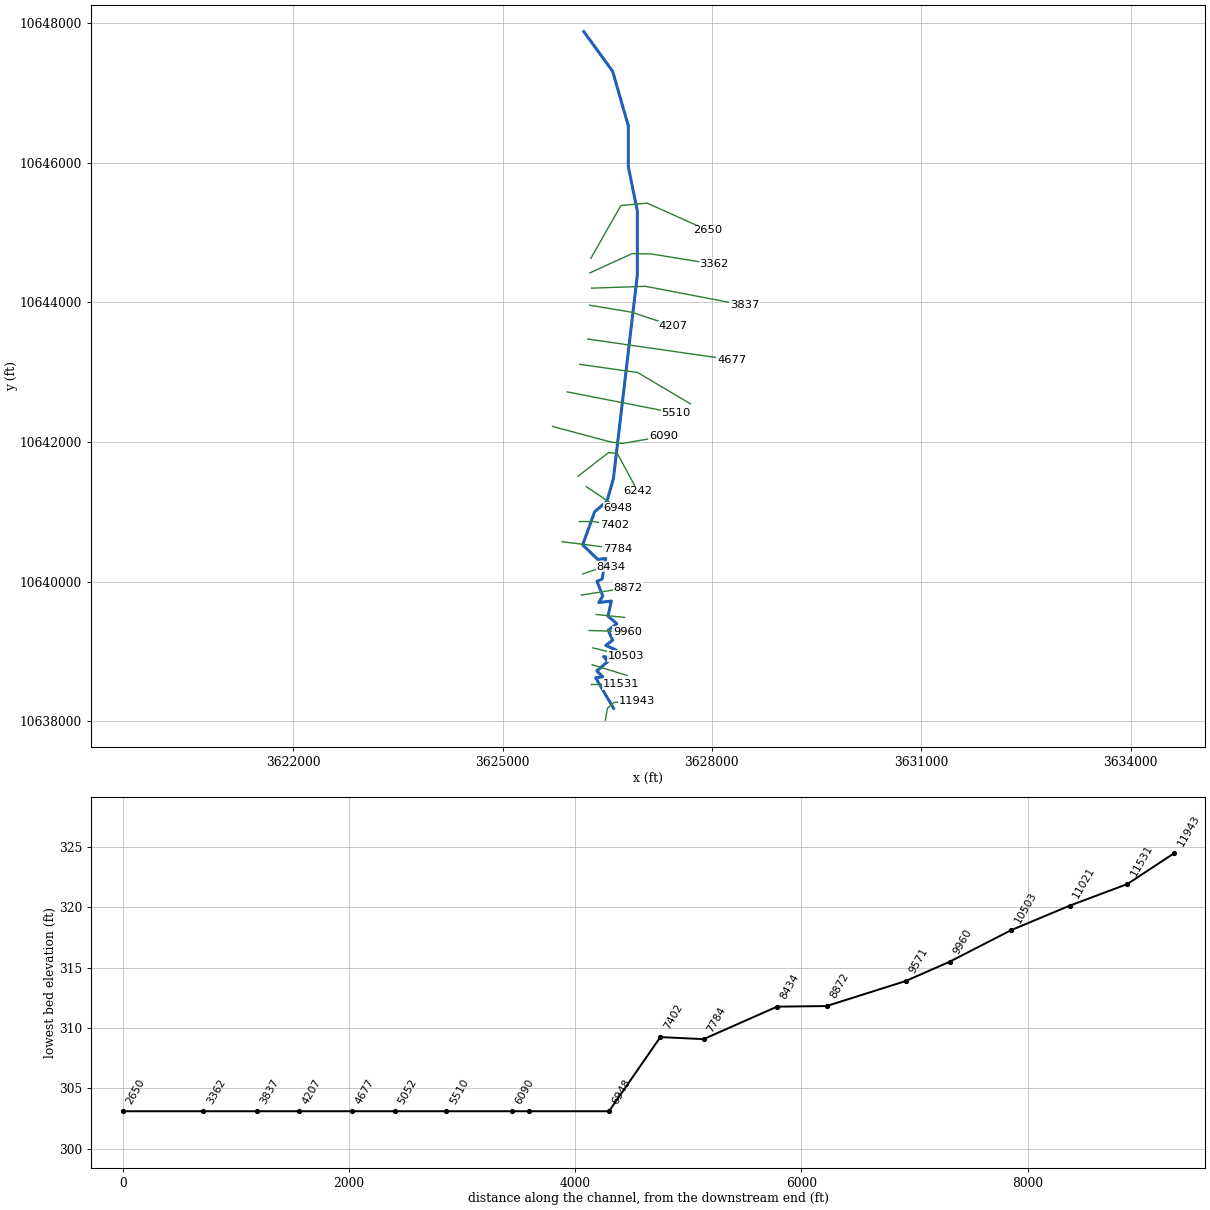
--- DRY BRANCH.prj (project) ---

Proj Title=DRY BRANCH Base Level Engineering
Current Plan=p01
Default Exp/Contr=0.3,0.1
English Units
Geom File=g01
Flow File=f01
Plan File=p01
BEGIN DESCRIPTION:
DRY BRANCH
END DESCRIPTION:

--- DRY BRANCH.p01 (plan) ---

Plan Title=Multiple Run
Short Identifier=Multiple
Geom File=g01
Flow File=f01
Subcritical Flow
K Sum by GR= 0
Std Step Tol= 0.01
Critical Tol= 0.01
Num of Std Step Trials= 20
Max Error Tol= 0.3
Flow Tol Ratio= 0.001
Split Flow NTrial= 30
Split Flow Tol= 0.02
Split Flow Ratio= 0.02
Log Output Level= 0
Friction Slope Method= 1
Unsteady Friction Slope Method= 2
Unsteady Bridges Friction Slope Method= 1
Parabolic Critical Depth
Global Vel Dist=  1 , 1 , 1
Global Log Level= 0
CheckData=True
Encroach Param= -1, 0, 0, 0
BEGIN DESCRIPTION:
Multiple Run
END DESCRIPTION:

--- DRY BRANCH.f01 (steady flow) ---

Flow Title=Multiple
Number of Profiles=7
Profile Names=10-year,25-year,50-year,1pct_min,100-year,1pct_plu,500-year
River Rch & RM= DRY BRANCH,Reach-1,11943
    1325    1827    2243    2013    2722    3682    3993
River Rch & RM= DRY BRANCH,Reach-1,6090
    1956    2745    3410    3089    4178    5650    6251
Boundary for River Rch & Prof#=DRY BRANCH,Reach-1,1
Up Type=0
Dn Type=3
Dn Slope=0.005
Boundary for River Rch & Prof#=DRY BRANCH,Reach-1,2
Up Type=0
Dn Type=3
Dn Slope=0.005
Boundary for River Rch & Prof#=DRY BRANCH,Reach-1,3
Up Type=0
Dn Type=3
Dn Slope=0.005
Boundary for River Rch & Prof#=DRY BRANCH,Reach-1,4
Up Type=0
Dn Type=3
Dn Slope=0.005
Boundary for River Rch & Prof#=DRY BRANCH,Reach-1,5
Up Type=0
Dn Type=3
Dn Slope=0.005
Boundary for River Rch & Prof#=DRY BRANCH,Reach-1,6
Up Type=0
Dn Type=3
Dn Slope=0.005
Boundary for River Rch & Prof#=DRY BRANCH,Reach-1,7
Up Type=0
Dn Type=3
Dn Slope=0.005

--- DRY BRANCH.g01 (geometry) ---

Geom Title=Existing Conditions

River Reach=DRY BRANCH,Reach-1
Reach XY= 30
      3626591.79     10638183.88      3626335.00     10638621.00
      3626437.00     10638636.00      3626351.75     10638720.00
      3626511.75     10638857.00      3626447.50     10638926.00
      3626598.00     10638894.00      3626629.50     10639019.00
      3626479.25     10639085.00      3626579.00     10639160.00
      3626514.75     10639303.00      3626638.50     10639396.00
      3626511.25     10639505.00      3626559.75     10639721.00
      3626380.00     10639700.00      3626436.75     10639794.00
      3626353.25     10640005.00      3626427.25     10640036.00
      3626478.75     10640331.00      3626363.25     10640317.00
      3626149.00     10640527.00      3626320.75     10641001.00
      3626496.75     10641151.00      3626588.50     10641471.00
      3626932.50     10644396.00      3626932.50     10645308.00
      3626802.50     10645946.00      3626802.50     10646532.00
      3626578.25     10647312.00      3626164.50     10647881.00

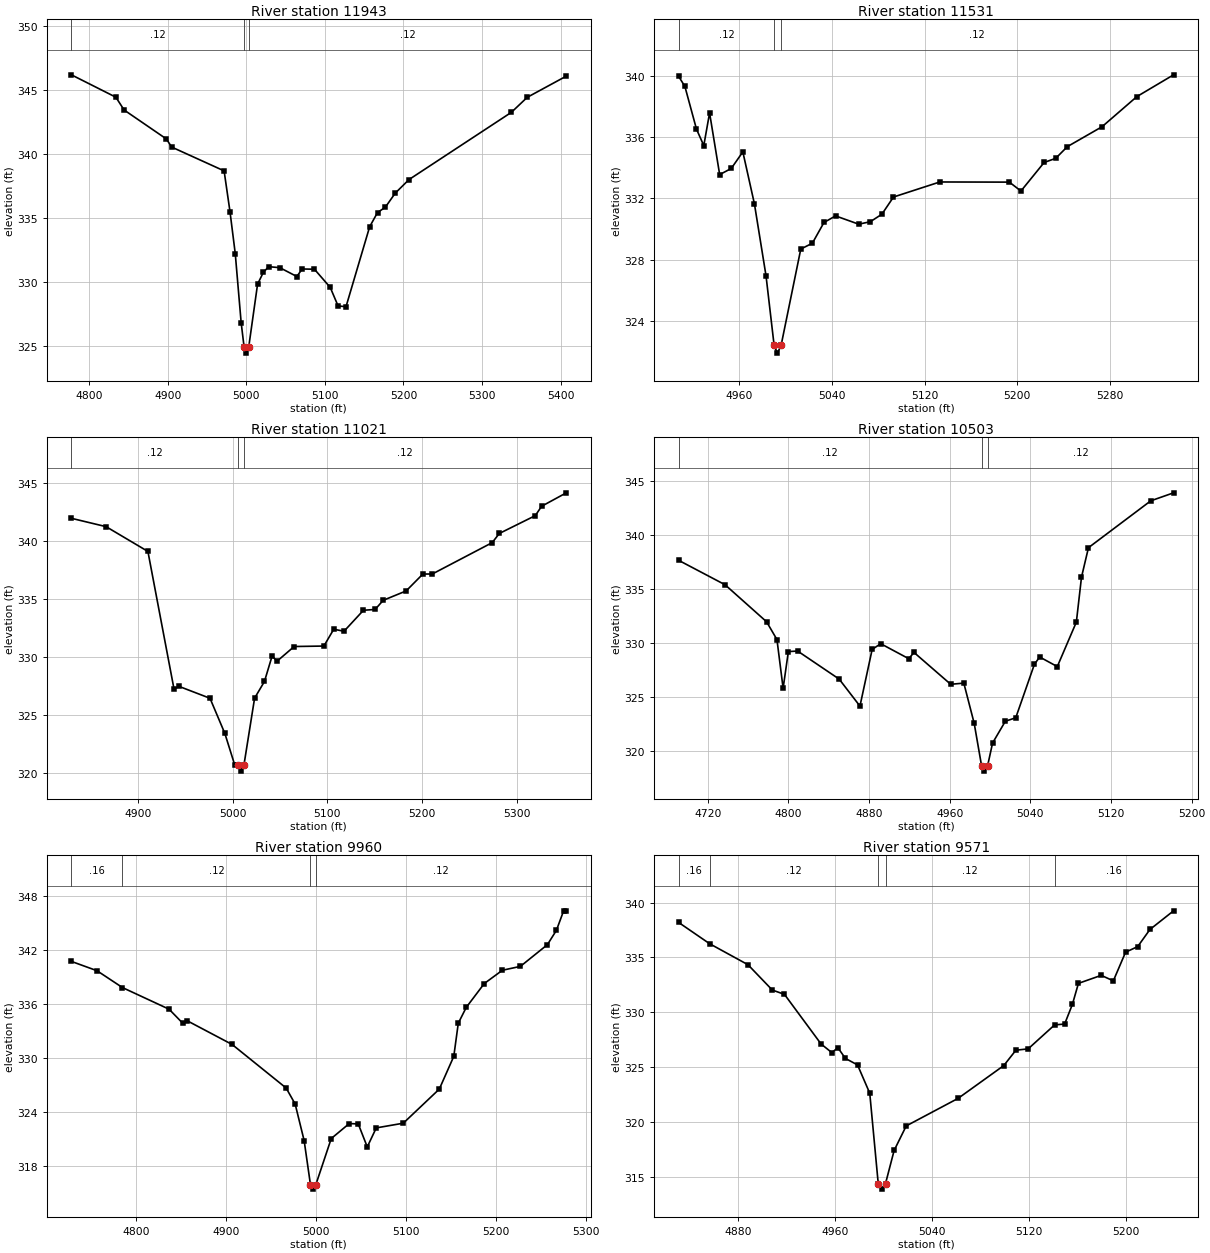
Type RM Length L Ch R = 1,11943,412,412,412
BEGIN DESCRIPTION:
DRY BRANCH 19.0
END DESCRIPTION:
XS GIS Cut Line= 4
      3626473.60     10638014.49      3626503.99     10638183.80
      3626595.14     10638266.27      3626929.29     10638292.31
#Sta/Elev= 30
  4777.3  346.22  4833.9  344.47  4844.4  343.47  4898.1  341.21  4905.0  340.57
  4971.7  338.71  4979.2  335.52  4985.9  332.24  4993.4  326.85  4997.1  324.96
  4999.8  324.46  5003.1  324.96  5014.3  329.85  5021.7  330.78  5028.5  331.22
  5042.7  331.14  5064.3  330.45  5071.1  331.04  5086.7  331.02  5106.8  329.60
  5116.8  328.15  5126.9  328.09  5157.0  334.34  5167.0  335.45  5177.0  335.87
  5189.6  336.97  5207.1  338.03  5337.5  343.29  5357.6  344.46  5407.4  346.12
#Mann=3,-1,0
  4777.3    0.12       0  4997.1    0.07       0  5003.1    0.12       0
Bank Sta=4997.1,5003.1
Exp/Cntr=0.3,0.1

Type RM Length L Ch R = 1,11531,510,510,510
BEGIN DESCRIPTION:
DRY BRANCH 18.0
END DESCRIPTION:
XS GIS Cut Line= 2
      3626274.18     10638525.00      3626701.26     10638528.47
#Sta/Elev= 30
  4907.8  339.95  4913.2  339.29  4923.2  336.51  4929.5  335.44  4934.5  337.57
  4943.2  333.55  4953.2  333.95  4963.2  335.03  4973.2  331.64  4983.2  326.96
  4990.2  322.42  4993.0  321.92  4996.2  322.42  5013.2  328.70  5023.2  329.08
  5033.2  330.43  5043.2  330.86  5063.2  330.32  5073.2  330.48  5083.2  330.97
  5093.2  332.09  5133.2  333.07  5193.2  333.06  5203.2  332.48  5223.2  334.34
  5233.2  334.61  5243.2  335.37  5273.2  336.67  5303.2  338.63  5334.9  340.05
#Mann=3,-1,0
  4907.8    0.12       0  4990.2    0.07       0  4996.2    0.12       0
Bank Sta=4990.2,4996.2
Exp/Cntr=0.3,0.1

Type RM Length L Ch R = 1,11021,518,518,518
BEGIN DESCRIPTION:
DRY BRANCH 17.0
END DESCRIPTION:
XS GIS Cut Line= 2
      3626284.57     10638807.99      3626784.53     10638655.15
#Sta/Elev= 30
  4829.8  341.96  4866.4  341.24  4910.6  339.10  4938.2  327.21  4943.4  327.45
  4976.2  326.42  4991.9  323.38  5002.4  320.64  5006.0  320.63  5008.8  320.13
  5012.0  320.63  5023.3  326.43  5033.7  327.87  5041.8  330.07  5047.0  329.62
  5065.1  330.89  5096.5  330.93  5106.9  332.38  5117.8  332.21  5138.3  334.02
  5150.6  334.09  5159.2  334.88  5183.4  335.69  5201.1  337.15  5211.0  337.15
  5274.3  339.86  5281.8  340.65  5319.8  342.19  5326.5  343.00  5352.6  344.16
#Mann=3,-1,0
  4829.8    0.12       0  5006.0    0.07       0  5012.0    0.12       0
Bank Sta=5006,5012
Exp/Cntr=0.3,0.1

Type RM Length L Ch R = 1,10503,543,543,543
BEGIN DESCRIPTION:
Mapping XS 4a410594
END DESCRIPTION:
XS GIS Cut Line= 2
      3626294.98     10639050.18      3626771.58     10638932.99
#Sta/Elev= 30
  4691.2  337.62  4737.2  335.36  4778.4  331.93  4788.7  330.28  4794.8  325.77
  4800.0  329.17  4809.2  329.22  4850.4  326.62  4871.0  324.12  4883.1  329.37
  4891.6  329.90  4919.4  328.51  4924.6  329.09  4961.0  326.14  4974.0  326.25
  4984.3  322.52  4991.6  318.60  4994.4  318.10  4997.6  318.60  5002.5  320.70
  5015.2  322.72  5025.5  323.04  5044.0  327.99  5049.2  328.67  5066.7  327.78
  5085.6  331.90  5090.7  336.06  5097.6  338.79  5159.4  343.13  5182.0  343.87
#Mann=3,-1,0
  4691.2    0.12       0  4991.6    0.07       0  4997.6    0.12       0
Bank Sta=4991.6,4997.6
Exp/Cntr=0.3,0.1

Type RM Length L Ch R = 1,9960,389,389,389
BEGIN DESCRIPTION:
DRY BRANCH 16.0
END DESCRIPTION:
XS GIS Cut Line= 2
      3626241.22     10639299.31      3626790.62     10639281.08
#Sta/Elev= 30
  4728.5  340.74  4756.9  339.71  4785.2  337.84  4837.0  335.44  4852.3  333.87
  4857.3  334.15  4907.0  331.53  4967.0  326.70  4977.0  324.93  4987.0  320.87
  4994.0  315.99  4996.8  315.49  5000.0  315.99  5017.1  321.10  5037.1  322.76
  5047.1  322.72  5057.1  320.17  5067.1  322.28  5097.1  322.80  5137.1  326.58
  5153.2  330.21  5158.2  333.89  5167.1  335.65  5187.1  338.29  5207.2  339.76
  5227.2  340.19  5257.2  342.60  5267.2  344.19  5275.2  346.35  5278.2  346.35
#Mann=4,-1,0
  4728.5    0.16       0  4785.2    0.12       0  4994.0    0.07       0
  5000.0    0.12       0
Bank Sta=4994,5000
Exp/Cntr=0.3,0.1

Type RM Length L Ch R = 1,9571,699,699,699
BEGIN DESCRIPTION:
DRY BRANCH 15.0
END DESCRIPTION:
XS GIS Cut Line= 2
      3626342.76     10639528.47      3626749.02     10639486.81
#Sta/Elev= 30
  4830.7  338.19  4856.3  336.25  4887.9  334.34  4908.0  332.03  4918.0  331.64
  4948.2  327.12  4957.1  326.33  4962.1  326.78  4968.3  325.80  4978.3  325.21
  4988.4  322.63  4995.4  314.39  4998.2  313.89  5001.4  314.39  5008.5  317.41
  5018.5  319.65  5061.3  322.16  5099.0  325.15  5109.0  326.55  5119.1  326.67
  5141.0  328.86  5149.2  328.93  5155.6  330.72  5160.6  332.64  5179.4  333.37
  5189.4  332.87  5199.5  335.48  5209.5  335.99  5219.6  337.55  5239.1  339.25
#Mann=5,-1,0
  4830.7    0.16       0  4856.3    0.12       0  4995.4    0.07       0
  5001.4    0.12       0  5141.0    0.16       0
Bank Sta=4995.4,5001.4
Exp/Cntr=0.3,0.1

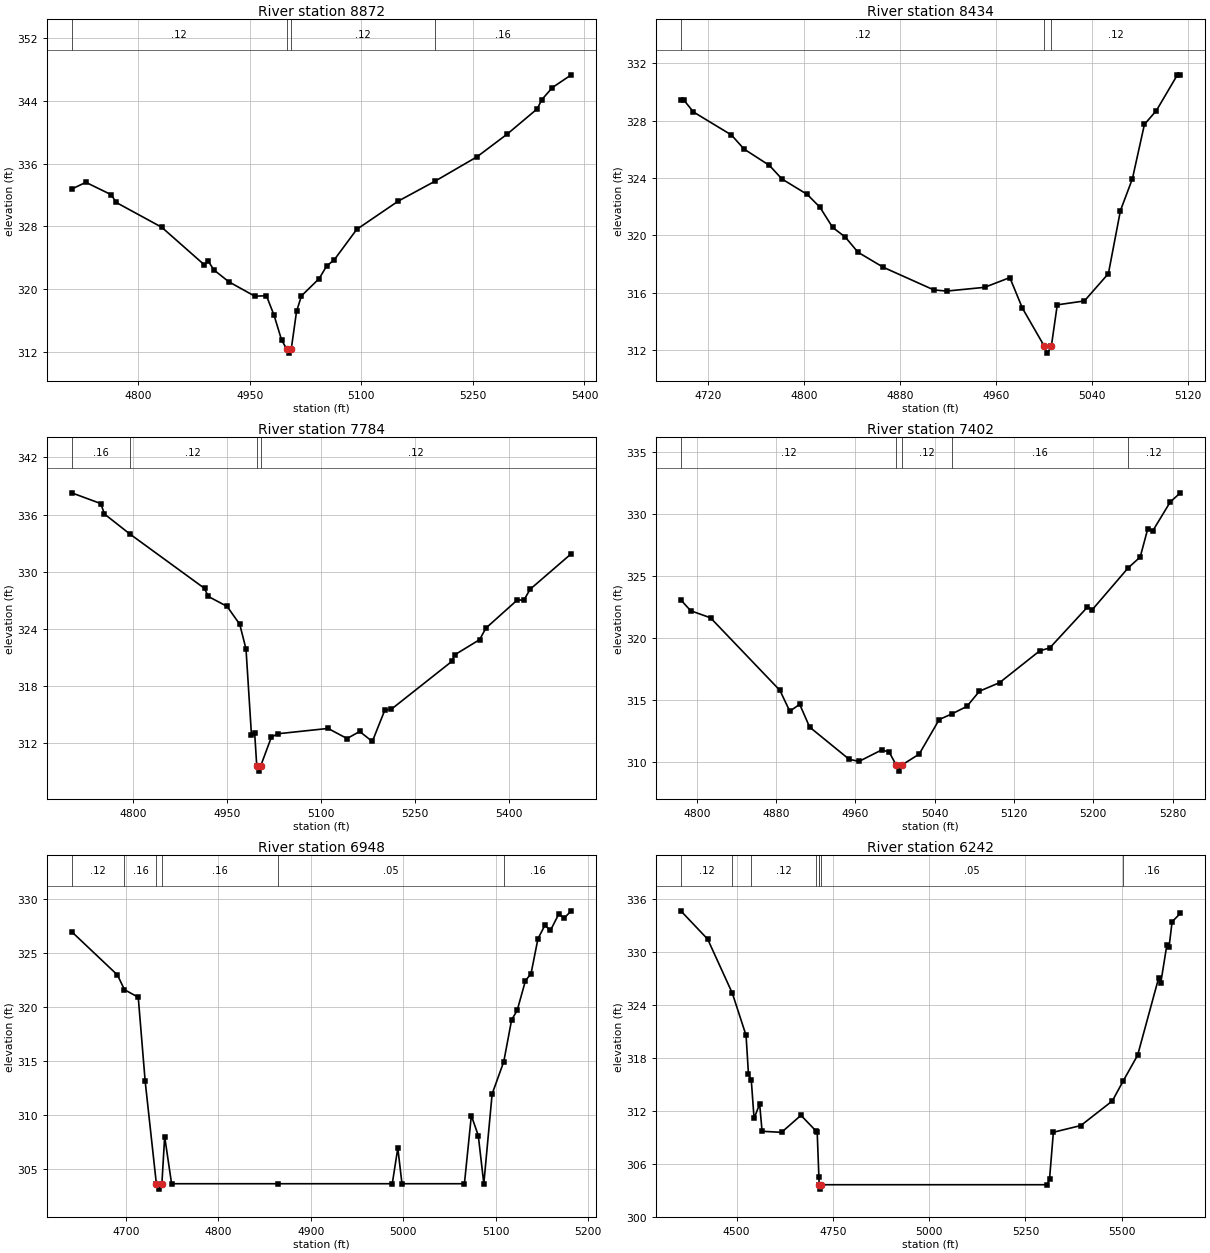
Type RM Length L Ch R = 1,8872,438,438,438
BEGIN DESCRIPTION:
DRY BRANCH 14.0
END DESCRIPTION:
XS GIS Cut Line= 2
      3626130.74     10639807.07      3626794.72     10639911.22
#Sta/Elev= 30
  4710.2  332.74  4729.3  333.60  4763.7  332.01  4769.8  331.05  4831.4  327.87
  4888.9  323.06  4894.0  323.54  4901.4  322.44  4921.6  320.92  4956.6  319.08
  4972.2  319.14  4982.4  316.67  4992.5  313.52  4999.6  312.32  5002.4  311.82
  5005.6  312.32  5012.7  317.13  5019.3  319.12  5043.1  321.32  5053.2  322.93
  5063.3  323.70  5093.7  327.60  5149.6  331.21  5198.7  333.73  5255.7  336.87
  5296.2  339.76  5336.6  342.98  5342.5  344.13  5356.9  345.69  5382.3  347.31
#Mann=4,-1,0
  4710.2    0.12       0  4999.6    0.07       0  5005.6    0.12       0
  5198.7    0.16       0
Bank Sta=4999.6,5005.6
Exp/Cntr=0.3,0.1

Type RM Length L Ch R = 1,8434,650,650,650
BEGIN DESCRIPTION:
DRY BRANCH 13.0
END DESCRIPTION:
XS GIS Cut Line= 3
      3626149.61     10640110.19      3626449.61     10640210.19
      3626549.58     10640210.19
#Sta/Elev= 30
  4697.4  329.42  4700.0  329.42  4707.9  328.60  4739.6  326.99  4750.1  326.01
  4771.2  324.87  4781.7  323.92  4802.8  322.84  4813.3  321.95  4823.9  320.54
  4834.4  319.87  4845.0  318.81  4866.1  317.76  4908.2  316.18  4918.8  316.10
  4950.4  316.36  4971.5  317.04  4982.0  314.90  5000.1  312.27  5002.8  311.77
  5006.1  312.27  5011.0  315.14  5033.6  315.41  5053.6  317.32  5063.6  321.71
  5073.6  323.94  5083.6  327.73  5093.6  328.70  5111.1  331.19  5113.6  331.19
#Mann=3,-1,0
  4697.4    0.12       0  5000.1    0.07       0  5006.1    0.12       0
Bank Sta=5000.1,5006.1
Exp/Cntr=0.3,0.1

Type RM Length L Ch R = 1,7784,382,382,382
BEGIN DESCRIPTION:
DRY BRANCH 12.0
END DESCRIPTION:
XS GIS Cut Line= 2
      3625853.39     10640571.88      3626644.81     10640471.21
#Sta/Elev= 30
  4701.3  338.29  4747.9  337.16  4753.6  336.07  4793.8  333.99  4913.5  328.26
  4919.3  327.42  4949.5  326.37  4969.7  324.49  4979.7  321.90  4988.4  312.90
  4993.5  313.13  4996.9  309.58  4999.7  309.08  5002.9  309.58  5020.1  312.63
  5030.2  313.00  5110.8  313.56  5141.0  312.50  5161.2  313.24  5181.4  312.19
  5201.5  315.51  5211.6  315.57  5308.2  320.59  5313.3  321.30  5352.7  322.88
  5362.8  324.09  5413.2  327.06  5423.3  327.01  5433.4  328.17  5499.1  331.90
#Mann=4,-1,0
  4701.3    0.16       0  4793.8    0.12       0  4996.9    0.07       0
  5002.9    0.12       0
Bank Sta=4996.9,5002.9
Exp/Cntr=0.3,0.1

Type RM Length L Ch R = 1,7402,454,454,454
BEGIN DESCRIPTION:
DRY BRANCH 11.0
END DESCRIPTION:
XS GIS Cut Line= 3
      3626099.59     10640860.19      3626299.61     10640860.19
      3626599.65     10640810.18
#Sta/Elev= 30
  4783.8  323.09  4793.8  322.21  4813.8  321.64  4883.8  315.78  4893.8  314.09
  4903.8  314.65  4913.8  312.81  4953.8  310.20  4963.8  310.04  4986.4  310.96
  4994.0  310.80  5001.1  309.75  5003.8  309.25  5007.1  309.75  5024.4  310.63
  5044.6  313.42  5057.5  313.88  5072.5  314.48  5085.2  315.71  5105.5  316.40
  5146.0  318.97  5156.2  319.21  5194.2  322.51  5199.2  322.31  5235.2  325.67
  5247.4  326.55  5255.0  328.82  5260.1  328.67  5277.8  331.01  5288.0  331.74
#Mann=5,-1,0
  4783.8    0.12       0  5001.1    0.07       0  5007.1    0.12       0
  5057.5    0.16       0  5235.2    0.12       0
Bank Sta=5001.1,5007.1
Exp/Cntr=0.3,0.1

Type RM Length L Ch R = 1,6948,706,706,706
BEGIN DESCRIPTION:
DRY BRANCH 10.0
END DESCRIPTION:
XS GIS Cut Line= 3
      3626199.59     10641360.20      3626499.61     10641160.19
      3626649.65     10641060.16
#Sta/Elev= 30
  4641.1  326.94  4690.7  322.93  4698.3  321.57  4713.2  320.87  4720.7  313.08
  4732.8  303.61  4735.5  303.11  4738.8  303.61  4741.8  307.97  4749.3  303.61
  4864.7  303.61  4988.2  303.61  4994.2  306.91  4998.7  303.61  5066.3  303.61
  5073.8  309.92  5081.3  308.07  5087.3  303.61  5096.3  311.92  5108.9  314.91
  5117.4  318.78  5123.4  319.65  5132.4  322.41  5138.4  323.05  5145.9  326.28
  5153.4  327.53  5159.4  327.05  5168.4  328.56  5174.4  328.21  5182.0  328.87
#Mann=6,-1,0
  4641.1    0.12       0  4698.3    0.16       0  4732.8   0.033       0
  4738.8    0.16       0  4864.7    0.05       0  5108.9    0.16       0
Bank Sta=4732.8,4738.8
Exp/Cntr=0.3,0.1

Type RM Length L Ch R = 1,6242,152,152,152
BEGIN DESCRIPTION:
DRY BRANCH 9.0
END DESCRIPTION:
XS GIS Cut Line= 4
      3626082.74     10641509.79      3626520.26     10641848.35
      3626645.26     10641835.33      3626939.52     10641291.08
#Sta/Elev= 30
  4354.9  334.67  4424.8  331.45  4488.7  325.33  4524.4  320.55  4530.7  316.13
  4538.0  315.46  4545.2  311.13  4559.7  312.77  4566.0  309.67  4616.5  309.55
  4667.0  311.48  4706.8  309.67  4709.1  309.64  4713.5  304.54  4714.3  303.61
  4717.0  303.11  4720.3  303.61  5306.3  303.61  5312.5  304.23  5322.5  309.56
  5393.8  310.32  5475.6  313.11  5503.5  315.35  5541.3  318.29  5595.6  327.00
  5601.2  326.43  5617.4  330.84  5623.1  330.60  5630.8  333.43  5652.5  334.39
#Mann=8,-1,0
  4354.9    0.12       0  4488.7    0.16       0  4538.0    0.12       0
  4706.8    0.16       0  4713.5    0.05       0  4714.3   0.033       0
  4720.3    0.05       0  5503.5    0.16       0
Bank Sta=4714.3,4720.3
Exp/Cntr=0.3,0.1

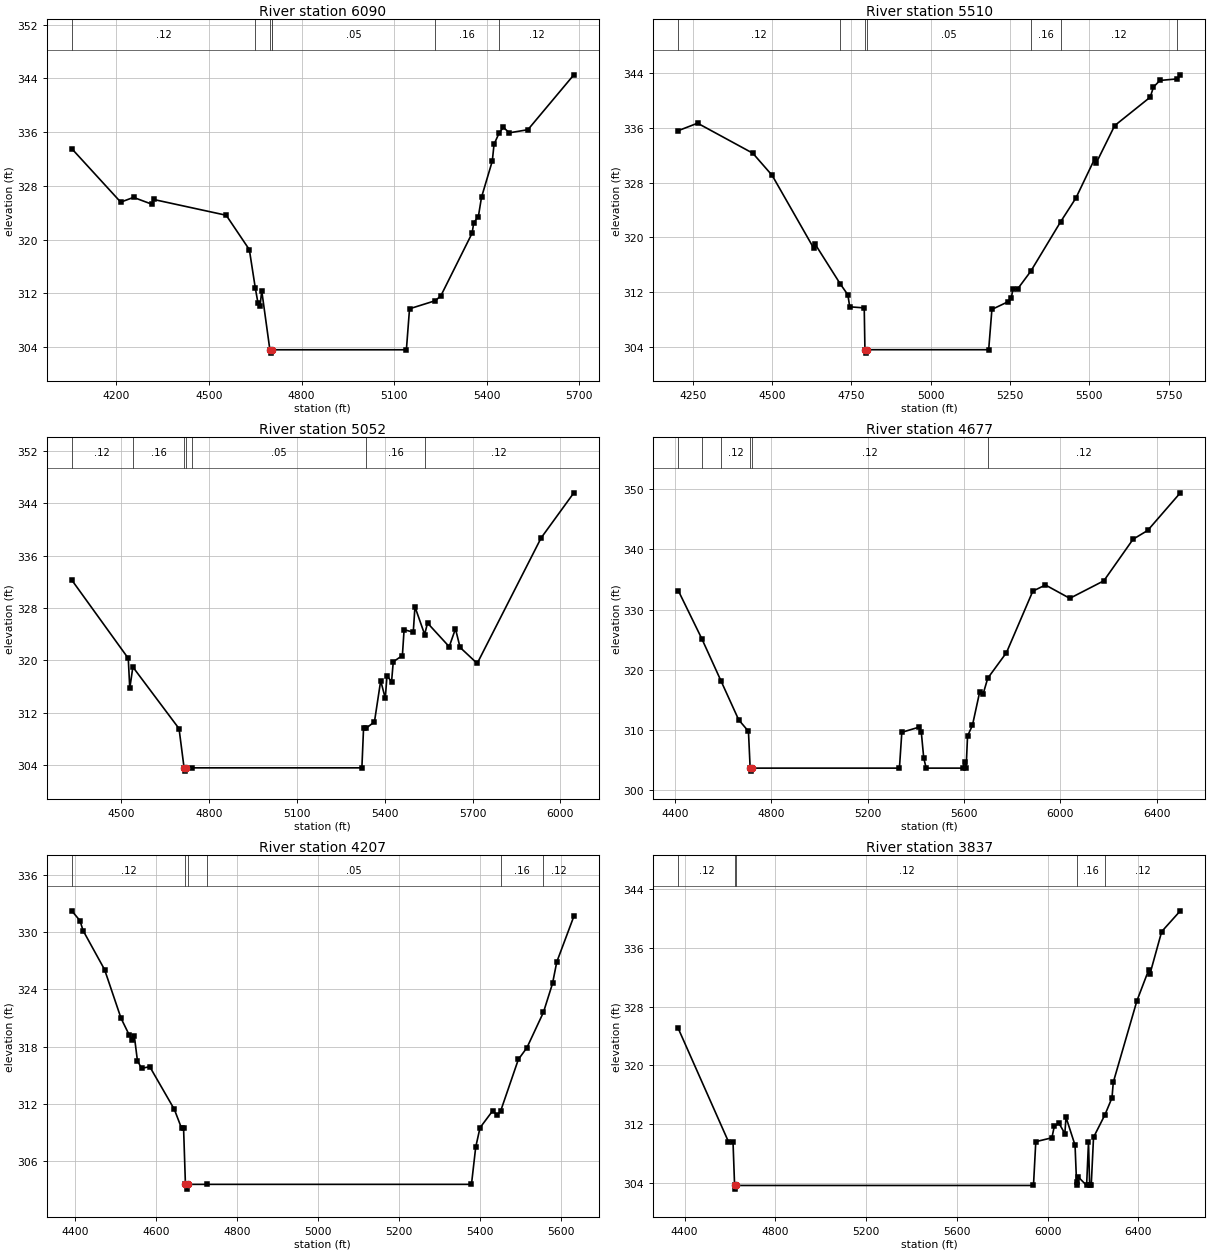
Type RM Length L Ch R = 1,6090,580,580,580
BEGIN DESCRIPTION:
DRY BRANCH 8.0
END DESCRIPTION:
XS GIS Cut Line= 4
      3625716.25     10642222.91      3626562.58     10641997.22
      3626718.83     10641979.86      3627304.68     10642079.67
#Sta/Elev= 30
  4055.3  333.54  4214.0  325.58  4255.4  326.29  4315.2  325.27  4320.4  325.98
  4555.9  323.63  4630.9  318.51  4650.1  312.82  4659.0  310.53  4665.8  310.15
  4671.0  312.41  4697.4  303.61  4700.2  303.11  4703.4  303.61  4705.6  303.61
  5139.9  303.61  5150.1  309.71  5233.4  310.91  5251.5  311.63  5353.0  320.97
  5358.2  322.53  5373.2  323.43  5383.4  326.31  5418.4  331.70  5424.0  334.19
  5440.9  335.91  5454.4  336.71  5473.5  335.90  5533.7  336.36  5682.7  344.53
#Mann=7,-1,0
  4055.3    0.12       0  4650.1    0.16       0  4697.4   0.033       0
  4703.4    0.16       0  4705.6    0.05       0  5233.4    0.16       0
  5440.9    0.12       0
Bank Sta=4697.4,4703.4
Exp/Cntr=0.3,0.1

Type RM Length L Ch R = 1,5510,458,458,458
BEGIN DESCRIPTION:
DRY BRANCH 7.0
END DESCRIPTION:
XS GIS Cut Line= 2
      3625928.92     10642717.71      3627482.70     10642413.90
#Sta/Elev= 30
  4204.0  335.58  4265.0  336.67  4439.1  332.29  4500.2  329.05  4630.8  318.46
  4635.9  319.00  4715.1  313.20  4738.9  311.62  4744.7  309.87  4790.5  309.71
  4792.7  303.61  4795.4  303.11  4798.7  303.61  5182.9  303.61  5193.1  309.49
  5244.0  310.61  5254.2  311.14  5259.3  312.43  5274.6  312.50  5315.2  315.03
  5409.9  322.29  5458.0  325.75  5517.0  331.45  5522.1  330.87  5580.3  336.32
  5692.3  340.47  5702.5  341.94  5722.9  342.91  5778.1  343.14  5787.2  343.73
#Mann=7,-1,0
  4204.0    0.12       0  4715.1    0.05       0  4792.7   0.033       0
  4798.7    0.05       0  5315.2    0.16       0  5409.9    0.12       0
  5778.1    0.16       0
Bank Sta=4792.7,4798.7
Exp/Cntr=0.3,0.1

Type RM Length L Ch R = 1,5052,375,375,375
BEGIN DESCRIPTION:
DRY BRANCH 6.0
END DESCRIPTION:
XS GIS Cut Line= 3
      3626106.82     10643112.68      3626935.85     10642995.49
      3627691.07     10642548.43
#Sta/Elev= 30
  4331.2  332.26  4524.2  320.31  4529.3  315.73  4539.9  318.99  4697.6  309.59
  4714.8  303.61  4717.5  303.11  4720.8  303.61  4740.9  303.61  5322.1  303.61
  5327.9  309.73  5337.2  309.68  5365.0  310.62  5386.4  316.91  5402.0  314.21
  5407.9  317.64  5423.5  316.75  5429.3  319.79  5460.5  320.74  5466.3  324.69
  5497.6  324.30  5503.4  328.18  5536.5  323.95  5546.3  325.70  5620.4  322.09
  5641.8  324.82  5657.5  321.98  5716.0  319.54  5934.3  338.68  6046.1  345.56
#Mann=7,-1,0
  4331.2    0.12       0  4539.9    0.16       0  4714.8   0.033       0
  4720.8    0.16       0  4740.9    0.05       0  5337.2    0.16       0
  5536.5    0.12       0
Bank Sta=4714.8,4720.8
Exp/Cntr=0.3,0.1

Type RM Length L Ch R = 1,4677,470,470,470
BEGIN DESCRIPTION:
DRY BRANCH 5.0
END DESCRIPTION:
XS GIS Cut Line= 2
      3626221.18     10643475.30      3628283.62     10643178.43
#Sta/Elev= 30
  4414.5  333.17  4513.1  325.08  4591.8  318.14  4665.5  311.64  4705.9  309.74
  4713.0  303.61  4715.8  303.11  4719.0  303.61  5332.5  303.61  5342.4  309.57
  5413.1  310.42  5423.2  309.62  5433.3  305.32  5443.4  303.61  5595.0  303.61
  5604.3  304.68  5609.3  303.61  5615.2  308.96  5635.4  310.72  5665.7  316.31
  5679.8  315.95  5699.0  318.57  5776.8  322.84  5886.1  333.07  5938.5  334.09
  6039.5  331.87  6180.9  334.79  6302.2  341.71  6362.8  343.17  6498.2  349.43
#Mann=6,-1,0
  4414.5    0.12       0  4513.1    0.16       0  4591.8    0.12       0
  4713.0   0.033       0  4719.0    0.12       0  5699.0    0.12       0
Bank Sta=4713,4719
Exp/Cntr=0.3,0.1

Type RM Length L Ch R = 1,4207,370,370,370
BEGIN DESCRIPTION:
DRY BRANCH 4.0
END DESCRIPTION:
XS GIS Cut Line= 3
      3626249.57     10643960.20      3626849.61     10643860.19
      3627449.63     10643660.18
#Sta/Elev= 30
  4391.1  332.22  4411.4  331.19  4419.0  330.16  4472.2  326.07  4512.8  320.99
  4533.1  319.23  4540.7  318.76  4545.7  319.12  4553.3  316.56  4563.5  315.74
  4583.8  315.92  4644.6  311.45  4662.3  309.49  4667.4  309.50  4672.0  303.61
  4674.8  303.11  4678.0  303.61  4725.2  303.61  5378.9  303.61  5389.4  307.51
  5400.0  309.53  5431.6  311.32  5442.1  310.82  5451.1  311.29  5494.8  316.68
  5515.9  317.90  5556.8  321.61  5579.2  324.62  5589.7  326.87  5631.9  331.64
#Mann=6,-1,0
  4391.1    0.12       0  4672.0   0.033       0  4678.0    0.12       0
  4725.2    0.05       0  5451.1    0.16       0  5556.8    0.12       0
Bank Sta=4672,4678
Exp/Cntr=0.3,0.1

Type RM Length L Ch R = 1,3837,475,475,475
BEGIN DESCRIPTION:
DRY BRANCH 3.0
END DESCRIPTION:
XS GIS Cut Line= 3
      3626278.39     10644204.47      3627049.27     10644230.51
      3628465.31     10643959.80
#Sta/Elev= 30
  4371.7  325.02  4593.0  309.58  4613.1  309.59  4620.1  303.61  4622.8  303.11
  4626.1  303.61  5937.5  303.61  5947.7  309.58  6018.7  310.11  6029.1  311.65
  6049.5  312.11  6075.8  310.68  6080.9  312.91  6120.7  309.10  6127.9  303.61
  6129.6  304.02  6133.0  304.83  6171.7  303.61  6180.0  309.55  6185.1  303.61
  6192.0  303.61  6202.2  310.17  6252.8  313.27  6283.6  315.56  6289.2  317.67
  6393.4  328.78  6445.5  333.01  6450.6  332.41  6502.6  338.22  6584.7  341.05
#Mann=5,-1,0
  4371.7    0.12       0  4620.1   0.033       0  4626.1    0.12       0
  6129.6    0.16       0  6252.8    0.12       0
Bank Sta=4620.1,4626.1
Exp/Cntr=0.3,0.1

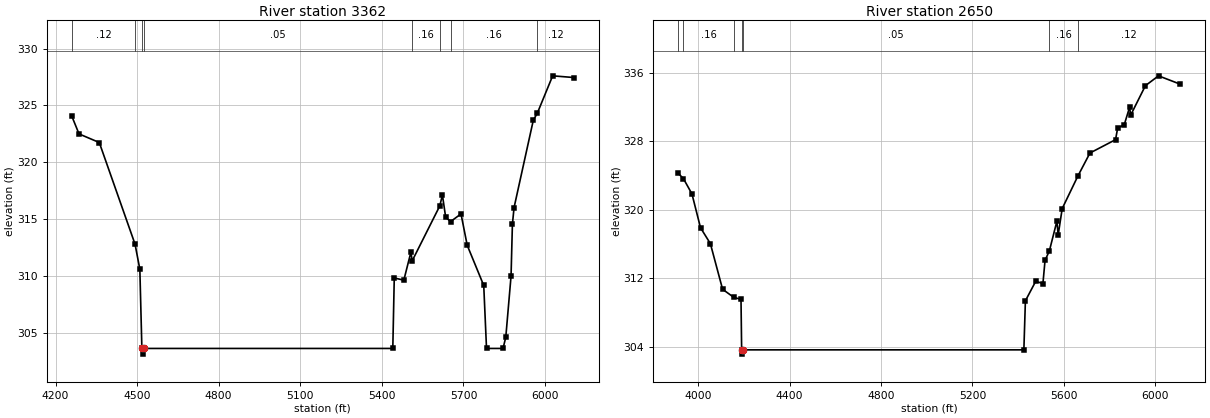
Type RM Length L Ch R = 1,3362,712,712,712
BEGIN DESCRIPTION:
DRY BRANCH 2.0
END DESCRIPTION:
XS GIS Cut Line= 4
      3626252.39     10644423.22      3626856.56     10644699.26
      3627137.81     10644694.06      3628026.53     10644548.54
#Sta/Elev= 30
  4259.8  324.06  4286.4  322.49  4361.0  321.73  4492.5  312.78  4510.1  310.58
  4517.6  303.61  4520.4  303.11  4523.6  303.61  5440.2  303.61  5445.6  309.81
  5480.8  309.62  5506.9  312.10  5511.3  311.31  5612.9  316.15  5622.6  317.11
  5634.7  315.14  5653.1  314.78  5691.0  315.45  5713.8  312.69  5774.6  309.15
  5784.8  303.61  5845.6  303.61  5855.7  304.61  5875.0  309.98  5880.0  314.54
  5886.1  316.01  5957.0  323.71  5971.4  324.30  6028.0  327.60  6105.9  327.45
#Mann=8,-1,0
  4259.8    0.12       0  4492.5    0.05       0  4517.6   0.033       0
  4523.6    0.05       0  5511.3    0.16       0  5612.9    0.12       0
  5653.1    0.16       0  5971.4    0.12       0
Bank Sta=4517.6,4523.6
Exp/Cntr=0.3,0.1

Type RM Length L Ch R = 1,2650,0,0,0
BEGIN DESCRIPTION:
DRY BRANCH 1.0
END DESCRIPTION:
XS GIS Cut Line= 4
      3626265.85     10644631.44      3626696.41     10645388.39
      3627071.41     10645423.11      3627938.35     10645034.73
#Sta/Elev= 30
  3912.6  324.24  3935.5  323.61  3972.6  321.83  4010.1  317.88  4053.3  316.02
  4106.7  310.69  4155.8  309.74  4187.3  309.51  4190.1  303.61  4192.9  303.11
  4196.1  303.61  5425.3  303.61  5432.0  309.34  5477.1  311.62  5508.7  311.36
  5518.0  314.07  5537.0  315.18  5569.9  318.65  5575.4  317.03  5593.1  320.12
  5661.5  323.91  5714.5  326.61  5826.5  328.17  5835.9  329.54  5864.6  329.91
  5887.7  331.93  5893.2  331.06  5957.3  334.48  6014.6  335.63  6110.0  334.65
#Mann=7,-1,0
  3912.6    0.12       0  3935.5    0.16       0  4155.8    0.05       0
  4190.1   0.033       0  4196.1    0.05       0  5537.0    0.16       0
  5661.5    0.12       0
Bank Sta=4190.1,4196.1
Exp/Cntr=0.3,0.1

Chan Stop Cuts=-1