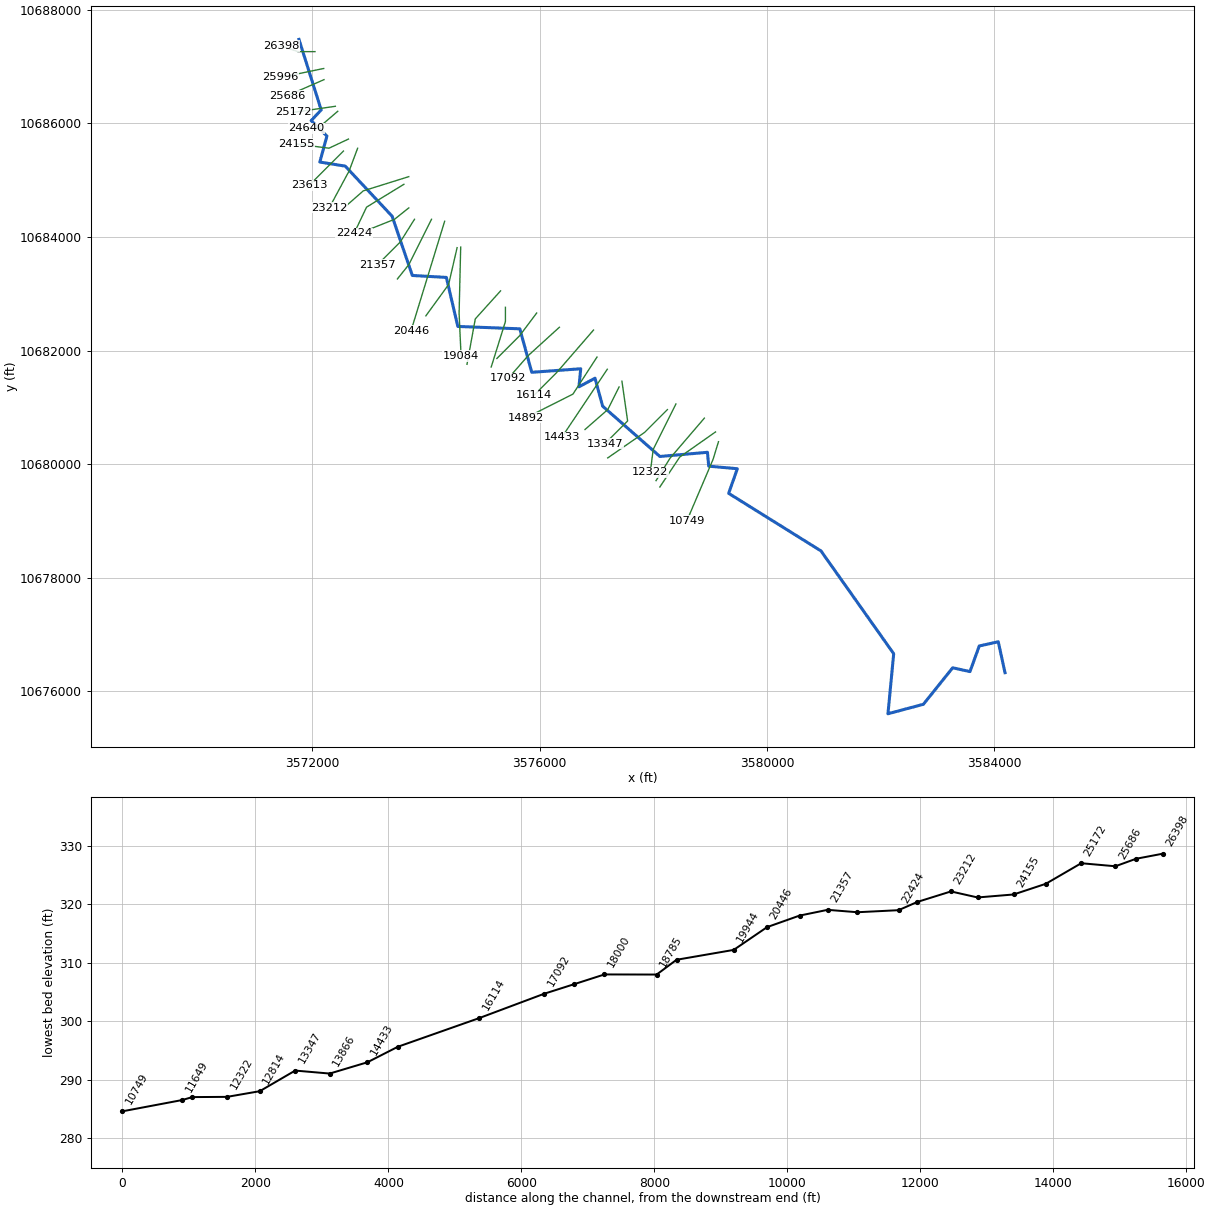
--- GREENBRIAR CREEK.prj (project) ---

Proj Title=GREENBRIAR CREEK Base Level Engineering
Current Plan=p01
Default Exp/Contr=0.3,0.1
English Units
Geom File=g01
Flow File=f01
Plan File=p01
Y Axis Title=Elevation
X Axis Title(PF)=Main Channel Distance
X Axis Title(XS)=Station
BEGIN DESCRIPTION:
GREENBRIAR CREEK
END DESCRIPTION:
DSS Export Rating Curves= 0
DSS Export Rating Curve Sorted= 0
DSS Export Volume Flow Curves= 0
DXF OffsetX= 0
DXF OffsetY= 0
DXF ScaleX= 1
DXF ScaleY= 10

--- GREENBRIAR CREEK.p01 (plan) ---

Plan Title=Multiple Run
Short Identifier=Multiple
Geom File=g01
Flow File=f01
Subcritical Flow
K Sum by GR= 0
Std Step Tol= 0.01
Critical Tol= 0.01
Num of Std Step Trials= 20
Max Error Tol= 0.3
Flow Tol Ratio= 0.001
Split Flow NTrial= 30
Split Flow Tol= 0.02
Split Flow Ratio= 0.02
Log Output Level= 0
Friction Slope Method= 1
Unsteady Friction Slope Method= 2
Unsteady Bridges Friction Slope Method= 1
Parabolic Critical Depth
Global Vel Dist=  1 , 1 , 1
Global Log Level= 0
CheckData=True
Encroach Param= -1, 0, 0, 0
BEGIN DESCRIPTION:
Multiple Run
END DESCRIPTION:

--- GREENBRIAR CREEK.f01 (steady flow) ---

Flow Title=Multiple
Number of Profiles=7
Profile Names=10-year,25-year,50-year,1pct_min,100-year,1pct_plu,500-year
River Rch & RM= GREENBRIAR CREEK,Reach-1,26398
    1290    1771    2167    1936    2618    3541    3810
River Rch & RM= GREENBRIAR CREEK,Reach-1,24640
    2045    2873    3570    3232    4371    5912    6537
River Rch & RM= GREENBRIAR CREEK,Reach-1,20934
    2287    3226    4019    3646    4931    6668    7405
River Rch & RM= GREENBRIAR CREEK,Reach-1,18785
    3002    4284    5379    4913    6645    8986   10119
River Rch & RM= GREENBRIAR CREEK,Reach-1,12814
    3588    5121    6428    5862    7928   10722   12036
Boundary for River Rch & Prof#=GREENBRIAR CREEK,Reach-1,1
Up Type=0
Dn Type=3
Dn Slope=0.005
Boundary for River Rch & Prof#=GREENBRIAR CREEK,Reach-1,2
Up Type=0
Dn Type=3
Dn Slope=0.005
Boundary for River Rch & Prof#=GREENBRIAR CREEK,Reach-1,3
Up Type=0
Dn Type=3
Dn Slope=0.005
Boundary for River Rch & Prof#=GREENBRIAR CREEK,Reach-1,4
Up Type=0
Dn Type=3
Dn Slope=0.005
Boundary for River Rch & Prof#=GREENBRIAR CREEK,Reach-1,5
Up Type=0
Dn Type=3
Dn Slope=0.005
Boundary for River Rch & Prof#=GREENBRIAR CREEK,Reach-1,6
Up Type=0
Dn Type=3
Dn Slope=0.005
Boundary for River Rch & Prof#=GREENBRIAR CREEK,Reach-1,7
Up Type=0
Dn Type=3
Dn Slope=0.005

--- GREENBRIAR CREEK.g01 (geometry) ---

Geom Title=Existing Conditions
Program Version=4.10

River Reach=GREENBRIAR CREEK,Reach-1
Reach XY= 30
      3571767.25       10687476.      3572158.25       10686234.
      3571981.25       10686046.        3572259.       10685774.
      3572134.75       10685317.        3572582.       10685245.
      3573406.25       10684364.      3573761.75       10683321.
      3574360.75       10683287.        3574562.       10682424.
      3575652.75       10682382.      3575863.25       10681617.
       3576724.5       10681679.      3576693.75       10681362.
        3576976.       10681513.      3577110.25       10681021.
      3578117.25       10680136.       3578954.5       10680209.
      3578976.75       10679965.      3579480.25       10679920.
       3579327.5       10679487.      3580951.25       10678474.
        3582231.       10676665.      3582130.25       10675608.
      3582754.25       10675775.      3583268.75       10676417.
       3583573.5       10676350.      3583736.25       10676801.
      3584070.75       10676875.       3584189.5       10676330.

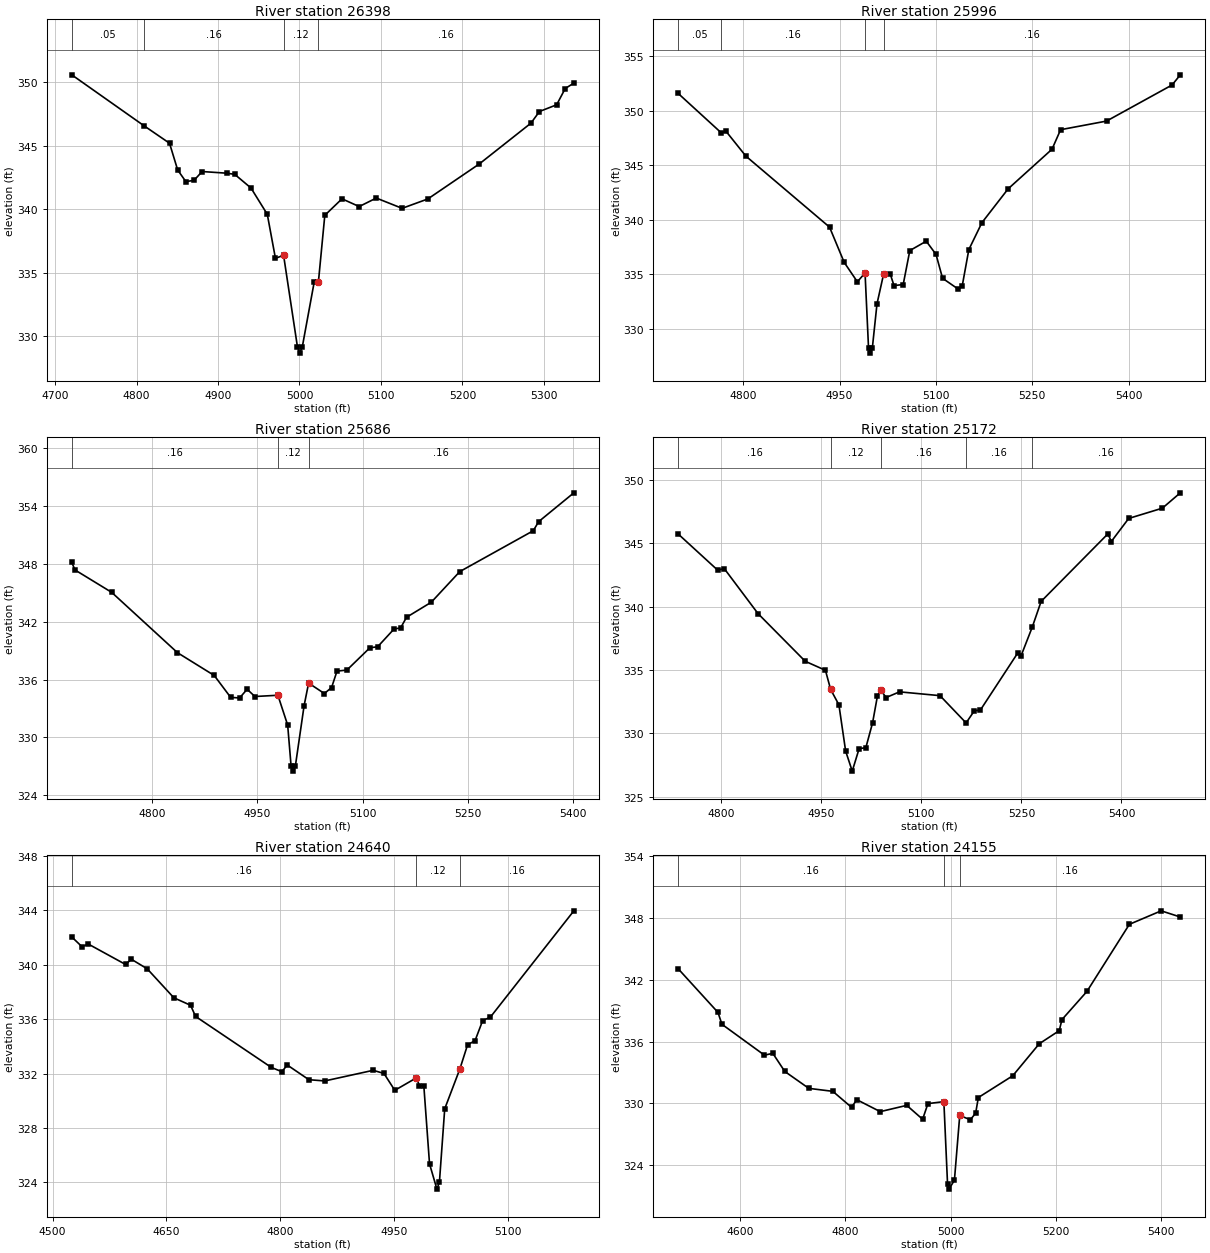
Type RM Length L Ch R = 1 ,26398   ,402,402,402
BEGIN DESCRIPTION:
GREENBRIAR CREEK 41.0
END DESCRIPTION:
XS GIS Cut Line= 3
      3572049.65     10687260.19      3571749.61     10687260.19
      3571449.58      10687360.2
#Sta/Elev= 30
  4720.5  350.59  4809.1  346.58  4840.5   345.2  4850.5  343.09  4860.5  342.18
  4870.5  342.27  4880.5  342.97  4910.5  342.84  4920.5  342.75  4940.5  341.67
  4960.5   339.6  4970.5  336.13  4980.5  336.37  4997.5  329.16  5000.3  328.66
  5003.5  329.16    5018  334.23  5023.2  334.23  5031.1  339.52  5052.2  340.82
  5073.3  340.21  5094.3  340.88    5126  340.07  5157.6  340.81  5220.8  343.57
  5284.1  346.78  5294.6   347.7  5315.7  348.23  5326.2  349.51  5336.8  349.94
#Mann= 4 ,-1 , 0
  4720.5     .05       0  4809.1     .16       0  4980.5     .12       0
  5023.2     .16       0
Bank Sta=4980.5,5023.2
XS Rating Curve= 0 ,0
Exp/Cntr=0.3,0.1

Type RM Length L Ch R = 1 ,25996   ,310,310,310
BEGIN DESCRIPTION:
GREENBRIAR CREEK 40.0
END DESCRIPTION:
XS GIS Cut Line= 2
      3572202.69     10686963.43      3571437.09      10686805.1
#Sta/Elev= 30
  4698.7  351.59  4765.2  348.01  4773.3  348.11    4804  345.85  4934.3  339.34
  4957.1  336.11  4977.6  334.33  4989.6  335.14    4995  328.29  4997.7  327.79
    5001  328.29  5008.2  332.31  5018.4  335.01  5028.6  335.08  5034.7  333.98
    5049  334.08  5059.3  337.19  5084.9  338.05  5100.1  336.84  5110.3  334.65
  5135.1  333.64  5140.9  333.95  5151.2  337.28  5171.6  339.75  5212.4  342.85
  5280.7  346.48  5294.1  348.27  5365.6  349.06  5467.7  352.37  5480.5   353.3
#Mann= 4 ,-1 , 0
  4698.7     .05       0  4765.2     .16       0  4989.6     .12       0
  5018.4     .16       0
#XS Ineff= 1 ,-1
 5082.95 5172.16  337.84
Permanent Ineff=
       F
Bank Sta=4989.6,5018.4
XS Rating Curve= 0 ,0
Exp/Cntr=0.3,0.1

Type RM Length L Ch R = 1 ,25686   ,514,514,514
BEGIN DESCRIPTION:
GREENBRIAR CREEK 39.0
END DESCRIPTION:
XS GIS Cut Line= 2
      3572208.38     10686767.22      3571553.77      10686481.1
#Sta/Elev= 30
  4686.2  348.13  4690.8  347.35    4743  345.03  4836.6  338.78  4888.9  336.42
  4912.3  334.15    4925  334.09  4935.7  334.99  4946.8  334.24  4979.5  334.37
  4993.4  331.28  4998.3  327.01  5001.1  326.51  5004.3  327.01  5016.8   333.3
  5023.2  335.63  5045.6  334.55  5055.9  335.17  5063.6  336.87  5077.7  336.98
  5110.4  339.29  5121.4  339.39  5144.7  341.23  5154.1  341.35  5162.6  342.45
  5197.8  344.01  5238.3  347.18  5342.8  351.41  5350.6  352.36  5400.6  355.34
#Mann= 3 , 0 , 0
  4686.2     .16       0  4979.5     .12       0  5023.2     .16       0
Bank Sta=4979.5,5023.2
XS Rating Curve= 0 ,0
Exp/Cntr=0.3,0.1

Type RM Length L Ch R = 1 ,25172   ,532,532,532
BEGIN DESCRIPTION:
GREENBRIAR CREEK 38.0
END DESCRIPTION:
XS GIS Cut Line= 2
      3572408.01     10686298.46      3571663.03     10686190.18
#Sta/Elev= 30
  4735.4  345.72  4794.4  342.88  4804.5  342.99    4855  339.45  4925.8  335.69
  4956.1  334.98  4963.9  333.47  4976.3  332.26  4986.4  328.61  4996.3  327.03
  5006.6   328.8  5016.7  328.88  5026.8  330.84  5034.1  332.96  5039.1  333.43
    5047  332.83  5067.2  333.28  5127.9  332.98    5167  330.83  5179.4  331.79
  5188.5  331.85  5244.4  336.34  5249.5  336.13  5266.4  338.41  5279.5  340.41
  5379.7  345.74  5384.7  345.13  5410.8  346.95  5461.3  347.76  5488.2  348.97
#Mann= 5 ,-1 , 0
  4735.4     .16       0  4963.9     .12       0  5039.1     .16       0
    5167     .16       0  5266.4     .16       0
Bank Sta=4963.9,5039.1
XS Rating Curve= 0 ,0
Exp/Cntr=0.3,0.1

Type RM Length L Ch R = 1 ,24640   ,485,485,485
BEGIN DESCRIPTION:
GREENBRIAR CREEK 37.0
END DESCRIPTION:
XS GIS Cut Line= 3
       3572449.6     10686210.18      3572099.61     10685910.19
      3571899.57     10685910.19
#Sta/Elev= 30
  4525.3  342.04    4539  341.31  4546.7  341.53  4596.1  340.02  4603.8   340.4
  4624.6   339.7  4659.7  337.57  4681.7  337.02  4688.3   336.2  4788.1  332.45
  4801.9  332.14    4809  332.63  4837.5  331.55  4858.4  331.46  4922.1  332.24
  4936.3  332.01  4950.6  330.77  4979.1  331.69    4983   331.1  4988.8   331.1
  4996.3  325.37    5006  323.51  5009.3  324.01  5016.3  329.41  5036.3  332.35
  5046.3   334.1  5056.3  334.43  5066.3   335.9  5076.3  336.14  5186.3  343.96
#Mann= 3 , 0 , 0
  4525.3     .16       0  4979.1     .12       0  5036.3     .16       0
Bank Sta=4979.1,5036.3
XS Rating Curve= 0 ,0
Exp/Cntr=0.3,0.1

Type RM Length L Ch R = 1 ,24155   ,542,542,542
BEGIN DESCRIPTION:
GREENBRIAR CREEK 36.0
END DESCRIPTION:
XS GIS Cut Line= 3
      3572638.09     10685721.22      3572295.17     10685560.61
      3571723.46     10685634.24
#Sta/Elev= 30
  4481.9  343.06  4557.5  338.83    4565  337.68  4645.9  334.68  4661.8  334.86
  4684.6   333.1  4730.3  331.46    4776  331.17  4811.5  329.62  4821.6  330.36
  4866.2   329.2  4916.6  329.81  4946.8  328.46  4956.9  329.98  4987.2  330.17
  4994.2  322.18    4997  321.68  5007.3  322.55  5017.4  328.83  5037.6  328.41
  5047.7  329.06  5052.8  330.57  5118.2  332.68  5168.7  335.79  5206.7  337.06
  5211.8  338.13  5259.4  340.87  5340.1  347.38  5400.6  348.69    5437  348.09
#Mann= 3 , 0 , 0
  4481.9     .16       0  4987.2     .12       0  5017.4     .16       0
Bank Sta=4987.2,5017.4
XS Rating Curve= 0 ,0
Exp/Cntr=0.3,0.1

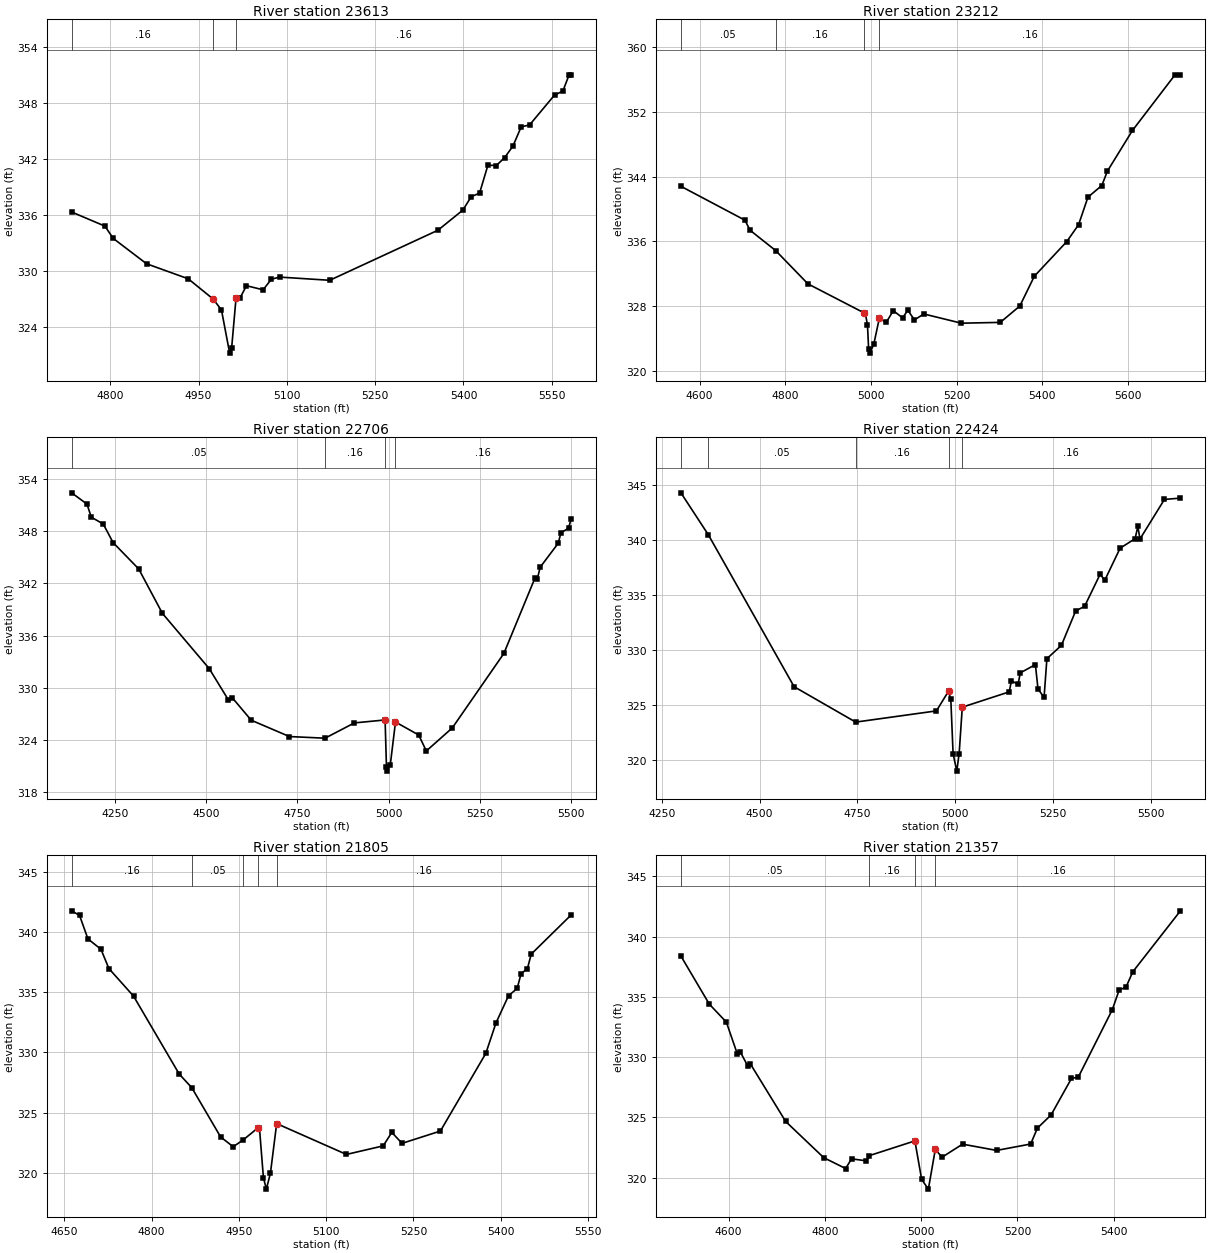
Type RM Length L Ch R = 1 ,23613   ,401,401,401
BEGIN DESCRIPTION:
GREENBRIAR CREEK 35.0
END DESCRIPTION:
XS GIS Cut Line= 3
      3572549.59     10685510.17      3572349.61     10685310.19
      3571949.61     10684910.19
#Sta/Elev= 30
  4734.4  336.28  4790.9  334.77  4805.1  333.45  4861.6  330.74  4932.4  329.13
  4974.8  326.96  4988.9  325.79  5002.8  321.17  5006.1  321.67  5013.7  327.11
  5020.7  327.11  5031.4  328.39  5059.6  327.95  5073.8  329.09  5087.9  329.31
  5172.8  328.97  5356.6  334.33    5399  336.49  5413.2  337.93  5427.3   338.3
  5441.5   341.3  5455.6  341.25  5469.8   342.1  5483.9  343.33    5498   345.4
  5512.2   345.6  5554.6   348.8  5568.8  349.23  5579.4  350.97  5582.9  350.97
#Mann= 3 , 0 , 0
  4734.4     .16       0  4974.8     .12       0  5013.7     .16       0
Bank Sta=4974.8,5013.7
XS Rating Curve= 0 ,0
Exp/Cntr=0.3,0.1

Type RM Length L Ch R = 1 ,23212   ,506,506,506
BEGIN DESCRIPTION:
GREENBRIAR CREEK 34.0
END DESCRIPTION:
XS GIS Cut Line= 3
      3572799.62     10685560.21      3572649.61     10685160.19
      3572299.59     10684510.15
#Sta/Elev= 30
  4556.6  342.82  4706.1  338.63  4717.7   337.4  4777.6  334.88    4853  330.76
  4983.8  327.18  4986.7  327.18  4991.9  325.66  4994.6   322.7  4997.4   322.2
  5006.5  323.27  5019.5   326.5  5035.7  325.99    5052  327.45  5073.9  326.56
    5086   327.5  5101.5  326.31  5123.4  327.04    5211   325.9  5301.8     326
  5347.3  328.02  5381.3  331.71  5456.8  335.98  5484.4  338.07  5506.3  341.48
  5538.7  342.92  5551.7   344.7  5610.1  349.72  5708.3  356.52  5722.1   356.6
#Mann= 4 ,-1 , 0
  4556.6     .05       0  4777.6     .16       0  4983.8     .12       0
  5019.5     .16       0
Bank Sta=4983.8,5019.5
XS Rating Curve= 0 ,0
Exp/Cntr=0.3,0.1

Type RM Length L Ch R = 1 ,22706   ,282,282,282
BEGIN DESCRIPTION:
GREENBRIAR CREEK 33.0
END DESCRIPTION:
XS GIS Cut Line= 3
      3573699.62     10685060.19      3572899.61     10684810.19
      3572499.59     10684460.17
#Sta/Elev= 30
  4130.9  352.43  4172.8  351.14  4184.9  349.62  4217.4  348.85  4244.6   346.7
  4314.8  343.67  4379.7  338.56  4508.1   332.2  4560.5  328.61  4570.9  328.87
  4623.3  326.26  4728.1  324.38  4825.6  324.19  4906.2  325.95  4990.4  326.29
  4994.1   320.9  4996.8   320.4  5004.7  321.16  5018.9  326.05  5082.5  324.56
  5103.4  322.72  5174.6  325.37    5316  333.94  5401.4  342.63    5408  342.55
  5415.6  343.87    5465  346.62  5472.6  347.84  5493.5  348.36  5500.6  349.46
#Mann= 4 ,-1 , 0
  4130.9     .05       0  4825.6     .16       0  4990.4     .12       0
  5018.9     .16       0
Bank Sta=4990.4,5018.9
XS Rating Curve= 0 ,0
Exp/Cntr=0.3,0.1

Type RM Length L Ch R = 1 ,22424   ,619,619,619
BEGIN DESCRIPTION:
GREENBRIAR CREEK 32.0
END DESCRIPTION:
XS GIS Cut Line= 3
      3573613.34       10684925.      3572957.06     10684523.94
       3572738.3     10684065.59
#Sta/Elev= 30
  4298.8  344.31    4369  340.49  4588.2  326.67  4745.6  323.45    4952  324.47
  4982.9  326.26  4988.8  325.51  4994.6  320.58    5004  318.99  5010.1  320.59
  5018.1  324.81  5138.1   326.2  5143.7  327.21  5160.7  326.89  5166.4  327.93
    5205  328.68  5211.7  326.46  5227.2   325.7  5234.4  329.22  5271.5  330.43
    5308  333.57  5330.7  333.98  5370.6  336.91  5382.3  336.35  5421.5  339.27
  5459.9  340.14  5466.9  341.25  5472.4  340.11  5534.9  343.71  5575.8  343.83
#Mann= 5 ,-1 , 0
  4298.8     .16       0    4369     .05       0  4745.6     .16       0
  4982.9     .12       0  5018.1     .16       0
Bank Sta=4982.9,5018.1
XS Rating Curve= 0 ,0
Exp/Cntr=0.3,0.1

Type RM Length L Ch R = 1 ,21805   ,448,448,448
BEGIN DESCRIPTION:
GREENBRIAR CREEK 31.0
END DESCRIPTION:
XS GIS Cut Line= 3
      3573699.59     10684510.17      3573449.61     10684310.19
      3572949.66     10684110.21
#Sta/Elev= 30
  4662.5  341.74  4676.1  341.36  4690.5  339.41  4712.9  338.55  4726.5  336.95
  4768.9  334.66  4847.4  328.19    4869  327.06  4918.6  322.97  4940.2  322.16
  4957.5  322.73  4982.6  323.72  4985.3  323.72  4992.1   319.6  4997.2  318.64
  5004.2  319.97  5014.9  324.08  5134.8  321.52    5198  322.23  5212.8  323.35
  5230.4  322.44  5296.3  323.46  5374.4  329.91  5391.9  332.44  5413.4  334.69
  5428.3   335.3    5435  336.53  5445.8  336.93  5452.5  338.15  5521.1   341.4
#Mann= 5 ,-1 , 0
  4662.5     .16       0    4869     .05       0  4957.5     .16       0
  4982.6     .12       0  5014.9     .16       0
Bank Sta=4982.6,5014.9
XS Rating Curve= 0 ,0
Exp/Cntr=0.3,0.1

Type RM Length L Ch R = 1 ,21357   ,423,423,423
BEGIN DESCRIPTION:
GREENBRIAR CREEK 30.0
END DESCRIPTION:
XS GIS Cut Line= 3
      3573799.63     10684310.22      3573549.61     10683910.19
      3573149.62      10683510.2
#Sta/Elev= 30
  4501.1  338.38  4560.1  334.39  4595.5   332.9  4618.5  330.23  4624.4  330.43
  4639.7  329.28  4645.6  329.42  4718.7  324.66  4797.7  321.66  4843.1  320.76
  4855.5  321.56  4886.2   321.4  4892.5  321.83    4987  323.05  5001.1  319.85
    5015  319.05  5029.4  322.34  5043.5   321.7    5086  322.78  5156.7  322.26
  5227.4  322.79  5241.5  324.11  5269.8   325.2  5312.2  328.23  5326.4  328.34
  5397.1  333.94  5411.2  335.56  5425.4   335.8  5439.5  337.07  5538.5  342.13
#Mann= 4 ,-1 , 0
  4501.1     .05       0  4892.5     .16       0    4987     .12       0
  5029.4     .16       0
Bank Sta=4987,5029.4
XS Rating Curve= 0 ,0
Exp/Cntr=0.3,0.1

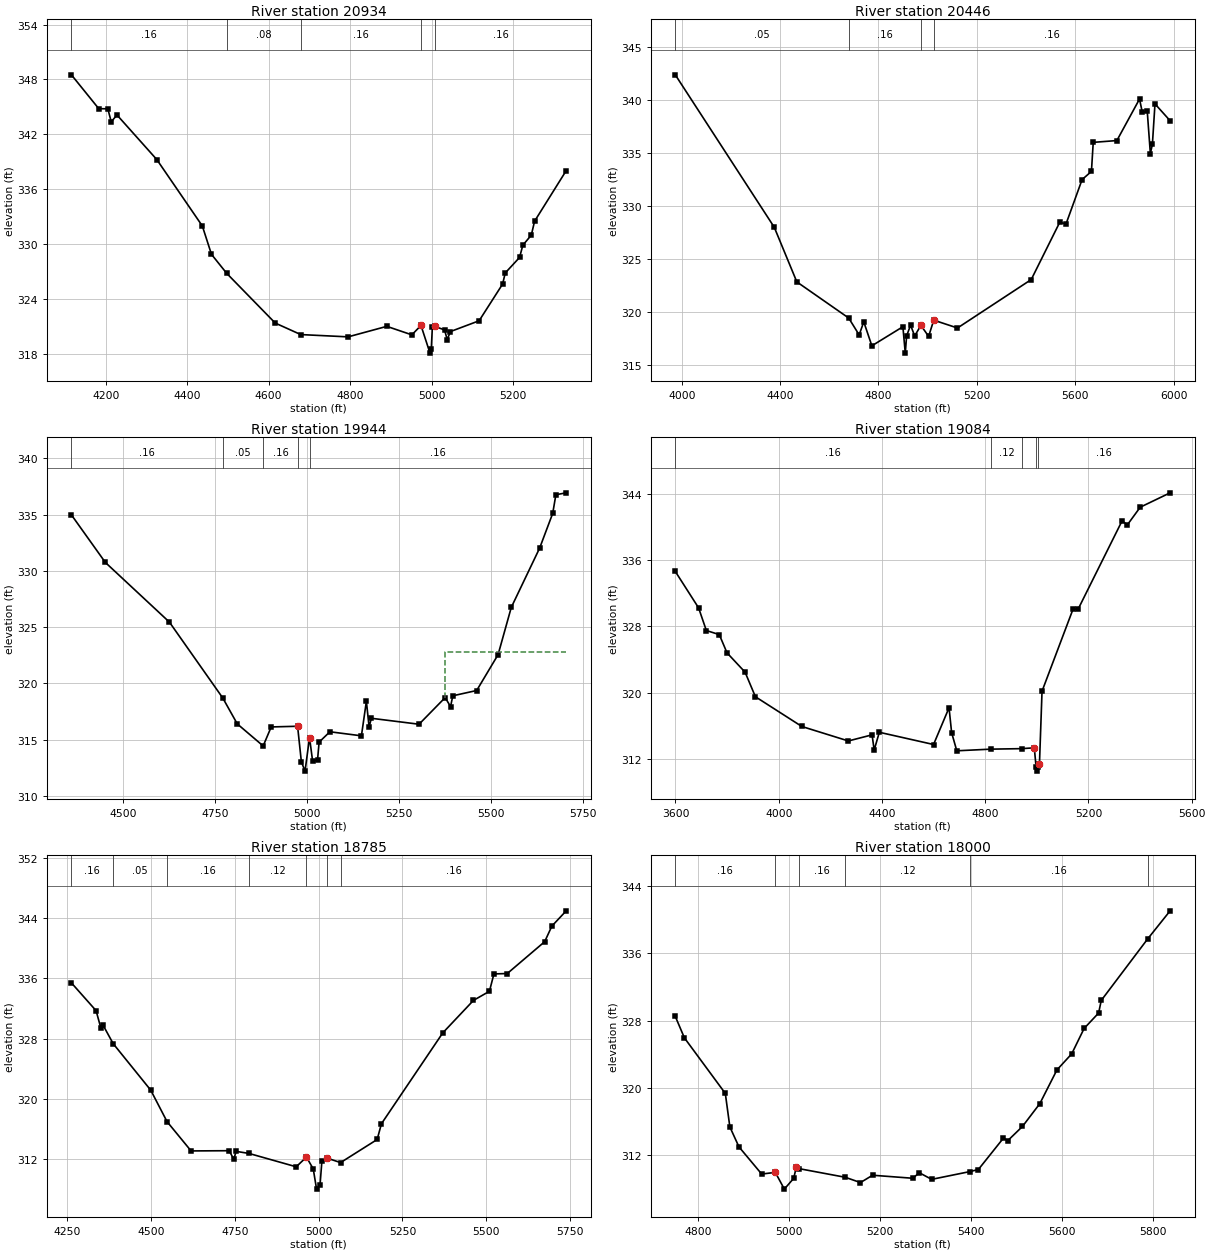
Type RM Length L Ch R = 1 ,20934   ,488,488,488
BEGIN DESCRIPTION:
GREENBRIAR CREEK 29.0
END DESCRIPTION:
XS GIS Cut Line= 3
       3574099.6     10684310.16      3573699.61     10683510.19
      3573499.58     10683260.15
#Sta/Elev= 30
  4115.8  348.51  4182.9  344.81  4205.2  344.79  4213.6  343.37  4227.6  344.12
  4325.4  339.24  4437.2  331.97  4459.6  328.87  4497.2  326.78  4616.1  321.35
  4678.8  320.09    4795  319.84    4890  320.99  4951.5  320.06  4973.9  321.09
    4996  318.06  4999.2  318.56  5001.8  320.87  5007.4  320.99  5031.8   320.6
  5038.2  319.55  5046.2  320.42  5116.6   321.6  5174.3  325.62  5180.7  326.83
  5215.9  328.53  5223.9  329.87  5244.7  330.97  5252.7  332.49  5330.4  338.03
#Mann= 5 ,-1 , 0
  4115.8     .16       0  4497.2     .08       0  4678.8     .16       0
  4973.9     .12       0  5007.4     .16       0
Bank Sta=4973.9,5007.4
XS Rating Curve= 0 ,0
Exp/Cntr=0.3,0.1

Type RM Length L Ch R = 1 ,20446   ,502,502,502
BEGIN DESCRIPTION:
GREENBRIAR CREEK 28.0
END DESCRIPTION:
XS GIS Cut Line= 2
      3574330.42     10684274.94      3573740.15     10682351.36
#Sta/Elev= 30
    3974  342.34  4376.5  327.96  4468.2  322.81  4679.2   319.4  4721.6  317.81
  4740.5  319.04  4773.3  316.78  4899.5  318.58  4909.2  316.09  4914.7  317.72
  4930.8  318.73  4947.4  317.71  4972.7  318.71  5004.1  317.67    5025   319.2
  5121.5  318.46  5421.4  323.03  5537.5  328.44  5562.8  328.27  5628.2  332.46
  5666.2  333.23  5673.5  335.97  5769.6  336.14  5861.8  340.06  5873.1  338.79
  5893.2  338.89  5905.8  334.91  5914.1  335.79  5924.6   339.6  5986.1  338.01
#Mann= 4 ,-1 , 0
    3974     .05       0  4679.2     .16       0  4972.7     .12       0
    5025     .16       0
Bank Sta=4972.7,5025
XS Rating Curve= 0 ,0
Exp/Cntr=0.3,0.1

Type RM Length L Ch R = 1 ,19944   ,860,860,860
BEGIN DESCRIPTION:
GREENBRIAR CREEK 27.0
END DESCRIPTION:
XS GIS Cut Line= 3
      3574549.61     10683810.21      3574399.61     10683160.19
       3573999.6     10682610.17
#Sta/Elev= 30
  4358.2  334.98  4450.6  330.75  4625.1  325.44  4770.4  318.69  4809.8  316.39
  4880.3  314.43  4902.2  316.12    4974  316.18  4984.3  313.02  4994.3  312.19
  5006.5  315.18    5015  313.06  5028.4  313.21  5032.6  314.77    5062  315.69
  5147.8  315.33  5161.3   318.4  5168.7  316.11  5174.8  316.89  5304.7  316.36
  5375.8  318.73  5390.5  317.93  5396.6  318.89  5461.6  319.36  5519.9  322.55
  5555.8  326.75  5633.1  332.03  5668.7  335.12  5677.2  336.77  5705.4  336.94
#Mann= 5 ,-1 , 0
  4358.2     .16       0  4770.4     .05       0  4880.3     .16       0
    4974     .12       0  5006.5     .16       0
#XS Ineff= 2 , 0
                         5376.36           322.8
Permanent Ineff=
       F       F
Bank Sta=4974,5006.5
XS Rating Curve= 0 ,0
Exp/Cntr=0.3,0.1

Type RM Length L Ch R = 1 ,19084   ,299,299,299
BEGIN DESCRIPTION:
GREENBRIAR CREEK 25.0
END DESCRIPTION:
XS GIS Cut Line= 3
      3574612.68      10683820.5       3574584.9     10682653.87
       3574619.6     10681904.53
#Sta/Elev= 30
  3599.4  334.66  3689.7  330.25  3719.7  327.51  3769.8  327.02  3799.8  324.81
  3869.8  322.47  3909.8   319.5  4089.8   315.9  4269.9  314.15  4361.8  314.89
  4369.9  313.05  4389.9   315.2    4600  313.72    4660  318.17    4670  315.16
    4690  312.96    4823  313.16  4941.5  313.22  4990.3  313.32  4997.3     311
    5000   310.5  5003.3     311  5010.3  311.35  5020.3  320.17  5140.4   330.1
  5160.5  330.12  5330.6  340.79  5350.7  340.29  5400.7  342.43  5516.5  344.17
#Mann= 5 ,-1 , 0
  3599.4     .16       0    4823     .12       0  4941.5     .16       0
  4997.3     .07       0  5003.3     .16       0
Bank Sta=4990.3,5010.3
XS Rating Curve= 0 ,0
Exp/Cntr=0.3,0.1

Type RM Length L Ch R = 1 ,18785   ,785,785,785
BEGIN DESCRIPTION:
GREENBRIAR CREEK 24.0
END DESCRIPTION:
XS GIS Cut Line= 3
      3575314.08      10683049.7      3574869.63     10682556.64
       3574723.8     10681758.06
#Sta/Elev= 30
  4262.7   335.4  4336.3   331.7  4350.5  329.39  4357.3  329.76  4387.2  327.32
  4499.3  321.13    4548  316.94  4619.6  313.05  4733.2  313.08  4746.7  311.96
  4754.1  312.99  4791.9  312.72  4933.1  310.94  4963.6  312.23  4983.9  310.66
  4993.8  307.97  5004.2  308.56  5009.7   311.7  5024.6   312.1  5065.4   311.5
  5174.5  314.57  5187.2  316.66  5370.2  328.75  5461.7  333.07  5509.3  334.28
  5522.7  336.59  5562.5  336.64  5674.1  340.88  5695.5  342.95  5738.3  344.98
#Mann= 7 ,-1 , 0
  4262.7     .16       0  4387.2     .05       0    4548     .16       0
  4791.9     .12       0  4963.6     .12       0  5024.6     .12       0
  5065.4     .16       0
Bank Sta=4963.6,5024.6
XS Rating Curve= 0 ,0
Exp/Cntr=0.3,0.1

Type RM Length L Ch R = 1 ,18000   ,454,454,454
BEGIN DESCRIPTION:
GREENBRIAR CREEK 23.0
END DESCRIPTION:
XS GIS Cut Line= 3
      3575399.61      10682760.2      3575399.61     10682510.19
       3575149.6     10681710.16
#Sta/Elev= 30
  4750.2  328.51  4770.2  325.96  4860.2  319.36  4870.2  315.38  4890.2  313.01
  4940.2  309.78  4970.2  309.98    4990  307.99  5010.7  309.28  5016.5  310.67
  5021.7  310.43  5123.8   309.4  5157.4  308.77  5184.1  309.64  5272.6  309.28
  5286.8  309.94    5314  309.15  5398.6  310.08  5416.7  310.32  5471.7  314.04
  5481.6  313.76  5513.6  315.43  5551.8  318.14  5589.5  322.15    5622  324.06
  5649.3  327.08  5681.2  328.91    5687  330.41    5789  337.71  5838.4  341.05
#Mann= 6 ,-1 , 0
  4750.2     .16       0  4970.2     .12       0  5021.7     .16       0
  5123.8     .12       0  5398.6     .16       0    5789      .1       0
Bank Sta=4970.2,5016.5
XS Rating Curve= 0 ,0
Exp/Cntr=0.3,0.1

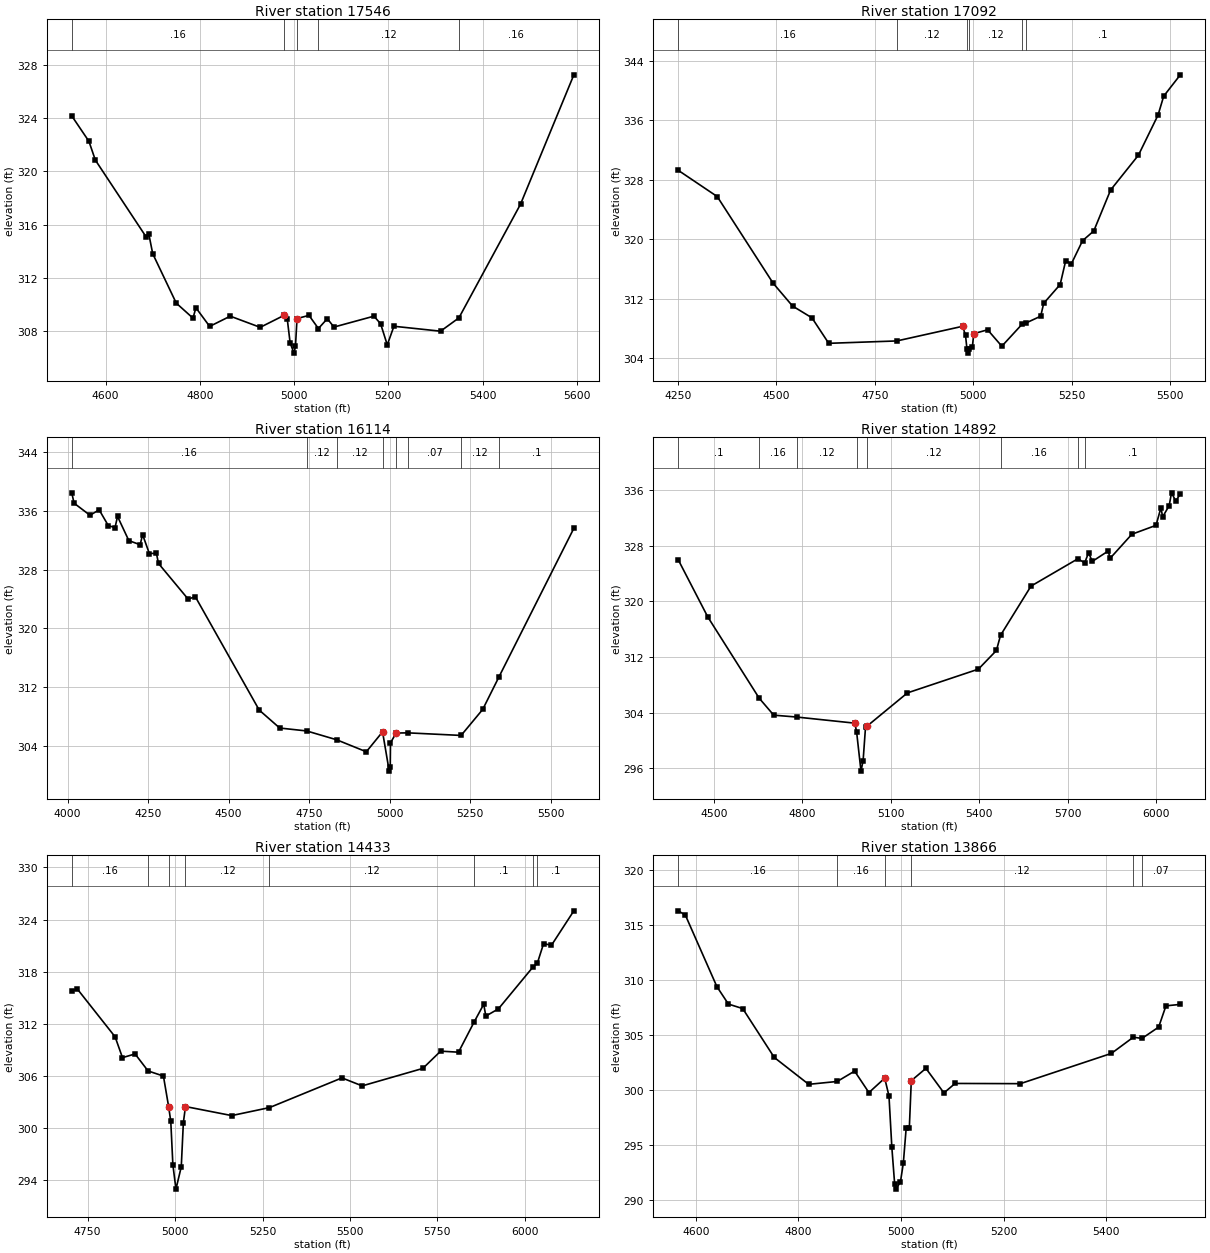
Type RM Length L Ch R = 1 ,17546   ,454,454,454
BEGIN DESCRIPTION:
GREENBRIAR CREEK 22.0
END DESCRIPTION:
XS GIS Cut Line= 3
      3575949.59     10682660.16      3575649.61     10682260.19
      3575249.58     10681860.16
#Sta/Elev= 30
  4528.1  324.17  4564.5  322.26  4578.1  320.85  4685.4   315.1  4691.6  315.29
  4699.9  313.81  4749.9  310.09  4785.4  308.96  4791.6  309.74  4820.8  308.34
  4864.5  309.11  4928.1  308.27  4978.1  309.16  4985.4  308.92  4991.6   307.1
  4999.7  306.33  5002.9  306.83  5006.2  308.93  5031.6  309.17  5051.6  308.18
  5070.5  308.92  5084.6  308.29  5169.5  309.11  5183.6  308.54  5197.8  306.95
  5211.9  308.35  5310.9  307.98  5349.8  308.98  5480.6  317.53  5593.8  327.26
#Mann= 5 ,-1 , 0
  4528.1     .16       0  4978.1     .12       0  5006.2     .16       0
  5051.6     .12       0  5349.8     .16       0
Bank Sta=4978.1,5006.2
XS Rating Curve= 0 ,0
Exp/Cntr=0.3,0.1

Type RM Length L Ch R = 1 ,17092   ,978,978,978
BEGIN DESCRIPTION:
GREENBRIAR CREEK 21.0
END DESCRIPTION:
XS GIS Cut Line= 3
       3576349.6     10682410.18      3575799.61     10681910.19
      3575449.61     10681510.19
#Sta/Elev= 30
    4251  329.28    4350  325.75  4491.9  314.09  4541.2  311.02  4590.5  309.43
  4633.1     306    4806  306.32    4973  308.29  4980.4  307.08  4984.2  305.18
  4986.9  304.68  4990.2  305.18  4997.6  305.44  5001.4   307.3  5036.5  307.82
  5072.6  305.61  5125.1  308.63  5132.8  308.71  5171.3  309.65  5178.9  311.38
  5220.7  313.91  5234.9  317.14  5249.1  316.69  5277.6  319.81  5306.1  321.12
  5348.8  326.63  5419.5  331.32  5469.3  336.72  5483.6  339.26  5525.8  342.13
#Mann= 6 ,-1 , 0
    4251     .16       0    4806     .12       0  4984.2     .07       0
  4990.2     .12       0  5125.1     .16       0  5132.8      .1       0
Bank Sta=4973,5001.4
XS Rating Curve= 0 ,0
Exp/Cntr=0.3,0.1

Type RM Length L Ch R = 1 ,16114   ,1222,1222,1222
BEGIN DESCRIPTION:
GREENBRIAR CREEK 19.0
END DESCRIPTION:
XS GIS Cut Line= 3
      3576949.59     10682360.17      3576299.61     10681610.19
      3575899.63     10681210.21
#Sta/Elev= 30
  4013.1  338.48  4020.2  337.07  4069.6  335.42  4098.1  336.16  4126.6     334
  4147.4  333.74  4155.1  335.26  4190.2  331.96  4225.3   331.4  4232.9  332.78
  4253.8   330.2  4275.7  330.23  4282.3  328.84  4374.4  323.97  4396.3  324.32
  4594.8  308.84  4658.4  306.39  4742.3  305.99    4835  304.79  4927.2  303.15
  4977.6  305.87  4998.2  300.51  5001.4  301.01  5002.2  304.37  5019.7  305.71
  5056.9  305.73  5221.3  305.38  5288.4  308.93  5339.2   313.4  5571.2  333.64
#Mann= 8 ,-1 , 0
  4013.1     .16       0  4742.3     .12       0    4835     .12       0
  4977.6      .1       0  5019.7     .12       0  5056.9     .07       0
  5221.3     .12       0  5339.2      .1       0
Bank Sta=4977.6,5019.7
XS Rating Curve= 0 ,0
Exp/Cntr=0.3,0.1

Type RM Length L Ch R = 1 ,14892   ,459,459,459
BEGIN DESCRIPTION:
GREENBRIAR CREEK 18.0
END DESCRIPTION:
XS GIS Cut Line= 3
      3577011.42     10681885.87       3576587.8     10681233.08
        3575763.     10680817.21
#Sta/Elev= 30
  4379.7  325.97    4480  317.75  4654.2  306.08  4703.4  303.65  4781.1  303.38
  4978.3   302.5  4984.3  301.25  4999.2  295.61  5006.4  297.12  5014.6  301.97
  5020.5   302.1  5156.6  306.85  5397.1  310.26  5458.2  312.94  5472.2  315.12
  5575.5  322.19  5734.6  326.12  5757.4  325.52  5770.7     327    5783  325.73
  5837.6  327.24  5843.2  326.16  5917.4  329.64  5999.3  330.92    6016  333.47
  6021.6  332.12  6043.9  333.76  6051.8  335.59  6066.2  334.41  6081.6  335.43
#Mann= 8 ,-1 , 0
  4379.7      .1       0  4654.2     .16       0  4781.1     .12       0
  4984.3      .1       0  5020.5     .12       0  5472.2     .16       0
  5734.6     .16       0  5757.4      .1       0
Bank Sta=4978.3,5020.5
XS Rating Curve= 0 ,0
Exp/Cntr=0.3,0.1

Type RM Length L Ch R = 1 ,14433   ,567,567,567
BEGIN DESCRIPTION:
GREENBRIAR CREEK 16.0
END DESCRIPTION:
XS GIS Cut Line= 2
      3577191.94     10681670.54      3576393.96     10680477.04
#Sta/Elev= 30
  4704.5  315.75  4720.3     316  4828.4  310.49  4849.5  308.09  4885.5  308.52
  4922.7  306.56  4966.6  305.97  4981.6  302.42  4987.6  300.76  4993.6  295.76
  5002.4  292.95  5017.6  295.52  5023.6  300.61  5029.7  302.46  5161.8  301.42
  5269.9  302.34  5477.1  305.76  5534.9  304.84  5708.3  306.85  5759.3  308.84
  5810.4  308.72  5855.2  312.21  5882.5  314.24  5888.5  312.88  5924.5  313.71
  6023.4  318.53  6035.6  318.94  6053.6  321.22  6076.3  321.04  6140.2     325
#Mann= 8 ,-1 , 0
  4704.5     .16       0  4922.7     .12       0  4981.6      .1       0
  5029.7     .12       0  5269.9     .12       0  5855.2      .1       0
  6023.4     .16       0  6035.6      .1       0
Bank Sta=4981.6,5029.7
XS Rating Curve= 0 ,0
Exp/Cntr=0.3,0.1

Type RM Length L Ch R = 1 ,13866   ,519,519,519
BEGIN DESCRIPTION:
GREENBRIAR CREEK 15.0
END DESCRIPTION:
XS GIS Cut Line= 3
       3577399.6     10681360.16      3577199.61     10680960.19
       3576799.6     10680610.18
#Sta/Elev= 30
  4565.7   316.3  4579.6  315.91  4641.1  309.41  4663.5  307.83  4691.4  307.42
  4752.9  302.98    4820  300.54  4875.6   300.8  4909.5  301.74  4937.4  299.79
  4968.2   301.1  4976.5  299.48  4982.1  294.81  4987.5  291.52  4990.3  291.02
  4998.9  291.69  5004.5  293.39  5010.1  296.61  5016.2  296.61    5020  300.87
  5048.5  301.99  5083.6  299.76  5105.4  300.62  5232.6   300.6  5410.1  303.35
  5452.8  304.82  5469.7  304.71  5502.2  305.74  5516.4  307.67  5544.4   307.8
#Mann= 6 ,-1 , 0
  4565.7     .16       0  4875.6     .16       0  4968.2     .12       0
    5020     .12       0  5452.8     .16       0  5469.7     .07       0
Bank Sta=4968.2,5020
XS Rating Curve= 0 ,0
Exp/Cntr=0.3,0.1

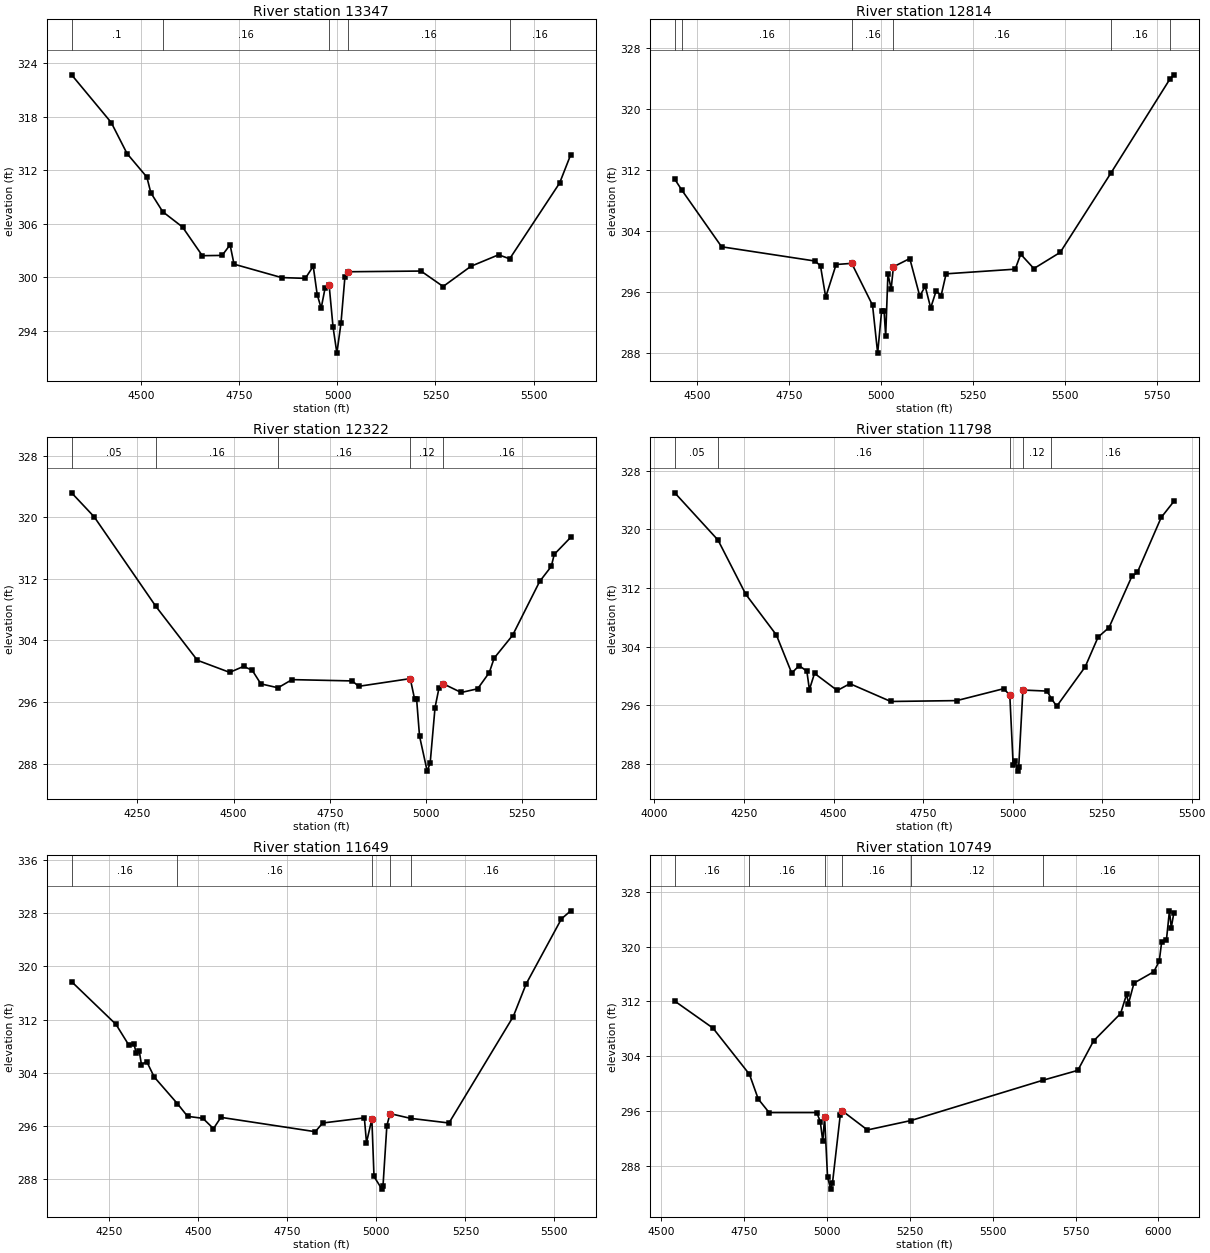
Type RM Length L Ch R = 1 ,13347   ,533,533,533
BEGIN DESCRIPTION:
GREENBRIAR CREEK 14.0
END DESCRIPTION:
XS GIS Cut Line= 3
      3577449.61     10681460.19      3577549.61     10680760.19
       3577149.6     10680360.18
#Sta/Elev= 30
    4322  322.69    4423  317.35  4463.4  313.87  4513.9  311.24    4524  309.48
  4554.4  307.36  4604.8  305.65  4655.3  302.44  4705.9  302.47  4726.1  303.66
  4736.2  301.49  4857.4  299.99    4918   299.9  4938.2  301.26  4948.3  298.09
  4958.4  296.56  4968.5  298.83  4978.6   299.2  4988.7  294.46  4998.5  291.53
  5008.9  294.86    5019  300.06  5026.6  300.64    5213  300.72  5269.5  298.99
  5340.2  301.25  5410.9  302.54  5439.2  302.09  5566.5  310.57  5594.8  313.74
#Mann= 5 ,-1 , 0
    4322      .1       0  4554.4     .16       0  4978.6     .12       0
  5026.6     .16       0  5439.2     .16       0
Bank Sta=4978.6,5026.6
XS Rating Curve= 0 ,0
Exp/Cntr=0.3,0.1

Type RM Length L Ch R = 1 ,12814   ,492,492,492
BEGIN DESCRIPTION:
GREENBRIAR CREEK 13.0
END DESCRIPTION:
XS GIS Cut Line= 3
       3578249.6     10680960.18      3577849.61     10680560.19
      3577199.64     10680110.21
#Sta/Elev= 30
  4439.1  310.78  4458.9  309.31  4566.4  301.93  4820.9  300.06  4835.1  299.41
  4849.2  295.34  4877.5  299.61  4919.9  299.76  4976.5  294.28  4990.4     288
  5001.2  293.54  5007.8  293.54  5012.2  290.24  5018.3  298.39  5027.1  296.41
  5033.2  299.31  5077.7  300.39  5104.8  295.47  5119.6  296.76  5134.5  293.92
  5149.4  296.17  5162.9  295.54  5176.4  298.39  5364.2     299  5379.1  300.96
  5414.9  299.08  5486.5   301.2  5623.7  311.55  5784.1  323.87  5795.3  324.46
#Mann= 6 ,-1 , 0
  4439.1     .05       0  4458.9     .16       0  4919.9     .16       0
  5033.2     .16       0  5623.7     .16       0  5784.1      .1       0
Bank Sta=4919.9,5033.2
XS Rating Curve= 0 ,0
Exp/Cntr=0.3,0.1

Type RM Length L Ch R = 1 ,12322   ,524,524,524
BEGIN DESCRIPTION:
GREENBRIAR CREEK 12.0
END DESCRIPTION:
XS GIS Cut Line= 3
       3578399.6     10681060.17      3577999.61     10680260.19
      3577949.61      10679860.2
#Sta/Elev= 30
    4079  323.16  4137.7  320.04  4297.7  308.44    4406  301.42  4489.9  299.85
  4526.2  300.63  4548.6  300.12  4570.9  298.36  4615.6  297.85    4652  298.91
  4808.5  298.74  4825.3  298.04  4959.4  299.04  4970.6   296.4  4975.9   296.4
  4983.5  291.58  5003.4  287.03  5011.2  288.09  5023.8  295.28  5033.9  297.77
  5043.9   298.4  5091.8  297.24  5134.6  297.72  5164.9  299.83  5177.5   301.7
  5225.3  304.65  5295.9  311.66  5326.1  313.61  5333.7  315.17  5376.5  317.38
#Mann= 5 ,-1 , 0
    4079     .05       0  4297.7     .16       0  4615.6     .16       0
  4959.4     .12       0  5043.9     .16       0
Bank Sta=4959.4,5043.9
XS Rating Curve= 0 ,0
Exp/Cntr=0.3,0.1

Type RM Length L Ch R = 1 ,11798   ,149,149,149
BEGIN DESCRIPTION:
GREENBRIAR CREEK 11.0
END DESCRIPTION:
XS GIS Cut Line= 3
      3578899.61     10680810.18      3578299.61     10680110.19
      3578049.63     10679710.23
#Sta/Elev= 30
  4056.7  324.99  4177.4  318.54  4254.8  311.15  4340.4  305.58  4383.2  300.38
  4404.1   301.4  4425.5  300.63  4432.6  298.12  4446.9  300.34  4510.5     298
  4545.7  298.93  4659.8   296.5  4844.2  296.62  4975.4  298.25  4992.2  297.36
  5001.6  287.82  5007.5  288.31  5013.8  286.99    5017  287.49  5028.8  298.06
    5096  297.92  5108.4   296.9  5123.1  295.84  5202.7  301.23  5238.7  305.29
  5269.3   306.6    5333  313.58  5348.3  314.12    5415  321.63  5450.3  323.82
#Mann= 5 ,-1 , 0
  4056.7     .05       0  4177.4     .16       0  4992.2     .12       0
  5028.8     .12       0  5108.4     .16       0
Bank Sta=4992.2,5028.8
XS Rating Curve= 0 ,0
Exp/Cntr=0.3,0.1

Type RM Length L Ch R = 1 ,11649   ,900,900,900
BEGIN DESCRIPTION:
GREENBRIAR CREEK 10.0
END DESCRIPTION:
XS GIS Cut Line= 3
      3579096.04     10680567.27      3578465.84     10680124.57
      3578116.89     10679598.54
#Sta/Elev= 30
  4144.3   317.7    4269  311.27  4304.7  308.18  4319.5   308.3  4325.6  306.99
  4334.3  307.21  4340.4  305.23  4355.2  305.68  4376.2  303.36  4441.5  299.34
  4469.9  297.44    4513  297.14  4542.6  295.59  4563.5  297.29  4828.4  295.13
  4849.3  296.44  4966.3  297.21  4972.3  293.49  4987.4  297.03  4993.4  288.39
  5015.5  286.49  5018.7  286.99  5029.5  296.04  5038.5  297.85  5095.9  297.14
  5203.9  296.44  5384.4  312.45  5420.5  317.35  5519.7  327.15  5545.7  328.36
#Mann= 5 ,-1 , 0
  4144.3     .16       0  4441.5     .16       0  4987.4     .12       0
  5038.5     .12       0  5095.9     .16       0
Bank Sta=4987.4,5038.5
XS Rating Curve= 0 ,0
Exp/Cntr=0.3,0.1

Type RM Length L Ch R = 1 ,10749   ,505,505,505
BEGIN DESCRIPTION:
GREENBRIAR CREEK 9.0
END DESCRIPTION:
XS GIS Cut Line= 3
      3579148.14     10680395.44      3579054.38     10680088.11
      3578590.86     10678999.61
#Sta/Elev= 30
  4541.9  312.04    4657   308.1    4767  301.34  4793.5  297.73  4826.3  295.75
  4969.9  295.75  4980.5  294.42  4988.1  291.54  4993.5  295.09  5002.3  286.39
  5011.5  284.56  5017.2  285.42  5040.8  295.44  5046.2  296.02  5122.6  293.21
  5253.3  294.58  5650.4  300.46  5756.8  301.92  5804.1  306.21  5885.8  310.23
    5904  313.07  5909.5  311.67  5926.1  314.68  5985.8  316.33  6002.2  317.88
  6009.4  320.62  6023.9  320.97    6033  325.24  6038.5  322.78  6046.3  324.95
#Mann= 6 ,-1 , 0
  4541.9     .16       0    4767     .16       0  4993.5     .12       0
  5046.2     .16       0  5253.3     .12       0  5650.4     .16       0
Bank Sta=4993.5,5046.2
XS Rating Curve= 0 ,0
Exp/Cntr=0.3,0.1