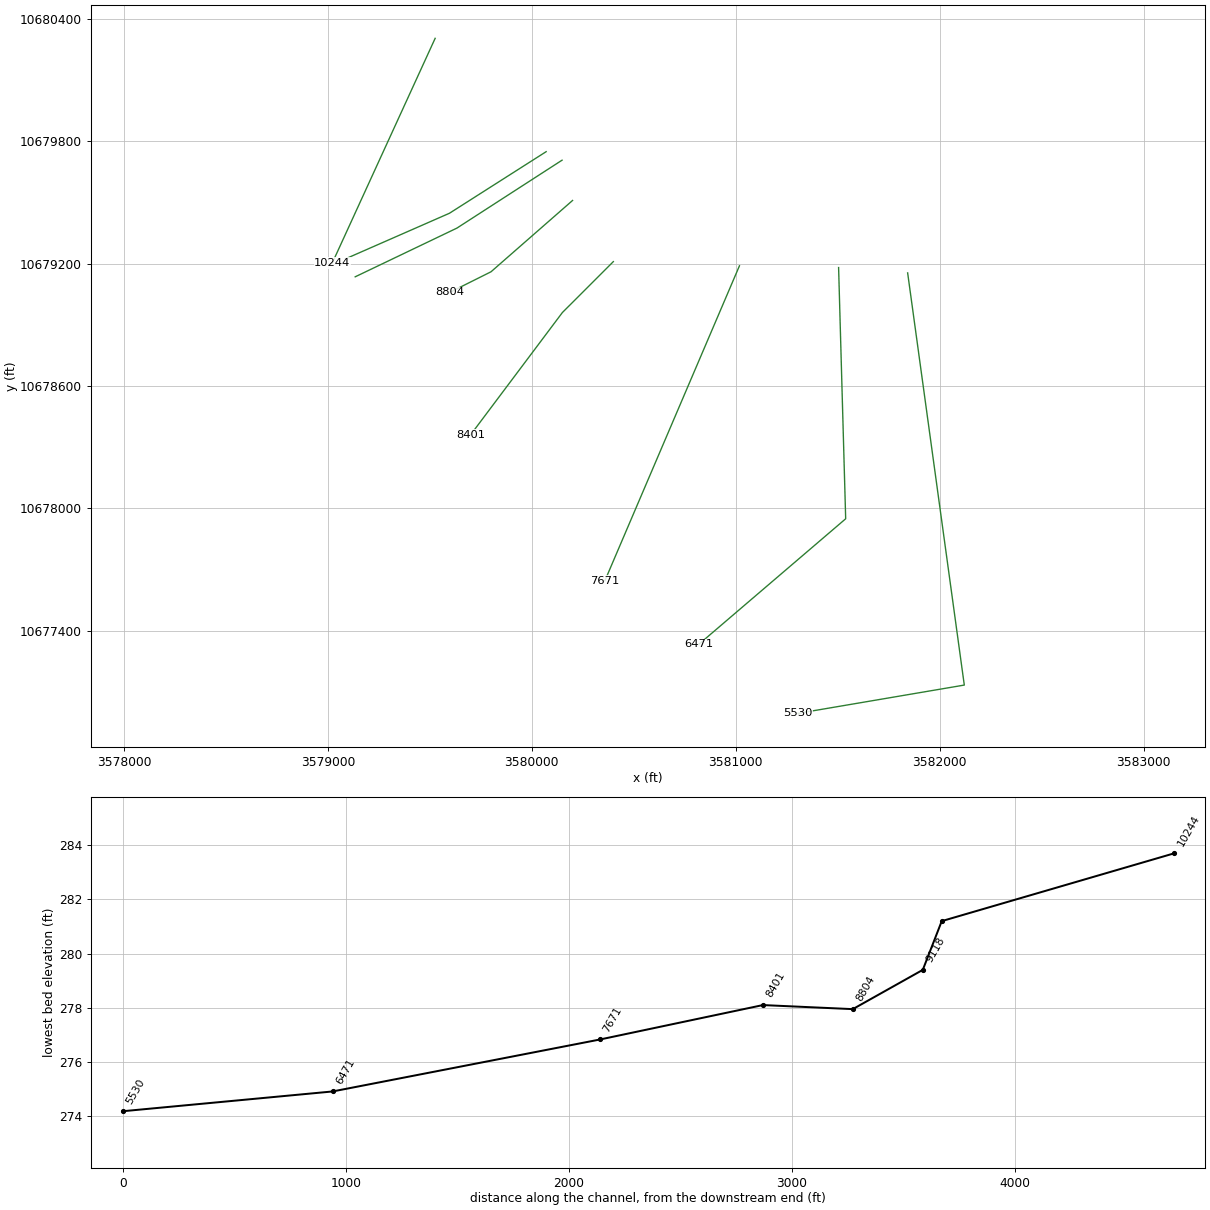
HEC-RAS study GREENBRIAR CREEK.prj: GREENBRIAR CREEK Base Level Engineering

--- GREENBRIAR CREEK.g01 (geometry) --- (continued)

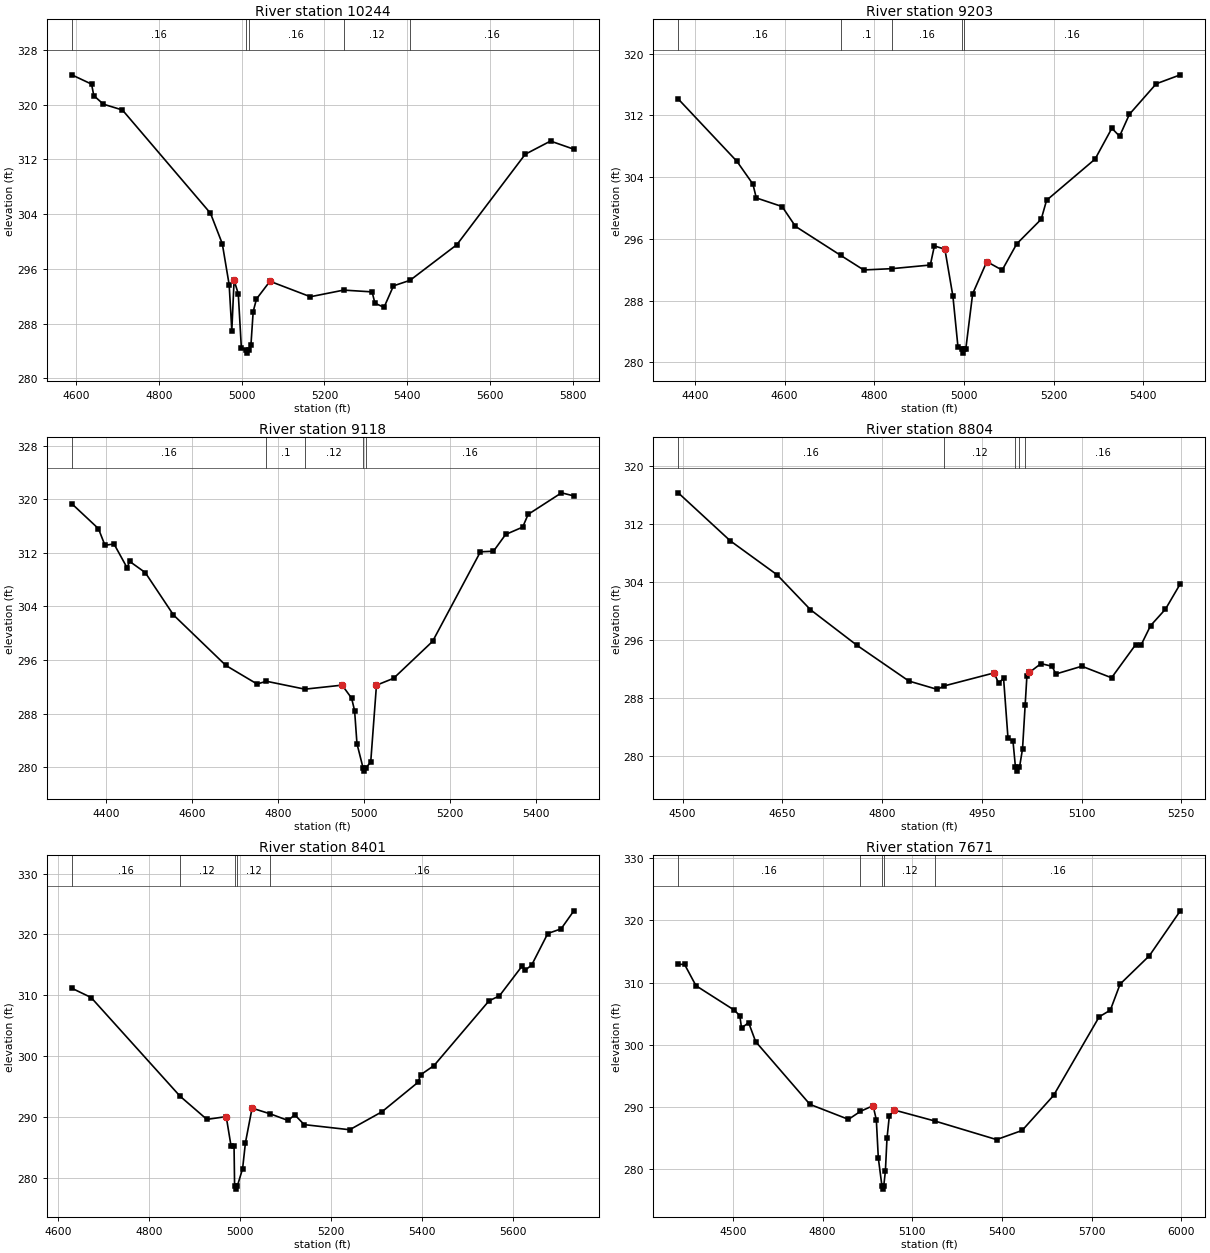
Type RM Length L Ch R = 1 ,10244   ,1041,1041,1041
BEGIN DESCRIPTION:
GREENBRIAR CREEK 8.0
END DESCRIPTION:
XS GIS Cut Line= 2
       3579525.8     10680305.72      3579021.45     10679203.42
#Sta/Elev= 30
  4590.1  324.37  4637.9  323.01  4643.3  321.33  4666.4  320.08  4712.4  319.23
    4925  304.14  4953.5  299.69  4970.1   293.7  4976.5  286.99    4982  294.34
  4992.1  292.38  4999.6  284.41  5011.1   284.2  5013.8   283.7  5017.1   284.2
  5022.6  284.83  5028.1  289.77  5036.1  291.62  5068.6   294.2  5166.2  291.94
  5246.6  292.91  5315.2  292.65    5322     291    5344  290.39  5366.8  293.53
  5406.8  294.34  5519.9  299.55  5684.9  312.76    5746  314.69  5802.3   313.5
#Mann= 5 ,-1 , 0
  4590.1     .16       0  5011.1     .07       0  5017.1     .16       0
  5246.6     .12       0  5406.8     .16       0
Bank Sta=4982,5068.6
XS Rating Curve= 0 ,0
Exp/Cntr=0.3,0.1

Type RM Length L Ch R = 1 ,9203    ,85,85,85
BEGIN DESCRIPTION:
GREENBRIAR CREEK 7.0
END DESCRIPTION:
XS GIS Cut Line= 3
        3580070.     10679749.56      3579596.04     10679447.49
      3579085.65     10679223.54
#Sta/Elev= 30
  4362.9  314.11  4493.8  306.03  4529.4  303.09  4536.9   301.3  4594.5  300.18
  4624.2  297.62  4725.1  293.86  4776.4  291.97  4839.6  292.14  4924.9  292.61
    4934  295.08  4957.4  294.66  4975.3  288.57  4986.6  281.99  4994.5   281.7
  4997.2   281.2  5000.5   281.7  5004.1  281.78  5019.3  288.88  5050.9  293.05
  5085.1  291.95  5117.6  295.35  5172.2  298.54  5184.1  300.99  5292.3  306.33
  5329.7  310.32  5346.9  309.29  5368.8  312.13  5428.6  316.08  5482.3  317.24
#Mann= 5 ,-1 , 0
  4362.9     .16       0  4725.1      .1       0  4839.6     .16       0
  4994.5     .07       0  5000.5     .16       0
Bank Sta=4957.4,5050.9
XS Rating Curve= 0 ,0
Exp/Cntr=0.3,0.1

Type RM Length L Ch R = 1 ,9118    ,314,314,314
BEGIN DESCRIPTION:
GREENBRIAR CREEK 6.0
END DESCRIPTION:
XS GIS Cut Line= 3
       3580148.1     10679707.88       3579632.5     10679374.57
      3579133.76     10679135.59
#Sta/Elev= 30
    4321  319.34    4383  315.61  4398.1  313.13  4419.2  313.32  4449.6  309.77
  4455.5  310.72  4491.8  309.05  4557.4  302.72  4679.2  295.18  4751.7  292.41
  4773.4  292.82  4862.9  291.64  4949.3  292.24  4971.4   290.3  4978.4  288.43
  4983.9   283.5    4998   279.9  5000.8   279.4    5004   279.9  5015.8   280.7
  5029.2  292.23    5069  293.26  5159.7  298.78  5270.8  312.15  5301.2  312.24
  5329.4  314.74  5369.1  315.84  5381.7  317.74  5459.3  320.96    5488   320.5
#Mann= 5 ,-1 , 0
    4321     .16       0  4773.4      .1       0  4862.9     .12       0
    4998     .07       0    5004     .16       0
Bank Sta=4949.3,5029.2
XS Rating Curve= 0 ,0
Exp/Cntr=0.3,0.1

Type RM Length L Ch R = 1 ,8804    ,403,403,403
BEGIN DESCRIPTION:
GREENBRIAR CREEK 5.0
END DESCRIPTION:
XS GIS Cut Line= 3
      3580199.62      10679510.2      3579799.61     10679160.19
      3579599.64      10679060.2
#Sta/Elev= 30
  4493.5  316.26  4571.8  309.65  4642.1  304.98  4692.4  300.17  4762.6  295.25
  4840.4  290.35  4883.1   289.2  4893.5  289.68  4968.6  291.47  4975.2  290.08
  4982.8  290.72  4989.4  282.54    4997  282.03  5000.7  278.45  5003.4  277.95
  5006.7  278.45  5011.3  281.01  5015.3  287.11  5017.9  291.08  5021.7  291.54
    5039  292.75  5055.8  292.38  5061.4  291.32  5100.5  292.39  5145.2   290.8
  5181.5  295.37  5189.9  295.37  5203.9  297.98  5226.3  300.25  5248.6  303.74
#Mann= 5 ,-1 , 0
  4493.5     .16       0  4893.5     .12       0  5000.7     .07       0
  5006.7     .12       0  5015.3     .16       0
Bank Sta=4968.6,5021.7
XS Rating Curve= 0 ,0
Exp/Cntr=0.3,0.1

Type RM Length L Ch R = 1 ,8401    ,730,730,730
BEGIN DESCRIPTION:
GREENBRIAR CREEK 4.0
END DESCRIPTION:
XS GIS Cut Line= 3
      3580399.64     10679210.22      3580149.61     10678960.19
      3579699.61     10678360.19
#Sta/Elev= 30
  4630.8  311.15  4673.3  309.62  4868.9  293.38  4927.8  289.57  4970.3  290.03
  4980.9  285.19  4987.5  285.19  4988.7   278.6  4991.4   278.1  4994.7   278.6
  5006.3  281.47  5012.5  285.72  5027.1  291.42  5067.6  290.47  5106.3  289.39
  5120.9  290.33  5141.7  288.71  5241.7  287.87  5312.5  290.82  5391.7  295.66
  5397.9  296.92  5427.1  298.43  5547.9  309.07  5570.9   309.9  5620.9  314.82
  5627.1   314.1  5641.7  314.96  5677.1  320.15  5706.3  320.91  5734.4  323.88
#Mann= 5 ,-1 , 0
  4630.8     .16       0  4868.9     .12       0  4988.7     .07       0
  4994.7     .12       0  5067.6     .16       0
Bank Sta=4970.3,5027.1
XS Rating Curve= 0 ,0
Exp/Cntr=0.3,0.1

Type RM Length L Ch R = 1 ,7671    ,1200,1200,1200
BEGIN DESCRIPTION:
GREENBRIAR CREEK 3.0
END DESCRIPTION:
XS GIS Cut Line= 2
      3581017.92     10679189.68      3580358.35     10677644.89
#Sta/Elev= 30
  4316.9  312.96  4338.1  312.94  4376.2  309.52  4505.1  305.57  4522.9  304.68
  4528.7  302.71  4552.3  303.59  4575.9  300.53  4757.5  290.45  4886.4  288.04
  4926.6  289.33  4968.7  290.24  4979.6  287.98  4986.3  281.82  4998.4  277.33
  5001.1  276.83  5004.4  277.33  5009.9   279.7  5015.3  284.98  5023.1  288.57
  5038.9  289.55  5176.5  287.76  5381.9  284.79  5467.4  286.26  5572.7  291.89
  5725.2  304.52  5762.5  305.59  5795.1  309.77    5893  314.33  5996.6  321.55
#Mann= 5 ,-1 , 0
  4316.9     .16       0  4926.6     .12       0  4998.4     .07       0
  5004.4     .12       0  5176.5     .16       0
Bank Sta=4968.7,5038.9
XS Rating Curve= 0 ,0
Exp/Cntr=0.3,0.1

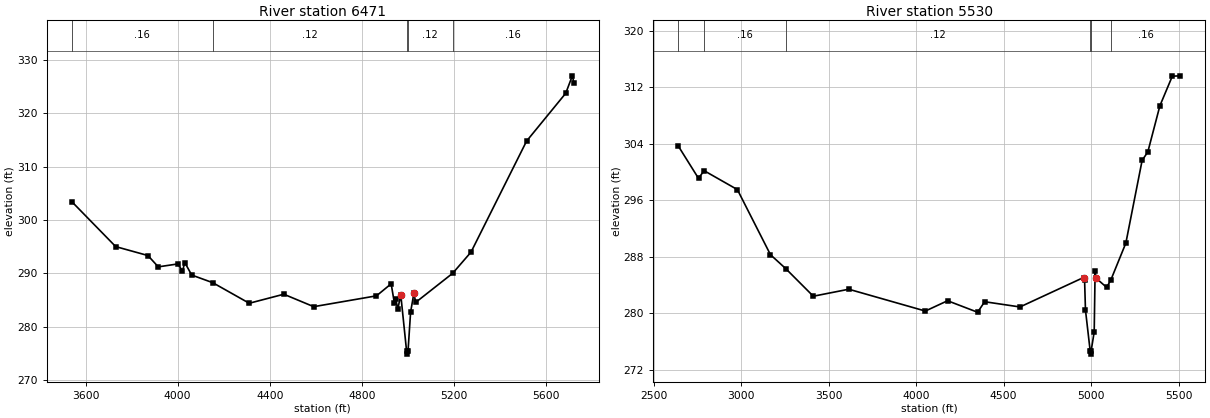
Type RM Length L Ch R = 1 ,6471    ,941,941,941
BEGIN DESCRIPTION:
GREENBRIAR CREEK 2.0
END DESCRIPTION:
XS GIS Cut Line= 3
      3581504.03       10679181.      3581538.75     10677948.35
      3580818.24     10677332.01
#Sta/Elev= 30
  3540.1  303.45    3731  295.03    3871  293.36  3915.9  291.24  4001.1  291.79
  4021.1  290.43  4031.1  292.05  4061.1  289.71  4152.6  288.28  4311.2  284.43
  4461.3  286.12  4591.3  283.79    4864  285.82  4927.7  288.07    4942  284.39
  4948.5  285.14  4956.2  283.28  4969.5     286  4994.9  275.41  4997.7  274.91
  5000.9  275.41  5012.2  282.79  5026.5   286.3  5034.2  284.59    5195  290.04
  5274.6     294  5516.1  314.78  5686.2  323.73  5714.8  326.99  5721.4  325.73
#Mann= 5 ,-1 , 0
  3540.1     .16       0  4152.6     .12       0  4994.9     .07       0
  5000.9     .12       0    5195     .16       0
Bank Sta=4969.5,5026.5
XS Rating Curve= 0 ,0
Exp/Cntr=0.3,0.1

Type RM Length L Ch R = 1 ,5530    ,0,0,0
BEGIN DESCRIPTION:
GREENBRIAR CREEK 1.0
END DESCRIPTION:
XS GIS Cut Line= 3
      3581842.57     10679154.94      3582120.35     10677132.38
      3581304.53     10676993.52
#Sta/Elev= 30
  2640.8  303.66  2756.6  299.07  2788.5  300.16  2978.7  297.48  3167.8  288.26
  3254.6   286.3  3412.7  282.38  3615.4  283.37  4052.9  280.28  4179.9  281.74
  4351.5  280.11  4391.8   281.6  4593.7  280.86    4957  285.03  4962.8  284.74
  4967.9  280.43  4994.6  274.68  4997.3  274.18  5000.6  274.68  5017.8  277.32
    5023  285.95  5028.1  284.95  5088.9  283.63  5112.6  284.66  5198.7  289.91
  5291.7  301.62  5324.2  302.81  5393.2  309.35  5464.2  313.54  5509.9  313.59
#Mann= 6 ,-1 , 0
  2640.8     .05       0  2788.5     .16       0  3254.6     .12       0
  4994.6     .07       0  5000.6     .12       0  5112.6     .16       0
Bank Sta=4957,5028.1
XS Rating Curve= 0 ,0
Exp/Cntr=0.3,0.1

Chan Stop Cuts=-1
Use User Specified Reach Order=0
Composite Channel Slope=5