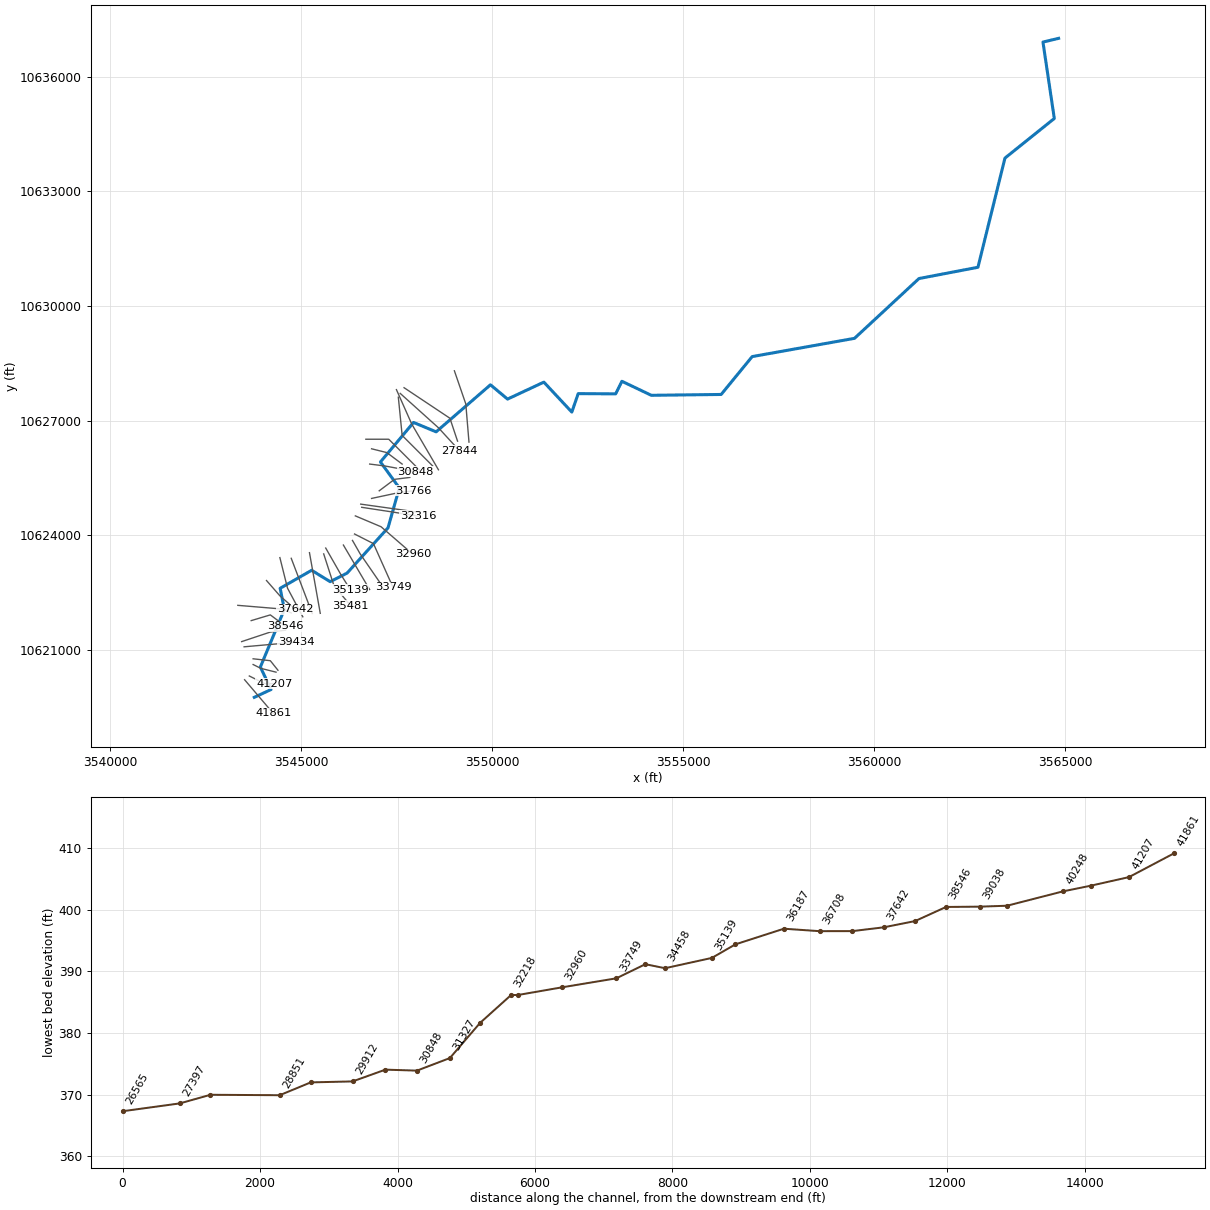
--- GRINDSTONE CREEK.prj (project) ---

Proj Title=GRINDSTONE CREEK Base Level Engineering
Current Plan=p01
Default Exp/Contr=0.3,0.1
English Units
Geom File=g01
Flow File=f01
Plan File=p01
Y Axis Title=Elevation
X Axis Title(PF)=Main Channel Distance
X Axis Title(XS)=Station
BEGIN DESCRIPTION:
GRINDSTONE CREEK
END DESCRIPTION:
DSS Export Rating Curves= 0
DSS Export Rating Curve Sorted= 0
DSS Export Volume Flow Curves= 0
DXF OffsetX= 0
DXF OffsetY= 0
DXF ScaleX= 1
DXF ScaleY= 10

--- GRINDSTONE CREEK.p01 (plan) ---

Plan Title=Multiple Run
Short Identifier=Multiple
Geom File=g01
Flow File=f01
Subcritical Flow
K Sum by GR= 0
Std Step Tol= 0.01
Critical Tol= 0.01
Num of Std Step Trials= 20
Max Error Tol= 0.3
Flow Tol Ratio= 0.001
Split Flow NTrial= 30
Split Flow Tol= 0.02
Split Flow Ratio= 0.02
Log Output Level= 0
Friction Slope Method= 1
Unsteady Friction Slope Method= 2
Unsteady Bridges Friction Slope Method= 1
Parabolic Critical Depth
Global Vel Dist=  1 , 1 , 1
Global Log Level= 0
CheckData=True
Encroach Param= -1, 0, 0, 0
BEGIN DESCRIPTION:
Multiple Run
END DESCRIPTION:

--- GRINDSTONE CREEK.f01 (steady flow) ---

Flow Title=Multiple
Program Version=4.10
Number of Profiles= 7
Profile Names=10-year,25-year,50-year,1pct_min,100-year,1pct_plu,500-year
River Rch & RM=GRINDSTONE CREEK,Reach-1         ,41861
    2235    3166    3957    3605    4875    6593    7379
River Rch & RM=GRINDSTONE CREEK,Reach-1         ,37642
    2787    3986    5013    4590    6207    8394    9496
River Rch & RM=GRINDSTONE CREEK,Reach-1         ,34458
    3273    4702    5932    5444    7362    9956   11315
River Rch & RM=GRINDSTONE CREEK,Reach-1         ,29302
    4270    6201    7879    7276    9840   13307   15317
River Rch & RM=GRINDSTONE CREEK,Reach-1         ,28851
    4270    6201    7879    7276    9840   13307   15317
River Rch & RM=GRINDSTONE CREEK,Reach-1         ,24589
    5071    7423    9483    8801   11902   16097   18714
River Rch & RM=GRINDSTONE CREEK,Reach-1         ,24051
    5426    7955   10173    9450   12780   17283   20127
River Rch & RM=GRINDSTONE CREEK,Reach-1         ,22163
    5426    7955   10173    9450   12780   17283   20127
River Rch & RM=GRINDSTONE CREEK,Reach-1         ,20299
    6321    9297   11915   11086   14993   20276   23688
River Rch & RM=GRINDSTONE CREEK,Reach-1         ,16857
    6321    9297   11915   11086   14993   20276   23688
River Rch & RM=GRINDSTONE CREEK,Reach-1         ,16117
    6876   10117   12967   12061   16311   22059   25752
River Rch & RM=GRINDSTONE CREEK,Reach-1         ,7834
    7166   10546   13520   12576   17008   23001   26853
River Rch & RM=GRINDSTONE CREEK,Reach-1         ,7617
    7452   10954   14031   13036   17630   23843   27774
Boundary for River Rch & Prof#=GRINDSTONE CREEK,Reach-1         , 1
Up Type= 0
Dn Type= 3
Dn Slope=0.003
Boundary for River Rch & Prof#=GRINDSTONE CREEK,Reach-1         , 2
Up Type= 0
Dn Type= 3
Dn Slope=0.003
Boundary for River Rch & Prof#=GRINDSTONE CREEK,Reach-1         , 3
Up Type= 0
Dn Type= 3
Dn Slope=0.003
Boundary for River Rch & Prof#=GRINDSTONE CREEK,Reach-1         , 4
Up Type= 0
Dn Type= 3
Dn Slope=0.003
Boundary for River Rch & Prof#=GRINDSTONE CREEK,Reach-1         , 5
Up Type= 0
Dn Type= 3
Dn Slope=0.003
Boundary for River Rch & Prof#=GRINDSTONE CREEK,Reach-1         , 6
Up Type= 0
Dn Type= 3
Dn Slope=0.003
Boundary for River Rch & Prof#=GRINDSTONE CREEK,Reach-1         , 7
Up Type= 0
Dn Type= 3
Dn Slope=0.003
DSS Import GetInterval= 0
DSS Import GetPeak= 0
DSS Import FillOption= 0

--- GRINDSTONE CREEK.g01 (geometry) ---

Geom Title=Existing Conditions
Program Version=4.10

River Reach=GRINDSTONE CREEK,Reach-1
Reach XY= 30
      3543780.25       10619751.      3544218.25       10619955.
      3543939.25       10620545.      3544566.25       10622051.
      3544457.25       10622607.        3545281.       10623078.
        3545766.       10622780.      3546208.25       10623004.
       3547279.5       10624190.      3547575.75       10625236.
       3547081.5       10625915.      3547947.25       10626950.
        3548539.       10626704.      3549960.75       10627936.
        3550408.       10627562.      3551358.25       10628006.
      3552090.25       10627221.      3552256.75       10627705.
      3553236.75       10627699.        3553401.       10628028.
        3554170.       10627661.      3555998.25       10627683.
        3556810.       10628675.        3559488.       10629153.
        3561175.       10630719.      3562718.25       10631014.
        3563425.       10633873.      3564716.75       10634911.
      3564419.75       10636912.       3564829.5       10637010.

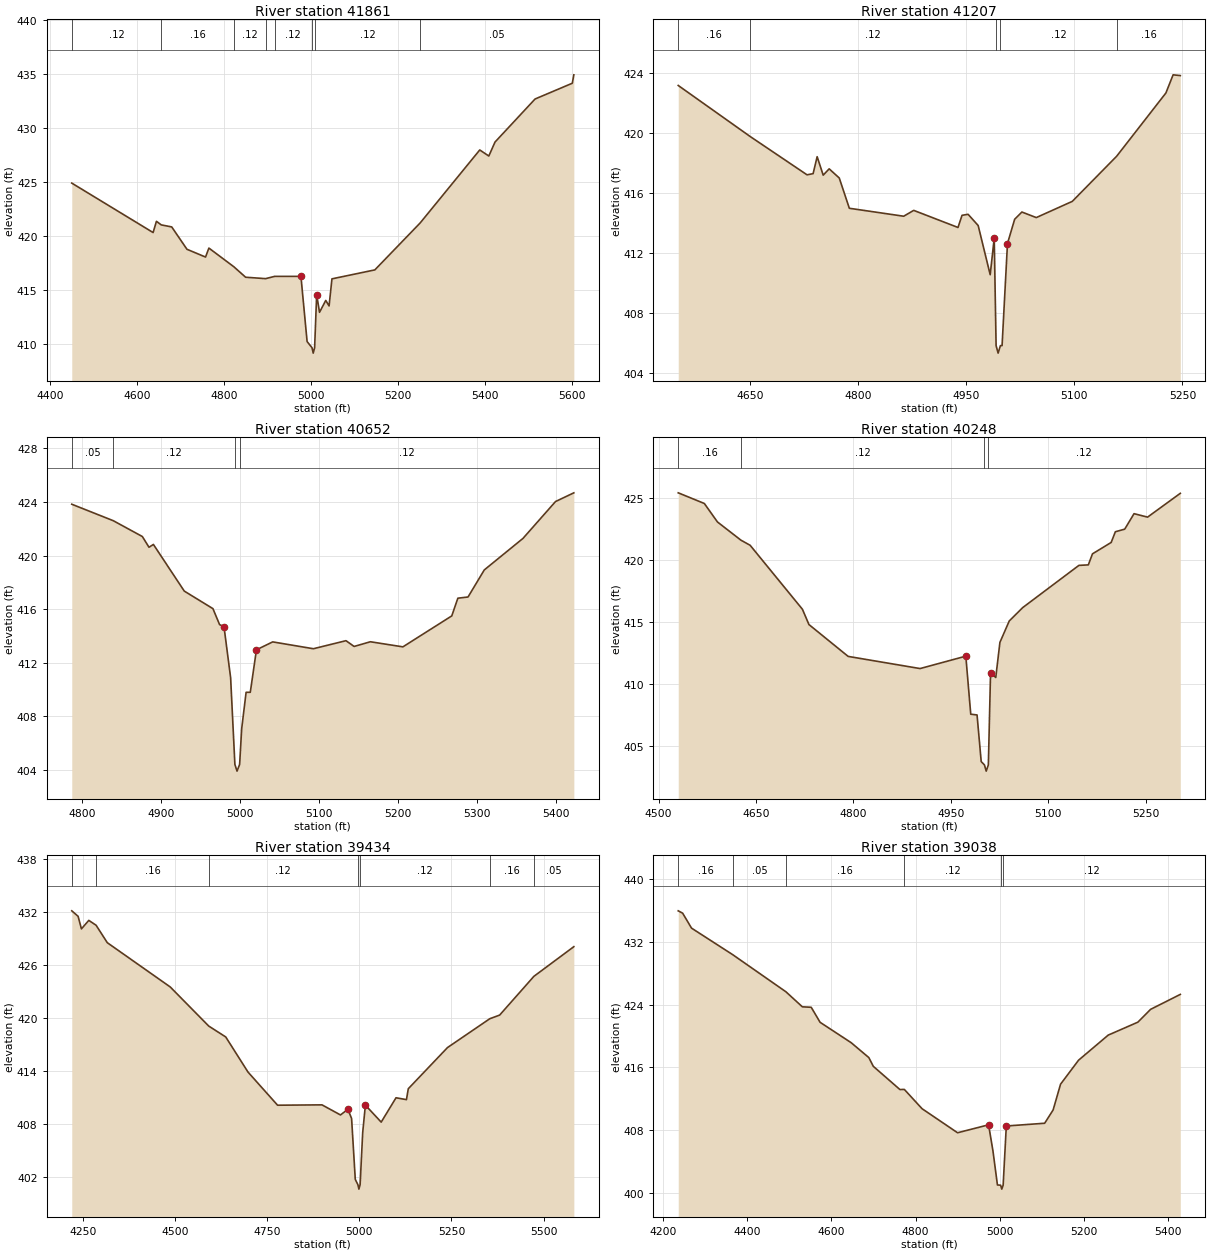
Type RM Length L Ch R = 1 ,41861   ,654,654,654
BEGIN DESCRIPTION:
GRINDSTONE CREEK 67.0
END DESCRIPTION:
XS GIS Cut Line= 2
      3543526.44     10620211.62      3544275.52     10619330.76
#Sta/Elev= 30
    4449  424.91  4636.3  420.33    4644  421.37  4655.1  421.04  4679.2  420.85
  4714.3  418.78  4757.1  418.06  4764.8  418.89  4822.3  417.16  4849.4  416.19
  4895.4  416.06  4916.2  416.27  4976.8  416.27    4991  410.23  5002.3  409.66
  5005.1  409.16  5008.3  409.66    5013  414.57  5019.6  412.94  5033.9  414.04
  5041.6  413.53  5048.2  416.04    5147  416.87  5251.4  421.22  5388.6  427.98
  5409.5  427.42  5423.7  428.71    5516   432.7  5601.7  434.16  5605.3  434.94
#Mann= 8 ,-1 , 0
    4449     .12       0  4655.1     .16       0  4822.3     .12       0
  4895.4     .16       0  4916.2     .12       0  5002.3     .07       0
  5008.3     .12       0  5251.4     .05       0
Bank Sta=4976.8,5013
XS Rating Curve= 0 ,0
Exp/Cntr=0.3,0.1

Type RM Length L Ch R = 1 ,41207   ,555,555,555
BEGIN DESCRIPTION:
GRINDSTONE CREEK 66.0
END DESCRIPTION:
XS GIS Cut Line= 3
      3543649.61     10620310.19      3544049.61     10620110.19
      3544299.59     10620110.19
#Sta/Elev= 30
  4549.9  423.16    4650  419.75  4728.8   417.2  4737.2  417.28  4742.8  418.41
  4751.2  417.18  4759.5   417.6  4773.5  416.99  4787.5  414.97    4863  414.44
  4876.9  414.83  4938.4  413.69    4944   414.5  4952.4  414.57  4966.4  413.82
  4983.1  410.54  4988.7  412.98  4991.3  405.81  4994.1  405.31  4997.3  405.81
  4999.6  405.81  5007.1  412.62  5017.1  414.24  5027.1  414.72  5047.1  414.35
  5097.1  415.43  5158.7  418.44  5227.1  422.66  5237.1  423.87  5247.1  423.82
#Mann= 5 ,-1 , 0
  4549.9     .16       0    4650     .12       0  4991.3     .07       0
  4997.3     .12       0  5158.7     .16       0
Bank Sta=4988.7,5007.1
XS Rating Curve= 0 ,0
Exp/Cntr=0.3,0.1

Type RM Length L Ch R = 1 ,40652   ,404,404,404
BEGIN DESCRIPTION:
GRINDSTONE CREEK 65.0
END DESCRIPTION:
XS GIS Cut Line= 3
      3543749.64     10620610.17      3543949.61     10620510.19
      3544349.63     10620410.18
#Sta/Elev= 30
  4787.1  423.83  4839.7   422.6  4876.5  421.42  4884.9  420.62  4890.5  420.83
  4929.6  417.35  4965.9  416.04  4974.3  414.85  4979.9   414.7  4988.3  410.89
  4993.7  404.42  4996.4  403.92  4999.7  404.42  5002.3  407.08  5007.9   409.8
  5013.2   409.8    5021  412.97  5041.6  413.56  5093.1  413.05  5134.4  413.65
  5144.7  413.22  5165.3  413.57  5206.5  413.19  5268.4   415.5  5276.1  416.82
    5289  416.91  5309.6  418.93  5358.6  421.28  5399.8  424.03    5423  424.68
#Mann= 4 ,-1 , 0
  4787.1     .05       0  4839.7     .12       0  4993.7     .07       0
  4999.7     .12       0
Bank Sta=4979.9,5021
XS Rating Curve= 0 ,0
Exp/Cntr=0.3,0.1

Type RM Length L Ch R = 1 ,40248   ,814,814,814
BEGIN DESCRIPTION:
GRINDSTONE CREEK 64.0
END DESCRIPTION:
XS GIS Cut Line= 3
      3543749.61     10620760.19      3544199.61     10620710.19
       3544399.6     10620460.21
#Sta/Elev= 30
  4530.3  425.44  4570.5  424.58  4590.7  423.09  4626.9  421.62    4641  421.21
  4721.5  416.05  4731.5  414.82  4791.9  412.25  4902.6  411.27    4973  412.27
  4980.6  407.59  4990.3  407.53  4996.7  403.77  5001.7   403.5  5004.4     403
  5007.7   403.5  5011.1  410.95  5019.1  410.55  5025.5  413.38  5039.9  415.11
  5060.7  416.19  5147.1  419.59  5161.6  419.63    5168  420.52  5196.8  421.44
  5203.2   422.3  5217.6  422.51    5232  423.76  5252.8  423.48  5303.2   425.4
#Mann= 4 ,-1 , 0
  4530.3     .16       0  4626.9     .12       0  5001.7     .07       0
  5007.7     .12       0
Bank Sta=4973,5011.1
XS Rating Curve= 0 ,0
Exp/Cntr=0.3,0.1

Type RM Length L Ch R = 1 ,39434   ,396,396,396
BEGIN DESCRIPTION:
GRINDSTONE CREEK 63.0
END DESCRIPTION:
XS GIS Cut Line= 2
      3543513.55     10621074.01      3544870.13     10621195.37
#Sta/Elev= 30
    4220  432.11  4237.2  431.49  4246.2  430.07  4266.2  431.03    4286  430.48
  4316.4  428.51  4487.1  423.51  4591.6  419.09  4637.7  417.86    4698   413.9
  4778.3  410.15  4898.8  410.19    4949  409.05    4969  409.69  4979.1  408.65
  4989.1  401.77  4996.2  401.17  4998.9  400.67  5002.2  401.17  5009.2  407.05
  5016.5  410.16  5059.4  408.24  5099.6  410.99  5127.9  410.78  5132.9  412.01
  5239.2  416.66    5354  419.92  5380.7  420.33  5473.7  424.71    5582  428.06
#Mann= 7 ,-1 , 0
    4220     .05       0    4286     .16       0  4591.6     .12       0
  4996.2     .07       0  5002.2     .12       0    5354     .16       0
  5473.7     .05       0
Bank Sta=4969,5016.5
XS Rating Curve= 0 ,0
Exp/Cntr=0.3,0.1

Type RM Length L Ch R = 1 ,39038   ,492,492,492
BEGIN DESCRIPTION:
GRINDSTONE CREEK 62.0
END DESCRIPTION:
XS GIS Cut Line= 3
      3543449.62     10621210.19      3544199.61     10621460.19
      3544599.64     10621510.19
#Sta/Elev= 30
  4235.7  435.92  4246.2  435.62  4267.3  433.72  4365.3  430.34  4491.8  425.62
  4530.8  423.71  4551.9  423.65    4573  421.74  4646.8  419.15  4688.9  417.25
  4699.5  416.14  4762.7  413.19  4773.3   413.2  4815.4  410.75  4899.8  407.69
  4973.6   408.7  4984.1  405.33  4994.6  401.05  5002.2  401.02  5004.9  400.52
  5008.2  401.02  5015.7  408.55  5106.9   408.9    5127  410.59  5144.7  413.87
  5187.5  416.92    5258  420.11  5328.6  421.76  5358.8  423.39  5429.4  425.29
#Mann= 6 ,-1 , 0
  4235.7     .16       0  4365.3     .05       0  4491.8     .16       0
  4773.3     .12       0  5002.2     .07       0  5008.2     .12       0
Bank Sta=4973.6,5015.7
XS Rating Curve= 0 ,0
Exp/Cntr=0.3,0.1

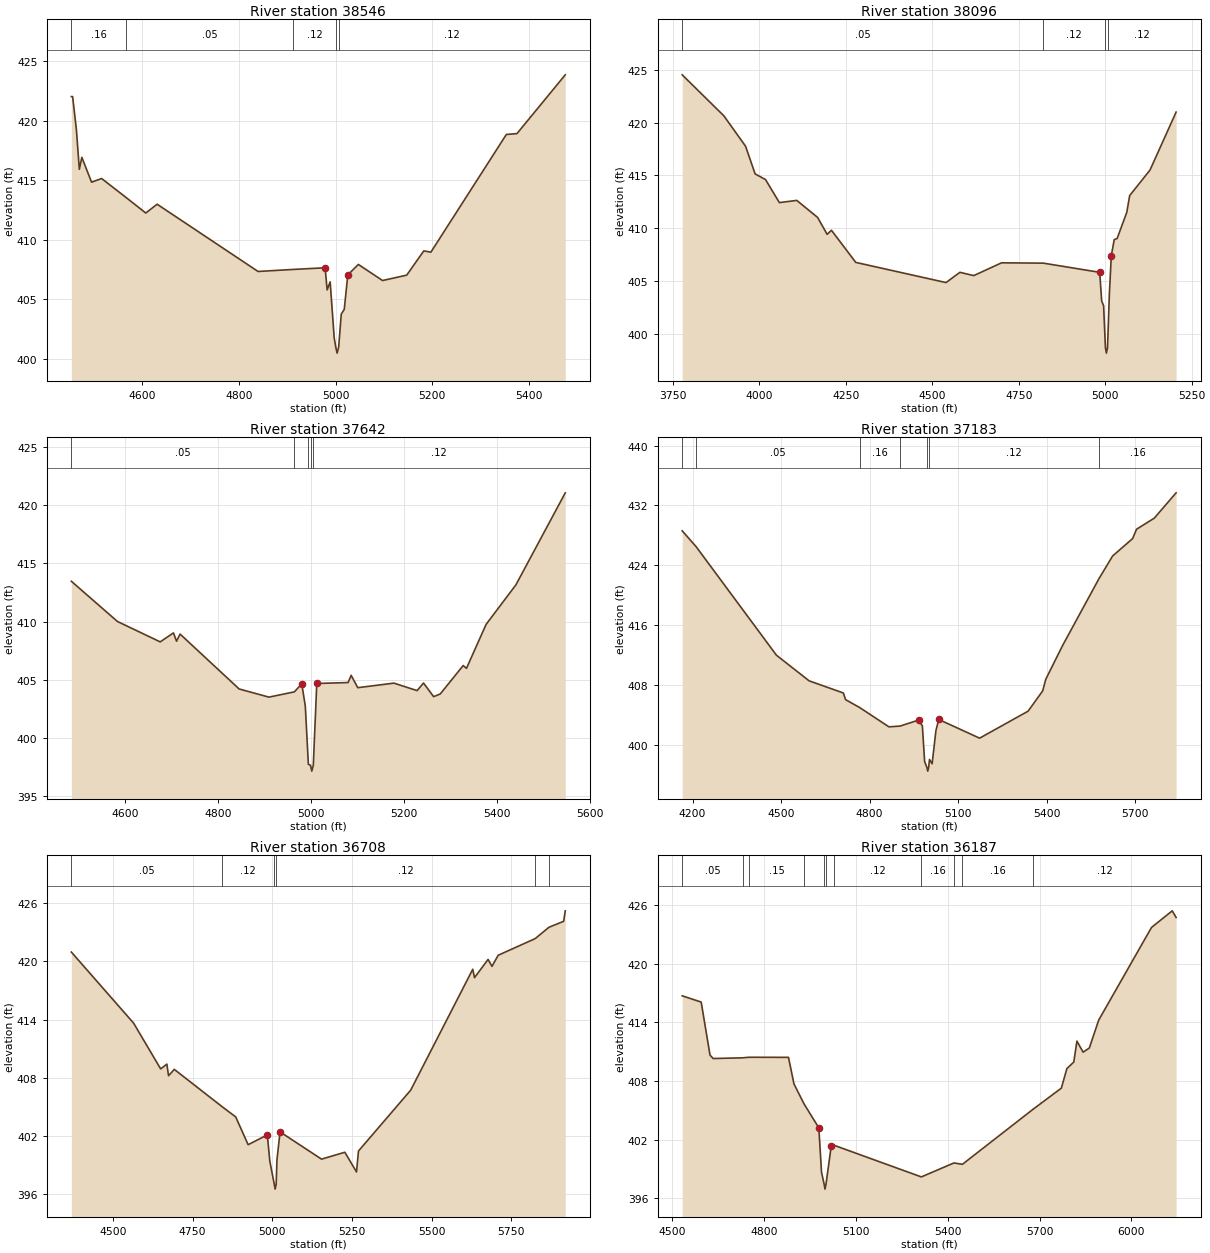
Type RM Length L Ch R = 1 ,38546   ,450,450,450
BEGIN DESCRIPTION:
GRINDSTONE CREEK 61.0
END DESCRIPTION:
XS GIS Cut Line= 3
      3543699.62     10621760.19      3544199.61     10621910.19
       3544599.6     10621610.19
#Sta/Elev= 30
  4453.4  422.02    4456  422.02  4463.8  419.26  4469.9  415.91  4475.1  416.92
  4495.2  414.83    4516  415.14  4567.4  413.52  4607.4  412.24  4630.9  412.98
  4839.7  407.33    4912   407.5  4978.5  407.64  4982.7  405.78  4988.9  406.46
  4997.3  401.75  5000.5  400.97  5003.3  400.47  5006.5  400.97  5011.9  403.75
  5018.1  404.15  5025.4  407.04  5047.3  407.92  5097.3  406.57  5147.3  407.02
  5182.7  409.06  5197.3  408.95  5353.5  418.84  5375.4  418.91  5475.4  423.85
#Mann= 5 ,-1 , 0
  4453.4     .16       0  4567.4     .05       0    4912     .12       0
  5000.5     .07       0  5006.5     .12       0
Bank Sta=4978.5,5025.4
XS Rating Curve= 0 ,0
Exp/Cntr=0.3,0.1

Type RM Length L Ch R = 1 ,38096   ,454,454,454
BEGIN DESCRIPTION:
GRINDSTONE CREEK 60.0
END DESCRIPTION:
XS GIS Cut Line= 3
      3543349.58     10622160.19      3544549.61     10622060.19
      3544749.61     10621960.19
#Sta/Elev= 30
  3777.1  424.53  3897.5  420.65  3960.3  417.77  3987.9  415.15    4018  414.61
  4058.1  412.43  4108.3  412.64  4168.5  411.03  4196.1  409.43  4208.6  409.81
  4278.9  406.77  4539.8  404.86  4579.9  405.83    4620  405.52  4700.3  406.73
    4821   406.7  4984.1  405.83  4989.7  403.13  4995.3  402.66  5000.6  398.68
  5003.4  398.18  5006.6  398.68    5012   403.8  5017.6  407.42    5026  408.93
  5034.4  409.03  5062.3  411.51  5070.7   413.1  5129.4  415.51  5204.9     421
#Mann= 4 ,-1 , 0
  3777.1     .05       0    4821     .12       0  5000.6     .07       0
  5006.6     .12       0
Bank Sta=4984.1,5017.6
XS Rating Curve= 0 ,0
Exp/Cntr=0.3,0.1

Type RM Length L Ch R = 1 ,37642   ,459,459,459
BEGIN DESCRIPTION:
GRINDSTONE CREEK 59.0
END DESCRIPTION:
XS GIS Cut Line= 3
      3544099.61     10622810.18      3544449.61     10622410.19
       3544849.6     10622060.19
#Sta/Elev= 30
  4484.7  413.46  4583.9  410.01  4675.9  408.26  4704.4  409.03  4711.1  408.32
  4718.7  408.93  4845.8  404.22  4909.9  403.52  4964.6  403.97  4980.6  404.66
  4988.2  402.75  4993.1  399.05  4994.8  397.76  4999.4  397.67  5002.2  397.17
  5005.4  397.67  5012.9  404.69  5080.3  404.77  5086.9  405.39  5101.1  404.33
    5179  404.72  5228.8  404.08  5242.6  404.73  5264.4  403.56  5278.6  403.79
    5328  406.23  5335.1  405.99  5377.3  409.76  5441.4  413.15  5547.7  421.05
#Mann= 5 ,-1 , 0
  4484.7     .05       0  4964.6     .16       0  4993.1     .12       0
  4999.4     .07       0  5005.4     .12       0
Bank Sta=4980.6,5012.9
XS Rating Curve= 0 ,0
Exp/Cntr=0.3,0.1

Type RM Length L Ch R = 1 ,37183   ,475,475,475
BEGIN DESCRIPTION:
GRINDSTONE CREEK 58.0
END DESCRIPTION:
XS GIS Cut Line= 3
      3544449.61     10623410.16      3544649.61     10622610.19
      3545049.61     10621860.19
#Sta/Elev= 30
  4164.7  428.62  4212.2  426.49  4484.2  412.02    4595   408.6    4711  406.98
  4718.7  406.09  4766.6  405.03  4865.6  402.46  4903.4  402.56  4966.1  403.36
    4979  402.58  4986.7  397.82  4994.4  397.05  4997.2  396.55  5000.4  397.05
  5003.1  398.11    5012  397.53  5025.1  401.99  5034.6  403.44  5173.1  400.95
  5337.4  404.55    5387  407.26  5397.3   408.8    5454  413.28    5577  422.18
    5624  425.26    5692  427.59  5705.1  428.83  5765.3  430.31  5839.3  433.69
#Mann= 7 ,-1 , 0
  4164.7     .16       0  4212.2     .05       0  4766.6     .16       0
  4903.4     .12       0  4994.4     .07       0  5000.4     .12       0
    5577     .16       0
Bank Sta=4966.1,5034.6
XS Rating Curve= 0 ,0
Exp/Cntr=0.3,0.1

Type RM Length L Ch R = 1 ,36708   ,521,521,521
BEGIN DESCRIPTION:
GRINDSTONE CREEK 57.0
END DESCRIPTION:
XS GIS Cut Line= 2
      3544746.96     10623392.13      3545297.67      10621943.8
#Sta/Elev= 30
  4369.8  420.97    4565  413.65    4650  408.93  4669.4  409.42  4674.7  408.23
  4692.8  408.88  4843.4  405.02  4885.4  403.98  4924.4  401.12  4984.6  402.13
  4992.4  399.43  5006.4  397.04  5009.1  396.54  5012.4  397.04  5014.7  399.52
  5024.5  402.44  5154.6  399.63  5227.8  400.34  5264.4  398.31  5270.6  400.47
  5434.4  406.74  5629.1   419.2  5634.5  418.33  5677.1  420.21  5689.4   419.5
  5708.8  420.64  5825.1  422.36  5867.9  423.52  5914.2  424.14  5919.3  425.22
#Mann= 6 ,-1 , 0
  4369.8     .05       0  4843.4     .12       0  5006.4     .07       0
  5012.4     .12       0  5825.1     .16       0  5867.9     .12       0
Bank Sta=4984.6,5024.5
XS Rating Curve= 0 ,0
Exp/Cntr=0.3,0.1

Type RM Length L Ch R = 1 ,36187   ,706,706,706
BEGIN DESCRIPTION:
GRINDSTONE CREEK 56.0
END DESCRIPTION:
XS GIS Cut Line= 2
      3545224.39      10623539.7      3545506.51     10621951.15
#Sta/Elev= 30
  4532.7  416.73  4594.7  416.09  4623.6  410.66  4633.8  410.31  4729.9  410.38
  4750.6  410.44  4879.9  410.43  4897.8  407.71  4930.6  405.67  4979.1  403.21
  4987.8  398.66  4996.4  397.44  4999.1  396.94  5002.4  397.44  5019.7  401.38
  5029.5  401.42  5313.9  398.19  5420.4  399.62    5448  399.48  5678.2   405.1
  5771.3  407.28  5789.3  409.28  5811.9  409.95  5822.1  412.09  5842.4  410.96
  5862.7  411.39  5893.2  414.24  6065.8  423.73  6133.5  425.43  6146.1  424.75
#Mann= 11 ,-1 , 0
  4532.7     .05       0  4729.9      .1       0  4750.6     .15       0
  4930.6     .05       0  4996.4     .03       0  5002.4     .05       0
  5029.5     .12       0  5313.9     .16       0  5420.4     .12       0
    5448     .16       0  5678.2     .12       0
Bank Sta=4979.1,5019.7
XS Rating Curve= 0 ,0
Exp/Cntr=0.3,0.1

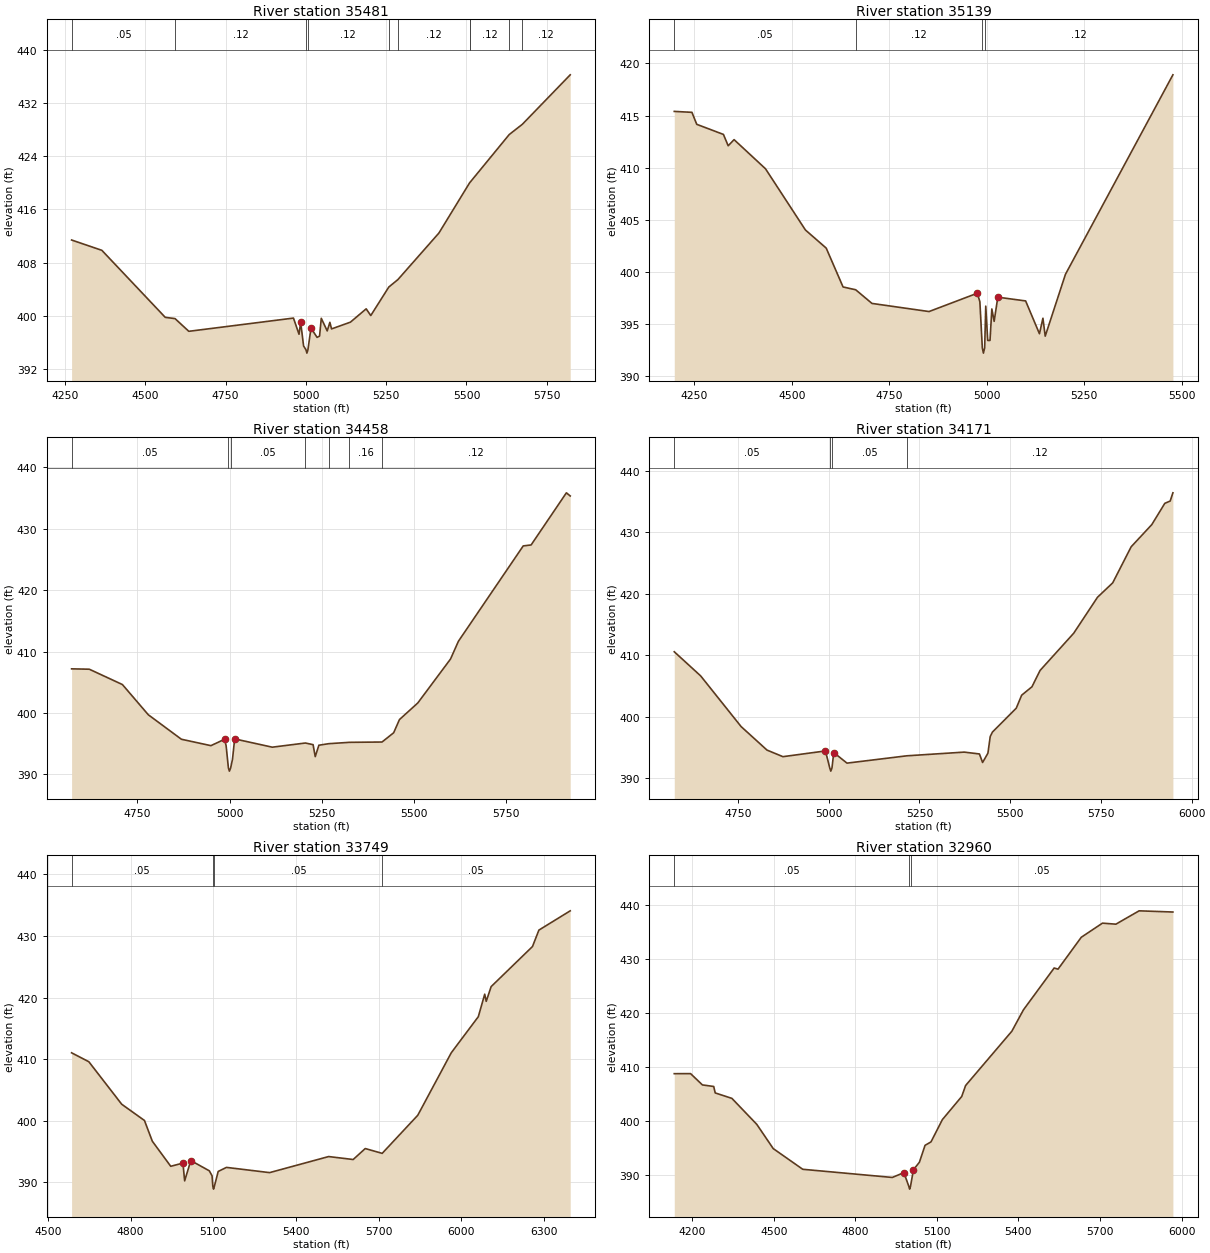
Type RM Length L Ch R = 1 ,35481   ,342,342,342
BEGIN DESCRIPTION:
GRINDSTONE CREEK 55.0
END DESCRIPTION:
XS GIS Cut Line= 3
      3545596.55     10623507.55      3545865.66     10622674.19
      3546298.92     10622154.29
#Sta/Elev= 30
  4270.6  411.41  4364.8  409.86  4562.2  399.78  4592.7  399.59  4635.6  397.68
  4961.4  399.67  4978.7  397.24  4983.9  399.03  4992.9  395.48  5000.4   394.9
  5003.2   394.4  5006.4   394.9    5016  398.17  5034.9  396.77  5042.7  396.96
    5048  399.64  5066.5  397.74  5074.8  399.03    5080  398.04  5138.8  399.06
  5187.8  401.06  5202.1  400.05  5258.3  404.34  5286.6  405.46  5414.3  412.46
  5509.6  419.99  5511.8  420.12  5633.2  427.27    5674  428.81  5823.1  436.25
#Mann= 10 ,-1 , 0
  4270.6     .05       0  4592.7     .12       0  5000.4     .07       0
  5006.4     .12       0  5258.3     .07       0  5286.6     .12       0
  5509.6     .05       0  5511.8     .12       0  5633.2     .07       0
    5674     .12       0
Bank Sta=4983.9,5016
XS Rating Curve= 0 ,0
Exp/Cntr=0.3,0.1

Type RM Length L Ch R = 1 ,35139   ,681,681,681
BEGIN DESCRIPTION:
GRINDSTONE CREEK 54.0
END DESCRIPTION:
XS GIS Cut Line= 3
      3545649.62     10623660.17      3546049.61     10622960.19
      3546299.61     10622560.19
#Sta/Elev= 30
    4199   415.4  4244.3  415.31  4256.6  414.16    4325  413.19  4337.2   412.1
  4352.3  412.69  4432.9  409.89  4535.1  404.02  4588.4  402.28  4631.6  398.55
    4664  398.28  4705.7  396.97  4851.9  396.19  4975.7  397.95  4982.2  397.13
  4988.5   392.7  4991.3   392.2  4994.5   392.7  4997.3  396.71  5002.3  393.42
  5008.2  393.42  5012.9  396.44  5018.8  395.25  5028.2  397.57  5099.5  397.21
  5134.9  394.06  5143.8  395.55  5149.7  393.83  5201.5  399.76  5476.9  418.91
#Mann= 4 ,-1 , 0
    4199     .05       0    4664     .12       0  4988.5     .07       0
  4994.5     .12       0
Bank Sta=4975.7,5028.2
XS Rating Curve= 0 ,0
Exp/Cntr=0.3,0.1

Type RM Length L Ch R = 1 ,34458   ,287,287,287
BEGIN DESCRIPTION:
GRINDSTONE CREEK 53.0
END DESCRIPTION:
XS GIS Cut Line= 2
       3546111.8     10623739.23      3546798.51     10622573.91
#Sta/Elev= 30
  4571.3  407.19  4619.3  407.13  4709.2  404.63  4779.4  399.71  4869.2  395.72
  4949.2  394.68  4986.4  395.72  4990.5  394.65  4996.7  391.03  4999.4  390.53
  5002.7  391.03  5007.8  392.47  5013.6  395.78  5115.7  394.43  5205.5  395.11
  5226.4  394.84  5232.2  392.89  5242.1  394.75  5268.8     395  5325.1  395.22
  5413.4  395.27    5445  396.78  5460.7  398.93  5510.4  401.63  5599.2  408.79
  5620.7  411.69  5796.4  427.21  5817.8  427.37  5913.5  435.86  5923.9  435.35
#Mann= 7 ,-1 , 0
  4571.3     .05       0  4996.7     .03       0  5002.7     .05       0
  5205.5     .16       0  5268.8     .12       0  5325.1     .16       0
  5413.4     .12       0
Bank Sta=4986.4,5013.6
XS Rating Curve= 0 ,0
Exp/Cntr=0.3,0.1

Type RM Length L Ch R = 1 ,34171   ,422,422,422
BEGIN DESCRIPTION:
GRINDSTONE CREEK 52.0
END DESCRIPTION:
XS GIS Cut Line= 3
      3546349.63     10623860.16      3546549.61     10623510.19
      3547099.61     10622710.19
#Sta/Elev= 30
  4574.4  410.58  4647.1  406.66  4758.6  398.42  4829.9   394.6  4873.8  393.53
    4991  394.46  5002.9  391.68  5005.6  391.18  5008.9  391.68  5013.9   394.2
  5050.3  392.48  5215.3  393.67  5373.3  394.27  5415.2  393.97    5424  392.59
  5438.6  394.09    5445   396.8    5451  397.52  5516.7  401.41  5531.6  403.52
    5560  404.89  5582.3  407.54    5675  413.59  5740.6  419.44  5782.5  421.78
  5833.3  427.64  5890.1  431.24    5926   434.7  5940.9  435.08  5948.3  436.41
#Mann= 4 ,-1 , 0
  4574.4     .05       0  5002.9     .03       0  5008.9     .05       0
  5215.3     .12       0
Bank Sta=4991,5013.9
XS Rating Curve= 0 ,0
Exp/Cntr=0.3,0.1

Type RM Length L Ch R = 1 ,33749   ,789,789,789
BEGIN DESCRIPTION:
GRINDSTONE CREEK 51.0
END DESCRIPTION:
XS GIS Cut Line= 3
      3546403.86     10624028.36      3546898.65     10623776.62
      3547410.79     10622630.81
#Sta/Elev= 30
  4585.6  411.03  4648.2  409.58  4767.5  402.68  4850.1  400.04  4878.7  396.67
  4945.5   392.6  4989.9  393.12    4996  390.23  5018.4  393.53  5085.7  391.86
  5095.6  391.05  5098.2  389.39  5100.9  388.89  5104.2  389.39  5117.8  391.76
  5147.8  392.42  5304.5  391.57  5518.8  394.18  5607.8   393.7  5651.7  395.48
  5713.2   394.7  5842.4  400.89  5963.9  411.03  6062.2   416.9  6085.4  420.55
  6090.9  419.39  6108.7  421.78  6258.8  428.29  6282.1  430.96  6395.8  434.09
#Mann= 4 ,-1 , 0
  4585.6     .05       0  5098.2     .03       0  5104.2     .05       0
  5713.2     .05       0
Bank Sta=4989.9,5018.4
XS Rating Curve= 0 ,0
Exp/Cntr=0.3,0.1

Type RM Length L Ch R = 1 ,32960   ,644,644,644
BEGIN DESCRIPTION:
GRINDSTONE CREEK 50.0
END DESCRIPTION:
XS GIS Cut Line= 3
      3546424.31     10624503.13       3547097.9     10624218.41
      3547931.21     10623496.22
#Sta/Elev= 30
  4134.3  408.79  4194.3   408.8  4237.8  406.71  4279.4  406.42  4284.9  405.23
  4346.3  404.22  4437.9  399.41  4498.3  394.93  4606.9   391.1  4936.1  389.59
  4978.9  390.48  4997.2  387.93  4999.9  387.43  5003.2  387.93    5014  391.02
  5035.9   392.4  5056.7  395.53  5078.6  396.17  5120.4  400.29  5191.6  404.57
  5205.9   406.6  5375.9  416.64  5418.6   420.6  5531.6  428.34  5545.8  428.13
  5631.4  434.03  5709.2  436.64  5758.6  436.45  5844.1  438.92  5968.3   438.7
#Mann= 3 ,-1 , 0
  4134.3     .05       0  4997.2     .03       0  5003.2     .05       0
Bank Sta=4978.9,5014
XS Rating Curve= 0 ,0
Exp/Cntr=0.3,0.1

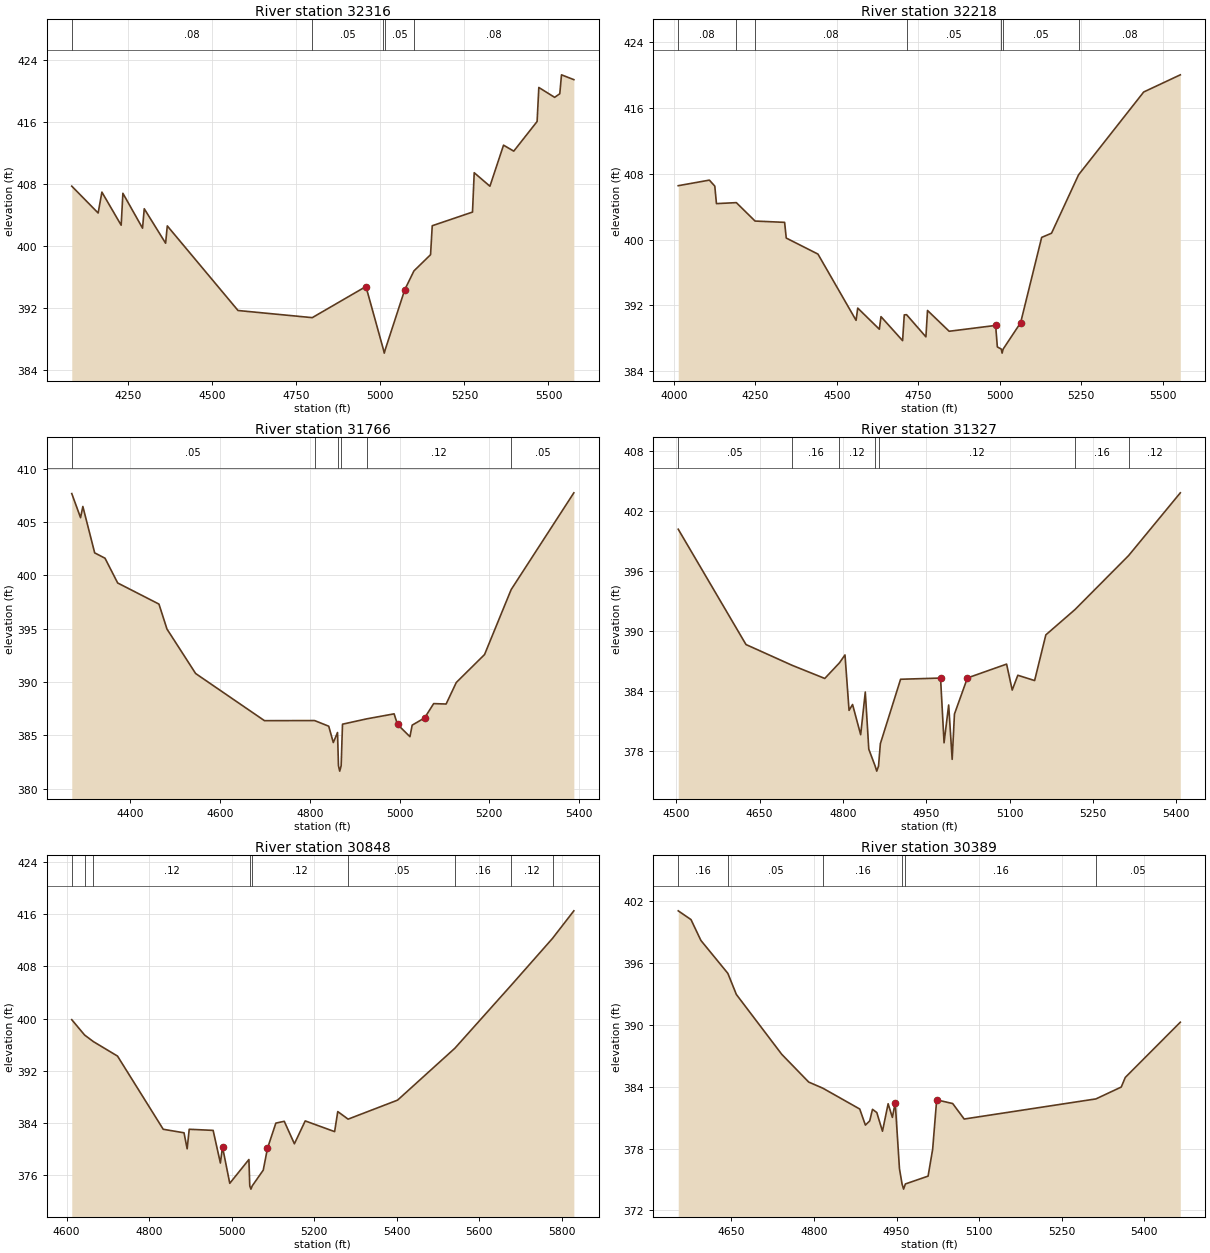
Type RM Length L Ch R = 1 ,32316   ,98,98,98
BEGIN DESCRIPTION:
GRINDSTONE CREEK 49.0
END DESCRIPTION:
XS GIS Cut Line= 3
        3546591.     10624727.61      3547393.04     10624605.22
      3548066.04     10624498.68
#Sta/Elev= 30
  4082.7  407.69  4161.1  404.23  4172.3  406.92  4229.6  402.66  4234.7  406.77
  4293.1  402.28  4298.2  404.78  4361.7  400.34  4366.7  402.57    4577  391.67
  4797.7  390.75  4957.3  394.76    5009  386.68  5011.8  386.18    5015  386.68
  5072.8  394.36    5100  396.77  5149.4  398.86  5154.4  402.59  5274.1  404.35
  5279.2  409.42  5325.9  407.68  5366.4  412.97  5396.8   412.2  5466.2  416.02
  5471.3   420.4  5518.3  419.13  5533.6  419.59  5538.7  422.03  5575.4  421.41
#Mann= 5 ,-1 , 0
  4082.7     .08       0  4797.7     .05       0    5009     .03       0
    5015     .05       0    5100     .08       0
Bank Sta=4957.3,5072.8
XS Rating Curve= 0 ,0
Exp/Cntr=0.3,0.1

Type RM Length L Ch R = 1 ,32218   ,452,452,452
BEGIN DESCRIPTION:
GRINDSTONE CREEK 48.0
END DESCRIPTION:
XS GIS Cut Line= 2
      3546564.93     10624810.95      3548090.96     10624597.41
#Sta/Elev= 30
  4013.1  406.55  4108.7  407.23  4125.3   406.5  4130.4  404.37  4191.4  404.49
  4248.9  402.25  4339.6  402.09  4344.6  400.18  4441.9  398.23  4558.9  390.17
    4564  391.66  4630.3  389.09  4635.4  390.62  4701.7   387.7  4706.8  390.83
  4713.8  390.86  4773.2  388.16  4778.2  391.37  4844.6  388.84  4987.2  389.55
  4992.5  386.93  5004.4  386.68  5007.1  386.18  5010.4  386.68  5063.9  389.88
  5128.5  400.26  5158.8  400.77  5241.8  407.88  5441.6  417.95    5554  420.04
#Mann= 7 ,-1 , 0
  4013.1     .08       0  4191.4     .05       0  4248.9     .08       0
  4713.8     .05       0  5004.4     .04       0  5010.4     .05       0
  5241.8     .08       0
Bank Sta=4987.2,5063.9
XS Rating Curve= 0 ,0
Exp/Cntr=0.3,0.1

Type RM Length L Ch R = 1 ,31766   ,439,439,439
BEGIN DESCRIPTION:
GRINDSTONE CREEK 47.0
END DESCRIPTION:
XS GIS Cut Line= 3
      3546849.61     10624960.19      3547549.61     10625110.19
      3547949.61     10625160.19
#Sta/Elev= 30
  4269.3  407.67  4288.9  405.41    4294  406.46  4320.4  402.11  4343.4  401.61
  4371.6  399.29  4463.6  397.31  4481.5  394.97  4545.4   390.8  4698.8  386.38
  4810.5  386.39    4842  385.86  4852.2  384.33  4861.6  385.27  4863.7  382.15
  4866.5  381.65  4869.7  382.15  4872.7  386.05  4926.6  386.55  4987.7  387.02
  4995.3  386.03    5023  384.88    5028  385.96  5055.7  386.64  5075.9  387.98
  5103.6  387.94  5126.3  389.96  5189.3  392.58  5248.6  398.67  5388.3  407.74
#Mann= 6 ,-1 , 0
  4269.3     .05       0  4810.5     .16       0  4863.7     .07       0
  4869.7     .16       0  4926.6     .12       0  5248.6     .05       0
Bank Sta=4995.3,5055.7
XS Rating Curve= 0 ,0
Exp/Cntr=0.3,0.1

Type RM Length L Ch R = 1 ,31327   ,479,479,479
BEGIN DESCRIPTION:
GRINDSTONE CREEK 46.0
END DESCRIPTION:
XS GIS Cut Line= 3
      3547049.57     10625160.16      3547449.61     10625460.19
      3547849.65     10625510.19
#Sta/Elev= 30
  4503.8   400.2  4625.7  388.64  4708.6  386.56  4767.4  385.24  4793.9  386.81
  4803.8   387.6  4811.1  382.04  4817.4  382.63    4832   379.6  4840.3  383.88
  4846.6  378.15  4858.1  376.45  4860.9  375.95  4864.1  376.45  4867.4   378.7
  4903.8  385.16  4975.7  385.28    4982  378.79  4990.3  382.58  4996.6  377.13
  5000.7  381.67    5024  385.29  5094.5  386.68  5104.6  384.08  5114.7  385.56
  5144.9  385.03  5165.1  389.61  5217.4  392.14    5314  397.56    5407  403.85
#Mann= 7 ,-1 , 0
  4503.8     .05       0  4708.6     .16       0  4793.9     .12       0
  4858.1     .07       0  4864.1     .12       0  5217.4     .16       0
    5314     .12       0
Bank Sta=4975.7,5024
XS Rating Curve= 0 ,0
Exp/Cntr=0.3,0.1

Type RM Length L Ch R = 1 ,30848   ,459,459,459
BEGIN DESCRIPTION:
GRINDSTONE CREEK 45.0
END DESCRIPTION:
XS GIS Cut Line= 3
      3546799.58     10625860.19      3547199.61     10625810.19
      3547999.62     10625660.19
#Sta/Elev= 30
  4612.5  399.84  4643.5   397.5  4664.8  396.49  4723.4  394.27  4834.2  383.07
  4884.6  382.53  4892.2  380.08  4897.2  383.07  4955.2   382.9  4972.8   377.9
  4977.9  380.38  4995.5   374.8  5041.9  378.44    5044  374.41  5046.8  373.91
    5050  374.41  5076.7  376.82  5086.9  380.15  5107.2  384.01  5127.6  384.29
  5152.2  380.85  5178.4  384.35  5249.7  382.71  5257.3  385.78  5282.4  384.62
  5402.3  387.53  5541.2  395.47  5676.6  405.03    5778  412.29  5829.6   416.5
#Mann= 9 ,-1 , 0
  4612.5     .05       0  4643.5     .07       0  4664.8     .12       0
    5044     .07       0    5050     .12       0  5282.4     .05       0
  5541.2     .16       0  5676.6     .12       0    5778     .16       0
Bank Sta=4977.9,5086.9
XS Rating Curve= 0 ,0
Exp/Cntr=0.3,0.1

Type RM Length L Ch R = 1 ,30389   ,477,477,477
BEGIN DESCRIPTION:
GRINDSTONE CREEK 44.0
END DESCRIPTION:
XS GIS Cut Line= 3
      3546849.63     10626260.18      3547249.61     10626160.19
      3547649.62     10625860.18
#Sta/Elev= 30
  4553.4  401.03  4576.6  400.18  4594.6  398.16  4643.6  394.97    4659  392.93
  4741.5  387.13  4790.5  384.44  4816.1  383.85  4883.2  381.83  4893.5  380.27
  4901.3  380.68  4906.4   381.8  4914.2  381.49  4924.5  379.68  4934.8  382.34
  4942.5  381.02  4947.7  382.44  4955.4  376.04  4960.1  374.57  4962.9  374.07
  4966.1  374.57  5007.4  375.33  5015.7  377.93    5023  382.72  5052.1  382.36
    5073  380.86  5312.4  382.81  5358.4  383.96  5365.7  384.89  5465.7  390.24
#Mann= 6 ,-1 , 0
  4553.4     .16       0  4643.6     .05       0  4816.1     .16       0
  4960.1     .07       0  4966.1     .16       0  5312.4     .05       0
Bank Sta=4947.7,5023
XS Rating Curve= 0 ,0
Exp/Cntr=0.3,0.1

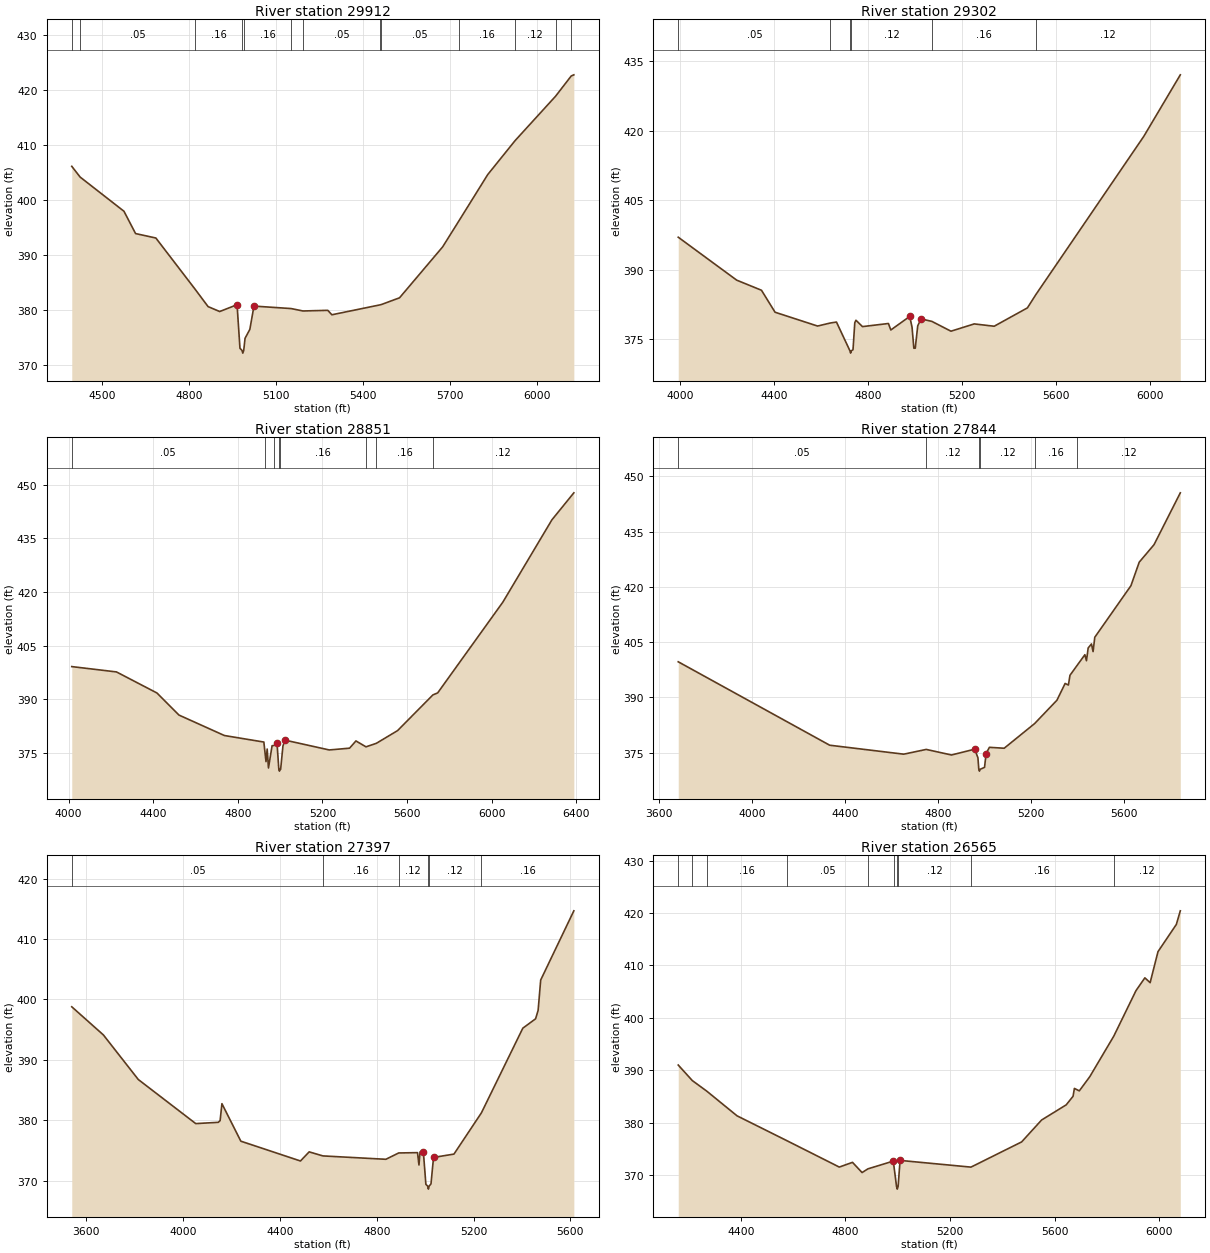
Type RM Length L Ch R = 1 ,29912   ,610,610,610
BEGIN DESCRIPTION:
GRINDSTONE CREEK 43.0
END DESCRIPTION:
XS GIS Cut Line= 3
      3546699.66     10626510.19      3547299.61     10626510.19
      3548099.59     10625710.21
#Sta/Elev= 30
  4395.6  406.16  4424.5   404.2  4575.6  397.98  4615.6  393.92  4685.6  393.11
  4820.2  383.84  4865.6  380.63  4905.6  379.73  4965.6  380.97  4975.6  373.04
  4982.6  372.66  4985.3  372.16  4988.6  372.66  4993.1  374.85  5009.7  376.49
  5023.8  380.72  5152.2  380.27  5192.8  379.83  5278.4  379.95  5292.5  379.14
  5458.3  380.94  5463.6  381.01  5525.9  382.23  5674.4  391.49  5729.7  396.15
  5829.9  404.65  5924.2  410.83    6064  418.92  6117.8   422.6  6126.9  422.81
#Mann= 13 ,-1 , 0
  4395.6     .07       0  4424.5     .05       0  4820.2     .16       0
  4982.6     .07       0  4988.6     .16       0  5152.2     .12       0
  5192.8     .05       0  5458.3     .16       0  5463.6     .05       0
  5729.7     .16       0  5924.2     .12       0    6064     .16       0
  6117.8     .12       0
Bank Sta=4965.6,5023.8
XS Rating Curve= 0 ,0
Exp/Cntr=0.3,0.1

Type RM Length L Ch R = 1 ,29302   ,451,451,451
BEGIN DESCRIPTION:
GRINDSTONE CREEK 42.0
END DESCRIPTION:
XS GIS Cut Line= 3
      3547549.61     10627610.17      3547649.61     10626610.19
      3548449.58     10625810.21
#Sta/Elev= 30
  3991.2     397  4239.9  387.74  4345.4  385.56  4403.2  380.82  4584.1  377.84
  4638.6   378.5  4664.5   378.7  4721.8   372.5  4724.6     372  4727.8   372.5
  4734.9  372.74  4742.4  378.55  4747.4  379.09  4775.1  377.72  4885.6  378.39
  4895.7  376.99  4976.1  379.91  4986.1  377.58  4993.7  373.06  4999.7  373.06
  5010.3   377.9  5024.5  379.38  5070.6  378.84  5151.7  376.73  5250.7   378.3
  5335.6   377.8    5477  381.76  5512.7  384.61    5972  418.74  6127.5  432.02
#Mann= 6 ,-1 , 0
  3991.2     .05       0  4638.6     .12       0  4721.8     .07       0
  4727.8     .12       0  5070.6     .16       0  5512.7     .12       0
Bank Sta=4976.1,5024.5
XS Rating Curve= 0 ,0
Exp/Cntr=0.3,0.1

Type RM Length L Ch R = 1 ,28851   ,1007,1007,1007
BEGIN DESCRIPTION:
GRINDSTONE CREEK 41.0
END DESCRIPTION:
XS GIS Cut Line= 3
      3547499.62     10627810.16      3547899.61     10626910.19
      3548599.61     10625710.19
#Sta/Elev= 30
  4014.7  399.15    4226  397.66  4417.5  391.77  4521.5   385.6  4736.2  379.88
    4923  378.05  4927.4  375.69  4933.2  372.58  4938.7   376.1  4944.8   370.8
  4961.9  377.02  4971.6   377.1  4985.2  377.85  4993.8  370.42  4996.6  369.92
  4999.8  370.42  5002.4  370.42  5013.2  376.93  5022.7  378.59  5232.3  375.84
  5328.3  376.34  5358.4  378.36    5406  376.71  5455.1   377.7  5555.3  381.25
  5722.3  391.23    5745   391.8  6053.1  417.17    6285  440.18  6388.8  447.74
#Mann= 8 ,-1 , 0
  4014.7     .05       0  4927.4     .12       0  4971.6     .16       0
  4993.8     .07       0  4999.8     .16       0    5406     .12       0
  5455.1     .16       0  5722.3     .12       0
Bank Sta=4985.2,5022.7
XS Rating Curve= 0 ,0
Exp/Cntr=0.3,0.1

Type RM Length L Ch R = 1 ,27844   ,447,447,447
BEGIN DESCRIPTION:
GRINDSTONE CREEK 40.0
END DESCRIPTION:
XS GIS Cut Line= 3
      3547599.61     10627710.19      3548599.61     10626810.19
       3549149.6     10626210.19
#Sta/Elev= 30
  3681.7  399.66  4333.1  377.02  4651.5  374.59  4748.3  375.88    4857  374.37
  4956.4  375.94  4970.6  373.63  4974.4  370.49  4977.1  369.99  4980.4  370.49
    4999  371.01  5005.8  374.76    5020  376.45  5083.5   376.2  5214.2  382.88
  5310.4  389.23  5345.6  393.78  5359.7  393.35  5366.5     396  5397.4   398.7
  5430.6  401.58  5437.4  399.95  5444.8  403.42    5459   404.5  5465.8  402.42
  5473.2  406.32  5628.6   420.3  5664.3  426.69  5727.9  431.43    5841  445.51
#Mann= 6 ,-1 , 0
  3681.7     .05       0  4748.3     .12       0  4974.4     .07       0
  4980.4     .12       0  5214.2     .16       0  5397.4     .12       0
Bank Sta=4956.4,5005.8
XS Rating Curve= 0 ,0
Exp/Cntr=0.3,0.1

Type RM Length L Ch R = 1 ,27397   ,832,832,832
BEGIN DESCRIPTION:
GRINDSTONE CREEK 39.0
END DESCRIPTION:
XS GIS Cut Line= 3
       3547699.6     10627860.19      3548899.61     10627060.19
      3549099.61     10626460.17
#Sta/Elev= 30
  3539.9  398.78  3670.6  394.12  3814.8  386.74  4052.2  379.44  4145.3  379.65
  4152.9  379.93  4160.4  382.74  4238.5  376.53  4484.9  373.25  4520.9  374.76
  4577.6  374.09  4837.9  373.53  4890.9  374.58  4968.6  374.63  4974.6  372.59
  4979.1  374.75  4992.7   374.8  5003.2  369.38  5010.7  369.09  5013.5  368.59
  5016.7  369.09  5024.3  369.46  5034.8  373.84  5119.2  374.39  5232.8  381.23
  5403.8  395.24  5456.5  396.79    5467  398.19  5477.6  403.21  5614.6  414.67
#Mann= 6 ,-1 , 0
  3539.9     .05       0  4577.6     .16       0  4890.9     .12       0
  5010.7     .07       0  5016.7     .12       0  5232.8     .16       0
Bank Sta=4992.7,5034.8
XS Rating Curve= 0 ,0
Exp/Cntr=0.3,0.1

Type RM Length L Ch R = 1 ,26565   ,795,795,795
BEGIN DESCRIPTION:
GRINDSTONE CREEK 38.0
END DESCRIPTION:
XS GIS Cut Line= 3
      3549016.66     10628302.95      3549315.26     10627434.91
      3549398.59     10626435.04
#Sta/Elev= 30
  4160.1     391  4213.9  388.04  4269.5  386.01  4385.1  381.31  4576.5  376.55
  4776.4  371.53    4827  372.43  4863.6  370.48    4886  371.19  4983.2  372.67
  4985.8  371.61  4995.5  367.82  4998.2  367.32  5001.5  367.82    5009   372.8
  5280.3  371.52  5474.2  376.33  5550.6  380.51  5644.7   383.4    5671  385.04
  5676.1  386.54  5694.9  386.07  5735.1  388.79  5826.8  396.51  5911.9  405.21
  5945.8  407.64  5965.9  406.72    5996  412.64  6066.2  417.83  6081.4  420.43
#Mann= 10 ,-1 , 0
  4160.1     .16       0  4213.9     .05       0  4269.5     .16       0
  4576.5     .05       0    4886     .16       0  4985.8     .12       0
  4995.5     .07       0  5001.5     .12       0  5280.3     .16       0
  5826.8     .12       0
Bank Sta=4983.2,5009
XS Rating Curve= 0 ,0
Exp/Cntr=0.3,0.1