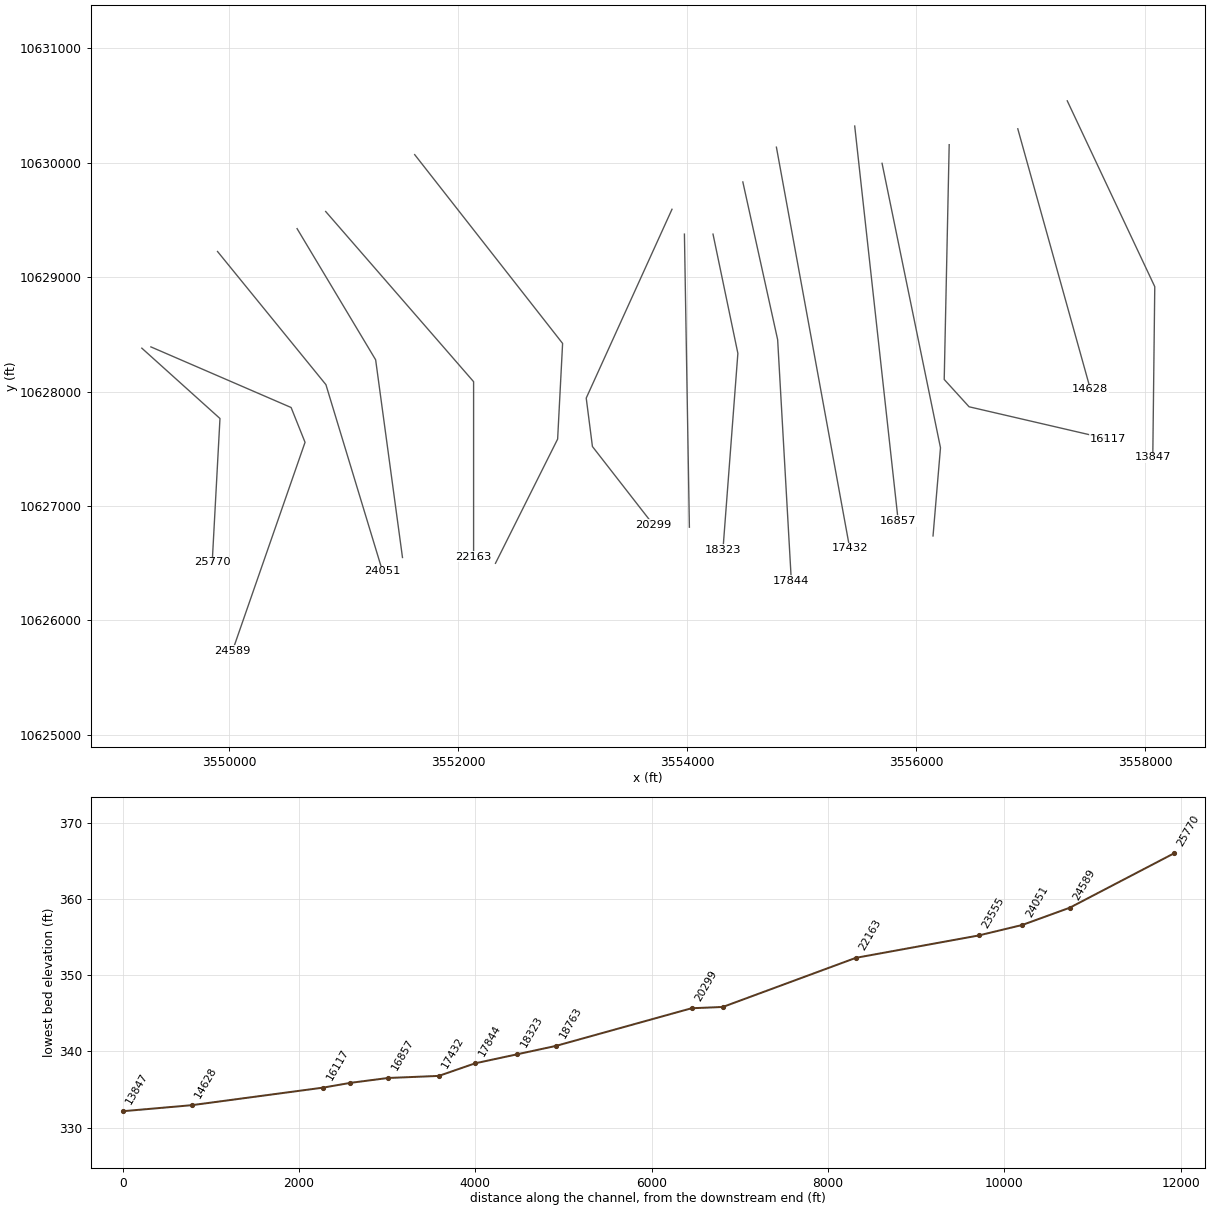
HEC-RAS study GRINDSTONE CREEK.prj: GRINDSTONE CREEK Base Level Engineering

--- GRINDSTONE CREEK.g01 (geometry) --- (continued)

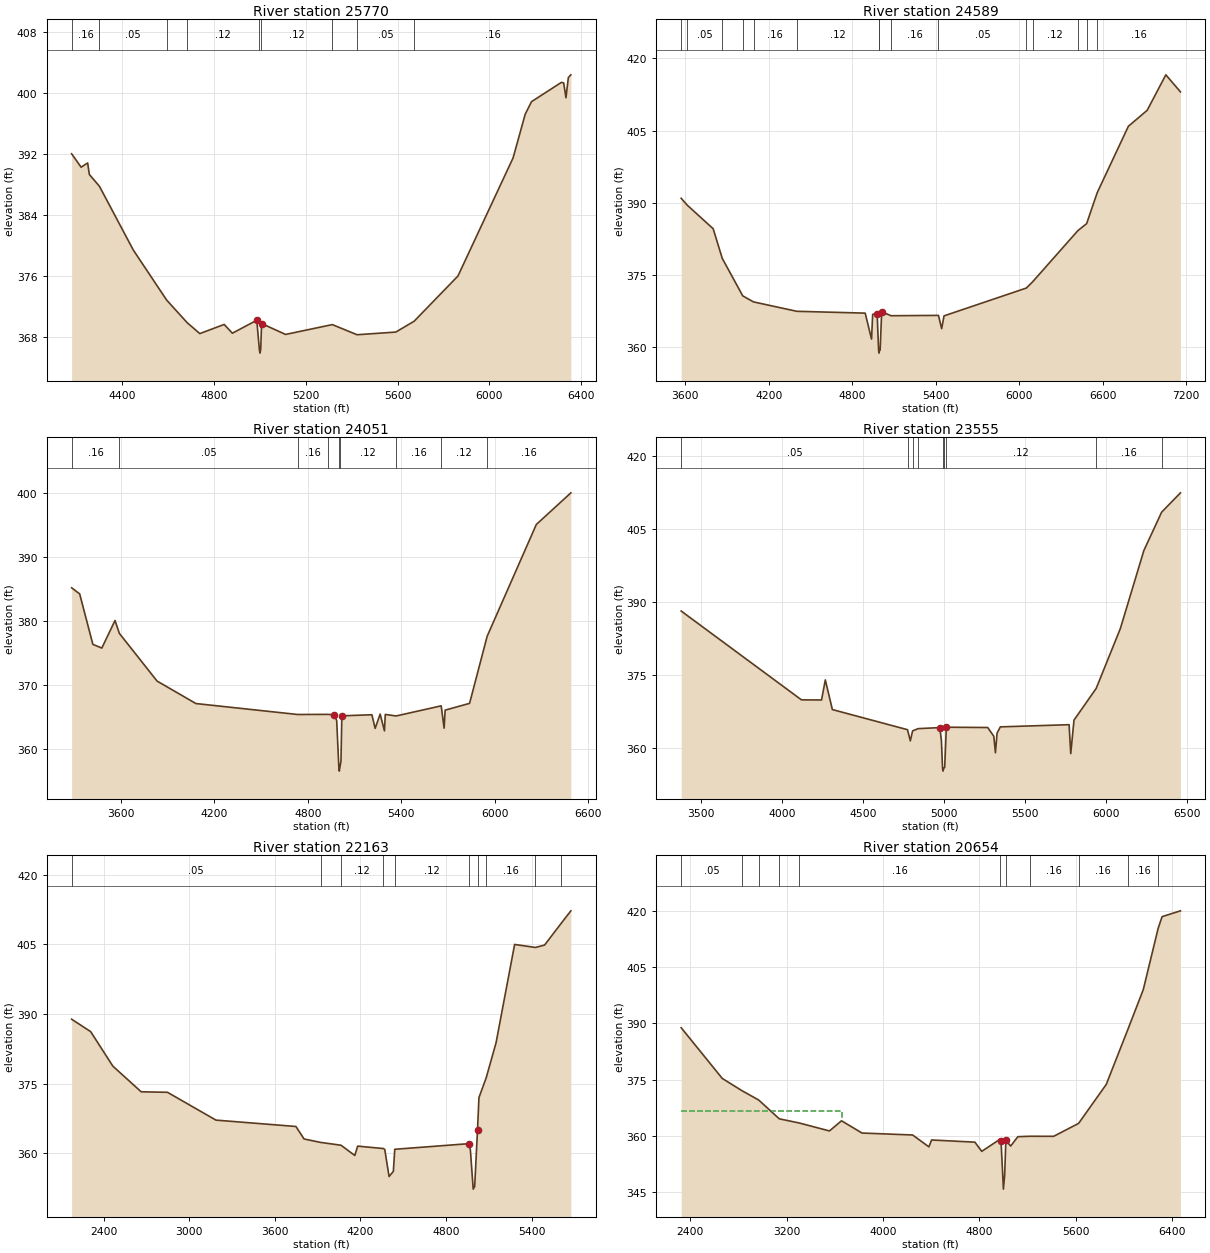
Type RM Length L Ch R = 1 ,25770   ,1181,1181,1181
BEGIN DESCRIPTION:
GRINDSTONE CREEK 36.0
END DESCRIPTION:
XS GIS Cut Line= 3
       3549239.2     10628378.65      3549921.48     10627764.08
      3549853.77     10626508.86
#Sta/Elev= 30
  4179.4  392.08  4220.8  390.32  4249.2  390.88  4256.6  389.37  4300.4  387.83
    4448  379.47  4593.6   372.9  4682.5  369.95  4737.9  368.51  4844.1  369.71
  4879.8  368.56  4986.1  370.26  4997.3  366.45    5000  365.95  5003.3  366.45
    5007  369.83  5111.6   368.4  5315.2  369.69    5423  368.36  5591.9  368.71
  5671.7  370.13  5862.7  376.06    6103  391.55  6155.7  397.27  6183.1  398.91
  6313.3  401.44  6323.3  401.37  6333.3  399.43  6343.7  402.08  6354.7  402.43
#Mann= 9 ,-1 , 0
  4179.4     .16       0  4300.4     .05       0  4593.6     .16       0
  4682.5     .12       0  4997.3     .07       0  5003.3     .12       0
  5315.2     .16       0    5423     .05       0  5671.7     .16       0
Bank Sta=4986.1,5007
XS Rating Curve= 0 ,0
Exp/Cntr=0.3,0.1

Type RM Length L Ch R = 1 ,24589   ,538,538,538
BEGIN DESCRIPTION:
GRINDSTONE CREEK 35.0
END DESCRIPTION:
XS GIS Cut Line= 4
      3549318.52     10628389.67      3550542.51     10627860.14
      3550664.04     10627556.32      3550030.68     10625734.31
#Sta/Elev= 30
    3570  390.96  3613.3  389.54    3800  384.64  3865.3  378.49  4012.7  370.71
  4089.9  369.46  4401.2  367.51    4893  367.13  4938.7  361.74  4946.7  366.88
    4979     367  4989.6  359.33  4992.3  358.83  4995.6  359.33  5000.5  359.45
  5011.3  367.28  5016.8  367.36  5078.7  366.59  5419.7  366.66    5443  363.91
  5459.7  366.56  6051.3  372.33    6096   373.6  6422.6  384.26  6485.3   385.7
  6561.1  392.11  6785.3   405.9  6920.7  409.22  7054.7  416.58  7159.8  413.05
#Mann= 15 ,-1 , 0
    3570     .16       0  3613.3     .05       0  3865.3     .16       0
  4012.7     .12       0  4089.9     .16       0  4401.2     .12       0
  4989.6     .07       0  4995.6     .12       0  5078.7     .16       0
  5419.7     .05       0  6051.3     .16       0    6096     .12       0
  6422.6     .16       0  6485.3     .12       0  6561.1     .16       0
#XS Ineff= 2 ,-1
 4879.55 4952.27  366.38 5406.82    5475  366.38
Permanent Ineff=
       F       F
Bank Sta=4979,5016.8
XS Rating Curve= 0 ,0
Exp/Cntr=0.3,0.1

Type RM Length L Ch R = 1 ,24051   ,496,496,496
BEGIN DESCRIPTION:
GRINDSTONE CREEK 34.0
END DESCRIPTION:
XS GIS Cut Line= 3
      3549900.18     10629222.95      3550846.33     10628059.79
      3551341.13     10626427.84
#Sta/Elev= 30
  3283.6  385.22  3335.2  384.27    3420  376.38  3477.4   375.8  3562.2  380.11
  3589.9   378.1  3832.2  370.64  4081.5  367.13  4734.3  365.42  4926.1  365.44
  4970.7  365.38  4985.1  364.45    4999  357.07  5001.8  356.57    5005  357.07
  5012.5  358.11    5018  365.21    5211  365.38  5231.9  363.25    5264  365.48
  5291.7  362.86  5296.9  365.43  5366.4  365.19  5655.9  366.77  5674.6  363.29
  5681.2   366.1    5838  367.16  5950.8  377.64  6266.4  395.11  6488.3  400.06
#Mann= 9 ,-1 , 0
  3283.6     .16       0  3589.9     .05       0  4734.3     .16       0
  4926.1     .12       0    4999     .07       0    5005     .12       0
  5366.4     .16       0  5655.9     .12       0  5950.8     .16       0
#XS Ineff= 2 ,-1
 5143.75 5302.84  364.57  5642.9 5692.61  366.07
Permanent Ineff=
       F       F
Bank Sta=4970.7,5018
XS Rating Curve= 0 ,0
Exp/Cntr=0.3,0.1

Type RM Length L Ch R = 1 ,23555   ,1392,1392,1392
BEGIN DESCRIPTION:
GRINDSTONE CREEK 33.0
END DESCRIPTION:
XS GIS Cut Line= 3
       3550594.6     10629422.63      3551280.36      10628276.8
      3551514.67     10626549.89
#Sta/Elev= 30
  3379.6  388.11    4121  369.85  4244.9  369.82  4268.2  373.95  4311.6  367.85
  4774.9  363.71  4792.3  361.41  4806.3  363.46  4840.7  363.93  4974.3  364.14
    4984  361.44  4991.1  355.69  4993.9  355.19  4997.1  355.69  5004.2  355.99
  5011.3  361.78  5014.3  364.22  5269.4  364.16    5307  362.36    5317  358.97
  5327.1  363.01  5347.3  364.29  5771.2  364.74  5781.3  358.79  5801.4  365.68
  5938.2   372.2  6087.2  384.51  6232.2  400.56  6341.5  408.43  6457.7  412.42
#Mann= 9 ,-1 , 0
  3379.6     .05       0  4774.9     .16       0  4806.3     .05       0
  4840.7     .16       0  4991.1     .07       0  4997.1     .16       0
  5011.3     .12       0  5938.2     .16       0  6341.5     .12       0
#XS Ineff= 3 ,-1
 4028.12 4264.77  372.08 5263.07  5362.5   363.4 5760.23 5829.83  364.11
Permanent Ineff=
       F       F       F
Bank Sta=4974.3,5014.3
XS Rating Curve= 0 ,0
Exp/Cntr=0.3,0.1

Type RM Length L Ch R = 1 ,22163   ,1509,1509,1509
BEGIN DESCRIPTION:
GRINDSTONE CREEK 32.0
END DESCRIPTION:
XS GIS Cut Line= 3
      3550844.14      10629572.4       3552135.4     10628085.83
       3552135.4      10626555.9
#Sta/Elev= 30
  2175.6  388.85    2309  386.18  2464.7  378.74  2663.1  373.22  2847.4  373.11
  3187.3  367.12  3747.6  365.75  3804.6  363.06  3920.6  362.32  4063.7  361.71
  4160.3  359.51  4180.3  361.52  4360.3     361  4370.3  360.79  4400.3  354.98
  4430.3  356.07  4440.3  360.84  4960.3  362.05  4970.3  360.69  4990.1  352.26
  5000.3  352.81  5020.3  365.09  5030.3  371.97  5081.1  376.24  5150.3  383.79
  5280.3  404.95  5426.4   404.3  5490.3  404.82  5608.6  409.58  5674.6  412.19
#Mann= 10 ,-1 , 0
  2175.6     .05       0  3920.6     .16       0  4063.7     .12       0
  4360.3     .16       0  4440.3     .12       0  4960.3     .12       0
  5020.3     .16       0  5081.1     .16       0  5426.4     .12       0
  5608.6     .16       0
#XS Ineff= 1 ,-1
    4350 4461.36  360.25
Permanent Ineff=
       F
Bank Sta=4960.3,5020.3
XS Rating Curve= 0 ,0
Exp/Cntr=0.3,0.1

Type RM Length L Ch R = 1 ,20654   ,355,355,355
BEGIN DESCRIPTION:
GRINDSTONE CREEK 31.0
END DESCRIPTION:
XS GIS Cut Line= 4
      3551621.12      10630069.2      3552912.33     10628419.91
      3552868.93     10627584.41      3552326.39     10626499.32
#Sta/Elev= 30
  2325.7  388.84  2666.5  375.33    2828   372.1  2969.4  369.56  3140.1  364.56
  3306.7  363.44  3556.4  361.33  3656.6  364.04  3826.6  360.77    4247  360.25
  4381.9  357.09  4404.3  358.92  4763.7  358.34  4820.6  355.89  4970.8  359.09
  4980.8  358.55  5000.6  345.82  5010.8  349.55  5020.8  358.79  5060.9  357.31
  5120.7   359.8  5221.1  359.91  5417.9   359.9  5624.7  363.34  5854.2  373.73
  6032.6   388.3  6161.4  398.98  6285.3  415.37  6317.9  418.45  6470.1     420
#Mann= 11 ,-1 , 0
  2325.7     .05       0    2828     .16       0  2969.4     .12       0
  3140.1     .16       0  3306.7     .16       0  4970.8     .12       0
  5020.8     .12       0  5221.1     .16       0  5624.7     .16       0
  6032.6     .16       0  6285.3     .05       0
#XS Ineff= 2 , 0
         3656.91  366.77
Permanent Ineff=
       F       F
Bank Sta=4980.8,5020.8
XS Rating Curve= 0 ,0
Exp/Cntr=0.3,0.1

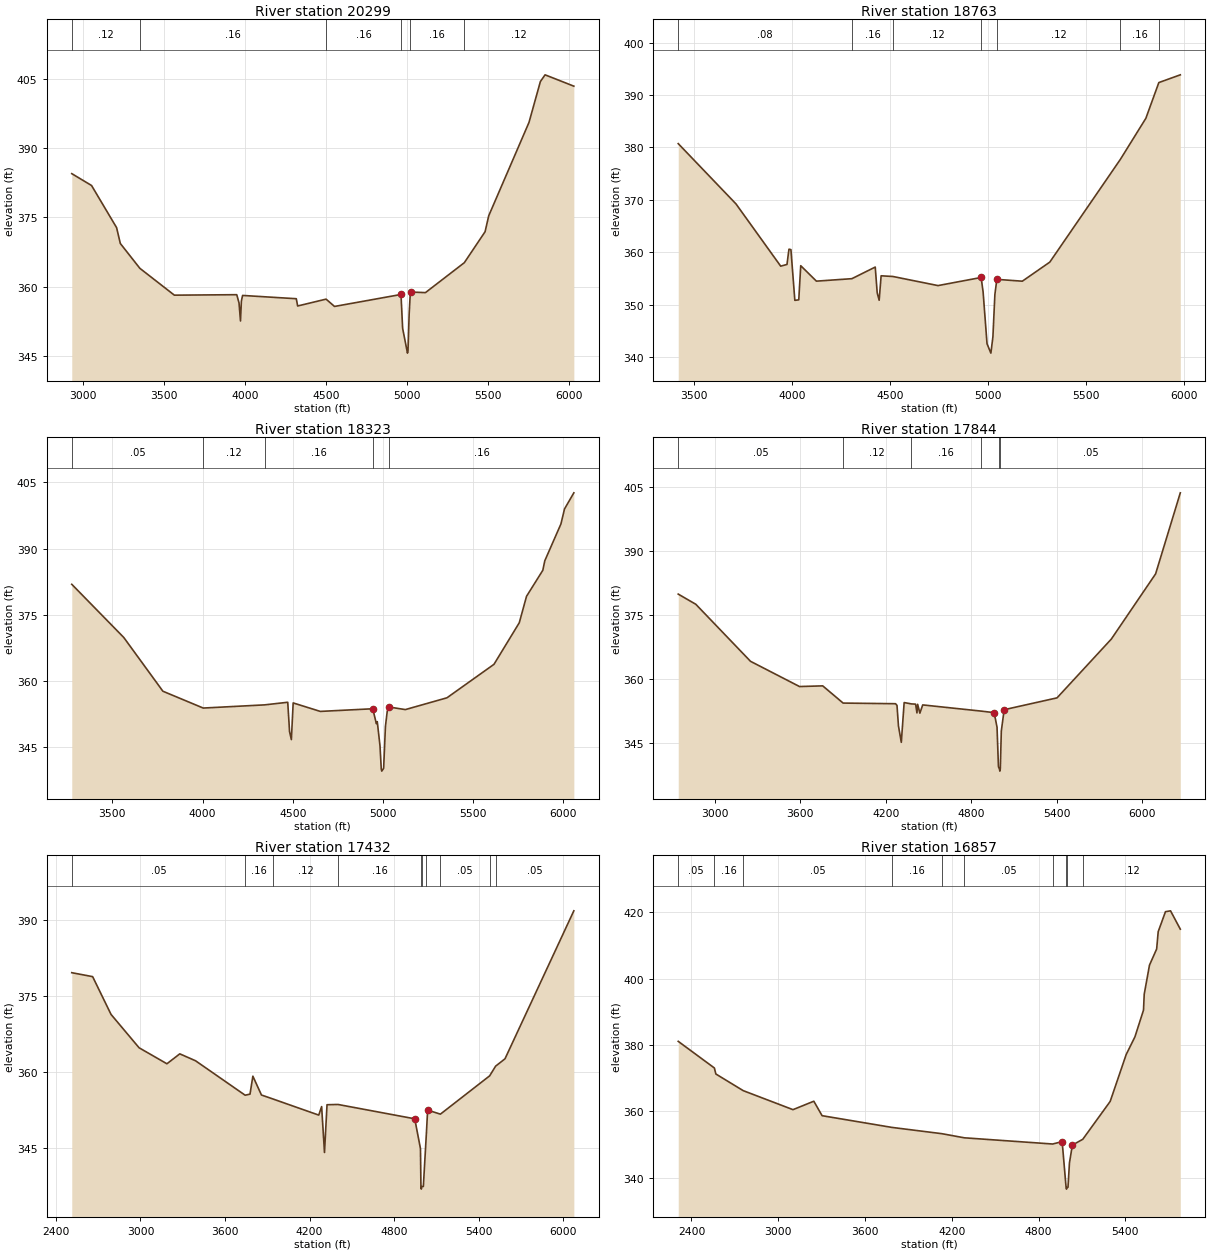
Type RM Length L Ch R = 1 ,20299   ,1536,1536,1536
BEGIN DESCRIPTION:
GRINDSTONE CREEK 30.0
END DESCRIPTION:
XS GIS Cut Line= 4
       3553867.2     10629591.81       3553118.5     10627942.48
      3553172.75     10627519.31      3553704.46     10626835.69
#Sta/Elev= 30
  2928.8  384.45    3051  381.89  3205.9  372.78    3229  369.35  3349.9  363.98
  3563.1  358.18  3948.8  358.28  3962.9   356.5  3971.9   352.6  3977.4   356.9
  3984.9  358.12  4316.9  357.41  4325.3  355.84    4501  357.32  4553.2  355.74
  4964.2  358.33  4974.3  351.02  5004.3  345.65  5007.5  346.15  5014.6  354.04
  5021.9  358.81  5026.9  358.85  5115.4  358.73  5355.7   365.2    5484  371.89
  5506.6  375.34  5755.4  395.51    5826  404.36    5855  405.81  6032.8  403.36
#Mann= 6 ,-1 , 0
  2928.8     .12       0  3349.9     .16       0    4501     .16       0
  4964.2     .12       0  5021.9     .16       0  5355.7     .12       0
#XS Ineff= 1 ,-1
 3948.52 3986.94  357.92
Permanent Ineff=
       F
Bank Sta=4964.2,5026.9
XS Rating Curve= 0 ,0
Exp/Cntr=0.3,0.1

Type RM Length L Ch R = 1 ,18763   ,440,440,440
BEGIN DESCRIPTION:
GRINDSTONE CREEK 28.0
END DESCRIPTION:
XS GIS Cut Line= 2
       3553975.7     10629374.76      3554019.09     10626814.63
#Sta/Elev= 30
  3419.7  380.74  3714.3  369.22  3942.3  357.33  3974.3  357.66  3984.4  360.57
  3994.4  360.49  4014.4   350.8  4034.4   350.9  4044.4  357.42  4124.4  354.47
  4305.2  354.94  4424.4  357.16  4434.4  352.24  4444.4  350.82  4454.4  355.49
  4514.4  355.36  4744.5  353.62  4964.5  355.17  4974.5   352.4  4994.5  342.51
  5014.2  340.72  5024.5  343.85  5034.5  351.89  5044.5  354.81  5174.5  354.46
  5314.5   358.1  5674.7  377.74  5804.6  385.58  5870.7   392.4  5980.2  393.88
#Mann= 7 ,-1 , 0
  3419.7     .08       0  4305.2     .16       0  4514.4     .12       0
  4964.5     .12       0  5044.5     .12       0  5674.7     .16       0
  5870.7     .05       0
Bank Sta=4964.5,5044.5
XS Rating Curve= 0 ,0
Exp/Cntr=0.3,0.1

Type RM Length L Ch R = 1 ,18323   ,479,479,479
BEGIN DESCRIPTION:
GRINDSTONE CREEK 26.0
END DESCRIPTION:
XS GIS Cut Line= 3
      3554225.27     10629374.78      3554442.28     10628333.11
      3554312.07     10626618.68
#Sta/Elev= 30
  3275.2  381.92  3563.5  369.88  3780.4  357.71    4004   353.9  4344.3  354.62
  4472.5  355.21  4482.6  348.57  4492.6  346.76  4502.6  355.06  4653.1  353.14
  4943.9  353.74  4963.8  350.36  4968.9  350.82    4984  345.34    4991  340.12
  4993.8  339.62  5004.1  340.25  5014.1  349.73  5024.1  353.18  5034.1  354.14
  5124.4  353.55  5355.1  356.22  5615.8   363.8  5756.1  373.21  5796.3   379.2
  5886.6  385.09  5897.4  387.23  5986.9  395.57  6006.9  398.98  6058.6  402.63
#Mann= 5 ,-1 , 0
  3275.2     .05       0    4004     .12       0  4344.3     .16       0
  4943.9     .12       0  5034.1     .16       0
Bank Sta=4943.9,5034.1
XS Rating Curve= 0 ,0
Exp/Cntr=0.3,0.1

Type RM Length L Ch R = 1 ,17844   ,412,412,412
BEGIN DESCRIPTION:
GRINDSTONE CREEK 25.0
END DESCRIPTION:
XS GIS Cut Line= 3
      3554485.68     10629830.54       3554789.5     10628452.47
      3554908.86     10626347.42
#Sta/Elev= 30
  2745.7  379.87  2868.9  377.49  3252.3  364.14    3596  358.23  3758.6  358.39
  3901.6  354.36  4269.3  354.21  4279.3   353.8  4289.4  349.04  4309.4  345.17
  4329.4  354.48  4379.8  354.17  4409.6  354.11  4419.1  352.06  4424.1  354.07
  4439.6     352  4459.6  353.93  4869.8  352.48  4960.4  352.12  4980.5  348.71
  4990.5  339.43  4997.5  338.93  5000.2  338.43  5003.5  338.93  5010.5  347.81
  5030.5  352.81  5401.1  355.58  5781.8  369.35  6092.2  384.61  6265.3  403.58
#Mann= 6 ,-1 , 0
  2745.7     .05       0  3901.6     .12       0  4379.8     .16       0
  4869.8     .05       0  4997.5     .03       0  5003.5     .05       0
Bank Sta=4960.4,5030.5
XS Rating Curve= 0 ,0
Exp/Cntr=0.3,0.1

Type RM Length L Ch R = 1 ,17432   ,575,575,575
BEGIN DESCRIPTION:
GRINDSTONE CREEK 24.0
END DESCRIPTION:
XS GIS Cut Line= 2
      3554778.65     10630134.36      3555418.84     10626629.55
#Sta/Elev= 30
  2512.8  379.53  2660.9  378.75  2791.5  371.29  2990.5   364.7    3188  361.54
  3279.4   363.5  3391.3  362.13  3743.1  355.33  3777.6  355.54  3797.9  359.09
  3858.9  355.37    3941  354.58  4265.5   351.4  4285.8  353.08  4306.2  344.02
  4324.1  353.45  4402.4   353.5  4946.6  350.67  4987.2  344.79  4990.5  337.28
  4993.2  336.78  4996.5  337.28  5007.6   337.3  5029.8  348.06  5038.1  352.39
  5128.7  351.59  5477.9  359.15  5520.5  361.07    5587  362.52  6075.6  391.75
#Mann= 10 ,-1 , 0
  2512.8     .05       0  3743.1     .16       0    3941     .12       0
  4402.4     .16       0  4990.5     .07       0  4996.5     .16       0
  5029.8     .12       0  5128.7     .05       0  5477.9     .16       0
  5520.5     .05       0
Bank Sta=4946.6,5038.1
XS Rating Curve= 0 ,0
Exp/Cntr=0.3,0.1

Type RM Length L Ch R = 1 ,16857   ,427,427,427
BEGIN DESCRIPTION:
GRINDSTONE CREEK 23.0
END DESCRIPTION:
XS GIS Cut Line= 2
      3555462.25      10630318.8      3555842.02     10626868.24
#Sta/Elev= 30
  2308.4  381.06  2558.3  373.03  2568.6  371.22  2757.6   366.2  3101.8  360.47
  3245.9  363.01    3303  358.65  3785.4  355.12  4130.3  353.23  4286.6  351.98
  4897.6  350.11  4962.9  350.84  4990.1  337.01  4992.9  336.51  4996.1  337.01
  5003.2  337.08  5013.3   344.4  5033.4  349.79  5105.4  351.53  5294.9  362.95
  5405.6  377.09    5466  382.41  5525.3  390.48  5530.3  395.27  5566.6  404.03
  5616.2   408.9  5626.9  414.12  5677.2  420.15  5712.2  420.41  5779.8  414.88
#Mann= 10 ,-1 , 0
  2308.4     .05       0  2558.3     .16       0  2757.6     .05       0
  3785.4     .16       0  4130.3     .12       0  4286.6     .05       0
  4897.6     .16       0  4990.1     .07       0  4996.1     .16       0
  5105.4     .12       0
Bank Sta=4962.9,5033.4
XS Rating Curve= 0 ,0
Exp/Cntr=0.3,0.1

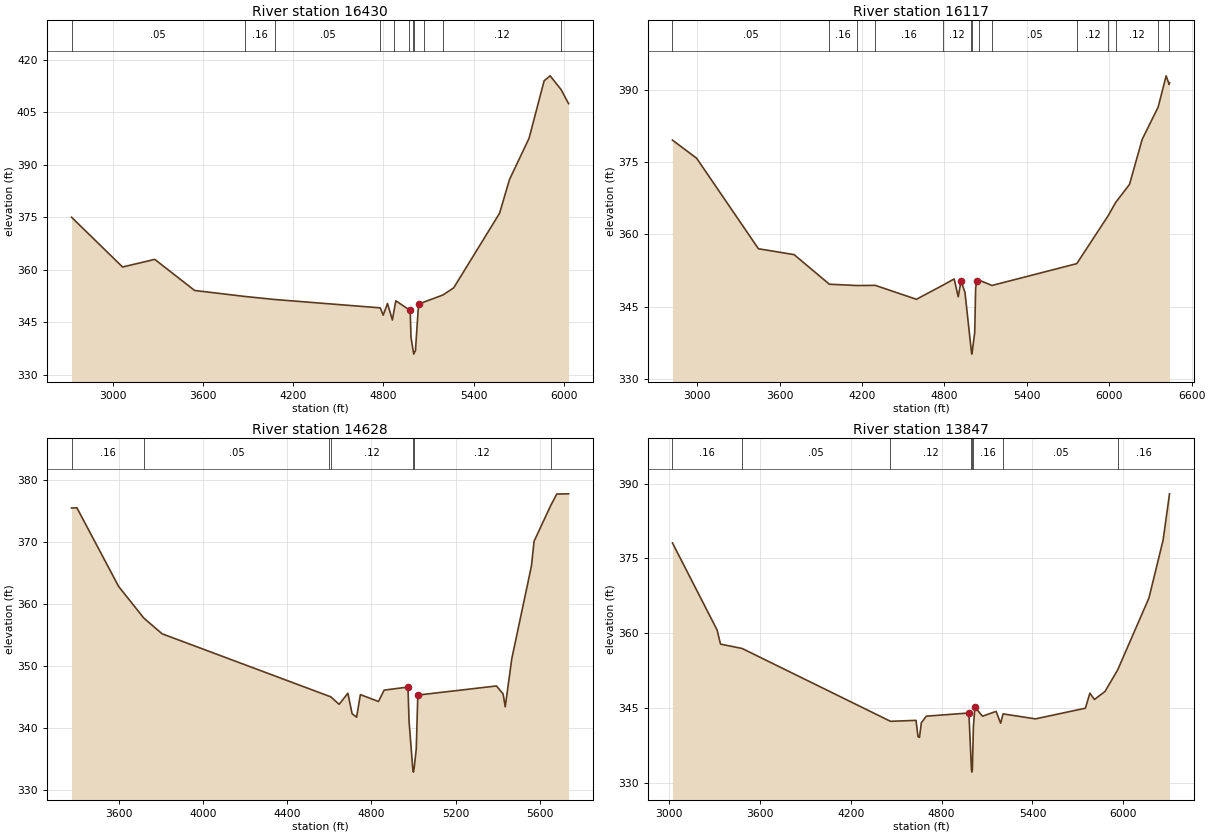
Type RM Length L Ch R = 1 ,16430   ,313,313,313
BEGIN DESCRIPTION:
GRINDSTONE CREEK 22.0
END DESCRIPTION:
XS GIS Cut Line= 3
      3555700.97     10629993.23      3556210.95     10627508.46
      3556145.84     10626738.07
#Sta/Elev= 30
  2722.8  375.02  3062.8  360.78  3277.2  362.96  3542.6  354.07  3876.8  352.36
  4075.4  351.49  4778.6   349.1  4798.2  347.01  4826.8  350.36  4859.5  345.63
  4869.9  348.21  4882.3  351.12  4969.2   348.6    4978  348.57  4983.1  340.77
  4999.4  336.37  5002.1  335.87  5005.4  336.37  5012.6  336.71  5033.5  350.08
  5068.5  350.74  5196.5  352.79  5267.7  354.83  5572.9  376.14    5639  385.78
  5769.4  397.58  5869.8  414.02  5909.9  415.44  5982.6  411.52  6032.5  407.49
#Mann= 11 ,-1 , 0
  2722.8     .05       0  3876.8     .16       0  4075.4     .05       0
  4778.6     .12       0  4869.9     .16       0  4969.2     .12       0
  4999.4     .07       0  5005.4     .12       0  5068.5     .16       0
  5196.5     .12       0  5982.6     .16       0
Bank Sta=4978,5033.5
XS Rating Curve= 0 ,0
Exp/Cntr=0.3,0.1

Type RM Length L Ch R = 1 ,16117   ,1489,1489,1489
BEGIN DESCRIPTION:
GRINDSTONE CREEK 21.0
END DESCRIPTION:
XS GIS Cut Line= 4
       3556286.9     10630156.04       3556243.5     10628105.24
      3556460.51     10627866.53      3557673.49     10627584.94
#Sta/Elev= 30
  2819.6  379.53  2995.5  375.79  3445.6  357.05  3705.6  355.83  3962.1  349.71
  4161.5  349.44  4296.6  349.47  4595.8  346.59  4787.4  349.49  4870.9   350.8
  4900.1   347.1    4921  350.36  4949.4  348.03  4996.3  335.74  4999.1  335.24
  5002.3  335.74  5020.4  339.72  5027.1  348.86  5034.6   350.3  5053.3  350.54
    5146  349.45  5763.5  353.97  5992.8  363.92  6046.5  366.63  6147.3  370.36
  6239.7  379.69    6356  386.37  6414.2  392.84  6436.3  391.05  6438.7  391.41
#Mann= 14 ,-1 , 0
  2819.6     .05       0  3962.1     .16       0  4161.5     .05       0
  4296.6     .16       0  4787.4     .12       0  4996.3     .07       0
  5002.3     .12       0  5053.3     .16       0    5146     .05       0
  5763.5     .12       0  5992.8     .05       0  6046.5     .12       0
    6356     .05       0  6436.3     .16       0
Bank Sta=4921,5034.6
XS Rating Curve= 0 ,0
Exp/Cntr=0.3,0.1

Type RM Length L Ch R = 1 ,14628   ,781,781,781
BEGIN DESCRIPTION:
GRINDSTONE CREEK 19.0
END DESCRIPTION:
XS GIS Cut Line= 2
       3556885.7     10630294.71      3557519.39     10628020.34
#Sta/Elev= 30
  3375.9  375.41  3401.4  375.46  3599.6  362.81  3719.2  357.72  3806.2  355.19
  4599.4  345.15  4606.3  345.08  4647.1  343.85  4688.6  345.63  4708.6  342.34
  4730.1  341.78    4748  345.41  4833.9   344.3    4861  346.13    4974  346.62
  4979.3  341.09    4997  333.44  4999.8  332.94    5003  333.44  5013.4  336.67
  5020.8  345.33  5394.5   346.8  5425.9  345.52    5436  343.45  5467.2  351.18
  5560.6  366.11  5573.1  370.07  5651.8   375.8  5680.9  377.67  5736.9   377.7
#Mann= 7 ,-1 , 0
  3375.9     .16       0  3719.2     .05       0  4599.4     .16       0
  4606.3     .12       0    4997     .07       0    5003     .12       0
  5651.8     .05       0
Bank Sta=4974,5020.8
XS Rating Curve= 0 ,0
Exp/Cntr=0.3,0.1

Type RM Length L Ch R = 1 ,13847   ,997,997,997
BEGIN DESCRIPTION:
GRINDSTONE CREEK 17.0
END DESCRIPTION:
XS GIS Cut Line= 3
      3557317.57     10630539.03      3558081.45     10628915.78
       3558064.1     10627423.99
#Sta/Elev= 30
  3020.2  378.11  3315.2  360.66    3338  357.82  3480.6  356.95  4461.6  342.34
  4630.4  342.53  4643.6  339.24  4653.2  339.12  4665.7  342.07  4698.7  343.37
  4979.8  344.01  4996.8  332.65  4999.6  332.15  5002.8  332.65  5005.4  335.89
  5009.8  341.37  5019.8  345.18  5069.8  343.37  5159.8  344.33  5189.8  341.96
  5205.9  343.83  5419.8  342.83  5749.9  344.97  5779.9  347.99  5809.9  346.72
  5879.9  348.33  5963.7  352.67  6169.9  367.05  6263.7  378.66  6306.1  387.96
#Mann= 8 ,-1 , 0
  3020.2     .16       0  3480.6     .05       0  4461.6     .12       0
  4996.8     .07       0  5002.8     .12       0  5005.4     .16       0
  5205.9     .05       0  5963.7     .16       0
Bank Sta=4979.8,5019.8
XS Rating Curve= 0 ,0
Exp/Cntr=0.3,0.1