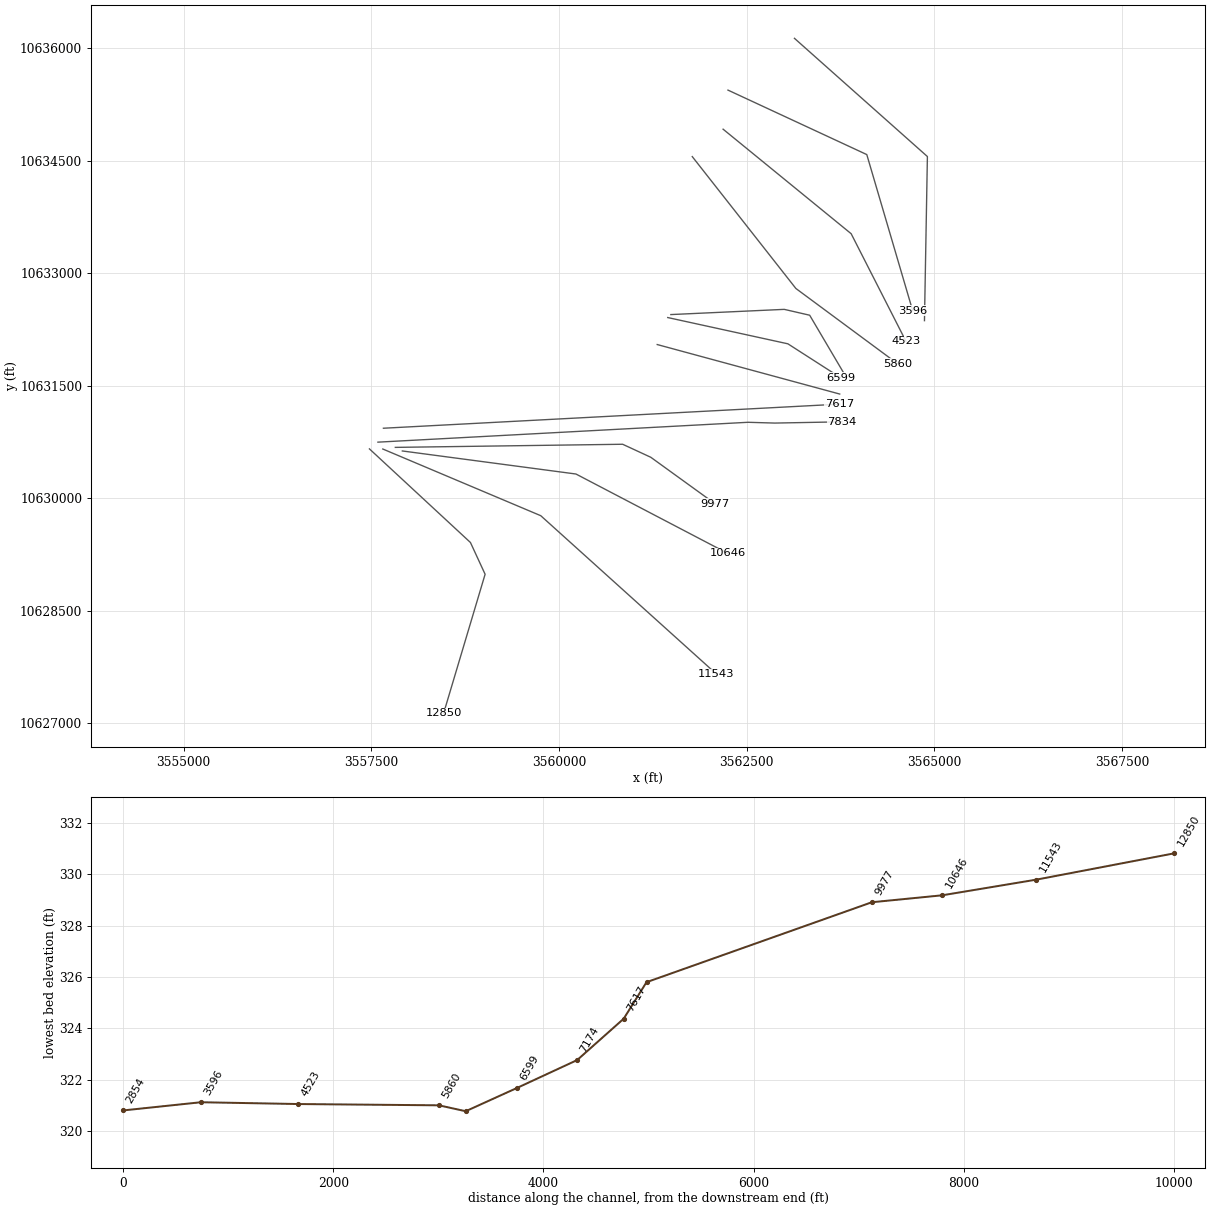
HEC-RAS study GRINDSTONE CREEK.prj: GRINDSTONE CREEK Base Level Engineering

--- GRINDSTONE CREEK.g01 (geometry) --- (continued)

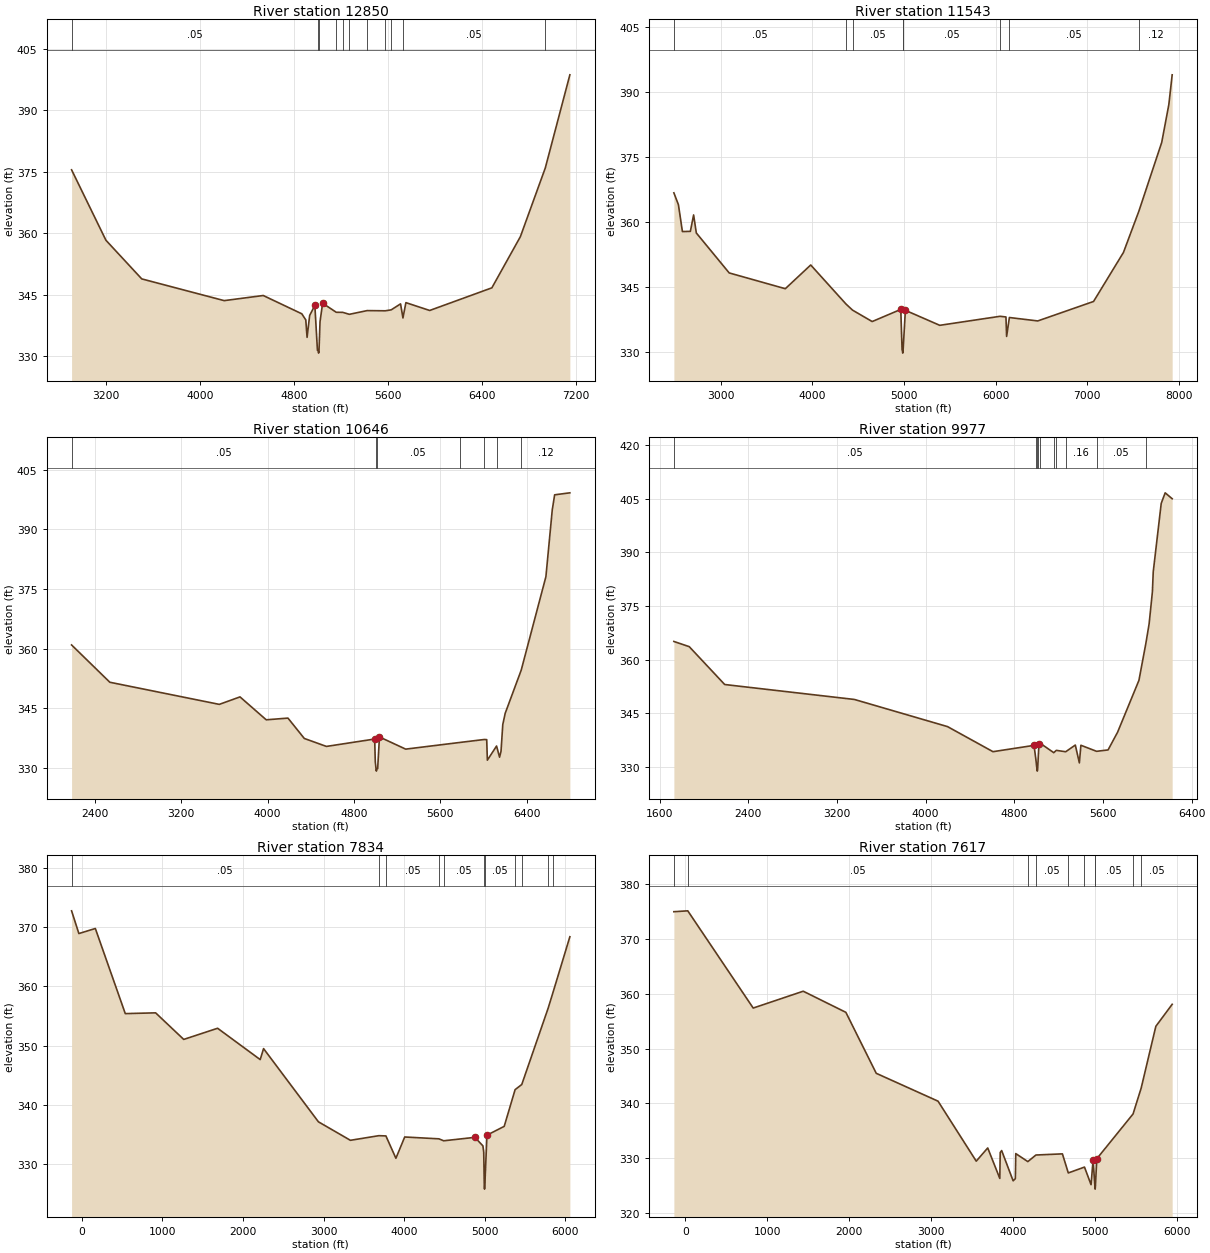
Type RM Length L Ch R = 1 ,12850   ,1307,1307,1307
BEGIN DESCRIPTION:
GRINDSTONE CREEK 16.0
END DESCRIPTION:
XS GIS Cut Line= 4
        3557476.     10630659.69      3558821.47     10629411.88
      3559016.78      10628988.7      3558463.69     10627134.23
#Sta/Elev= 30
  2910.4  375.51  3202.5  358.33  3506.9  348.91  4207.7  343.61  4539.9  344.86
  4867.6   340.4  4901.5  338.91  4912.5  334.66  4934.5  339.99  4978.6  342.46
  5000.6  331.51  5007.8  331.31  5010.5  330.81  5013.8  331.31  5022.6  338.48
  5044.7  342.98  5160.6  340.77  5216.2  340.75  5271.8  340.27  5423.3  341.18
  5577.5  341.13  5627.6  341.36  5707.3  342.82  5727.6  339.39  5752.6  343.12
    5955  341.21  6483.5  346.73    6726  359.21  6937.9  375.97  7146.7  398.67
#Mann= 11 ,-1 , 0
  2910.4     .05       0  5007.8     .03       0  5013.8     .05       0
  5160.6     .16       0  5216.2     .12       0  5271.8     .05       0
  5423.3     .16       0  5577.5     .05       0  5627.6     .16       0
  5727.6     .05       0  6937.9     .12       0
Bank Sta=4978.6,5044.7
XS Rating Curve= 0 ,0
Exp/Cntr=0.3,0.1

Type RM Length L Ch R = 1 ,11543   ,897,897,897
BEGIN DESCRIPTION:
GRINDSTONE CREEK 14.0
END DESCRIPTION:
XS GIS Cut Line= 3
      3557653.97     10630657.95       3559758.1     10629769.08
      3562098.34       10627658.
#Sta/Elev= 30
  2490.2  366.74  2539.7  364.01  2583.2  357.82    2670  357.86  2705.4  361.65
  2735.1  357.49  3093.6  348.28  3705.9  344.64  3982.9  350.11  4369.1  341.08
  4439.4   339.7  4653.5  337.07  4965.5  339.87  4979.7  330.56  4984.2  330.29
  4986.9  329.79  4990.2  330.29  5015.6  339.66  5390.7   336.2  6048.2  338.28
  6112.7  338.13  6120.1  333.64  6150.2     338  6459.8  337.21  7068.5   341.7
  7394.3  352.99  7562.3  362.48  7812.1  378.37  7889.8   387.1  7926.1  393.95
#Mann= 8 ,-1 , 0
  2490.2     .05       0  4369.1     .16       0  4439.4     .05       0
  4984.2     .03       0  4990.2     .05       0  6048.2     .12       0
  6150.2     .05       0  7562.3     .12       0
#XS Ineff= 1 ,-1
  6087.5 6169.32  337.92
Permanent Ineff=
       F
Bank Sta=4965.5,5015.6
XS Rating Curve= 0 ,0
Exp/Cntr=0.3,0.1

Type RM Length L Ch R = 1 ,10646   ,669,669,669
BEGIN DESCRIPTION:
GRINDSTONE CREEK 13.0
END DESCRIPTION:
XS GIS Cut Line= 3
      3557914.37     10630631.93      3560226.85     10630324.64
      3562246.16     10629268.14
#Sta/Elev= 30
  2186.5   360.9  2540.6  351.52  3553.7  345.96  3745.3  347.84  3988.1  342.08
  4189.2  342.51  4340.5  337.39  4545.2  335.39  4991.7  337.25  4997.4  331.49
  5004.7  329.68  5007.5  329.18  5010.7  329.68  5019.4   329.8  5035.9  337.77
  5278.7  334.71  5777.9  336.38  6005.9  337.13  6028.6   337.1  6034.7  331.94
  6119.9  335.49  6147.6  332.68    6161  334.15  6177.5  340.91  6199.5   343.7
  6347.9  354.56  6576.5  378.06  6635.3  394.85  6657.4  398.64  6798.3  399.14
#Mann= 7 ,-1 , 0
  2186.5     .05       0  5004.7     .03       0  5010.7     .05       0
  5777.9     .16       0  6005.9     .12       0  6119.9     .05       0
  6347.9     .12       0
#XS Ineff= 1 ,-1
 6008.52 6190.34  337.12
Permanent Ineff=
       F
Bank Sta=4991.7,5035.9
XS Rating Curve= 0 ,0
Exp/Cntr=0.3,0.1

Type RM Length L Ch R = 1 ,9977    ,2143,2143,2143
BEGIN DESCRIPTION:
GRINDSTONE CREEK 11.0
END DESCRIPTION:
XS GIS Cut Line= 4
      3557821.02     10630679.67      3560848.81     10630721.34
      3561223.81     10630547.73      3562077.95     10629929.69
#Sta/Elev= 30
  1728.6  365.11  1867.2  363.66  2187.2  353.09  3357.3  348.92  4197.4  341.34
  4607.5  334.34    4978   336.1  4994.5  332.17  5004.4  329.41  5007.2  328.91
  5010.4  329.41    5022  336.53    5035  336.66  5155.9  334.06  5179.1  334.71
  5263.3  334.32  5350.4  336.19  5386.9  331.21  5400.7  336.13  5542.2  334.44
  5645.9  334.83  5731.8  339.78  5924.3  354.25  5986.2  364.46  6016.4  370.07
  6045.8  378.96  6053.4  384.56  6125.4  403.67    6161  406.61  6224.2  404.96
#Mann= 10 ,-1 , 0
  1728.6     .05       0  4994.5     .16       0  5004.4     .07       0
  5010.4     .16       0    5035     .05       0  5155.9     .16       0
  5179.1     .05       0  5263.3     .16       0  5542.2     .05       0
  5986.2     .12       0
#XS Ineff= 1 ,-1
 5343.18 5411.36  335.14
Permanent Ineff=
       F
Bank Sta=4978,5022
XS Rating Curve= 0 ,0
Exp/Cntr=0.3,0.1

Type RM Length L Ch R = 1 ,7834    ,217,217,217
BEGIN DESCRIPTION:
GRINDSTONE CREEK 9.0
END DESCRIPTION:
XS GIS Cut Line= 4
      3557589.16      10630749.4      3562517.95     10631014.15
      3562874.72     10631003.74      3563768.85     10631020.41
#Sta/Elev= 30
  -128.6  372.72     -38  368.89   166.5  369.74   538.2  355.39   914.9  355.52
  1263.9  351.04  1684.5  352.92  2213.4  347.64  2255.3  349.49  2936.3  337.15
  3333.5  334.03  3685.9  334.81  3774.2  334.77  3898.5     331  4007.8  334.59
  4432.2  334.28  4491.7  333.95    4879  334.53    4979  333.09    4989  332.03
    4996   326.3  4998.8   325.8    5002   326.3    5029   334.9  5243.1  336.38
  5378.5  342.57  5461.3  343.44  5789.7  356.34  5849.2  358.97  6058.5  368.35
#Mann= 11 ,-1 , 0
  -128.6     .05       0  3685.9     .16       0  3774.2     .05       0
  4432.2     .16       0  4491.7     .05       0    4996     .03       0
    5002     .05       0  5378.5      .1       0  5461.3     .05       0
  5789.7     .12       0  5849.2     .05       0
#XS Ineff= 1 ,-1
 3777.27 4022.73  334.27
Permanent Ineff=
       F
Bank Sta=4879,5029
XS Rating Curve= 0 ,0
Exp/Cntr=0.3,0.1

Type RM Length L Ch R = 1 ,7617    ,443,443,443
BEGIN DESCRIPTION:
GRINDSTONE CREEK 8.0
END DESCRIPTION:
XS GIS Cut Line= 2
      3557662.44     10630934.99      3563738.76     10631256.17
#Sta/Elev= 30
    -139  374.97    30.7  375.13   829.5   357.4  1440.4  360.47  1961.1  356.62
  2332.1   345.5  3086.6  340.42  3553.3  329.48  3693.5  331.89    3841  326.33
    3846  331.06  3863.7  331.41  4003.9  325.89  4030.8  326.29  4035.9  330.86
  4183.1   329.4    4282   330.6  4605.4  330.81  4677.4  327.33  4875.1   328.4
  4955.3  325.19  4980.1  329.69  5002.3  324.88  5005.1  324.38  5008.3  324.88
  5025.4  329.92  5468.3  338.09  5567.2   342.8  5746.4  354.07  5945.8  358.08
#Mann= 10 ,-1 , 0
    -139     .08       0    30.7     .05       0  4183.1     .08       0
    4282     .05       0  4677.4     .08       0  4875.1     .05       0
  5002.3     .04       0  5008.3     .05       0  5468.3      .1       0
  5567.2     .05       0
Bank Sta=4980.1,5025.4
XS Rating Curve= 0 ,0
Exp/Cntr=0.3,0.1

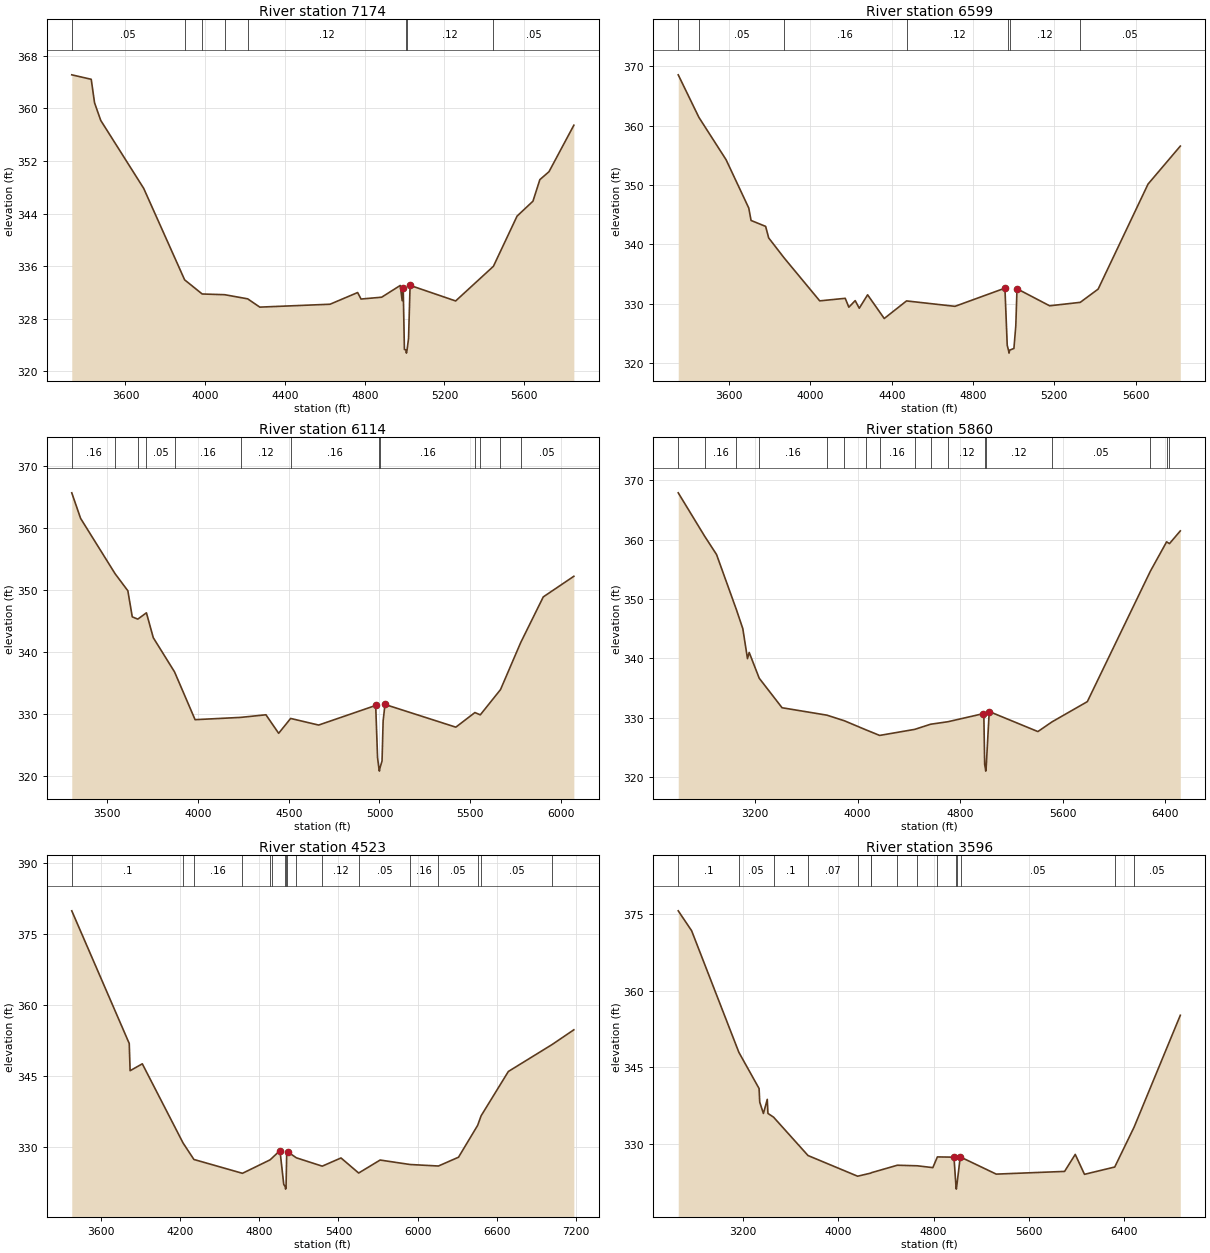
Type RM Length L Ch R = 1 ,7174    ,575,575,575
BEGIN DESCRIPTION:
GRINDSTONE CREEK 7.0
END DESCRIPTION:
XS GIS Cut Line= 2
      3561309.32     10632050.44      3563739.88     10631390.71
#Sta/Elev= 30
  3330.5  365.12  3428.1  364.44  3444.8  360.86  3475.9  358.18  3691.2  347.85
  3896.7  333.92  3984.7  331.77  4097.8  331.66    4213  331.03  4273.7  329.77
    4626  330.21  4764.5  331.99  4781.5     331  4885.1  331.28  4978.3  333.07
  4987.8  330.75    4993  332.74  4999.1  323.32  5006.4  323.27  5009.2  322.77
  5012.4  323.27  5019.8     325  5027.6  333.08  5256.1  330.71  5445.5  335.98
  5564.2  343.62  5643.9  345.89  5678.5  349.17  5724.4  350.38    5849  357.45
#Mann= 8 ,-1 , 0
  3330.5     .05       0  3896.7     .16       0  3984.7     .05       0
  4097.8     .16       0    4213     .12       0  5006.4     .07       0
  5012.4     .12       0  5445.5     .05       0
Bank Sta=4993,5027.6
XS Rating Curve= 0 ,0
Exp/Cntr=0.3,0.1

Type RM Length L Ch R = 1 ,6599    ,485,485,485
BEGIN DESCRIPTION:
GRINDSTONE CREEK 6.0
END DESCRIPTION:
XS GIS Cut Line= 3
      3561449.57      10632410.2      3563049.61     10632060.19
      3563749.57     10631610.21
#Sta/Elev= 30
  3349.9  368.54  3451.4  361.39  3585.4  354.24  3696.9  346.11  3708.2  344.02
  3779.9  343.02  3794.9  341.08  3870.7  337.72    4046  330.48  4171.4  330.91
  4189.3  329.41  4220.4  330.52  4240.5  329.24  4281.5   331.5  4363.4  327.51
    4473  330.47  4711.4  329.56  4957.1  332.62  4968.4     323  4974.5  322.18
  4977.3  321.68  4980.5  322.18  5001.3  322.47  5010.6  326.29  5016.5  332.52
    5177  329.65  5327.6  330.23  5415.7  332.46  5661.1  350.14  5819.9  356.54
#Mann= 7 ,-1 , 0
  3349.9     .16       0  3451.4     .05       0  3870.7     .16       0
    4473     .12       0  4974.5     .07       0  4980.5     .12       0
  5327.6     .05       0
Bank Sta=4957.1,5016.5
XS Rating Curve= 0 ,0
Exp/Cntr=0.3,0.1

Type RM Length L Ch R = 1 ,6114    ,254,254,254
BEGIN DESCRIPTION:
GRINDSTONE CREEK 5.0
END DESCRIPTION:
XS GIS Cut Line= 4
      3561490.97     10632449.91      3563001.41     10632519.36
      3563339.95     10632441.24      3563800.01     10631660.01
#Sta/Elev= 30
  3304.9  365.73  3353.6   361.6  3543.7  352.66  3613.9  349.91  3638.2   345.7
  3668.6  345.33  3716.2  346.35    3754  342.33  3871.1  336.81  3984.3  329.09
  4235.7  329.46  4374.7  329.88  4444.7  326.89  4510.7  329.29    4665  328.22
  4979.3  331.39  4989.6  322.97  4996.8  321.28  4999.6  320.78  5002.8  321.28
  5014.3  322.43  5020.3  328.89  5030.6  331.55  5420.9  327.88  5525.8  330.24
  5555.6  329.87  5666.8  333.94    5778  341.53  5902.6  348.92    6071  352.25
#Mann= 13 ,-1 , 0
  3304.9     .16       0  3543.7     .05       0  3668.6     .16       0
  3716.2     .05       0  3871.1     .16       0  4235.7     .12       0
  4510.7     .16       0  4996.8     .07       0  5002.8     .16       0
  5525.8     .16       0  5555.6     .05       0  5666.8     .16       0
    5778     .05       0
Bank Sta=4979.3,5030.6
XS Rating Curve= 0 ,0
Exp/Cntr=0.3,0.1

Type RM Length L Ch R = 1 ,5860    ,1337,1337,1337
BEGIN DESCRIPTION:
GRINDSTONE CREEK 4.0
END DESCRIPTION:
XS GIS Cut Line= 3
      3561776.11     10634555.47      3563156.32     10632797.66
      3564510.37     10631795.15
#Sta/Elev= 30
  2599.1  367.86  2805.2  360.56  2898.1  357.48  3053.6  348.17  3103.3  344.99
  3139.8  339.95  3153.1  340.99  3231.4  336.65  3409.7  331.68  3760.2  330.43
  3896.9  329.48  4065.6  327.95  4171.7  327.02  4445.6  328.04  4568.6   328.9
  4705.8  329.33  4976.9  330.67  4985.3  330.11  4991.5  322.13  4996.9  321.51
  4999.6  321.01  5002.9  321.51    5027  331.04  5406.9  327.67  5516.2  329.29
    5793  332.71  6285.1  354.67  6411.9  359.61  6434.2  359.31  6518.8  361.45
#Mann= 17 ,-1 , 0
  2599.1      .1       0  2805.2     .16       0  3053.6     .12       0
  3231.4     .16       0  3760.2     .12       0  3896.9     .16       0
  4065.6     .05       0  4171.7     .16       0  4445.6     .12       0
  4568.6     .16       0  4705.8     .12       0  4996.9     .07       0
  5002.9     .12       0  5516.2     .05       0  6285.1     .16       0
  6411.9     .12       0  6434.2     .16       0
Bank Sta=4976.9,5027
XS Rating Curve= 0 ,0
Exp/Cntr=0.3,0.1

Type RM Length L Ch R = 1 ,4523    ,927,927,927
BEGIN DESCRIPTION:
GRINDSTONE CREEK 3.0
END DESCRIPTION:
XS GIS Cut Line= 3
      3562186.72     10634920.98      3563892.43     10633527.77
       3564621.6     10632095.47
#Sta/Elev= 30
  3376.6  379.82  3812.7  351.81  3819.3  346.06  3911.8  347.52  4221.2   330.8
  4303.4  327.32  4671.7   324.4  4881.2  327.24    4895  327.59  4956.4  329.21
  4985.1  322.06  4996.5  321.56  4999.2  321.06  5002.5  321.56  5007.2  328.26
  5013.1  328.89  5013.8  328.96  5080.8  327.67  5277.1  325.91  5419.5  327.64
  5553.6  324.46  5716.3   327.2  5943.1  326.26  6158.9  325.94  6311.2   327.8
  6456.6  334.54  6482.5  336.54  6689.3   345.9  7021.9   351.6  7186.2   354.7
#Mann= 17 ,-1 , 0
  3376.6      .1       0  4221.2     .05       0  4303.4     .16       0
  4671.7     .12       0  4881.2     .16       0    4895     .12       0
  4996.5     .07       0  5002.5     .12       0  5013.1     .16       0
  5080.8     .05       0  5277.1     .12       0  5553.6     .05       0
  5943.1     .16       0  6158.9     .05       0  6456.6     .16       0
  6482.5     .05       0  7021.9     .12       0
Bank Sta=4956.4,5013.8
XS Rating Curve= 0 ,0
Exp/Cntr=0.3,0.1

Type RM Length L Ch R = 1 ,3596    ,742,742,742
BEGIN DESCRIPTION:
GRINDSTONE CREEK 2.0
END DESCRIPTION:
XS GIS Cut Line= 3
      3562251.76     10635441.85      3564100.76     10634582.46
      3564712.74     10632499.14
#Sta/Elev= 30
  2659.4  375.64  2771.5  371.75  3167.8  347.93  3337.4  340.83  3342.9  338.16
  3373.8  335.95    3406  338.71  3411.5  335.96  3458.6  335.23  3747.8  327.71
  4163.5  323.66  4274.6  324.27  4279.4  324.35  4496.9  325.81  4664.3   325.7
  4794.5  325.34  4832.5  327.44  4971.7  327.39  4988.6  321.63  4991.3  321.13
  4994.6  321.63  5023.8  327.36  5033.5  327.34  5326.1  324.07  5899.3   324.6
  5988.6  327.93  6066.1  324.03  6319.7  325.46  6482.3  333.28  6869.7  355.18
#Mann= 15 ,-1 , 0
  2659.4      .1       0  3167.8     .05       0  3458.6      .1       0
  3747.8     .07       0  4163.5     .05       0  4274.6      .1       0
  4279.4     .07       0  4496.9     .12       0  4664.3     .07       0
  4832.5     .12       0  4988.6     .07       0  4994.6     .12       0
  5033.5     .05       0  6319.7     .16       0  6482.3     .05       0
#XS Ineff= 1 ,-1
 5987.45 6387.96  327.45
Permanent Ineff=
       F
Bank Sta=4971.7,5023.8
XS Rating Curve= 0 ,0
Exp/Cntr=0.3,0.1

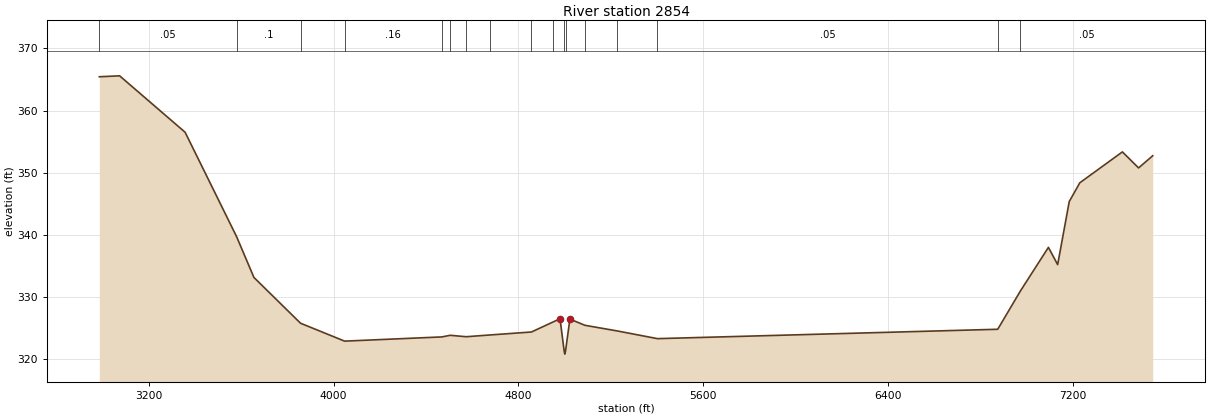
Type RM Length L Ch R = 1 ,2854    ,0,0,0
BEGIN DESCRIPTION:
GRINDSTONE CREEK 1.0
END DESCRIPTION:
XS GIS Cut Line= 3
      3563137.24     10636131.92      3564908.05     10634556.41
      3564868.99      10632368.9
#Sta/Elev= 30
  2986.4  365.44  3074.2  365.59  3357.6  356.51  3580.5   339.7  3655.3  333.15
  3857.1  325.78  4047.8   322.9  4468.9  323.58  4504.5  323.84  4573.6  323.61
  4675.7  323.89  4856.1  324.37  4950.1  325.99  4979.8   326.5  4997.7  321.31
  5000.5  320.81  5003.7  321.31  5022.5  326.45  5087.4  325.45  5224.6  324.56
  5401.5   323.3  6873.8  324.81  6971.9  330.97  7093.1  337.99  7133.1  335.21
  7183.2  345.36    7229  348.38  7413.2  353.35  7483.2  350.77  7544.5  352.73
#Mann= 17 ,-1 , 0
  2986.4     .05       0  3580.5      .1       0  3857.1     .12       0
  4047.8     .16       0  4468.9     .12       0  4504.5     .16       0
  4573.6     .07       0  4675.7     .16       0  4856.1     .07       0
  4950.1     .12       0  4997.7     .07       0  5003.7     .12       0
  5087.4     .16       0  5224.6     .12       0  5401.5     .05       0
  6873.8     .16       0  6971.9     .05       0
Bank Sta=4979.8,5022.5
XS Rating Curve= 0 ,0
Exp/Cntr=0.3,0.1

Chan Stop Cuts=-1
Use User Specified Reach Order=0
Composite Channel Slope=5