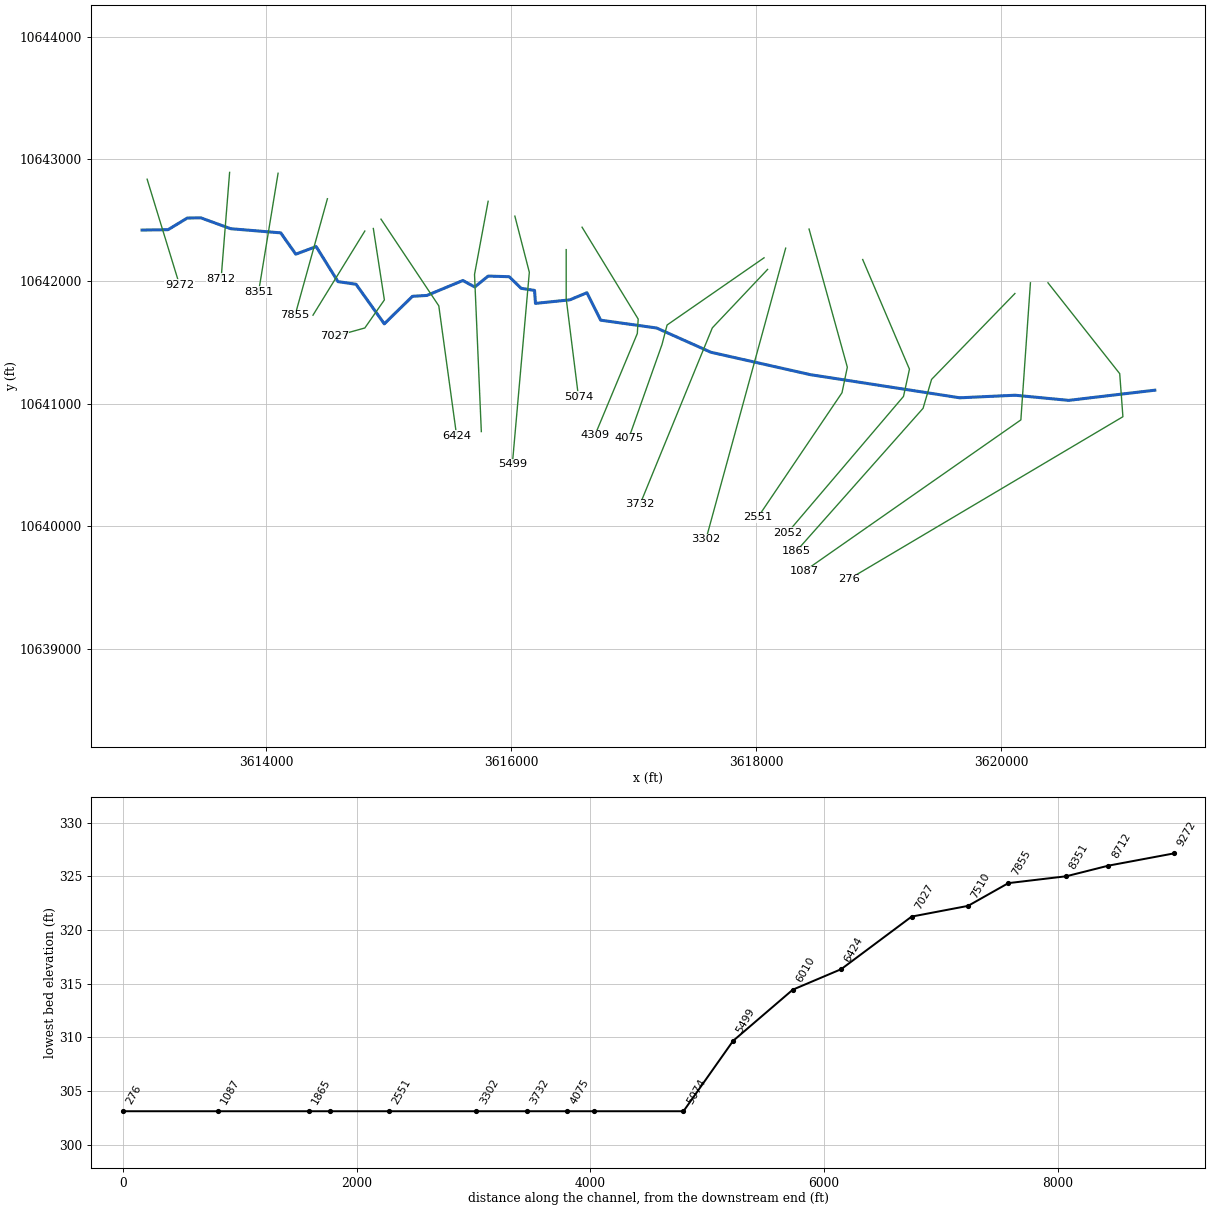
--- HARPERS BRANCH.prj (project) ---

Proj Title=HARPERS BRANCH Base Level Engineering
Current Plan=p01
Default Exp/Contr=0.3,0.1
English Units
Geom File=g01
Flow File=f01
Plan File=p01
BEGIN DESCRIPTION:
HARPERS BRANCH
END DESCRIPTION:

--- HARPERS BRANCH.p01 (plan) ---

Plan Title=Multiple Run
Short Identifier=Multiple
Geom File=g01
Flow File=f01
Subcritical Flow
K Sum by GR= 0
Std Step Tol= 0.01
Critical Tol= 0.01
Num of Std Step Trials= 20
Max Error Tol= 0.3
Flow Tol Ratio= 0.001
Split Flow NTrial= 30
Split Flow Tol= 0.02
Split Flow Ratio= 0.02
Log Output Level= 0
Friction Slope Method= 1
Unsteady Friction Slope Method= 2
Unsteady Bridges Friction Slope Method= 1
Parabolic Critical Depth
Global Vel Dist=  1 , 1 , 1
Global Log Level= 0
CheckData=True
Encroach Param= -1, 0, 0, 0
BEGIN DESCRIPTION:
Multiple Run
END DESCRIPTION:

--- HARPERS BRANCH.f01 (steady flow) ---

Flow Title=Multiple
Number of Profiles=7
Profile Names=10-year,25-year,50-year,1pct_min,100-year,1pct_plu,500-year
River Rch & RM= HARPERS BRANCH,Reach-1,9272
    1738    2451    3058    2787    3769    5098    5706
River Rch & RM= HARPERS BRANCH,Reach-1,7855
    2571    3694    4665    4295    5809    7856    8980
River Rch & RM= HARPERS BRANCH,Reach-1,4075
    2901    4181    5289    4875    6593    8916   10215
River Rch & RM= HARPERS BRANCH,Reach-1,1865
    3009    4259    5319    4875    6593    8916   10215
Boundary for River Rch & Prof#=HARPERS BRANCH,Reach-1,1
Up Type=0
Dn Type=3
Dn Slope=0.005
Boundary for River Rch & Prof#=HARPERS BRANCH,Reach-1,2
Up Type=0
Dn Type=3
Dn Slope=0.005
Boundary for River Rch & Prof#=HARPERS BRANCH,Reach-1,3
Up Type=0
Dn Type=3
Dn Slope=0.005
Boundary for River Rch & Prof#=HARPERS BRANCH,Reach-1,4
Up Type=0
Dn Type=3
Dn Slope=0.005
Boundary for River Rch & Prof#=HARPERS BRANCH,Reach-1,5
Up Type=0
Dn Type=3
Dn Slope=0.005
Boundary for River Rch & Prof#=HARPERS BRANCH,Reach-1,6
Up Type=0
Dn Type=3
Dn Slope=0.005
Boundary for River Rch & Prof#=HARPERS BRANCH,Reach-1,7
Up Type=0
Dn Type=3
Dn Slope=0.005

--- HARPERS BRANCH.g01 (geometry) ---

Geom Title=Existing Conditions

River Reach=HARPERS BRANCH,Reach-1
Reach XY= 30
      3612986.02     10642419.85      3613198.25     10642423.00
      3613355.25     10642518.00      3613465.00     10642520.00
      3613709.75     10642431.00      3614118.50     10642397.00
      3614241.25     10642223.00      3614407.75     10642285.00
      3614585.75     10641999.00      3614733.50     10641977.00
      3614964.25     10641654.00      3615194.25     10641879.00
      3615312.25     10641886.00      3615605.50     10642008.00
      3615702.75     10641955.00      3615812.25     10642044.00
      3615984.00     10642039.00      3616081.75     10641944.00
      3616191.25     10641927.00      3616198.75     10641821.00
      3616479.50     10641850.00      3616618.75     10641908.00
      3616731.00     10641684.00      3617188.25     10641620.00
      3617631.00     10641422.00      3618443.50     10641239.00
      3619663.50     10641050.00      3620115.00     10641071.00
      3620552.50     10641029.00      3621256.00     10641112.00

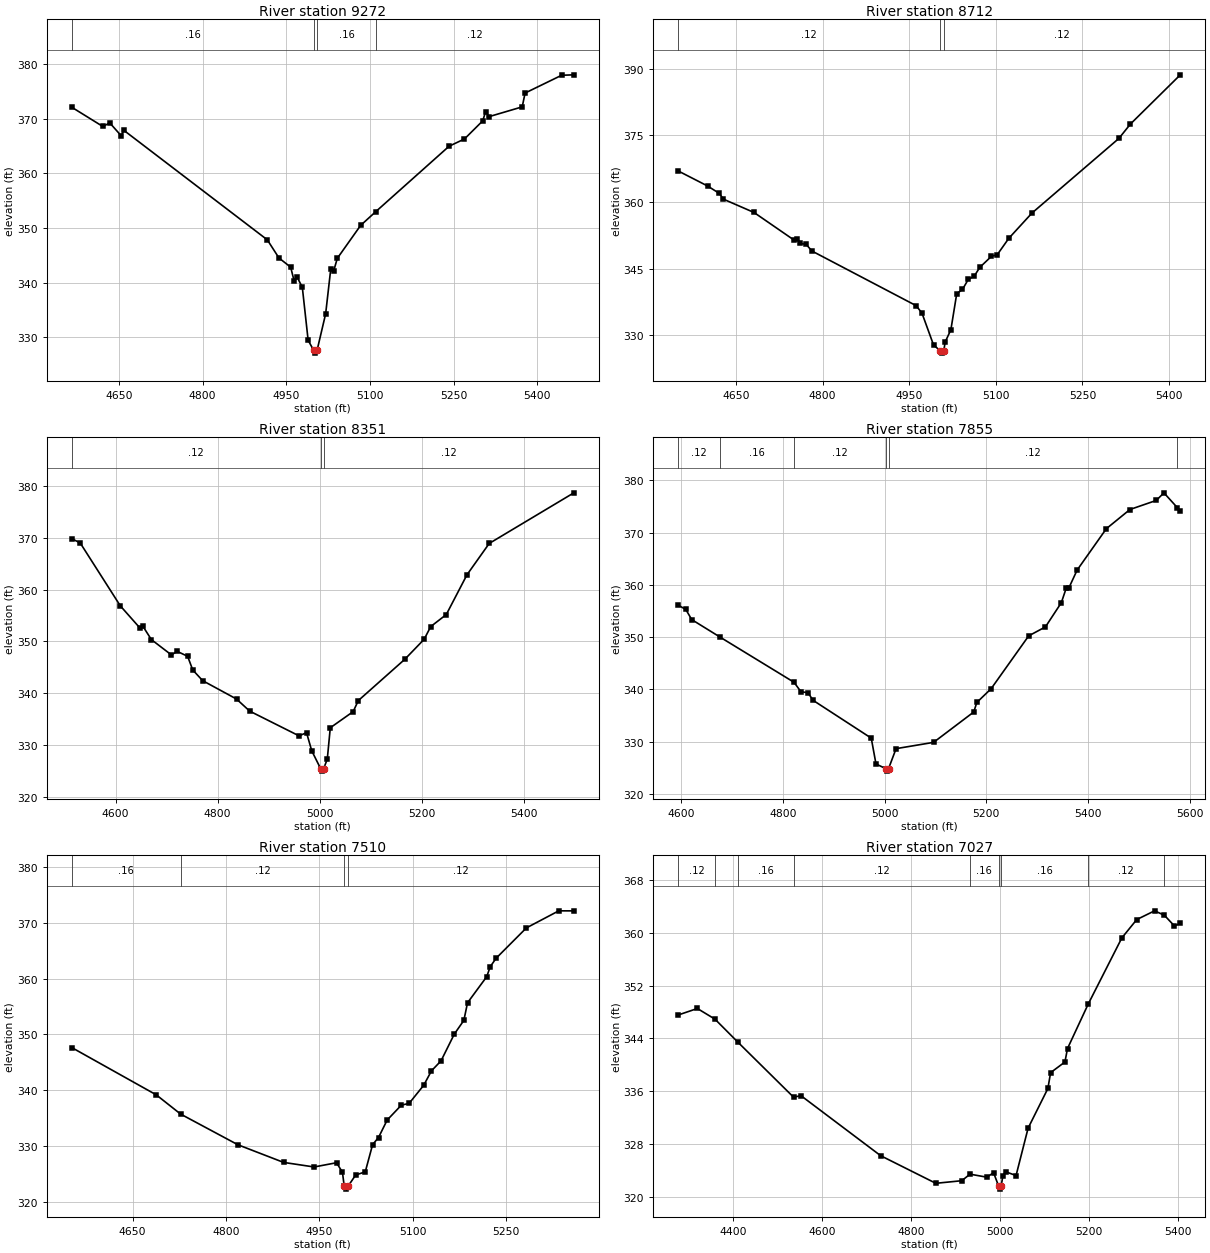
Type RM Length L Ch R = 1,9272,560,560,560
BEGIN DESCRIPTION:
HARPERS BRANCH 18.0
END DESCRIPTION:
XS GIS Cut Line= 2
      3613027.42     10642835.43      3613291.18     10641974.74
#Sta/Elev= 30
  4565.5  372.11  4621.1  368.60  4633.7  369.24  4653.9  366.92  4659.1  367.87
  4916.1  347.86  4937.0  344.54  4958.0  342.86  4964.3  340.29  4969.6  341.05
  4978.9  339.15  4989.3  329.49  4999.3  327.64  5002.1  327.14  5005.3  327.64
  5020.7  334.34  5029.8  342.48  5035.1  342.17  5041.6  344.48  5083.5  350.51
  5110.6  353.02  5242.0  364.98  5269.6  366.31  5302.3  369.62  5307.5  371.30
  5313.6  370.39  5373.1  372.18  5378.3  374.71  5443.8  377.96  5465.7  378.04
#Mann=4,-1,0
  4565.5    0.16       0  4999.3    0.07       0  5005.3    0.16       0
  5110.6    0.12       0
Bank Sta=4999.3,5005.3
Exp/Cntr=0.3,0.1

Type RM Length L Ch R = 1,8712,361,361,361
BEGIN DESCRIPTION:
HARPERS BRANCH 17.0
END DESCRIPTION:
XS GIS Cut Line= 2
      3613701.02     10642891.02      3613631.67     10642024.09
#Sta/Elev= 30
  4549.9  366.98  4600.9  363.59  4621.0  361.94  4628.1  360.64  4681.2  357.64
  4751.0  351.39  4756.1  351.74  4761.4  350.67  4771.4  350.48  4781.5  348.97
  4962.0  336.68  4972.1  335.00  4992.1  327.85  5003.9  326.50  5006.6  326.00
  5009.9  326.50  5012.2  328.47  5022.2  331.28  5032.3  339.36  5042.3  340.34
  5052.3  342.58  5062.4  343.28  5072.4  345.31  5092.5  347.79  5102.5  348.15
  5122.6  351.84  5162.7  357.52  5313.2  374.30  5333.2  377.54  5419.6  388.61
#Mann=3,-1,0
  4549.9    0.12       0  5003.9    0.07       0  5009.9    0.12       0
Bank Sta=5003.9,5009.9
Exp/Cntr=0.3,0.1

Type RM Length L Ch R = 1,8351,496,496,496
BEGIN DESCRIPTION:
HARPERS BRANCH 16.0
END DESCRIPTION:
XS GIS Cut Line= 2
      3614096.85     10642884.05      3613937.41     10641913.56
#Sta/Elev= 30
  4514.3  369.82  4530.8  369.00  4609.4  356.87  4648.2  352.56  4653.3  352.99
  4670.2  350.37  4709.4  347.42  4720.9  348.09  4741.2  347.15  4751.3  344.51
  4770.7  342.45  4837.0  338.91  4862.8  336.58  4959.5  331.81  4974.2  332.42
  4984.4  328.92  5001.7  325.51  5004.4  325.01  5007.7  325.51  5014.8  327.30
  5020.7  333.37  5065.5  336.48  5075.6  338.61  5166.8  346.58  5204.5  350.42
  5217.5  352.88  5247.9  355.19  5288.4  362.85  5332.0  368.90  5497.8  378.66
#Mann=3,-1,0
  4514.3    0.12       0  5001.7    0.07       0  5007.7    0.12       0
Bank Sta=5001.7,5007.7
Exp/Cntr=0.3,0.1

Type RM Length L Ch R = 1,7855,345,345,345
BEGIN DESCRIPTION:
HARPERS BRANCH 15.0
END DESCRIPTION:
XS GIS Cut Line= 2
      3614499.64     10642675.75      3614235.86     10641724.75
#Sta/Elev= 30
  4594.5  356.11  4609.4  355.28  4621.0  353.35  4676.7  350.00  4822.1  341.36
  4835.8  339.54  4849.3  339.38  4859.7  337.90  4973.9  330.68  4983.2  325.74
  5002.0  324.87  5004.7  324.37  5008.0  324.87  5022.7  328.67  5096.4  329.87
  5175.4  335.68  5181.4  337.50  5209.6  340.14  5283.4  350.24  5316.3  351.95
  5347.5  356.58  5357.1  359.35  5362.3  359.40  5378.6  362.82  5436.0  370.73
  5482.4  374.40  5534.2  376.14  5549.2  377.59  5575.5  374.76  5581.4  374.11
#Mann=6,-1,0
  4594.5    0.12       0  4676.7    0.16       0  4822.1    0.12       0
  5002.0    0.07       0  5008.0    0.12       0  5575.5    0.07       0
Bank Sta=5002,5008
Exp/Cntr=0.3,0.1

Type RM Length L Ch R = 1,7510,483,483,483
BEGIN DESCRIPTION:
HARPERS BRANCH 14.0
END DESCRIPTION:
XS GIS Cut Line= 2
      3614805.20     10642411.87      3614381.81     10641724.73
#Sta/Elev= 30
  4552.2  347.62  4688.0  339.15  4727.2  335.70  4819.3  330.20  4892.7  327.04
  4941.8  326.22  4977.8  326.98  4987.3  325.28  4990.2  322.75  4993.0  322.25
  4996.2  322.75  5008.6  324.78  5024.0  325.35  5035.8  330.23  5045.3  331.50
  5059.2  334.63  5082.0  337.30  5094.5  337.62  5118.0  340.87  5130.4  343.45
  5145.8  345.24  5167.1  350.03  5182.5  352.50  5188.4  355.65  5219.2  360.32
  5225.0  362.15  5234.6  363.66  5283.0  369.07  5335.1  372.13  5359.3  372.12
#Mann=4,-1,0
  4552.2    0.16       0  4727.2    0.12       0  4990.2    0.07       0
  4996.2    0.12       0
Bank Sta=4990.2,4996.2
Exp/Cntr=0.3,0.1

Type RM Length L Ch R = 1,7027,603,603,603
BEGIN DESCRIPTION:
HARPERS BRANCH 13.0
END DESCRIPTION:
XS GIS Cut Line= 4
      3614874.63     10642432.67      3614964.91     10641849.35
      3614805.19     10641620.18      3614555.16     10641550.73
#Sta/Elev= 30
  4276.6  347.55  4319.6  348.53  4359.2  346.92  4409.9  343.50  4536.2  335.12
  4552.3  335.38  4731.8  326.30  4855.9  322.13  4914.2  322.52  4932.8  323.51
  4970.9  323.05  4985.7  323.74  4996.9  321.75  4999.7  321.25  5002.9  321.75
  5006.7  323.27  5012.8  323.88  5036.3  323.30  5063.4  330.46  5107.9  336.45
  5114.0  338.84  5146.2  340.45  5152.0  342.48  5198.6  349.20  5274.2  359.19
  5307.7  361.96  5347.8  363.28  5369.9  362.61  5392.5  360.99  5405.7  361.40
#Mann=9,-1,0
  4276.6    0.12       0  4359.2    0.05       0  4409.9    0.16       0
  4536.2    0.12       0  4932.8    0.16       0  4996.9    0.07       0
  5002.9    0.16       0  5198.6    0.12       0  5369.9    0.16       0
Bank Sta=4996.9,5002.9
Exp/Cntr=0.3,0.1

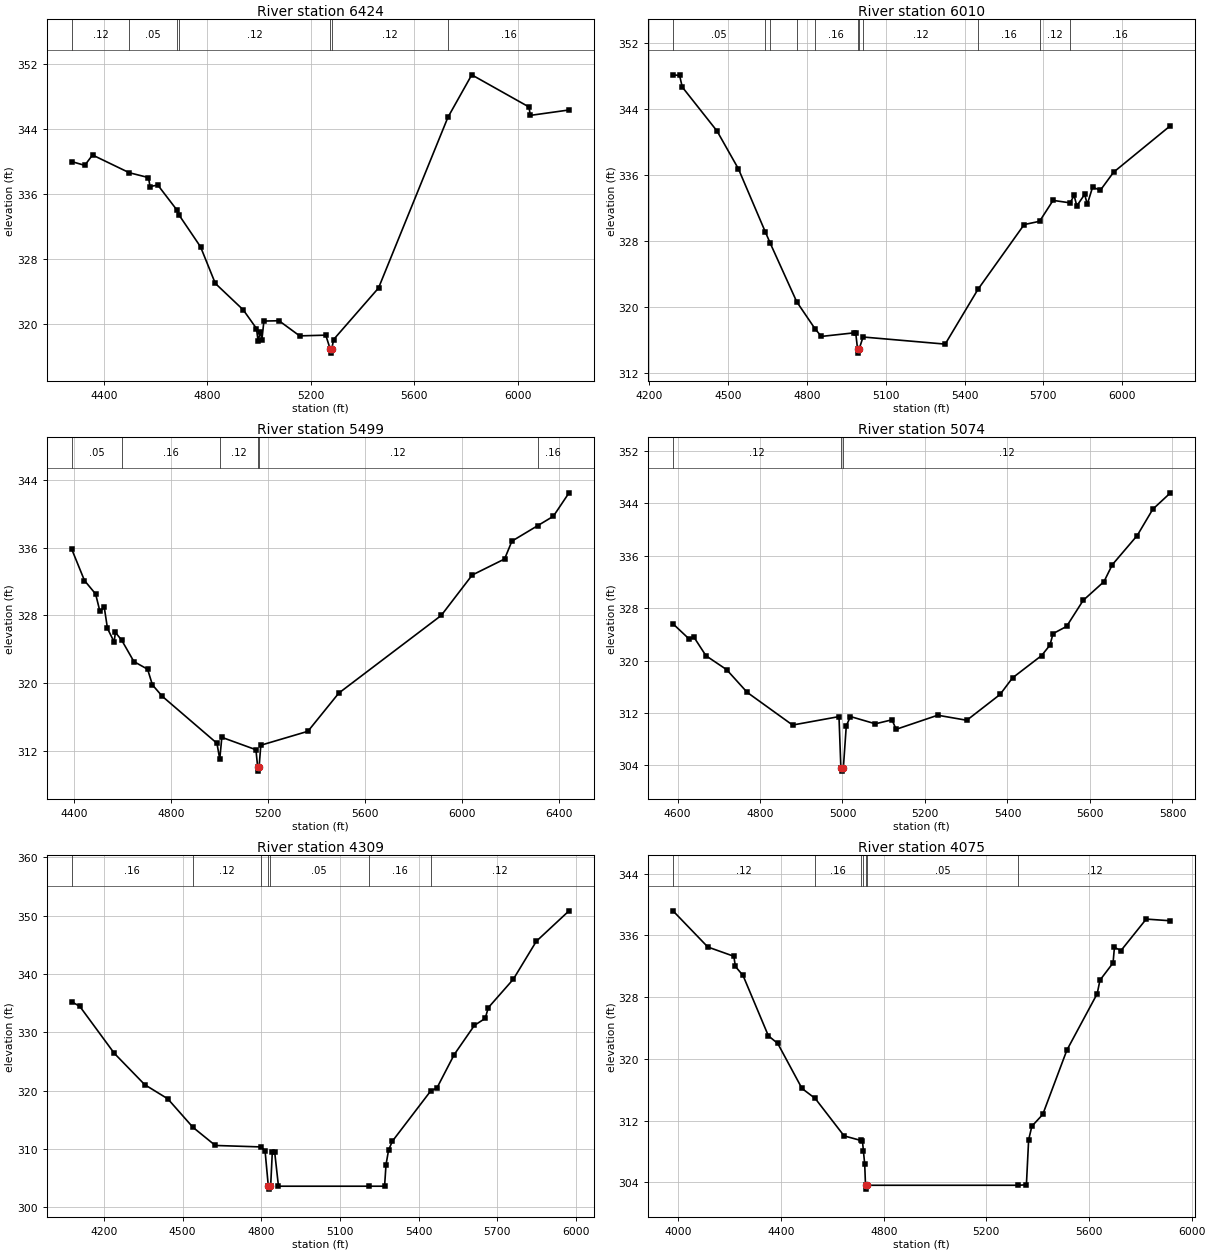
Type RM Length L Ch R = 1,6424,414,414,414
BEGIN DESCRIPTION:
HARPERS BRANCH 12.0
END DESCRIPTION:
XS GIS Cut Line= 3
      3614937.16     10642509.03      3615409.35     10641800.74
      3615555.18     10640738.27
#Sta/Elev= 30
  4274.3  340.01  4325.4  339.54  4355.4  340.82  4497.5  338.63  4571.8  338.03
  4577.8  336.92  4607.8  337.11  4681.6  334.03  4688.8  333.46  4773.1  329.48
  4830.2  324.96  4938.3  321.69  4989.4  319.39  4995.4  317.88  5004.4  318.95
  5010.4  318.02  5018.1  320.31  5076.5  320.35  5156.4  318.48  5257.3  318.57
  5274.5  316.85  5277.3  316.35  5280.5  316.85  5287.6  318.03  5461.3  324.39
  5729.6  345.47  5821.8  350.72  6043.1  346.75  6048.2  345.71  6198.0  346.38
#Mann=7,-1,0
  4274.3    0.12       0  4497.5    0.05       0  4681.6    0.07       0
  4688.8    0.12       0  5274.5    0.07       0  5280.5    0.12       0
  5729.6    0.16       0
Bank Sta=5274.5,5280.5
Exp/Cntr=0.3,0.1

Type RM Length L Ch R = 1,6010,511,511,511
BEGIN DESCRIPTION:
HARPERS BRANCH 11.0
END DESCRIPTION:
XS GIS Cut Line= 3
      3615812.14     10642654.95      3615701.02     10642057.68
      3615756.53     10640774.10
#Sta/Elev= 30
  4291.1  348.11  4316.3  348.03  4326.5  346.63  4458.7  341.31  4540.1  336.73
  4642.0  329.13  4661.4  327.71  4761.9  320.65  4831.1  317.40  4855.4  316.46
  4981.4  316.90  4986.4  316.82  4993.2  314.94  4996.0  314.44  4999.2  314.94
  5014.2  316.39  5326.5  315.53  5451.1  322.15  5626.8  329.99  5685.6  330.39
  5736.9  332.92  5801.6  332.62  5817.0  333.52  5827.0  332.25  5857.0  333.64
  5867.0  332.45  5887.0  334.50  5917.1  334.16  5967.1  336.33  6183.4  341.96
#Mann=11,-1,0
  4291.1    0.05       0  4642.0    0.12       0  4661.4    0.16       0
  4761.9    0.12       0  4831.1    0.16       0  4993.2    0.07       0
  4999.2    0.16       0  5014.2    0.12       0  5451.1    0.16       0
  5685.6    0.12       0  5801.6    0.16       0
Bank Sta=4993.2,4999.2
Exp/Cntr=0.3,0.1

Type RM Length L Ch R = 1,5499,425,425,425
BEGIN DESCRIPTION:
HARPERS BRANCH 10.0
END DESCRIPTION:
XS GIS Cut Line= 3
      3616030.48     10642533.51      3616148.53     10642075.22
      3616009.64     10640505.80
#Sta/Elev= 30
  4391.0  335.86  4444.3  332.11  4490.1  330.53  4508.0  328.47  4525.7  328.97
  4539.0  326.47  4566.4  324.88  4571.5  326.00  4597.1  325.11  4647.8  322.57
  4704.2  321.67  4724.0  319.83  4764.7  318.48  4989.8  312.95  5001.4  311.07
  5009.9  313.65  5150.4  312.19  5157.4  310.17  5160.2  309.67  5163.4  310.17
  5170.5  312.72  5364.4  314.36  5491.7  318.86  5913.4  328.00  6041.0  332.76
  6174.4  334.65  6204.5  336.75  6310.5  338.57  6375.2  339.68  6439.8  342.44
#Mann=6,-1,0
  4391.0    0.05       0  4597.1    0.16       0  5001.4    0.12       0
  5157.4    0.07       0  5163.4    0.12       0  6310.5    0.16       0
Bank Sta=5157.4,5163.4
Exp/Cntr=0.3,0.1

Type RM Length L Ch R = 1,5074,765,765,765
BEGIN DESCRIPTION:
HARPERS BRANCH 9.0
END DESCRIPTION:
XS GIS Cut Line= 3
      3616449.61     10642260.19      3616449.61     10641860.19
      3616549.61     10641060.21
#Sta/Elev= 30
  4589.0  325.62  4629.0  323.25  4639.0  323.66  4669.0  320.74  4719.0  318.62
  4769.0  315.14  4879.0  310.15  4991.5  311.44  4996.1  303.61  4998.8  303.11
  5002.1  303.61  5009.2  310.02  5019.2  311.45  5079.7  310.34  5120.0  310.95
  5130.1  309.50  5230.9  311.65  5301.4  310.88  5382.0  314.82  5412.3  317.36
  5482.8  320.77  5503.0  322.36  5510.5  324.12  5543.3  325.22  5583.6  329.20
  5634.0  332.06  5654.1  334.64  5714.6  339.11  5752.4  343.13  5795.2  345.63
#Mann=3,-1,0
  4589.0    0.12       0  4996.1    0.07       0  5002.1    0.12       0
Bank Sta=4996.1,5002.1
Exp/Cntr=0.3,0.1

Type RM Length L Ch R = 1,4309,234,234,234
BEGIN DESCRIPTION:
HARPERS BRANCH 8.0
END DESCRIPTION:
XS GIS Cut Line= 4
      3616579.11     10642443.24      3617037.42     10641693.27
      3617030.47     10641575.22      3616684.62     10640745.17
#Sta/Elev= 30
  4077.0  335.26  4108.3  334.47  4239.9  326.41  4356.0  321.03  4443.9  318.60
  4539.4  313.73  4625.0  310.60  4798.8  310.35  4814.7  309.66  4827.1  303.61
  4829.9  303.11  4833.1  303.61  4836.0  303.61  4842.3  309.47  4851.4  309.44
  4865.8  303.61  5209.8  303.61  5270.3  303.61  5275.7  307.30  5285.5  309.80
  5299.6  311.31  5446.8  319.99  5469.6  320.44  5535.7  326.19  5612.7  331.20
  5653.8  332.40  5665.7  334.24  5761.1  339.12  5848.8  345.63  5973.4  350.85
#Mann=7,-1,0
  4077.0    0.16       0  4539.4    0.12       0  4798.8    0.05       0
  4827.1   0.033       0  4833.1    0.05       0  5209.8    0.16       0
  5446.8    0.12       0
Bank Sta=4827.1,4833.1
Exp/Cntr=0.3,0.1

Type RM Length L Ch R = 1,4075,343,343,343
BEGIN DESCRIPTION:
HARPERS BRANCH 7.0
END DESCRIPTION:
XS GIS Cut Line= 4
      3618065.20     10642193.27      3617273.53     10641644.66
      3617231.86     10641484.94      3616961.04     10640721.08
#Sta/Elev= 30
  3978.7  339.18  4114.5  334.49  4215.9  333.29  4221.9  331.97  4251.7  330.80
  4350.5  322.98  4387.0  321.99  4481.4  316.16  4533.0  314.86  4645.5  310.01
  4710.6  309.42  4717.1  309.35  4720.9  308.04  4725.9  306.32  4729.0  303.61
  4731.8  303.11  4735.0  303.61  5325.0  303.61  5356.0  303.67  5364.7  309.50
  5377.2  311.26  5419.7  312.79  5513.8  321.13  5631.9  328.44  5642.6  330.19
  5693.7  332.43  5699.0  334.44  5724.6  334.03  5822.9  338.11  5917.4  337.89
#Mann=7,-1,0
  3978.7    0.12       0  4533.0    0.16       0  4710.6    0.12       0
  4720.9    0.05       0  4729.0   0.033       0  4735.0    0.05       0
  5325.0    0.12       0
Bank Sta=4729,4735
Exp/Cntr=0.3,0.1

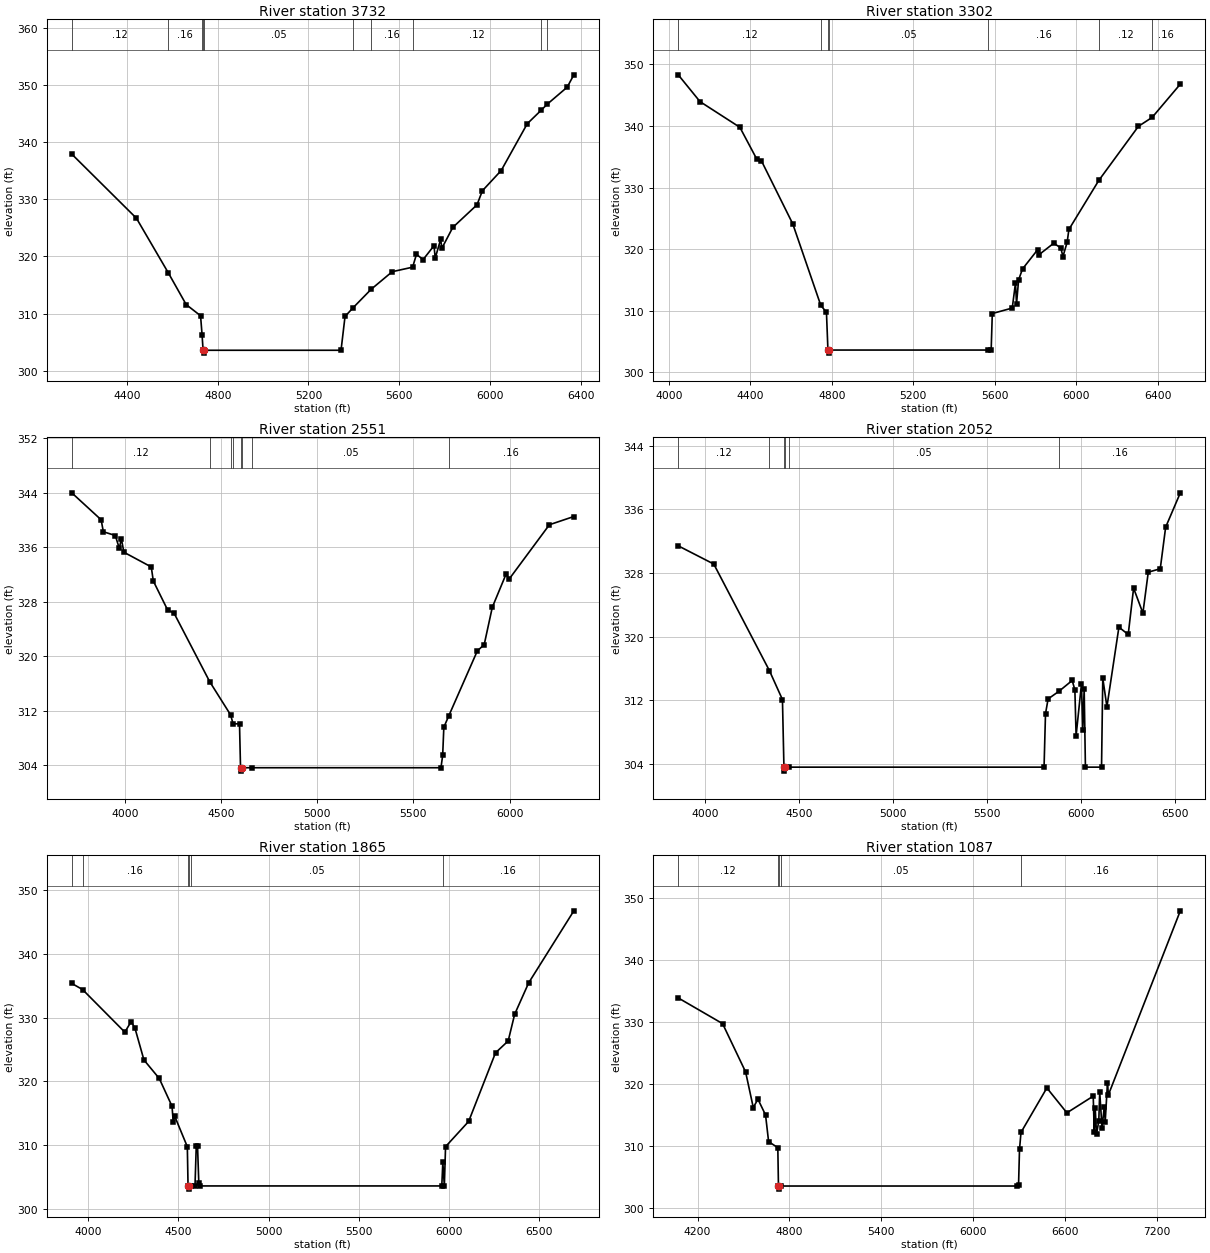
Type RM Length L Ch R = 1,3732,430,430,430
BEGIN DESCRIPTION:
HARPERS BRANCH 6.0
END DESCRIPTION:
XS GIS Cut Line= 3
      3618094.27     10642098.50      3617642.86     10641621.05
      3617052.60     10640180.12
#Sta/Elev= 30
  4156.3  337.89  4441.5  326.68  4581.6  317.17  4660.8  311.60  4724.3  309.64
  4731.0  306.28  4735.4  303.61  4738.2  303.11  4741.4  303.61  5343.8  303.61
  5361.4  309.52  5396.2  311.01  5476.7  314.27  5569.6  317.34  5659.5  318.13
  5676.4  320.37  5705.8  319.46  5753.7  321.88  5759.2  319.73  5783.1  322.97
  5788.6  321.44  5836.5  325.07  5943.3  329.02  5967.3  331.49  6050.1  335.02
  6165.1  343.20  6227.1  345.58  6252.9  346.60  6341.1  349.58  6370.5  351.74
#Mann=10,-1,0
  4156.3    0.12       0  4581.6    0.16       0  4731.0    0.05       0
  4735.4   0.033       0  4741.4    0.05       0  5396.2    0.12       0
  5476.7    0.16       0  5659.5    0.12       0  6227.1    0.16       0
  6252.9    0.12       0
Bank Sta=4735.4,4741.4
Exp/Cntr=0.3,0.1

Type RM Length L Ch R = 1,3302,751,751,751
BEGIN DESCRIPTION:
HARPERS BRANCH 5.0
END DESCRIPTION:
XS GIS Cut Line= 2
      3618241.81     10642272.05      3617590.99     10639894.41
#Sta/Elev= 30
  4046.3  348.30  4153.2  343.95  4348.9  339.78  4431.8  334.62  4455.0  334.32
  4608.6  324.10  4746.3  310.86  4774.0  309.75  4781.3  303.61  4784.1  303.11
  4787.3  303.61  5568.5  303.61  5582.7  303.61  5588.3  309.54  5686.3  310.43
  5702.1  314.50  5707.3  311.13  5717.5  315.01  5736.6  316.78  5810.7  319.89
  5815.9  319.05  5890.1  320.96  5924.6  320.19  5935.2  318.80  5955.9  321.13
  5964.3  323.19  6111.3  331.16  6305.8  339.94  6373.2  341.39  6511.4  346.79
#Mann=7,-1,0
  4046.3    0.12       0  4746.3    0.05       0  4781.3   0.033       0
  4787.3    0.05       0  5568.5    0.16       0  6111.3    0.12       0
  6373.2    0.16       0
Bank Sta=4781.3,4787.3
Exp/Cntr=0.3,0.1

Type RM Length L Ch R = 1,2551,499,499,499
BEGIN DESCRIPTION:
HARPERS BRANCH 4.0
END DESCRIPTION:
XS GIS Cut Line= 4
      3618432.80     10642428.30      3618745.29     10641299.87
      3618701.89     10641091.53      3618016.11     10640075.89
#Sta/Elev= 30
  3724.8  344.00  3877.4  340.04  3888.9  338.28  3951.1  337.73  3971.9  335.83
  3982.2  337.26  3995.8  335.27  4137.9  333.11  4148.6  331.04  4222.4  326.82
  4256.7  326.30  4441.5  316.26  4550.3  311.37  4563.2  310.05  4596.5  310.07
  4601.8  303.61  4604.6  303.11  4607.8  303.61  4663.9  303.61  5643.4  303.61
  5652.3  305.42  5658.4  309.56  5683.7  311.21  5832.2  320.76  5868.2  321.71
  5910.2  327.18  5982.1  332.08  5997.1  331.30  6206.9  339.31  6334.0  340.52
#Mann=8,-1,0
  3724.8    0.12       0  4441.5    0.16       0  4550.3    0.12       0
  4563.2    0.16       0  4601.8   0.033       0  4607.8    0.16       0
  4663.9    0.05       0  5683.7    0.16       0
Bank Sta=4601.8,4607.8
Exp/Cntr=0.3,0.1

Type RM Length L Ch R = 1,2052,187,187,187
BEGIN DESCRIPTION:
Mapping XS 9bd32a81
END DESCRIPTION:
XS GIS Cut Line= 4
      3618870.76     10642179.37      3619252.70     10641283.55
      3619204.09     10641061.33      3618254.49     10639945.38
#Sta/Elev= 30
  3859.5  331.42  4048.3  329.13  4343.5  315.75  4413.0  312.10  4420.9  303.61
  4423.6  303.11  4426.9  303.61  4448.4  303.61  5802.4  303.61  5810.1  310.32
  5823.9  312.18  5882.5  313.16  5951.8  314.50  5966.1  313.33  5972.6  307.56
  6001.2  314.06  6007.8  308.26  6015.5  313.47  6022.1  303.61  6107.7  303.61
  6114.3  314.79  6136.3  311.19  6200.0  321.20  6249.4  320.28  6278.0  326.10
  6327.4  322.97  6355.9  328.11  6419.6  328.54  6448.2  333.76  6526.1  338.08
#Mann=6,-1,0
  3859.5    0.12       0  4343.5    0.16       0  4420.9   0.033       0
  4426.9    0.16       0  4448.4    0.05       0  5882.5    0.16       0
Bank Sta=4420.9,4426.9
Exp/Cntr=0.3,0.1

Type RM Length L Ch R = 1,1865,778,778,778
BEGIN DESCRIPTION:
HARPERS BRANCH 3.0
END DESCRIPTION:
XS GIS Cut Line= 4
      3620113.83     10641901.63      3619433.25     10641200.22
      3619363.81     10640964.10      3618329.06     10639797.40
#Sta/Elev= 30
  3909.3  335.37  3968.9  334.42  4203.4  327.73  4238.6  329.40  4259.7  328.34
  4309.3  323.37  4394.2  320.47  4465.0  316.11  4471.9  313.60  4479.1  314.60
  4549.8  309.76  4553.8  303.61  4556.6  303.11  4559.8  303.61  4567.4  303.61
  4592.3  303.61  4599.3  309.86  4606.4  309.84  4613.4  304.10  4620.6  303.61
  5960.2  303.61  5966.0  307.31  5974.4  303.61  5981.1  309.77  6109.1  313.73
  6258.0  324.49  6328.2  326.35  6364.2  330.54  6441.9  335.47  6692.2  346.76
#Mann=6,-1,0
  3909.3    0.12       0  3968.9    0.16       0  4553.8   0.033       0
  4559.8    0.16       0  4567.4    0.05       0  5966.0    0.16       0
Bank Sta=4553.8,4559.8
Exp/Cntr=0.3,0.1

Type RM Length L Ch R = 1,1087,811,811,811
BEGIN DESCRIPTION:
HARPERS BRANCH 2.0
END DESCRIPTION:
XS GIS Cut Line= 3
      3620240.55     10641989.29      3620162.42     10640869.49
      3618393.07     10639633.54
#Sta/Elev= 30
  4073.6  333.89  4363.4  329.75  4513.8  321.98  4563.9  316.25  4594.5  317.58
  4644.1  315.05  4664.1  310.76  4724.3  309.78  4728.5  303.61  4731.2  303.11
  4734.5  303.61  4747.0  303.61  6288.8  303.61  6297.4  303.80  6303.6  309.49
  6313.3  312.24  6482.4  319.40  6613.3  315.39  6785.3  318.08  6792.1  312.26
  6798.2  316.19  6806.9  311.94  6821.7  314.11  6827.8  318.75  6842.7  312.95
  6857.5  316.37  6863.6  313.95  6878.4  320.20  6884.5  318.29  7354.4  347.91
#Mann=5,-1,0
  4073.6    0.12       0  4728.5   0.033       0  4734.5    0.12       0
  4747.0    0.05       0  6313.3    0.16       0
Bank Sta=4728.5,4734.5
Exp/Cntr=0.3,0.1

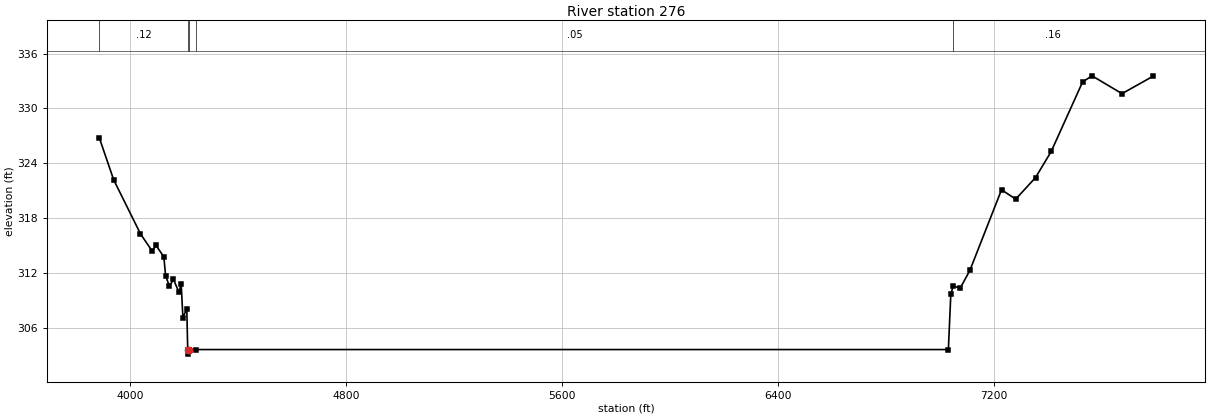
Type RM Length L Ch R = 1,276,0,0,0
BEGIN DESCRIPTION:
HARPERS BRANCH 1.0
END DESCRIPTION:
XS GIS Cut Line= 4
      3620383.75     10641989.30      3620969.71     10641247.09
      3620995.75     10640895.53      3618756.20     10639567.42
#Sta/Elev= 30
  3886.5  326.77  3939.5  322.19  4038.9  316.27  4082.2  314.39  4096.6  315.00
  4125.5  313.75  4131.9  311.69  4146.3  310.53  4160.8  311.31  4181.6  309.86
  4189.6  310.81  4196.0  307.11  4210.5  308.07  4213.8  303.61  4216.6  303.11
  4219.8  303.61  4245.7  303.61  7031.4  303.61  7040.4  309.65  7049.1  310.58
  7075.2  310.32  7111.3  312.29  7228.2  321.09  7280.9  320.07  7354.3  322.43
  7412.4  325.29  7528.7  332.90  7563.5  333.56  7674.6  331.61  7788.4  333.50
#Mann=5,-1,0
  3886.5    0.12       0  4213.8   0.033       0  4219.8    0.12       0
  4245.7    0.05       0  7049.1    0.16       0
Bank Sta=4213.8,4219.8
Exp/Cntr=0.3,0.1

Chan Stop Cuts=-1