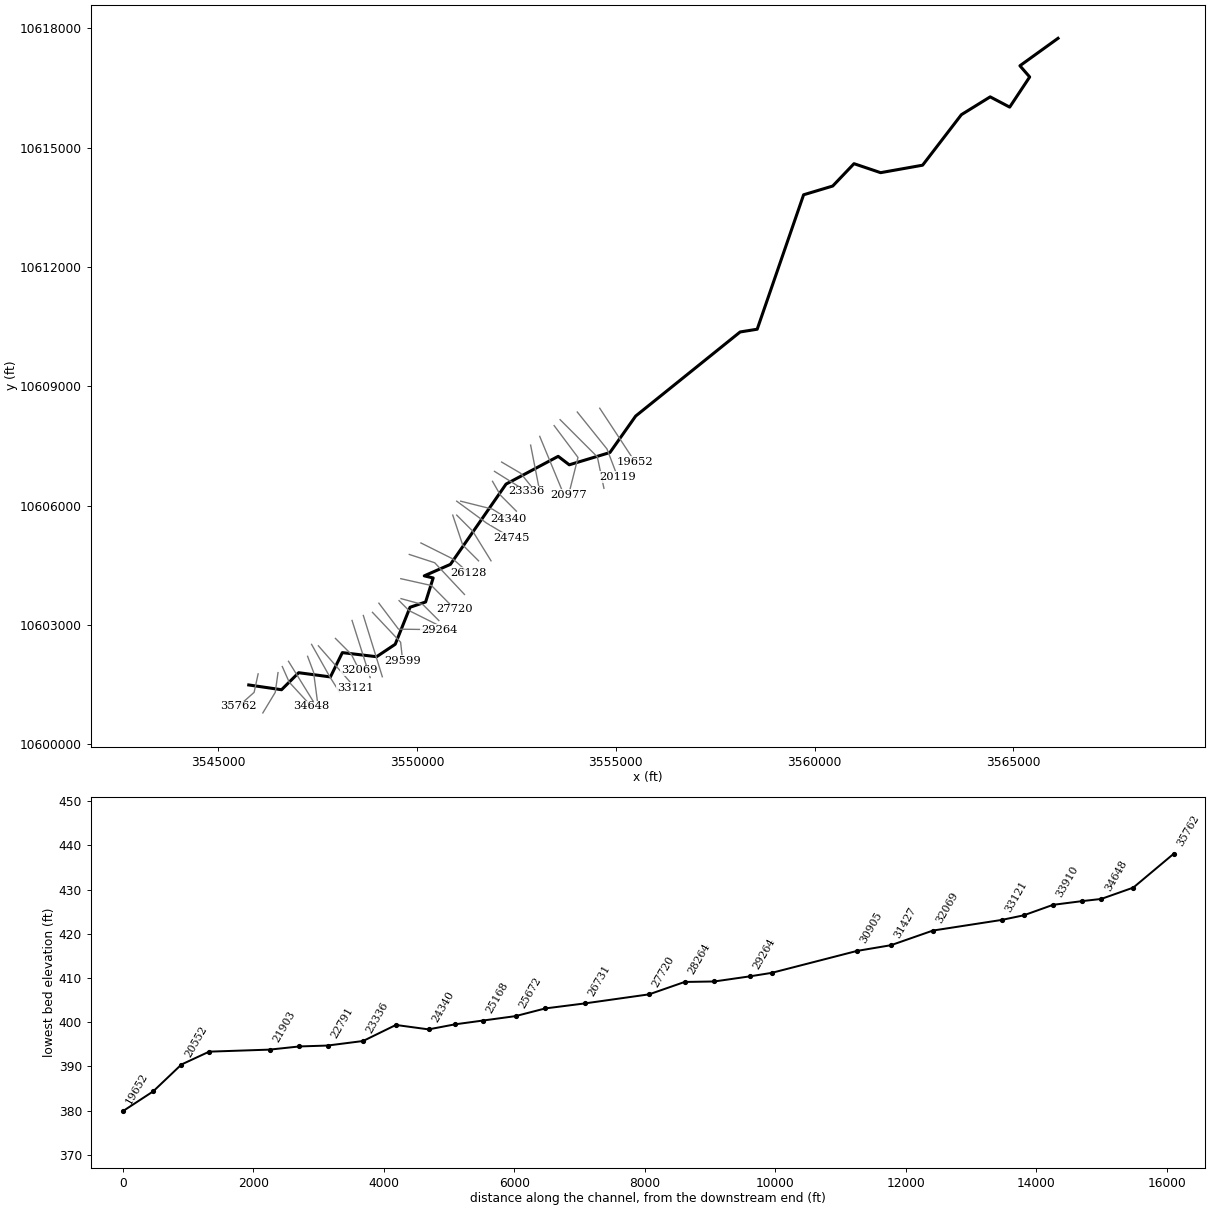
--- HAUSLER CREEK.prj (project) ---

Proj Title=HAUSLER CREEK Base Level Engineering
Current Plan=p01
Default Exp/Contr=0.3,0.1
English Units
Geom File=g01
Flow File=f01
Plan File=p01
Y Axis Title=Elevation
X Axis Title(PF)=Main Channel Distance
X Axis Title(XS)=Station
BEGIN DESCRIPTION:
HAUSLER CREEK
END DESCRIPTION:
DSS Export Rating Curves= 0
DSS Export Rating Curve Sorted= 0
DSS Export Volume Flow Curves= 0
DXF OffsetX= 0
DXF OffsetY= 0
DXF ScaleX= 1
DXF ScaleY= 10

--- HAUSLER CREEK.p01 (plan) ---

Plan Title=Multiple Run
Short Identifier=Multiple
Geom File=g01
Flow File=f01
Subcritical Flow
K Sum by GR= 0
Std Step Tol= 0.01
Critical Tol= 0.01
Num of Std Step Trials= 20
Max Error Tol= 0.3
Flow Tol Ratio= 0.001
Split Flow NTrial= 30
Split Flow Tol= 0.02
Split Flow Ratio= 0.02
Log Output Level= 0
Friction Slope Method= 1
Unsteady Friction Slope Method= 2
Unsteady Bridges Friction Slope Method= 1
Parabolic Critical Depth
Global Vel Dist=  1 , 1 , 1
Global Log Level= 0
CheckData=True
Encroach Param= -1, 0, 0, 0
BEGIN DESCRIPTION:
Multiple Run
END DESCRIPTION:

--- HAUSLER CREEK.f01 (steady flow) ---

Flow Title=Multiple
Program Version=4.10
Number of Profiles= 7
Profile Names=10-year,25-year,50-year,1pct_min,100-year,1pct_plu,500-year
River Rch & RM=HAUSLER CREEK,Reach-1         ,35762
    1395    1925    2364    2120    2867    3878    4202
River Rch & RM=HAUSLER CREEK,Reach-1         ,35140
    1982    2783    3458    3132    4235    5728    6336
River Rch & RM=HAUSLER CREEK,Reach-1         ,29264
    3367    4819    6062    5546    7500   10143   11453
River Rch & RM=HAUSLER CREEK,Reach-1         ,20119
    3871    5568    7029    6449    8722   11795   13399
River Rch & RM=HAUSLER CREEK,Reach-1         ,15080
    4208    6063    7662    7035    9513   12866   14636
River Rch & RM=HAUSLER CREEK,Reach-1         ,10411
    6893   10090   12887   11940   16147   21837   25295
Boundary for River Rch & Prof#=HAUSLER CREEK,Reach-1         , 1
Up Type= 0
Dn Type= 3
Dn Slope=0.00133
Boundary for River Rch & Prof#=HAUSLER CREEK,Reach-1         , 2
Up Type= 0
Dn Type= 3
Dn Slope=0.00133
Boundary for River Rch & Prof#=HAUSLER CREEK,Reach-1         , 3
Up Type= 0
Dn Type= 3
Dn Slope=0.00133
Boundary for River Rch & Prof#=HAUSLER CREEK,Reach-1         , 4
Up Type= 0
Dn Type= 3
Dn Slope=0.00133
Boundary for River Rch & Prof#=HAUSLER CREEK,Reach-1         , 5
Up Type= 0
Dn Type= 3
Dn Slope=0.00133
Boundary for River Rch & Prof#=HAUSLER CREEK,Reach-1         , 6
Up Type= 0
Dn Type= 3
Dn Slope=0.00133
Boundary for River Rch & Prof#=HAUSLER CREEK,Reach-1         , 7
Up Type= 0
Dn Type= 3
Dn Slope=0.00133
DSS Import GetInterval= 0
DSS Import GetPeak= 0
DSS Import FillOption= 0

--- HAUSLER CREEK.g01 (geometry) ---

Geom Title=Existing Conditions
Program Version=4.10

River Reach=HAUSLER CREEK   ,Reach-1
Reach XY= 30
      3545769.75       10601490.       3546594.5       10601370.
       3547025.5       10601798.       3547823.5       10601692.
      3548123.75       10602303.       3548984.5       10602200.
       3549453.5       10602513.       3549825.5       10603443.
      3550217.25       10603576.       3550407.5       10604180.
      3550183.25       10604233.      3550841.75       10604522.
        3552240.       10606540.        3553551.       10607238.
        3553830.       10607025.      3554852.75       10607334.
        3555500.       10608251.        3558127.       10610365.
        3558556.       10610434.        3559723.       10613814.
      3560455.25       10614034.       3560990.5       10614596.
       3561659.5       10614370.      3562715.75       10614558.
      3563690.75       10615828.        3564415.       10616276.
      3564905.75       10616018.      3565408.25       10616776.
        3565163.       10617058.        3566121.       10617748.

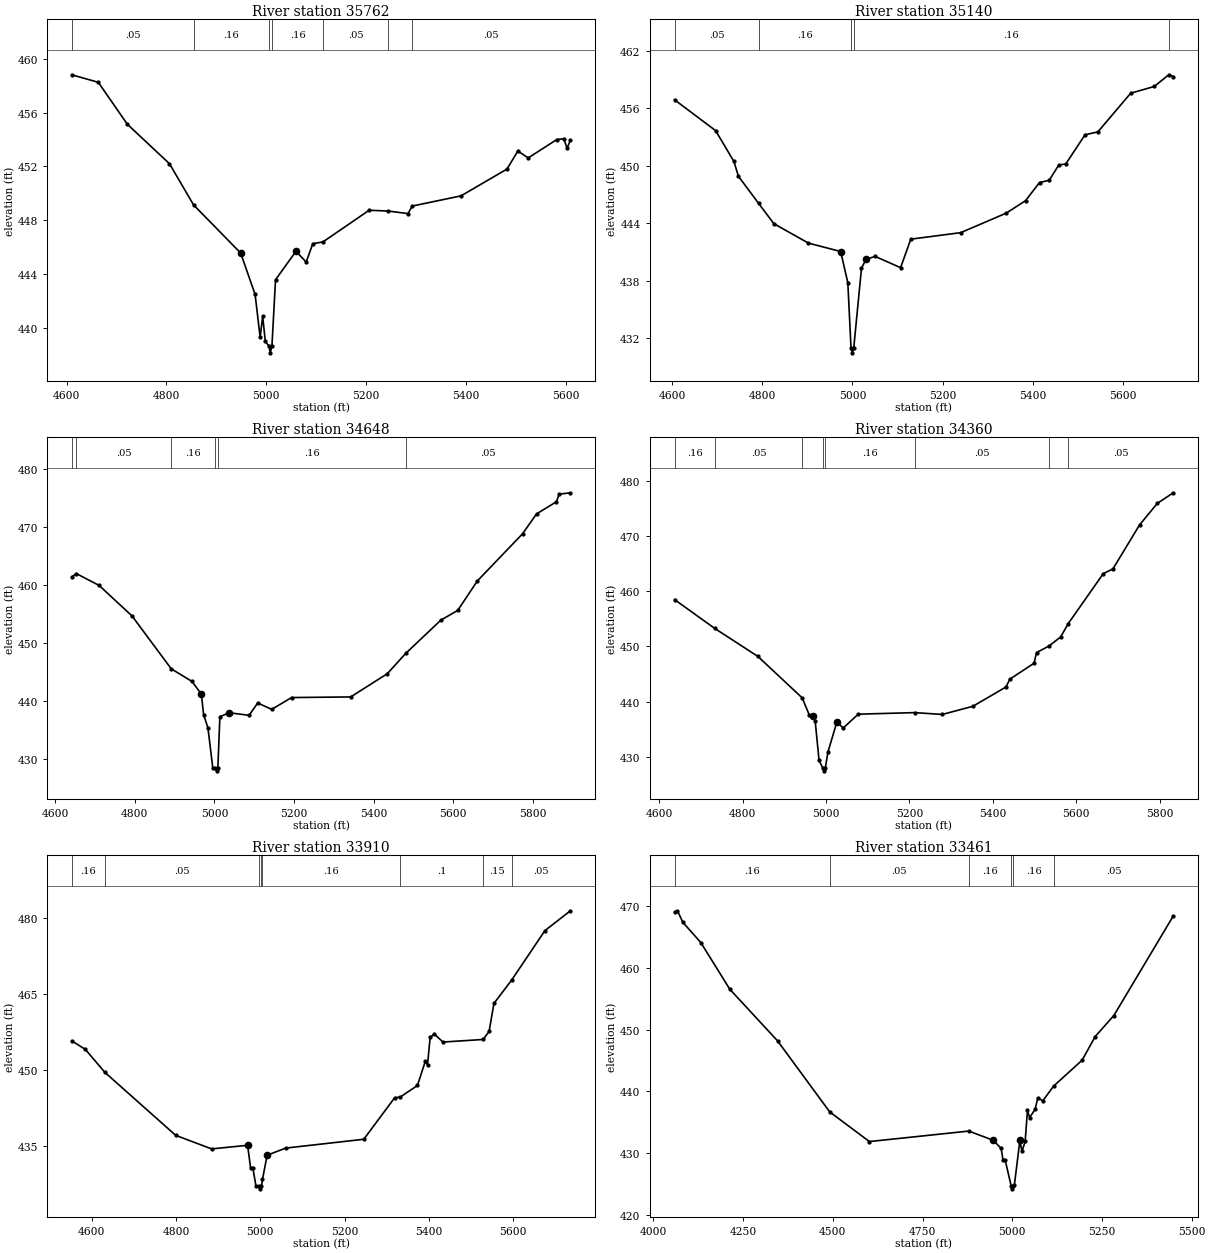
Type RM Length L Ch R = 1 ,35762   ,622,622,622
BEGIN DESCRIPTION:
HAUSLER CREEK 58.0
END DESCRIPTION:
XS GIS Cut Line= 3
      3546005.44     10601768.97      3545904.74     10601303.65
      3545513.52     10600957.44
#Sta/Elev= 30
  4610.4  458.81  4663.5  458.25  4721.7  455.13    4806   452.2  4854.4  449.13
  4948.6  445.56  4977.5  442.48  4987.6   439.3  4992.7  440.85  4997.9     439
  5005.2  438.64  5007.9  438.14  5011.2  438.64  5018.4  443.57  5059.3  445.69
  5079.8  444.89    5093  446.25  5113.6  446.39  5205.9  448.74  5244.3  448.68
  5283.6  448.49  5292.2  449.05  5389.9  449.81  5481.9   451.8  5503.6  453.14
  5524.5  452.63  5581.4  453.99  5595.6  454.06  5602.3  453.35  5608.9  453.95
#Mann= 7 ,-1 , 0
  4610.4     .05       0  4854.4     .16       0  5005.2     .07       0
  5011.2     .16       0  5113.6     .05       0  5244.3     .16       0
  5292.2     .05       0
Bank Sta=4948.6,5059.3
XS Rating Curve= 0 ,0
Exp/Cntr=0.3,0.1

Type RM Length L Ch R = 1 ,35140   ,492,492,492
BEGIN DESCRIPTION:
HAUSLER CREEK 57.0
END DESCRIPTION:
XS GIS Cut Line= 3
      3546505.43      10601800.2      3546435.99     10601303.65
      3546124.05     10600787.23
#Sta/Elev= 30
    4606  456.89  4696.9  453.67  4737.3  450.45  4747.4   448.9  4792.2  446.06
  4825.8  443.95  4902.3  441.92  4973.8  441.04  4989.7  437.79  4996.8  430.95
  4999.6  430.45  5002.8  430.95    5020   439.3  5030.1  440.22  5050.3  440.53
  5106.6  439.35  5129.2  442.33  5239.8  443.01  5340.7  445.05  5383.4  446.35
  5414.4  448.25  5435.8  448.48  5457.1  450.08  5472.6  450.19  5515.3  453.24
  5543.7  453.54  5616.3  457.58  5668.7  458.29  5700.8  459.51  5710.7  459.33
#Mann= 5 ,-1 , 0
    4606     .05       0  4792.2     .16       0  4996.8     .07       0
  5002.8     .16       0  5700.8     .05       0
Bank Sta=4973.8,5030.1
XS Rating Curve= 0 ,0
Exp/Cntr=0.3,0.1

Type RM Length L Ch R = 1 ,34648   ,288,288,288
BEGIN DESCRIPTION:
Mapping XS c98cd6c9
END DESCRIPTION:
XS GIS Cut Line= 3
      3546613.06     10601952.98      3546786.68      10601560.6
      3547344.12     10600954.69
#Sta/Elev= 30
  4641.6  461.34  4652.8  461.97  4710.3  459.91    4793  454.63  4891.5   445.5
  4943.7  443.32    4967  441.14  4972.7  437.57  4983.6  435.32  4995.7  428.41
  5002.5  428.38  5005.3  427.88  5008.5  428.38  5013.6  437.22  5036.8  437.92
    5087  437.47  5108.6   439.6  5143.7   438.5  5193.5  440.54  5342.2  440.65
  5434.1  444.66  5480.8   448.2  5568.5  453.91    5611   455.6  5660.4   460.7
  5773.8  468.83  5808.9  472.27  5858.9  474.37  5865.7  475.68    5894  475.92
#Mann= 6 ,-1 , 0
  4641.6     .16       0  4652.8     .05       0  4891.5     .16       0
  5002.5     .07       0  5008.5     .16       0  5480.8     .05       0
Bank Sta=4967,5036.8
XS Rating Curve= 0 ,0
Exp/Cntr=0.3,0.1

Type RM Length L Ch R = 1 ,34360   ,450,450,450
BEGIN DESCRIPTION:
HAUSLER CREEK 56.0
END DESCRIPTION:
XS GIS Cut Line= 2
      3546769.34     10602084.87       3547397.8     10601067.53
#Sta/Elev= 30
    4637  458.51  4733.4  453.27  4836.9  448.18    4943  440.65  4959.9  437.55
  4968.1  437.35    4974  436.49  4983.4  429.29  4992.3   427.9    4995   427.4
  4998.3   427.9  5004.8  430.85    5026  436.26  5041.4  435.19  5077.4   437.7
  5212.8  437.98    5279  437.65  5352.3  439.13  5431.5  442.63    5441  444.06
    5499  446.96  5504.9  448.89  5534.7  450.08  5562.8  451.73  5580.8  454.14
  5665.1  463.25  5688.1  464.09    5752  472.09  5794.5     476  5832.8  477.93
#Mann= 8 ,-1 , 0
    4637     .16       0  4733.4     .05       0    4943     .16       0
  4992.3     .07       0  4998.3     .16       0  5212.8     .05       0
  5534.7     .08       0  5580.8     .05       0
Bank Sta=4968.1,5026
XS Rating Curve= 0 ,0
Exp/Cntr=0.3,0.1

Type RM Length L Ch R = 1 ,33910   ,449,449,449
BEGIN DESCRIPTION:
HAUSLER CREEK 55.0
END DESCRIPTION:
XS GIS Cut Line= 3
       3547249.6     10602210.22      3547399.61     10601810.19
      3547499.61     10601060.16
#Sta/Elev= 30
  4552.4  455.74  4584.5  454.07  4631.2  449.51    4799  437.11  4884.4  434.43
  4969.8  435.14    4977  430.69  4982.2  430.69  4989.7  427.14  4996.8  427.05
  4999.6  426.55  5002.8  427.05  5005.2  428.41  5016.2  433.18  5060.3  434.59
  5245.7  436.33  5318.9  444.51  5332.3  444.66  5373.1  446.94    5392  451.77
    5397  450.98  5403.3  456.45  5413.4  457.09  5433.6  455.51  5529.1  456.02
  5543.3  457.62  5554.7  463.13  5596.9  467.75  5675.7  477.49  5736.3  481.41
#Mann= 8 ,-1 , 0
  4552.4     .16       0  4631.2     .05       0  4996.8     .03       0
  5002.8     .05       0  5005.2     .16       0  5332.3      .1       0
  5529.1     .15       0  5596.9     .05       0
Bank Sta=4969.8,5016.2
XS Rating Curve= 0 ,0
Exp/Cntr=0.3,0.1

Type RM Length L Ch R = 1 ,33461   ,340,340,340
BEGIN DESCRIPTION:
HAUSLER CREEK 54.0
END DESCRIPTION:
XS GIS Cut Line= 3
      3547349.63     10602510.15      3547799.61     10601710.19
      3548049.59     10601310.22
#Sta/Elev= 30
  4059.2  469.09  4067.1  469.29  4082.1  467.42  4132.1  464.14  4213.1  456.55
    4346  448.19  4491.4  436.66  4601.9  431.85  4878.8  433.55  4947.4  432.05
  4969.1  430.73  4974.2  428.92    4980  428.92    4997  424.68  4999.8  424.18
    5003  424.68  5005.9  424.76  5021.3  432.03  5027.2  430.26    5036  431.87
  5042.5  436.94  5048.4  435.74  5063.7  437.08  5071.4  438.97  5084.9  438.45
  5115.7  440.87  5194.6  445.04  5231.2  448.89  5283.1  452.29  5448.7  468.44
#Mann= 6 ,-1 , 0
  4059.2     .16       0  4491.4     .05       0  4878.8     .16       0
    4997     .07       0    5003     .16       0  5115.7     .05       0
Bank Sta=4947.4,5021.3
XS Rating Curve= 0 ,0
Exp/Cntr=0.3,0.1

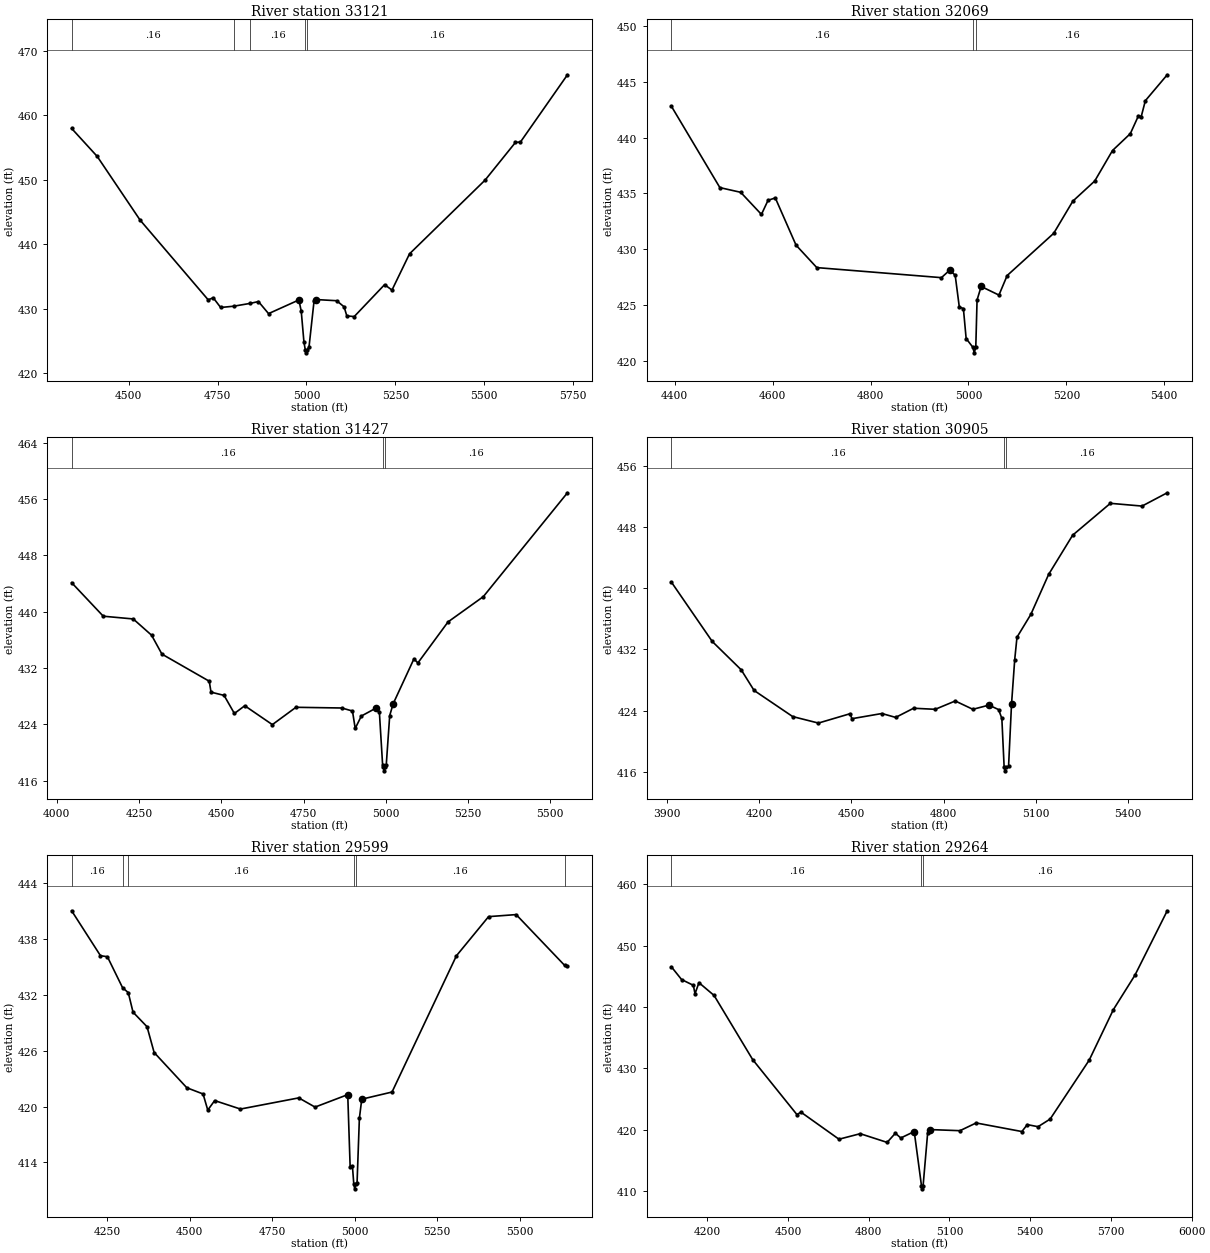
Type RM Length L Ch R = 1 ,33121   ,1052,1052,1052
BEGIN DESCRIPTION:
HAUSLER CREEK 53.0
END DESCRIPTION:
XS GIS Cut Line= 2
      3547521.07     10602473.77      3548440.43     10601424.32
#Sta/Elev= 30
  4339.2  457.92  4411.2  453.58  4531.7  443.72  4723.4  431.35  4737.6  431.67
  4758.5  430.16  4795.3  430.36  4841.8   430.8  4864.8  431.08  4893.3  429.21
  4978.7  431.33  4985.3  429.57  4992.9  424.78  4996.6  423.63  4999.3  423.13
  5002.6  423.63  5007.2  424.06  5021.4  431.21  5028.1  431.39    5085  431.21
  5105.9  430.26  5113.5  428.86  5134.3  428.75  5219.8   433.7  5240.6  432.86
    5290  438.48  5502.6  449.91    5588  455.75  5602.2  455.82  5734.4  466.24
#Mann= 5 ,-1 , 0
  4339.2     .16       0  4795.3     .05       0  4841.8     .16       0
  4996.6     .07       0  5002.6     .16       0
Bank Sta=4978.7,5028.1
XS Rating Curve= 0 ,0
Exp/Cntr=0.3,0.1

Type RM Length L Ch R = 1 ,32069   ,642,642,642
BEGIN DESCRIPTION:
HAUSLER CREEK 52.0
END DESCRIPTION:
XS GIS Cut Line= 3
      3547949.58     10602660.22      3548349.61     10602260.19
      3548549.59     10601860.23
#Sta/Elev= 30
  4393.2   442.8  4492.2  435.52  4534.7   435.1  4577.1  433.12 4590.57  434.38
  4605.4   434.6  4647.8  430.37  4690.2  428.36  4944.8  427.46  4961.7  428.13
  4972.9  427.68  4981.3  424.84  4989.7  424.69  4995.3  422.01    5009  421.23
  5011.8  420.73    5015  421.23  5017.6  425.46    5026  426.67  5062.3   425.9
  5079.1  427.65  5174.2  431.43  5213.3  434.31    5258  436.11  5294.3  438.84
  5330.7  440.35  5347.4  441.96    5353  441.88  5361.4   443.3  5406.1  445.62
#Mann= 3 ,-1 , 0
  4393.2     .16       0    5009     .07       0    5015     .16       0
#XS Ineff= 2 , 0
          4585.5   433.9
Permanent Ineff=
       F       F
Bank Sta=4961.7,5026
XS Rating Curve= 0 ,0
Exp/Cntr=0.3,0.1

Type RM Length L Ch R = 1 ,31427   ,522,522,522
BEGIN DESCRIPTION:
HAUSLER CREEK 51.0
END DESCRIPTION:
XS GIS Cut Line= 2
      3548367.42     10603111.77      3548823.13     10601675.22
#Sta/Elev= 30
  4045.1  444.13  4141.2  439.37  4232.3  438.98  4288.1  436.67  4319.5  433.99
  4463.4  430.14  4468.7  428.59  4508.4  428.13  4539.8  425.56  4571.3  426.66
  4655.2  423.98  4726.9  426.44  4866.4  426.34  4898.7  425.91    4907  423.44
  4925.7   425.2    4970  426.32  4980.5  425.76  4990.3  418.28  4992.5  417.92
  4995.3  417.42  4998.5  417.92  5001.4  418.26  5011.9  425.27  5022.4  426.94
  5085.4   433.3  5097.6  432.74  5189.2  438.56  5296.5  442.15  5552.2  456.89
#Mann= 3 ,-1 , 0
  4045.1     .16       0  4992.5     .07       0  4998.5     .16       0
Bank Sta=4970,5022.4
XS Rating Curve= 0 ,0
Exp/Cntr=0.3,0.1

Type RM Length L Ch R = 1 ,30905   ,1306,1306,1306
BEGIN DESCRIPTION:
HAUSLER CREEK 50.0
END DESCRIPTION:
XS GIS Cut Line= 2
      3548651.24     10603236.99      3549128.65     10601696.26
#Sta/Elev= 30
  3914.8  440.81  4047.6  433.05  4141.8  429.34  4183.7  426.64  4309.3  423.22
    4393  422.37  4496.5   423.6  4501.8  422.94  4599.5  423.62  4644.3  423.11
  4702.6  424.31    4773  424.17  4838.2  425.26  4895.5  424.17  4947.9  424.72
  4979.3  424.13  4989.8  422.97  4997.2  416.62    5000  416.12  5003.2  416.62
  5011.6  416.69  5021.2  424.81  5031.6  430.66    5039   433.6    5084  436.58
    5142  441.82  5220.1  446.95  5342.8  451.12  5445.9  450.76  5527.8   452.5
#Mann= 3 ,-1 , 0
  3914.8     .16       0  4997.2     .07       0  5003.2     .16       0
Bank Sta=4947.9,5021.2
XS Rating Curve= 0 ,0
Exp/Cntr=0.3,0.1

Type RM Length L Ch R = 1 ,29599   ,335,335,335
BEGIN DESCRIPTION:
HAUSLER CREEK 48.0
END DESCRIPTION:
XS GIS Cut Line= 3
      3548881.25     10603315.18      3549588.73      10602564.3
      3549640.81     10602095.55
#Sta/Elev= 30
  4141.7  441.06  4229.1  436.23  4250.1  436.12  4296.2  432.78  4313.4  432.26
  4327.8  430.16  4370.3  428.59  4391.8  425.82  4490.9  422.03  4540.2  421.36
  4554.4  419.63  4575.4  420.65  4653.5  419.74  4830.3  420.94  4879.7  419.95
  4978.8  421.29  4986.1  413.54    4993  413.62  4997.2  411.66    5000  411.16
  5003.2  411.66  5007.1  411.83  5014.1  418.74  5021.3   420.8  5113.1  421.57
  5308.3  436.22  5405.8  440.43  5489.4  440.65  5636.1   435.2    5645  435.07
#Mann= 6 ,-1 , 0
  4141.7     .16       0  4296.2     .05       0  4313.4     .16       0
  4997.2     .07       0  5003.2     .16       0  5636.1     .05       0
Bank Sta=4978.8,5021.3
XS Rating Curve= 0 ,0
Exp/Cntr=0.3,0.1

Type RM Length L Ch R = 1 ,29264   ,545,545,545
BEGIN DESCRIPTION:
HAUSLER CREEK 47.0
END DESCRIPTION:
XS GIS Cut Line= 3
       3549042.3     10603545.97      3549535.37     10602893.18
      3550559.69     10602879.29
#Sta/Elev= 30
  4066.7  446.56  4104.5  444.49  4148.2  443.55  4154.4  442.17    4169  443.98
  4225.2   441.9  4368.8  431.43  4533.2  422.47  4547.8  422.88  4689.4  418.46
  4768.4  419.36  4868.3  417.94    4899  419.44    4919  418.66    4969  419.71
    4996  410.87  4998.8  410.37    5002  410.87    5019  419.53    5029  420.03
    5139  419.85  5199.1  421.11  5369.1  419.71  5389.1  420.84  5429.1   420.5
    5474  421.74  5619.1  431.34  5709.1  439.59  5789.1  445.19  5909.2   455.7
#Mann= 3 ,-1 , 0
  4066.7     .16       0    4996     .07       0    5002     .16       0
Bank Sta=4969,5029
XS Rating Curve= 0 ,0
Exp/Cntr=0.3,0.1

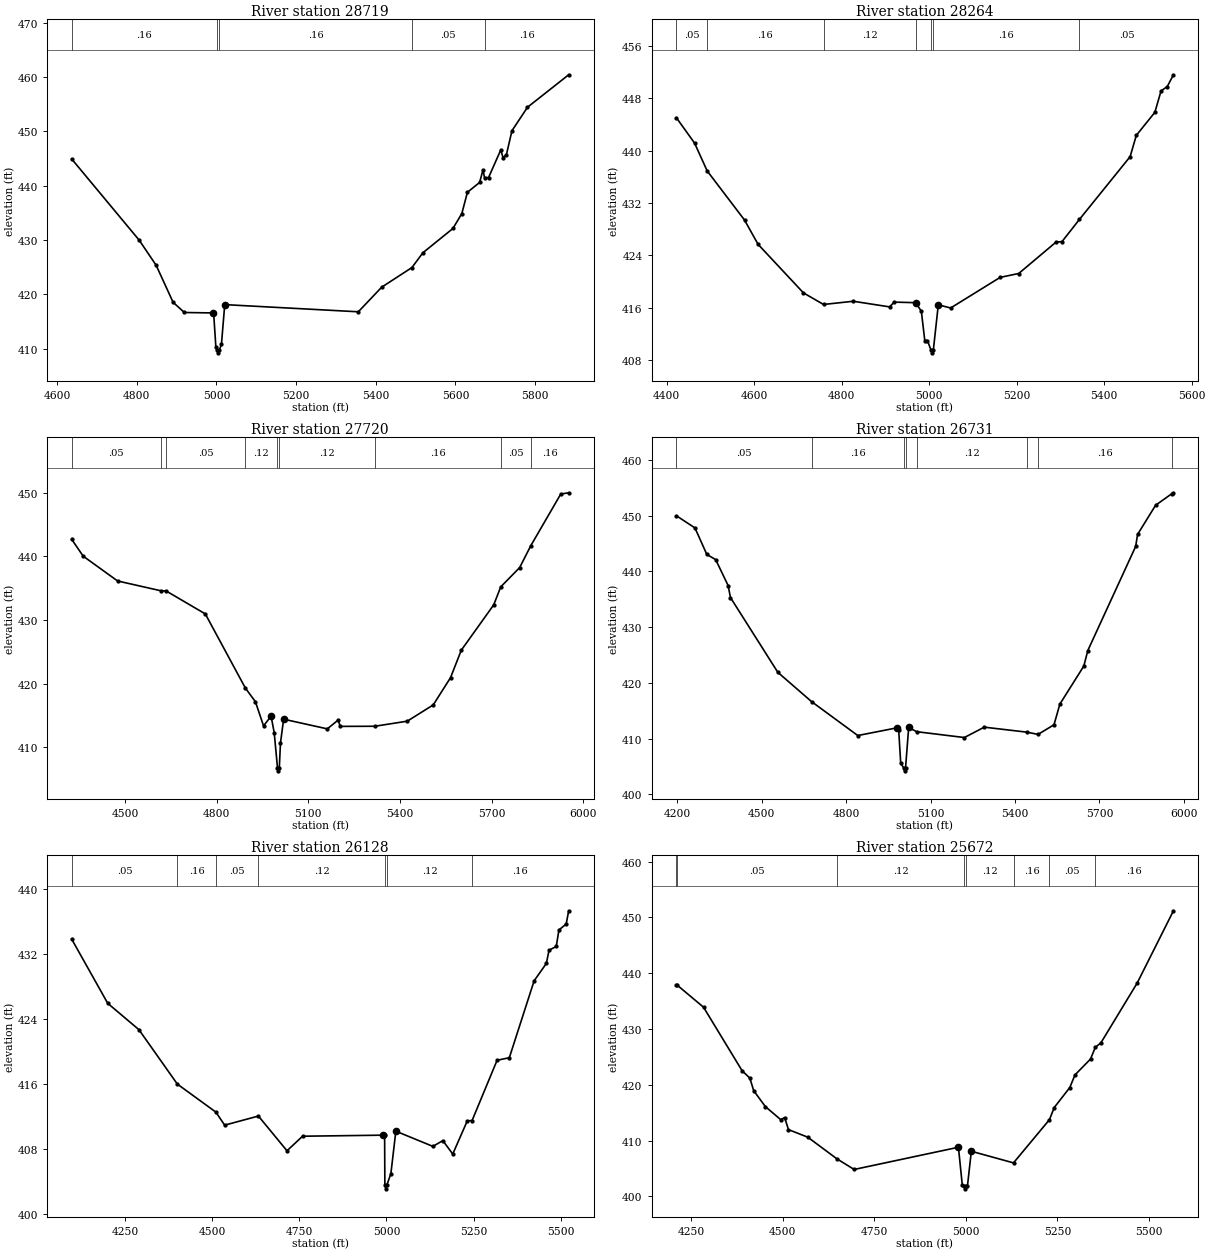
Type RM Length L Ch R = 1 ,28719   ,455,455,455
BEGIN DESCRIPTION:
HAUSLER CREEK 46.0
END DESCRIPTION:
XS GIS Cut Line= 3
      3549549.58     10603610.22      3549799.61     10603360.19
      3550599.59      10602960.2
#Sta/Elev= 30
  4636.4  444.91  4806.1  429.94  4848.6  425.32    4891  418.52  4919.3  416.64
    4990  416.56  4992.8  416.56  4998.4  410.31    5001  409.71  5003.7  409.21
    5007  409.71  5012.4  410.75  5020.7  418.09  5356.2  416.77  5414.8   421.3
  5490.8  424.92  5518.3  427.64  5593.7  432.11  5616.1  434.86  5630.1  438.78
  5660.8  440.59  5669.2  442.91  5673.1  441.48  5683.2  441.49  5713.9  446.58
  5719.5  445.18  5727.9  445.65  5741.9  450.11    5781  454.44  5884.4  460.42
#Mann= 5 ,-1 , 0
  4636.4     .16       0    5001     .07       0    5007     .16       0
  5490.8     .05       0  5673.1     .16       0
Bank Sta=4990,5020.7
XS Rating Curve= 0 ,0
Exp/Cntr=0.3,0.1

Type RM Length L Ch R = 1 ,28264   ,544,544,544
BEGIN DESCRIPTION:
HAUSLER CREEK 45.0
END DESCRIPTION:
XS GIS Cut Line= 3
      3549599.62     10603660.18      3550149.61     10603510.19
      3550549.64     10603110.16
#Sta/Elev= 30
  4422.6     445    4464  441.14  4492.7   436.9  4578.1  429.39  4609.2  425.67
  4712.8  418.26  4758.7  416.49  4826.8  416.98  4909.7  416.12  4920.1  416.85
  4969.7  416.76  4982.3  415.43  4990.1  410.98  4996.2  410.98  5003.8   409.6
  5006.6   409.1  5009.8   409.6    5021  416.44  5049.2  415.95  5162.4  420.63
  5204.8  421.22  5289.7     426  5303.8   426.1  5343.5  429.48  5459.4  439.07
  5473.5  442.32  5515.9  445.84  5530.1  449.12  5544.2  449.77  5558.4  451.58
#Mann= 7 ,-1 , 0
  4422.6     .05       0  4492.7     .16       0  4758.7     .12       0
  4969.7     .16       0  5003.8     .07       0  5009.8     .16       0
  5343.5     .05       0
Bank Sta=4969.7,5021
XS Rating Curve= 0 ,0
Exp/Cntr=0.3,0.1

Type RM Length L Ch R = 1 ,27720   ,989,989,989
BEGIN DESCRIPTION:
HAUSLER CREEK 44.0
END DESCRIPTION:
XS GIS Cut Line= 3
      3549592.97     10604161.98      3550363.78     10603990.11
      3550952.36     10603396.33
#Sta/Elev= 30
  4325.8  442.65  4363.3  440.01    4476  436.11    4617  434.58  4635.2  434.53
  4762.9  430.94  4893.9   419.3  4926.8  417.15  4953.4  413.36  4978.1  414.89
  4988.3  412.29    4999   406.8  5001.7   406.3    5005   406.8  5008.8  410.68
  5019.1  414.41    5162  412.89  5197.4  414.27  5204.4  413.28  5317.6   413.3
  5423.7   414.1  5508.5  416.65  5565.1  420.93  5600.4  425.25  5706.5  432.37
  5729.3  435.18  5791.3  438.22  5827.9  441.67  5925.7  449.76  5951.6  449.96
#Mann= 9 ,-1 , 0
  4325.8     .05       0    4617     .16       0  4635.2     .05       0
  4893.9     .12       0    4999     .07       0    5005     .12       0
  5317.6     .16       0  5729.3     .05       0  5827.9     .16       0
Bank Sta=4978.1,5019.1
XS Rating Curve= 0 ,0
Exp/Cntr=0.3,0.1

Type RM Length L Ch R = 1 ,26731   ,603,603,603
BEGIN DESCRIPTION:
HAUSLER CREEK 42.0
END DESCRIPTION:
XS GIS Cut Line= 3
      3549807.12     10604771.08      3550446.01     10604562.75
       3551194.8     10603765.42
#Sta/Elev= 30
    4197  449.96  4262.7  447.79  4304.8  443.04  4336.4   442.1  4380.5  437.46
  4388.9   435.3  4557.2   421.9    4677  416.65  4841.2  410.57  4979.6  411.94
  4986.5  411.63  4993.8  405.58  5004.9  404.74  5007.7  404.24  5010.9  404.74
  5022.1  412.02  5050.2  411.26  5219.9  410.21  5290.7  412.07    5443  411.17
  5481.7  410.77  5538.4   412.5  5559.4  416.22  5644.4  423.03  5658.5   425.8
  5828.5  444.46  5835.4  446.62  5899.3  451.85  5956.1  453.89  5962.8  454.09
#Mann= 8 ,-1 , 0
    4197     .05       0    4677     .16       0  5004.9     .07       0
  5010.9     .16       0  5050.2     .12       0    5443     .05       0
  5481.7     .16       0  5956.1     .05       0
Bank Sta=4979.6,5022.1
XS Rating Curve= 0 ,0
Exp/Cntr=0.3,0.1

Type RM Length L Ch R = 1 ,26128   ,456,456,456
BEGIN DESCRIPTION:
HAUSLER CREEK 41.0
END DESCRIPTION:
XS GIS Cut Line= 3
      3550099.61     10605060.19      3550899.61     10604660.19
      3551299.58     10604310.21
#Sta/Elev= 30
  4096.8  433.81  4200.2  425.92  4289.7  422.68  4399.9  415.99  4510.6  412.54
  4535.6  410.94  4632.5  412.06  4714.5  407.79  4759.2  409.58  4991.2  409.71
  4994.6  409.71  4995.3  403.61  4998.1  403.11  5001.3  403.61  5012.6  404.98
  5026.8   410.2  5133.1  408.33  5161.6  409.04  5190.1  407.39  5231.8  411.47
  5245.6  411.51  5317.3  418.92  5352.4  419.23  5423.6  428.69  5458.7  430.83
  5466.3  432.44  5487.1  432.92  5494.7  434.94  5515.6  435.67  5522.7   437.3
#Mann= 7 ,-1 , 0
  4096.8     .05       0  4399.9     .16       0  4510.6     .05       0
  4632.5     .12       0  4995.3     .07       0  5001.3     .12       0
  5245.6     .16       0
Bank Sta=4991.2,5026.8
XS Rating Curve= 0 ,0
Exp/Cntr=0.3,0.1

Type RM Length L Ch R = 1 ,25672   ,504,504,504
BEGIN DESCRIPTION:
HAUSLER CREEK 40.0
END DESCRIPTION:
XS GIS Cut Line= 3
      3550899.61      10605760.2      3551149.61     10605010.19
      3551549.63     10604610.16
#Sta/Elev= 30
  4210.4   437.9  4211.6   437.9  4284.2  433.91  4389.6  422.52  4410.7   421.2
  4421.2  418.95  4452.9  416.11    4495  413.76  4505.6  414.13  4516.1  411.98
  4568.8  410.62  4648.4  406.74  4695.3  404.84  4979.9  408.82  4990.4  402.06
  4995.3  401.87  4998.1  401.37  5001.3  401.87  5004.5  401.87  5015.1   408.1
  5130.2  406.02  5228.3  413.76  5241.4  415.94  5283.8  419.51    5298  421.78
  5340.4  424.62  5353.4  426.71  5368.7  427.52  5467.7  438.23  5566.7  451.18
#Mann= 8 ,-1 , 0
  4210.4     .16       0  4211.6     .05       0  4648.4     .12       0
  4995.3     .07       0  5001.3     .12       0  5130.2     .16       0
  5228.3     .05       0  5353.4     .16       0
Bank Sta=4979.9,5015.1
XS Rating Curve= 0 ,0
Exp/Cntr=0.3,0.1

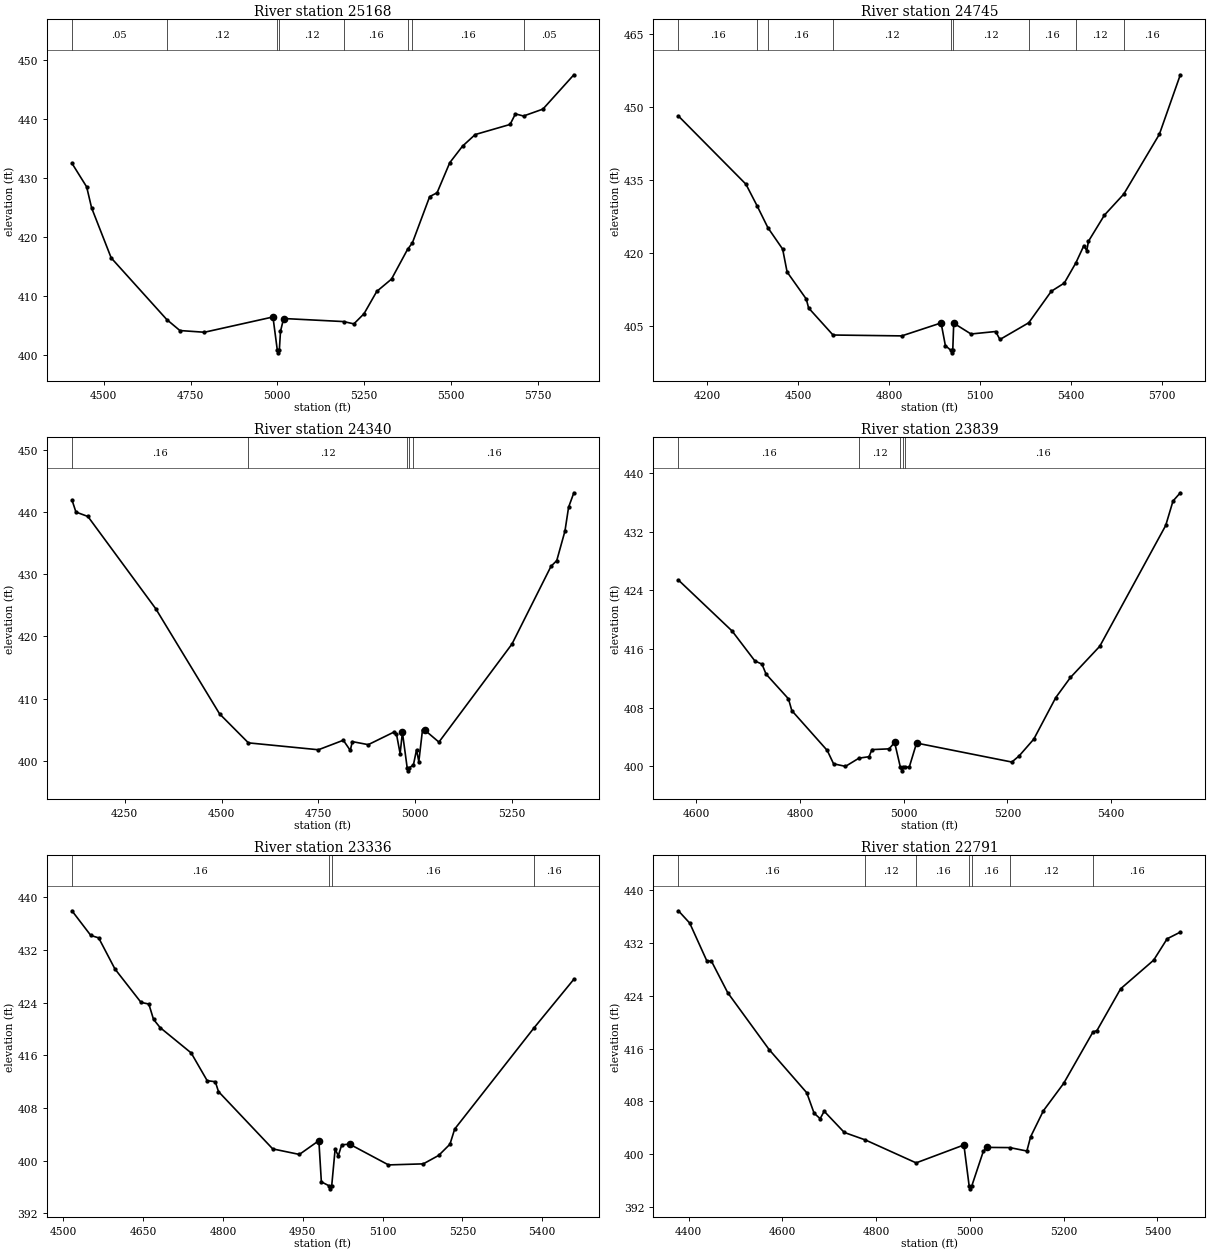
Type RM Length L Ch R = 1 ,25168   ,423,423,423
BEGIN DESCRIPTION:
HAUSLER CREEK 39.0
END DESCRIPTION:
XS GIS Cut Line= 3
       3550999.6     10605760.19      3551399.61     10605360.19
      3551862.53     10604610.96
#Sta/Elev= 30
  4408.3  432.49  4450.7  428.49  4464.9  424.94  4521.4  416.45  4681.6     406
  4719.4  404.14  4790.1  403.85  4987.6  406.44    5000  400.86  5002.7  400.36
    5006  400.86  5009.3     404  5018.3  406.18    5191  405.66  5220.8  405.27
    5250  406.99  5286.7  410.77  5329.2  412.86  5375.3  417.88  5389.3  418.99
  5439.2  426.84  5460.5  427.49  5497.1  432.59  5533.8  435.39  5570.4  437.36
  5670.9  439.07  5686.3  440.86  5709.6   440.5  5765.5  441.67  5854.7  447.49
#Mann= 8 ,-1 , 0
  4408.3     .05       0  4681.6     .12       0    5000     .07       0
    5006     .12       0    5191     .16       0  5375.3     .05       0
  5389.3     .16       0  5709.6     .05       0
Bank Sta=4987.6,5018.3
XS Rating Curve= 0 ,0
Exp/Cntr=0.3,0.1

Type RM Length L Ch R = 1 ,24745   ,405,405,405
BEGIN DESCRIPTION:
HAUSLER CREEK 38.0
END DESCRIPTION:
XS GIS Cut Line= 3
       3550999.6     10606110.19      3551749.61     10605560.19
      3552372.94     10605189.09
#Sta/Elev= 30
  4105.7  448.14  4328.4  434.14  4365.6  429.65  4400.9   425.2  4449.5  420.81
  4464.2  416.11  4527.3  410.57  4535.2  408.72  4615.6  403.17  4842.4  402.99
  4972.1  405.65  4986.2  401.01  5004.6  400.01  5007.3  399.51  5010.6  400.01
  5013.8   405.6  5070.8  403.38  5152.1  403.89  5166.2  402.25  5261.3  405.69
  5335.6  412.15  5378.5  413.84  5416.7  417.99  5443.1  421.53  5452.5  420.49
  5458.3  422.43  5510.9  427.79  5574.7  432.11    5692  444.38  5761.2  456.61
#Mann= 9 ,-1 , 0
  4105.7     .16       0  4365.6     .05       0  4400.9     .16       0
  4615.6     .12       0  5004.6     .07       0  5010.6     .12       0
  5261.3     .16       0  5416.7     .12       0  5574.7     .16       0
Bank Sta=4972.1,5013.8
XS Rating Curve= 0 ,0
Exp/Cntr=0.3,0.1

Type RM Length L Ch R = 1 ,24340   ,501,501,501
BEGIN DESCRIPTION:
HAUSLER CREEK 37.0
END DESCRIPTION:
XS GIS Cut Line= 3
      3551099.65     10606110.18      3551899.61     10605910.19
      3552299.63     10605660.18
#Sta/Elev= 30
  4113.7  441.94    4124  439.98  4154.9  439.27  4330.1  424.44    4495  407.53
  4569.4  402.87  4750.2  401.76  4814.6  403.29  4832.6  401.65  4837.8  403.07
    4879  402.58  4945.9  404.62  4951.8   404.3  4961.3  401.14  4967.2  404.56
  4979.5  398.87  4982.3  398.37  4985.5  398.87  4995.7  399.34  5003.7  401.76
  5009.6  399.85  5019.1  404.97    5025  404.92  5061.5  402.99  5250.2  418.76
    5351  431.26  5365.8  432.17    5387  436.92  5396.4  440.76    5410  443.08
#Mann= 5 ,-1 , 0
  4113.7     .16       0  4569.4     .12       0  4979.5     .07       0
  4985.5     .12       0  4995.7     .16       0
Bank Sta=4967.2,5025
XS Rating Curve= 0 ,0
Exp/Cntr=0.3,0.1

Type RM Length L Ch R = 1 ,23839   ,503,503,503
BEGIN DESCRIPTION:
HAUSLER CREEK 36.0
END DESCRIPTION:
XS GIS Cut Line= 3
      3551899.59     10606610.22      3552099.61     10606260.19
      3552499.58     10605860.21
#Sta/Elev= 30
  4565.1  425.41  4668.8  418.45  4712.7  414.37  4726.4  413.93  4734.3  412.57
  4777.5   409.2    4784  407.59  4852.4  402.15  4864.6  400.33  4887.6  399.98
  4913.6   401.1    4933   401.3  4938.7  402.27  4971.8  402.37  4982.4  403.25
  4993.5  399.87  4996.3  399.37  4999.5  399.87    5002  399.87  5010.7  399.88
  5024.8  403.16  5208.7  400.57  5222.8  401.41  5251.1   403.7  5293.5  409.37
  5321.8  412.11  5378.4  416.37  5505.7  432.86  5519.8   436.2  5533.9  437.32
#Mann= 5 ,-1 , 0
  4565.1     .16       0  4913.6     .12       0  4993.5     .07       0
  4999.5     .12       0    5002     .16       0
Bank Sta=4982.4,5024.8
XS Rating Curve= 0 ,0
Exp/Cntr=0.3,0.1

Type RM Length L Ch R = 1 ,23336   ,545,545,545
BEGIN DESCRIPTION:
HAUSLER CREEK 35.0
END DESCRIPTION:
XS GIS Cut Line= 3
      3551949.57     10606860.21      3552349.61     10606610.19
      3552749.58     10606360.21
#Sta/Elev= 30
    4516  437.93  4551.4  434.19  4566.2  433.82  4596.8   429.1  4645.8  424.03
  4660.5  423.78  4669.3  421.46  4681.7  420.21  4740.1  416.36  4770.2  412.15
  4785.5  411.99  4791.4   410.5  4893.4   401.8  4943.5  400.96  4980.1  403.05
  4984.8   396.8  4998.3  396.24  5001.1  395.74  5004.3  396.24  5010.7  401.78
  5016.6  400.75  5023.1  402.42  5037.9  402.52    5111  399.37  5176.4  399.53
  5205.3  400.81  5226.5  402.51  5235.4  404.81  5383.9   420.1  5459.4  427.54
#Mann= 4 ,-1 , 0
    4516     .16       0  4998.3     .07       0  5004.3     .16       0
  5383.9     .16       0
Bank Sta=4980.1,5037.9
XS Rating Curve= 0 ,0
Exp/Cntr=0.3,0.1

Type RM Length L Ch R = 1 ,22791   ,431,431,431
BEGIN DESCRIPTION:
HAUSLER CREEK 34.0
END DESCRIPTION:
XS GIS Cut Line= 3
      3552128.86     10607093.95      3552608.06     10606812.68
      3552930.95     10606411.67
#Sta/Elev= 30
  4378.4  436.92  4402.5  435.05  4439.1   429.3  4448.8  429.28  4483.6  424.48
    4572  415.84  4652.1   409.3  4667.8  406.19  4680.7  405.36  4689.3  406.49
  4732.2  403.27  4777.2  402.13  4885.4  398.65  4987.3  401.37  4998.4  395.21
  5001.2  394.71  5004.4  395.21  5028.9  400.44  5036.9     401  5085.3  400.97
  5121.6  400.45  5129.6  402.61  5156.9  406.57    5200  410.71  5262.5  418.51
  5271.1  418.74  5321.6  425.08    5392  429.42  5420.8  432.67  5448.9  433.68
#Mann= 7 ,-1 , 0
  4378.4     .16       0  4777.2     .12       0  4885.4     .16       0
  4998.4     .07       0  5004.4     .16       0  5085.3     .12       0
  5262.5     .16       0
Bank Sta=4987.3,5036.9
XS Rating Curve= 0 ,0
Exp/Cntr=0.3,0.1

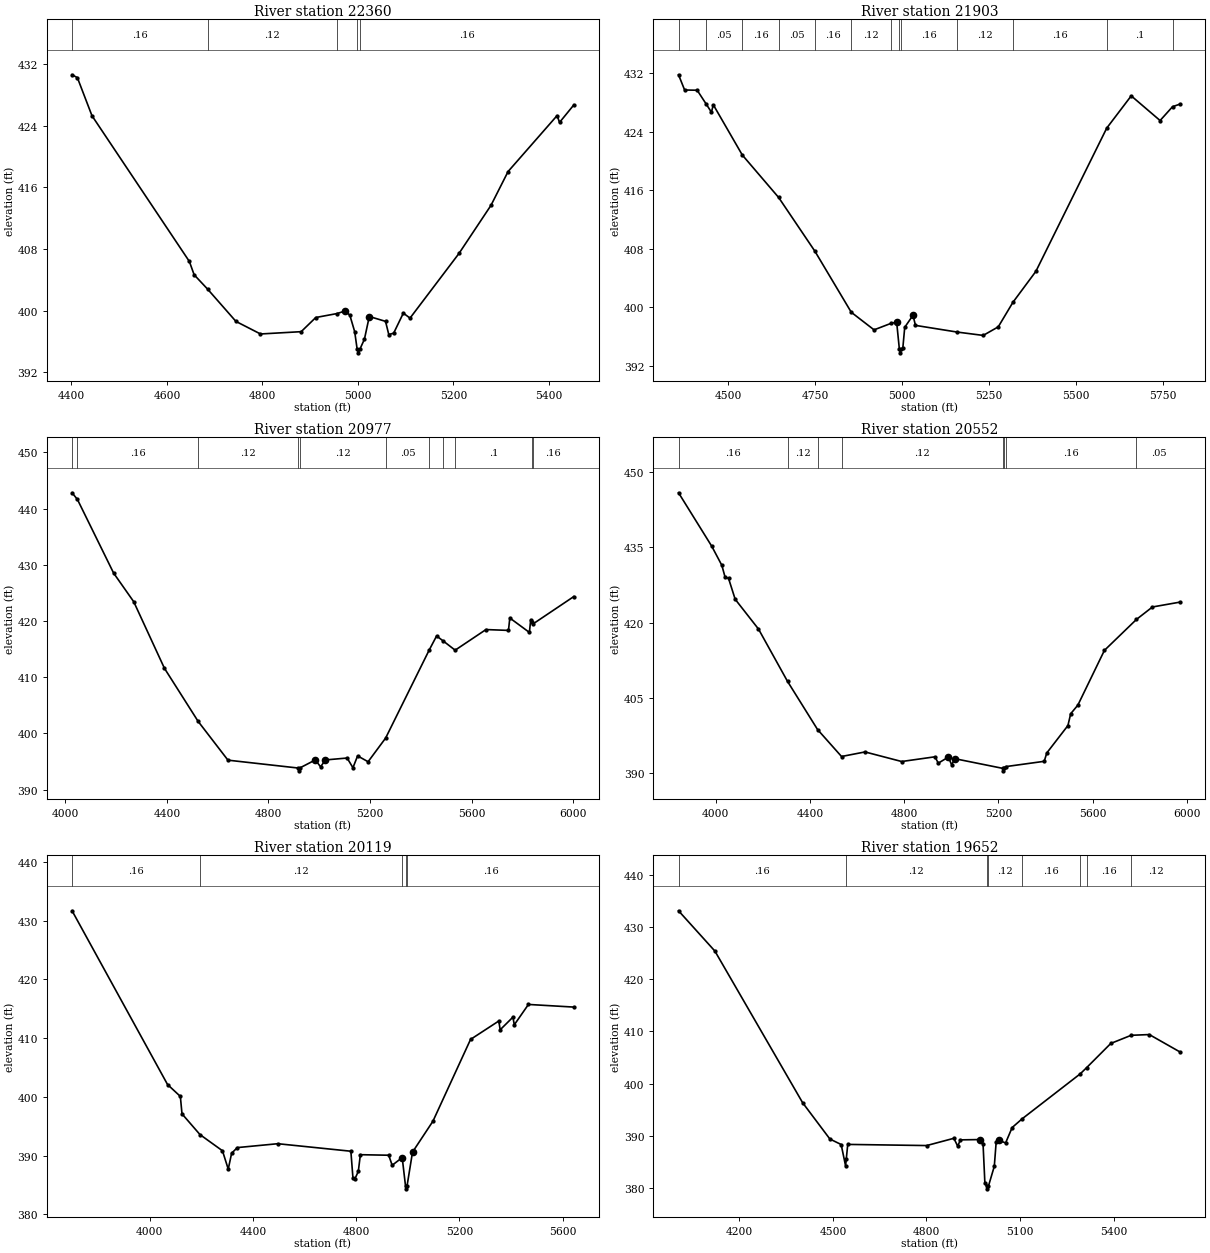
Type RM Length L Ch R = 1 ,22360   ,457,457,457
BEGIN DESCRIPTION:
HAUSLER CREEK 33.0
END DESCRIPTION:
XS GIS Cut Line= 2
      3552858.06     10607521.06      3553061.19     10606489.77
#Sta/Elev= 30
  4401.4  430.63  4412.5  430.26  4443.1  425.31  4647.1  406.38  4657.1  404.65
  4685.7  402.76  4744.7  398.59  4796.1  396.96  4881.3  397.26  4911.9   399.1
  4956.2  399.61    4973  399.94  4983.2  399.41  4993.4  397.26  4998.5  395.01
  5001.3  394.51  5004.5  395.01  5013.8  396.28    5024  399.23    5058   398.6
  5064.8  396.89    5075  397.06  5095.3  399.67  5109.3  399.02    5212  407.43
  5278.8  413.66  5314.7  418.06  5417.4  425.33  5422.5  424.44  5452.5  426.72
#Mann= 5 ,-1 , 0
  4401.4     .16       0  4685.7     .12       0  4956.2     .16       0
  4998.5     .07       0  5004.5     .16       0
Bank Sta=4973,5024
XS Rating Curve= 0 ,0
Exp/Cntr=0.3,0.1

Type RM Length L Ch R = 1 ,21903   ,926,926,926
BEGIN DESCRIPTION:
HAUSLER CREEK 32.0
END DESCRIPTION:
XS GIS Cut Line= 2
      3553087.25     10607739.73      3553639.32     10606406.41
#Sta/Elev= 30
  4357.9  431.77  4375.4  429.69  4411.5  429.66  4436.9  427.81  4452.5  426.66
  4457.9  427.67  4541.3  420.81  4645.8  415.01  4750.2  407.66  4854.7  399.33
  4920.2  396.93  4969.7  397.83  4985.2  397.98    4993  394.29  4995.7  393.79
    4999  394.29  5002.9  394.42  5008.4  397.28  5032.2  398.92  5039.3  397.54
  5158.8  396.63  5234.1  396.17  5277.4  397.34  5319.7   400.7  5385.6  404.92
  5589.4  424.49  5659.8  428.89  5742.8  425.52  5778.6  427.41    5801  427.78
#Mann= 13 ,-1 , 0
  4357.9     .16       0  4436.9     .05       0  4541.3     .16       0
  4645.8     .05       0  4750.2     .16       0  4854.7     .12       0
  4969.7     .16       0    4993     .07       0    4999     .16       0
  5158.8     .12       0  5319.7     .16       0  5589.4      .1       0
  5778.6     .16       0
Bank Sta=4985.2,5032.2
XS Rating Curve= 0 ,0
Exp/Cntr=0.3,0.1

Type RM Length L Ch R = 1 ,20977   ,425,425,425
BEGIN DESCRIPTION:
HAUSLER CREEK 30.0
END DESCRIPTION:
XS GIS Cut Line= 3
      3553449.62     10608010.18      3554049.61     10607210.19
      3553812.19     10606264.73
#Sta/Elev= 30
    4027  442.81  4048.1  441.62  4190.5  428.52  4269.7  423.42  4390.5  411.58
    4523  402.14  4640.5  395.23  4916.7  393.83  4919.4  393.33  4922.7  393.83
  4984.3  395.27  5005.1  394.04  5023.9  395.27  5109.5  395.61  5132.4  393.88
  5150.7  395.99    5192  394.95    5261  399.16  5432.5  414.83  5461.6  417.33
  5485.6  416.51  5534.6   414.8  5655.9  418.47  5744.5  418.32  5749.7  420.53
  5826.8  417.96    5832  420.23  5836.6  419.84    5841  419.47  6001.8  424.35
#Mann= 11 ,-1 , 0
    4027     .05       0  4048.1     .16       0    4523     .12       0
  4916.7     .07       0  4922.7     .12       0    5261     .05       0
  5432.5     .16       0  5485.6     .05       0  5534.6      .1       0
  5836.6     .05       0    5841     .16       0
Bank Sta=4984.3,5023.9
XS Rating Curve= 0 ,0
Exp/Cntr=0.3,0.1

Type RM Length L Ch R = 1 ,20552   ,433,433,433
BEGIN DESCRIPTION:
HAUSLER CREEK 29.0
END DESCRIPTION:
XS GIS Cut Line= 4
      3553599.57     10608160.22      3554399.61     10607360.19
      3554536.59     10607223.21      3554701.67     10606434.44
#Sta/Elev= 30
  3841.9  445.89  3983.4  435.19  4025.8  431.42  4039.9     429  4054.1  428.84
  4082.4  424.65  4181.4  418.71  4304.7  408.27  4432.3  398.66  4534.1  393.28
  4633.9  394.19  4789.5  392.28  4930.9  393.22    4945  391.95  4987.5  393.16
  5001.6  391.64  5015.7  392.84  5218.2  390.92    5221  390.42  5224.2  390.92
  5232.6  391.27  5394.9  392.32  5405.8  393.99  5495.5  399.45  5507.3  401.81
  5537.9  403.54  5650.5  414.45  5786.7  420.63  5854.6  423.11  5972.9  424.09
#Mann= 8 ,-1 , 0
  3841.9     .16       0  4304.7     .12       0  4432.3     .16       0
  4534.1     .12       0  5218.2     .07       0  5224.2     .12       0
  5232.6     .16       0  5786.7     .05       0
Bank Sta=4987.5,5015.7
XS Rating Curve= 0 ,0
Exp/Cntr=0.3,0.1

Type RM Length L Ch R = 1 ,20119   ,467,467,467
BEGIN DESCRIPTION:
HAUSLER CREEK 28.0
END DESCRIPTION:
XS GIS Cut Line= 3
      3554031.65     10608352.11      3554778.18     10607423.28
      3555047.27     10606720.17
#Sta/Elev= 30
  3699.2  431.66  4069.2  402.09  4118.8  400.07  4125.2   397.1  4194.9  393.57
    4282  390.82  4304.4  387.69  4317.5   390.4  4339.6  391.36  4496.4  392.02
  4779.6  390.74  4787.6  386.21    4794  385.93  4808.4   387.3  4816.4  390.15
  4926.3  390.06  4939.6  388.35  4978.5  389.66  4991.3  384.84  4994.1  384.34
  4997.3  384.84 5018.47  390.59  5097.6  395.85  5243.4  409.77  5352.8   412.9
  5358.2  411.41  5407.6  413.56  5412.9  412.26  5467.7  415.72  5643.7  415.27
#Mann= 5 ,-1 , 0
  3699.2     .16       0  4194.9     .12       0  4978.5     .16       0
  4991.3     .07       0  4997.3     .16       0
Bank Sta=4978.5,5018.47
XS Rating Curve= 0 ,0
Exp/Cntr=0.3,0.1

Type RM Length L Ch R = 1 ,19652   ,904,904,904
BEGIN DESCRIPTION:
HAUSLER CREEK 27.0
END DESCRIPTION:
XS GIS Cut Line= 2
      3554595.89     10608447.58      3555480.27     10607103.67
#Sta/Elev= 30
    4005   433.1  4121.6  425.38  4402.9  396.33  4490.3  389.38  4526.4  388.33
  4540.6  384.23  4542.9   385.6  4547.5  388.35  4800.5  388.13  4887.7  389.52
  4899.9  388.03    4909  389.22  4972.2  389.28  4981.3  388.46  4987.2  380.93
  4992.5  380.34  4995.2  379.84  4998.5  380.34  5017.4  384.16  5023.4  388.82
  5031.4  389.16  5053.6  388.63  5074.6  391.58  5106.6  393.25  5292.6  401.85
  5313.7  403.07  5390.9  407.69  5456.2  409.25  5514.4  409.39  5613.8  406.02
#Mann= 8 ,-1 , 0
    4005     .16       0  4542.9     .12       0  4992.5     .07       0
  4998.5     .12       0  5106.6     .16       0  5292.6     .12       0
  5313.7     .16       0  5456.2     .12       0
Bank Sta=4972.2,5031.4
XS Rating Curve= 0 ,0
Exp/Cntr=0.3,0.1