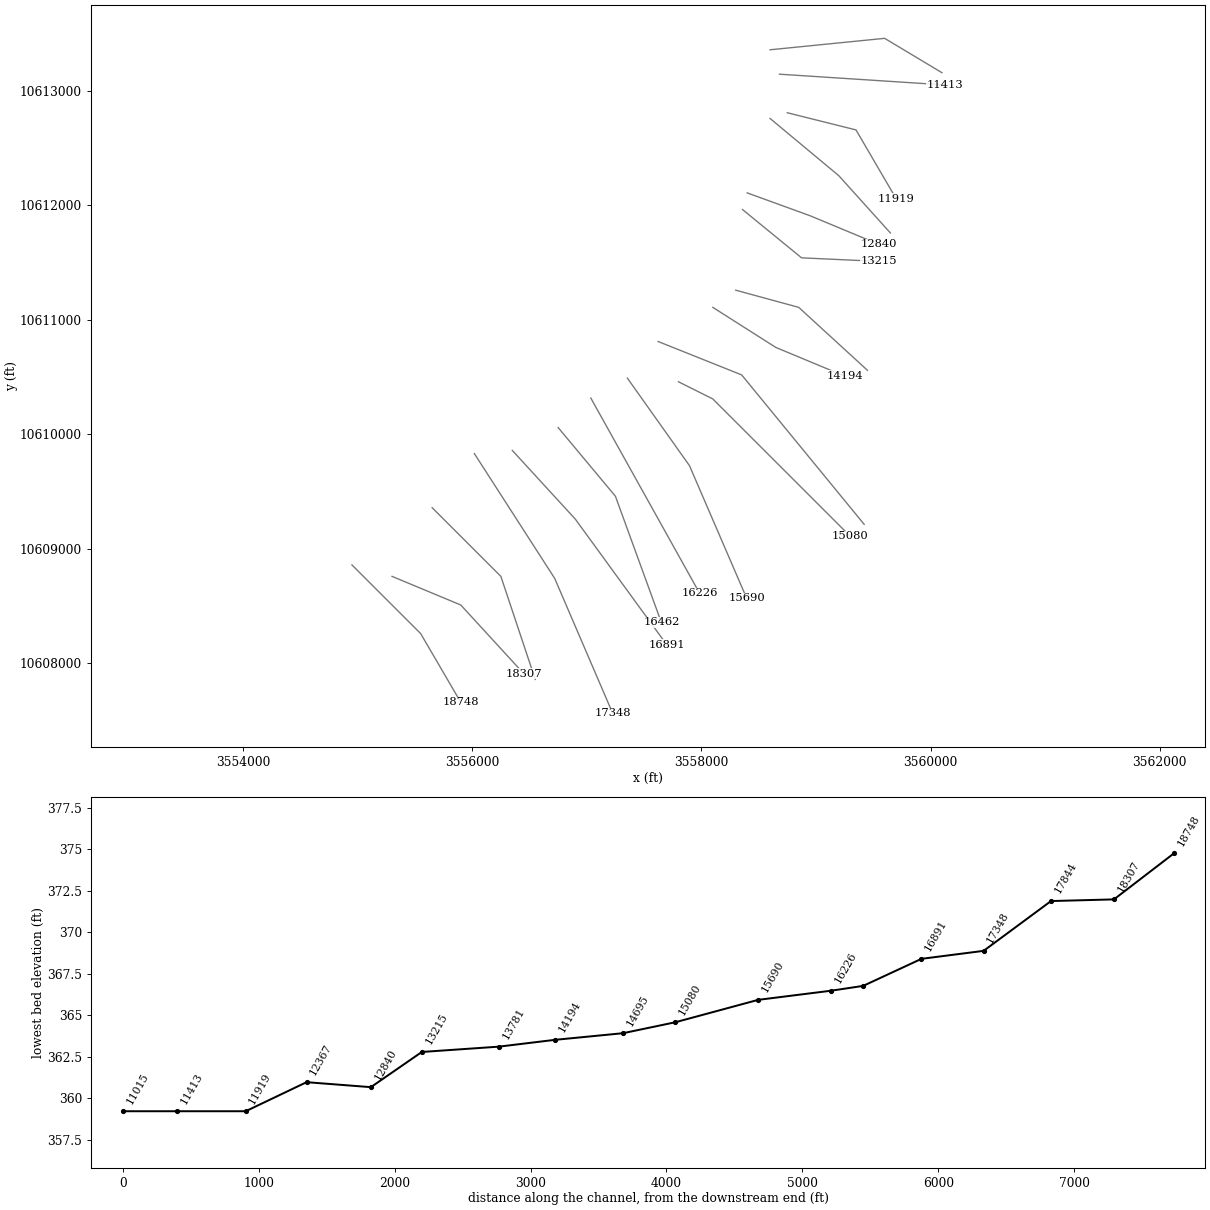
HEC-RAS study HAUSLER CREEK.prj: HAUSLER CREEK Base Level Engineering

--- HAUSLER CREEK.g01 (geometry) --- (continued)

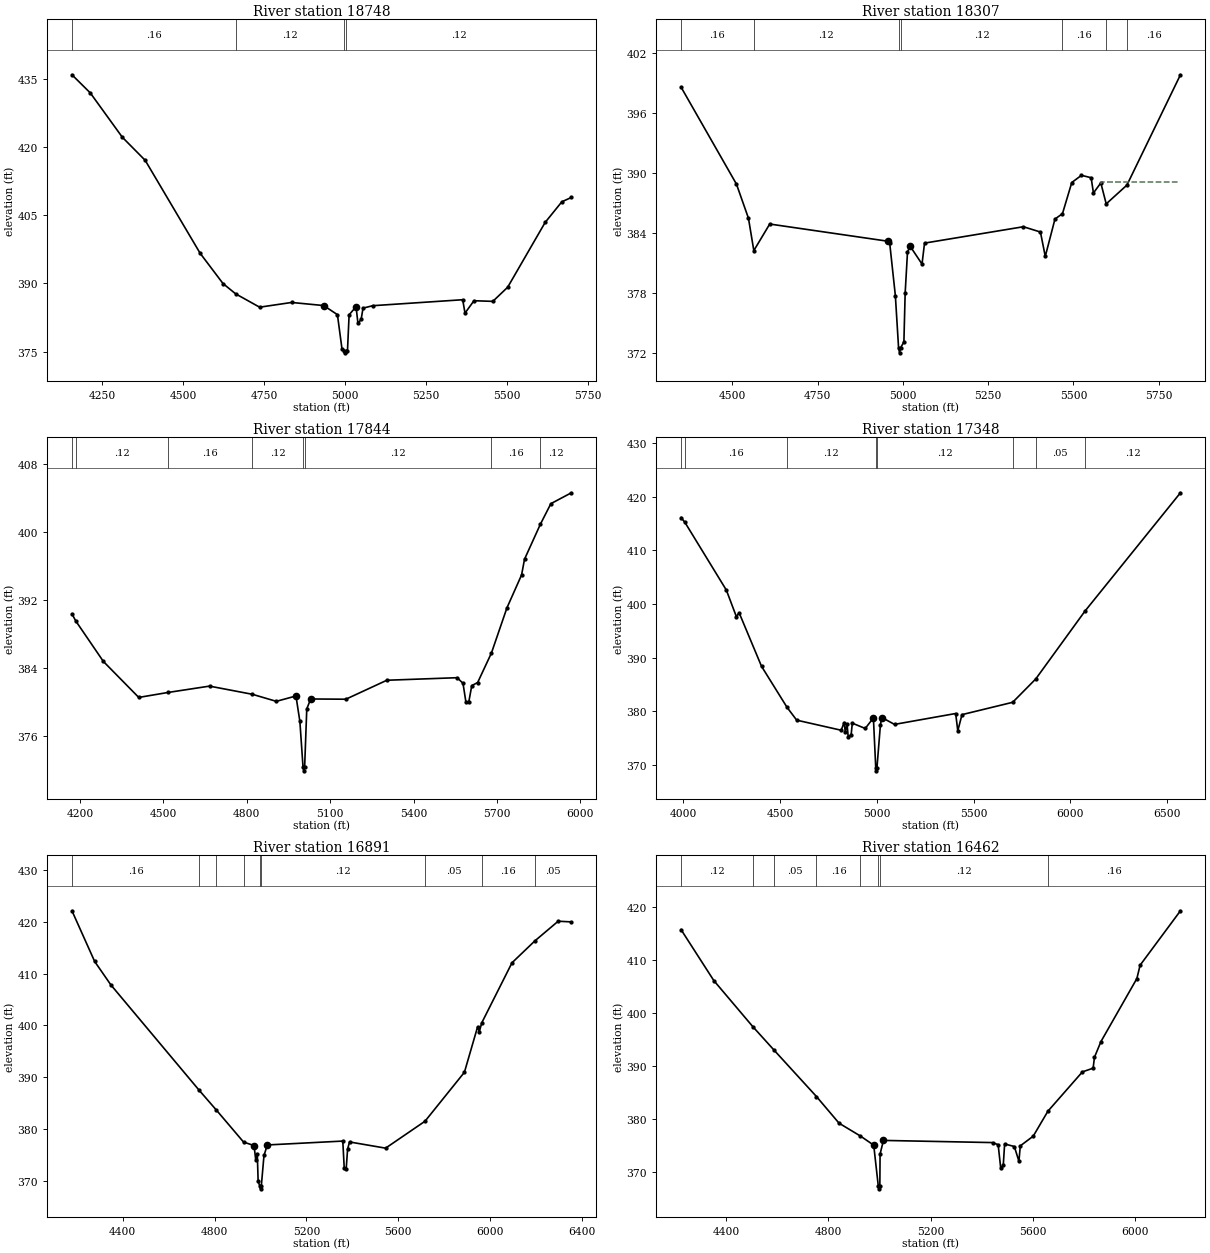
Type RM Length L Ch R = 1 ,18748   ,441,441,441
BEGIN DESCRIPTION:
HAUSLER CREEK 25.0
END DESCRIPTION:
XS GIS Cut Line= 3
      3554949.59     10608860.21      3555549.61     10608260.19
      3555899.62     10607660.17
#Sta/Elev= 30
  4156.1  435.84  4212.7  431.86  4311.7  422.12  4382.4  417.04  4552.1  396.63
  4622.8  389.97    4662   387.7    4736  384.77  4834.9  385.81  4933.9  385.13
  4976.4  383.13  4990.5   375.6  4998.1  375.24  5000.9  374.74  5004.1  375.24
  5007.5  375.24  5012.5  383.09    5034  384.89  5039.8  381.21  5049.7  382.09
  5055.5  384.56  5085.7   385.1  5363.5  386.41  5370.6  383.47  5398.3  386.19
  5456.6  386.05  5502.5  389.16  5618.2  403.39  5669.9  407.94  5699.3  408.88
#Mann= 4 ,-1 , 0
  4156.1     .16       0    4662     .12       0  4998.1     .07       0
  5004.1     .12       0
Bank Sta=4933.9,5034
XS Rating Curve= 0 ,0
Exp/Cntr=0.3,0.1

Type RM Length L Ch R = 1 ,18307   ,463,463,463
BEGIN DESCRIPTION:
HAUSLER CREEK 24.0
END DESCRIPTION:
XS GIS Cut Line= 3
      3555299.65     10608760.17      3555899.61     10608510.19
      3556449.61     10607910.18
#Sta/Elev= 30
  4349.6  398.59  4512.1  388.87  4547.3  385.45    4563  382.21  4609.6  384.87
  4955.7  383.15  4961.1  383.02  4977.9  377.69  4987.3  372.47  4990.1  371.97
  4993.3  372.47  5002.9  373.07  5006.6  377.95  5013.4  382.03  5020.8  382.67
    5056  380.86  5063.4  382.96  5353.2   384.6  5403.1  384.07  5417.3  381.63
  5445.7  385.37  5467.7  385.91    5495  389.03  5523.4  389.75  5551.7  389.51
  5558.5  387.98  5580.1  388.99  5595.9  386.89  5656.6  388.77  5813.5  399.82
#Mann= 7 ,-1 , 0
  4349.6     .16       0    4563     .12       0  4987.3     .07       0
  4993.3     .12       0  5467.7     .16       0  5595.9     .12       0
  5656.6     .16       0
#XS Ineff= 2 , 0
                         5580.68          389.07
Permanent Ineff=
       F       F
Bank Sta=4955.7,5020.8
XS Rating Curve= 0 ,0
Exp/Cntr=0.3,0.1

Type RM Length L Ch R = 1 ,17844   ,496,496,496
BEGIN DESCRIPTION:
HAUSLER CREEK 23.0
END DESCRIPTION:
XS GIS Cut Line= 3
      3555649.61     10609360.18      3556249.61     10608760.19
      3556549.61     10607860.19
#Sta/Elev= 30
  4170.8  390.32  4184.9  389.47  4283.9  384.73  4411.2   380.5  4515.7  381.08
  4665.8  381.83  4819.9  380.87  4906.2  380.04  4976.9  380.67    4991  377.68
  5002.2  372.37  5004.9  371.87  5008.2  372.37  5015.8  379.15  5029.9  380.32
  5156.4  380.29  5303.9  382.52  5556.9  382.82    5578  382.16  5588.5  379.95
  5599.1  380.02  5609.6  381.89  5630.7  382.25  5680.3  385.72  5736.1  391.03
  5788.8   394.9  5799.4  396.75  5856.4  400.86  5894.2  403.28    5968  404.56
#Mann= 8 ,-1 , 0
  4170.8     .16       0  4184.9     .12       0  4515.7     .16       0
  4819.9     .12       0  5002.2     .07       0  5008.2     .12       0
  5680.3     .16       0  5856.4     .12       0
Bank Sta=4976.9,5029.9
XS Rating Curve= 0 ,0
Exp/Cntr=0.3,0.1

Type RM Length L Ch R = 1 ,17348   ,457,457,457
BEGIN DESCRIPTION:
HAUSLER CREEK 22.0
END DESCRIPTION:
XS GIS Cut Line= 3
      3556018.21     10609832.67      3556719.61     10608742.37
      3557225.84     10607563.48
#Sta/Elev= 30
  3989.3  416.11  4009.3  415.21  4223.5  402.57    4275  397.64  4289.5  398.34
  4405.1  388.36  4536.7  380.72  4586.7  378.32  4816.5  376.44  4831.7  377.87
  4837.7  376.17  4846.9  377.59  4852.8  375.16    4868  375.63    4874  377.76
  4940.7  376.77  4982.9  378.74  4995.1  369.37  4997.9  368.87  5001.1  369.37
  5019.2   377.5  5026.7  378.81  5091.9  377.53  5407.8  379.56  5418.7  376.33
  5440.5  379.35  5702.2  381.65  5821.3     386  6075.1  398.63  6568.7  420.72
#Mann= 8 ,-1 , 0
  3989.3     .12       0  4009.3     .16       0  4536.7     .12       0
  4995.1     .07       0  5001.1     .12       0  5702.2     .16       0
  5821.3     .05       0  6075.1     .12       0
Bank Sta=4982.9,5026.7
XS Rating Curve= 0 ,0
Exp/Cntr=0.3,0.1

Type RM Length L Ch R = 1 ,16891   ,429,429,429
BEGIN DESCRIPTION:
HAUSLER CREEK 21.0
END DESCRIPTION:
XS GIS Cut Line= 3
      3556349.64     10609860.16      3556899.61     10609260.19
      3557699.58     10608160.22
#Sta/Elev= 30
  4179.4  422.18  4278.3  412.37  4349.2  407.82  4733.9  387.42  4808.2  383.62
  4926.4  377.44    4972  376.76  4979.4  374.01  4986.2   375.2  4989.9  369.81
  4997.6  368.89  5000.4  368.39  5003.6  368.89  5015.3  374.84    5030  376.88
  5358.4  377.63  5364.6  372.43  5373.1  372.19  5379.3  376.09  5387.8  377.46
  5544.7  376.26  5716.3  381.47  5887.8  390.94  5945.4  399.76  5952.7  398.78
  5963.2   400.5  6094.9  412.12  6193.9  416.33  6295.9  420.16  6353.4  420.03
#Mann= 9 ,-1 , 0
  4179.4     .16       0  4733.9     .05       0  4808.2     .16       0
  4926.4     .12       0  4997.6     .07       0  5003.6     .12       0
  5716.3     .05       0  5963.2     .16       0  6193.9     .05       0
Bank Sta=4972,5030
XS Rating Curve= 0 ,0
Exp/Cntr=0.3,0.1

Type RM Length L Ch R = 1 ,16462   ,236,236,236
BEGIN DESCRIPTION:
HAUSLER CREEK 20.0
END DESCRIPTION:
XS GIS Cut Line= 3
      3556749.62     10610060.18      3557249.61     10609460.19
      3557649.62     10608360.17
#Sta/Elev= 30
  4224.9  415.75  4353.1  406.11  4505.4  397.41    4589  392.94  4754.2   384.2
  4842.5  379.16  4926.2  376.73  4977.9  375.01  4995.8  367.26  4998.5  366.76
  5001.8  367.26  5002.7  373.32  5015.9  375.91  5442.2   375.5  5464.1   375.1
  5474.1  370.69  5484.1  371.22  5489.4  375.24  5527.3  374.76  5545.3  371.97
  5550.6  374.88  5601.1  376.71  5658.5  381.43  5793.3  388.86  5835.2  389.56
  5840.5  391.63  5865.8  394.59  6006.1  406.49  6018.8  409.02  6176.4   419.3
#Mann= 8 ,-1 , 0
  4224.9     .12       0  4505.4     .16       0    4589     .05       0
  4754.2     .16       0  4926.2     .12       0  4995.8     .07       0
  5001.8     .12       0  5658.5     .16       0
Bank Sta=4977.9,5015.9
XS Rating Curve= 0 ,0
Exp/Cntr=0.3,0.1

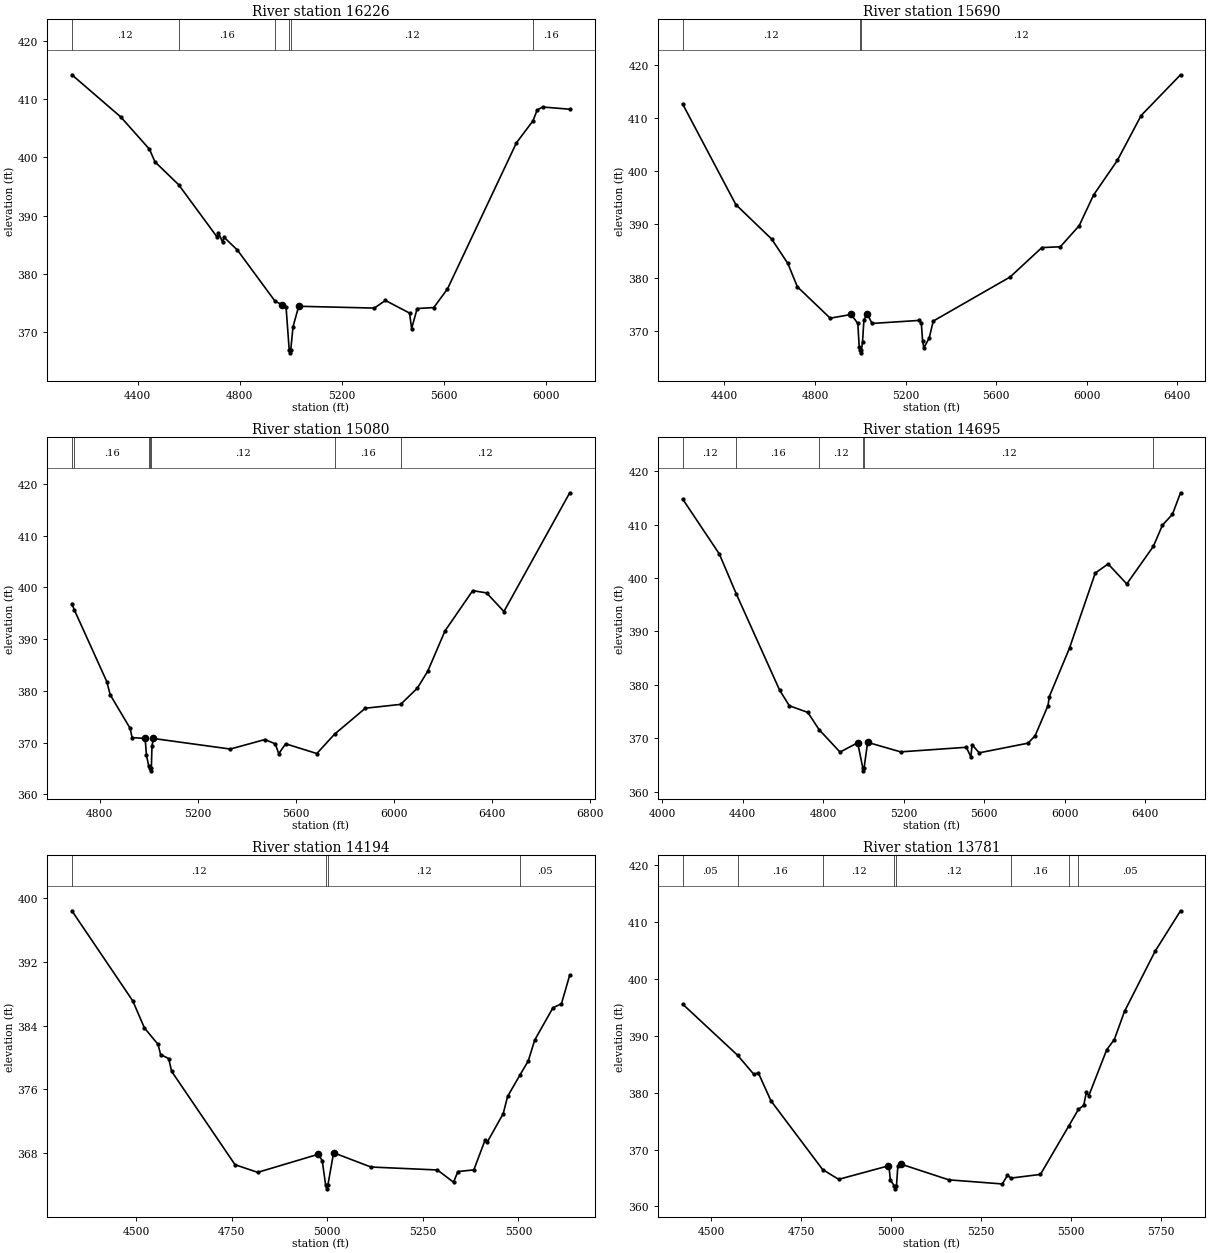
Type RM Length L Ch R = 1 ,16226   ,536,536,536
BEGIN DESCRIPTION:
HAUSLER CREEK 19.0
END DESCRIPTION:
XS GIS Cut Line= 2
      3557034.76     10610317.93      3557985.37     10608610.99
#Sta/Elev= 30
  4141.3  414.18  4333.3  406.94  4445.7  401.41  4467.4  399.24  4560.5  395.31
  4710.9  386.36  4716.6  387.09  4732.6  385.46  4738.3  386.31  4791.2  384.09
  4938.1  375.36  4965.8  374.72  4981.8  374.34  4994.2  366.97  4996.9  366.47
  5000.2  366.97  5009.3  370.97  5031.5  374.46  5328.2  374.15  5371.7  375.46
  5466.5  373.29  5474.6  370.62  5496.3  374.07  5561.5  374.24  5615.2  377.43
  5886.1  402.52    5951  406.29  5967.3  408.14    5989  408.65  6095.1  408.27
#Mann= 6 ,-1 , 0
  4141.3     .12       0  4560.5     .16       0  4938.1     .12       0
  4994.2     .07       0  5000.2     .12       0    5951     .16       0
Bank Sta=4965.8,5031.5
XS Rating Curve= 0 ,0
Exp/Cntr=0.3,0.1

Type RM Length L Ch R = 1 ,15690   ,610,610,610
BEGIN DESCRIPTION:
HAUSLER CREEK 18.0
END DESCRIPTION:
XS GIS Cut Line= 3
      3557354.23     10610491.49      3557895.89     10609727.62
      3558395.24     10608569.41
#Sta/Elev= 30
    4216   412.6  4450.5  393.75    4609  387.26  4680.4  382.69  4722.2  378.32
  4867.3  372.42  4959.7  373.12  4989.2  371.43  4995.3  367.07  4999.2  366.42
  5001.9  365.92  5005.2  366.42  5010.1  368.01  5016.2  372.14    5031  373.21
  5051.9  371.43  5258.5     372  5269.4  371.61  5275.2   368.1  5280.6  366.85
  5304.1  368.67  5322.2  371.88  5661.5  380.15  5801.7  385.67  5883.2  385.82
  5966.4  389.78  6029.7  395.52  6134.7  402.01  6239.7  410.44  6413.7  418.09
#Mann= 3 ,-1 , 0
    4216     .12       0  4999.2     .07       0  5005.2     .12       0
Bank Sta=4959.7,5031
XS Rating Curve= 0 ,0
Exp/Cntr=0.3,0.1

Type RM Length L Ch R = 1 ,15080   ,385,385,385
BEGIN DESCRIPTION:
HAUSLER CREEK 17.0
END DESCRIPTION:
XS GIS Cut Line= 3
      3557799.65     10610460.17      3558099.61     10610310.19
      3559299.59      10609110.2
#Sta/Elev= 30
  4686.9  396.87  4696.7  395.68  4829.4  381.81  4843.4  379.25  4924.4  372.81
  4932.8     371  4985.9  370.82  4991.5  367.55  5000.9  365.45  5005.3  365.07
    5008  364.57  5011.3  365.07  5013.9  369.33  5019.5  370.82  5333.4  368.78
  5474.8  370.61  5517.2  369.79  5531.4  367.89  5559.7  369.79  5686.9  367.91
  5759.2  371.65  5884.9  376.66    6029  377.41  6097.1  380.54  6139.5   383.8
  6210.2  391.61  6323.3  399.38  6379.9  398.94  6450.6  395.34  6719.3  418.28
#Mann= 7 ,-1 , 0
  4686.9     .12       0  4696.7     .16       0  5000.9     .12       0
  5005.3     .07       0  5011.3     .12       0  5759.2     .16       0
    6029     .12       0
Bank Sta=4985.9,5019.5
XS Rating Curve= 0 ,0
Exp/Cntr=0.3,0.1

Type RM Length L Ch R = 1 ,14695   ,501,501,501
BEGIN DESCRIPTION:
HAUSLER CREEK 16.0
END DESCRIPTION:
XS GIS Cut Line= 3
      3557622.39     10610811.81      3558351.55     10610520.15
      3559420.75     10609214.89
#Sta/Elev= 30
  4102.5  414.77  4284.9  404.47  4368.9  397.01  4584.2     379  4632.3  376.09
  4724.2  374.84  4779.6  371.64  4884.1  367.42  4971.7  369.16  4997.4  364.41
  5000.1  363.91  5003.4  364.41  5021.2  369.24  5185.1  367.46  5511.4  368.32
  5533.7  366.51  5540.1  368.79  5575.3  367.28  5817.9  369.09  5853.1  370.49
  5916.9  376.12  5923.4  377.79  6023.9   386.9  6151.6  400.91  6215.5  402.63
  6308.1  398.88  6440.4  405.93  6485.4  409.89  6534.9  411.91  6575.1  415.94
#Mann= 6 ,-1 , 0
  4102.5     .12       0  4368.9     .16       0  4779.6     .12       0
  4997.4     .07       0  5003.4     .12       0  6440.4     .05       0
Bank Sta=4971.7,5021.2
XS Rating Curve= 0 ,0
Exp/Cntr=0.3,0.1

Type RM Length L Ch R = 1 ,14194   ,413,413,413
BEGIN DESCRIPTION:
HAUSLER CREEK 15.0
END DESCRIPTION:
XS GIS Cut Line= 3
      3558099.58     10611110.21      3558649.61     10610760.19
      3559249.65     10610510.17
#Sta/Elev= 30
  4332.2  398.43  4491.4  387.12  4521.9  383.72  4557.4  381.66  4564.2  380.38
  4585.4  379.87    4593  378.27  4758.9  366.54  4818.2  365.58  4976.5  367.85
  4986.9  367.06  4995.8  364.01  4998.5  363.51  5001.8  364.01  5016.7  368.04
  5114.2  366.25    5288  365.88  5330.3  364.34  5341.7  365.68  5383.4  365.89
  5412.6  369.61    5418  369.34  5460.3  372.96  5471.7  375.12  5504.7  377.86
  5525.8  379.58  5542.6   382.2  5590.3  386.25  5612.5  386.75  5634.2  390.36
#Mann= 4 ,-1 , 0
  4332.2     .12       0  4995.8     .07       0  5001.8     .12       0
  5504.7     .05       0
Bank Sta=4976.5,5016.7
XS Rating Curve= 0 ,0
Exp/Cntr=0.3,0.1

Type RM Length L Ch R = 1 ,13781   ,566,566,566
BEGIN DESCRIPTION:
HAUSLER CREEK 14.0
END DESCRIPTION:
XS GIS Cut Line= 3
       3558299.6     10611260.19      3558849.61     10611110.19
      3559449.58     10610560.22
#Sta/Elev= 30
    4421  395.58    4574  386.57    4618   383.3  4631.8  383.43  4666.3  378.59
    4810   366.5  4854.6  364.77  4991.1  367.11  4994.5  367.11  4998.2   364.7
  5009.4   363.6  5012.1   363.1  5015.4   363.6  5019.2  367.13  5026.6  367.47
    5161  364.68  5309.6  363.96  5323.8  365.46    5334  364.99  5415.6  365.64
  5494.6  374.18  5521.1  377.06  5535.9  377.78  5543.3  380.07  5550.1  379.49
    5600  387.58    5621  389.35  5649.3   394.3  5734.4  404.88    5805  411.99
#Mann= 8 ,-1 , 0
    4421     .05       0    4574     .16       0    4810     .12       0
  5009.4     .07       0  5015.4     .12       0    5334     .16       0
  5494.6     .08       0  5521.1     .05       0
Bank Sta=4991.1,5026.6
XS Rating Curve= 0 ,0
Exp/Cntr=0.3,0.1

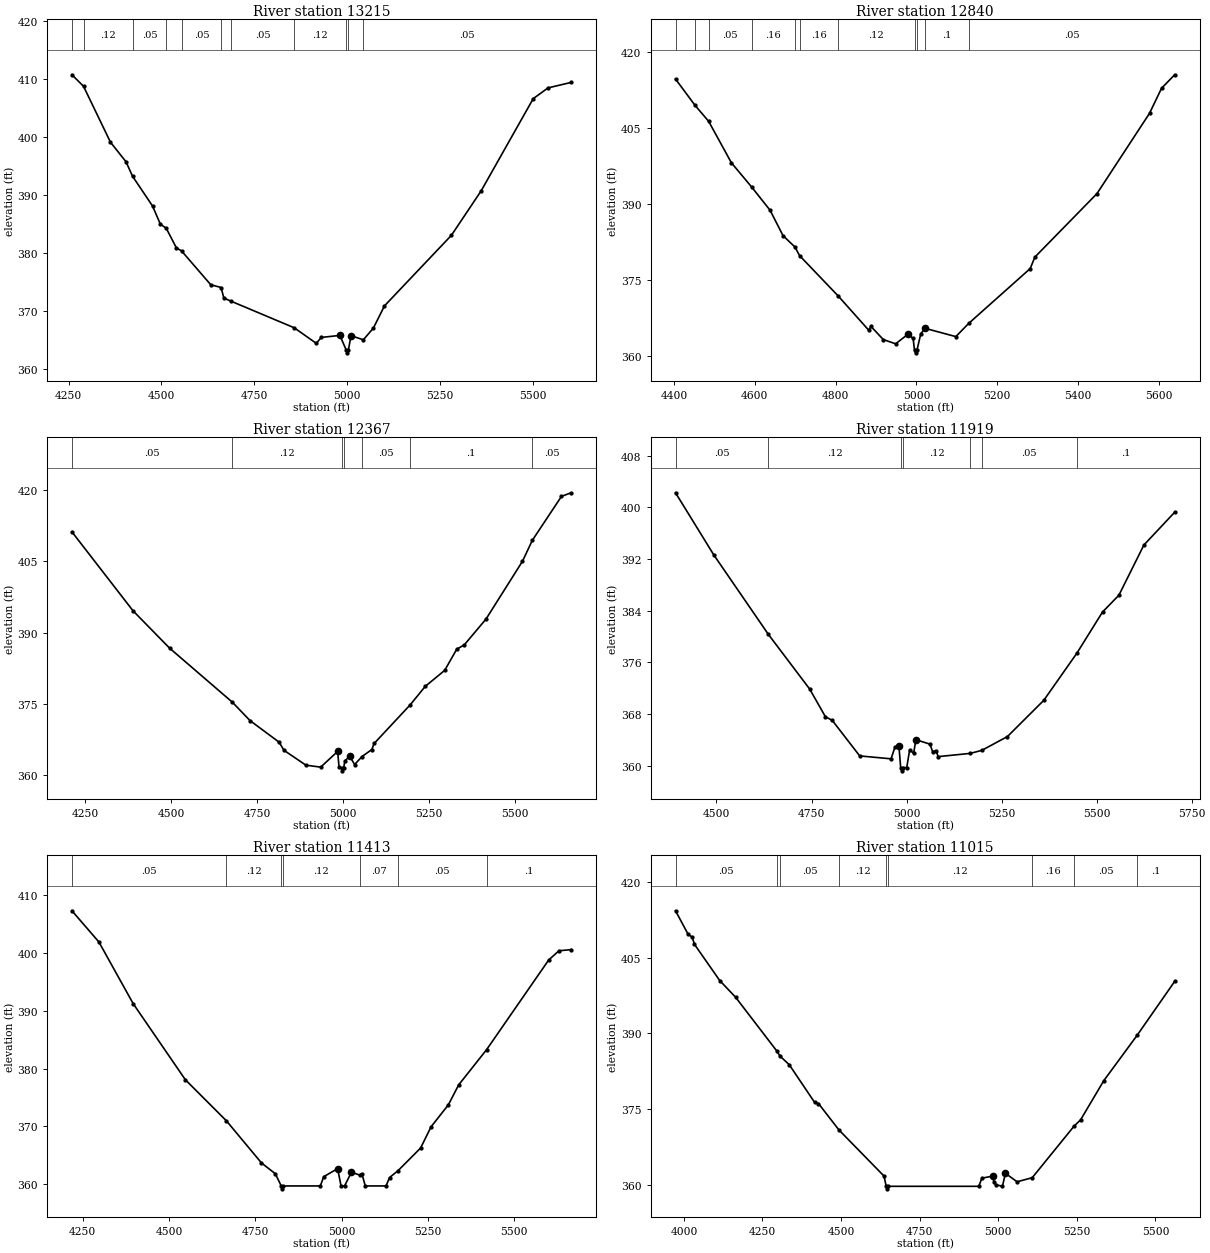
Type RM Length L Ch R = 1 ,13215   ,375,375,375
BEGIN DESCRIPTION:
HAUSLER CREEK 13.0
END DESCRIPTION:
XS GIS Cut Line= 3
      3558358.86     10611964.67      3558874.47      10611542.8
      3559551.55     10611511.55
#Sta/Elev= 30
  4259.2  410.79  4290.4   408.8    4363  399.14  4404.6  395.79  4422.5  393.26
  4476.4  388.11  4497.2  385.01  4513.1  384.29  4540.3  380.92  4554.6  380.36
  4632.9  374.54  4660.9  374.06  4668.1  372.25  4686.7  371.72  4857.6  367.11
  4917.1  364.42  4930.5  365.44  4980.6  365.79  4997.6  363.28  5000.4  362.78
  5003.6  363.28  5010.6  365.75  5043.7  365.03  5070.7  367.04  5100.7  370.89
  5280.9  383.07    5361  390.75  5501.2  406.67  5541.2  408.53  5603.2  409.47
#Mann= 11 ,-1 , 0
  4259.2     .16       0  4290.4     .12       0  4422.5     .05       0
  4513.1     .16       0  4554.6     .05       0  4660.9     .16       0
  4686.7     .05       0  4857.6     .12       0  4997.6     .07       0
  5003.6     .12       0  5043.7     .05       0
Bank Sta=4980.6,5010.6
XS Rating Curve= 0 ,0
Exp/Cntr=0.3,0.1

Type RM Length L Ch R = 1 ,12840   ,473,473,473
BEGIN DESCRIPTION:
HAUSLER CREEK 12.0
END DESCRIPTION:
XS GIS Cut Line= 3
       3558399.6     10612110.19      3558949.61     10611910.19
      3559549.57      10611660.2
#Sta/Elev= 30
  4403.9  414.65    4452  409.48  4485.8  406.32  4542.2  398.13  4592.6  393.33
    4638  388.76  4669.9  383.77  4699.4  381.53    4711  379.82  4806.1   371.9
  4882.1  365.11  4887.4  365.88    4918  363.28  4948.6  362.44  4979.2  364.34
  4991.8   363.5  4995.3  361.16  4998.1  360.66  5001.3  361.16  5010.8  364.42
  5020.3  365.36  5021.6  365.49  5097.5  363.86  5129.3  366.46  5281.6  377.28
    5293  379.53  5446.8  392.06  5576.8  407.89  5606.6  412.84  5639.1  415.49
#Mann= 11 ,-1 , 0
  4403.9     .05       0    4452     .08       0  4485.8     .05       0
  4592.6     .16       0  4699.4      .1       0    4711     .16       0
  4806.1     .12       0  4995.3     .07       0  5001.3     .12       0
  5020.3      .1       0  5129.3     .05       0
Bank Sta=4979.2,5021.6
XS Rating Curve= 0 ,0
Exp/Cntr=0.3,0.1

Type RM Length L Ch R = 1 ,12367   ,448,448,448
BEGIN DESCRIPTION:
HAUSLER CREEK 11.0
END DESCRIPTION:
XS GIS Cut Line= 3
      3558599.63     10612760.17      3559199.61     10612260.19
      3559649.62     10611760.18
#Sta/Elev= 30
  4211.1  411.21  4388.8  394.63  4495.5  386.76  4678.3  375.39  4729.8  371.52
  4814.4  366.99  4828.7  365.27  4892.5  362.15  4935.5  361.74  4984.9  365.04
  4988.8  361.87  4996.2  361.46    4999  360.96  5002.2  361.46  5005.9  363.05
  5020.1  364.03  5034.3  362.28  5055.8  363.96  5084.4  365.44  5091.1  366.71
  5196.2  374.84  5239.9  378.71  5296.7  382.09  5331.8  386.55  5353.5  387.43
    5417  392.88  5523.1  405.02    5552  409.45  5636.8  418.68  5664.8  419.43
#Mann= 7 ,-1 , 0
  4211.1     .05       0  4678.3     .12       0  4996.2     .07       0
  5002.2     .12       0  5055.8     .05       0  5196.2      .1       0
    5552     .05       0
Bank Sta=4984.9,5020.1
XS Rating Curve= 0 ,0
Exp/Cntr=0.3,0.1

Type RM Length L Ch R = 1 ,11919   ,506,506,506
BEGIN DESCRIPTION:
HAUSLER CREEK 10.0
END DESCRIPTION:
XS GIS Cut Line= 3
      3558749.57      10612810.2      3559349.61     10612660.19
      3559699.59     10612060.21
#Sta/Elev= 30
  4392.3  402.24  4492.8  392.64  4636.6  380.32  4745.4  371.85  4786.6  367.58
  4804.7  367.01  4876.8  361.52  4959.3  361.07  4969.6  362.89  4979.9  363.05
  4984.6  359.71  4987.4  359.21  4990.6  359.71  5000.5  359.71  5008.2  362.46
  5018.7  361.92  5024.5  364.03  5061.7  363.34  5068.7  362.15  5077.4  362.34
  5083.2  361.41  5167.6  361.91    5198  362.38  5265.5  364.52    5361  370.12
  5448.1  377.42  5515.6  383.79  5558.6  386.39  5624.4  394.16  5705.4  399.23
#Mann= 7 ,-1 , 0
  4392.3     .05       0  4636.6     .12       0  4984.6     .07       0
  4990.6     .12       0  5167.6     .16       0    5198     .05       0
  5448.1      .1       0
Bank Sta=4979.9,5024.5
XS Rating Curve= 0 ,0
Exp/Cntr=0.3,0.1

Type RM Length L Ch R = 1 ,11413   ,398,398,398
BEGIN DESCRIPTION:
HAUSLER CREEK 9.0
END DESCRIPTION:
XS GIS Cut Line= 2
      3558681.72     10613146.97      3560124.48     10613053.22
#Sta/Elev= 30
    4219  407.32  4297.1  401.92  4396.5  391.24  4547.6  378.08  4666.4  370.98
    4768  363.69  4808.1  361.82  4825.2  359.71  4827.9  359.21  4831.2  359.71
  4938.4  359.71  4948.4  361.32  4988.5   362.7  4998.5  359.71  5008.6  359.71
  5028.6  362.09  5051.9   361.6  5058.7  361.84  5068.7  359.71  5128.8  359.71
  5138.8  361.16  5163.3  362.34    5229  366.28  5259.1  369.94  5309.2  373.74
  5339.2   377.2    5420  383.29  5599.8   398.8  5629.6   400.4  5664.8   400.6
#Mann= 7 ,-1 , 0
    4219     .05       0  4666.4     .12       0  4825.2     .07       0
  4831.2     .12       0  5051.9     .07       0  5163.3     .05       0
    5420      .1       0
Bank Sta=4988.5,5028.6
XS Rating Curve= 0 ,0
Exp/Cntr=0.3,0.1

Type RM Length L Ch R = 1 ,11015   ,604,604,604
BEGIN DESCRIPTION:
HAUSLER CREEK 8.0
END DESCRIPTION:
XS GIS Cut Line= 3
      3558599.61     10613360.19      3559599.61     10613460.19
      3560099.62     10613160.18
#Sta/Elev= 30
  3973.3  414.31  4013.5  409.63  4026.1  409.11  4033.6  407.66    4114  400.48
  4164.3  397.19  4294.8  386.58  4305.9   385.5  4335.1  383.81  4415.5  376.37
  4428.1  376.12  4492.9   370.9  4636.6  361.74  4643.6  359.71  4646.4  359.21
  4649.6  359.71  4938.1  359.71  4948.1  361.33  4983.3  361.74  4986.1  360.48
  4991.9  360.03  5013.3  359.72    5023  362.28  5059.9  360.61    5108  361.41
  5241.2  371.63  5262.1  372.89  5335.9  380.65  5441.7  389.62  5561.4  400.32
#Mann= 9 ,-1 , 0
  3973.3     .05       0  4294.8     .16       0  4305.9     .05       0
  4492.9     .12       0  4643.6     .07       0  4649.6     .12       0
    5108     .16       0  5241.2     .05       0  5441.7      .1       0
Bank Sta=4983.3,5023
XS Rating Curve= 0 ,0
Exp/Cntr=0.3,0.1