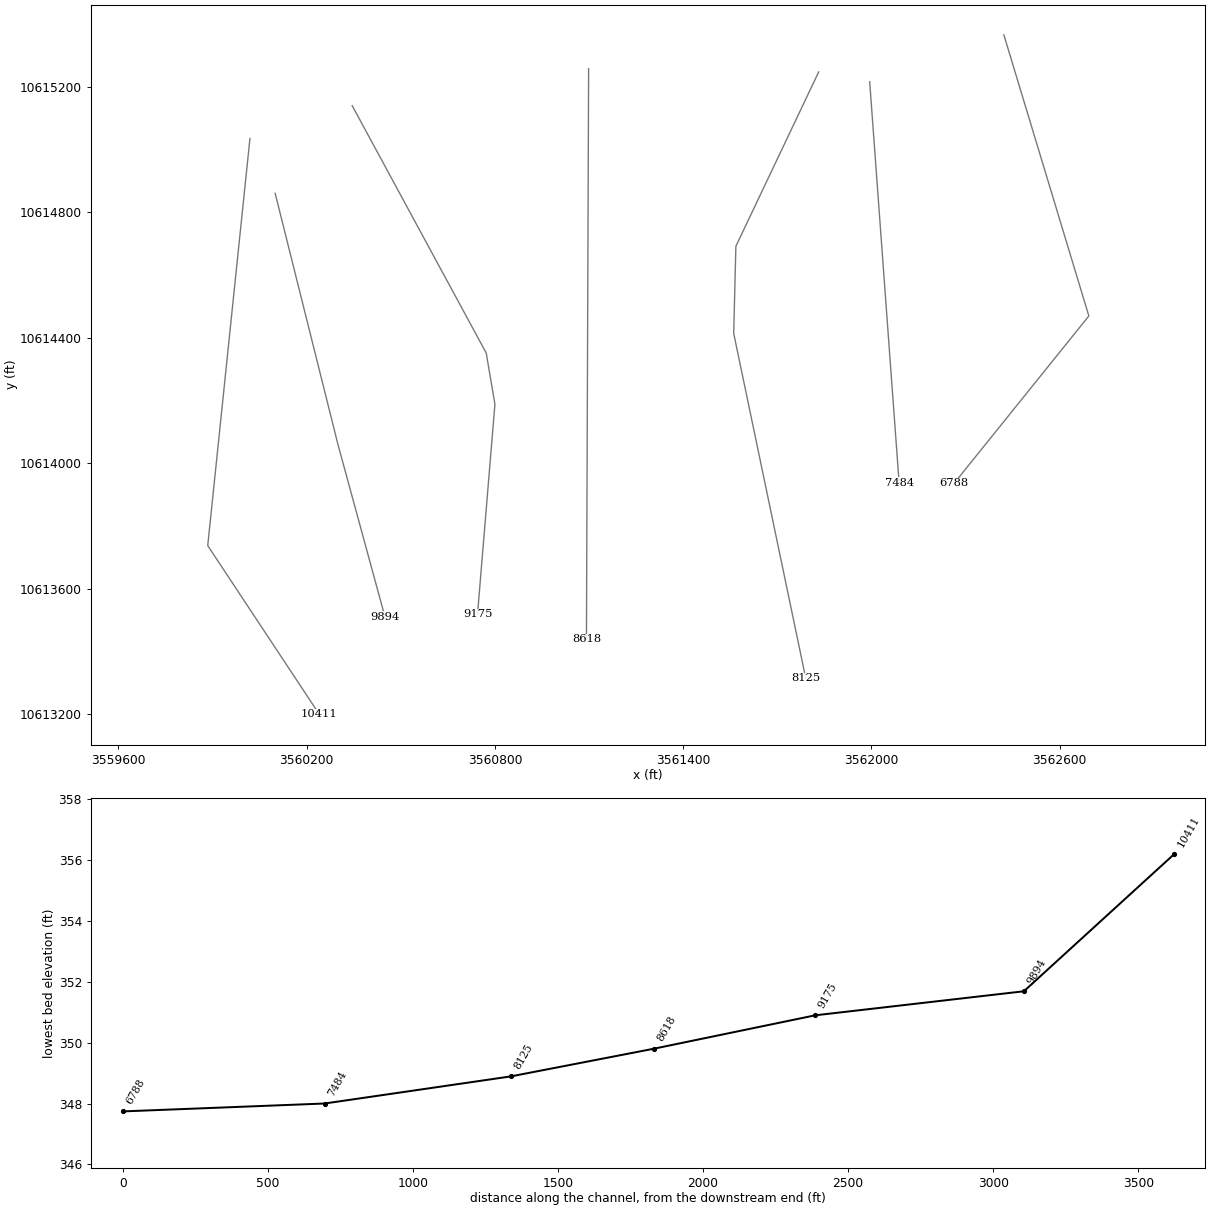
HEC-RAS study HAUSLER CREEK.prj: HAUSLER CREEK Base Level Engineering

--- HAUSLER CREEK.g01 (geometry) --- (continued)

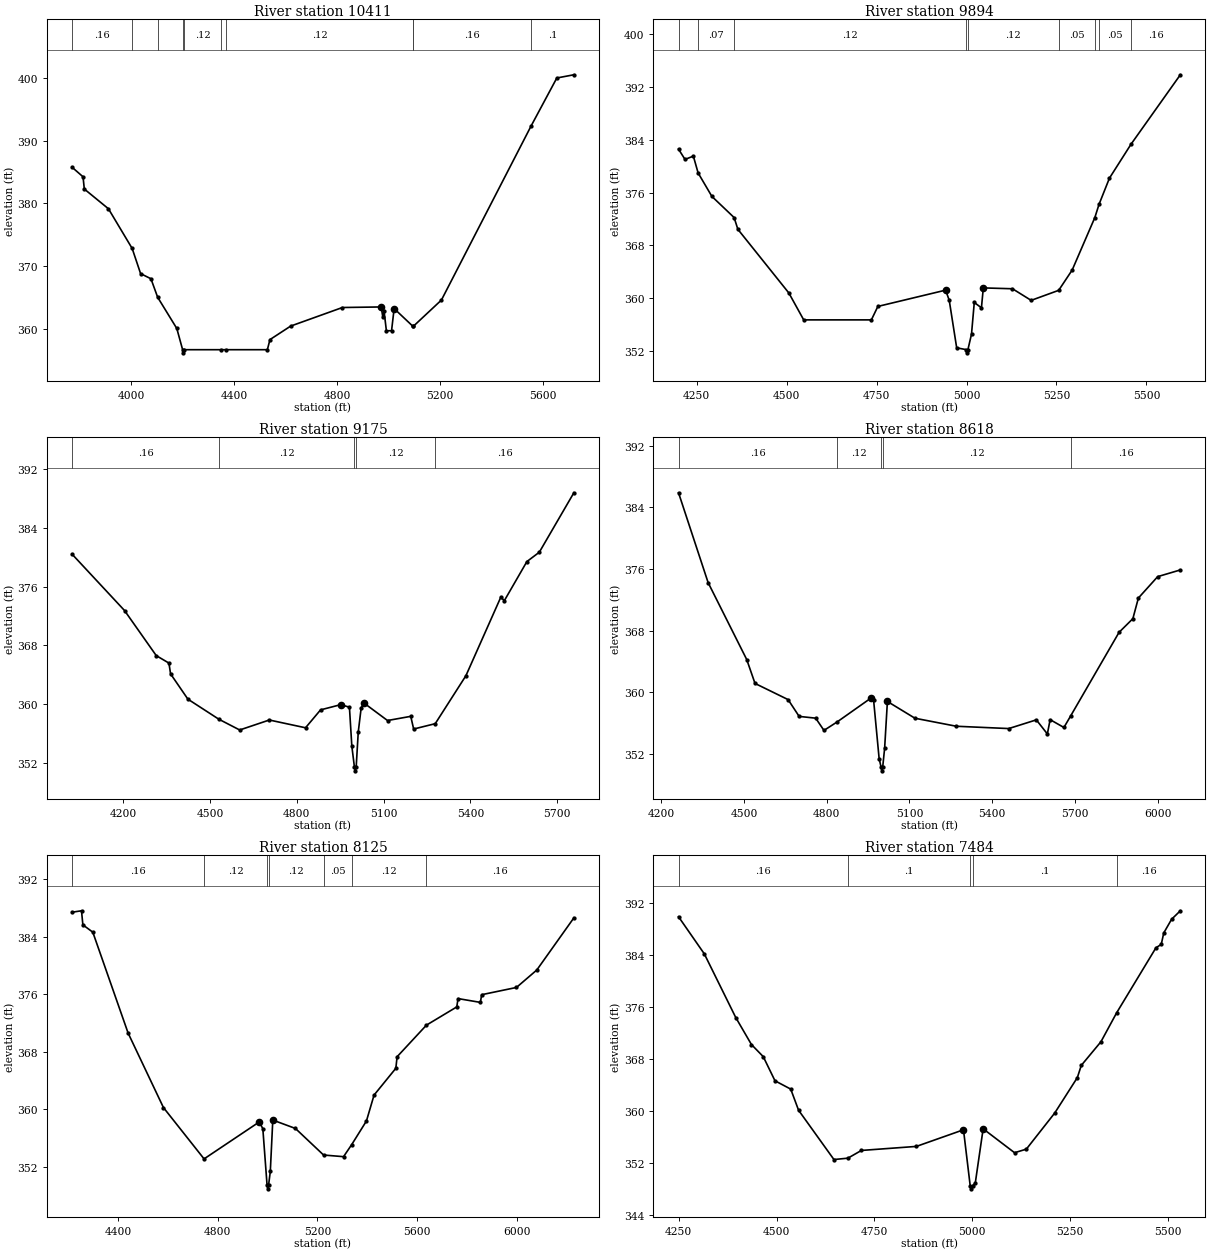
Type RM Length L Ch R = 1 ,10411   ,517,517,517
BEGIN DESCRIPTION:
HAUSLER CREEK 7.0
END DESCRIPTION:
XS GIS Cut Line= 3
      3560019.26     10615035.04      3559884.71     10613737.31
       3560240.6     10613199.13
#Sta/Elev= 30
  3770.4  385.75    3813  384.23    3818  382.28  3911.7  379.14    4004  372.81
  4036.7  368.81  4076.9  367.99    4103  365.04  4177.4  360.07    4200  356.69
  4202.7  356.19    4206  356.69  4350.7  356.69  4369.6  356.69  4529.3  356.69
  4539.4   358.3  4619.8  360.45  4820.9  363.41  4971.7   363.5  4977.9  361.89
  4982.9   362.8  4991.8  359.71  5011.9  359.71  5021.9  363.24  5095.5  360.39
  5095.8  360.39  5205.7   364.6  5554.2  392.33  5654.1  399.97  5720.3  400.48
#Mann= 10 ,-1 , 0
  3770.4     .16       0    4004     .05       0    4103     .12       0
    4200     .07       0    4206     .12       0  4350.7     .05       0
  4369.6     .12       0  5095.5     .07       0  5095.8     .16       0
  5554.2      .1       0
Bank Sta=4971.7,5021.9
XS Rating Curve= 0 ,0
Exp/Cntr=0.3,0.1

Type RM Length L Ch R = 1 ,9894    ,719,719,719
BEGIN DESCRIPTION:
HAUSLER CREEK 6.0
END DESCRIPTION:
XS GIS Cut Line= 3
      3560099.62     10614860.16      3560299.61     10614060.19
      3560449.61     10613510.17
#Sta/Elev= 30
  4199.5  382.59  4217.5  381.03  4240.7  381.53  4253.9  378.98  4292.2  375.42
    4354  372.21  4364.4  370.43  4506.1  360.77  4547.4  356.69  4735.5  356.69
  4753.5  358.73 4941.82   361.2  4951.9  359.66  4972.6  352.45  4997.9  352.19
  5000.6  351.69  5003.9  352.19  5013.8  354.53  5021.5  359.33  5041.4  358.52
  5046.6  361.54  5127.7  361.41  5179.6  359.65  5256.1  361.17  5293.6  364.25
  5356.6  372.21  5368.2  374.21  5397.2  378.19  5457.2  383.34  5594.2  393.87
#Mann= 9 ,-1 , 0
  4199.5     .16       0  4253.9     .07       0    4354     .12       0
  4997.9     .07       0  5003.9     .12       0  5256.1     .05       0
  5356.6     .16       0  5368.2     .05       0  5457.2     .16       0
Bank Sta=4941.82,5046.6
XS Rating Curve= 0 ,0
Exp/Cntr=0.3,0.1

Type RM Length L Ch R = 1 ,9175    ,557,557,557
BEGIN DESCRIPTION:
HAUSLER CREEK 5.0
END DESCRIPTION:
XS GIS Cut Line= 4
       3560345.2     10615139.46       3560772.3     10614351.25
      3560800.07     10614188.05      3560744.57     10613518.48
#Sta/Elev= 30
  4023.8  380.44    4205  372.76  4314.7  366.61  4358.5  365.59  4364.2  364.12
  4424.1  360.67  4530.9  357.94    4603  356.47  4705.4  357.83  4830.5  356.77
  4882.4  359.21  4951.8  359.92  4982.2  359.58  4990.5  354.27  4999.5   351.4
  5002.3   350.9  5005.5   351.4  5012.7  356.19  5022.8   359.5  5032.9  360.13
  5113.8  357.76  5194.1  358.33  5204.1   356.6  5278.7  357.33  5384.7  363.87
  5505.1  374.56  5517.6  374.11  5595.4  379.43  5638.4  380.71  5757.7  388.81
#Mann= 5 ,-1 , 0
  4023.8     .16       0  4530.9     .12       0  4999.5     .07       0
  5005.5     .12       0  5278.7     .16       0
Bank Sta=4951.8,5032.9
XS Rating Curve= 0 ,0
Exp/Cntr=0.3,0.1

Type RM Length L Ch R = 1 ,8618    ,493,493,493
BEGIN DESCRIPTION:
HAUSLER CREEK 4.0
END DESCRIPTION:
XS GIS Cut Line= 2
      3561098.69     10615257.47      3561091.74     10613438.09
#Sta/Elev= 30
  4262.6  385.91  4369.9  374.24  4509.9  364.25  4539.9  361.15  4659.9  359.05
  4699.9  356.87  4759.9  356.64  4789.9  355.05  4837.2  356.14  4959.9  359.24
  4969.9  358.97  4989.9   351.4  4996.9   350.3  4999.6   349.8  5002.9   350.3
  5009.9  352.75  5019.9  358.81  5119.9  356.63  5269.9  355.59  5459.9  355.29
  5559.9  356.42  5599.9  354.59  5609.9  356.45  5659.9  355.43  5684.5  356.94
  5859.9  367.79  5909.9  369.56  5929.9  372.24  5999.9  375.02    6082  375.89
#Mann= 5 ,-1 , 0
  4262.6     .16       0  4837.2     .12       0  4996.9     .07       0
  5002.9     .12       0  5684.5     .16       0
Bank Sta=4959.9,5019.9
XS Rating Curve= 0 ,0
Exp/Cntr=0.3,0.1

Type RM Length L Ch R = 1 ,8125    ,641,641,641
BEGIN DESCRIPTION:
HAUSLER CREEK 3.0
END DESCRIPTION:
XS GIS Cut Line= 4
      3561831.96     10615247.05      3561568.05     10614691.45
      3561561.11     10614413.67      3561790.74     10613314.45
#Sta/Elev= 30
  4214.5  387.42  4252.4  387.62  4257.9  385.66  4297.8  384.64  4439.7  370.58
  4581.6  360.21  4744.8  353.06  4966.7  358.21  4980.9  357.26  4997.9  349.39
  5000.7  348.89  5003.9  349.39  5010.9  351.31  5020.9  358.47  5111.8   357.3
  5224.9   353.6  5305.1  353.37  5337.7  355.04  5397.1  358.34  5427.7  361.95
  5515.2  365.68  5520.3  367.29  5638.1  371.69    5760  374.23  5765.1  375.39
  5854.9  374.86    5860  375.93  5999.8  376.94  6081.5  379.37  6230.4  386.63
#Mann= 7 ,-1 , 0
  4214.5     .16       0  4744.8     .12       0  4997.9     .07       0
  5003.9     .12       0  5224.9     .05       0  5337.7     .12       0
  5638.1     .16       0
Bank Sta=4966.7,5020.9
XS Rating Curve= 0 ,0
Exp/Cntr=0.3,0.1

Type RM Length L Ch R = 1 ,7484    ,696,696,696
BEGIN DESCRIPTION:
HAUSLER CREEK 2.0
END DESCRIPTION:
XS GIS Cut Line= 2
      3561994.52     10615215.88      3562088.27     10613938.01
#Sta/Elev= 30
  4249.8  389.88  4315.7  384.16  4395.9  374.37    4436  370.21  4466.1  368.35
  4496.1  364.63  4536.3  363.35  4556.3   360.1  4646.6  352.51  4682.2  352.72
  4716.7  353.91  4857.1  354.53  4977.4  357.09  4994.5   348.5  4997.2     348
  5000.5   348.5  5007.5  348.88  5027.6  357.24  5107.8  353.56  5137.9  354.11
  5210.4  359.67  5268.2  365.13  5278.2     367  5328.4  370.64  5368.6  375.11
  5468.8   385.1  5482.4  385.63  5488.8  387.39  5508.9   389.5  5531.1   390.8
#Mann= 5 ,-1 , 0
  4249.8     .16       0  4682.2      .1       0  4994.5     .05       0
  5000.5      .1       0  5368.6     .16       0
Bank Sta=4977.4,5027.6
XS Rating Curve= 0 ,0
Exp/Cntr=0.3,0.1

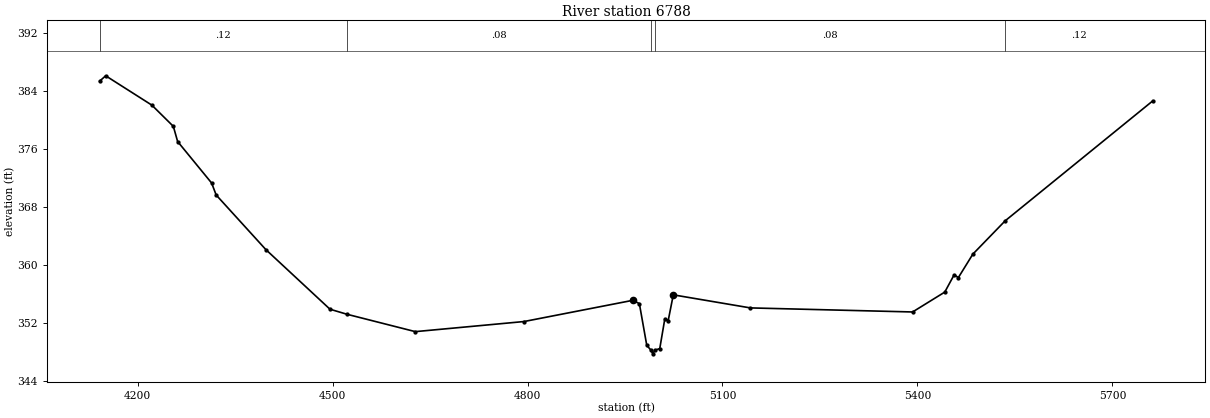
Type RM Length L Ch R = 1 ,6788    ,0,0,0
BEGIN DESCRIPTION:
HAUSLER CREEK 1.0
END DESCRIPTION:
XS GIS Cut Line= 3
      3562422.22     10615365.07      3562693.05     10614469.23
      3562263.82     10613936.14
#Sta/Elev= 30
  4141.7  385.32    4151  386.06  4222.1  382.01  4255.1  379.09  4261.7     377
    4314  371.28    4321  369.63  4397.5   362.1  4496.1  353.89  4522.4  353.19
  4627.4   350.8  4794.5  352.19  4961.7  355.11  4972.1  354.67  4983.5  348.91
    4990  348.24  4992.8  347.74    4996  348.24  5003.5  348.47  5011.3  352.58
  5016.5  352.33  5024.3  355.87  5142.9  354.07  5392.5  353.51    5442  356.25
  5456.4  358.63  5462.9  358.25  5485.2  361.48  5534.9  366.07    5762   382.6
#Mann= 5 ,-1 , 0
  4141.7     .12       0  4522.4     .08       0    4990     .05       0
    4996     .08       0  5534.9     .12       0
Bank Sta=4961.7,5024.3
XS Rating Curve= 0 ,0
Exp/Cntr=0.3,0.1

Chan Stop Cuts=-1
Use User Specified Reach Order=0
Composite Channel Slope=5