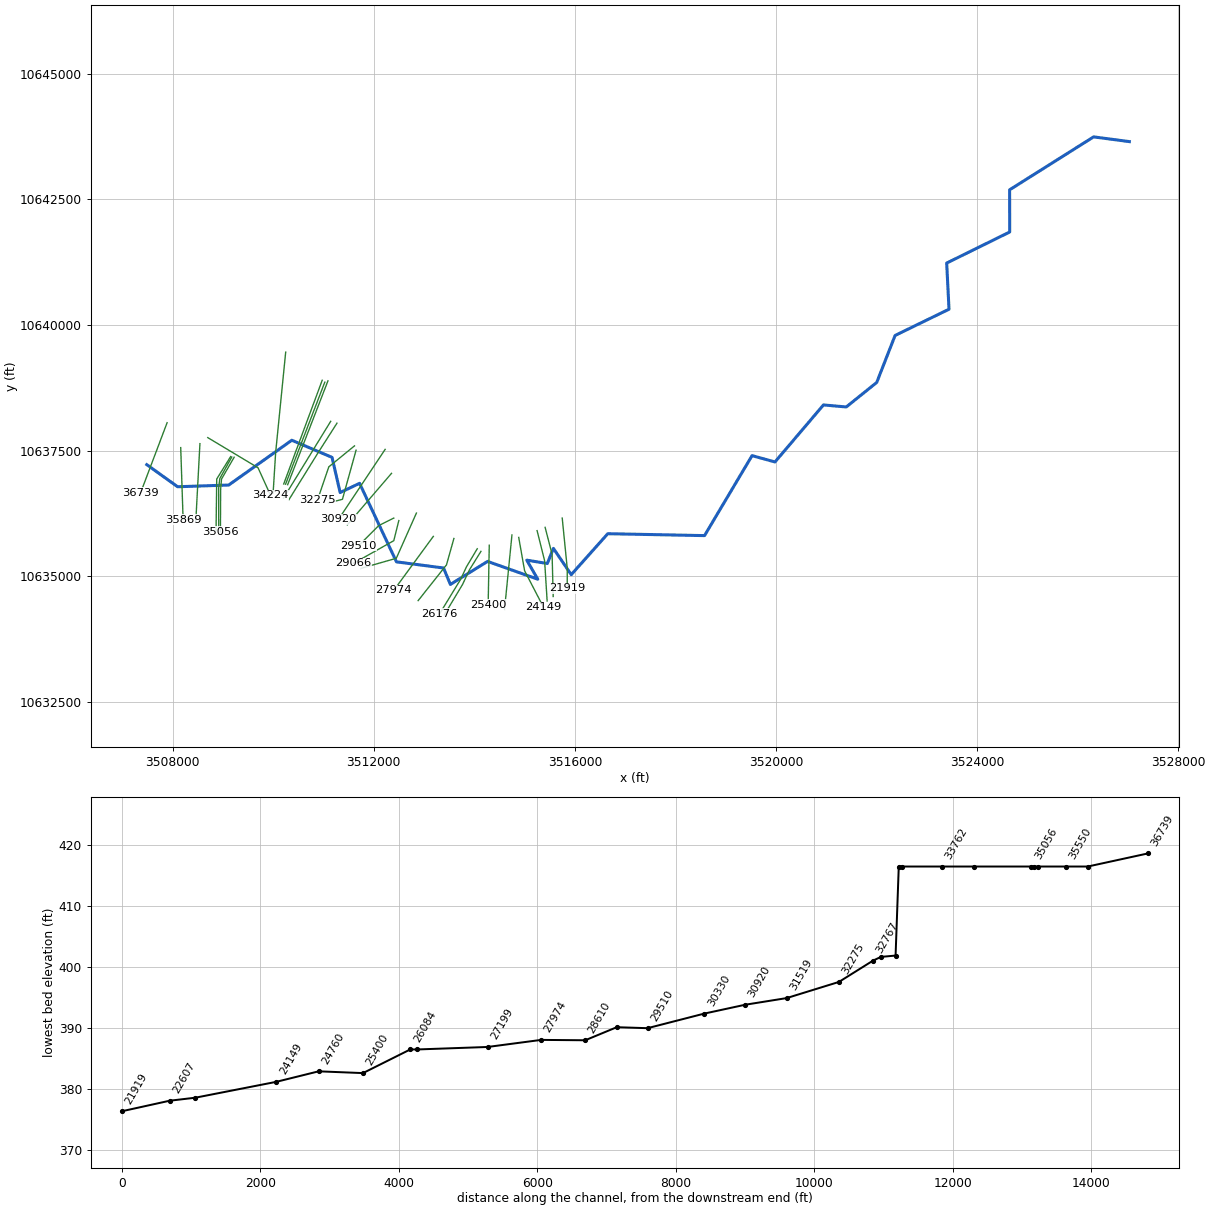
--- JACKSON BRANCH.prj (project) ---

Proj Title=JACKSON BRANCH Base Level Engineering
Current Plan=p01
Default Exp/Contr=0.3,0.1
English Units
Geom File=g01
Flow File=f01
Plan File=p01
Y Axis Title=Elevation
X Axis Title(PF)=Main Channel Distance
X Axis Title(XS)=Station
BEGIN DESCRIPTION:
JACKSON BRANCH
END DESCRIPTION:
DSS Export Rating Curves= 0
DSS Export Rating Curve Sorted= 0
DSS Export Volume Flow Curves= 0
DXF OffsetX= 0
DXF OffsetY= 0
DXF ScaleX= 1
DXF ScaleY= 10

--- JACKSON BRANCH.p01 (plan) ---

Plan Title=Multiple Run
Short Identifier=Multiple
Geom File=g01
Flow File=f01
Subcritical Flow
K Sum by GR= 0
Std Step Tol= 0.01
Critical Tol= 0.01
Num of Std Step Trials= 20
Max Error Tol= 0.3
Flow Tol Ratio= 0.001
Split Flow NTrial= 30
Split Flow Tol= 0.02
Split Flow Ratio= 0.02
Log Output Level= 0
Friction Slope Method= 1
Unsteady Friction Slope Method= 2
Unsteady Bridges Friction Slope Method= 1
Parabolic Critical Depth
Global Vel Dist=  1 , 1 , 1
Global Log Level= 0
CheckData=True
Encroach Param= -1, 0, 0, 0
BEGIN DESCRIPTION:
Multiple Run
END DESCRIPTION:

--- JACKSON BRANCH.f01 (steady flow) ---

Flow Title=Multiple
Program Version=4.10
Number of Profiles= 7
Profile Names=10-year,25-year,50-year,1pct_min,100-year,1pct_plu,500-year
River Rch & RM=JACKSON BRANCH,Reach-1         ,36739
    1382    1900    2326    2077    2809    3799    4084
River Rch & RM=JACKSON BRANCH,Reach-1         ,33762
    1933    2697    3335    3002    4060    5491    6006
River Rch & RM=JACKSON BRANCH,Reach-1         ,24149
    2452    3453    4295    3886    5256    7108    7855
River Rch & RM=JACKSON BRANCH,Reach-1         ,10309
    3574    5104    6407    5843    7902   10686   11999
River Rch & RM=JACKSON BRANCH,Reach-1         ,8907
    3574    5104    6407    5843    7902   10686   11999
Boundary for River Rch & Prof#=JACKSON BRANCH,Reach-1         , 1
Up Type= 0
Dn Type= 3
Dn Slope=0.005
Boundary for River Rch & Prof#=JACKSON BRANCH,Reach-1         , 2
Up Type= 0
Dn Type= 3
Dn Slope=0.005
Boundary for River Rch & Prof#=JACKSON BRANCH,Reach-1         , 3
Up Type= 0
Dn Type= 3
Dn Slope=0.005
Boundary for River Rch & Prof#=JACKSON BRANCH,Reach-1         , 4
Up Type= 0
Dn Type= 3
Dn Slope=0.005
Boundary for River Rch & Prof#=JACKSON BRANCH,Reach-1         , 5
Up Type= 0
Dn Type= 3
Dn Slope=0.005
Boundary for River Rch & Prof#=JACKSON BRANCH,Reach-1         , 6
Up Type= 0
Dn Type= 3
Dn Slope=0.005
Boundary for River Rch & Prof#=JACKSON BRANCH,Reach-1         , 7
Up Type= 0
Dn Type= 3
Dn Slope=0.005
DSS Import GetInterval= 0
DSS Import GetPeak= 0
DSS Import FillOption= 0

--- JACKSON BRANCH.g01 (geometry) ---

Geom Title=Existing Conditions
Program Version=4.10

River Reach=JACKSON BRANCH  ,Reach-1
Reach XY= 30
       3507486.5     10637222.72      3508100.25       10636783.
      3509116.25       10636817.       3510371.5       10637708.
      3511171.75       10637367.      3511332.75       10636668.
        3511719.       10636851.       3512452.5       10635289.
      3513388.75       10635167.      3513525.25       10634840.
        3514265.       10635298.        3515263.       10634944.
      3515044.25       10635323.        3515453.       10635256.
      3515574.25       10635557.      3515928.75       10635034.
       3516655.5       10635849.      3518579.75       10635811.
        3519525.       10637402.      3519981.25       10637276.
        3520945.       10638410.      3521398.25       10638370.
      3522004.75       10638857.      3522369.75       10639792.
      3523442.25       10640314.        3523396.       10641232.
       3524649.5       10641850.       3524647.5       10642689.
       3526318.5       10643742.      3527029.25       10643648.

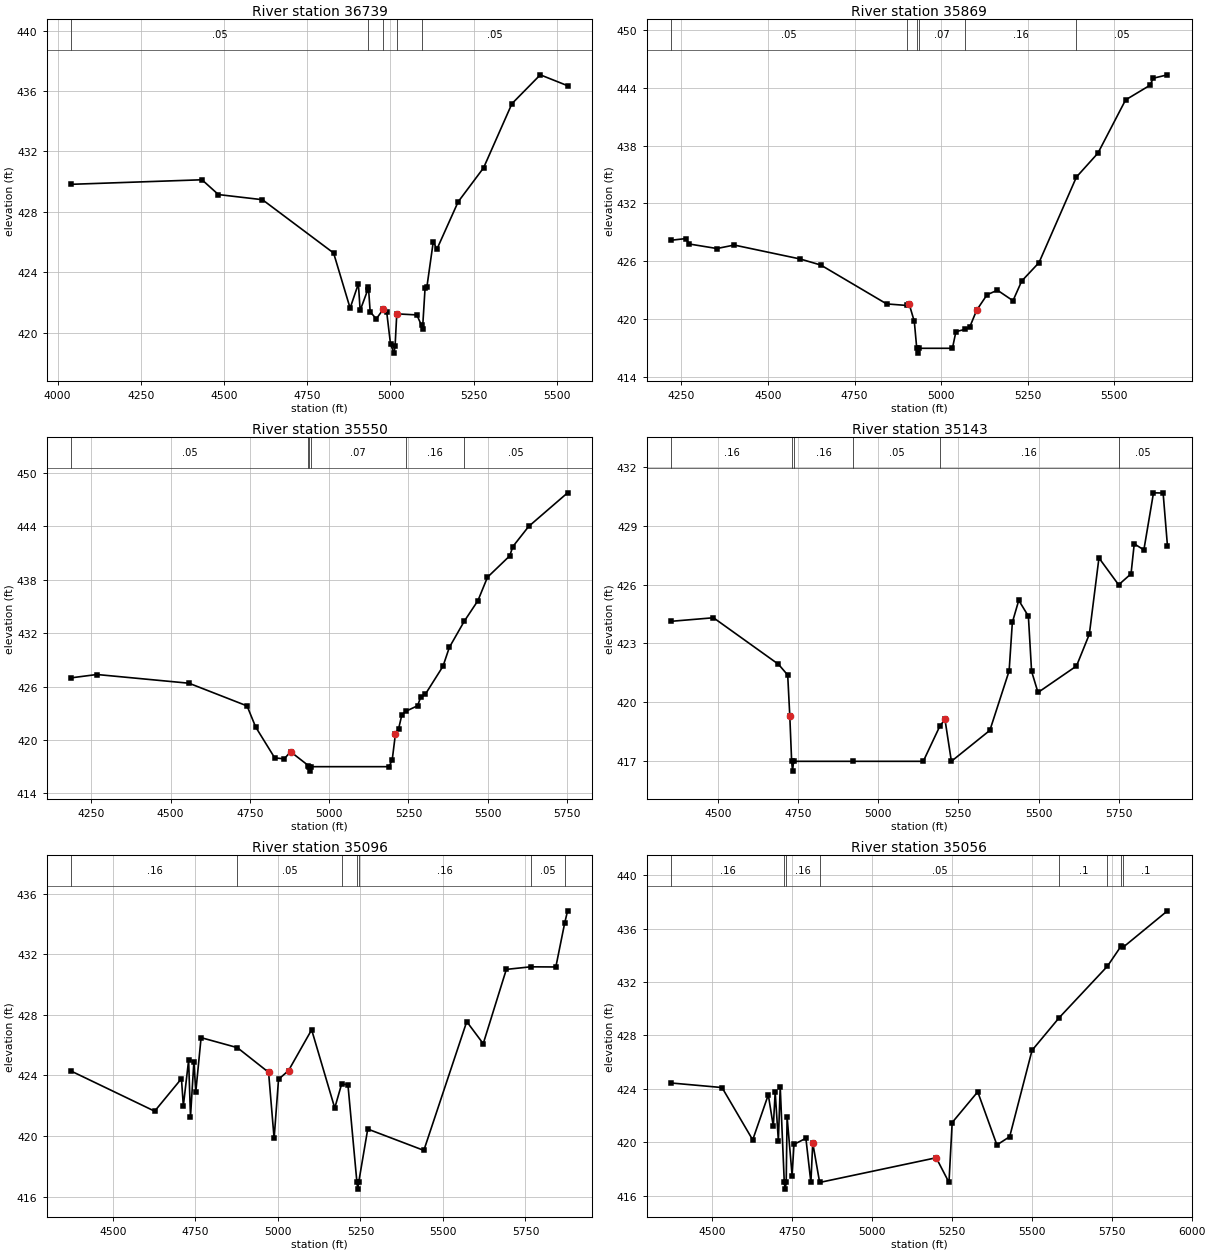
Type RM Length L Ch R = 1 ,36739   ,870,870,870
BEGIN DESCRIPTION:
JACKSON BRANCH 49.0
END DESCRIPTION:
XS GIS Cut Line= 2
       3507891.2     10638056.93      3507364.02     10636662.67
#Sta/Elev= 30
  4041.5  429.82  4433.6  430.12    4483  429.14  4615.3   428.8  4829.1  425.27
  4878.7  421.62  4903.5  423.23  4908.9  421.47  4931.2   422.8  4933.7  423.03
    4939  421.37  4957.4  420.91  4978.8  421.56  4988.7  421.35  5000.2  419.22
  5010.6  418.64  5013.9  419.14  5018.9  421.24  5079.2  421.17  5093.3  420.47
  5096.4  420.27    5104  422.98  5109.4  423.02  5128.5  426.01  5139.6  425.53
  5203.3  428.66  5279.7  430.91  5364.9  435.16  5450.1  437.07  5532.1  436.35
#Mann= 5 ,-1 , 0
  4041.5     .05       0  4931.2      .7       0  4978.8     .03       0
  5018.9     .05       0  5093.3     .05       0
Bank Sta=4978.8,5018.9
XS Rating Curve= 0 ,0
Exp/Cntr=0.3,0.1

Type RM Length L Ch R = 1 ,35869   ,319,319,319
BEGIN DESCRIPTION:
JACKSON BRANCH 48.0
END DESCRIPTION:
XS GIS Cut Line= 2
      3508161.74      10637561.6      3508209.48     10636129.29
#Sta/Elev= 30
  4220.9  428.19  4262.3  428.36  4272.3   427.8  4352.4  427.33  4402.4  427.69
  4592.5  426.25  4652.5  425.62  4842.7  421.59  4901.1  421.43  4907.6   421.6
  4922.7  419.77  4929.7  416.99  4932.5  416.49  4935.7  416.99  5032.8  416.99
  5042.8  418.71  5070.5  418.97  5082.8  419.19  5102.8  420.94  5132.8  422.54
  5162.8  423.01  5207.7  421.92  5232.9  423.96  5282.9  425.87    5391  434.74
    5453  437.21    5533  442.73  5603.1  444.24  5613.1  444.98    5654  445.33
#Mann= 6 ,-1 , 0
  4220.9     .05       0  4901.1     .07       0  4929.7     .07       0
  4935.7     .07       0  5070.5     .16       0    5391     .05       0
Bank Sta=4907.6,5102.8
XS Rating Curve= 0 ,0
Exp/Cntr=0.3,0.1

Type RM Length L Ch R = 1 ,35550   ,407,407,407
BEGIN DESCRIPTION:
JACKSON BRANCH 47.0
END DESCRIPTION:
XS GIS Cut Line= 2
      3508543.99     10637640.31      3508460.66     10636077.83
#Sta/Elev= 30
  4187.1  426.98  4267.3  427.35  4557.7  426.37  4740.9  423.82    4768  421.45
  4828.1  417.98  4858.2  417.87  4878.2  418.67    4934  417.12  4935.3  416.99
    4938  416.49  4941.3  416.99  5188.6  416.99  5198.7  417.75  5208.7  420.62
  5218.7  421.22  5228.7  422.76  5241.3  423.21  5278.8  423.84  5288.8  424.84
    5303  425.12  5358.9  428.28  5378.9   430.4    5426  433.34    5469  435.65
  5499.1  438.28  5569.2  440.68  5579.2  441.73  5629.3     444  5751.8  447.77
#Mann= 6 ,-1 , 0
  4187.1     .05       0    4934     .07       0  4935.3     .07       0
  4941.3     .07       0  5241.3     .16       0    5426     .05       0
Bank Sta=4878.2,5208.7
XS Rating Curve= 0 ,0
Exp/Cntr=0.3,0.1

Type RM Length L Ch R = 1 ,35143   ,47,47,47
BEGIN DESCRIPTION:
JACKSON BRANCH 46.0
END DESCRIPTION:
XS GIS Cut Line= 3
      3509155.66     10637383.66      3508877.88      10636936.6
      3508864.86     10635916.61
#Sta/Elev= 30
  4355.4  424.13  4486.6  424.31  4689.1  421.94    4718  421.39  4724.5  419.31
  4730.3  416.99  4733.1  416.49  4736.3  416.99  4922.3  416.99  5140.6  416.99
  5192.1  418.78  5208.2  419.13  5228.2  416.99  5348.2  418.57  5408.2   421.6
  5418.2  424.07  5438.2   425.2  5468.2  424.39  5478.2  421.58  5498.2   420.5
  5618.2  421.85  5658.2  423.47  5688.2  427.36  5749.5  425.99  5788.2  426.55
  5798.2  428.08  5828.2  427.77  5858.2  430.68  5888.2  430.67  5901.8  427.96
#Mann= 6 ,-1 , 0
  4355.4     .16       0  4730.3    .033       0  4736.3     .16       0
  4922.3     .05       0  5192.1     .16       0  5749.5     .05       0
Bank Sta=4724.5,5208.2
XS Rating Curve= 0 ,0
Exp/Cntr=0.3,0.1

Type RM Length L Ch R = 1 ,35096   ,40,40,40
BEGIN DESCRIPTION:
Mapping XS 81be9ccc
END DESCRIPTION:
XS GIS Cut Line= 4
      3509177.35     10637374.94      3508938.65     10636945.28
      3508916.94     10636754.31      3508916.94     10635934.62
#Sta/Elev= 30
  4374.2  424.28  4626.3  421.64  4707.5  423.79  4713.2  421.99  4729.2  425.01
  4734.9  421.27  4745.2  424.92  4750.9  422.91    4767   426.5  4876.8  425.84
  4971.5  424.21  4988.3  419.84  5001.7  423.75  5031.9  424.32    5102  427.02
    5172  421.85  5192.8  423.43    5212  423.39    5239  416.99  5241.8  416.49
    5245  416.99    5272  420.46    5442  419.05    5572  427.56    5622   426.1
    5692  431.01  5765.7  431.18    5842  431.17  5868.9  434.08  5877.6  434.88
#Mann= 7 ,-1 , 0
  4374.2     .16       0  4876.8     .05       0  5192.8     .16       0
    5239    .033       0    5245     .16       0  5765.7     .05       0
  5868.9      .1       0
Bank Sta=4971.5,5031.9
XS Rating Curve= 0 ,0
Exp/Cntr=0.3,0.1

Type RM Length L Ch R = 1 ,35056   ,832,832,832
BEGIN DESCRIPTION:
JACKSON BRANCH 45.0
END DESCRIPTION:
XS GIS Cut Line= 4
       3509225.1     10637370.62      3508973.37      10636936.6
      3508956.01     10636732.61      3508951.67     10635886.29
#Sta/Elev= 30
  4371.5  424.44    4530   424.1  4626.1  420.18  4674.9  423.56  4690.6  421.19
  4696.4  423.76  4706.4  420.11  4712.2  424.15  4724.9  416.99  4727.7  416.49
  4730.9  416.99  4733.7  421.91  4749.4  417.51  4755.2  419.84  4792.5   420.3
  4808.2  416.99    4814  419.95  4835.6  416.99  5200.4  418.84  5240.4  416.99
  5250.4  421.48  5330.4  423.78  5390.4   419.8  5430.4  420.42  5500.4  426.89
  5585.6  429.34  5736.3  433.19    5780  434.73  5785.5  434.61  5924.3  437.34
#Mann= 8 ,-1 , 0
  4371.5     .16       0  4724.9    .033       0  4730.9     .16       0
  4835.6     .05       0  5585.6      .1       0  5736.3     .16       0
    5780     .05       0  5785.5      .1       0
Bank Sta=4814,5200.4
XS Rating Curve= 0 ,0
Exp/Cntr=0.3,0.1

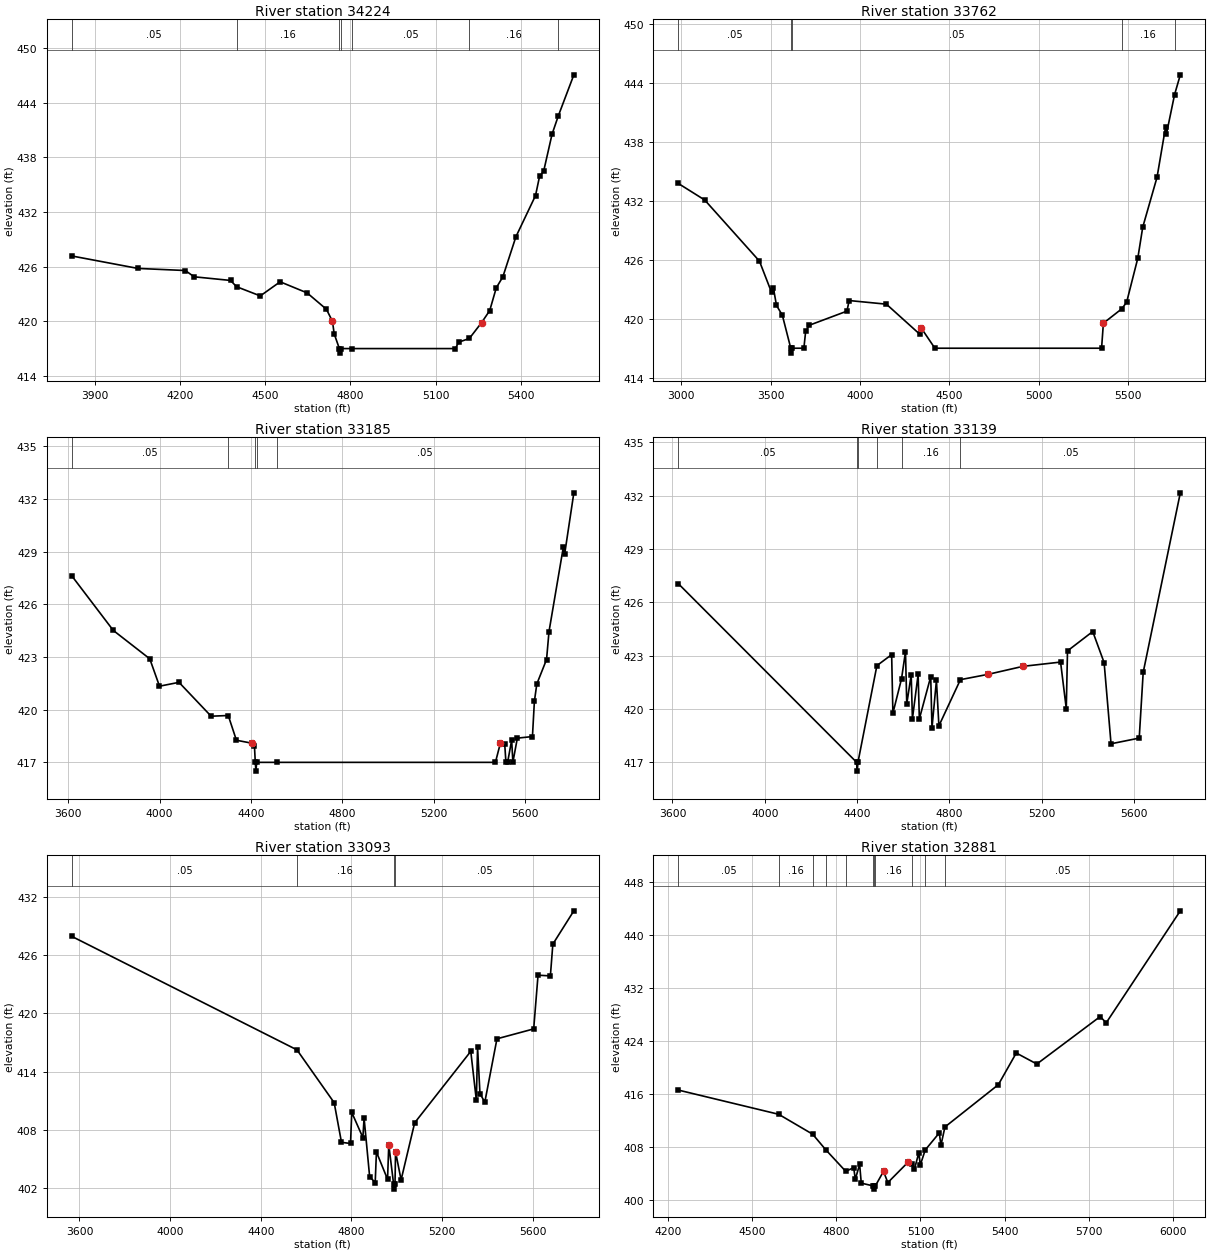
Type RM Length L Ch R = 1 ,34224   ,462,462,462
BEGIN DESCRIPTION:
JACKSON BRANCH 44.0
END DESCRIPTION:
XS GIS Cut Line= 3
      3508699.64     10637760.17      3509699.61     10637160.19
       3509949.6      10636610.2
#Sta/Elev= 30
  3817.3  427.17  4050.5   425.8  4217.7  425.57  4248.8  424.88    4377  424.48
  4398.4  423.79    4482  422.78    4552  424.33  4647.2  423.11  4715.2  421.31
  4736.6  419.98  4742.4  418.63  4760.8  416.99  4763.6  416.49  4766.8  416.99
  4806.7  416.99  5170.2  416.99  5181.2  417.69  5219.1   418.1  5262.5  419.85
    5291  421.17  5314.1  423.67  5337.2  424.87  5383.3  429.28  5452.5  433.81
  5466.8  435.94  5481.1  436.48  5510.7  440.55  5533.1  442.59  5587.6  447.08
#Mann= 7 ,-1 , 0
  3817.3     .05       0  4398.4     .16       0  4760.8    .033       0
  4766.8     .16       0  4806.7     .05       0  5219.1     .16       0
  5533.1     .05       0
Bank Sta=4736.6,5262.5
XS Rating Curve= 0 ,0
Exp/Cntr=0.3,0.1

Type RM Length L Ch R = 1 ,33762   ,577,577,577
BEGIN DESCRIPTION:
JACKSON BRANCH 43.0
END DESCRIPTION:
XS GIS Cut Line= 3
      3510249.61     10639460.15      3510049.61     10637460.19
      3509999.61     10636660.18
#Sta/Elev= 30
  2982.5  433.79  3130.7   432.1  3437.2  425.87  3505.1  422.68  3515.1  423.16
  3532.7  421.35  3565.4  420.36  3612.6  416.99  3615.4  416.49  3618.6  416.99
    3686  416.99    3696   418.7  3716.1  419.33  3927.1  420.77  3939.7  421.85
  4148.2  421.48  4336.7  418.39  4341.7  419.09  4419.6  416.99  5353.1  416.99
  5363.2  419.54  5466.4  421.01  5493.4  421.68    5556  426.17  5583.6  429.33
  5663.7  434.42  5711.3  439.52  5716.3  438.83  5761.8  442.84    5794  444.86
#Mann= 5 ,-1 , 0
  2982.5     .05       0  3612.6    .033       0  3618.6     .05       0
  5466.4     .16       0  5761.8     .05       0
Bank Sta=4341.7,5363.2
XS Rating Curve= 0 ,0
Exp/Cntr=0.3,0.1

Type RM Length L Ch R = 1 ,33185   ,46,46,46
BEGIN DESCRIPTION:
Mapping XS 5d4f3ca6
END DESCRIPTION:
XS GIS Cut Line= 2
      3510975.98     10638900.58      3510210.36      10636838.1
#Sta/Elev= 30
  3614.9  427.62  3796.7  424.51  3956.7  422.89  3999.3  421.33  4084.7  421.55
  4225.5  419.62  4300.6  419.66  4336.3  418.25  4404.7  418.08  4415.3  417.94
    4419  416.99  4421.8  416.49    4425  416.99  4512.9  416.99  5471.3  416.99
  5492.7  418.07    5512  418.03  5517.3  416.99  5524.7  416.99  5542.4  418.26
  5547.7  416.99  5567.3  418.37  5633.5  418.46    5642  420.47  5652.7  421.46
  5695.3  422.85    5706  424.44  5769.3  429.29  5774.6  428.86  5814.9  432.35
#Mann= 5 ,-1 , 0
  3614.9     .05       0  4300.6     .16       0    4419    .033       0
    4425     .16       0  4512.9     .05       0
Bank Sta=4404.7,5492.7
XS Rating Curve= 0 ,0
Exp/Cntr=0.3,0.1

Type RM Length L Ch R = 1 ,33139   ,46,46,46
BEGIN DESCRIPTION:
Mapping XS 8bf41d88
END DESCRIPTION:
XS GIS Cut Line= 2
      3511028.04     10638864.09      3510247.27     10636834.06
#Sta/Elev= 30
    3625  427.05  4397.6  416.99  4400.3  416.49  4403.6  416.99  4485.6  422.43
  4549.5  423.05  4554.9  419.75  4592.3  421.69  4609.5  423.22  4614.9  420.27
  4634.2  421.91  4639.5  419.44  4664.2  421.94  4669.5  419.43  4718.8  421.81
  4724.2  418.92  4743.5   421.6  4754.2  419.04  4847.4  421.64  4967.4  421.94
  5118.4  422.39  5281.3  422.63    5306  420.01  5311.3  423.26  5420.6  424.35
  5469.9   422.6  5499.9  418.03    5622  418.35  5639.2  422.05    5800  432.16
#Mann= 6 ,-1 , 0
    3625     .05       0  4397.6    .033       0  4403.6     .05       0
  4485.6     .05       0  4592.3     .16       0  4847.4     .05       0
Bank Sta=4967.4,5118.4
XS Rating Curve= 0 ,0
Exp/Cntr=0.3,0.1

Type RM Length L Ch R = 1 ,33093   ,212,212,212
BEGIN DESCRIPTION:
JACKSON BRANCH 42.0
END DESCRIPTION:
XS GIS Cut Line= 2
      3511090.56     10638890.18        3510289.      10636823.8
#Sta/Elev= 30
  3565.9  427.93  4560.1  416.24  4724.3   410.8  4756.5  406.72  4796.5   406.6
  4801.9   409.8    4851  407.21  4856.3  409.22  4880.9  403.17  4905.4  402.58
  4910.8  405.73  4959.9  402.91  4965.3  406.47  4986.8   402.4  4989.6   401.9
  4992.8   402.4  4995.2  405.74  5019.7  402.85  5079.6  408.73  5327.3  416.09
  5351.9  411.05  5357.3   416.5  5367.9  411.73  5389.3  410.86  5442.9  417.38
    5605   418.4  5624.2  423.93  5678.7  423.86  5689.6  427.13  5782.3  430.56
#Mann= 4 ,-1 , 0
  3565.9     .05       0  4560.1     .16       0  4986.8     .03       0
  4992.8     .05       0
Bank Sta=4965.3,4995.2
XS Rating Curve= 0 ,0
Exp/Cntr=0.3,0.1

Type RM Length L Ch R = 1 ,32881   ,114,114,114
BEGIN DESCRIPTION:
JACKSON BRANCH 41.0
END DESCRIPTION:
XS GIS Cut Line= 2
      3511144.79     10638084.14      3510207.29      10636558.1
#Sta/Elev= 30
    4236   416.6  4594.3  412.95  4715.5  409.95    4762  407.62  4833.5  404.36
  4861.8  404.91  4867.7  403.18  4883.1  405.41  4888.9  402.58  4930.1  402.18
  4932.8  401.68  4936.1  402.18  4939.6   402.2  4968.3  404.36  4983.6  402.66
  5057.1  405.79  5069.4  405.52  5078.4  404.65  5093.8  407.11  5099.6  405.33
  5117.1  407.58  5167.2  410.14  5173.1  408.29  5187.4  411.04  5377.9  417.41
  5441.8  422.18  5515.2  420.52  5741.3  427.67  5762.6  426.72    6027  443.59
#Mann= 11 ,-1 , 0
    4236     .05       0  4594.3     .16       0  4715.5     .08       0
    4762     .16       0  4833.5     .08       0  4930.1     .07       0
  4936.1     .08       0  4939.6     .16       0  5069.4     .05       0
  5117.1     .16       0  5187.4     .05       0
Bank Sta=4968.3,5057.1
XS Rating Curve= 0 ,0
Exp/Cntr=0.3,0.1

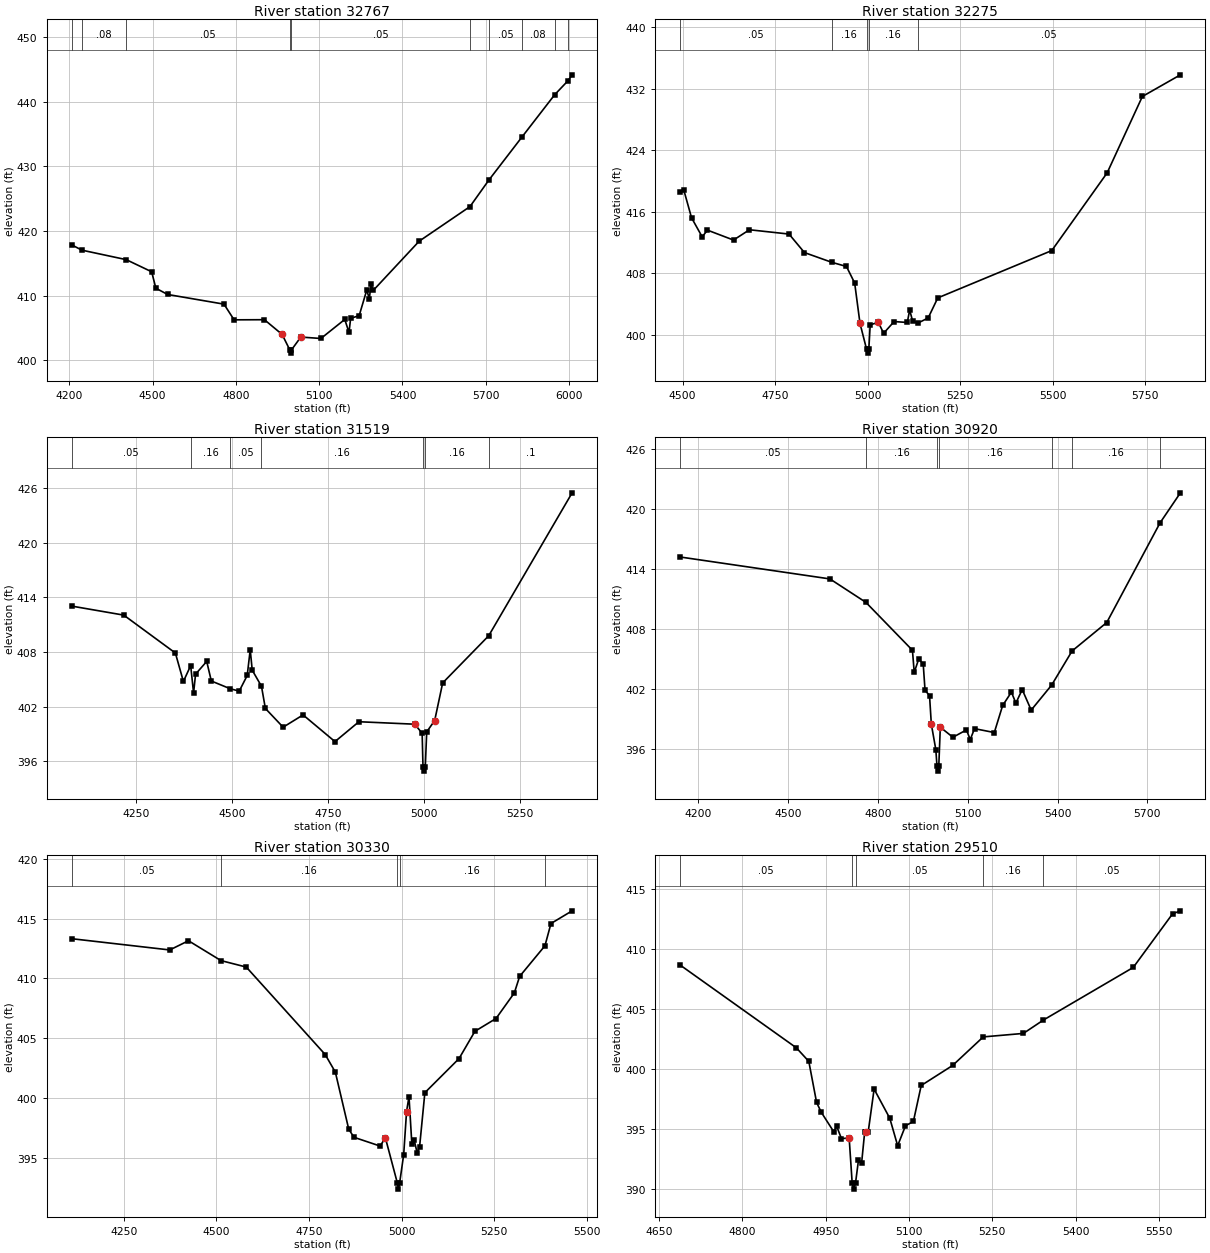
Type RM Length L Ch R = 1 ,32767   ,492,492,492
BEGIN DESCRIPTION:
JACKSON BRANCH 40.0
END DESCRIPTION:
XS GIS Cut Line= 3
      3511269.79     10638047.68      3510900.02     10637469.59
      3510311.48     10636521.67
#Sta/Elev= 30
  4208.8  417.85  4245.4  417.03    4405  415.56  4496.7  413.68  4511.9  411.13
  4554.2  410.16  4757.2  408.66  4793.6  406.23  4902.8  406.25  4966.5  403.97
  4994.2  401.57    4997  401.07  5000.2  401.57  5033.8  403.56  5106.2  403.34
  5192.1  406.29  5207.4  404.28  5213.3  406.46    5244  406.88  5271.2  410.83
  5280.7  409.51  5286.5  411.76  5294.5  410.78  5460.1  418.42    5643  423.78
  5711.2   427.9  5829.6  434.53  5947.9  441.11  5995.6  443.27  6010.8   444.2
#Mann= 10 ,-1 , 0
  4208.8     .05       0  4245.4     .08       0    4405     .05       0
  4994.2     .04       0  5000.2     .05       0    5643     .08       0
  5711.2     .05       0  5829.6     .08       0  5947.9     .05       0
  5995.6     .08       0
Bank Sta=4966.5,5033.8
XS Rating Curve= 0 ,0
Exp/Cntr=0.3,0.1

Type RM Length L Ch R = 1 ,32275   ,756,756,756
BEGIN DESCRIPTION:
JACKSON BRANCH 39.0
END DESCRIPTION:
XS GIS Cut Line= 3
      3511617.89     10637595.75      3511107.45     10637179.07
       3510883.5     10636522.85
#Sta/Elev= 30
  4492.7   418.5  4503.2  418.79    4524   415.2  4552.7  412.72  4567.1  413.59
  4637.4   412.3  4680.5  413.64  4787.4  413.08  4829.1  410.67  4902.5  409.41
  4942.6  408.86  4964.8  406.71  4979.2  401.45    4997  398.08  4999.8  397.58
    5003  398.08  5006.8  401.27  5028.7  401.58  5043.1  400.17  5071.4  401.69
    5107  401.57  5113.4  403.19  5121.3  401.78  5135.6  401.49  5163.4  402.16
  5189.4  404.77  5497.4  410.93  5647.1  421.05  5742.2  430.99    5845  433.81
#Mann= 5 ,-1 , 0
  4492.7     .05       0  4902.5     .16       0    4997     .07       0
    5003     .16       0  5135.6     .05       0
Bank Sta=4979.2,5028.7
XS Rating Curve= 0 ,0
Exp/Cntr=0.3,0.1

Type RM Length L Ch R = 1 ,31519   ,599,599,599
BEGIN DESCRIPTION:
JACKSON BRANCH 38.0
END DESCRIPTION:
XS GIS Cut Line= 3
      3511649.61     10637510.19      3511378.28     10636533.23
      3511099.63     10636460.19
#Sta/Elev= 30
  4083.5  413.04    4219  412.05  4353.3  407.89  4374.1  404.77  4393.1  406.51
  4400.6   403.5  4405.8  405.57  4434.8  406.97  4446.8  404.82    4496  403.97
  4519.4  403.71  4540.2  405.43    4548  408.26  4553.2  406.01  4577.3  404.24
  4587.4  401.81  4633.6  399.75  4685.5   401.1  4768.5  398.17  4830.8  400.35
  4976.1  400.08  4995.3  399.08  4997.5  395.43  5000.3  394.93  5003.5  395.43
  5007.2  399.24  5027.9  400.48  5048.7  404.61  5168.4  409.78  5385.5  425.47
#Mann= 7 ,-1 , 0
  4083.5     .05       0  4393.1     .16       0    4496     .05       0
  4577.3     .16       0  4997.5     .07       0  5003.5     .16       0
  5168.4      .1       0
Bank Sta=4976.1,5027.9
XS Rating Curve= 0 ,0
Exp/Cntr=0.3,0.1

Type RM Length L Ch R = 1 ,30920   ,590,590,590
BEGIN DESCRIPTION:
JACKSON BRANCH 37.0
END DESCRIPTION:
XS GIS Cut Line= 2
      3512228.14     10637526.88      3511301.07     10636136.27
#Sta/Elev= 30
  4138.8  415.21  4639.6  413.02  4759.8  410.68  4915.2   405.9  4921.2  403.69
  4936.2  405.03  4951.2  404.53  4957.3   401.9  4972.3  401.38  4978.3  398.52
  4993.3  395.99  4997.2  394.34  4999.9  393.84  5003.2  394.34  5008.3  398.22
  5050.4  397.22  5095.5  397.95  5108.3  396.99  5122.5  398.08  5188.6  397.69
  5216.5  400.39  5245.7  401.72  5260.7  400.63  5281.8  401.98  5311.8  399.93
  5380.2  402.43  5448.4  405.83  5564.2  408.67  5742.1  418.61  5810.1  421.61
#Mann= 7 ,-1 , 0
  4138.8     .05       0  4759.8     .16       0  4997.2     .07       0
  5003.2     .16       0  5380.2      .1       0  5448.4     .16       0
  5742.1     .05       0
Bank Sta=4978.3,5008.3
XS Rating Curve= 0 ,0
Exp/Cntr=0.3,0.1

Type RM Length L Ch R = 1 ,30330   ,820,820,820
BEGIN DESCRIPTION:
JACKSON BRANCH 35.0
END DESCRIPTION:
XS GIS Cut Line= 2
      3512354.05      10637049.4      3511474.99      10636024.7
#Sta/Elev= 30
  4109.8  413.32  4374.4  412.38  4424.9  413.15  4512.6  411.49  4580.8  410.95
  4793.7  403.64  4821.1  402.17  4857.3  397.39  4871.6  396.72  4941.9  395.99
  4956.1  396.68  4988.5  392.89  4991.3  392.39  4994.5  392.89  5005.5  395.28
  5013.2  398.86  5019.8  400.13  5027.5  396.16    5034  396.46  5041.7  395.44
  5048.3   395.9  5062.6  400.45  5154.8   403.3  5197.6  405.58  5254.6  406.65
    5304  408.79  5318.3  410.17  5386.6  412.73  5402.8  414.59  5459.9  415.65
#Mann= 5 ,-1 , 0
  4109.8     .05       0  4512.6     .16       0  4988.5     .07       0
  4994.5     .16       0  5386.6     .05       0
Bank Sta=4956.1,5013.2
XS Rating Curve= 0 ,0
Exp/Cntr=0.3,0.1

Type RM Length L Ch R = 1 ,29510   ,444,444,444
BEGIN DESCRIPTION:
JACKSON BRANCH 34.0
END DESCRIPTION:
XS GIS Cut Line= 3
      3512399.61     10636160.19      3512099.61     10636010.19
      3511699.61     10635610.19
#Sta/Elev= 30
  4687.5  408.69  4897.1  401.78  4919.5  400.65  4933.5  397.23  4941.9  396.41
  4964.2   394.8  4969.8  395.23  4978.2  394.22  4992.2  394.25  4997.6   390.5
  5000.3     390  5003.6   390.5  5008.9   392.4  5014.5  392.14  5020.1  394.75
  5022.9  394.75  5026.4  394.75  5037.1  398.34  5065.3  395.91  5079.5  393.62
  5093.6  395.28  5107.8  395.64  5121.9  398.64  5178.5  400.31  5233.6  402.69
  5305.8  402.98  5342.1   404.1  5503.7  408.48  5574.5  412.95  5588.6   413.2
#Mann= 5 ,-1 , 0
  4687.5     .05       0  4997.6    .035       0  5003.6     .05       0
  5233.6     .16       0  5342.1     .05       0
Bank Sta=4992.2,5022.9
XS Rating Curve= 0 ,0
Exp/Cntr=0.3,0.1

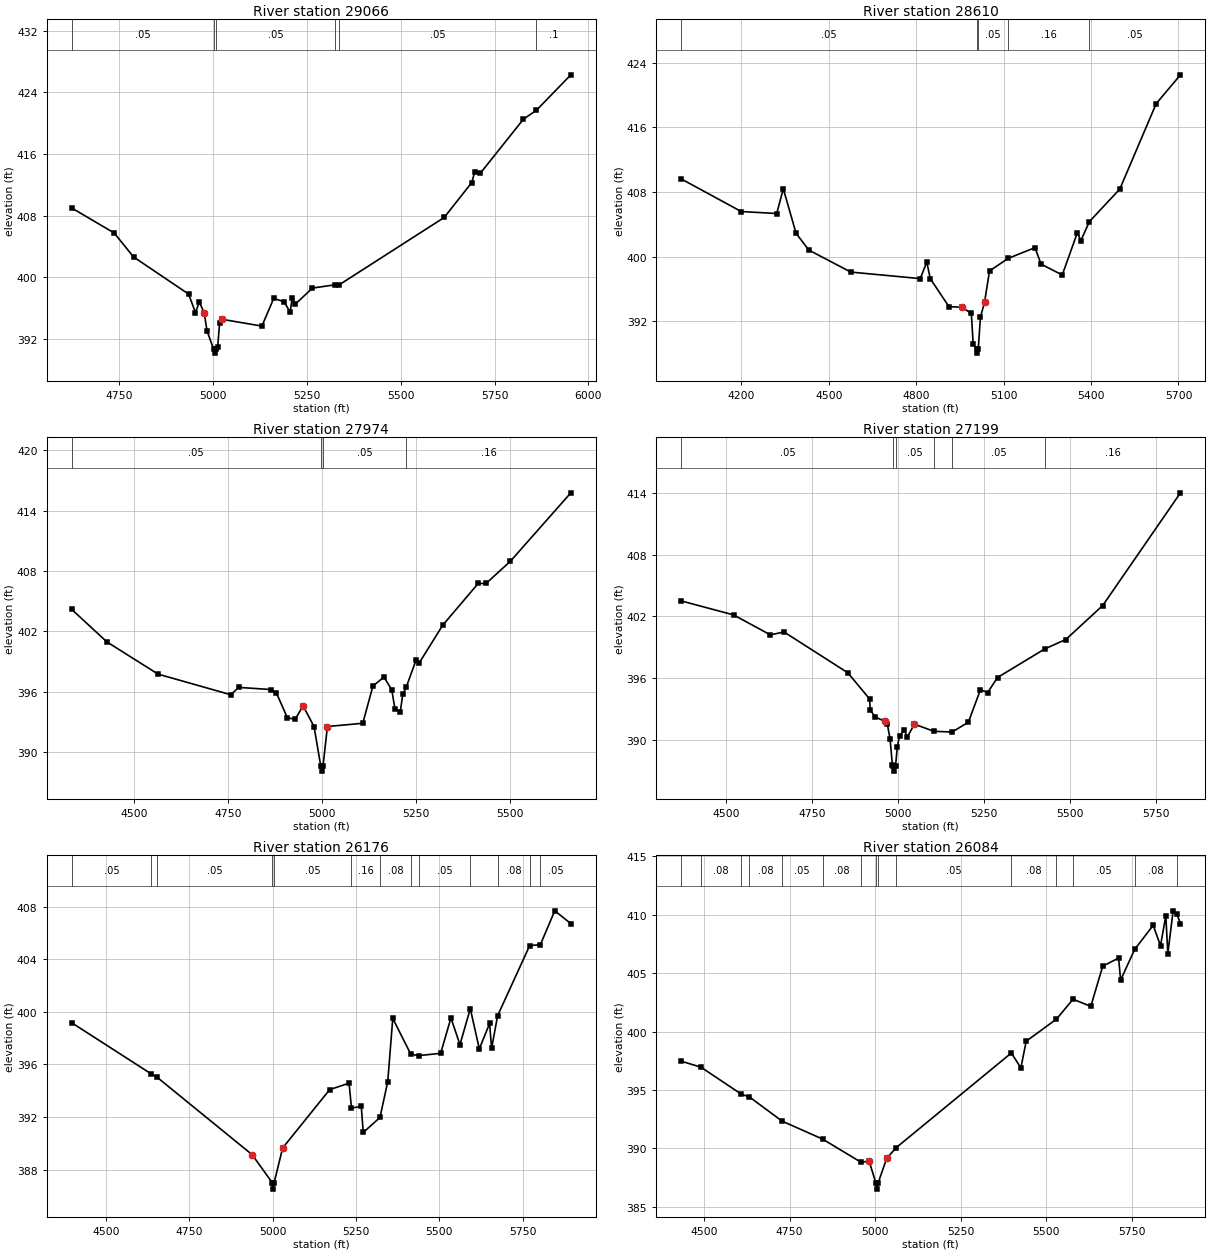
Type RM Length L Ch R = 1 ,29066   ,456,456,456
BEGIN DESCRIPTION:
JACKSON BRANCH 33.0
END DESCRIPTION:
XS GIS Cut Line= 3
      3512499.61     10636110.19      3512399.61     10635710.19
       3511599.6     10635260.19
#Sta/Elev= 30
  4623.2  409.01  4736.6  405.76  4788.1  402.65    4935  397.82  4953.1  395.43
  4963.4  396.78  4976.2  395.43    4984  393.05  5001.6  390.66  5004.3  390.16
  5007.6  390.66  5012.3  390.92  5017.5  394.07  5025.2  394.54  5130.2  393.67
  5161.7  397.26  5189.5  396.83  5205.4  395.47  5211.1  397.33  5219.1  396.51
  5264.7   398.6  5326.1  399.04  5334.6  398.98  5615.9  407.77  5689.5  412.31
  5696.8  413.63  5712.5  413.53  5827.2  420.54  5861.7  421.69  5953.4  426.29
#Mann= 6 ,-1 , 0
  4623.2     .05       0  5001.6    .035       0  5007.6     .05       0
  5326.1     .16       0  5334.6     .05       0  5861.7      .1       0
Bank Sta=4976.2,5025.2
XS Rating Curve= 0 ,0
Exp/Cntr=0.3,0.1

Type RM Length L Ch R = 1 ,28610   ,636,636,636
BEGIN DESCRIPTION:
JACKSON BRANCH 32.0
END DESCRIPTION:
XS GIS Cut Line= 3
      3512849.61      10636260.2      3512449.61     10635360.19
      3511749.62     10635160.19
#Sta/Elev= 30
    3994  409.62  4199.9  405.58  4321.6  405.33  4344.2   408.4    4388  402.88
  4431.7   400.8    4576  398.07  4814.1  397.26  4836.6  399.32  4848.3  397.27
  4912.6  393.78    4957  393.71  4989.3  392.94  4995.8  389.12  5007.1  388.52
  5009.8  388.02  5013.1  388.52  5020.5  392.45  5034.8  394.34  5051.7  398.21
  5115.8  399.77  5207.7   401.1  5228.5  399.06  5301.3  397.71  5353.3  402.97
    5365  401.96  5394.3  404.32  5498.9  408.37  5623.7  418.96  5706.9  422.53
#Mann= 5 ,-1 , 0
    3994     .05       0  5007.1    .035       0  5013.1     .05       0
  5115.8     .16       0  5394.3     .05       0
Bank Sta=4957,5034.8
XS Rating Curve= 0 ,0
Exp/Cntr=0.3,0.1

Type RM Length L Ch R = 1 ,27974   ,775,775,775
BEGIN DESCRIPTION:
JACKSON BRANCH 31.0
END DESCRIPTION:
XS GIS Cut Line= 2
      3513186.02     10635795.83      3512400.38     10634724.03
#Sta/Elev= 30
  4333.3  404.18  4427.1  400.94  4563.5  397.73  4757.1  395.68    4778  396.41
  4863.6   396.2  4878.3  395.87  4907.6  393.39  4928.5  393.24  4949.3  394.58
  4978.6  392.52  4996.5  388.58  4999.2  388.08  5002.5  388.58  5014.2  392.52
  5108.3  392.84  5135.4  396.55  5164.7  397.44  5185.5  396.17    5194  394.26
  5208.2  394.01  5214.8  395.72  5223.9  396.42  5250.3  399.14  5257.8   398.8
  5321.4  402.61  5415.5  406.75  5436.4  406.75  5501.2  408.96  5662.2  415.77
#Mann= 4 ,-1 , 0
  4333.3     .05       0  4996.5    .035       0  5002.5     .05       0
  5223.9     .16       0
Bank Sta=4949.3,5014.2
XS Rating Curve= 0 ,0
Exp/Cntr=0.3,0.1

Type RM Length L Ch R = 1 ,27199   ,1023,1023,1023
BEGIN DESCRIPTION:
JACKSON BRANCH 30.0
END DESCRIPTION:
XS GIS Cut Line= 3
      3513595.15     10635754.04      3513447.59     10635228.87
      3512883.98     10634517.86
#Sta/Elev= 30
  4369.7   403.5  4521.9  402.14  4629.3  400.19  4668.6  400.48  4854.5   396.5
  4917.6  393.96    4920  392.86  4934.4  392.19  4963.2  391.76  4969.6  391.48
  4977.3  390.08  4984.1  387.54  4987.4  387.42  4990.2  386.92  4993.4  387.42
  4998.5  389.29  5004.9  390.35  5019.3  390.92  5027.3  390.22  5048.1   391.5
  5104.6   390.8  5157.7  390.73  5205.2  391.68  5240.4  394.85  5261.3  394.57
  5290.1  396.04    5428  398.83  5488.8  399.74  5596.2  403.05  5822.5  414.03
#Mann= 6 ,-1 , 0
  4369.7     .05       0  4987.4    .035       0  4993.4     .05       0
  5104.6     .16       0  5157.7     .05       0    5428     .16       0
Bank Sta=4963.2,5048.1
XS Rating Curve= 0 ,0
Exp/Cntr=0.3,0.1

Type RM Length L Ch R = 1 ,26176   ,92,92,92
BEGIN DESCRIPTION:
JACKSON BRANCH 29.0
END DESCRIPTION:
XS GIS Cut Line= 4
      3514059.55     10635550.02      3513842.55     10635185.47
       3513729.7     10634942.42      3513309.59     10634253.77
#Sta/Elev= 30
  4396.1  399.17  4635.4  395.27  4651.3  395.05  4938.1  389.13  4998.2  387.01
    5001  386.51  5004.2  387.01  5029.7  389.64    5171  394.08  5229.1  394.57
  5236.4  392.68  5265.8   392.8  5271.7  390.82  5321.9  391.96  5345.2  394.68
  5360.3   399.5  5414.7  396.76  5439.6  396.67  5504.1  396.84    5535  399.53
  5562.1   397.5  5593.1  400.24  5620.2  397.18  5651.1  399.11    5657  397.21
  5675.1   399.7  5771.5  405.04  5803.4   405.1  5846.7  407.68    5895  406.71
#Mann= 13 ,-1 , 0
  4396.1     .05       0  4635.4     .08       0  4651.3     .05       0
  4998.2     .04       0  5004.2     .05       0  5236.4     .16       0
  5321.9     .08       0  5414.7     .16       0  5439.6     .05       0
  5593.1     .16       0  5675.1     .08       0  5771.5     .16       0
  5803.4     .05       0
Bank Sta=4938.1,5029.7
XS Rating Curve= 0 ,0
Exp/Cntr=0.3,0.1

Type RM Length L Ch R = 1 ,26084   ,684,684,684
BEGIN DESCRIPTION:
JACKSON BRANCH 28.0
END DESCRIPTION:
XS GIS Cut Line= 4
      3514133.33     10635497.94      3513903.32     10635129.05
      3513768.77     10634842.59      3513404.46     10634235.41
#Sta/Elev= 30
  4433.4  397.46    4491  396.95  4609.5  394.63  4632.4  394.41    4728  392.34
  4846.5   390.8  4958.4  388.83  4982.8   388.9  5002.6  387.02  5005.3  386.52
  5008.6  387.02  5033.9  389.14  5060.7  390.04  5398.3  398.16  5426.2  396.89
  5441.8  399.17  5530.3  401.06  5578.7  402.76  5630.6  402.15  5665.5  405.59
  5711.9  406.28  5717.8   404.4  5759.1  407.03    5813  409.08  5834.4  407.34
  5849.9   409.9  5855.8  406.67  5871.3  410.32  5881.7  410.07  5892.7  409.23
#Mann= 15 ,-1 , 0
  4433.4     .05       0    4491     .08       0  4609.5     .05       0
  4632.4     .08       0    4728     .05       0  4846.5     .08       0
  4958.4     .16       0  5002.6     .07       0  5008.6     .16       0
  5060.7     .05       0  5398.3     .08       0  5530.3     .16       0
  5578.7     .05       0  5759.1     .08       0  5881.7     .05       0
Bank Sta=4982.8,5033.9
XS Rating Curve= 0 ,0
Exp/Cntr=0.3,0.1

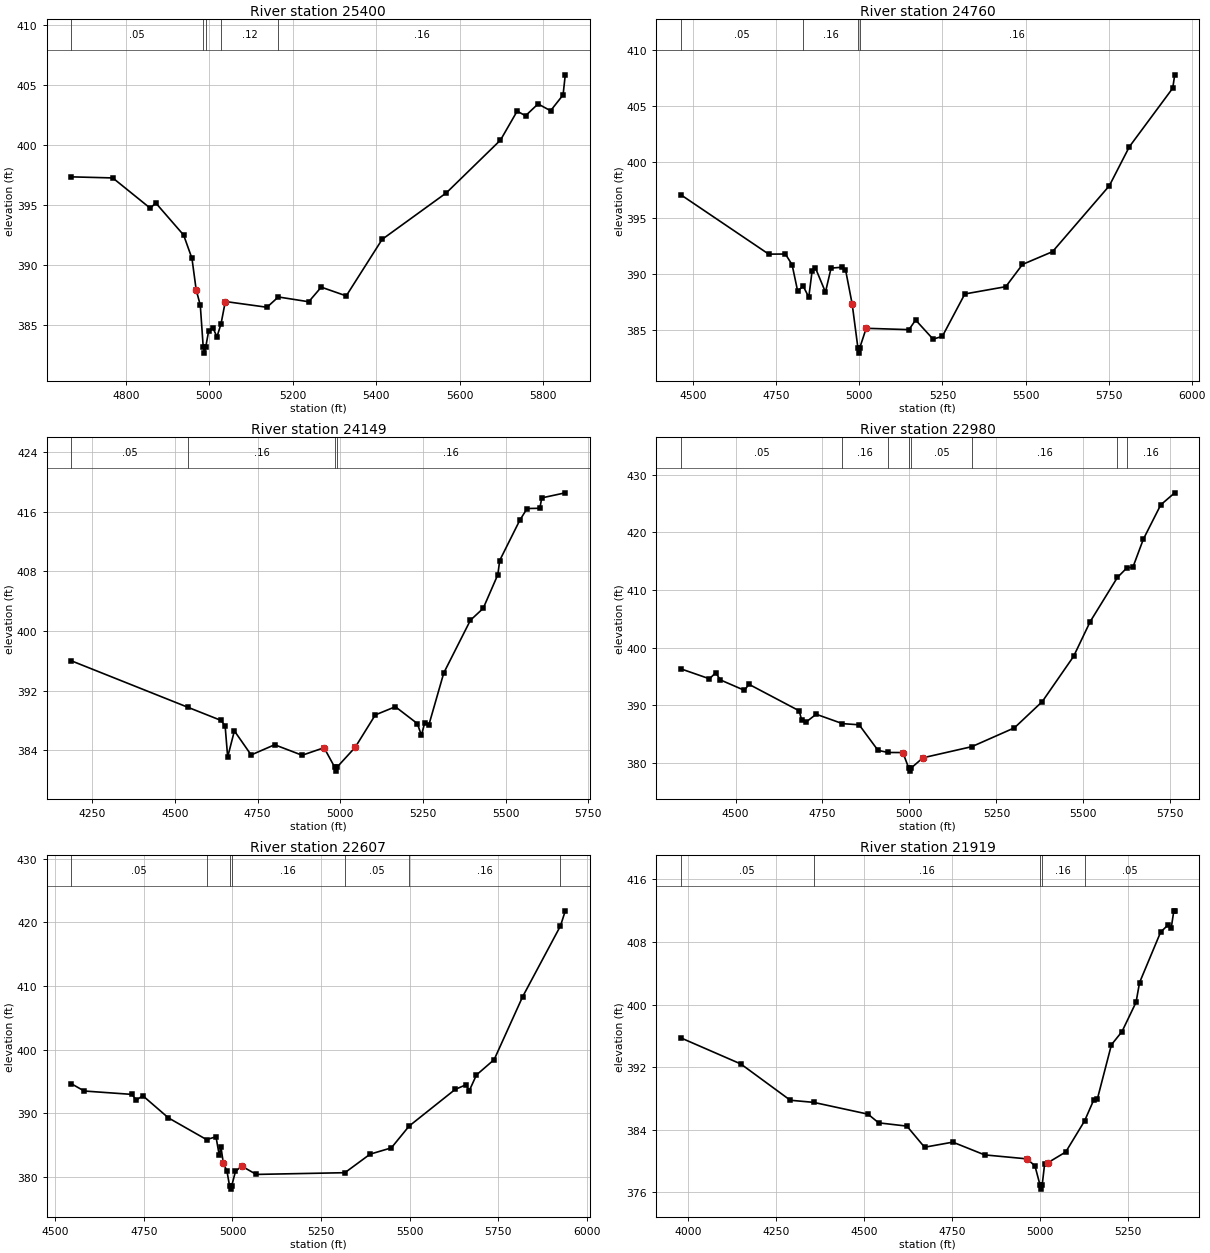
Type RM Length L Ch R = 1 ,25400   ,640,640,640
BEGIN DESCRIPTION:
JACKSON BRANCH 27.0
END DESCRIPTION:
XS GIS Cut Line= 2
      3514298.28     10635619.45      3514276.58     10634434.85
#Sta/Elev= 30
  4668.8  397.36  4768.1  397.27  4858.1  394.74  4871.2  395.18  4938.1   392.5
  4958.1  390.55  4968.1  387.95  4978.1  386.63  4985.1  383.14  4987.9  382.64
  4991.1  383.14  4998.1  384.49  5008.1  384.77  5018.1     384  5027.9   385.1
  5038.1  386.95  5138.1  386.47  5165.2  387.33  5238.2  386.93  5268.2  388.15
  5328.2  387.42  5414.3  392.14  5568.2  396.02  5698.2  400.43  5738.2  402.85
  5758.2  402.46  5788.3  403.45  5818.3  402.88  5848.3   404.2  5853.6  405.88
#Mann= 5 ,-1 , 0
  4668.8     .05       0  4985.1     .03       0  4991.1     .05       0
  5027.9     .12       0  5165.2     .16       0
Bank Sta=4968.1,5038.1
XS Rating Curve= 0 ,0
Exp/Cntr=0.3,0.1

Type RM Length L Ch R = 1 ,24760   ,611,611,611
BEGIN DESCRIPTION:
JACKSON BRANCH 26.0
END DESCRIPTION:
XS GIS Cut Line= 2
      3514749.67     10635823.49      3514602.19     10634344.32
#Sta/Elev= 30
  4462.5  397.09  4727.1  391.78  4777.4  391.79  4797.5  390.83  4814.2  388.48
  4830.9  388.92  4847.7  387.93  4857.7  390.27  4867.8  390.54  4897.9  388.38
  4914.8  390.53  4948.2  390.61  4958.2   390.4  4978.3  387.32  4995.4  383.43
  4998.2  382.93  5001.4  383.43  5020.5  385.15  5149.2  385.03  5169.3  385.89
  5221.8  384.18  5249.7  384.43  5317.4  388.22  5440.6  388.87  5490.9  390.86
  5581.3     392  5752.2  397.89  5812.5  401.38  5943.1  406.62    5949  407.81
#Mann= 4 ,-1 , 0
  4462.5     .05       0  4830.9     .16       0  4995.4     .07       0
  5001.4     .16       0
Bank Sta=4978.3,5020.5
XS Rating Curve= 0 ,0
Exp/Cntr=0.3,0.1

Type RM Length L Ch R = 1 ,24149   ,1169,1169,1169
BEGIN DESCRIPTION:
JACKSON BRANCH 25.0
END DESCRIPTION:
XS GIS Cut Line= 3
      3514884.22     10635775.75      3515001.41     10635111.69
      3515378.34     10634383.82
#Sta/Elev= 30
  4186.8  396.01  4540.8  389.75  4639.2  388.02  4651.9  387.29  4659.6   383.1
  4679.9  386.61  4730.6  383.38  4801.7  384.75  4884.8  383.34  4951.2  384.35
  4983.7  381.71  4986.4  381.21  4989.7  381.71  5045.3   384.4  5106.1  388.75
  5166.9  389.85  5233.3  387.59  5245.7  386.01  5255.4  387.67  5268.2  387.41
  5313.3  394.39  5393.9  401.46  5432.5  403.05  5476.8  407.57  5482.4  409.47
  5543.2  414.87  5565.3  416.44  5603.9  416.48  5609.6  417.87  5680.8  418.55
#Mann= 4 ,-1 , 0
  4186.8     .05       0  4540.8     .16       0  4983.7     .07       0
  4989.7     .16       0
Bank Sta=4951.2,5045.3
XS Rating Curve= 0 ,0
Exp/Cntr=0.3,0.1

Type RM Length L Ch R = 1 ,22980   ,373,373,373
BEGIN DESCRIPTION:
JACKSON BRANCH 24.0
END DESCRIPTION:
XS GIS Cut Line= 3
       3515249.6     10635910.22      3515399.61     10635310.19
      3515449.61     10634510.15
#Sta/Elev= 30
  4342.6  396.34  4425.1  394.61  4443.1  395.67    4456  394.43  4525.6  392.61
  4538.5  393.66  4682.8  389.07  4690.5  387.41  4703.4  387.14  4731.8  388.47
  4807.5  386.84  4855.4  386.64  4909.6  382.21  4938.9  381.84  4981.1  381.83
  4998.2  379.11  5000.9  378.61  5004.2  379.11  5038.8  380.92  5179.4  382.85
  5301.8  386.11  5381.9  390.66  5472.1  398.51  5519.7  404.52  5597.9  412.17
  5625.9  413.88  5642.4  413.93  5672.5   418.8  5722.6  424.76  5762.7  426.84
#Mann= 8 ,-1 , 0
  4342.6     .05       0  4807.5     .16       0  4938.9     .05       0
  4998.2     .03       0  5004.2     .05       0  5179.4     .16       0
  5597.9     .05       0  5625.9     .16       0
Bank Sta=4981.1,5038.8
XS Rating Curve= 0 ,0
Exp/Cntr=0.3,0.1

Type RM Length L Ch R = 1 ,22607   ,688,688,688
BEGIN DESCRIPTION:
JACKSON BRANCH 23.0
END DESCRIPTION:
XS GIS Cut Line= 3
       3515409.4     10635975.37      3515548.28     10635437.21
      3515569.98     10634599.58
#Sta/Elev= 30
  4545.4  394.66  4581.7  393.52    4716  392.99  4728.9   392.1    4747  392.78
  4819.3   389.3  4926.9  385.89  4953.5  386.33  4962.6  383.46  4967.7  384.65
  4974.2   382.2  4984.5  380.93  4991.8  378.61  4994.6  378.11  4997.8  378.61
  5008.4  380.88  5025.8  381.73  5067.1  380.42  5317.2  380.69  5388.3   383.6
  5448.3  384.59  5498.6  388.02  5628.4  393.77  5658.4  394.49  5668.4  393.59
  5688.4  396.04  5738.4  398.45  5818.4  408.29  5925.6  419.46  5939.1  421.82
#Mann= 7 ,-1 , 0
  4545.4     .05       0  4926.9     .16       0  4991.8     .07       0
  4997.8     .16       0  5317.2     .05       0  5498.6     .16       0
  5925.6     .05       0
Bank Sta=4974.2,5025.8
XS Rating Curve= 0 ,0
Exp/Cntr=0.3,0.1

Type RM Length L Ch R = 1 ,21919   ,422,422,422
BEGIN DESCRIPTION:
JACKSON BRANCH 22.0
END DESCRIPTION:
XS GIS Cut Line= 3
      3515749.61     10636160.16      3515849.61     10635160.19
      3515849.61     10634760.15
#Sta/Elev= 30
  3978.9  395.74  4149.7   392.4  4290.4  387.76  4356.6  387.49  4511.5  385.98
  4541.7  384.87  4622.1  384.45  4672.3  381.75  4752.7   382.4  4843.2  380.77
  4963.8  380.26  4986.4  379.36  5000.9  376.89  5003.6  376.39  5006.9  376.89
  5013.9  379.63  5023.9  379.79  5073.9  381.14  5127.4   385.1  5153.9  387.83
  5163.9  387.92  5203.9  394.86  5233.9  396.54  5273.9  400.29  5283.9  402.81
  5343.9  409.27  5363.9  410.14  5373.9  409.77  5381.4  411.99  5383.9  411.99
#Mann= 5 ,-1 , 0
  3978.9     .05       0  4356.6     .16       0  5000.9     .07       0
  5006.9     .16       0  5127.4     .05       0
Bank Sta=4963.8,5023.9
XS Rating Curve= 0 ,0
Exp/Cntr=0.3,0.1