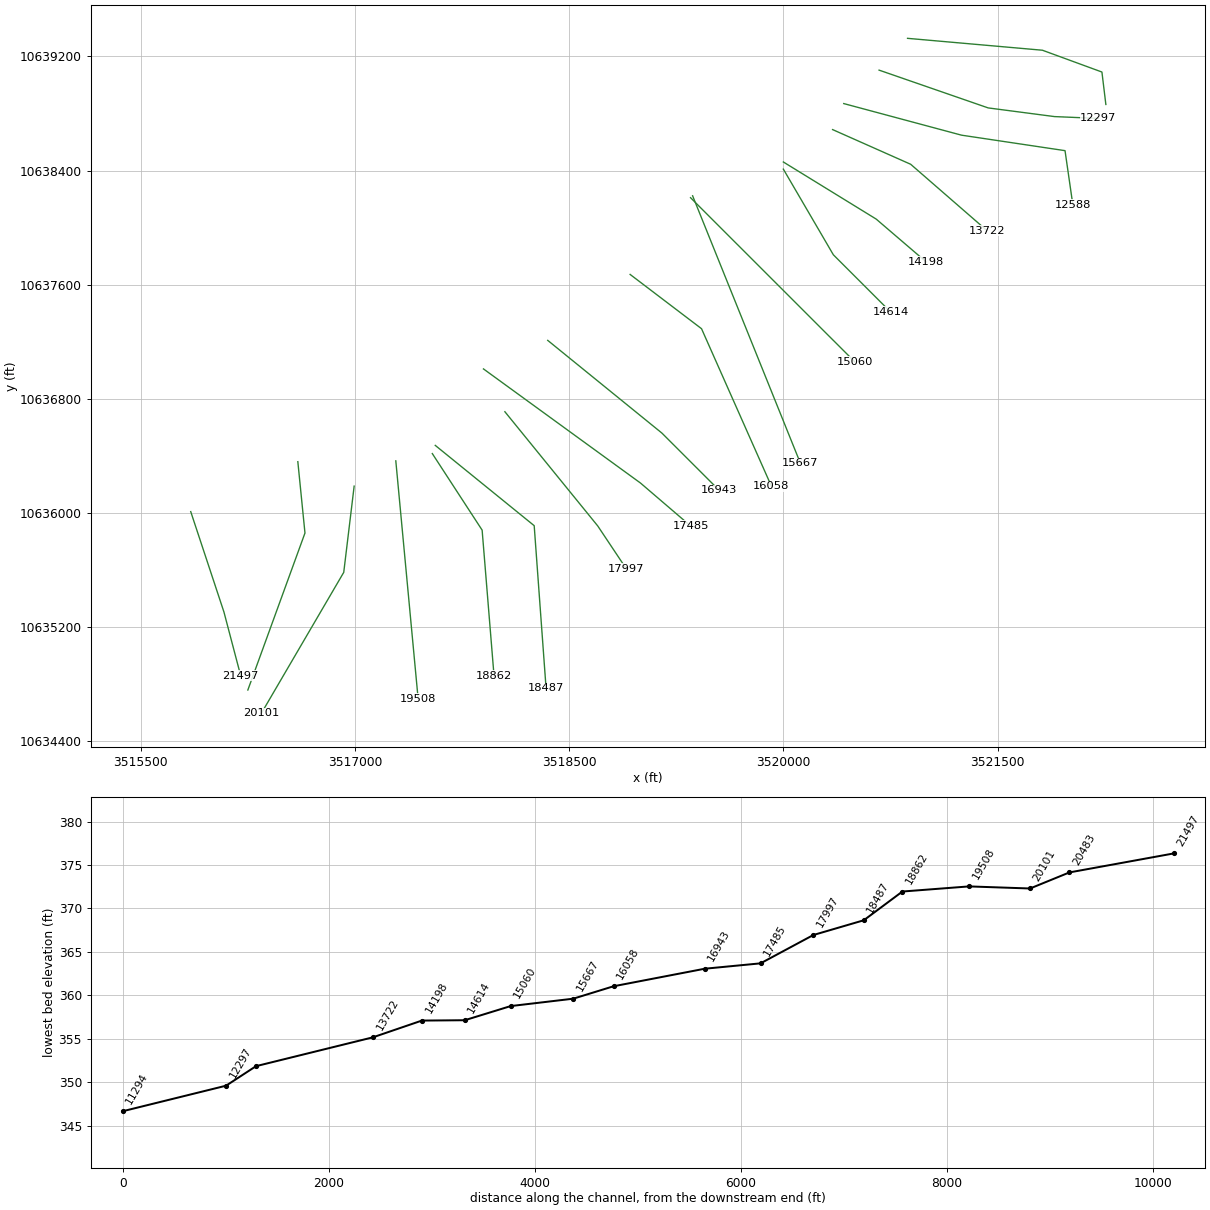
HEC-RAS study JACKSON BRANCH.prj: JACKSON BRANCH Base Level Engineering

--- JACKSON BRANCH.g01 (geometry) --- (continued)

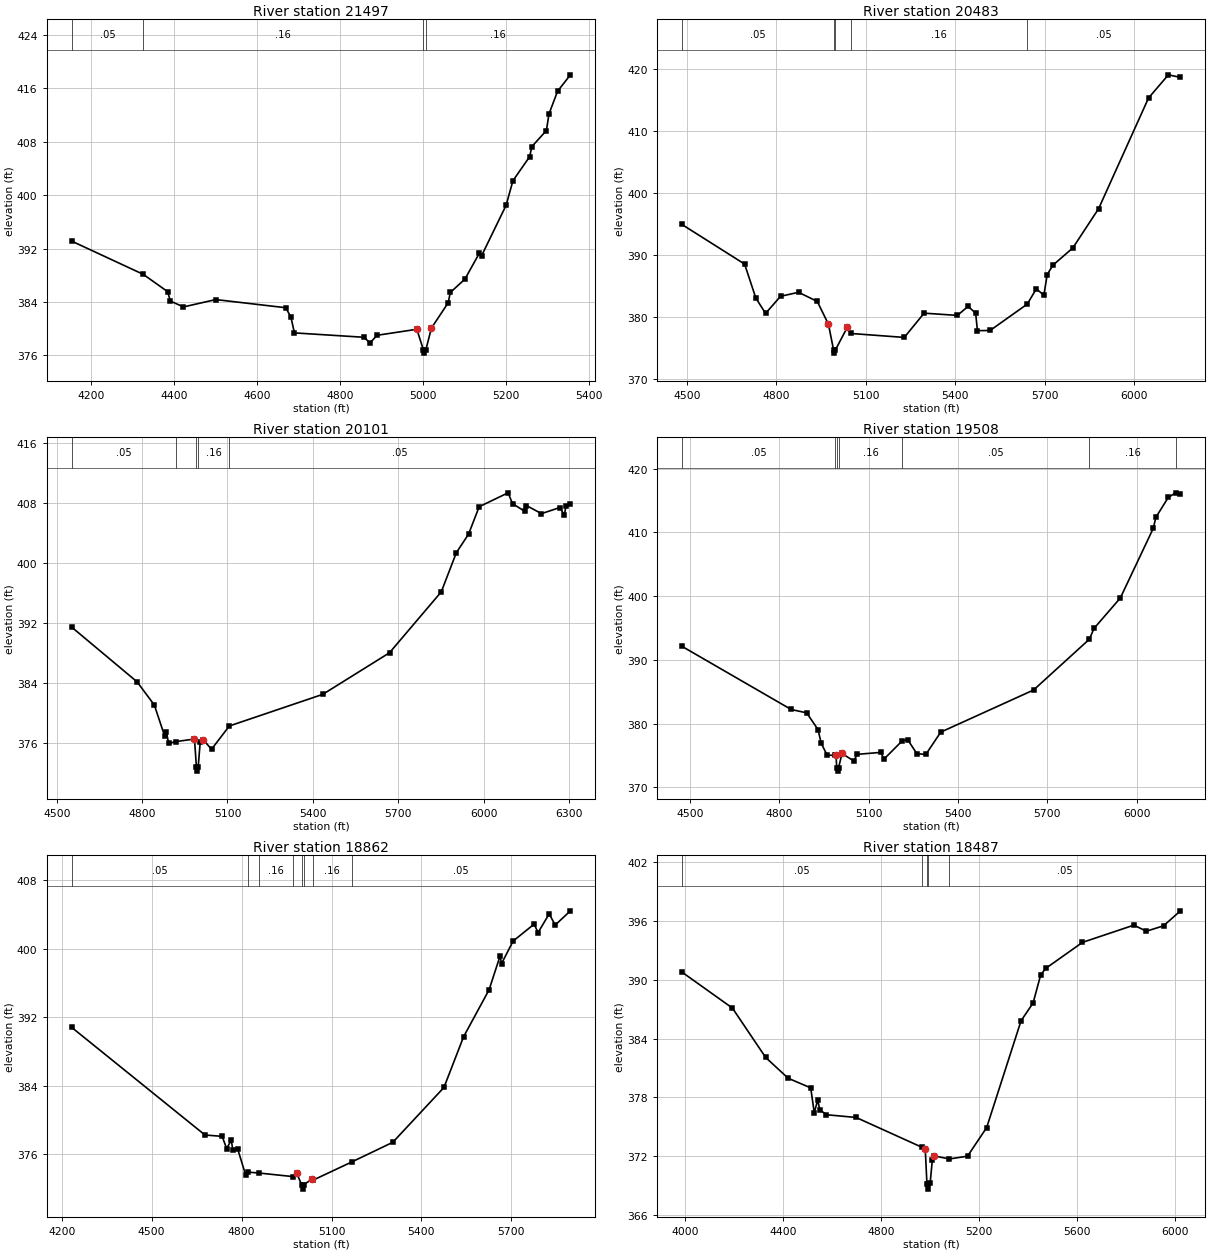
Type RM Length L Ch R = 1 ,21497   ,1014,1014,1014
BEGIN DESCRIPTION:
JACKSON BRANCH 21.0
END DESCRIPTION:
XS GIS Cut Line= 3
       3515849.6      10636010.2      3516082.14       10635307.
       3516199.6     10634860.23
#Sta/Elev= 30
  4153.1  393.12  4325.8  388.14  4384.8  385.54  4391.1  384.14  4422.8  383.26
  4500.7  384.36  4669.2  383.14  4681.8  381.76  4690.3  379.37  4858.8  378.71
  4872.2  377.84  4889.4  379.01  4985.4  379.91  5001.2  376.84  5003.9  376.34
  5007.2  376.84  5020.6  380.09  5060.9  383.87  5066.2  385.43  5101.3  387.42
  5136.4  391.33  5141.6  390.93  5200.7  398.49  5217.1  402.16  5257.5  405.77
  5262.7  407.27  5297.8  409.68    5304  412.15  5324.7  415.56  5355.7  418.02
#Mann= 4 ,-1 , 0
  4153.1     .05       0  4325.8     .16       0  5001.2     .07       0
  5007.2     .16       0
Bank Sta=4985.4,5020.6
XS Rating Curve= 0 ,0
Exp/Cntr=0.3,0.1

Type RM Length L Ch R = 1 ,20483   ,382,382,382
BEGIN DESCRIPTION:
JACKSON BRANCH 20.0
END DESCRIPTION:
XS GIS Cut Line= 3
      3516599.61     10636360.19      3516649.61     10635860.19
       3516249.6     10634760.16
#Sta/Elev= 30
  4482.9  394.91    4694   388.5  4731.6  383.03  4764.3  380.55  4814.6  383.31
  4874.9  383.95  4937.7  382.48  4975.3  378.79  4992.4  374.65  4995.1  374.15
  4998.4  374.65  5038.6  378.33  5049.6  377.32  5229.5  376.68    5296  380.59
  5407.7  380.23  5443.6  381.69  5468.9  380.59  5474.9  377.77  5517.4   377.8
    5642  382.05  5672.4  384.51  5697.7  383.49    5709  386.82  5728.2  388.33
  5794.8   391.1  5881.2  397.42  6048.8  415.27  6115.3     419  6155.9  418.59
#Mann= 5 ,-1 , 0
  4482.9     .05       0  4992.4     .03       0  4998.4     .05       0
  5049.6     .16       0    5642     .05       0
Bank Sta=4975.3,5038.6
XS Rating Curve= 0 ,0
Exp/Cntr=0.3,0.1

Type RM Length L Ch R = 1 ,20101   ,593,593,593
BEGIN DESCRIPTION:
JACKSON BRANCH 19.0
END DESCRIPTION:
XS GIS Cut Line= 3
      3516994.06     10636188.84      3516921.14     10635584.66
      3516343.85      10634596.5
#Sta/Elev= 30
  4552.2  391.48  4782.5  384.18  4842.9   381.1  4879.8  376.91  4884.9  377.55
  4893.3  375.99  4919.8  376.24    4984  376.57    4991   372.8  4993.8   372.3
    4997   372.8  5004.1  376.16  5014.2  376.51  5043.9  375.21  5106.5  378.31
  5434.8  382.52  5669.5  388.06  5851.4  396.17  5904.3  401.38  5947.3  403.85
  5984.5   407.5  6086.1  409.35  6101.8  407.91  6144.8  406.89  6150.6  407.66
  6203.5  406.58    6268  407.39  6283.7  406.38  6289.5  407.55  6305.2  407.84
#Mann= 5 ,-1 , 0
  4552.2     .05       0  4919.8     .16       0    4991     .07       0
    4997     .16       0  5106.5     .05       0
Bank Sta=4984,5014.2
XS Rating Curve= 0 ,0
Exp/Cntr=0.3,0.1

Type RM Length L Ch R = 1 ,19508   ,646,646,646
BEGIN DESCRIPTION:
JACKSON BRANCH 18.0
END DESCRIPTION:
XS GIS Cut Line= 2
      3517285.72     10636365.96      3517441.97     10634699.27
#Sta/Elev= 30
  4472.5  392.14  4839.9  382.21  4892.1  381.68  4930.3  379.04  4940.3  376.98
  4960.4  375.05  4988.2     375  4990.5  375.09  4992.9  373.04  4995.7  372.54
  4998.9  373.04  5010.6  375.31  5050.8  374.11  5060.8  375.17  5141.2  375.48
  5151.2  374.41  5213.5  377.33  5231.6  377.43  5261.7  375.28  5291.9  375.16
  5342.1  378.66  5653.4  385.26  5840.8  393.23  5856.3  394.92  5944.7   399.7
  6055.2  410.62  6063.9  412.34  6105.4  415.46    6130  416.19  6146.5  416.03
#Mann= 7 ,-1 , 0
  4472.5     .05       0  4988.2     .16       0  4992.9     .07       0
  4998.9     .16       0  5213.5     .05       0  5840.8     .16       0
    6130     .05       0
Bank Sta=4990.5,5010.6
XS Rating Curve= 0 ,0
Exp/Cntr=0.3,0.1

Type RM Length L Ch R = 1 ,18862   ,375,375,375
BEGIN DESCRIPTION:
JACKSON BRANCH 17.0
END DESCRIPTION:
XS GIS Cut Line= 3
      3517541.29     10636416.95      3517890.24      10635880.5
      3517973.57     10634859.65
#Sta/Elev= 30
  4232.9  390.84  4677.8  378.27  4735.1  378.11  4750.2  376.69  4765.4  377.66
  4771.3  376.48  4786.5  376.69  4813.6   373.6    4823  373.93  4858.3  373.83
    4972  373.41  4983.5  373.83  5000.6  372.45  5003.4  371.95  5006.6  372.45
  5033.7  373.09  5037.9  372.99  5166.9  375.11  5304.6  377.42  5475.2  383.82
  5540.7  389.74  5625.7  395.22  5662.4  399.16  5667.4  398.28  5705.9  400.91
  5776.2  402.89  5789.1   401.9  5826.3  404.08  5846.4  402.78  5897.1  404.44
#Mann= 8 ,-1 , 0
  4232.9     .05       0    4823     .12       0  4858.3     .16       0
    4972     .12       0  5000.6     .07       0  5006.6     .12       0
  5037.9     .16       0  5166.9     .05       0
Bank Sta=4983.5,5033.7
XS Rating Curve= 0 ,0
Exp/Cntr=0.3,0.1

Type RM Length L Ch R = 1 ,18487   ,490,490,490
BEGIN DESCRIPTION:
JACKSON BRANCH 16.0
END DESCRIPTION:
XS GIS Cut Line= 3
      3517562.09     10636474.27      3518254.82     10635911.75
      3518338.15     10634771.15
#Sta/Elev= 30
  3985.3   390.8  4192.4  387.11  4328.2  382.07  4420.1  379.95    4512  378.97
  4526.4  376.45  4540.8  377.73  4548.7  376.75    4576  376.23  4697.4  375.95
    4966  372.91  4979.5  372.75  4986.5  369.14  4989.3  368.64  4992.5  369.14
  4999.5  369.25  5008.3  371.58  5013.3  372.04  5078.2  371.72  5152.1     372
  5230.2  374.92  5370.5  385.81  5419.7  387.63  5450.7  390.49  5470.8  391.15
  5621.2  393.81  5831.1  395.57  5881.9  394.95  5952.1   395.5  6021.3  397.03
#Mann= 5 ,-1 , 0
  3985.3     .05       0    4966     .16       0  4986.5     .07       0
  4992.5     .16       0  5078.2     .05       0
Bank Sta=4979.5,5013.3
XS Rating Curve= 0 ,0
Exp/Cntr=0.3,0.1

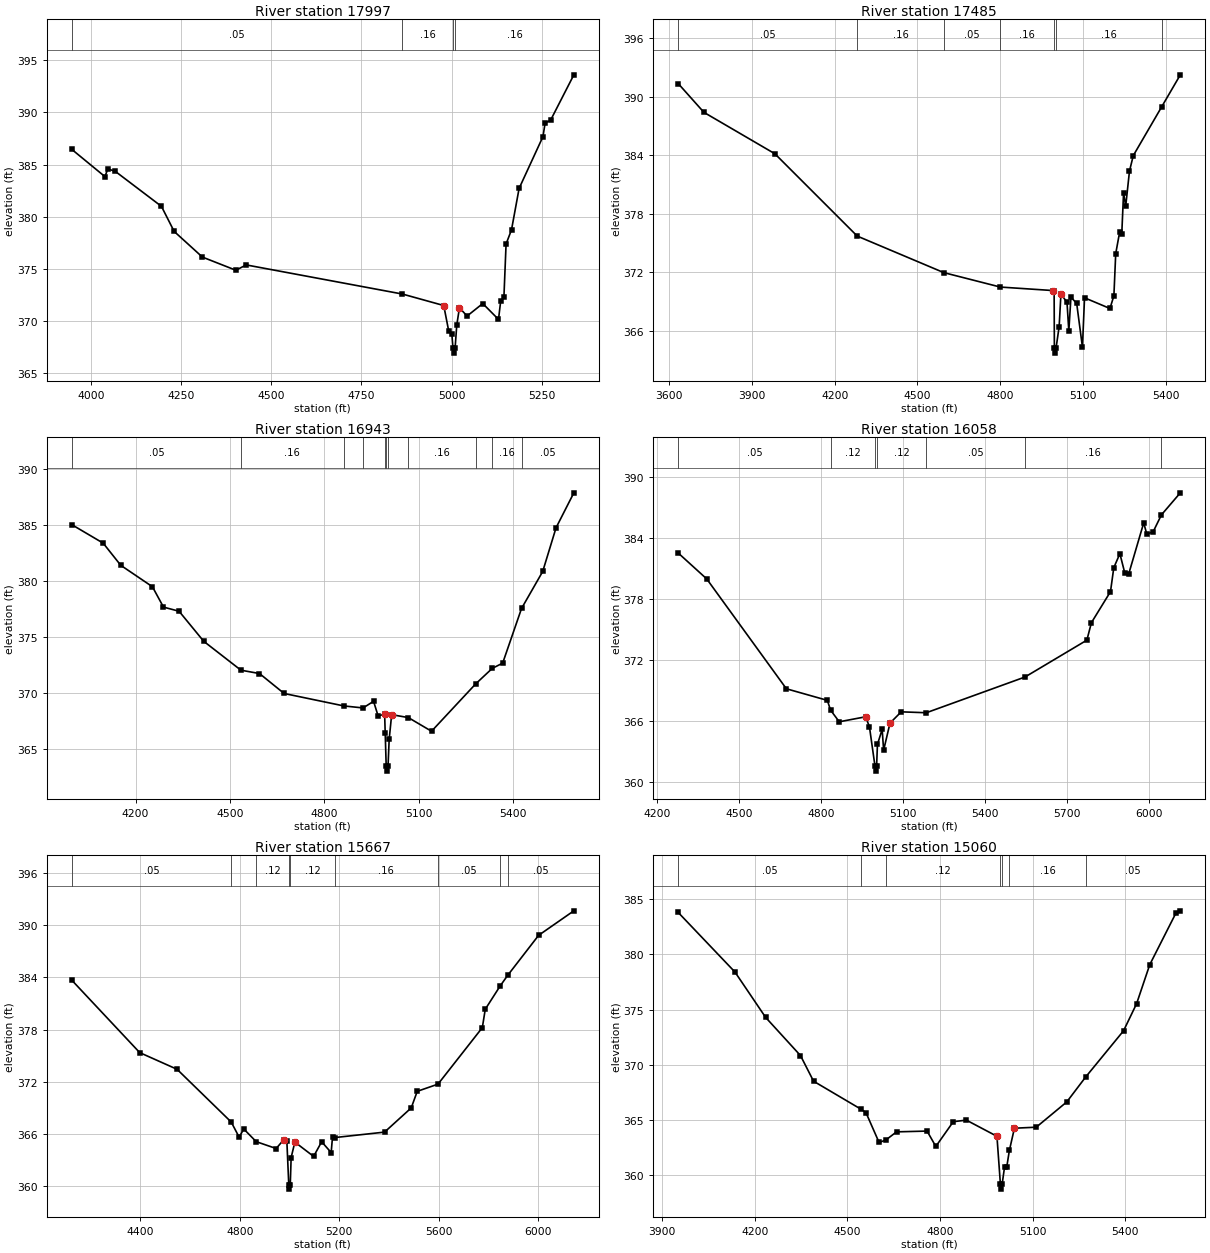
Type RM Length L Ch R = 1 ,17997   ,512,512,512
BEGIN DESCRIPTION:
JACKSON BRANCH 15.0
END DESCRIPTION:
XS GIS Cut Line= 3
      3518049.61     10636710.19      3518699.61     10635910.19
      3518899.59     10635610.22
#Sta/Elev= 30
  3947.2  386.46  4039.1  383.85  4047.1  384.59  4067.9  384.35  4195.7     381
  4230.9   378.6  4309.2  376.14  4401.9  374.88  4430.6  375.39  4863.4   372.6
    4978   371.5  4991.5   369.1  5000.5  368.73  5003.5  367.44  5006.3  366.94
  5009.5  367.44    5014  369.61  5021.5  371.29  5042.6  370.49  5086.1  371.69
  5129.7  370.17  5135.7   371.9  5144.7  372.29  5150.7  377.39  5165.8  378.76
  5186.8  382.72  5252.9  387.68  5258.9  388.99  5273.9  389.24  5338.5   393.6
#Mann= 4 ,-1 , 0
  3947.2     .05       0  4863.4     .16       0  5003.5     .07       0
  5009.5     .16       0
Bank Sta=4978,5021.5
XS Rating Curve= 0 ,0
Exp/Cntr=0.3,0.1

Type RM Length L Ch R = 1 ,17485   ,542,542,542
BEGIN DESCRIPTION:
JACKSON BRANCH 14.0
END DESCRIPTION:
XS GIS Cut Line= 3
      3517899.61     10637010.19      3518999.61     10636210.19
      3519349.59     10635910.21
#Sta/Elev= 30
  3632.4  391.34  3725.5  388.39  3982.9  384.14  4281.7  375.69  4595.8  371.94
  4800.7  370.46  4992.5   370.1  4995.8   370.1  4996.7  364.18  4999.4  363.68
  5002.7  364.18    5014   366.4  5020.5  369.75  5042.5  368.89  5049.1  365.95
  5056.8  369.42  5077.6  368.79  5098.5   364.3  5106.1  369.36  5198.3  368.26
  5212.6  369.57  5219.2  373.89  5233.5  376.11  5241.1  375.87  5247.7  380.15
  5255.4  378.75  5269.1  382.36  5282.9  383.95  5386.4  388.98  5453.5  392.24
#Mann= 7 ,-1 , 0
  3632.4     .05       0  4281.7     .16       0  4595.8     .05       0
  4800.7     .16       0  4996.7     .07       0  5002.7     .16       0
  5386.4     .05       0
Bank Sta=4992.5,5020.5
XS Rating Curve= 0 ,0
Exp/Cntr=0.3,0.1

Type RM Length L Ch R = 1 ,16943   ,885,885,885
BEGIN DESCRIPTION:
JACKSON BRANCH 13.0
END DESCRIPTION:
XS GIS Cut Line= 3
      3518349.64     10637210.16      3519149.61     10636560.19
       3519549.6      10636160.2
#Sta/Elev= 30
  3997.3  385.06  4097.1  383.41  4153.1  381.43  4253.7  379.52  4288.9   377.7
  4338.5  377.33  4416.8  374.65  4535.1  372.07  4594.2  371.77  4672.5  369.99
  4862.2  368.88  4923.5   368.7  4956.9  369.29  4971.3  367.99  4992.1  368.14
  4993.9  366.46    4997  363.56  4999.8  363.06    5003  363.56  5006.5  365.89
  5014.4   368.1  5067.4  367.84  5141.2  366.62  5281.7  370.85  5334.2  372.23
  5367.4   372.7  5427.4  377.58  5494.7  380.88  5537.1  384.78  5593.7   387.9
#Mann= 11 ,-1 , 0
  3997.3     .05       0  4535.1     .16       0  4862.2     .05       0
  4923.5     .16       0  4993.9     .05       0    4997     .03       0
    5003     .05       0  5067.4     .16       0  5281.7     .05       0
  5334.2     .16       0  5427.4     .05       0
Bank Sta=4992.1,5014.4
XS Rating Curve= 0 ,0
Exp/Cntr=0.3,0.1

Type RM Length L Ch R = 1 ,16058   ,391,391,391
BEGIN DESCRIPTION:
JACKSON BRANCH 11.0
END DESCRIPTION:
XS GIS Cut Line= 3
      3518926.68     10637672.18       3519426.7     10637291.96
      3519916.28     10636187.79
#Sta/Elev= 30
  4278.6  382.52  4382.8  379.97  4674.1  369.15  4823.8  368.01  4835.6  367.05
  4867.4   365.9  4963.4  366.39  4977.7  365.43    4998  361.54  5000.7  361.04
    5004  361.54  5007.1  363.67  5024.3  365.15  5029.7   363.1    5053  365.77
  5094.1  366.88  5185.7  366.79  5546.7  370.31  5772.9  373.94  5789.5  375.66
  5859.3  378.72  5871.3  381.07  5893.6  382.46  5911.4  380.57    5926  380.47
  5980.7  385.49  5992.1  384.38  6015.4  384.62  6045.5  386.28  6114.6  388.45
#Mann= 7 ,-1 , 0
  4278.6     .05       0  4835.6     .12       0    4998     .07       0
    5004     .12       0  5185.7     .05       0  5546.7     .16       0
  6045.5     .05       0
Bank Sta=4963.4,5053
XS Rating Curve= 0 ,0
Exp/Cntr=0.3,0.1

Type RM Length L Ch R = 1 ,15667   ,607,607,607
BEGIN DESCRIPTION:
JACKSON BRANCH 10.0
END DESCRIPTION:
XS GIS Cut Line= 2
      3519364.19     10638223.39      3520119.41     10636348.37
#Sta/Elev= 30
  4123.3  383.69  4396.9  375.34  4547.2  373.42  4765.3  367.34  4797.1   365.6
  4815.8  366.54  4865.9  365.08  4946.1  364.29    4977  365.31  4989.2  365.17
    4997  360.11  4999.7  359.61    5003  360.11  5006.5  363.25  5021.5  365.03
    5097  363.38  5129.4  365.07  5167.7  363.82  5173.1  365.65  5181.5  365.55
  5382.6  366.18    5490  368.97  5514.2  370.88  5597.8  371.71  5776.2  378.22
  5788.1  380.34    5848  383.02  5878.7  384.26    6003  388.86  6144.7  391.68
#Mann= 9 ,-1 , 0
  4123.3     .05       0  4765.3     .16       0  4865.9     .12       0
    4997     .07       0    5003     .12       0  5181.5     .16       0
  5597.8     .05       0    5848     .16       0  5878.7     .05       0
Bank Sta=4977,5021.5
XS Rating Curve= 0 ,0
Exp/Cntr=0.3,0.1

Type RM Length L Ch R = 1 ,15060   ,446,446,446
BEGIN DESCRIPTION:
JACKSON BRANCH 9.0
END DESCRIPTION:
XS GIS Cut Line= 3
       3519349.6      10638210.2      3520099.61     10637460.19
      3520499.64     10637060.16
#Sta/Elev= 30
  3952.3  383.78  4136.2  378.39  4235.2   374.3  4348.3  370.84  4390.7  368.52
  4543.6     366  4560.4  365.68  4602.9  362.98  4624.7   363.2  4659.4  363.94
  4758.4  364.01  4786.7  362.62  4843.3  364.86  4885.7     365  4984.7  363.54
  4995.8  359.26  4998.6  358.76  5001.8  359.26  5009.4  360.77  5016.5  360.77
    5025  362.26  5041.3  364.27    5112  364.36    5211  366.65  5272.1   368.9
  5394.8  373.08  5437.2  375.54  5479.7  379.06  5564.5  383.73  5578.7  383.93
#Mann= 7 ,-1 , 0
  3952.3     .05       0  4543.6     .16       0  4624.7     .12       0
  4995.8     .07       0  5001.8     .12       0    5025     .16       0
  5272.1     .05       0
Bank Sta=4984.7,5041.3
XS Rating Curve= 0 ,0
Exp/Cntr=0.3,0.1

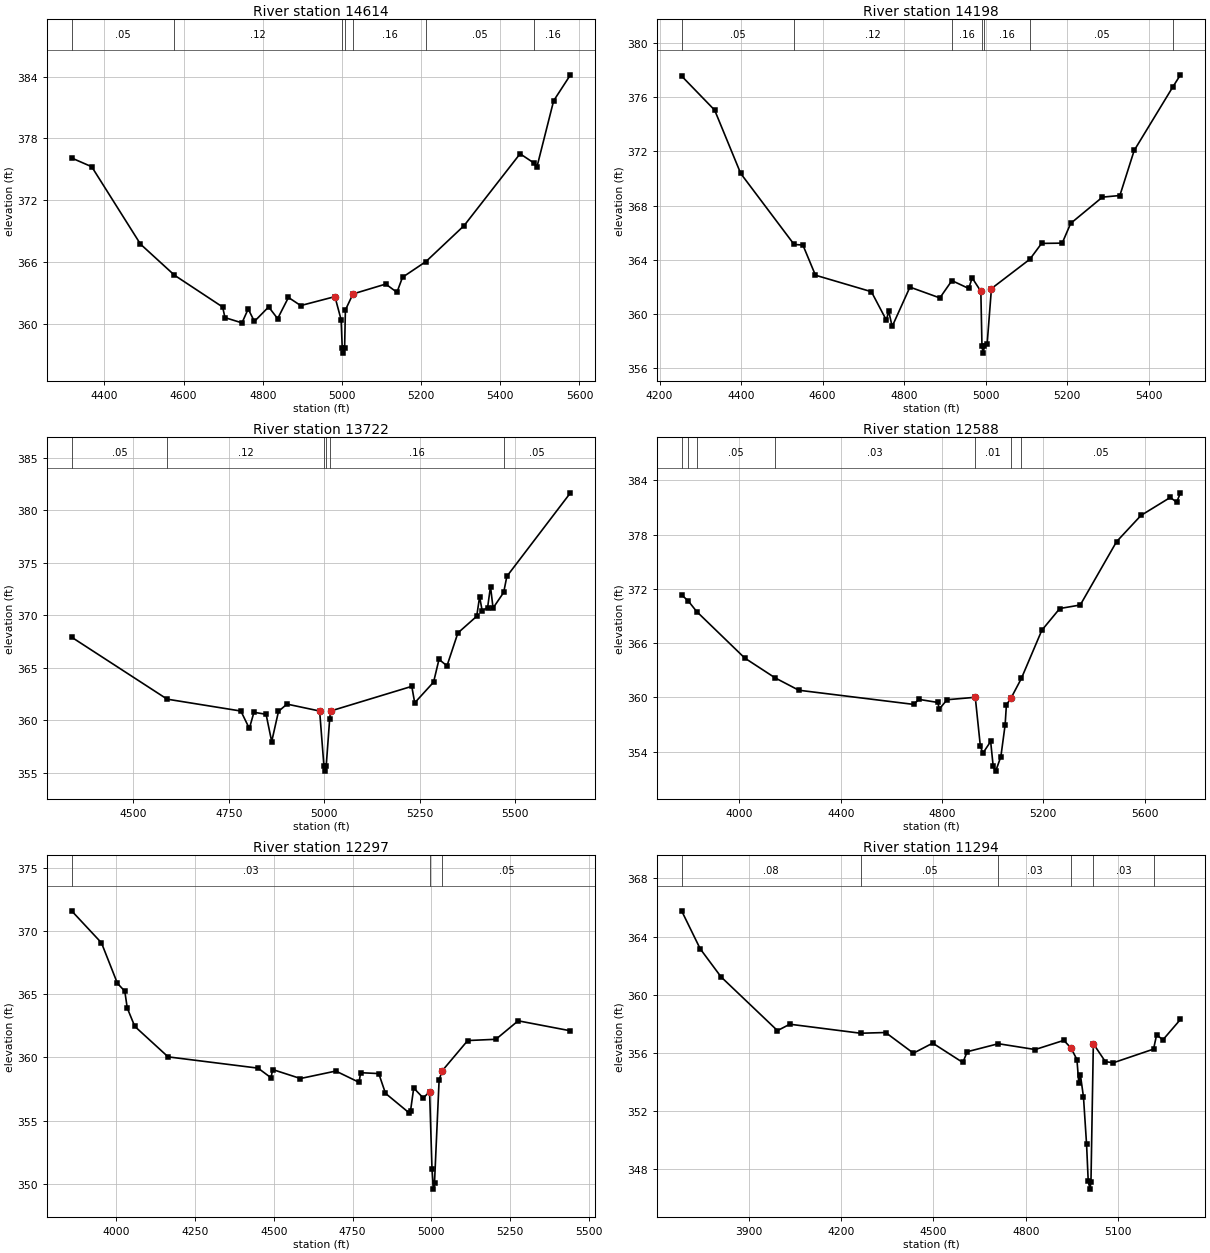
Type RM Length L Ch R = 1 ,14614   ,416,416,416
BEGIN DESCRIPTION:
JACKSON BRANCH 8.0
END DESCRIPTION:
XS GIS Cut Line= 3
      3519999.63     10638410.16      3520349.61     10637810.19
      3520749.63     10637410.17
#Sta/Elev= 30
    4317  376.09  4367.8  375.24    4491  367.72  4576.9   364.7  4698.6  361.61
  4704.4  360.58  4747.4  360.07  4763.1  361.42  4778.8  360.21  4814.8  361.62
  4837.5  360.48  4864.8  362.54  4895.8  361.75  4982.2  362.62  4997.9  360.37
  5000.7  357.63  5003.5  357.13  5006.7  357.63  5008.7  361.32  5027.8  362.88
  5110.6  363.84  5138.9  363.04    5153   364.5  5212.3  366.03  5308.6  369.52
    5450   376.5  5486.3  375.57  5492.4  375.19  5534.8  381.65  5577.3  384.17
#Mann= 7 ,-1 , 0
    4317     .05       0  4576.9     .12       0  5000.7     .07       0
  5006.7     .12       0  5027.8     .16       0  5212.3     .05       0
  5486.3     .16       0
Bank Sta=4982.2,5027.8
XS Rating Curve= 0 ,0
Exp/Cntr=0.3,0.1

Type RM Length L Ch R = 1 ,14198   ,476,476,476
BEGIN DESCRIPTION:
JACKSON BRANCH 7.0
END DESCRIPTION:
XS GIS Cut Line= 3
      3519999.58     10638460.21      3520649.61     10638060.19
      3520999.58     10637760.21
#Sta/Elev= 30
  4254.2  377.57  4335.3  375.05  4399.2  370.37  4530.3  365.12  4551.8  365.08
  4582.6  362.85  4719.9  361.63  4756.6  359.53  4762.4  360.19  4770.9  359.06
  4814.5  361.97  4887.9  361.17  4917.5  362.45  4958.7  361.87  4967.2  362.65
  4988.5  361.66  4991.3  357.59  4994.1  357.09  4997.3  357.59  5003.9  357.75
  5014.5  361.86  5108.8  364.03  5137.6   365.2  5188.1  365.22    5209  366.68
  5286.9  368.62  5329.7  368.74  5364.8  372.07  5459.5  376.76  5478.4  377.66
#Mann= 7 ,-1 , 0
  4254.2     .05       0  4530.3     .12       0  4917.5     .16       0
  4991.3     .07       0  4997.3     .16       0  5108.8     .05       0
  5459.5     .16       0
Bank Sta=4988.5,5014.5
XS Rating Curve= 0 ,0
Exp/Cntr=0.3,0.1

Type RM Length L Ch R = 1 ,13722   ,1134,1134,1134
BEGIN DESCRIPTION:
JACKSON BRANCH 6.0
END DESCRIPTION:
XS GIS Cut Line= 3
      3520344.48     10638687.22      3520891.38     10638444.15
      3521424.96     10637979.98
#Sta/Elev= 30
  4338.5  367.91  4588.6  362.01  4781.5  360.88  4803.7  359.22  4815.7  360.76
  4847.5  360.57  4862.2  357.97    4880  360.85  4902.2  361.54  4987.7  360.88
  4998.9  355.66  5001.7  355.16  5004.9  355.66  5013.9   360.1  5016.2  360.88
  5228.9  363.23  5236.5  361.66  5285.9  363.63  5300.1   365.8    5321  365.18
  5349.5  368.31  5398.8   369.9  5406.4  371.75  5413.1  370.43  5427.3  370.73
  5434.9  372.73  5441.6  370.68  5469.4  372.17  5477.7   373.7  5644.2  381.65
#Mann= 6 ,-1 , 0
  4338.5     .05       0  4588.6     .12       0  4998.9     .07       0
  5004.9     .12       0  5013.9     .16       0  5469.4     .05       0
Bank Sta=4987.7,5016.2
XS Rating Curve= 0 ,0
Exp/Cntr=0.3,0.1

Type RM Length L Ch R = 1 ,12588   ,291,291,291
BEGIN DESCRIPTION:
JACKSON BRANCH 5.0
END DESCRIPTION:
XS GIS Cut Line= 4
      3520422.59     10638869.51      3521247.28     10638648.14
      3521972.11     10638539.64      3522026.82     10638160.45
#Sta/Elev= 30
  3771.6  371.34  3798.3  370.65  3830.9   369.5  4020.9  364.35  4141.3  362.15
  4234.4  360.79  4688.5  359.22  4708.3  359.78  4782.6  359.44  4789.6  358.73
    4820  359.74  4931.2  360.01  4951.4  354.57  4961.5  353.84  4991.9  355.12
    5002  352.37  5011.8  351.84  5032.3  353.45  5049.1  356.96  5054.1  359.17
  5072.7  359.94  5113.2  362.09  5194.1  367.43  5264.9  369.83  5345.8  370.22
  5489.2  377.23  5585.6  380.13  5701.4  382.12  5726.3  381.59  5741.5  382.63
#Mann= 7 ,-1 , 0
  3771.6     .05       0  3798.3     .08       0  3830.9     .05       0
  4141.3     .03       0  4931.2     .01       0  5072.7     .07       0
  5113.2     .05       0
Bank Sta=4931.2,5072.7
XS Rating Curve= 0 ,0
Exp/Cntr=0.3,0.1

Type RM Length L Ch R = 1 ,12297   ,1003,1003,1003
BEGIN DESCRIPTION:
JACKSON BRANCH 4.0
END DESCRIPTION:
XS GIS Cut Line= 4
      3520670.05     10639103.86      3521433.91     10638839.12
      3521898.32     10638778.35      3522205.54     10638765.37
#Sta/Elev= 30
  3857.7  371.58  3952.5  369.05  4003.2  365.85  4026.6  365.23  4034.4   363.9
  4058.3  362.45  4164.2  360.04  4449.9  359.15  4490.9  358.39  4496.2  359.04
  4584.4  358.33  4696.8  358.92  4770.6  358.03  4775.6  358.79  4833.2  358.72
  4854.5  357.16  4928.4  355.64  4934.1  355.78  4944.2  357.58  4974.4  356.79
  4994.6  357.29  5002.2  351.21    5007  349.59  5010.2  350.09  5024.9  358.24
    5035  358.95  5115.6  361.33  5205.2  361.43  5275.9  362.89    5442   362.1
#Mann= 3 , 0 , 0
  3857.7     .03       0  4994.6     .01       0    5035     .05       0
Bank Sta=4994.6,5035
XS Rating Curve= 0 ,0
Exp/Cntr=0.3,0.1

Type RM Length L Ch R = 1 ,11294   ,985,985,985
BEGIN DESCRIPTION:
JACKSON BRANCH 3.0
END DESCRIPTION:
XS GIS Cut Line= 4
       3520869.4     10639326.67      3521813.83     10639243.34
       3522230.5     10639090.56      3522258.04     10638863.33
#Sta/Elev= 30
  3682.1  365.77  3742.5  363.16  3810.3  361.23  3993.5  357.54  4033.7  357.98
  4263.7  357.36  4344.9  357.41  4435.2  355.99  4497.9  356.68  4595.8  355.35
    4610  356.09  4711.3  356.64  4830.8  356.24  4923.9  356.87  4947.5  356.34
  4966.5  355.55  4972.6  353.92    4978  354.47  4987.8  352.97  4997.8  349.73
  5003.1  347.23  5008.9  346.65  5012.1  347.15  5019.8  356.64  5058.8  355.41
  5084.5  355.33  5215.4  356.27  5225.5  357.26  5245.6   356.9  5302.9  358.31
#Mann= 6 ,-1 , 0
  3682.1     .08       0  4263.7     .05       0  4711.3     .03       0
  4947.5     .01       0  5019.8     .03       0  5215.4     .05       0
Bank Sta=4947.5,5019.8
XS Rating Curve= 0 ,0
Exp/Cntr=0.3,0.1