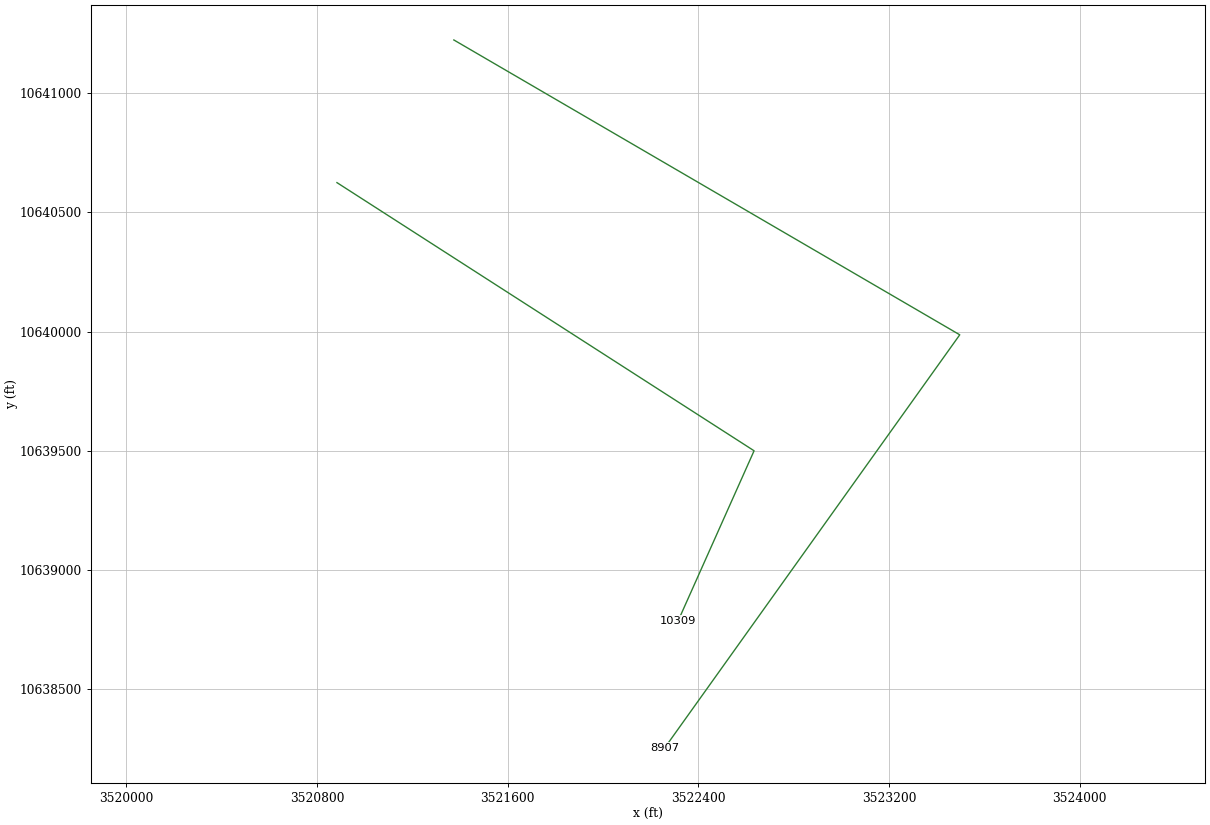
HEC-RAS study JACKSON BRANCH.prj: JACKSON BRANCH Base Level Engineering

--- JACKSON BRANCH.g01 (geometry) --- (continued)

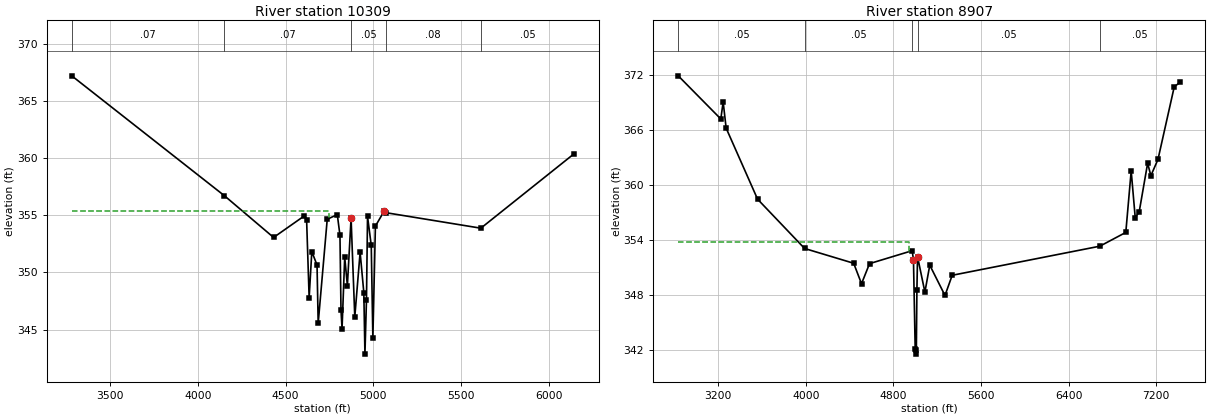
Type RM Length L Ch R = 1 ,10309   ,1402,1402,1402
BEGIN DESCRIPTION:
JACKSON BRANCH 2.0
END DESCRIPTION:
XS GIS Cut Line= 3
      3520883.24     10640625.31      3522633.28     10639500.29
      3522314.25     10638785.94
#Sta/Elev= 30
  3281.1  367.18  4150.5  356.71  4431.9  353.05  4607.5  354.94  4620.1   354.6
  4634.6  347.78  4649.8  351.82  4679.6  350.63  4686.1  345.54  4737.7  354.64
  4795.1  355.05  4810.3  353.24  4816.2  346.68  4822.2  345.08  4837.4  351.33
  4852.6  348.83  4873.7  354.74  4894.8  346.09  4925.2  351.75  4946.4  348.23
  4952.7  342.85  4961.5  347.61  4967.5  354.89  4988.7  352.36  4997.9  344.27
  5012.4  354.04  5061.3  355.33  5070.5  355.22  5613.6  353.86  6143.9  360.35
#Mann= 5 ,-1 , 0
  3281.1     .07       0  4150.5     .07       0  4873.7     .05       0
  5070.5     .08       0  5613.6     .05       0
#XS Ineff= 2 , 0
            4750  355.39
Permanent Ineff=
       F       F
Bank Sta=4873.7,5061.3
XS Rating Curve= 0 ,0
Exp/Cntr=0.3,0.1

Type RM Length L Ch R = 1 ,8907    ,0,0,0
BEGIN DESCRIPTION:
JACKSON BRANCH 1.0
END DESCRIPTION:
XS GIS Cut Line= 3
       3521373.7     10641223.82      3523496.13     10639986.83
      3522259.19     10638255.12
#Sta/Elev= 30
  2835.1  371.87  3223.8  367.17  3245.3  369.02  3272.6  366.17  3559.6  358.43
  3988.9  353.06  4437.2  351.45  4508.7  349.22    4582  351.41  4971.5  352.82
  4983.2  351.79  4998.8  342.15  5006.1  341.55  5009.4  342.05  5014.5  348.54
  5020.3  352.17  5087.4  348.31    5132  351.24  5270.9  347.94  5336.7  350.14
  6685.1  353.31    6922  354.81  6971.2  361.51    7008  356.43    7044  357.03
  7121.4  362.35  7150.9  360.99    7216  362.77  7364.7  370.69  7419.8  371.17
#Mann= 5 ,-1 , 0
  2835.1     .05       0  3988.9     .05       0  4971.5     .03       0
  5020.3     .05       0  6685.1     .05       0
#XS Ineff= 2 , 0
         4945.45   353.8
Permanent Ineff=
       F       F
Bank Sta=4983.2,5020.3
XS Rating Curve= 0 ,0
Exp/Cntr=0.3,0.1

Chan Stop Cuts=-1
Use User Specified Reach Order=0
Composite Channel Slope=5