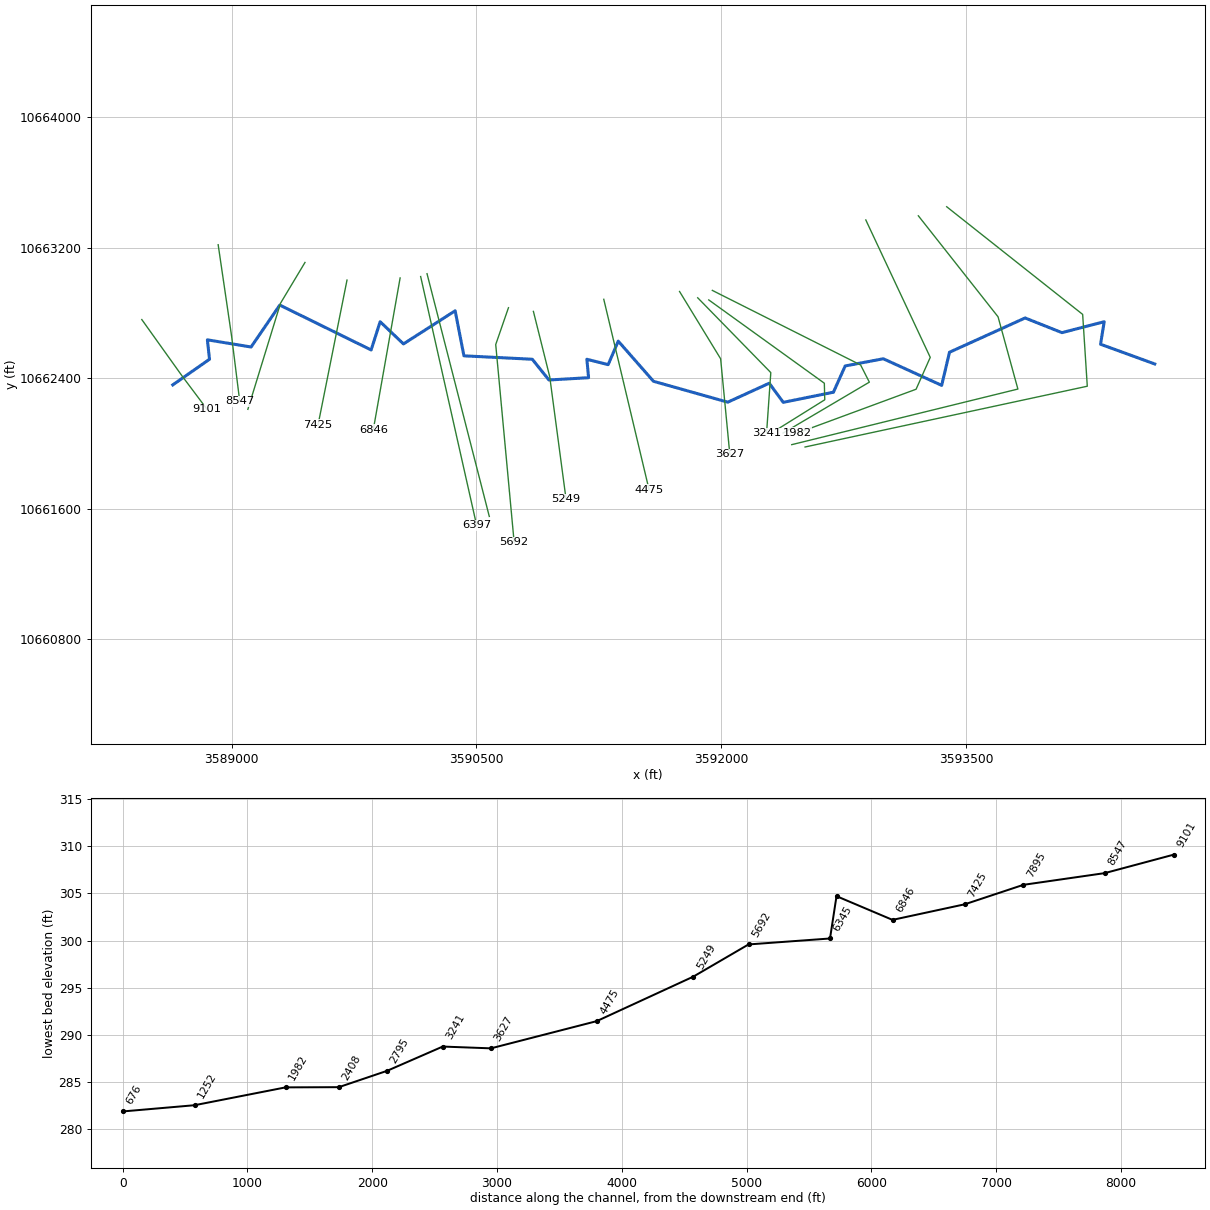
--- JOE CREEK.prj (project) ---

Proj Title=JOE CREEK Base Level Engineering
Current Plan=p01
Default Exp/Contr=0.3,0.1
English Units
Geom File=g01
Flow File=f01
Plan File=p01
BEGIN DESCRIPTION:
JOE CREEK
END DESCRIPTION:

--- JOE CREEK.p01 (plan) ---

Plan Title=Multiple Run
Short Identifier=Multiple
Geom File=g01
Flow File=f01
Subcritical Flow
K Sum by GR= 0
Std Step Tol= 0.01
Critical Tol= 0.01
Num of Std Step Trials= 20
Max Error Tol= 0.3
Flow Tol Ratio= 0.001
Split Flow NTrial= 30
Split Flow Tol= 0.02
Split Flow Ratio= 0.02
Log Output Level= 0
Friction Slope Method= 1
Unsteady Friction Slope Method= 2
Unsteady Bridges Friction Slope Method= 1
Parabolic Critical Depth
Global Vel Dist=  1 , 1 , 1
Global Log Level= 0
CheckData=True
Encroach Param= -1, 0, 0, 0
BEGIN DESCRIPTION:
Multiple Run
END DESCRIPTION:

--- JOE CREEK.f01 (steady flow) ---

Flow Title=Multiple
Number of Profiles=7
Profile Names=10-year,25-year,50-year,1pct_min,100-year,1pct_plu,500-year
River Rch & RM= JOE CREEK,Reach-1,9101
    1919    2687    3332    3013    4074    5510    6073
River Rch & RM= JOE CREEK,Reach-1,1982
    2854    4083    5137    4705    6364    8606    9742
Boundary for River Rch & Prof#=JOE CREEK,Reach-1,1
Up Type=0
Dn Type=3
Dn Slope=0.005
Boundary for River Rch & Prof#=JOE CREEK,Reach-1,2
Up Type=0
Dn Type=3
Dn Slope=0.005
Boundary for River Rch & Prof#=JOE CREEK,Reach-1,3
Up Type=0
Dn Type=3
Dn Slope=0.005
Boundary for River Rch & Prof#=JOE CREEK,Reach-1,4
Up Type=0
Dn Type=3
Dn Slope=0.005
Boundary for River Rch & Prof#=JOE CREEK,Reach-1,5
Up Type=0
Dn Type=3
Dn Slope=0.005
Boundary for River Rch & Prof#=JOE CREEK,Reach-1,6
Up Type=0
Dn Type=3
Dn Slope=0.005
Boundary for River Rch & Prof#=JOE CREEK,Reach-1,7
Up Type=0
Dn Type=3
Dn Slope=0.005

--- JOE CREEK.g01 (geometry) ---

Geom Title=Existing Conditions

River Reach=JOE CREEK,Reach-1
Reach XY= 30
      3588639.50     10662360.00      3588864.50     10662517.00
      3588851.50     10662636.00      3589119.25     10662592.00
      3589295.25     10662849.00      3589855.00     10662574.00
      3589910.25     10662747.00      3590053.25     10662611.00
      3590370.00     10662814.00      3590423.75     10662538.00
      3590842.75     10662517.00      3590944.75     10662390.00
      3591187.75     10662404.00      3591177.25     10662517.00
      3591307.75     10662484.00      3591369.50     10662628.00
      3591585.50     10662382.00      3592040.75     10662254.00
      3592294.75     10662370.00      3592380.75     10662253.00
      3592688.25     10662315.00      3592760.50     10662476.00
      3592994.00     10662520.00      3593351.75     10662357.00
      3593399.75     10662560.00      3593863.25     10662770.00
      3594088.75     10662680.00      3594347.75     10662747.00
      3594325.50     10662609.00      3594657.75     10662488.00

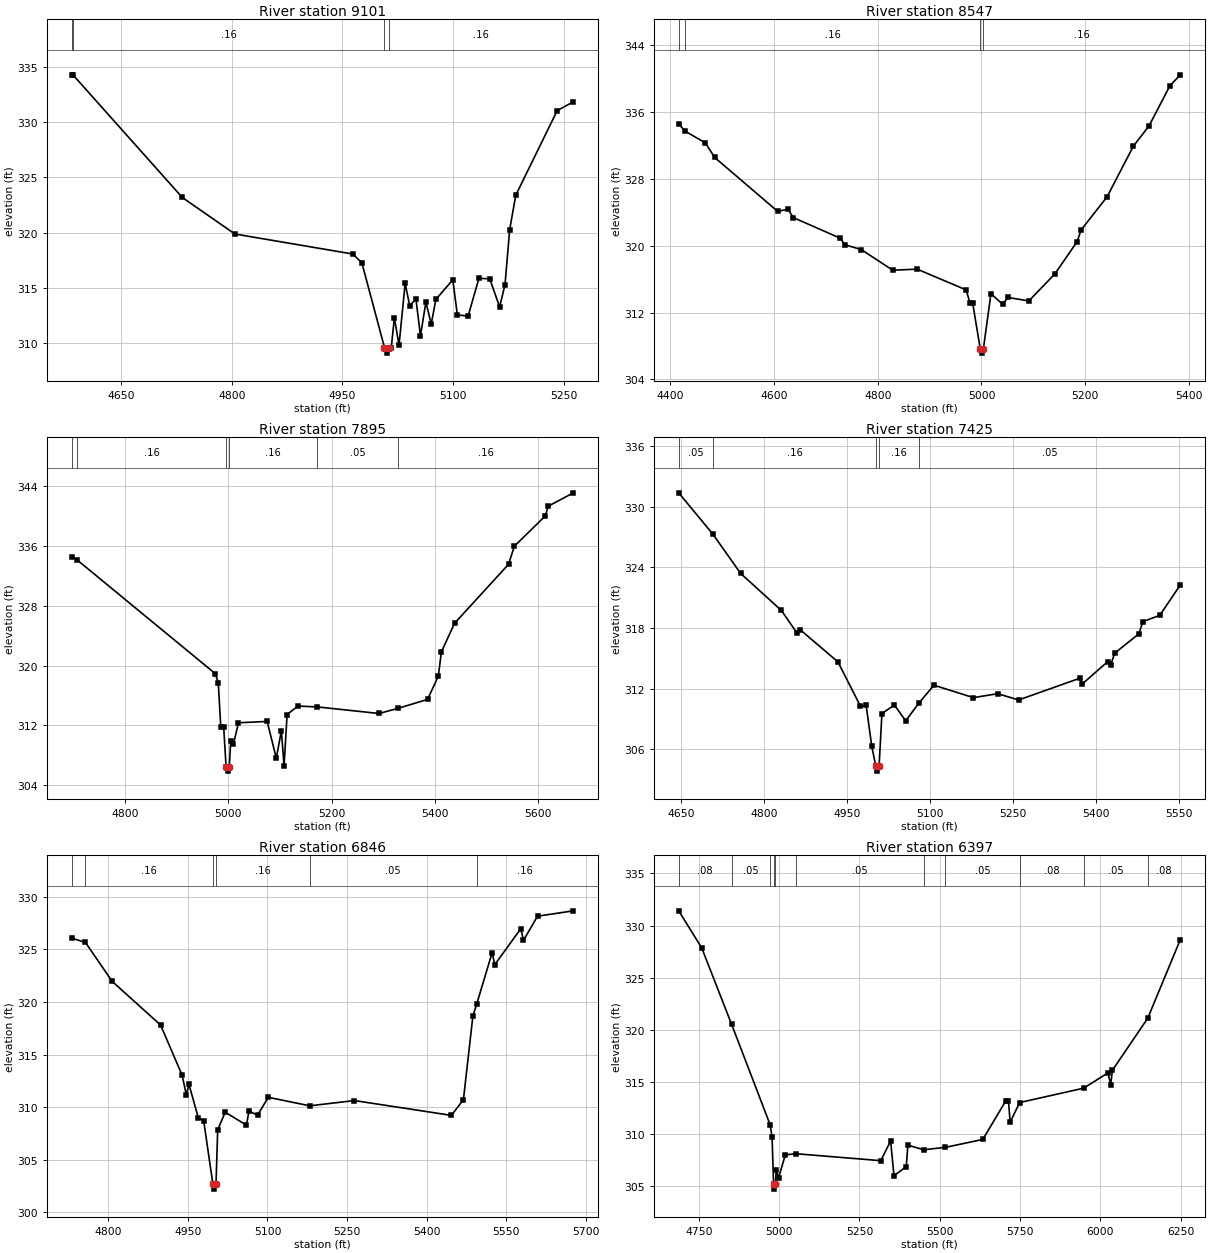
Type RM Length L Ch R = 1,9101,554,554,554
BEGIN DESCRIPTION:
JOE CREEK 13.0
END DESCRIPTION:
XS GIS Cut Line= 3
      3588449.61     10662760.19      3588699.61     10662410.19
      3588849.60     10662210.20
#Sta/Elev= 30
  4583.0  334.26  4584.6  334.26  4732.9  323.17  4804.2  319.87  4964.0  318.06
  4976.3  317.27  5007.0  309.60  5009.8  309.10  5013.0  309.60  5016.2  309.60
  5020.4  312.29  5026.7  309.82  5035.0  315.40  5041.2  313.38  5049.6  314.00
  5055.8  310.67  5063.1  313.71  5070.4  311.74  5076.7  313.96  5099.6  315.73
  5105.8  312.55  5120.4  312.46  5135.0  315.85  5149.6  315.83  5163.1  313.28
  5170.4  315.29  5176.7  320.25  5185.0  323.38  5241.2  331.03  5263.1  331.82
#Mann=4,-1,0
  4583.0    0.05       0  4584.6    0.16       0  5007.0    0.07       0
  5013.0    0.16       0
Bank Sta=5007,5013
Exp/Cntr=0.3,0.1

Type RM Length L Ch R = 1,8547,652,652,652
BEGIN DESCRIPTION:
JOE CREEK 12.0
END DESCRIPTION:
XS GIS Cut Line= 3
      3588917.56     10663218.85      3588999.61     10662660.19
      3589049.61     10662260.15
#Sta/Elev= 30
  4415.9  334.61  4427.8  333.75  4467.3  332.33  4485.3  330.58  4606.9  324.12
  4626.8  324.38  4636.9  323.38  4727.9  320.90  4736.3  320.13  4768.3  319.54
  4828.9  317.07  4875.9  317.20  4970.4  314.72  4978.0  313.13  4983.1  313.13
  4997.7  307.64  5000.5  307.14  5003.7  307.64  5018.3  314.26  5041.0  312.99
  5051.1  313.81  5091.4  313.39  5141.8  316.64  5184.6  320.50  5192.2  321.89
  5242.6  325.89  5293.0  331.93  5323.2  334.35  5363.5  339.16  5383.7  340.48
#Mann=4,-1,0
  4415.9    0.05       0  4427.8    0.16       0  4997.7    0.07       0
  5003.7    0.16       0
Bank Sta=4997.7,5003.7
Exp/Cntr=0.3,0.1

Type RM Length L Ch R = 1,7895,470,470,470
BEGIN DESCRIPTION:
JOE CREEK 11.0
END DESCRIPTION:
XS GIS Cut Line= 3
      3589449.61     10663110.18      3589299.61     10662860.19
      3589099.61     10662210.20
#Sta/Elev= 30
  4696.7  334.52  4706.5  334.15  4974.6  318.93  4980.5  317.72  4985.3  311.85
  4990.9  311.85  4995.7  306.40  4998.5  305.90  5001.7  306.40  5004.6  309.92
  5009.8  309.49  5019.6  312.36  5075.2  312.54  5092.9  307.62  5102.7  311.29
  5107.9  306.60  5113.8  313.46  5134.7  314.59  5172.3  314.48  5291.7  313.60
  5329.3  314.30  5385.8  315.48  5406.7  318.58  5412.6  321.82  5438.1  325.65
  5542.8  333.54  5553.9  335.94  5614.0  340.00  5619.3  341.29  5668.3  343.08
#Mann=6,-1,0
  4696.7    0.05       0  4706.5    0.16       0  4995.7    0.07       0
  5001.7    0.16       0  5172.3    0.05       0  5329.3    0.16       0
Bank Sta=4995.7,5001.7
Exp/Cntr=0.3,0.1

Type RM Length L Ch R = 1,7425,579,579,579
BEGIN DESCRIPTION:
Mapping XS 09747d76
END DESCRIPTION:
XS GIS Cut Line= 2
      3589707.16     10663002.12      3589529.50     10662113.81
#Sta/Elev= 30
  4645.9  331.37  4707.9  327.26  4757.9  323.39  4831.4  319.73  4859.9  317.47
  4865.0  317.84  4933.4  314.65  4974.2  310.26  4984.4  310.35  4994.6  306.28
  5001.8  304.34  5004.6  303.84  5007.8  304.34  5012.9  309.54  5035.4  310.38
  5055.8  308.82  5079.8  310.58  5106.8  312.34  5178.2  311.11  5221.9  311.50
  5259.8  310.88  5369.8  313.02  5374.9  312.47  5420.8  314.68  5425.9  314.30
  5433.1  315.50  5476.9  317.42  5484.1  318.63  5514.7  319.25  5551.8  322.26
#Mann=5,-1,0
  4645.9    0.05       0  4707.9    0.16       0  5001.8    0.07       0
  5007.8    0.16       0  5079.8    0.05       0
Bank Sta=5001.8,5007.8
Exp/Cntr=0.3,0.1

Type RM Length L Ch R = 1,6846,449,449,449
BEGIN DESCRIPTION:
JOE CREEK 10.0
END DESCRIPTION:
XS GIS Cut Line= 2
      3590032.68     10663015.14      3589868.03     10662083.58
#Sta/Elev= 30
  4730.9  326.08  4756.8  325.67  4807.0  321.97  4898.4  317.81  4939.0  313.04
  4946.9  311.18  4952.0  312.15  4969.5  308.99  4979.7  308.70  4997.0  302.69
  4999.7  302.19  5003.0  302.69  5006.1  307.83  5020.3  309.51  5060.2  308.29
  5065.3  309.63  5081.2  309.22  5101.5  310.93  5179.8  310.12  5264.0  310.62
  5446.8  309.21  5469.5  310.70  5487.4  318.68  5494.5  319.79  5523.6  324.69
  5528.7  323.56  5577.7  326.98  5582.8  325.87  5609.3  328.17  5676.9  328.68
#Mann=6,-1,0
  4730.9    0.05       0  4756.8    0.16       0  4997.0    0.07       0
  5003.0    0.16       0  5179.8    0.05       0  5494.5    0.16       0
Bank Sta=4997,5003
Exp/Cntr=0.3,0.1

Type RM Length L Ch R = 1,6397,52,52,52
BEGIN DESCRIPTION:
JOE CREEK 9.0
END DESCRIPTION:
XS GIS Cut Line= 2
      3590158.56     10663023.82      3590501.44     10661500.43
#Sta/Elev= 30
  4687.2  331.41  4758.9  327.85  4852.0  320.51  4971.7  310.89  4977.9  309.67
  4982.5  305.20  4985.3  304.70  4988.5  305.20  4990.6  306.54  4998.4  305.80
  5018.9  307.98  5051.3  308.10  5316.2  307.43  5346.9  309.32  5357.3  305.99
  5395.5  306.85  5400.6  308.92  5449.8  308.48  5517.5  308.71  5633.9  309.47
  5705.7  313.19  5713.7  313.19  5718.9  311.12  5748.6  313.01  5947.9  314.39
  6023.4  315.86  6032.0  314.72  6037.1  316.10  6147.2  321.10  6248.7  328.65
#Mann=11,-1,0
  4687.2    0.08       0  4852.0    0.05       0  4971.7    0.08       0
  4982.5    0.07       0  4988.5    0.08       0  5051.3    0.05       0
  5449.8    0.08       0  5517.5    0.05       0  5748.6    0.08       0
  5947.9    0.05       0  6147.2    0.08       0
Bank Sta=4982.5,4988.5
Exp/Cntr=0.3,0.1

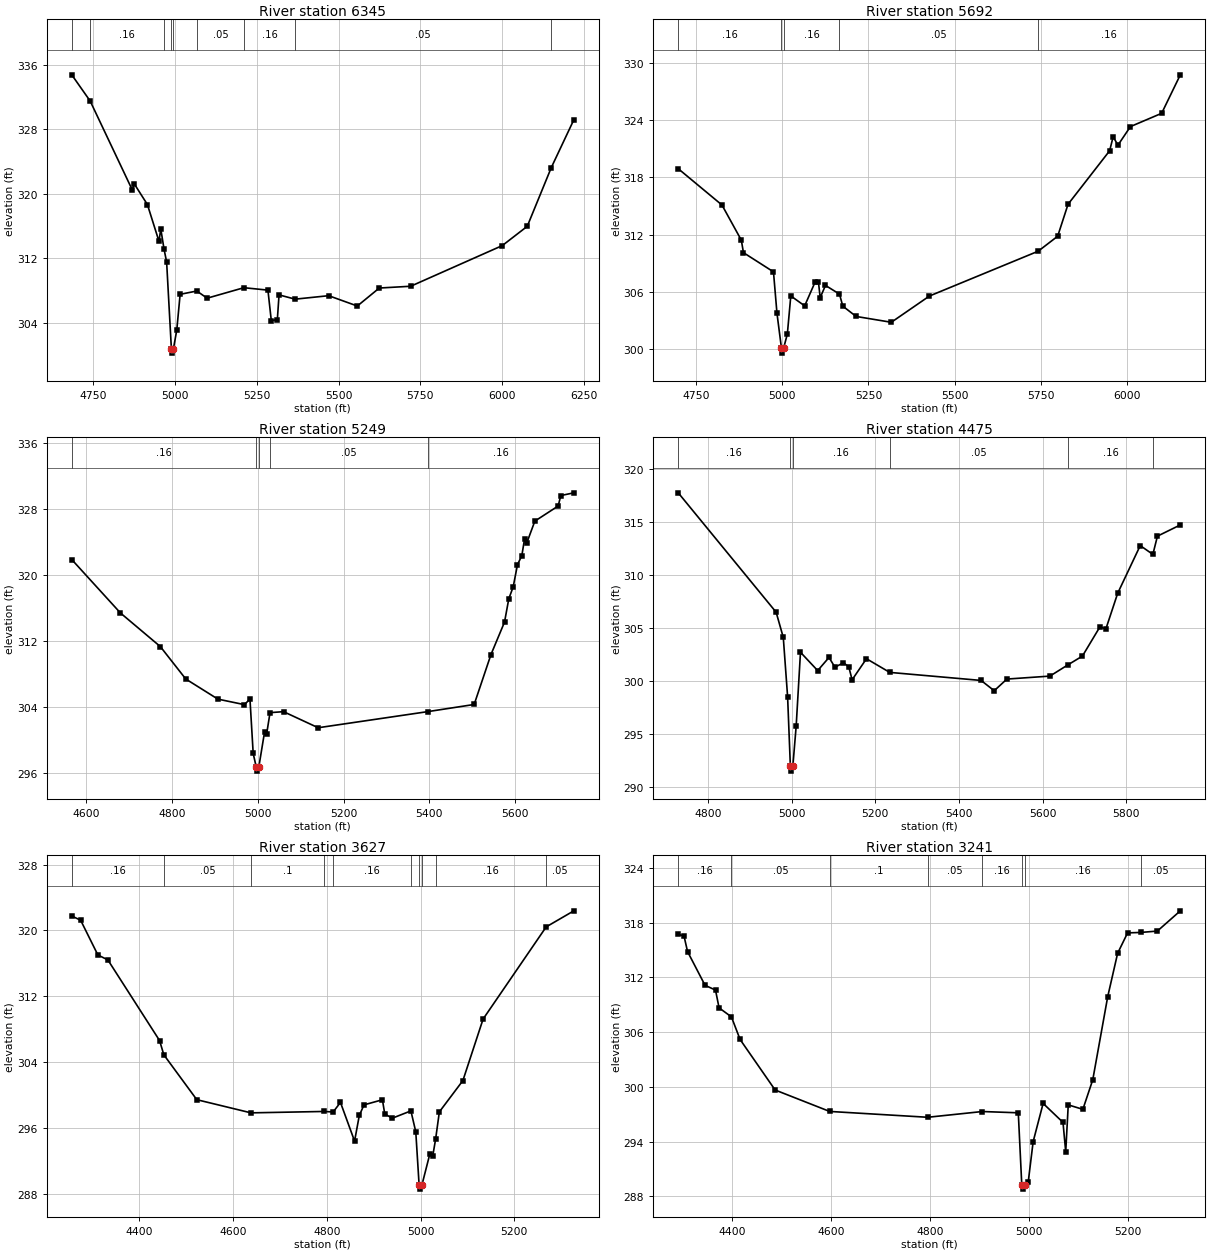
Type RM Length L Ch R = 1,6345,653,653,653
BEGIN DESCRIPTION:
JOE CREEK 8.0
END DESCRIPTION:
XS GIS Cut Line= 2
      3590197.62     10663041.22      3590579.21     10661553.89
#Sta/Elev= 30
  4683.9  334.72  4740.2  331.47  4869.3  320.42  4874.5  321.24  4915.2  318.64
  4950.8  314.06  4956.0  315.65  4966.1  313.11  4974.0  311.52  4988.6  300.72
  4991.4  300.22  4994.6  300.72  5005.0  303.07  5015.3  307.51  5066.3  307.92
  5097.9  307.03  5210.2  308.33  5283.8  308.03  5294.1  304.25  5312.6  304.38
  5317.8  307.44  5367.0  306.91  5469.6  307.34  5557.2  306.06  5624.4  308.29
  5720.3  308.51  6000.5  313.55  6076.9  315.94  6150.4  323.22  6219.4  329.15
#Mann=9,-1,0
  4683.9    0.08       0  4740.2    0.16       0  4966.1    0.08       0
  4988.6    0.07       0  4994.6    0.08       0  5066.3    0.05       0
  5210.2    0.16       0  5367.0    0.05       0  6150.4    0.16       0
Bank Sta=4988.6,4994.6
Exp/Cntr=0.3,0.1

Type RM Length L Ch R = 1,5692,443,443,443
BEGIN DESCRIPTION:
JOE CREEK 7.0
END DESCRIPTION:
XS GIS Cut Line= 3
      3590696.75     10662832.90      3590618.63     10662607.19
      3590731.47     10661396.29
#Sta/Elev= 30
  4698.8  318.90  4825.5  315.10  4881.6  311.42  4887.8  310.11  4974.8  308.10
  4984.9  303.77  4998.0  300.09  5000.8  299.59  5004.0  300.09  5015.0  301.59
  5025.0  305.58  5065.2  304.54  5095.3  307.02  5105.1  307.03  5110.2  305.40
  5125.5  306.68  5166.1  305.77  5175.7  304.51  5214.3  303.43  5316.3  302.82
  5426.8  305.57  5741.8  310.26  5798.4  311.83  5828.5  315.18  5949.0  320.78
  5959.1  322.24  5973.1  321.37  6009.3  323.31  6099.7  324.70  6153.8  328.73
#Mann=5,-1,0
  4698.8    0.16       0  4998.0    0.07       0  5004.0    0.16       0
  5166.1    0.05       0  5741.8    0.16       0
Bank Sta=4998,5004
Exp/Cntr=0.3,0.1

Type RM Length L Ch R = 1,5249,774,774,774
BEGIN DESCRIPTION:
JOE CREEK 6.0
END DESCRIPTION:
XS GIS Cut Line= 3
      3590849.60     10662810.21      3590949.61     10662410.19
      3591049.61     10661660.16
#Sta/Elev= 30
  4567.3  321.83  4680.7  315.35  4773.5  311.28  4832.7  307.35  4907.5  304.91
  4969.3  304.24  4982.2  304.92  4989.7  298.32  4996.8  296.68  4999.6  296.18
  5002.8  296.68  5016.2  300.93  5021.2  300.74  5028.9  303.27  5060.3  303.39
  5141.0  301.44  5395.7  303.39  5504.2  304.26  5543.3  310.31  5574.9  314.25
  5584.9  317.09  5595.0  318.50  5605.1  321.22  5615.2  322.30  5621.5  324.32
  5626.6  323.83  5645.5  326.49  5699.7  328.32  5706.0  329.59  5736.3  329.92
#Mann=5,-1,0
  4567.3    0.16       0  4996.8    0.07       0  5002.8    0.16       0
  5028.9    0.05       0  5395.7    0.16       0
Bank Sta=4996.8,5002.8
Exp/Cntr=0.3,0.1

Type RM Length L Ch R = 1,4475,848,848,848
BEGIN DESCRIPTION:
JOE CREEK 5.0
END DESCRIPTION:
XS GIS Cut Line= 2
      3591280.86     10662884.47      3591558.63     10661716.96
#Sta/Elev= 30
  4729.2  317.74  4963.2  306.47  4980.3  304.09  4990.6  298.51  4997.2  291.97
  4999.9  291.47  5003.2  291.97  5011.1  295.72  5021.4  302.69  5062.5  300.96
  5089.6  302.20  5103.7  301.28  5124.2  301.70  5136.9  301.31  5144.8  300.09
  5179.1  302.08  5234.8  300.79  5453.1  300.03  5484.5  299.06  5514.8  300.16
  5617.6  300.44  5661.0  301.51  5695.3  302.33  5737.5  305.11  5751.2  304.87
  5779.6  308.26  5833.5  312.76  5863.7  311.93  5874.6  313.65  5929.3  314.71
#Mann=6,-1,0
  4729.2    0.16       0  4997.2    0.07       0  5003.2    0.16       0
  5234.8    0.05       0  5661.0    0.16       0  5863.7    0.05       0
Bank Sta=4997.2,5003.2
Exp/Cntr=0.3,0.1

Type RM Length L Ch R = 1,3627,386,386,386
BEGIN DESCRIPTION:
Mapping XS 2803dfa4
END DESCRIPTION:
XS GIS Cut Line= 3
      3591745.28     10662932.21      3591997.00     10662519.92
      3592053.36     10661934.58
#Sta/Elev= 30
  4255.9  321.75  4274.8  321.24  4311.6  317.02  4332.9  316.42  4443.2  306.63
  4452.3  304.90  4522.6  299.45  4638.3  297.85  4793.8  298.02  4813.6  297.96
  4829.1  299.12  4859.2  294.42  4869.3  297.53  4879.3  298.82  4918.6  299.44
  4923.6  297.72  4939.6  297.20  4979.4  298.09  4989.8  295.54  4996.9  289.09
  4999.6  288.59  5002.9  289.09  5020.0  292.91  5026.0  292.62  5032.1  294.66
  5040.1  297.97  5090.3  301.77  5133.4  309.24  5268.0  320.43  5327.0  322.38
#Mann=10,-1,0
  4255.9    0.16       0  4452.3    0.05       0  4638.3     0.1       0
  4793.8    0.05       0  4813.6    0.16       0  4979.4    0.12       0
  4996.9    0.07       0  5002.9    0.12       0  5032.1    0.16       0
  5268.0    0.05       0
Bank Sta=4996.9,5002.9
Exp/Cntr=0.3,0.1

Type RM Length L Ch R = 1,3241,446,446,446
BEGIN DESCRIPTION:
Mapping XS 4d5db28a
END DESCRIPTION:
XS GIS Cut Line= 3
      3591856.60     10662893.62      3592304.49     10662435.31
      3592278.52     10662064.04
#Sta/Elev= 30
  4292.0  316.71  4303.6  316.55  4310.8  314.83  4346.1  311.13  4367.2  310.61
  4374.4  308.66  4399.3  307.67  4416.8  305.19  4487.5  299.65  4597.5  297.30
  4795.3  296.66  4905.6  297.29  4978.1  297.15  4985.1  289.28  4987.8  288.78
  4991.1  289.28  4998.1  289.54  5008.1  293.99  5028.2  298.18  5068.3  296.10
  5073.8  292.87  5078.9  298.02  5108.4  297.53  5128.4  300.78  5158.5  309.88
  5178.5  314.64  5198.6  316.88  5225.1  316.93  5258.7  317.08  5305.0  319.30
#Mann=8,-1,0
  4292.0    0.16       0  4399.3    0.05       0  4597.5     0.1       0
  4795.3    0.05       0  4905.6    0.16       0  4985.1    0.07       0
  4991.1    0.16       0  5225.1    0.05       0
Bank Sta=4985.1,4991.1
Exp/Cntr=0.3,0.1

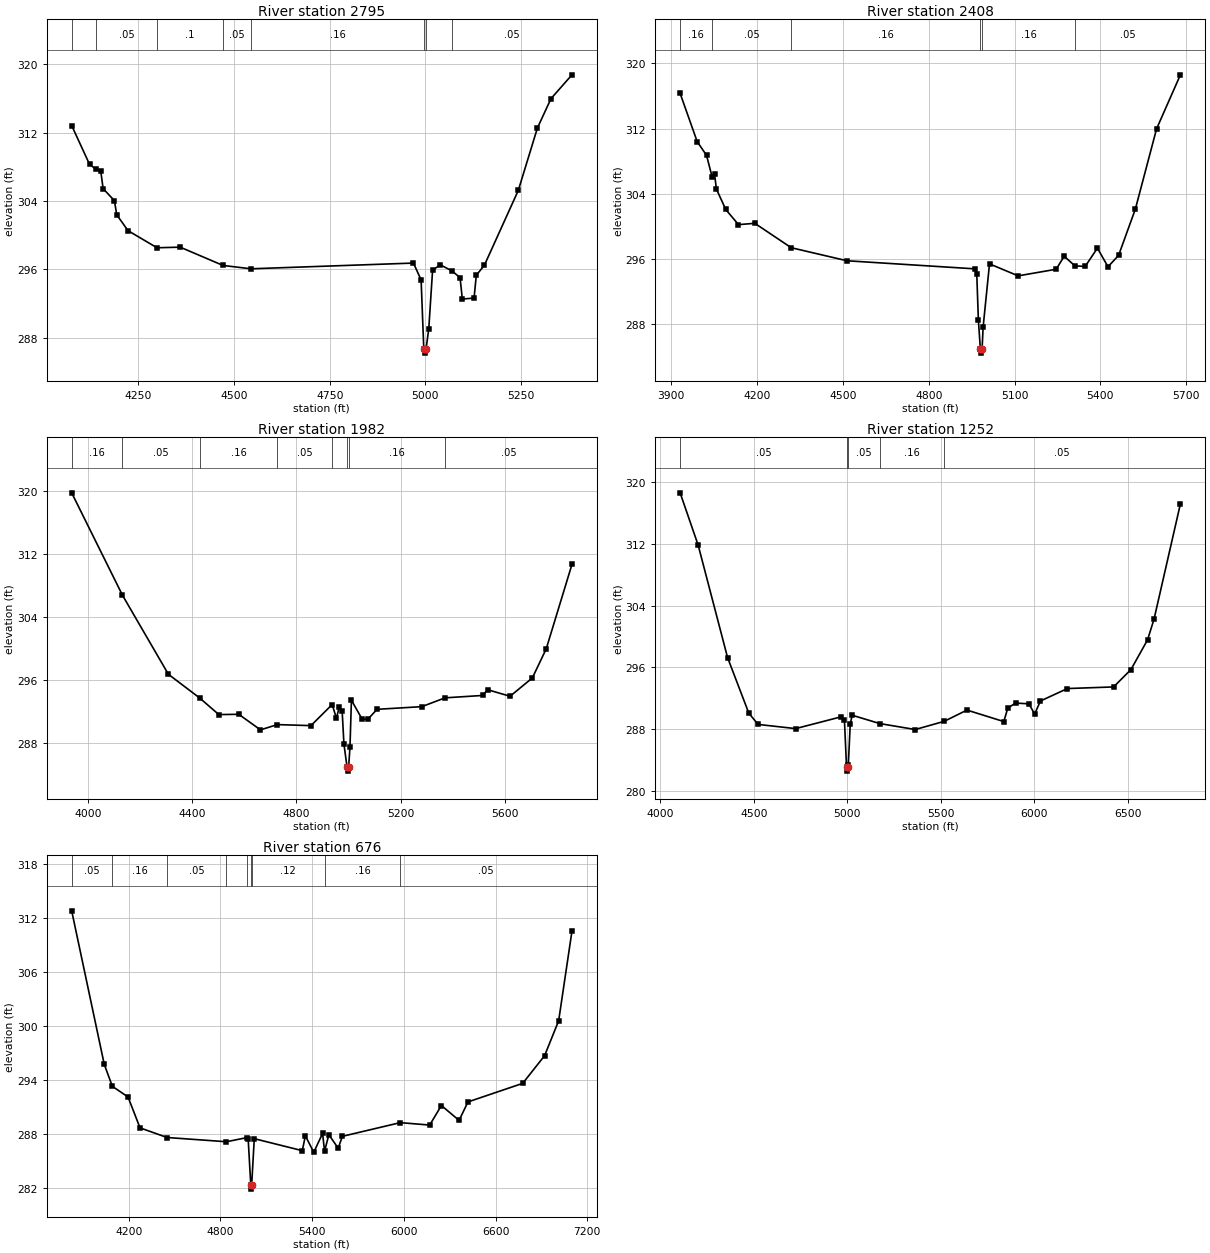
Type RM Length L Ch R = 1,2795,387,387,387
BEGIN DESCRIPTION:
Mapping XS 68ab954e
END DESCRIPTION:
XS GIS Cut Line= 4
      3591924.27     10662880.63      3592632.61     10662370.21
      3592635.21     10662268.65      3592353.01     10662092.59
#Sta/Elev= 30
  4075.6  312.82  4122.2  308.29  4138.3  307.73  4151.7  307.45  4157.8  305.44
  4187.2  304.04  4193.4  302.38  4222.8  300.53  4298.6  298.53  4359.1  298.60
  4471.3  296.46  4544.2  296.07  4968.7  296.74  4988.7  294.77  4995.7  286.71
  4998.5  286.21  5001.7  286.71  5008.7  289.06  5018.7  295.90  5038.7  296.54
  5069.0  295.83  5090.5  295.04  5096.4  292.53  5127.1  292.65  5132.9  295.31
  5154.2  296.50  5242.7  305.24  5292.6  312.53  5328.0  315.96  5382.9  318.75
#Mann=8,-1,0
  4075.6    0.16       0  4138.3    0.05       0  4298.6     0.1       0
  4471.3    0.05       0  4544.2    0.16       0  4995.7    0.07       0
  5001.7    0.16       0  5069.0    0.05       0
Bank Sta=4995.7,5001.7
Exp/Cntr=0.3,0.1

Type RM Length L Ch R = 1,2408,426,426,426
BEGIN DESCRIPTION:
JOE CREEK 4.0
END DESCRIPTION:
XS GIS Cut Line= 4
      3591946.28     10662938.82      3592855.12     10662481.79
      3592908.45     10662376.69      3592379.80     10662064.70
#Sta/Elev= 30
  3930.7  316.32  3990.4  310.40  4023.1  308.72  4042.9  306.03  4051.0  306.42
  4057.6  304.59  4090.1  302.09  4134.7  300.23  4191.9  300.39  4319.1  297.40
  4514.2  295.80  4961.0  294.81  4967.8  294.18  4973.4  288.53  4980.4  284.98
  4983.2  284.48  4986.4  284.98  4990.0  287.67  5012.3  295.42  5112.5  293.95
  5245.2  294.76  5273.5  296.35  5310.8  295.18  5346.6  295.10  5389.6  297.35
  5426.6  295.06  5463.7  296.47  5522.2  302.13  5596.4  311.97  5679.7  318.59
#Mann=6,-1,0
  3930.7    0.16       0  4042.9    0.05       0  4319.1    0.16       0
  4980.4    0.07       0  4986.4    0.16       0  5310.8    0.05       0
Bank Sta=4980.4,4986.4
Exp/Cntr=0.3,0.1

Type RM Length L Ch R = 1,1982,730,730,730
BEGIN DESCRIPTION:
JOE CREEK 3.0
END DESCRIPTION:
XS GIS Cut Line= 4
      3592886.77     10663370.57      3593281.72     10662528.60
      3593194.91     10662333.29      3592467.12     10662064.70
#Sta/Elev= 30
  3938.3  319.81  4133.2  306.80  4309.4  296.76  4429.0  293.76  4503.0  291.64
  4579.4  291.68  4662.7  289.70  4727.2  290.37  4856.3  290.24  4937.8  292.92
  4954.1  291.17  4965.1  292.64  4976.0  292.13  4982.9  287.90  4994.9  284.96
  4997.6  284.46  5000.9  284.96  5006.1  287.53  5011.6  293.47  5052.6  291.07
  5074.5  291.04  5109.9  292.31  5281.8  292.65  5370.9  293.77  5514.6  294.07
  5534.4  294.80  5620.3  293.97  5705.9  296.30  5759.2  300.01  5857.8  310.72
#Mann=8,-1,0
  3938.3    0.16       0  4133.2    0.05       0  4429.0    0.16       0
  4727.2    0.05       0  4937.8    0.16       0  4994.9    0.07       0
  5000.9    0.16       0  5370.9    0.05       0
Bank Sta=4994.9,5000.9
Exp/Cntr=0.3,0.1

Type RM Length L Ch R = 1,1252,576,576,576
BEGIN DESCRIPTION:
JOE CREEK 2.0
END DESCRIPTION:
XS GIS Cut Line= 4
      3593208.88     10663395.99      3593697.30     10662777.08
      3593818.83     10662334.37      3592432.90     10661993.67
#Sta/Elev= 30
  4105.8  318.63  4202.4  311.84  4359.4  297.29  4473.2  290.07  4522.9  288.62
  4723.4  288.08  4964.2  289.59  4984.3  289.14  4995.6  283.07  4998.4  282.57
  5001.6  283.07  5005.1  283.42  5015.4  288.70  5025.8  289.81  5173.8  288.73
  5362.8  287.96  5517.5  289.02  5639.4  290.48  5836.5  288.99  5857.4  290.73
  5898.9  291.39  5970.4  291.29  6001.3  289.97  6032.2  291.66  6176.3  293.27
  6423.5  293.48  6516.1  295.73  6605.1  299.59  6639.7  302.28  6780.5  317.20
#Mann=5,-1,0
  4105.8    0.05       0  4995.6    0.03       0  5001.6    0.05       0
  5173.8    0.16       0  5517.5    0.05       0
Bank Sta=4995.6,5001.6
Exp/Cntr=0.3,0.1

Type RM Length L Ch R = 1,676,0,0,0
BEGIN DESCRIPTION:
JOE CREEK 1.0
END DESCRIPTION:
XS GIS Cut Line= 4
      3593382.52     10663451.53      3594215.82     10662791.84
      3594244.17     10662351.73      3592514.54     10661979.36
#Sta/Elev= 30
  3827.1  312.80  4040.2  295.76  4093.2  293.32  4195.7  292.14  4274.2  288.71
  4451.3  287.64  4839.7  287.17  4971.3  287.62  4981.8  287.47  4998.8  282.41
  5001.6  281.91  5004.8  282.41  5021.7  287.51  5335.8  286.18  5356.1  287.83
  5410.9  286.00  5468.6  288.09  5481.7  286.13  5509.6  287.95  5570.9  286.45
  5598.0  287.77  5976.7  289.29  6169.5  289.02  6246.0  291.19  6361.7  289.54
  6419.9  291.59  6777.9  293.65  6921.1  296.72  7013.2  300.60  7100.2  310.55
#Mann=9,-1,0
  3827.1    0.05       0  4093.2    0.16       0  4451.3    0.05       0
  4839.7    0.16       0  4971.3    0.12       0  4998.8    0.07       0
  5004.8    0.12       0  5481.7    0.16       0  5976.7    0.05       0
Bank Sta=4998.8,5004.8
Exp/Cntr=0.3,0.1

Chan Stop Cuts=-1