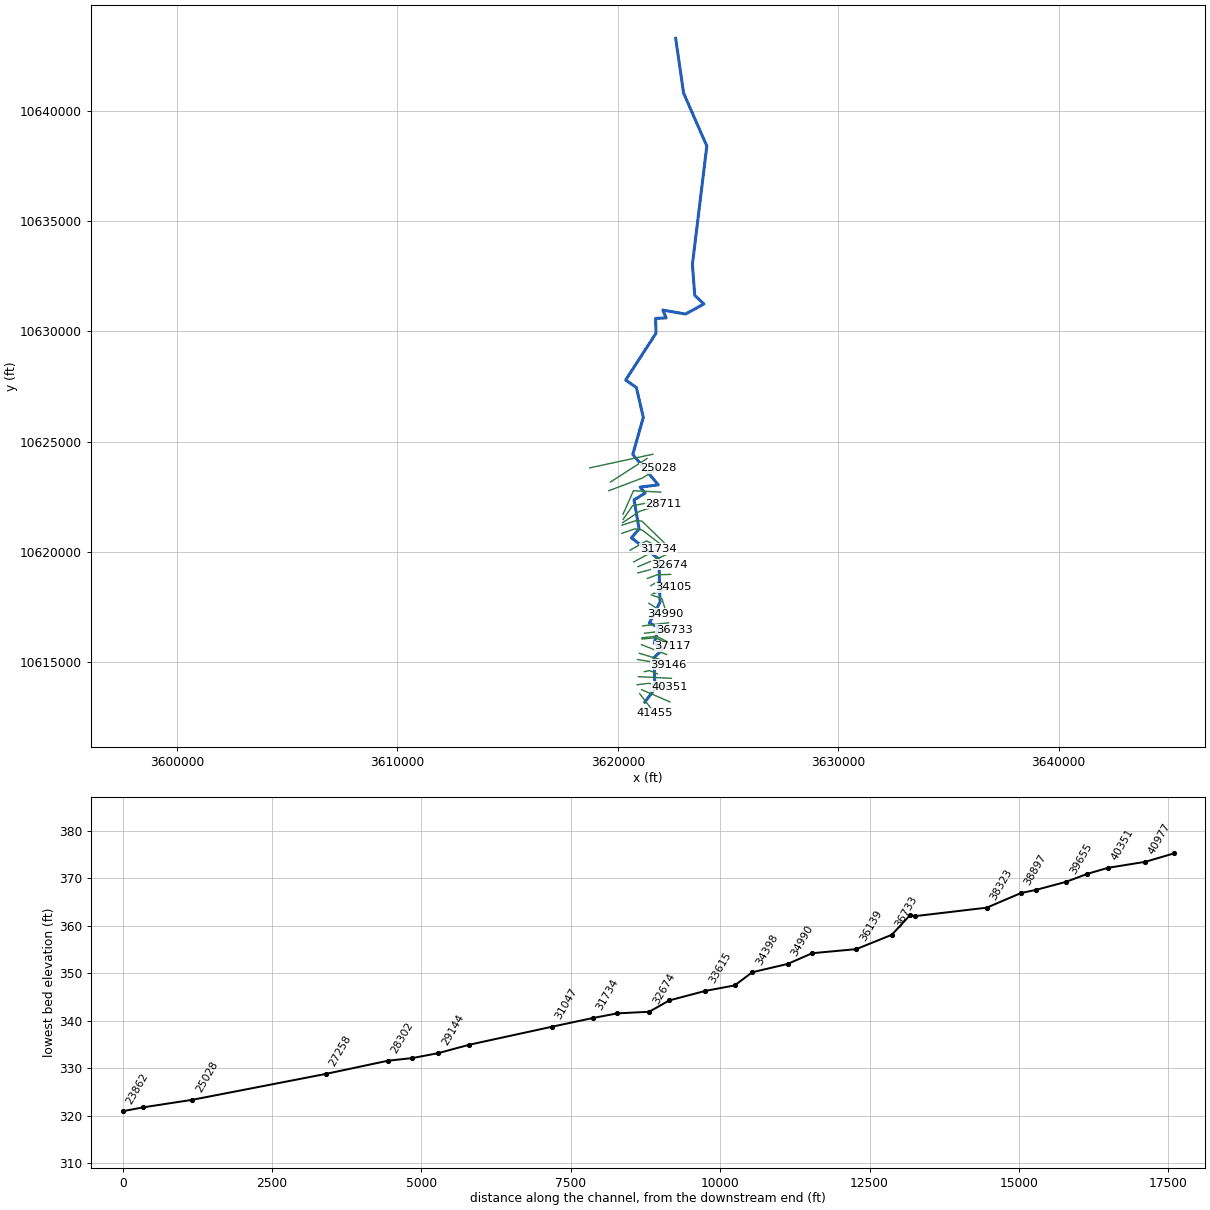
--- LITTLE BROWN CREEK.prj (project) ---

Proj Title=LITTLE BROWN CREEK Base Level Engineering
Current Plan=p01
Default Exp/Contr=0.3,0.1
English Units
Geom File=g01
Flow File=f01
Plan File=p01
Y Axis Title=Elevation
X Axis Title(PF)=Main Channel Distance
X Axis Title(XS)=Station
BEGIN DESCRIPTION:
LITTLE BROWN CREEK
END DESCRIPTION:
DSS Export Rating Curves= 0
DSS Export Rating Curve Sorted= 0
DSS Export Volume Flow Curves= 0
DXF OffsetX= 0
DXF OffsetY= 0
DXF ScaleX= 1
DXF ScaleY= 10

--- LITTLE BROWN CREEK.p01 (plan) ---

Plan Title=Multiple Run
Short Identifier=Multiple
Geom File=g01
Flow File=f01
Subcritical Flow
K Sum by GR= 0
Std Step Tol= 0.01
Critical Tol= 0.01
Num of Std Step Trials= 20
Max Error Tol= 0.3
Flow Tol Ratio= 0.001
Split Flow NTrial= 30
Split Flow Tol= 0.02
Split Flow Ratio= 0.02
Log Output Level= 0
Friction Slope Method= 1
Unsteady Friction Slope Method= 2
Unsteady Bridges Friction Slope Method= 1
Parabolic Critical Depth
Global Vel Dist=  1 , 1 , 1
Global Log Level= 0
CheckData=True
Encroach Param= -1, 0, 0, 0
BEGIN DESCRIPTION:
Multiple Run
END DESCRIPTION:

--- LITTLE BROWN CREEK.f01 (steady flow) ---

Flow Title=Multiple
Program Version=4.10
Number of Profiles= 7
Profile Names=10-year,25-year,50-year,1pct_min,100-year,1pct_plu,500-year
River Rch & RM=LITTLE BROWN CRE,Reach-1         ,41455
    2158    3065    3840    3509    4746    6419    7228
River Rch & RM=LITTLE BROWN CRE,Reach-1         ,40977
    2285    3232    4035    3671    4965    6715    7496
River Rch & RM=LITTLE BROWN CRE,Reach-1         ,34105
    3442    4962    6276    5776    7812   10565   12072
River Rch & RM=LITTLE BROWN CRE,Reach-1         ,32674
    3442    4962    6276    5776    7812   10565   12072
River Rch & RM=LITTLE BROWN CRE,Reach-1         ,28711
    4143    6000    7610    7017    9490   12834   14725
River Rch & RM=LITTLE BROWN CRE,Reach-1         ,25028
    5156    7510    9563    8845   11962   16177   18673
River Rch & RM=LITTLE BROWN CRE,Reach-1         ,23862
    5156    7510    9563    8845   11962   16177   18673
River Rch & RM=LITTLE BROWN CRE,Reach-1         ,17784
    5203    7568    9626    8893   12026   16264   18728
River Rch & RM=LITTLE BROWN CRE,Reach-1         ,14992
    6078    8872   11311   10467   14155   19143   22116
River Rch & RM=LITTLE BROWN CRE,Reach-1         ,12842
    6078    8872   11311   10467   14155   19143   22116
River Rch & RM=LITTLE BROWN CRE,Reach-1         ,8092
    7192   10556   13509   12542   16962   22939   26678
River Rch & RM=LITTLE BROWN CRE,Reach-1         ,6432
    7192   10556   13509   12542   16962   22939   26678
River Rch & RM=LITTLE BROWN CRE,Reach-1         ,4315
    7192   10556   13509   12542   16962   22939   26678
Boundary for River Rch & Prof#=LITTLE BROWN CRE,Reach-1         , 1
Up Type= 0
Dn Type= 3
Dn Slope=0.0016
Boundary for River Rch & Prof#=LITTLE BROWN CRE,Reach-1         , 2
Up Type= 0
Dn Type= 3
Dn Slope=0.0016
Boundary for River Rch & Prof#=LITTLE BROWN CRE,Reach-1         , 3
Up Type= 0
Dn Type= 3
Dn Slope=0.0016
Boundary for River Rch & Prof#=LITTLE BROWN CRE,Reach-1         , 4
Up Type= 0
Dn Type= 3
Dn Slope=0.0016
Boundary for River Rch & Prof#=LITTLE BROWN CRE,Reach-1         , 5
Up Type= 0
Dn Type= 3
Dn Slope=0.0016
Boundary for River Rch & Prof#=LITTLE BROWN CRE,Reach-1         , 6
Up Type= 0
Dn Type= 3
Dn Slope=0.0016
Boundary for River Rch & Prof#=LITTLE BROWN CRE,Reach-1         , 7
Up Type= 0
Dn Type= 3
Dn Slope=0.0016
DSS Import GetInterval= 0
DSS Import GetPeak= 0
DSS Import FillOption= 0

--- LITTLE BROWN CREEK.g01 (geometry) ---

Geom Title=Existing Conditions
Program Version=4.10

River Reach=LITTLE BROWN CRE,Reach-1
Reach XY= 30
       3621228.5       10613180.        3621693.       10613792.
        3621635.       10615185.        3622061.       10615588.
       3621653.5       10615855.        3621854.       10616573.
      3621432.25       10616762.      3621918.25       10617716.
       3621865.5       10619661.      3620620.75       10620633.
      3620968.25       10621036.      3620740.75       10622354.
        3621238.       10622661.       3621013.5       10622933.
        3621840.       10623035.      3620681.75       10624416.
        3621159.       10626095.        3620846.       10627449.
        3620359.       10627790.        3621734.       10629913.
      3621717.25       10630587.      3622194.25       10630608.
      3622042.75       10630964.      3623072.75       10630784.
       3623909.5       10631239.      3623491.75       10631636.
      3623387.25       10633043.       3624040.5       10638405.
      3622986.25       10640810.      3622627.25       10643292.

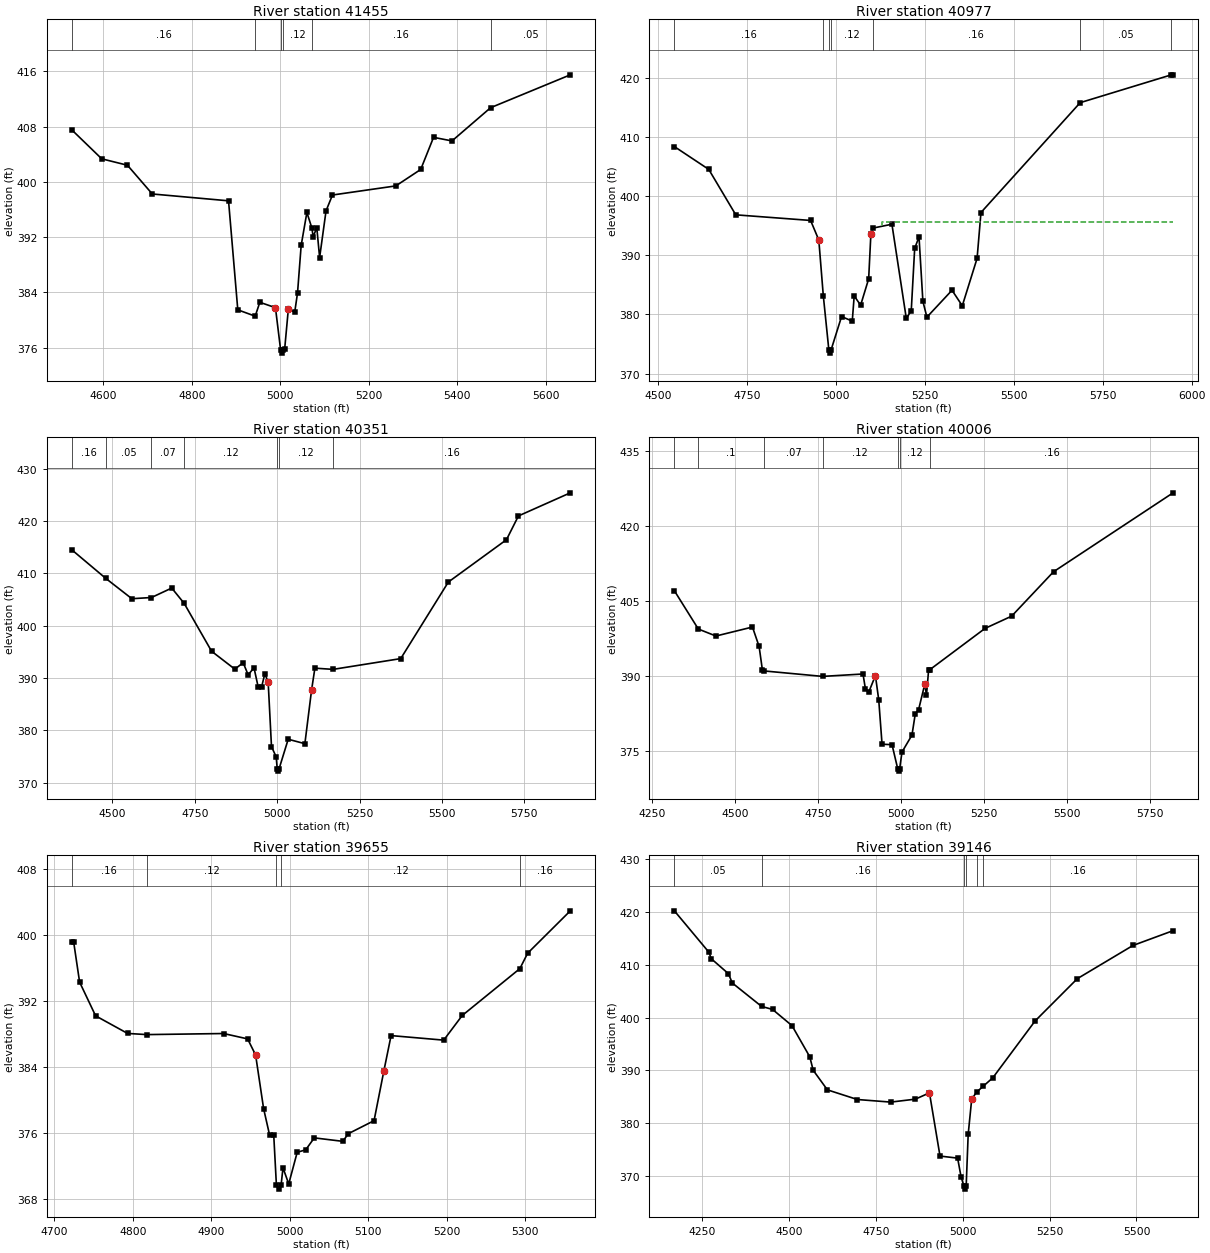
Type RM Length L Ch R = 1 ,41455   ,478,478,478
BEGIN DESCRIPTION:
LITTLE BROWN CREEK 67.0
END DESCRIPTION:
XS GIS Cut Line= 2
      3620995.29     10613562.04      3621681.05     10612667.94
#Sta/Elev= 30
  4528.3  407.57  4596.4  403.35  4654.5  402.42  4710.6  398.26  4882.9  397.27
  4903.8  381.49  4943.1  380.57  4953.6  382.58  4988.9   381.8  5000.5  375.72
  5003.2  375.22  5006.5  375.72  5009.8  375.87    5018  381.59  5032.5  381.18
  5038.8  383.95    5047  390.82  5059.9  395.58  5071.1  393.35  5074.1  392.07
  5082.3  393.38  5088.7  389.06  5103.2  395.82  5117.7  398.11  5260.9  399.43
  5317.1  401.81  5346.1  406.46  5387.8  405.94    5475  410.75  5655.1  415.51
#Mann= 6 ,-1 , 0
  4528.3     .16       0  4943.1     .12       0  5000.5     .07       0
  5006.5     .12       0  5071.1     .16       0    5475     .05       0
Bank Sta=4988.9,5018
XS Rating Curve= 0 ,0
Exp/Cntr=0.3,0.1

Type RM Length L Ch R = 1 ,40977   ,626,626,626
BEGIN DESCRIPTION:
LITTLE BROWN CREEK 66.0
END DESCRIPTION:
XS GIS Cut Line= 2
       3621077.8      10613744.3      3622365.69     10613189.25
#Sta/Elev= 30
  4545.3   408.4    4642  404.54    4718  396.85  4928.4   395.9  4951.5  392.59
  4964.1   383.2  4979.8  373.95  4982.6  373.45  4985.8  373.95  5015.5  379.64
  5045.6  378.86    5051  383.13  5069.1  381.56  5091.7  386.02    5098  393.67
  5102.5  394.59  5157.1  395.26  5197.6  379.31  5211.5  380.65  5221.1  391.16
  5233.3  393.13  5244.2  382.21  5255.5  379.54  5326.1  384.09    5355  381.46
  5396.6  389.48  5407.5  397.24  5686.5  415.83    5943  420.54  5947.7  420.49
#Mann= 7 ,-1 , 0
  4545.3     .16       0  4964.1     .12       0  4979.8     .07       0
  4985.8     .12       0  5102.5     .16       0  5686.5     .05       0
    5943     .08       0
#XS Ineff= 2 , 0
                            5130          395.68
Permanent Ineff=
       F       F
Bank Sta=4951.5,5098
XS Rating Curve= 0 ,0
Exp/Cntr=0.3,0.1

Type RM Length L Ch R = 1 ,40351   ,345,345,345
BEGIN DESCRIPTION:
LITTLE BROWN CREEK 65.0
END DESCRIPTION:
XS GIS Cut Line= 3
      3620878.12     10613965.67      3621394.61     10614030.78
      3622375.07      10613874.6
#Sta/Elev= 30
  4376.3  414.56  4479.8  409.07  4559.2  405.17  4618.7   405.4  4680.2  407.21
  4717.9  404.28  4801.1  395.12  4871.7  391.69  4896.9  392.93  4912.1   390.6
  4929.8  391.96  4942.4  388.31  4952.6  388.23  4962.7  390.79  4972.8  389.23
  4982.9  376.86  4997.1  374.91  5000.2  372.68    5003  372.18  5006.2  372.68
  5033.6  378.28  5084.2  377.43  5104.5  387.68  5114.6  391.88  5169.8  391.65
  5375.1  393.71  5519.6  408.36    5696  416.46  5732.3  421.01  5889.7  425.43
#Mann= 7 ,-1 , 0
  4376.3     .16       0  4479.8     .05       0  4618.7     .07       0
  4717.9     .12       0  5000.2     .07       0  5006.2     .12       0
  5169.8     .16       0
Bank Sta=4972.8,5104.5
XS Rating Curve= 0 ,0
Exp/Cntr=0.3,0.1

Type RM Length L Ch R = 1 ,40006   ,351,351,351
BEGIN DESCRIPTION:
LITTLE BROWN CREEK 64.0
END DESCRIPTION:
XS GIS Cut Line= 2
      3620934.52      10614334.6      3622435.39     10614256.52
#Sta/Elev= 30
    4316  407.02  4388.2  399.35  4441.3  397.95  4551.4  399.75  4571.4  395.86
  4581.4  391.12  4586.7  390.96  4762.9  389.87  4884.5  390.35  4891.9  387.32
  4901.9  386.74  4921.9  390.03  4931.9  385.19  4941.9   376.3    4972   376.2
    4989  371.41  4991.8  370.91    4995  371.41    5002  374.73  5032.1  378.13
  5042.1  382.41  5052.1  383.23  5070.8  388.35  5075.8  386.09  5082.1  391.05
  5086.2  391.23  5252.4  399.48  5332.5  401.93  5458.6  410.81  5818.9  426.61
#Mann= 7 ,-1 , 0
    4316     .16       0  4388.2      .1       0  4586.7     .07       0
  4762.9     .12       0    4989     .07       0    4995     .12       0
  5086.2     .16       0
Bank Sta=4921.9,5070.8
XS Rating Curve= 0 ,0
Exp/Cntr=0.3,0.1

Type RM Length L Ch R = 1 ,39655   ,509,509,509
BEGIN DESCRIPTION:
LITTLE BROWN CREEK 63.0
END DESCRIPTION:
XS GIS Cut Line= 3
      3621199.57     10614560.18      3621449.61     10614610.19
      3621799.62     10614460.18
#Sta/Elev= 30
    4722  399.16  4724.6  399.16  4732.2  394.29  4752.6  390.21  4793.4  388.08
    4818  387.94  4915.8  388.07  4946.4  387.42  4956.6  385.47  4966.8  378.98
  4974.4   375.8  4979.7   375.8  4983.1  369.75  4985.8  369.25  4989.1  369.75
  4991.5  371.83  4998.8  369.88  5009.6   373.7  5020.5  374.01  5031.4  375.45
  5067.7  375.03  5074.9  375.96  5107.6  377.53  5120.2  383.59  5129.3  387.82
  5196.4  387.27    5220  390.25  5293.5  395.92  5303.4  397.78  5357.8  402.91
#Mann= 5 ,-1 , 0
    4722     .16       0    4818     .12       0  4983.1     .07       0
  4989.1     .12       0  5293.5     .16       0
Bank Sta=4956.6,5120.2
XS Rating Curve= 0 ,0
Exp/Cntr=0.3,0.1

Type RM Length L Ch R = 1 ,39146   ,249,249,249
BEGIN DESCRIPTION:
LITTLE BROWN CREEK 62.0
END DESCRIPTION:
XS GIS Cut Line= 2
      3620894.95     10615111.22       3622311.6     10614876.85
#Sta/Elev= 30
  4169.4  420.23    4269  412.38  4275.5  411.17    4325  408.33  4336.3  406.56
  4420.5  402.13  4452.1  401.56  4508.1  398.49  4559.3  392.59  4569.1  390.04
    4610  386.33  4696.3   384.5  4792.4  384.01  4863.4  384.57  4903.9  385.76
  4934.3  373.79    4985   373.4  4995.1  369.81  5003.6  368.03  5006.3  367.53
  5009.6  368.03  5015.4   377.9  5025.5  384.56  5039.5  385.89  5059.5  387.06
  5086.4  388.62    5208  399.37  5329.6  407.38  5489.8  413.67  5605.3  416.47
#Mann= 6 ,-1 , 0
  4169.4     .05       0  4420.5     .16       0  5003.6     .07       0
  5009.6     .16       0  5039.5     .12       0  5059.5     .16       0
Bank Sta=4903.9,5025.5
XS Rating Curve= 0 ,0
Exp/Cntr=0.3,0.1

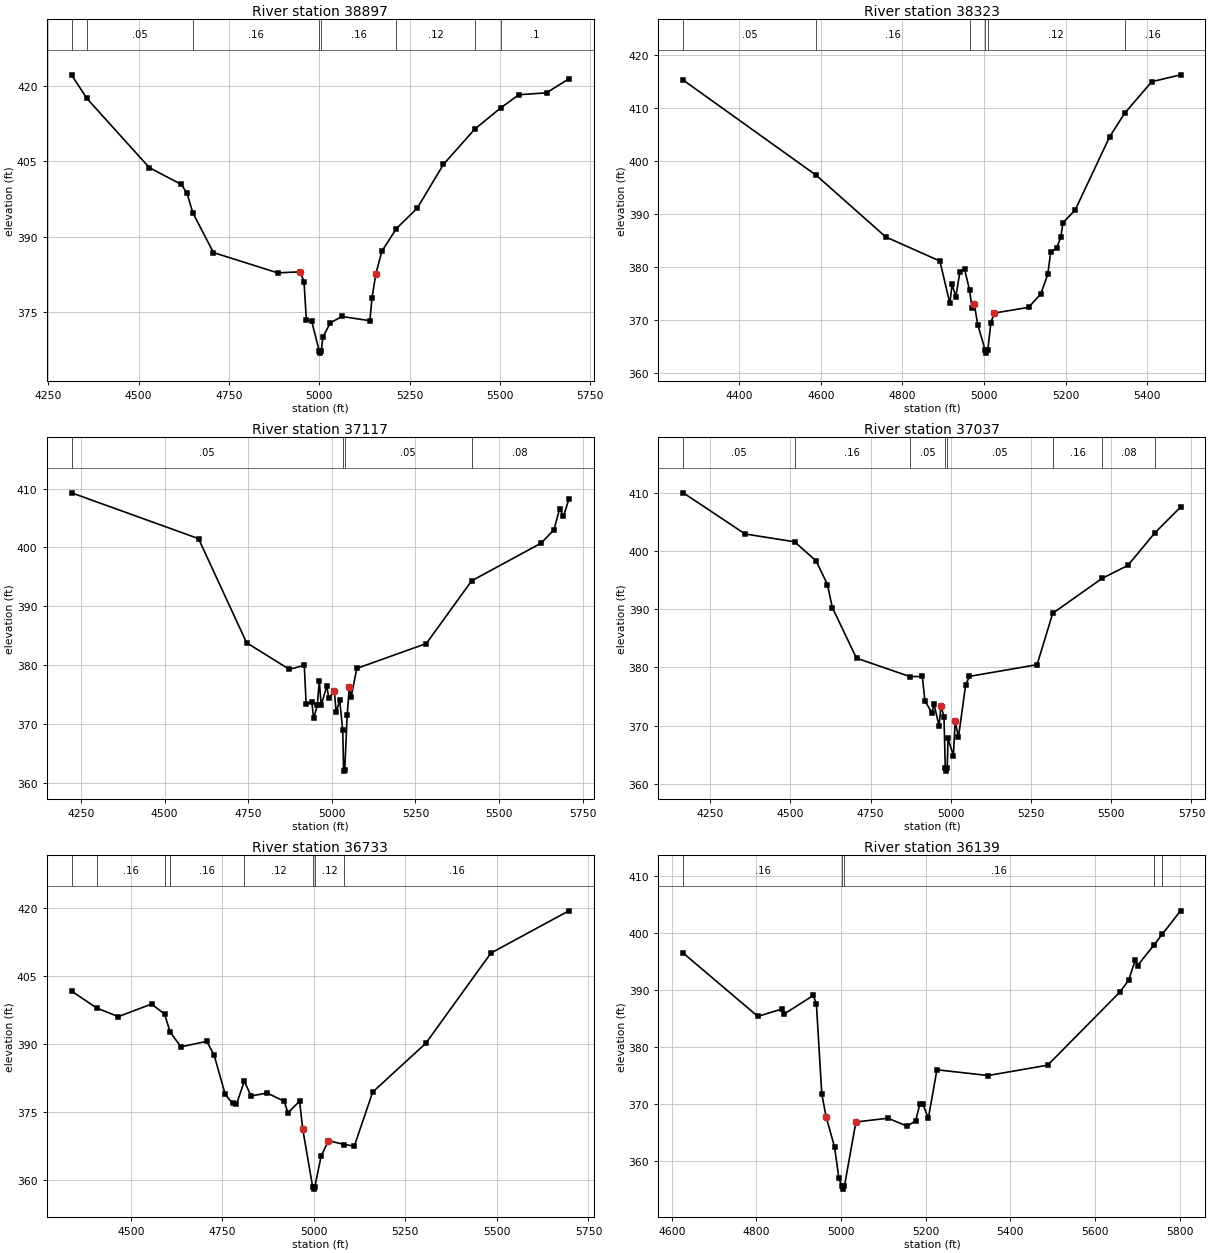
Type RM Length L Ch R = 1 ,38897   ,574,574,574
BEGIN DESCRIPTION:
LITTLE BROWN CREEK 61.0
END DESCRIPTION:
XS GIS Cut Line= 2
       3620983.5     10615392.47      3622301.23     10614996.63
#Sta/Elev= 30
  4314.4  422.24  4356.9  417.54  4529.6  403.78  4618.1  400.44    4634  398.68
  4649.7  394.83  4707.1  386.88  4884.6  382.85  4947.3  383.05  4957.7     381
  4964.1  373.43  4978.6   373.3  4999.4  367.38  5002.2  366.88  5005.4  367.38
  5009.9  370.09  5030.2  372.87  5062.1  374.17  5139.8  373.33  5145.7  377.85
  5156.1  382.57  5172.8  387.12    5213  391.64    5271  395.73  5343.3  404.42
  5429.3  411.39  5502.3  415.69    5552  418.28  5628.5  418.66  5690.3  421.45
#Mann= 8 ,-1 , 0
  4314.4     .16       0  4356.9     .05       0  4649.7     .16       0
  4999.4     .07       0  5005.4     .16       0    5213     .12       0
  5429.3     .16       0  5502.3      .1       0
Bank Sta=4947.3,5156.1
XS Rating Curve= 0 ,0
Exp/Cntr=0.3,0.1

Type RM Length L Ch R = 1 ,38323   ,1206,1206,1206
BEGIN DESCRIPTION:
LITTLE BROWN CREEK 60.0
END DESCRIPTION:
XS GIS Cut Line= 2
      3621077.22     10615783.11      3622212.66     10615340.39
#Sta/Elev= 30
  4262.9  415.25  4588.9  397.31  4759.2  385.69  4891.8  381.15  4916.3  373.18
  4921.7  376.73  4930.9  374.43  4940.8  379.04  4952.4   379.6  4964.6  375.65
  4970.7   372.3  4976.1  373.02  4984.6  369.16  5003.1  364.29  5005.8  363.79
  5009.1  364.29  5016.8  369.53  5025.1  371.34  5109.3  372.42  5139.1  374.94
  5156.3  378.68  5163.6  382.93  5177.8  383.52  5188.1  385.67  5193.5  388.38
  5223.4  390.77  5307.6  404.54  5344.4  408.98  5410.9  414.95  5481.6  416.25
#Mann= 6 ,-1 , 0
  4262.9     .05       0  4588.9     .16       0  4964.6     .12       0
  5003.1     .07       0  5009.1     .12       0  5344.4     .16       0
Bank Sta=4976.1,5025.1
XS Rating Curve= 0 ,0
Exp/Cntr=0.3,0.1

Type RM Length L Ch R = 1 ,37117   ,80,80,80
BEGIN DESCRIPTION:
Mapping XS 55edcaac
END DESCRIPTION:
XS GIS Cut Line= 3
       3621098.1     10616043.51      3621723.09     10616095.59
      3622493.96     10615715.37
#Sta/Elev= 30
  4221.9  409.29  4601.5  401.51  4745.2  383.82  4872.8   379.3  4917.7  379.97
  4923.3   373.4  4940.2  373.74  4945.7  370.95  4956.7  373.18  4962.6  377.38
  4968.2   373.2  4985.1  376.45  4990.7  374.42  5007.5  375.58  5013.1  371.99
  5023.6  374.03  5032.6  369.01  5035.3     362  5038.6   362.2  5045.9  371.52
  5052.4  376.33    5058  374.68  5074.9  379.46  5282.5  383.68  5418.1  394.34
  5625.7  400.74  5664.3  403.02  5681.1  406.62  5692.6  405.29  5708.6  408.22
#Mann= 4 ,-1 , 0
  4221.9     .05       0  5032.6     .04       0  5038.6     .05       0
  5418.1     .08       0
Bank Sta=5007.5,5052.4
XS Rating Curve= 0 ,0
Exp/Cntr=0.3,0.1

Type RM Length L Ch R = 1 ,37037   ,304,304,304
BEGIN DESCRIPTION:
LITTLE BROWN CREEK 58.0
END DESCRIPTION:
XS GIS Cut Line= 3
      3621098.09     10616095.59      3621754.34     10616168.51
      3622545.29     10615762.63
#Sta/Elev= 30
  4166.6     410  4359.3  402.93  4513.7  401.58  4580.7  398.29  4615.8  394.24
    4631  390.29  4706.4  381.59  4872.5  378.43  4911.5  378.44  4919.4  374.31
  4941.6  372.11  4947.3   373.8  4963.8  369.92  4969.4  373.38  4978.9  371.51
    4983  362.68  4985.8  362.18    4989  362.68  4991.6   367.8  5008.2  364.82
  5013.8  370.85  5023.9  367.96  5046.4     377  5058.2  378.46  5268.9  380.47
  5317.7  389.31  5471.3  395.29  5551.8  397.53  5636.2  403.14  5715.9  407.54
#Mann= 8 ,-1 , 0
  4166.6     .05       0  4513.7     .16       0  4872.5     .05       0
    4983     .04       0    4989     .05       0  5317.7     .16       0
  5471.3     .08       0  5636.2     .12       0
Bank Sta=4969.4,5013.8
XS Rating Curve= 0 ,0
Exp/Cntr=0.3,0.1

Type RM Length L Ch R = 1 ,36733   ,594,594,594
BEGIN DESCRIPTION:
LITTLE BROWN CREEK 57.0
END DESCRIPTION:
XS GIS Cut Line= 2
      3621212.63     10616303.92      3622561.61     10616460.17
#Sta/Elev= 30
  4338.4  401.66  4407.3  397.93  4466.2  396.04  4556.8  398.81  4592.5  396.62
  4607.5  392.65  4637.4  389.39  4707.8  390.61    4728   387.5  4758.2   378.9
  4778.3  376.94  4788.7   376.7  4810.1  381.83  4828.6  378.58  4872.4  379.22
  4919.2  377.41  4929.3  374.83  4961.2  377.46  4969.6  371.34  4996.8  358.57
  4999.5  358.07  5002.8  358.57  5019.9  365.31  5039.9  368.74  5083.1  367.89
  5110.5  367.53  5160.8  379.44  5306.1   390.2  5483.6  410.03  5696.4  419.33
#Mann= 8 ,-1 , 0
  4338.4     .07       0  4407.3     .16       0  4592.5     .05       0
  4607.5     .16       0  4810.1     .12       0  4996.8     .07       0
  5002.8     .12       0  5083.1     .16       0
Bank Sta=4969.6,5039.9
XS Rating Curve= 0 ,0
Exp/Cntr=0.3,0.1

Type RM Length L Ch R = 1 ,36139   ,738,738,738
BEGIN DESCRIPTION:
LITTLE BROWN CREEK 56.0
END DESCRIPTION:
XS GIS Cut Line= 2
      3621134.56     10616637.26      3622301.22     10616777.88
#Sta/Elev= 30
  4627.2  396.49  4803.5  385.38  4859.8  386.66  4864.8  385.76  4934.5  389.05
  4941.8  387.59  4954.6  371.78  4964.7  367.77  4984.8  362.43  4994.9     357
    5002  355.56  5004.7  355.06    5008  355.56  5035.2  366.84    5111  367.51
    5156  366.12  5176.2  367.03  5186.3  369.97  5193.1  370.05  5206.4  367.49
  5226.6  376.01  5347.4     375  5488.4  376.82  5659.7  389.71  5679.8  391.75
  5695.6  395.34  5700.6   394.3  5739.2  397.88  5759.1   399.8  5802.3  403.91
#Mann= 5 ,-1 , 0
  4627.2     .16       0    5002     .07       0    5008     .16       0
  5739.2     .05       0  5759.1     .16       0
Bank Sta=4964.7,5035.2
XS Rating Curve= 0 ,0
Exp/Cntr=0.3,0.1

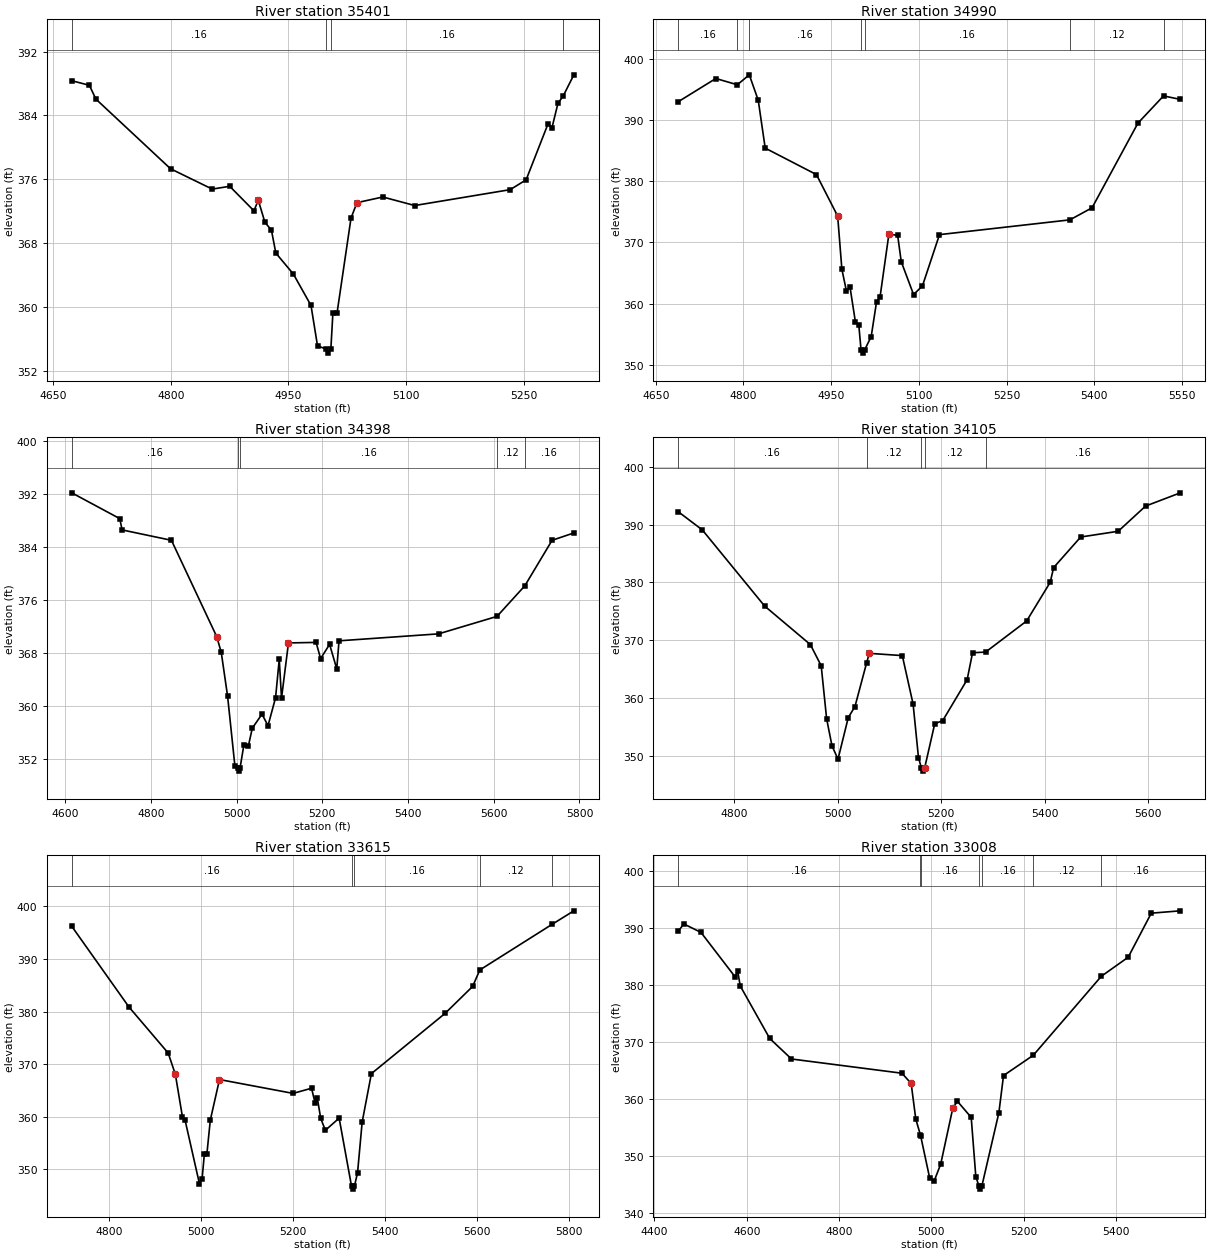
Type RM Length L Ch R = 1 ,35401   ,411,411,411
BEGIN DESCRIPTION:
LITTLE BROWN CREEK 55.0
END DESCRIPTION:
XS GIS Cut Line= 3
      3621399.61     10617010.19      3621699.61     10617160.19
      3621999.57      10617110.2
#Sta/Elev= 30
    4674  388.36  4696.4  387.79  4704.7  386.06  4799.8  377.32  4852.9  374.77
  4875.2  375.12    4906  372.05  4911.6  373.37    4920   370.6  4928.3  369.63
  4933.9  366.75  4956.3  364.11  4978.7  360.18    4987  355.12    4998   354.7
  5000.8   354.2    5004   354.7  5006.6  359.24  5011.9  359.24  5029.7  371.15
  5037.3  373.07  5070.2  373.78  5110.8  372.71  5232.4   374.7  5252.7  375.93
  5280.6  382.95  5285.7  382.49  5293.3  385.54  5299.8  386.42  5313.5   389.1
#Mann= 4 ,-1 , 0
    4674     .16       0    4998     .07       0    5004     .16       0
  5299.8     .05       0
Bank Sta=4911.6,5037.3
XS Rating Curve= 0 ,0
Exp/Cntr=0.3,0.1

Type RM Length L Ch R = 1 ,34990   ,592,592,592
BEGIN DESCRIPTION:
LITTLE BROWN CREEK 54.0
END DESCRIPTION:
XS GIS Cut Line= 2
      3621414.89     10617662.89      3622135.01      10617195.5
#Sta/Elev= 30
  4688.5  392.97  4752.8  396.76  4789.5  395.74    4810  397.36  4825.3  393.21
  4837.2   385.4  4924.8  381.08  4961.1  374.31  4968.3  365.63  4976.2  362.03
  4982.2  362.73  4991.4  357.05  4997.3  356.46  5001.1  352.44  5003.8  351.94
  5007.1  352.44  5018.4  354.63  5027.6  360.31  5033.6  361.12  5048.7  371.36
  5063.7  371.16  5069.8  366.87  5090.9   361.5  5106.1  362.92  5135.2  371.28
  5358.2  373.69  5396.1  375.66  5474.5  389.47  5518.3  393.92    5547  393.35
#Mann= 7 ,-1 , 0
  4688.5     .16       0  4789.5     .12       0    4810     .16       0
  5001.1     .07       0  5007.1     .16       0  5358.2     .12       0
  5518.3     .16       0
Bank Sta=4961.1,5048.7
XS Rating Curve= 0 ,0
Exp/Cntr=0.3,0.1

Type RM Length L Ch R = 1 ,34398   ,293,293,293
BEGIN DESCRIPTION:
LITTLE BROWN CREEK 53.0
END DESCRIPTION:
XS GIS Cut Line= 3
      3621519.09     10618041.34      3622001.74     10617878.14
      3622199.65      10617246.2
#Sta/Elev= 30
  4615.2  392.22  4727.3  388.32  4732.6  386.62  4847.8  385.05  4953.5   370.5
  4964.1  368.11  4978.9  361.48  4995.8  351.02    5002  350.69  5004.8  350.19
    5008  350.69  5016.9  354.16  5027.4     354  5036.5  356.68  5059.1  358.79
  5073.2  357.06  5090.8  361.28  5099.4  367.07  5104.7  361.21  5120.9  369.55
  5185.4  369.63  5195.9  367.19  5216.9  369.33  5233.6  365.63  5238.9  369.87
  5471.2  370.92  5607.6  373.56  5672.5  378.18  5736.1  385.05  5786.9  386.16
#Mann= 5 ,-1 , 0
  4615.2     .16       0    5002     .07       0    5008     .16       0
  5607.6     .12       0  5672.5     .16       0
Bank Sta=4953.5,5120.9
XS Rating Curve= 0 ,0
Exp/Cntr=0.3,0.1

Type RM Length L Ch R = 1 ,34105   ,490,490,490
BEGIN DESCRIPTION:
LITTLE BROWN CREEK 52.0
END DESCRIPTION:
XS GIS Cut Line= 2
      3621595.13     10618096.63      3622523.93     10618378.74
#Sta/Elev= 30
  4691.6  392.22  4738.1  389.08  4858.5  375.94  4947.1  369.27    4968  365.61
  4978.5  356.46  4988.9  351.77  5000.5  349.49  5020.3  356.66  5033.3  358.58
  5055.6  366.05    5061  367.76  5124.8  367.37  5145.7  358.99  5156.1  349.73
  5161.9  347.92  5164.6  347.42  5167.9  347.92  5187.5   355.6    5203  356.15
  5250.2  363.22  5260.6  367.86  5285.9  367.98  5365.2  373.35  5410.7  380.02
  5417.4  382.57  5469.7  387.85  5542.2  388.84  5595.1  393.19  5662.3  395.48
#Mann= 5 ,-1 , 0
  4691.6     .16       0  5055.6     .12       0  5161.9     .07       0
  5167.9     .12       0  5285.9     .16       0
Bank Sta=5061,5167.9
XS Rating Curve= 0 ,0
Exp/Cntr=0.3,0.1

Type RM Length L Ch R = 1 ,33615   ,607,607,607
BEGIN DESCRIPTION:
LITTLE BROWN CREEK 51.0
END DESCRIPTION:
XS GIS Cut Line= 3
       3621499.6     10618460.19      3621749.61     10618610.19
       3622549.6     10618560.19
#Sta/Elev= 30
  4718.3  396.18  4842.7  380.87  4928.2  372.11  4943.8  368.08  4959.3  359.96
  4965.1  359.32  4996.2  347.32  5002.1  348.28  5006.9  352.88  5012.4  352.88
  5019.9  359.37  5039.9  367.08  5200.2  364.45  5240.3  365.43  5247.8  362.72
  5252.8   363.6  5260.3   359.7  5270.4  357.44  5300.4  359.75  5327.5  346.77
  5330.2  346.27  5333.5  346.77  5340.5  349.38  5350.5  358.98  5370.6   368.2
  5530.9  379.63    5591  384.76  5606.7  387.89  5764.5  396.58  5811.4  399.12
#Mann= 5 ,-1 , 0
  4718.3     .16       0  5327.5     .07       0  5333.5     .16       0
  5606.7     .12       0  5764.5     .16       0
Bank Sta=4943.8,5039.9
XS Rating Curve= 0 ,0
Exp/Cntr=0.3,0.1

Type RM Length L Ch R = 1 ,33008   ,334,334,334
BEGIN DESCRIPTION:
LITTLE BROWN CREEK 50.0
END DESCRIPTION:
XS GIS Cut Line= 3
      3621343.41     10618791.08      3621781.77     10618951.67
      3622402.45     10618973.37
#Sta/Elev= 30
  4451.6  389.37  4463.5  390.68  4500.8   389.2  4574.9   381.4  4580.2  382.49
    4586  379.81  4649.9  370.62    4697  367.03  4936.3  364.54  4956.3  362.75
  4966.3  356.52  4976.4  353.72  4976.8   353.6  4996.3  346.23  5006.3  345.71
  5020.3  348.62  5046.4  358.38  5056.4  359.64  5086.4  356.81  5096.4  346.44
  5103.4  344.75  5106.1  344.25  5109.4  344.75  5146.4  357.64  5156.4  364.13
  5220.9  367.68  5368.3  381.51  5426.6  384.85  5476.6  392.56  5539.5  392.97
#Mann= 7 ,-1 , 0
  4451.6     .16       0  4976.4     .12       0  4976.8     .16       0
  5103.4     .07       0  5109.4     .16       0  5220.9     .12       0
  5368.3     .16       0
Bank Sta=4956.3,5046.4
XS Rating Curve= 0 ,0
Exp/Cntr=0.3,0.1

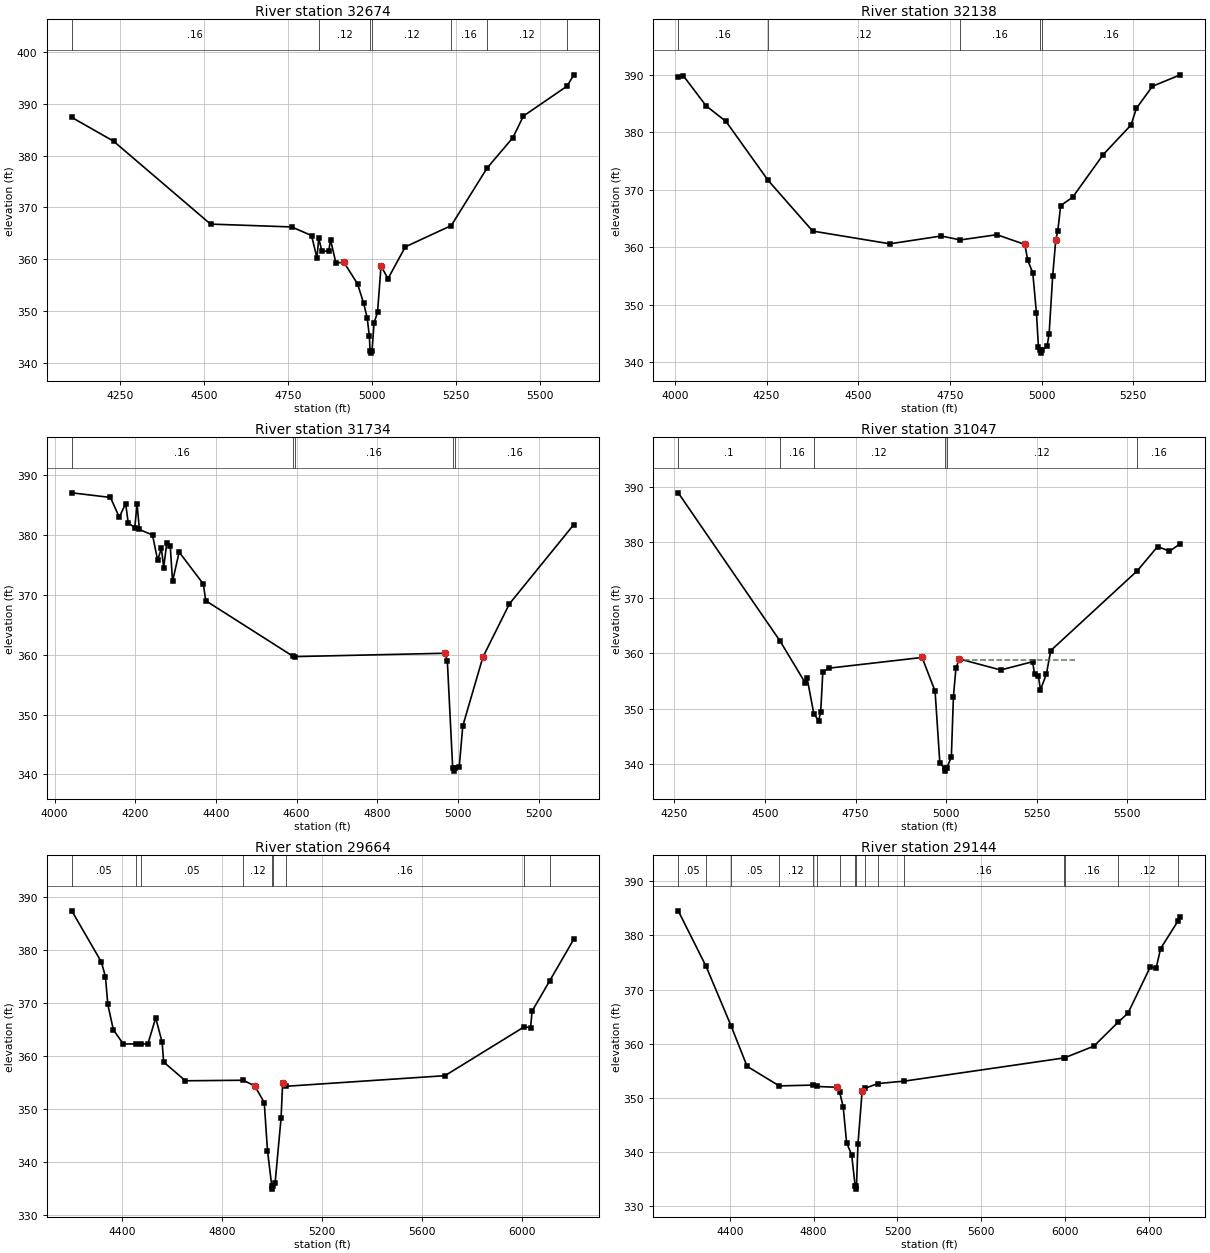
Type RM Length L Ch R = 1 ,32674   ,536,536,536
BEGIN DESCRIPTION:
LITTLE BROWN CREEK 49.0
END DESCRIPTION:
XS GIS Cut Line= 2
       3620909.4     10619038.48      3622354.69     10619420.42
#Sta/Elev= 30
    4106   387.4  4230.3  382.81  4519.2  366.79  4760.8  366.24  4819.9  364.58
  4836.1  360.25  4841.3  364.07  4850.9  361.51  4871.2  361.62  4876.4  363.76
  4892.3  359.32  4916.6  359.38  4956.9  355.24  4975.1  351.49  4985.4  348.74
    4992   345.2  4994.1  342.37  4996.9  341.87  5000.1  342.37  5006.1  347.73
  5016.4  349.75  5026.8   358.7  5047.5  356.25  5099.2   362.4  5235.8   366.5
  5342.5  377.61  5419.3  383.48  5450.8  387.66  5580.3  393.42  5600.9  395.62
#Mann= 7 ,-1 , 0
    4106     .16       0  4841.3     .12       0  4994.1     .07       0
  5000.1     .12       0  5235.8     .16       0  5342.5     .12       0
  5580.3     .16       0
Bank Sta=4916.6,5026.8
XS Rating Curve= 0 ,0
Exp/Cntr=0.3,0.1

Type RM Length L Ch R = 1 ,32138   ,404,404,404
BEGIN DESCRIPTION:
LITTLE BROWN CREEK 48.0
END DESCRIPTION:
XS GIS Cut Line= 2
      3620919.59      10619320.6      3622179.98     10619857.04
#Sta/Elev= 30
  4008.9  389.72  4022.9  389.86    4085  384.62  4139.3   381.9  4253.8  371.66
  4375.6   362.8  4586.4  360.58  4726.2  361.94  4778.8  361.26  4878.4  362.17
  4954.4  360.47  4962.6   357.7  4976.2  355.52  4986.3  348.44  4991.7  342.52
  4994.9  342.03  4997.7  341.53  5000.9  342.03  5015.3  342.77  5020.8  344.92
  5030.5  354.98    5039  361.32  5044.4  362.79  5052.3  367.25  5084.9  368.69
    5168   376.1  5244.4   381.3  5258.7  384.17  5302.5  388.03  5378.7  390.03
#Mann= 5 ,-1 , 0
  4008.9     .16       0  4253.8     .12       0  4778.8     .16       0
  4994.9     .07       0  5000.9     .16       0
Bank Sta=4954.4,5039
XS Rating Curve= 0 ,0
Exp/Cntr=0.3,0.1

Type RM Length L Ch R = 1 ,31734   ,687,687,687
BEGIN DESCRIPTION:
LITTLE BROWN CREEK 47.0
END DESCRIPTION:
XS GIS Cut Line= 2
      3620721.69     10619539.36      3621820.58     10620122.65
#Sta/Elev= 30
  4042.7  387.02  4138.5  386.25  4160.5  382.95  4176.2  385.23  4182.5  382.04
  4198.8  381.18  4204.5  385.19  4210.2   380.9  4242.8  379.98  4255.5  375.76
  4264.8  377.79  4270.4  374.53  4278.1  378.62  4286.8  378.06  4292.4  372.22
  4308.7  377.13  4368.7   371.8  4374.7  369.01    4590  359.77  4596.4  359.68
  4967.7  360.24  4973.3  358.98  4986.6  341.06  4989.4  340.56  4992.6  341.06
  5002.7  341.19  5011.6  348.09  5061.3  359.57  5127.2  368.49  5286.8  381.73
#Mann= 5 ,-1 , 0
  4042.7     .16       0    4590      .1       0  4596.4     .16       0
  4986.6     .07       0  4992.6     .16       0
Bank Sta=4967.7,5061.3
XS Rating Curve= 0 ,0
Exp/Cntr=0.3,0.1

Type RM Length L Ch R = 1 ,31047   ,1383,1383,1383
BEGIN DESCRIPTION:
LITTLE BROWN CREEK 46.0
END DESCRIPTION:
XS GIS Cut Line= 3
      3620562.45     10620071.18      3621307.28     10620493.08
      3621775.35     10620243.45
#Sta/Elev= 30
  4260.4  388.91  4541.4   362.2  4610.6   354.7  4616.3  355.48  4634.9  349.05
  4647.9  347.83  4653.8  349.38  4659.6  356.52  4675.5  357.28  4933.8  359.22
  4969.7  353.14  4982.8  340.21  4995.7  339.22  4998.4  338.72  5001.7  339.22
  5014.6  341.28  5020.3  352.13  5027.2  357.24  5036.2  358.96  5150.9  356.96
  5238.8  358.45  5244.4   356.3    5255   355.9  5260.7  353.37    5277  356.21
  5289.1  360.46  5528.2  374.86  5584.4  379.23    5617  378.38  5646.9  379.73
#Mann= 6 ,-1 , 0
  4260.4      .1       0  4541.4     .16       0  4634.9     .12       0
  4995.7     .07       0  5001.7     .12       0  5528.2     .16       0
#XS Ineff= 2 ,-1
 4559.09 4926.36  358.84    5050 5360.91  358.76
Permanent Ineff=
       F       F
Bank Sta=4933.8,5036.2
XS Rating Curve= 0 ,0
Exp/Cntr=0.3,0.1

Type RM Length L Ch R = 1 ,29664   ,520,520,520
BEGIN DESCRIPTION:
LITTLE BROWN CREEK 45.0
END DESCRIPTION:
XS GIS Cut Line= 4
      3620192.19     10620836.41      3620775.49     10621039.52
      3621103.62     10620987.44      3621945.99     10620342.66
#Sta/Elev= 30
  4198.2  387.33  4316.7   377.7  4333.1  374.92  4342.5  369.71  4364.9  364.91
  4404.6  362.26  4455.1  362.27  4475.1  362.23  4503.2   362.3  4534.3  367.18
  4560.1  362.58  4566.1  358.86  4653.4  355.33  4884.9  355.43  4931.4  354.35
    4969  351.24    4982  342.19  4999.3  335.43    5002  334.93  5005.3  335.43
  5012.4  336.02  5036.3  348.27  5042.8  354.92  5057.6   354.3  5692.8  356.29
  6010.2  365.49  6035.5  365.34  6041.8  368.45  6112.4  374.17  6208.9     382
#Mann= 9 ,-1 , 0
  4198.2     .05       0  4455.1     .15       0  4475.1     .05       0
  4884.9     .12       0  4999.3     .07       0  5005.3     .12       0
  5057.6     .16       0  6010.2     .12       0  6112.4     .16       0
Bank Sta=4931.4,5042.8
XS Rating Curve= 0 ,0
Exp/Cntr=0.3,0.1

Type RM Length L Ch R = 1 ,29144   ,433,433,433
BEGIN DESCRIPTION:
LITTLE BROWN CREEK 44.0
END DESCRIPTION:
XS GIS Cut Line= 4
      3620197.36     10621206.19      3620853.62     10621419.73
      3621098.41     10621388.48       3622145.3     10620372.84
#Sta/Elev= 30
  4154.1  384.52  4286.8  374.29  4407.1  363.21  4482.5  355.83  4635.9  352.21
  4796.3  352.36    4818   352.1  4910.8  351.96    4924  351.06    4941   348.4
  4957.6  341.69  4981.3  339.53  4998.5  333.66  5001.2  333.16  5004.5  333.66
  5011.6  341.47  5031.7  351.33  5042.9  351.74  5107.6  352.65  5232.8  353.09
    5993  357.36  6000.4  357.44  6137.4  359.55  6253.5  363.99    6300  365.64
    6406  374.14  6434.3  373.94  6455.6  377.56  6539.1  382.67  6549.6  383.46
#Mann= 16 ,-1 , 0
  4154.1     .05       0  4286.8     .16       0  4407.1     .05       0
  4635.9     .12       0  4796.3     .05       0    4818     .16       0
    4924     .12       0  4998.5     .07       0  5004.5     .12       0
  5042.9     .16       0  5107.6     .12       0  5232.8     .16       0
    5993     .12       0  6000.4     .16       0  6253.5     .12       0
  6539.1     .16       0
Bank Sta=4910.8,5031.7
XS Rating Curve= 0 ,0
Exp/Cntr=0.3,0.1

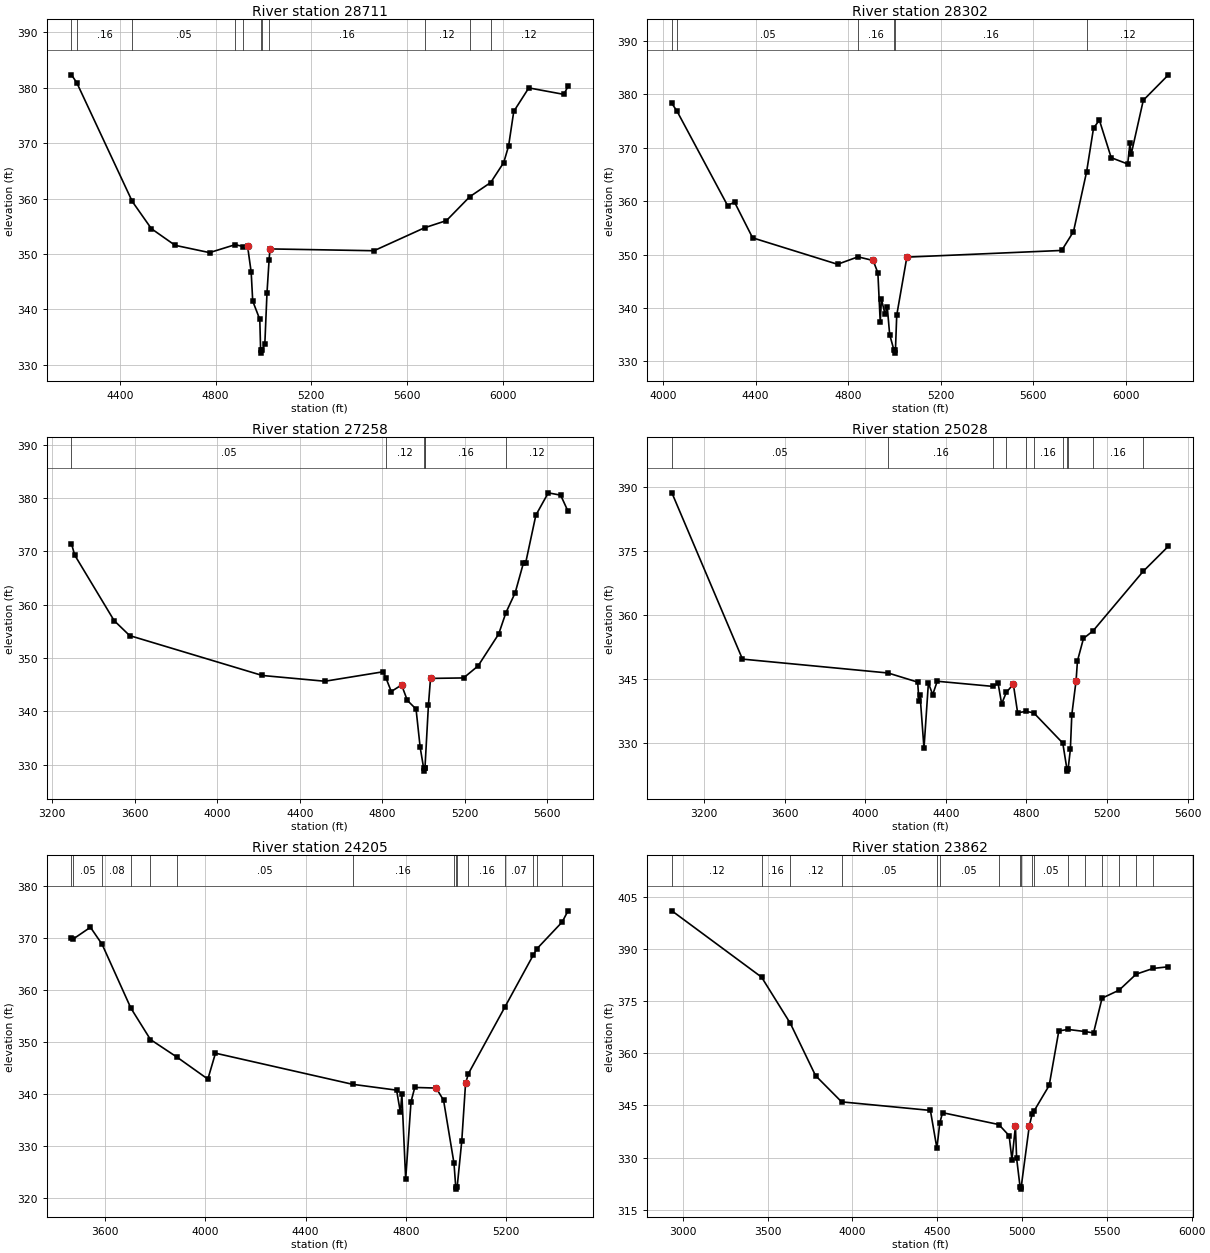
Type RM Length L Ch R = 1 ,28711   ,409,409,409
BEGIN DESCRIPTION:
LITTLE BROWN CREEK 42.0
END DESCRIPTION:
XS GIS Cut Line= 3
      3620219.93      10621317.3      3620997.71     10621838.14
      3622086.26     10622177.87
#Sta/Elev= 30
  4197.3  382.35  4219.5  380.91  4451.5  359.49  4531.4  354.58  4630.5  351.58
  4774.6  350.26  4882.1   351.7  4915.6  351.35  4933.7  351.39  4948.7  346.73
  4955.1  341.52  4984.7  338.21  4988.2  332.62    4991  332.12  4994.2  332.62
  5005.8   333.8  5014.8  342.99  5023.6  348.95  5027.3  350.93  5462.2   350.6
    5674  354.75  5765.2  356.04  5862.7  360.35  5950.3  362.91  6004.8  366.52
  6025.1  369.51  6046.7  375.74  6109.6  379.99  6256.3  378.82  6273.7  380.29
#Mann= 11 ,-1 , 0
  4197.3     .05       0  4219.5     .16       0  4451.5     .05       0
  4882.1     .16       0  4915.6     .12       0  4988.2     .07       0
  4994.2     .12       0  5023.6     .16       0    5674     .12       0
  5862.7     .16       0  5950.3     .12       0
Bank Sta=4933.7,5027.3
XS Rating Curve= 0 ,0
Exp/Cntr=0.3,0.1

Type RM Length L Ch R = 1 ,28302   ,1044,1044,1044
BEGIN DESCRIPTION:
LITTLE BROWN CREEK 41.0
END DESCRIPTION:
XS GIS Cut Line= 3
      3620240.77     10621463.13      3620671.32     10622088.14
      3622032.43     10622345.08
#Sta/Elev= 30
  4038.8  378.29  4060.8  376.86  4279.4  359.18  4309.2  359.83  4387.4  353.14
  4754.2  348.19  4842.5  349.58  4907.9   348.9  4928.3  346.58  4938.5  337.38
  4943.6  341.65  4958.8  338.93    4969  340.15  4979.2  335.03  4998.1  332.06
  5000.8  331.56  5004.1  332.06  5009.7  338.65  5053.5  349.53  5722.1  350.78
    5773  354.31  5829.5  365.48  5859.7  373.72  5884.9  375.15  5935.8  368.14
    6007  366.96  6016.9  370.91    6022  368.76  6074.4  378.89  6182.9  383.65
#Mann= 6 ,-1 , 0
  4038.8     .16       0  4060.8     .05       0  4842.5     .16       0
  4998.1     .07       0  5004.1     .16       0  5829.5     .12       0
Bank Sta=4907.9,5053.5
XS Rating Curve= 0 ,0
Exp/Cntr=0.3,0.1

Type RM Length L Ch R = 1 ,27258   ,2230,2230,2230
BEGIN DESCRIPTION:
LITTLE BROWN CREEK 40.0
END DESCRIPTION:
XS GIS Cut Line= 3
      3620240.75     10621706.15      3620712.99     10622768.69
      3621955.36     10622706.23
#Sta/Elev= 30
  3293.8  371.43  3309.2   369.3  3500.5     357  3575.7  354.19  4218.6  346.71
  4522.3  345.63  4803.6   347.4  4817.2  346.31  4843.7   343.7  4893.7  344.93
  4921.7  342.03  4963.8  340.41  4983.8  333.22  5000.9  329.27  5003.6  328.77
  5006.9  329.27    5007  329.34  5023.9  341.19  5033.9  346.16  5194.1  346.25
  5264.2  348.49  5364.3  354.48  5399.2  358.47  5444.4  362.24  5484.5  367.84
  5494.5  367.72  5544.5  376.77  5604.6  380.97  5664.7  380.53  5700.5   377.5
#Mann= 6 ,-1 , 0
  3293.8     .05       0  4817.2     .12       0  5000.9     .07       0
  5006.9     .12       0    5007     .16       0  5399.2     .12       0
Bank Sta=4893.7,5033.9
XS Rating Curve= 0 ,0
Exp/Cntr=0.3,0.1

Type RM Length L Ch R = 1 ,25028   ,823,823,823
BEGIN DESCRIPTION:
LITTLE BROWN CREEK 38.0
END DESCRIPTION:
XS GIS Cut Line= 3
      3619597.88     10622770.76      3621113.49     10623343.67
      3621835.09     10623784.93
#Sta/Elev= 30
  3038.8   388.7  3389.4  349.64  4112.7  346.38  4259.4  344.24  4266.1  339.88
  4271.4  341.15  4290.9  328.71  4312.8  344.01  4334.2  341.29  4356.6  344.44
    4634  343.23  4659.1  343.92  4676.6  339.13  4699.6  341.81  4734.7  343.75
    4756  337.03  4797.6  337.37  4836.1  337.02  4980.2  329.92  5000.7  323.83
  5003.4  323.33  5006.7  323.83  5017.9  328.42    5025  336.57  5046.3  344.58
  5053.1  349.22    5083   354.5  5130.4  356.26    5379  370.23  5504.9  376.17
#Mann= 11 ,-1 , 0
  3038.8     .05       0  4112.7     .16       0    4634     .05       0
  4699.6     .16       0  4797.6     .12       0  4836.1     .16       0
  4980.2     .12       0  5000.7     .07       0  5006.7     .12       0
  5130.4     .16       0    5379     .12       0
Bank Sta=4734.7,5046.3
XS Rating Curve= 0 ,0
Exp/Cntr=0.3,0.1

Type RM Length L Ch R = 1 ,24205   ,343,343,343
BEGIN DESCRIPTION:
LITTLE BROWN CREEK 35.0
END DESCRIPTION:
XS GIS Cut Line= 2
      3619665.58     10623161.38       3621332.2     10624234.27
#Sta/Elev= 30
  3465.2  369.95  3472.8   369.8  3540.8  372.03  3587.5  368.75  3702.3   356.5
  3780.4  350.47  3886.6  347.08  4009.6  342.87  4039.9  347.85  4587.4  341.87
  4762.9  340.75  4778.1  336.48    4784  339.92  4799.2  323.62  4820.4   338.5
  4835.5  341.27  4920.9  341.15  4950.4  338.82    4992  326.73  4998.9  322.24
  5001.7  321.74  5004.9  322.24  5023.1  330.99  5038.2  342.03  5049.7  343.93
  5194.3  356.63    5309  366.74  5323.4  367.92  5423.8  373.04  5447.3  375.19
#Mann= 15 ,-1 , 0
  3465.2     .16       0  3472.8     .05       0  3587.5     .08       0
  3702.3     .05       0  3780.4     .08       0  3886.6     .05       0
  4587.4     .16       0    4992     .12       0  4998.9     .07       0
  5004.9     .12       0  5049.7     .16       0  5194.3     .07       0
    5309     .16       0  5323.4     .12       0  5423.8     .05       0
Bank Sta=4920.9,5038.2
XS Rating Curve= 0 ,0
Exp/Cntr=0.3,0.1

Type RM Length L Ch R = 1 ,23862   ,751,751,751
BEGIN DESCRIPTION:
LITTLE BROWN CREEK 34.0
END DESCRIPTION:
XS GIS Cut Line= 2
      3618730.07     10623805.69      3621591.17     10624423.75
#Sta/Elev= 30
  2935.9   400.9  3464.6  381.84  3634.1  368.57  3782.7  353.55  3936.3     346
  4459.8  343.54  4498.2  332.68  4515.1  339.89  4531.4  342.89  4863.2  339.48
    4924  336.28  4940.6  329.37  4961.1  338.95  4968.1   329.8  4988.8  321.42
  4991.5  320.92  4994.8  321.42  5042.9  339.12  5059.5  342.44  5070.4  343.34
    5160  350.71  5216.9  366.39  5271.1  366.81  5371.5  366.21  5421.5  365.81
  5471.8   375.8  5572.2   378.1  5672.6  382.69  5772.9  384.35    5863  384.82
#Mann= 17 ,-1 , 0
  2935.9     .12       0  3464.6     .16       0  3634.1     .12       0
  3936.3     .05       0  4498.2     .16       0  4515.1     .05       0
  4863.2     .16       0  4988.8     .07       0  4994.8     .16       0
  5059.5     .12       0  5070.4     .05       0  5271.1      .1       0
  5371.5     .15       0  5471.8     .12       0  5572.2     .05       0
  5672.6      .1       0  5772.9     .15       0
Bank Sta=4961.1,5042.9
XS Rating Curve= 0 ,0
Exp/Cntr=0.3,0.1