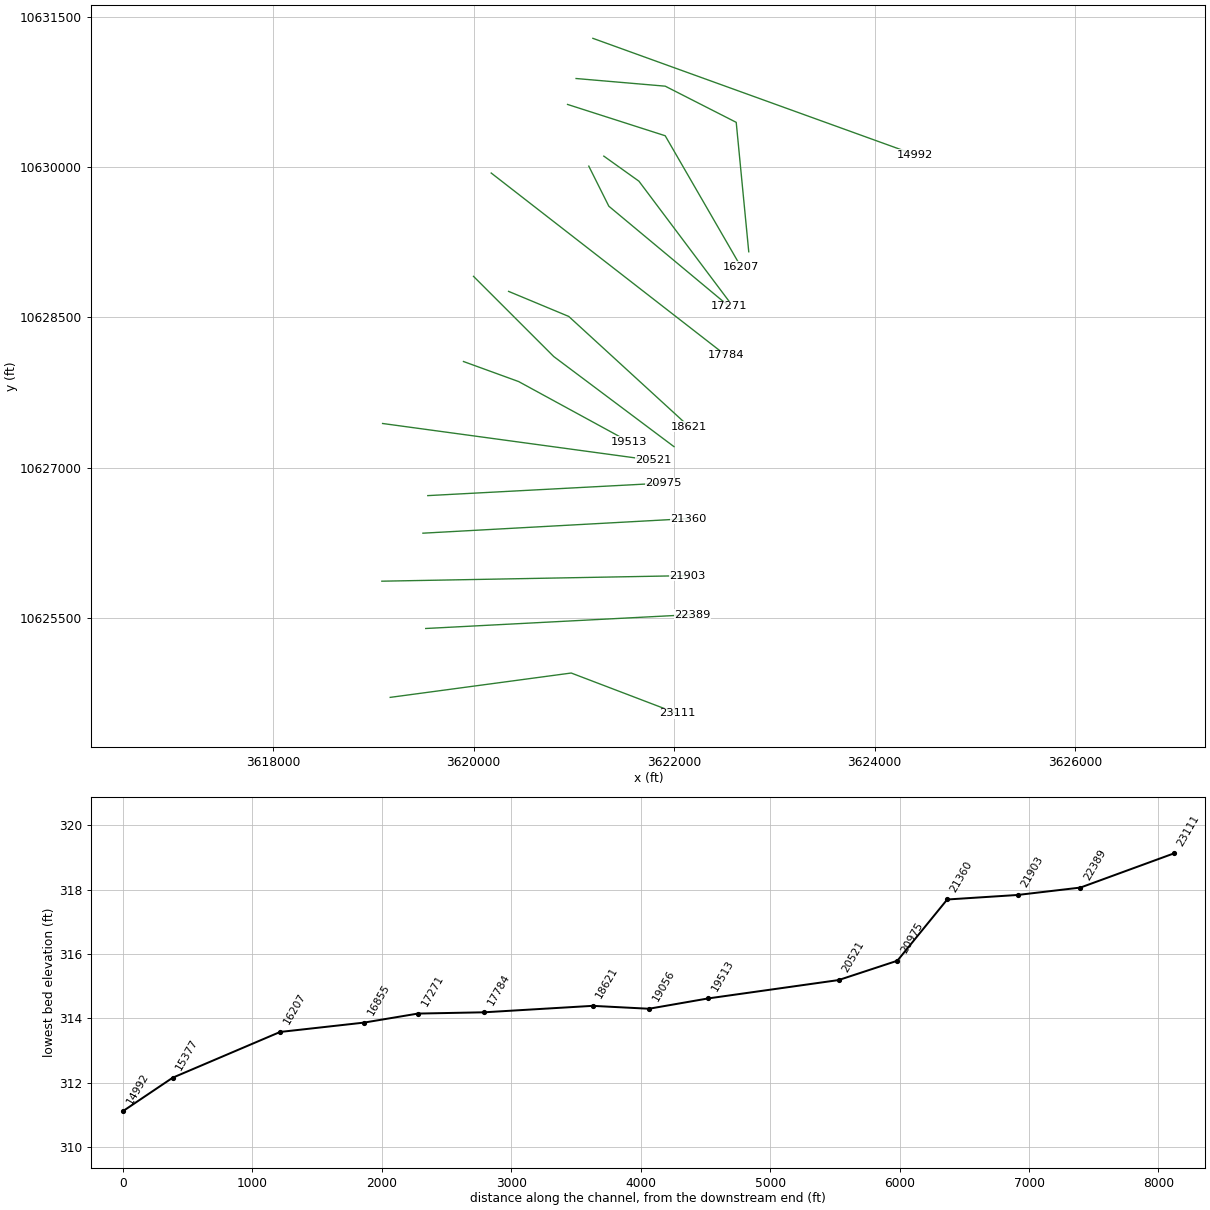
HEC-RAS study LITTLE BROWN CREEK.prj: LITTLE BROWN CREEK Base Level Engineering

--- LITTLE BROWN CREEK.g01 (geometry) --- (continued)

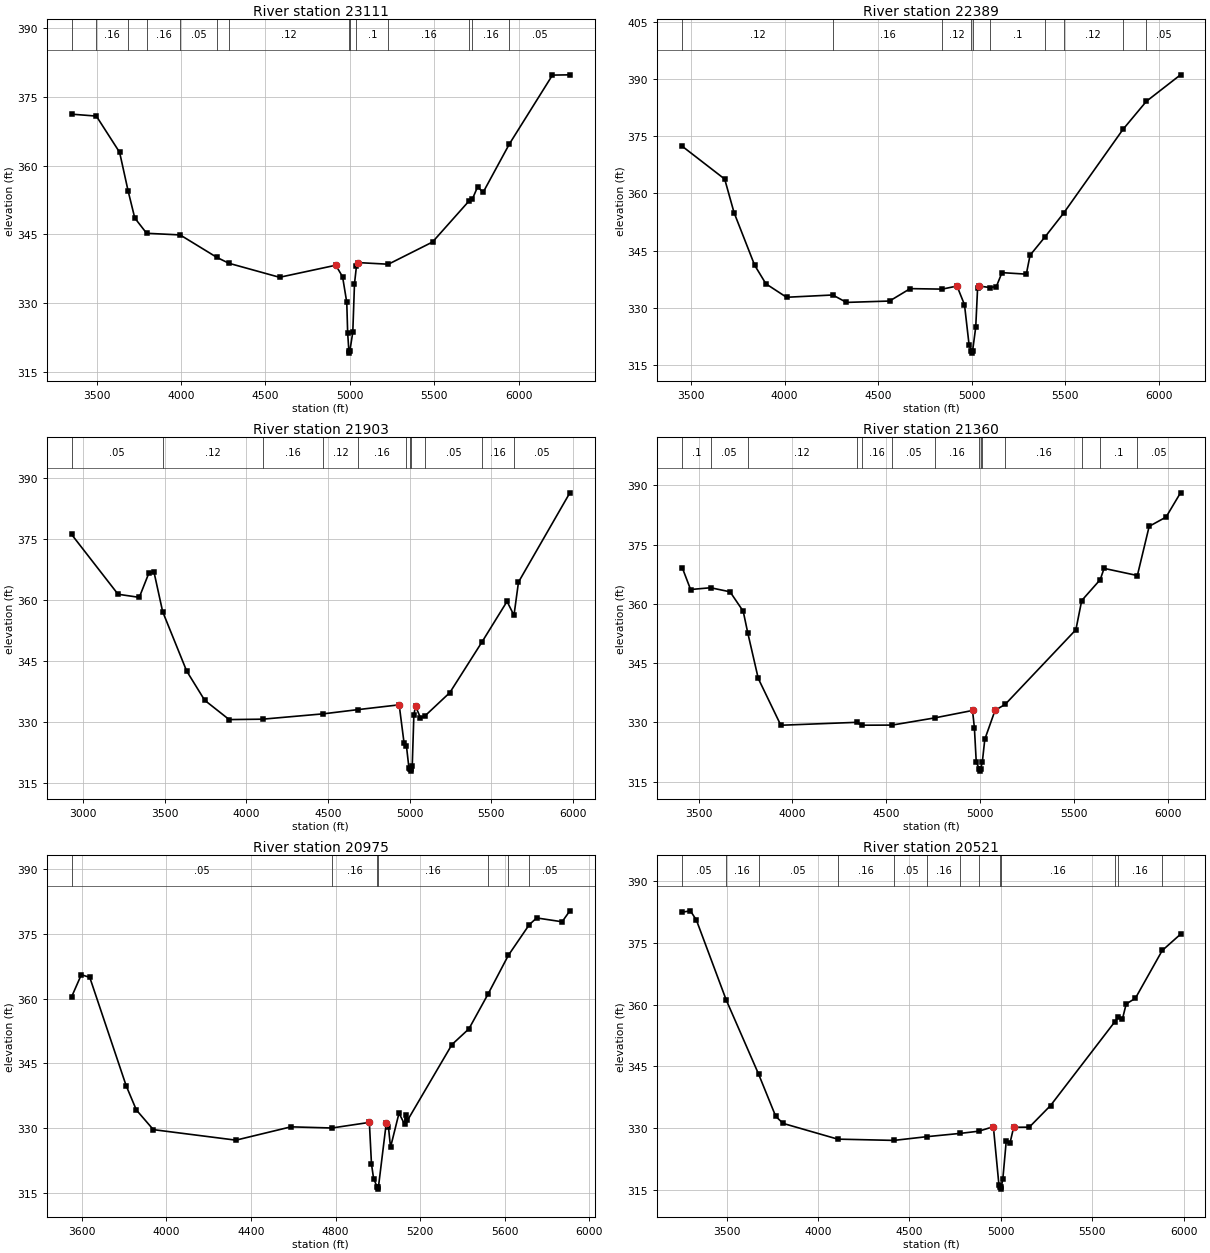
Type RM Length L Ch R = 1 ,23111   ,722,722,722
BEGIN DESCRIPTION:
LITTLE BROWN CREEK 32.0
END DESCRIPTION:
XS GIS Cut Line= 3
      3619168.68     10624707.77      3620974.27     10624950.83
      3622029.86     10624548.04
#Sta/Elev= 30
  3351.3  371.24    3498  370.82  3635.8  362.92  3686.3  354.48  3725.6  348.59
  3795.9  345.26  3994.5   344.9    4212     340  4283.1  338.72  4583.2  335.66
  4916.2  338.29  4956.6  335.78  4981.4   330.2  4986.8  323.46  4993.9  319.62
  4996.7  319.12  4999.9  319.62  5017.1  323.67  5027.2  334.25    5039  338.16
  5047.4  338.87  5227.8  338.51  5489.3  343.35  5705.8  352.31  5724.6  352.65
  5756.9  355.42    5789  354.17  5944.6  364.73  6199.9  379.76    6303  379.82
#Mann= 14 ,-1 , 0
  3351.3      .1       0    3498     .16       0  3686.3     .12       0
  3795.9     .16       0  3994.5     .05       0    4212     .16       0
  4283.1     .12       0  4993.9     .07       0  4999.9     .12       0
    5039      .1       0  5227.8     .16       0  5705.8     .05       0
  5724.6     .16       0  5944.6     .05       0
Bank Sta=4916.2,5047.4
XS Rating Curve= 0 ,0
Exp/Cntr=0.3,0.1

Type RM Length L Ch R = 1 ,22389   ,486,486,486
BEGIN DESCRIPTION:
LITTLE BROWN CREEK 31.0
END DESCRIPTION:
XS GIS Cut Line= 2
      3619522.91     10625395.27      3622182.59     10625534.16
#Sta/Elev= 30
  3453.1  372.39  3680.1  363.77  3730.2  354.96  3840.3  341.14  3900.4  336.27
  4010.6  332.73  4257.7  333.33    4331  331.38  4561.3  331.74  4671.5     335
  4842.9  334.87  4921.8  335.68  4961.8  330.78  4986.2   320.3  4998.9  318.56
  5001.7  318.06  5004.9  318.56  5021.9  324.86  5031.9  335.17    5042  335.67
  5096.7  335.29  5132.1  335.53  5162.1   339.2  5292.3   338.8  5312.3  343.77
  5393.3  348.65  5492.1  354.85  5808.8  376.81  5934.2   384.2  6116.4  391.15
#Mann= 10 ,-1 , 0
  3453.1     .12       0  4257.7     .16       0  4842.9     .12       0
  4998.9     .07       0  5004.9     .12       0  5096.7      .1       0
  5393.3     .07       0  5492.1     .12       0  5808.8     .16       0
  5934.2     .05       0
Bank Sta=4921.8,5042
XS Rating Curve= 0 ,0
Exp/Cntr=0.3,0.1

Type RM Length L Ch R = 1 ,21903   ,543,543,543
BEGIN DESCRIPTION:
LITTLE BROWN CREEK 30.0
END DESCRIPTION:
XS GIS Cut Line= 2
      3619085.39     10625867.49      3622133.98     10625923.05
#Sta/Elev= 30
  2931.2   376.2  3215.5  361.45  3345.5  360.68  3405.5  366.81  3435.5  366.92
  3488.5  357.16  3635.5  342.51  3745.6  335.31  3895.6  330.54  4099.9  330.64
  4471.8  331.96  4683.9     333  4935.8  334.18  4965.8  324.74  4980.5  323.95
  4995.4  318.68  5002.8  318.33  5005.5  317.83  5008.8  318.33  5015.8  319.15
  5025.8  331.74  5035.8  333.85  5065.8  331.01  5092.7  331.41  5245.8  337.19
  5443.2  349.72  5595.9  359.68  5638.3  356.24  5665.9  364.44  5980.3  386.46
#Mann= 11 ,-1 , 0
  2931.2     .05       0  3488.5     .12       0  4099.9     .16       0
  4471.8     .12       0  4683.9     .16       0  4980.5     .12       0
  5002.8     .07       0  5008.8     .12       0  5092.7     .05       0
  5443.2     .16       0  5638.3     .05       0
Bank Sta=4935.8,5035.8
XS Rating Curve= 0 ,0
Exp/Cntr=0.3,0.1

Type RM Length L Ch R = 1 ,21360   ,385,385,385
BEGIN DESCRIPTION:
LITTLE BROWN CREEK 29.0
END DESCRIPTION:
XS GIS Cut Line= 2
      3619495.05     10626346.66      3622146.25     10626492.41
#Sta/Elev= 30
    3413   369.2  3457.6  363.65  3564.4   364.1  3667.9  363.07    3738  358.15
  3762.1  352.72  3818.2  341.14  3938.4   329.3  4342.4  330.04    4369  329.31
  4531.2  329.34  4758.3  331.16  4959.9  333.04  4969.9  328.69  4979.9  319.92
    4997  318.19  4999.7  317.69    5003  318.19  5012.1  319.96  5025.4  325.75
  5080.1  333.08  5133.7  334.57  5510.7  353.47  5541.7  360.85  5640.5  366.15
  5660.9     369  5838.3  367.19  5901.3  379.64  5991.4  381.99  6068.2  388.12
#Mann= 14 ,-1 , 0
    3413      .1       0  3564.4     .05       0  3762.1     .12       0
  4342.4     .05       0    4369     .16       0  4531.2     .05       0
  4758.3     .16       0    4997     .07       0    5003     .16       0
  5012.1     .12       0  5133.7     .16       0  5541.7     .05       0
  5640.5      .1       0  5838.3     .05       0
Bank Sta=4959.9,5080.1
XS Rating Curve= 0 ,0
Exp/Cntr=0.3,0.1

Type RM Length L Ch R = 1 ,20975   ,454,454,454
BEGIN DESCRIPTION:
LITTLE BROWN CREEK 28.0
END DESCRIPTION:
XS GIS Cut Line= 2
       3619543.7     10626721.66      3621896.28     10626846.58
#Sta/Elev= 30
  3551.9  360.38  3597.9  365.53  3637.9  364.91  3810.1  339.76  3858.2  334.15
  3938.4  329.59  4328.9  327.15  4589.3  330.24  4782.4  329.97  4959.8  331.27
  4969.8  321.64  4979.8  318.25  4996.8  316.29  4999.6  315.79  5002.8  316.29
  5039.9  331.18  5049.9  330.29  5059.9  325.49    5100  333.42  5126.1  330.86
  5131.1  332.97    5140  331.73  5350.3  349.33  5430.5  352.97  5520.3  360.98
  5617.2  370.04  5716.1  377.15  5750.9   378.7  5871.1  377.81  5907.8  380.35
#Mann= 7 ,-1 , 0
  3551.9     .05       0  4782.4     .16       0  4996.8     .07       0
  5002.8     .16       0  5520.3     .12       0  5617.2     .16       0
  5716.1     .05       0
Bank Sta=4959.8,5039.9
XS Rating Curve= 0 ,0
Exp/Cntr=0.3,0.1

Type RM Length L Ch R = 1 ,20521   ,1008,1008,1008
BEGIN DESCRIPTION:
LITTLE BROWN CREEK 27.0
END DESCRIPTION:
XS GIS Cut Line= 2
      3619092.69     10627441.55      3621794.13     10627073.48
#Sta/Elev= 30
  3256.6  382.49  3301.3  382.82  3334.2  380.57  3497.4  361.15  3674.1  343.18
  3768.2  332.88  3808.6  331.16  4107.4  327.34    4415  327.03  4595.5  327.94
  4778.9  328.74  4879.3  329.27  4959.1  330.36  4989.4  316.25  4996.5  315.69
  4999.2  315.19  5002.5  315.69    5011  317.73  5029.8     327  5049.9  326.36
  5070.1  330.22  5155.7  330.25    5272  335.51  5623.1  355.83  5642.4  356.96
  5665.6  356.59  5685.8  360.19  5736.2  361.57    5883  373.18    5983  377.13
#Mann= 13 ,-1 , 0
  3256.6     .05       0  3497.4     .16       0  3674.1     .05       0
  4107.4     .16       0    4415     .05       0  4595.5     .16       0
  4778.9     .05       0  4879.3     .16       0  4996.5     .07       0
  5002.5     .16       0  5623.1     .12       0  5642.4     .16       0
    5883     .05       0
Bank Sta=4959.1,5070.1
XS Rating Curve= 0 ,0
Exp/Cntr=0.3,0.1

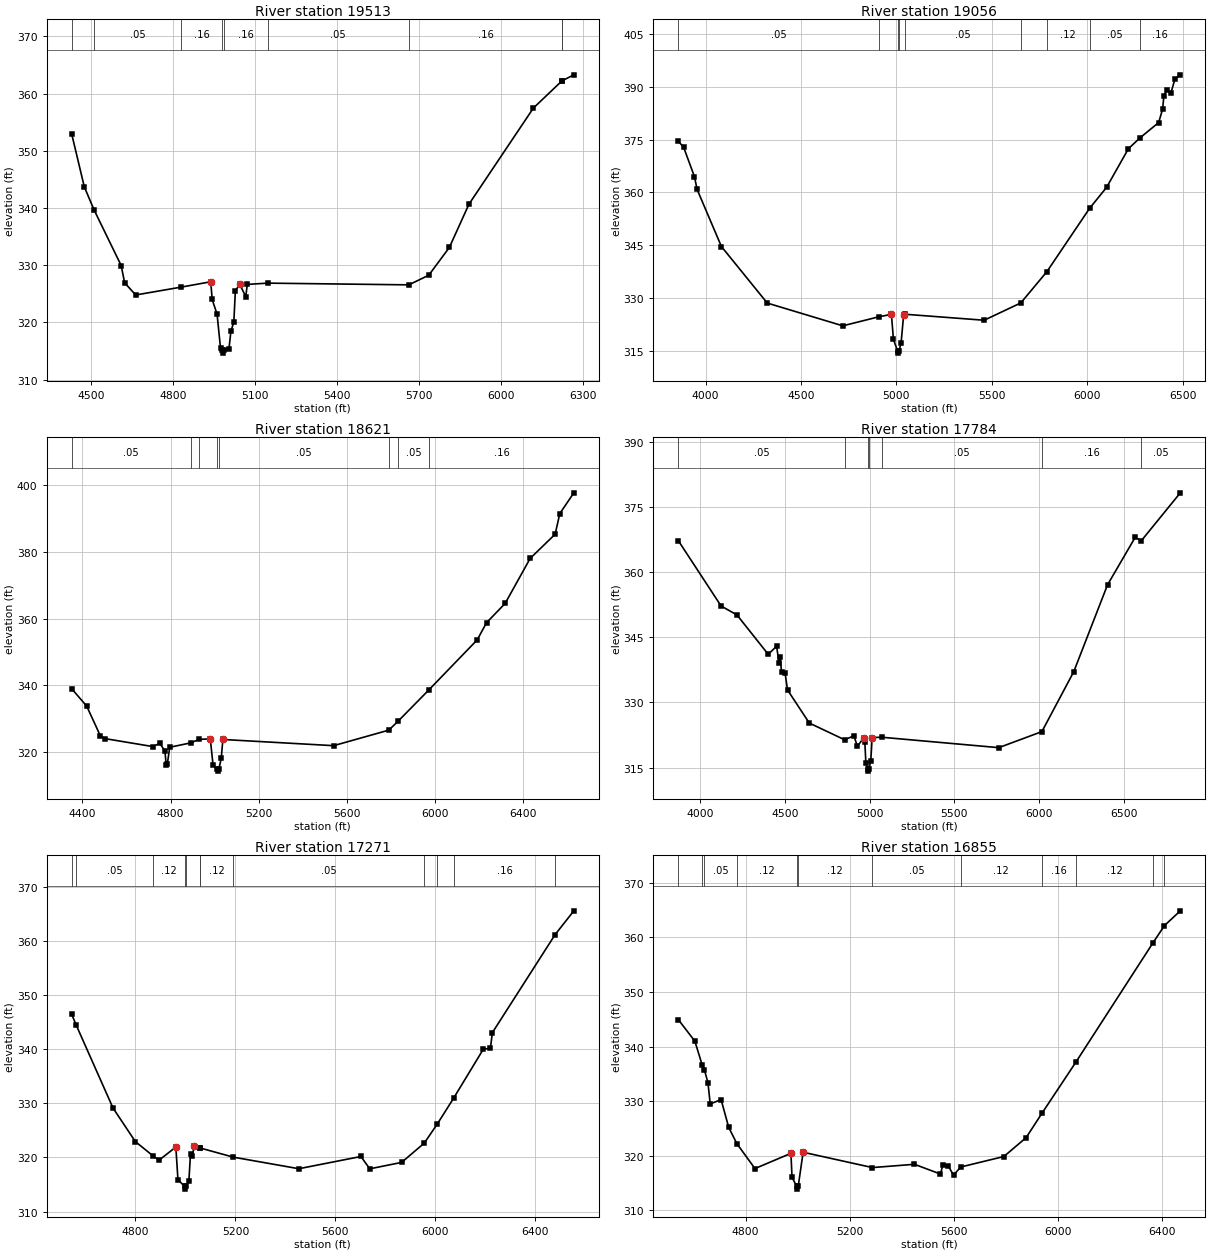
Type RM Length L Ch R = 1 ,19513   ,457,457,457
BEGIN DESCRIPTION:
LITTLE BROWN CREEK 26.0
END DESCRIPTION:
XS GIS Cut Line= 3
      3619899.56     10628060.21      3620449.61     10627860.19
      3621549.63     10627260.18
#Sta/Elev= 30
  4427.8  352.89  4473.7   343.7  4509.5  339.66  4608.7  329.94  4621.4  326.91
  4661.9  324.79  4829.1  326.17  4936.6   327.1  4941.9  324.01  4959.9  321.41
  4972.5  315.46  4978.2  315.12  4980.9  314.62  4984.2  315.12  5003.1  315.28
  5010.4  318.42  5021.2  320.08  5026.8  325.56    5043  326.63  5064.8  324.49
  5070.5  326.64    5145  326.86    5662  326.56    5735  328.25  5810.4  333.11
  5882.1  340.67    6118  357.48  6222.8  362.24  6222.9  362.24  6266.1  363.29
#Mann= 9 ,-1 , 0
  4427.8     .16       0  4509.5     .05       0  4829.1     .16       0
  4978.2     .07       0  4984.2     .16       0    5145     .05       0
    5662     .16       0  6222.8     .12       0  6222.9     .16       0
Bank Sta=4936.6,5043
XS Rating Curve= 0 ,0
Exp/Cntr=0.3,0.1

Type RM Length L Ch R = 1 ,19056   ,435,435,435
BEGIN DESCRIPTION:
LITTLE BROWN CREEK 25.0
END DESCRIPTION:
XS GIS Cut Line= 3
      3619999.64     10628910.16      3620799.61     10628110.19
      3621999.59      10627210.2
#Sta/Elev= 30
  3857.1  374.56  3885.3  372.83  3941.9  364.49  3956.1  360.82  4083.3  344.61
  4323.7  328.53  4719.7  322.06  4907.7  324.62  4974.3  325.32  4984.9  318.23
  5007.3   314.8  5010.1   314.3  5013.3   314.8  5024.9  317.11  5038.4  325.16
  5045.4  325.35  5460.3  323.65  5652.4  328.57  5789.1  337.45  6012.6  355.43
    6102  361.42  6216.6  372.43  6278.7  375.56  6374.9  379.84  6395.7  383.69
    6402  387.27  6416.6  389.14  6438.4  388.11  6460.3  392.23  6488.4  393.41
#Mann= 9 ,-1 , 0
  3857.1     .05       0  4907.7     .16       0  5007.3     .07       0
  5013.3     .16       0  5045.4     .05       0  5652.4     .16       0
  5789.1     .12       0  6012.6     .05       0  6278.7     .16       0
Bank Sta=4974.3,5038.4
XS Rating Curve= 0 ,0
Exp/Cntr=0.3,0.1

Type RM Length L Ch R = 1 ,18621   ,837,837,837
BEGIN DESCRIPTION:
LITTLE BROWN CREEK 24.0
END DESCRIPTION:
XS GIS Cut Line= 3
      3620349.59      10628760.2      3620949.61     10628510.19
      3622149.61     10627410.19
#Sta/Elev= 30
  4351.7  338.99  4419.4  333.83  4481.7  324.89  4503.4   324.1  4720.1  321.72
  4750.9  322.71  4774.2  320.43  4780.2  316.26  4785.6  316.61  4795.9  321.52
  4891.8  322.84  4928.9  323.87  4980.1  324.04  4992.5  316.32  5012.6  314.89
  5015.3  314.39  5018.6  314.89  5029.8  318.18  5037.2  323.85  5539.7     322
    5790  326.64  5833.1  329.37  5972.3   338.7  6190.9  353.61  6233.4  358.75
  6317.9  364.52  6431.4  377.98  6544.8  385.21  6565.8  391.37  6629.6  397.58
#Mann= 8 ,-1 , 0
  4351.7     .05       0  4891.8     .16       0  4928.9     .05       0
  5012.6     .03       0  5018.6     .05       0    5790     .16       0
  5833.1     .05       0  5972.3     .16       0
Bank Sta=4980.1,5037.2
XS Rating Curve= 0 ,0
Exp/Cntr=0.3,0.1

Type RM Length L Ch R = 1 ,17784   ,513,513,513
BEGIN DESCRIPTION:
LITTLE BROWN CREEK 22.0
END DESCRIPTION:
XS GIS Cut Line= 2
      3620176.04     10629941.55       3622515.5     10628122.74
#Sta/Elev= 30
  3870.6  367.23  4123.7  352.17  4216.9  350.13  4401.6  341.07  4451.3  342.92
  4465.8  338.95  4472.1  340.48  4480.3  336.92  4501.1  336.76  4515.6  332.87
  4644.1  325.25  4852.7   321.4  4907.4  322.32  4928.2  319.87  4964.4  321.85
  4971.7  320.98    4978  316.13  4989.5  314.69  4992.2  314.19  4995.5  314.69
    5007  316.56  5015.1  321.91  5070.3  321.99  5762.4  319.59  6016.9  323.28
  6205.1  337.07  6404.2  357.04    6568     368  6603.4  367.17  6833.9  378.21
#Mann= 7 ,-1 , 0
  3870.6     .05       0  4852.7     .16       0  4989.5     .07       0
  4995.5     .16       0  5070.3     .05       0  6016.9     .16       0
  6603.4     .05       0
Bank Sta=4964.4,5015.1
XS Rating Curve= 0 ,0
Exp/Cntr=0.3,0.1

Type RM Length L Ch R = 1 ,17271   ,416,416,416
BEGIN DESCRIPTION:
LITTLE BROWN CREEK 21.0
END DESCRIPTION:
XS GIS Cut Line= 3
      3621149.59     10630010.23      3621349.61     10629610.19
       3622549.6     10628610.19
#Sta/Elev= 30
  4545.1  346.42  4563.5  344.39  4710.1  329.14  4799.5  322.94  4871.2  320.26
  4894.5   319.5  4961.6  321.93    4970  315.91  4996.5  314.65  4999.3  314.15
  5002.5  314.65  5013.8  315.65  5020.3  320.71  5028.2  320.32  5034.7  322.16
  5058.3  321.76  5058.8  321.75  5191.4  320.06  5453.8  317.92  5702.4  320.18
  5737.6   317.9  5865.2  319.09  5955.8  322.65  6008.3  326.21  6073.5  330.97
  6191.9  339.99  6220.5  340.19  6228.3  343.06  6479.5  361.18  6554.4  365.57
#Mann= 12 ,-1 , 0
  4545.1      .1       0  4563.5     .05       0  4871.2     .12       0
  4996.5     .07       0  5002.5     .12       0  5058.3     .08       0
  5058.8     .12       0  5191.4     .05       0  5955.8     .16       0
  6008.3     .05       0  6073.5     .16       0  6479.5     .05       0
Bank Sta=4961.6,5034.7
XS Rating Curve= 0 ,0
Exp/Cntr=0.3,0.1

Type RM Length L Ch R = 1 ,16855   ,648,648,648
BEGIN DESCRIPTION:
LITTLE BROWN CREEK 20.0
END DESCRIPTION:
XS GIS Cut Line= 3
      3621299.62     10630110.18      3621649.61     10629860.19
      3622549.61     10628660.19
#Sta/Elev= 30
  4541.2  344.96  4605.1  340.99  4632.8  336.69  4641.6  335.75  4655.5  333.36
  4664.1  329.48  4705.9  330.28  4735.3  325.18  4766.7   322.2  4836.1  317.64
  4974.4  320.43  4978.6  316.08  4996.4  314.37  4999.2  313.87  5002.4  314.37
  5021.3  320.63  5287.9  317.82  5449.4  318.42  5549.4  316.63  5557.8  318.21
  5578.6  318.19  5599.4  316.42  5626.9  317.92  5793.2  319.85  5878.6  323.31
  5939.1  327.75  6070.6   337.2  6365.6  358.97  6410.4  362.18  6471.3  364.88
#Mann= 12 ,-1 , 0
  4541.2     .05       0  4632.8     .16       0  4641.6     .05       0
  4766.7     .12       0  4996.4     .07       0  5002.4     .12       0
  5287.9     .05       0  5626.9     .12       0  5939.1     .16       0
  6070.6     .12       0  6365.6     .16       0  6410.4     .05       0
Bank Sta=4974.4,5021.3
XS Rating Curve= 0 ,0
Exp/Cntr=0.3,0.1

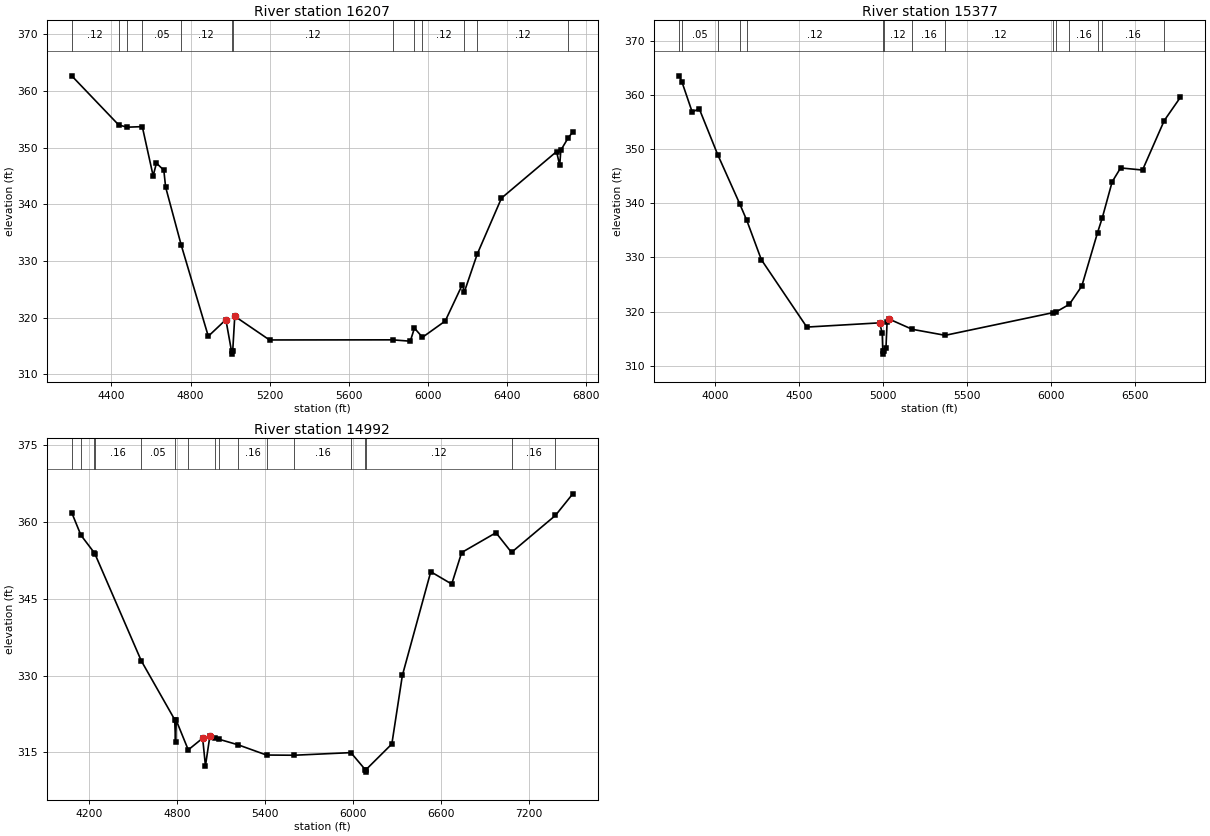
Type RM Length L Ch R = 1 ,16207   ,830,830,830
BEGIN DESCRIPTION:
Mapping XS 1063b117
END DESCRIPTION:
XS GIS Cut Line= 3
      3620937.69     10630626.23      3621911.67     10630313.72
      3622666.86     10629006.46
#Sta/Elev= 30
  4199.2  362.67  4436.7     354  4479.4  353.61  4555.9  353.71  4610.8  345.02
  4627.3  347.27  4664.7  346.03  4673.8  343.05  4752.4  332.85  4889.5  316.73
  4978.4  319.66  5006.9  314.08  5009.6  313.58  5012.9  314.08  5023.3  320.26
  5198.9  316.08  5820.6   316.1  5910.5  315.86  5931.4  318.17  5972.1  316.55
  6087.1  319.42  6173.2  325.81    6184  324.58  6248.8  331.22  6371.4   341.1
  6649.9  349.31  6665.7  346.88  6671.4  349.55  6709.6  351.79  6731.8  352.75
#Mann= 13 ,-1 , 0
  4199.2     .12       0  4436.7     .05       0  4479.4     .12       0
  4555.9     .05       0  4752.4     .12       0  5006.9     .07       0
  5012.9     .12       0  5820.6     .08       0  5931.4     .05       0
  5972.1     .12       0    6184     .16       0  6248.8     .12       0
  6709.6     .16       0
Bank Sta=4978.4,5023.3
XS Rating Curve= 0 ,0
Exp/Cntr=0.3,0.1

Type RM Length L Ch R = 1 ,15377   ,385,385,385
BEGIN DESCRIPTION:
LITTLE BROWN CREEK 18.0
END DESCRIPTION:
XS GIS Cut Line= 4
       3621022.8     10630884.99      3621911.72      10630808.6
      3622620.06     10630447.49      3622745.06      10629155.8
#Sta/Elev= 30
  3784.7   363.5  3801.6  362.27  3861.8   356.8  3903.1  357.46  4013.3  348.98
  4143.9  339.94  4186.7  336.84  4273.3  329.59  4544.3  317.15  4977.6  317.93
  4993.5  316.07    4997  312.66  4999.8  312.16    5003  312.66  5015.8   313.2
  5022.5  318.02  5032.4  318.66  5172.1  316.74  5368.9  315.63  6010.5  319.81
  6027.4  319.91  6108.6  321.35  6182.6  324.72  6276.5  334.59  6304.9  337.34
  6363.4  343.95  6413.7  346.51  6544.3  346.12  6673.6  355.24  6769.7  359.53
#Mann= 15 ,-1 , 0
  3784.7     .12       0  3801.6     .05       0  4013.3     .12       0
  4143.9     .16       0  4186.7     .12       0    4997     .07       0
    5003     .12       0  5172.1     .16       0  5368.9     .12       0
  6010.5     .08       0  6027.4     .05       0  6108.6     .16       0
  6276.5     .12       0  6304.9     .16       0  6673.6     .12       0
Bank Sta=4977.6,5032.4
XS Rating Curve= 0 ,0
Exp/Cntr=0.3,0.1

Type RM Length L Ch R = 1 ,14992   ,2150,2150,2150
BEGIN DESCRIPTION:
LITTLE BROWN CREEK 16.0
END DESCRIPTION:
XS GIS Cut Line= 2
      3621190.33     10631286.05      3624401.93     10630125.09
#Sta/Elev= 30
  4082.3  361.83  4144.8  357.43  4235.5     354  4240.3  353.78  4556.4  332.87
  4784.1  321.38  4789.7  317.03    4795  321.22  4876.5  315.47  4974.7  317.75
  4993.7  312.35  5024.4  318.26  5056.3   317.7  5085.3  317.55  5217.2  316.45
    5410  314.46  5597.6  314.42    5985  314.93  6082.5  311.62  6085.2  311.12
  6088.5  311.62  6264.1  316.62  6335.8  330.02  6529.4  350.28  6672.1  347.87
  6739.9  354.03  6973.8   357.9  7079.6  354.06    7379  361.28  7497.3   365.5
#Mann= 17 ,-1 , 0
  4082.3     .05       0  4144.8     .16       0  4235.5     .05       0
  4240.3     .16       0  4556.4     .05       0  4784.1     .16       0
  4876.5     .12       0  5056.3     .16       0  5085.3     .12       0
  5217.2     .16       0    5410     .05       0  5597.6     .16       0
    5985     .12       0  6082.5     .07       0  6088.5     .12       0
  7079.6     .16       0    7379     .05       0
Bank Sta=4974.7,5024.4
XS Rating Curve= 0 ,0
Exp/Cntr=0.3,0.1