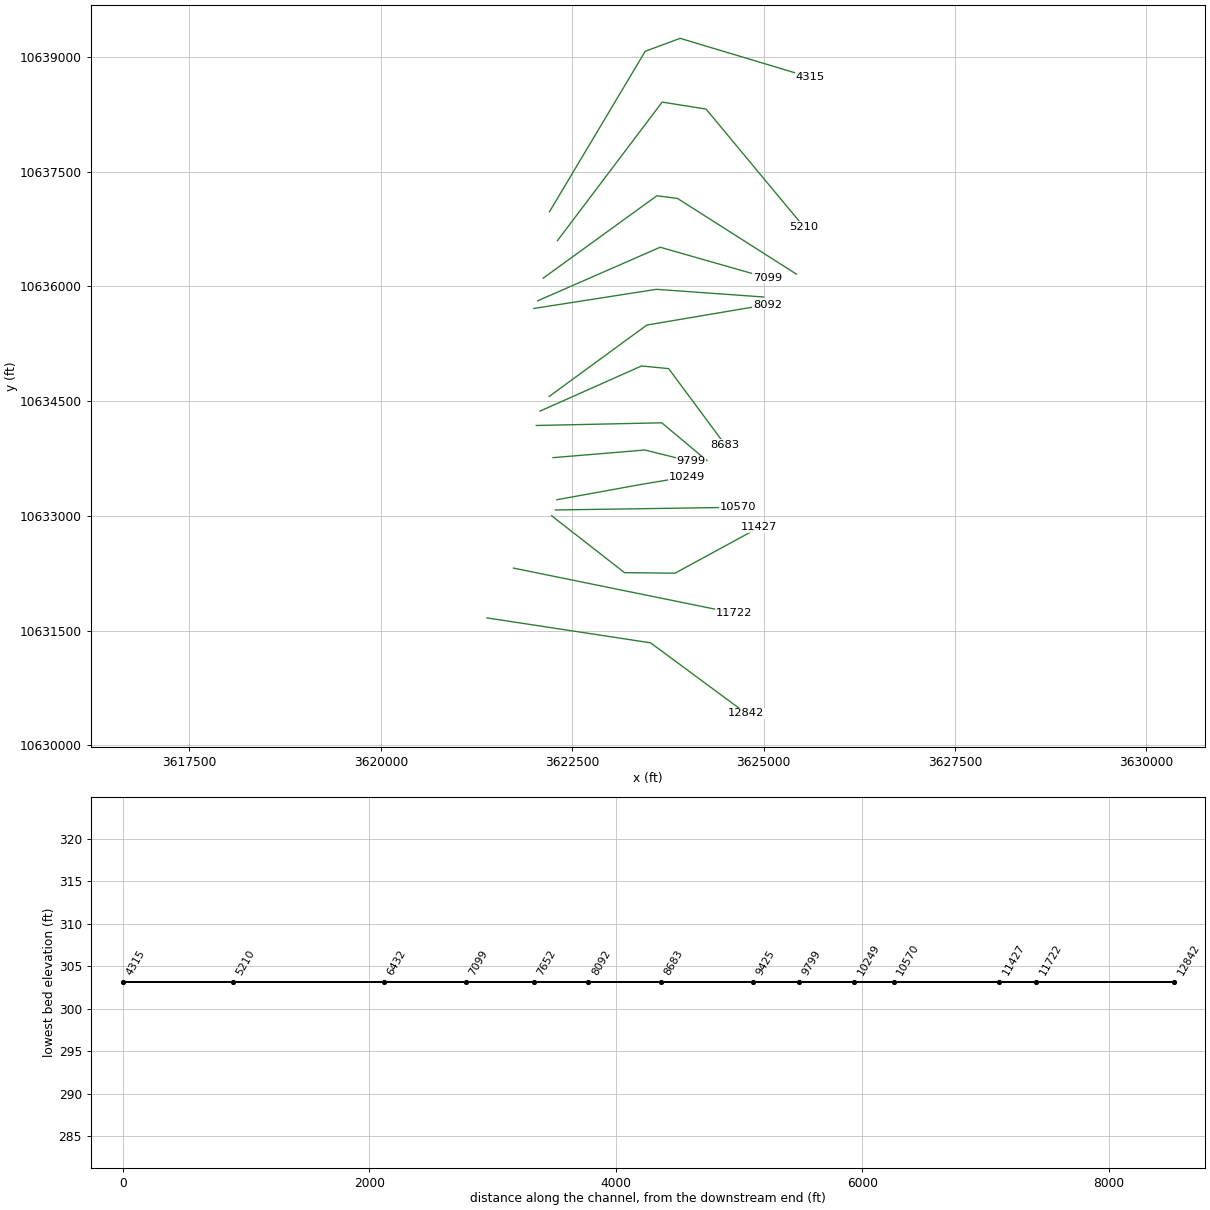
HEC-RAS study LITTLE BROWN CREEK.prj: LITTLE BROWN CREEK Base Level Engineering

--- LITTLE BROWN CREEK.g01 (geometry) --- (continued)

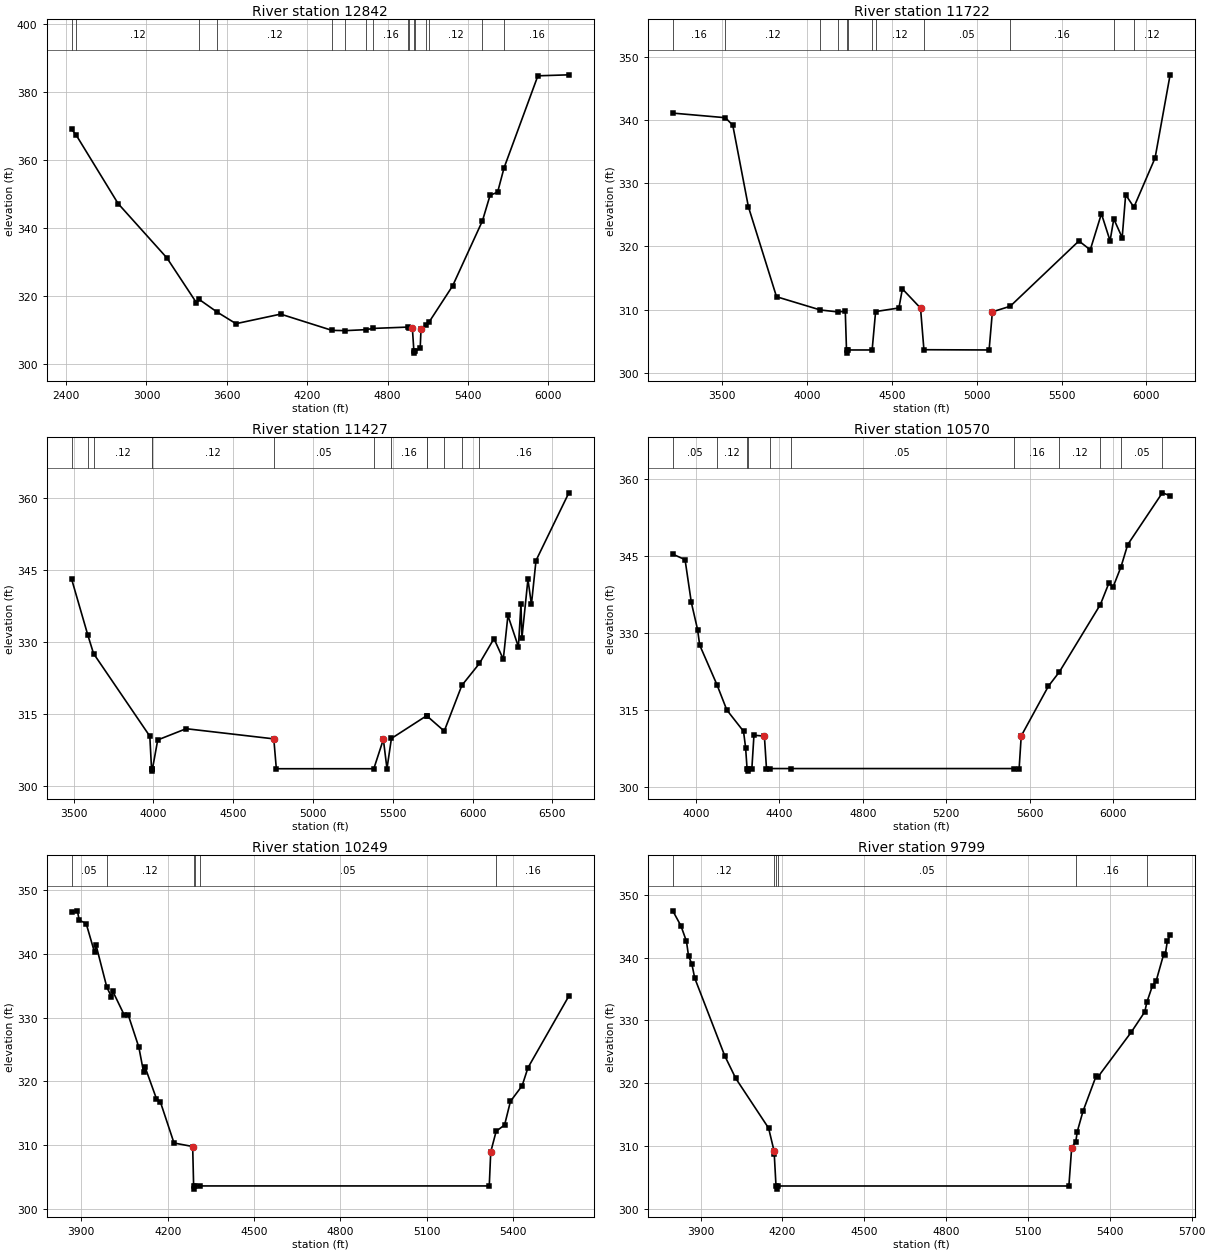
Type RM Length L Ch R = 1 ,12842   ,1120,1120,1120
BEGIN DESCRIPTION:
LITTLE BROWN CREEK 15.0
END DESCRIPTION:
XS GIS Cut Line= 3
      3621385.65     10631665.81      3623523.27     10631340.28
      3624771.14     10630417.95
#Sta/Elev= 30
  2440.3  369.09  2472.4  367.55  2788.2  347.18  3152.4  331.18  3372.1  318.02
    3393  318.95    3527  315.23  3668.3  311.79  4002.1  314.61  4385.1  309.82
  4485.8  309.74  4638.7  310.03  4691.2  310.39  4954.5  310.79  4962.3  310.54
  4985.5  310.58  4997.1  303.61  4999.9  303.11  5003.1  303.61    5044  304.57
  5050.2   310.2    5089   311.5  5108.8  312.17  5286.1  322.92  5509.1  342.12
  5565.9  349.64  5622.2  350.55    5670  357.68  5922.9  384.85  6154.3  385.14
#Mann= 16 ,-1 , 0
  2440.3     .05       0  2472.4     .12       0    3393     .16       0
    3527     .12       0  4385.1     .07       0  4485.8     .05       0
  4638.7     .12       0  4691.2     .16       0  4954.5     .12       0
  4962.3     .07       0  4997.1     .07       0  5003.1     .07       0
    5089     .16       0  5108.8     .12       0  5509.1     .05       0
    5670     .16       0
Bank Sta=4985.5,5050.2
XS Rating Curve= 0 ,0
Exp/Cntr=0.3,0.1

Type RM Length L Ch R = 1 ,11722   ,295,295,295
BEGIN DESCRIPTION:
LITTLE BROWN CREEK 13.0
END DESCRIPTION:
XS GIS Cut Line= 2
      3621732.93     10632316.84      3624606.48     10631731.29
#Sta/Elev= 30
  3207.7  341.11    3518  340.38  3561.5  339.19  3653.4   326.3  3819.4  312.04
    4078  309.94  4179.8  309.64  4224.9  309.73  4232.1  303.61  4234.8  303.11
  4238.1  303.61  4383.3  303.61  4403.7  309.69  4541.2  310.26  4561.6  313.28
  4668.6  310.24  4688.6  303.65    5073  303.61  5092.3  309.65  5197.5  310.53
  5602.6  320.87  5669.5  319.46  5735.3  325.18  5786.3  320.89  5808.2  324.35
  5857.7   321.4  5878.2  328.19  5926.7  326.21  6051.6     334  6140.3  347.17
#Mann= 12 ,-1 , 0
  3207.7     .16       0    3518     .12       0    4078      .1       0
  4179.8     .05       0  4232.1    .033       0  4238.1     .05       0
  4383.3     .07       0  4403.7     .12       0  4688.6     .05       0
  5197.5     .16       0  5808.2     .05       0  5926.7     .12       0
Bank Sta=4668.6,5092.3
XS Rating Curve= 0 ,0
Exp/Cntr=0.3,0.1

Type RM Length L Ch R = 1 ,11427   ,857,857,857
BEGIN DESCRIPTION:
LITTLE BROWN CREEK 12.0
END DESCRIPTION:
XS GIS Cut Line= 4
      3622232.18     10633000.21      3623183.56     10632257.16
      3623843.28     10632250.22      3624940.46     10632847.42
#Sta/Elev= 30
  3487.1  343.23    3589  331.51    3625  327.64  3977.5   310.4  3988.4  303.61
  3991.1  303.11  3994.4  303.61  4027.2  309.62  4205.4  311.96  4754.4  309.84
  4770.3  303.61  5381.1  303.61  5440.9  309.73  5463.5  303.61  5491.4  309.93
  5711.6  314.66    5712  314.68  5822.3  311.46  5932.6  320.99  6042.9  325.58
    6134  330.75  6192.4  326.45  6221.4  335.58    6287  329.05  6303.1  337.97
  6308.8  330.79  6346.8  343.13  6368.6  337.88  6397.3  347.04  6603.2  361.17
#Mann= 13 ,-1 , 0
  3487.1     .05       0    3589     .16       0    3625     .12       0
  3988.4    .033       0  3994.4     .12       0  4754.4     .05       0
  5381.1     .07       0  5491.4     .16       0  5711.6     .12       0
    5712     .16       0  5822.3     .05       0  5932.6     .05       0
  6042.9     .16       0
Bank Sta=4754.4,5440.9
XS Rating Curve= 0 ,0
Exp/Cntr=0.3,0.1

Type RM Length L Ch R = 1 ,10570   ,321,321,321
BEGIN DESCRIPTION:
LITTLE BROWN CREEK 11.0
END DESCRIPTION:
XS GIS Cut Line= 2
      3622280.83     10633076.61      3624662.67     10633111.33
#Sta/Elev= 30
  3889.6  345.36  3948.4   344.3  3978.4  335.97  4008.4  330.67  4018.4  327.67
  4100.9  319.97  4148.4  315.02  4228.4  310.87  4238.4  307.69  4245.4  303.61
  4248.2  303.11  4251.4  303.61  4268.4  303.61  4278.4   310.1  4328.4  309.93
  4338.4  303.61  4355.6  303.61  4454.5  303.61  5521.8  303.61  5548.6  303.61
  5558.6  309.96  5688.6  319.64  5741.2  322.43  5937.8  335.56  5978.6  339.74
  5998.6  338.97  6036.7  342.92  6068.6  347.22  6234.5  357.31  6271.7  356.75
#Mann= 11 ,-1 , 0
  3889.6     .05       0  4100.9     .12       0  4245.4    .033       0
  4251.4     .12       0  4355.6     .16       0  4454.5     .05       0
  5521.8     .16       0  5741.2     .12       0  5937.8     .08       0
  6036.7     .05       0  6234.5      .1       0
Bank Sta=4328.4,5558.6
XS Rating Curve= 0 ,0
Exp/Cntr=0.3,0.1

Type RM Length L Ch R = 1 ,10249   ,450,450,450
BEGIN DESCRIPTION:
LITTLE BROWN CREEK 10.0
END DESCRIPTION:
XS GIS Cut Line= 3
      3622299.65      10633210.2      3623399.61     10633410.19
      3623999.64     10633510.19
#Sta/Elev= 30
  3866.4  346.53  3886.7  346.74    3893  345.28  3917.2  344.75  3946.4  340.21
  3951.5  341.36    3989  334.75  4004.8  333.28  4009.9   334.1  4049.3  330.41
  4063.3  330.41  4100.1  325.35  4116.6  321.42  4121.7  322.23  4161.1  317.29
  4175.1  316.74  4222.1  310.34  4286.9  309.79  4290.2  303.61    4293  303.11
  4296.2  303.61  4312.7  303.61  5316.4  303.61  5321.5  308.93  5340.3  312.18
  5369.6  313.17  5389.9  316.87  5430.5  319.32  5450.7  322.14  5592.7  333.38
#Mann= 6 ,-1 , 0
  3866.4     .05       0    3989     .12       0  4290.2    .033       0
  4296.2     .12       0  4312.7     .05       0  5340.3     .16       0
Bank Sta=4286.9,5321.5
XS Rating Curve= 0 ,0
Exp/Cntr=0.3,0.1

Type RM Length L Ch R = 1 ,9799    ,374,374,374
BEGIN DESCRIPTION:
LITTLE BROWN CREEK 9.0
END DESCRIPTION:
XS GIS Cut Line= 3
      3622249.59     10633760.19      3623449.61     10633860.19
      3624049.57      10633710.2
#Sta/Elev= 30
  3798.4  347.46  3828.5  345.05  3848.6  342.59  3856.1  340.29  3868.7  338.91
  3878.7  336.76  3989.1  324.33  4029.2  320.76  4149.6  312.83  4169.7  309.16
  4170.3  308.68  4176.7  303.61  4179.5  303.11  4182.7  303.61    5250  303.61
  5260.3  309.74  5275.3  310.67  5280.9  312.29  5301.5  315.49  5350.5  321.21
  5355.6  320.93  5479.3  328.17  5528.3  331.37  5535.6  332.87  5556.6  335.56
  5569.5  336.23  5597.8   340.6    5603  340.44  5610.7  342.58    5621   343.6
#Mann= 6 ,-1 , 0
  3798.4     .12       0  4170.3     .05       0  4176.7    .033       0
  4182.7     .05       0  5275.3     .16       0  5535.6     .12       0
Bank Sta=4169.7,5260.3
XS Rating Curve= 0 ,0
Exp/Cntr=0.3,0.1

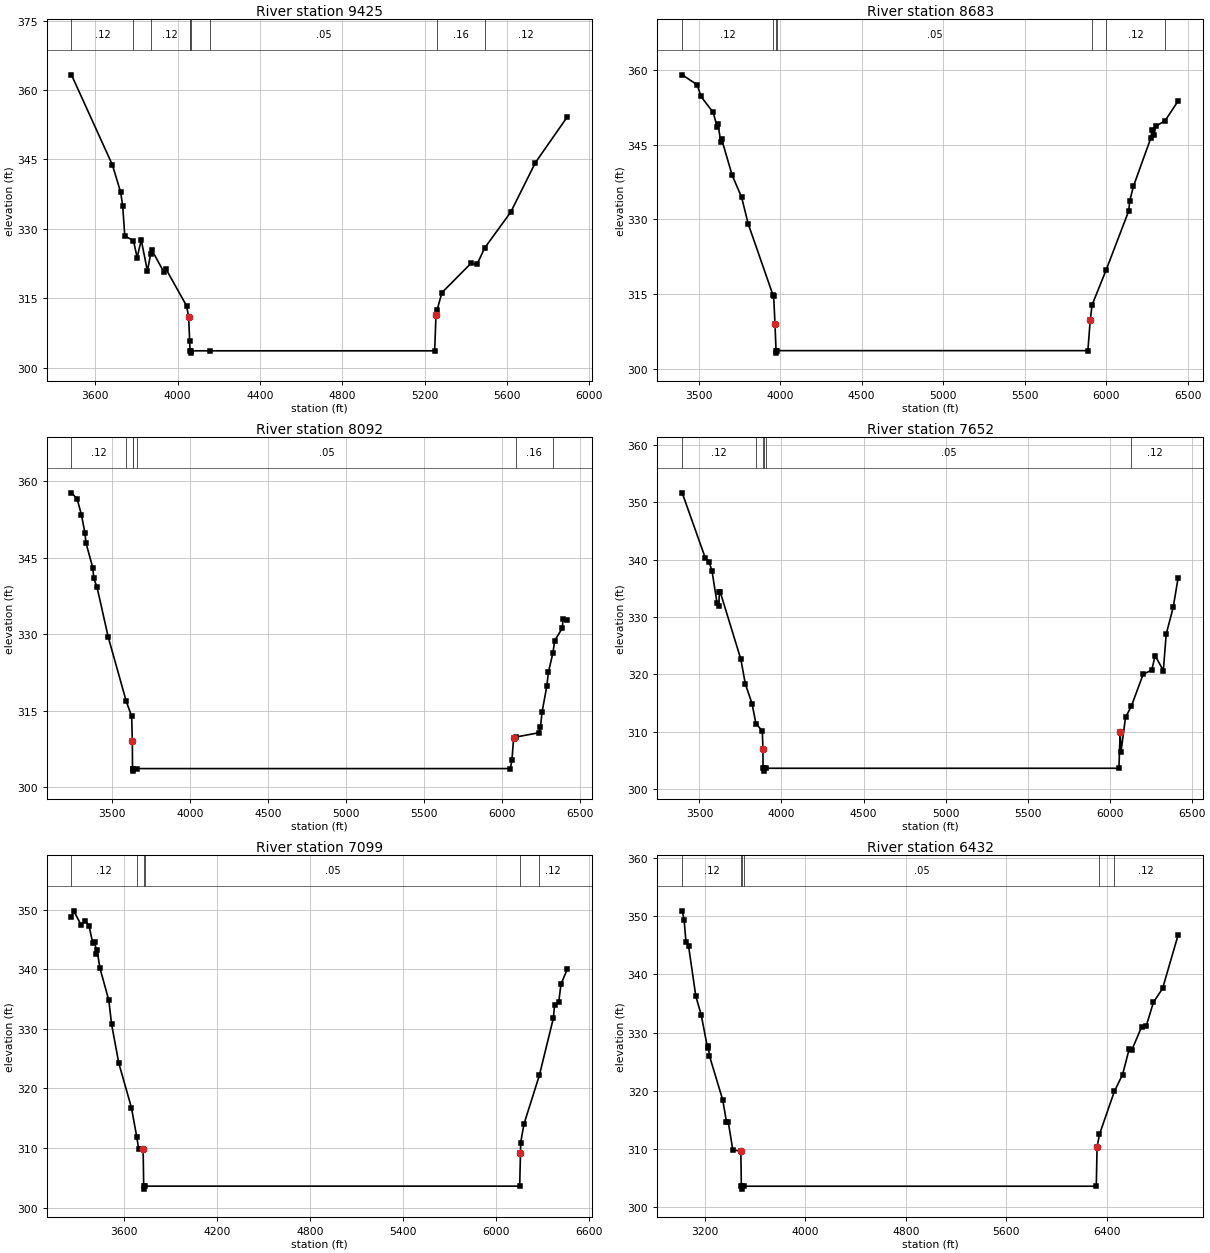
Type RM Length L Ch R = 1 ,9425    ,742,742,742
BEGIN DESCRIPTION:
LITTLE BROWN CREEK 8.0
END DESCRIPTION:
XS GIS Cut Line= 3
      3622030.75     10634180.77      3623669.67      10634215.5
      3624259.95     10633722.44
#Sta/Elev= 30
  3484.6  363.31  3683.5  343.81  3723.5   337.9  3733.5  334.93  3743.5  328.47
  3785.8  327.43  3803.5  323.79  3823.5  327.58  3853.5  320.85  3869.3  324.65
  3873.5  325.52  3933.6  320.63  3943.6   321.3  4043.6  313.34  4053.6  310.94
  4058.5  305.81  4060.6  303.61  4063.3  303.11  4066.6  303.61  4157.4  303.61
  5248.4  303.61  5254.9  311.39  5260.6  312.52  5283.5  316.19  5425.4  322.57
    5454  322.31  5491.2  325.86    5618  333.63  5737.7  344.33    5893  354.25
#Mann= 9 ,-1 , 0
  3484.6     .12       0  3785.8     .16       0  3869.3     .12       0
  4058.5     .16       0  4060.6    .033       0  4066.6     .16       0
  4157.4     .05       0  5260.6     .16       0  5491.2     .12       0
Bank Sta=4053.6,5254.9
XS Rating Curve= 0 ,0
Exp/Cntr=0.3,0.1

Type RM Length L Ch R = 1 ,8683    ,591,591,591
BEGIN DESCRIPTION:
LITTLE BROWN CREEK 7.0
END DESCRIPTION:
XS GIS Cut Line= 4
      3622079.36     10634368.26      3623405.78     10634958.55
      3623759.94     10634923.83      3624495.32     10633931.77
#Sta/Elev= 30
  3399.5  359.04  3491.6  357.04  3514.8  354.69    3590  351.48  3613.3  348.61
  3618.7  349.19  3636.5  345.54    3642  346.06  3706.2  338.85  3763.7  334.47
  3804.7  329.08  3957.1  314.72  3960.6  314.63  3968.9  308.92  3975.3  303.61
  3978.1  303.11  3981.3  303.61  5888.4  303.61  5903.1  309.85  5914.4  312.81
  5999.5  319.74  6138.9  331.69  6145.3  333.75  6168.1  336.66  6274.5  346.33
  6282.2  348.04  6295.3  346.97  6303.7  348.68  6361.8  349.81  6442.1  353.78
#Mann= 7 ,-1 , 0
  3399.5     .12       0  3957.1     .05       0  3975.3    .035       0
  3981.3     .05       0  5914.4     .16       0  5999.5     .12       0
  6361.8     .05       0
Bank Sta=3968.9,5903.1
XS Rating Curve= 0 ,0
Exp/Cntr=0.3,0.1

Type RM Length L Ch R = 1 ,8092    ,440,440,440
BEGIN DESCRIPTION:
LITTLE BROWN CREEK 6.0
END DESCRIPTION:
XS GIS Cut Line= 3
      3622199.64     10634560.21      3623475.22     10635493.28
      3625049.64     10635760.19
#Sta/Elev= 30
  3240.4  357.76    3277  356.57  3304.1  353.43  3327.1  349.85  3333.4  347.92
  3376.7  343.07  3383.6  340.98  3404.4   339.2  3475.8  329.45  3591.6  316.79
  3626.1  313.88  3630.4  308.94  3631.5  303.61  3634.3  303.11  3637.5  303.61
  3662.8  303.61  6052.5  303.61  6062.7  305.37  6072.8  309.55  6085.4  309.79
  6235.1  310.65  6245.2   311.8  6255.4  314.73  6285.8   319.8    6296  322.53
  6324.7  326.32  6336.5  328.75    6385  331.19    6390  333.04  6417.7  332.77
#Mann= 7 ,-1 , 0
  3240.4     .12       0  3591.6     .07       0  3631.5    .033       0
  3637.5     .07       0  3662.8     .05       0  6085.4     .16       0
  6324.7     .12       0
Bank Sta=3630.4,6072.8
XS Rating Curve= 0 ,0
Exp/Cntr=0.3,0.1

Type RM Length L Ch R = 1 ,7652    ,553,553,553
BEGIN DESCRIPTION:
LITTLE BROWN CREEK 5.0
END DESCRIPTION:
XS GIS Cut Line= 3
      3621999.61     10635710.19      3623599.61     10635960.19
      3624999.63     10635860.19
#Sta/Elev= 30
  3394.7  351.63  3536.4   340.2  3559.2  339.56  3576.9  337.93  3607.3  332.39
  3616.9  331.93  3621.9  334.26  3627.5  334.26  3752.5  322.58  3779.3  318.34
  3820.3   314.9  3844.1   311.4  3883.1  310.12 3886.93  306.98  3887.6  303.61
  3890.4  303.11  3893.6  303.61  3903.7  303.61  6056.8  303.61  6064.3  309.94
  6069.3  306.42  6096.9  312.47  6132.4  314.42  6204.6     320  6257.3  320.74
  6277.3  323.25  6327.5  320.64    6345     327  6387.6  331.65  6417.7  336.83
#Mann= 6 ,-1 , 0
  3394.7     .12       0  3844.1     .16       0  3887.6    .033       0
  3893.6     .16       0  3903.7     .05       0  6132.4     .12       0
Bank Sta=3886.93,6064.3
XS Rating Curve= 0 ,0
Exp/Cntr=0.3,0.1

Type RM Length L Ch R = 1 ,7099    ,667,667,667
BEGIN DESCRIPTION:
LITTLE BROWN CREEK 4.0
END DESCRIPTION:
XS GIS Cut Line= 3
      3622049.61     10635810.19      3623649.61     10636510.19
      3625049.57      10636110.2
#Sta/Elev= 30
  3259.1  348.78  3273.5  349.81  3320.3   347.5  3349.1  348.15  3372.5  347.28
  3395.9  344.46  3411.9  344.52  3419.3  342.63  3424.8  343.17  3442.7  340.23
  3500.4  334.77  3518.3  330.77  3564.7  324.25  3646.2  316.79  3680.6  311.89
    3693  309.86  3721.8  309.77  3725.5  303.61  3728.2  303.11  3731.5  303.61
  6153.4  303.61  6158.3  309.13  6159.9  310.93  6180.7  314.01  6280.1  322.18
  6370.5  331.77  6378.3  333.94  6405.6  334.52  6419.9  337.51  6461.5  340.05
#Mann= 6 ,-1 , 0
  3259.1     .12       0  3680.6     .05       0  3725.5    .033       0
  3731.5     .05       0  6158.3     .16       0  6280.1     .12       0
Bank Sta=3721.8,6158.3
XS Rating Curve= 0 ,0
Exp/Cntr=0.3,0.1

Type RM Length L Ch R = 1 ,6432    ,1222,1222,1222
BEGIN DESCRIPTION:
LITTLE BROWN CREEK 3.0
END DESCRIPTION:
XS GIS Cut Line= 4
      3622121.68     10636106.58      3623606.07     10637182.98
      3623875.17     10637148.26      3625428.99     10636158.67
#Sta/Elev= 30
  3019.6  350.92  3034.9  349.38  3049.6  345.59  3070.5  344.85  3128.2  336.24
    3171  333.05  3221.2  327.39  3227.4  327.72  3235.9  326.05  3342.6  318.42
    3372  314.65  3386.7   314.6  3422.3  309.86  3486.4  309.62  3490.4  303.61
  3493.1  303.11  3496.4  303.61  3509.7  303.61  6315.4  303.61  6321.5  310.34
  6340.8  312.52  6458.9  319.89  6524.6   322.8  6576.2   327.1  6597.4  326.98
  6676.1  330.98  6712.5  331.12  6770.1  335.21  6842.9  337.58  6966.7  346.77
#Mann= 6 ,-1 , 0
  3019.6     .12       0  3490.4    .033       0  3496.4     .12       0
  3509.7     .05       0  6340.8     .16       0  6458.9     .12       0
Bank Sta=3486.4,6321.5
XS Rating Curve= 0 ,0
Exp/Cntr=0.3,0.1

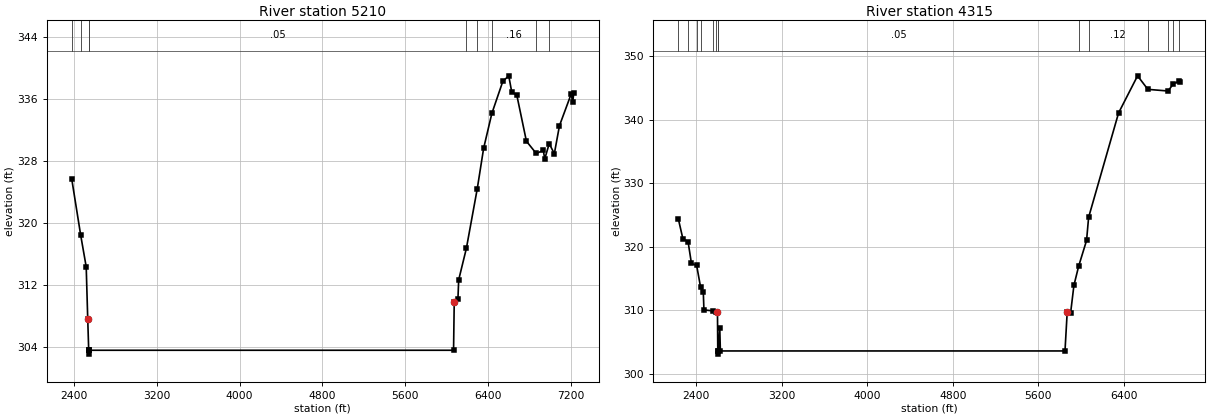
Type RM Length L Ch R = 1 ,5210    ,895,895,895
BEGIN DESCRIPTION:
LITTLE BROWN CREEK 2.0
END DESCRIPTION:
XS GIS Cut Line= 4
      3622308.12     10636597.35       3623675.3     10638407.24
      3624248.21     10638316.09      3625524.26     10636779.63
#Sta/Elev= 30
  2380.5   325.7  2466.2   318.5  2519.8  314.39  2534.4  307.69  2543.8  303.68
    2544  303.61  2546.7  303.11    2550  303.61  6065.2  303.61  6071.7  309.86
  6107.5  310.25  6114.7   312.7  6188.9  316.77  6294.2  324.49  6355.5   329.7
  6434.7  334.19  6540.4  338.33  6597.8  339.05  6626.4  336.98  6675.9  336.54
  6768.3  330.61  6863.4  329.02  6931.1  329.42  6945.4  328.33  6988.3  330.29
  7037.9     329  7087.3  332.61  7200.6  336.71  7214.9  335.65  7226.1  336.89
#Mann= 10 ,-1 , 0
  2380.5     .12       0  2466.2     .16       0  2543.8     .05       0
    2544    .033       0    2550     .05       0  6188.9     .16       0
  6294.2     .12       0  6434.7     .16       0  6863.4     .05       0
  6988.3     .16       0
Bank Sta=2534.4,6071.7
XS Rating Curve= 0 ,0
Exp/Cntr=0.3,0.1

Type RM Length L Ch R = 1 ,4315    ,0,0,0
BEGIN DESCRIPTION:
LITTLE BROWN CREEK 1.0
END DESCRIPTION:
XS GIS Cut Line= 4
      3622203.93     10636974.93      3623453.94      10639071.3
      3623909.67     10639240.57      3625602.34     10638732.77
#Sta/Elev= 30
  2233.2  324.46  2276.8  321.27    2325  320.83  2356.6   317.4  2405.4  317.07
  2441.9  313.68  2467.6  312.83  2473.4  310.07  2558.8  309.92  2586.7  309.82
    2600  309.82  2602.8  303.61  2605.5  303.11  2608.8  303.61  2621.4  307.27
  2627.2  303.61  5849.1  303.61  5869.8  309.73  5901.3  309.55  5932.6  313.94
  5976.8  316.95  6050.8  321.01  6069.9  324.64  6350.2  341.09  6527.7  346.93
  6623.8   344.8  6812.9  344.54    6863  345.69  6917.4  346.07  6927.3  346.03
#Mann= 14 ,-1 , 0
  2233.2     .16       0    2325     .05       0  2405.4     .16       0
  2441.9     .05       0  2558.8     .08       0  2586.7     .05       0
  2602.8    .033       0  2608.8     .05       0  5976.8     .16       0
  6069.9     .12       0  6623.8     .16       0  6812.9     .05       0
    6863     .16       0  6917.4     .05       0
Bank Sta=2600,5869.8
XS Rating Curve= 0 ,0
Exp/Cntr=0.3,0.1

Chan Stop Cuts=-1
Use User Specified Reach Order=0
Composite Channel Slope=5