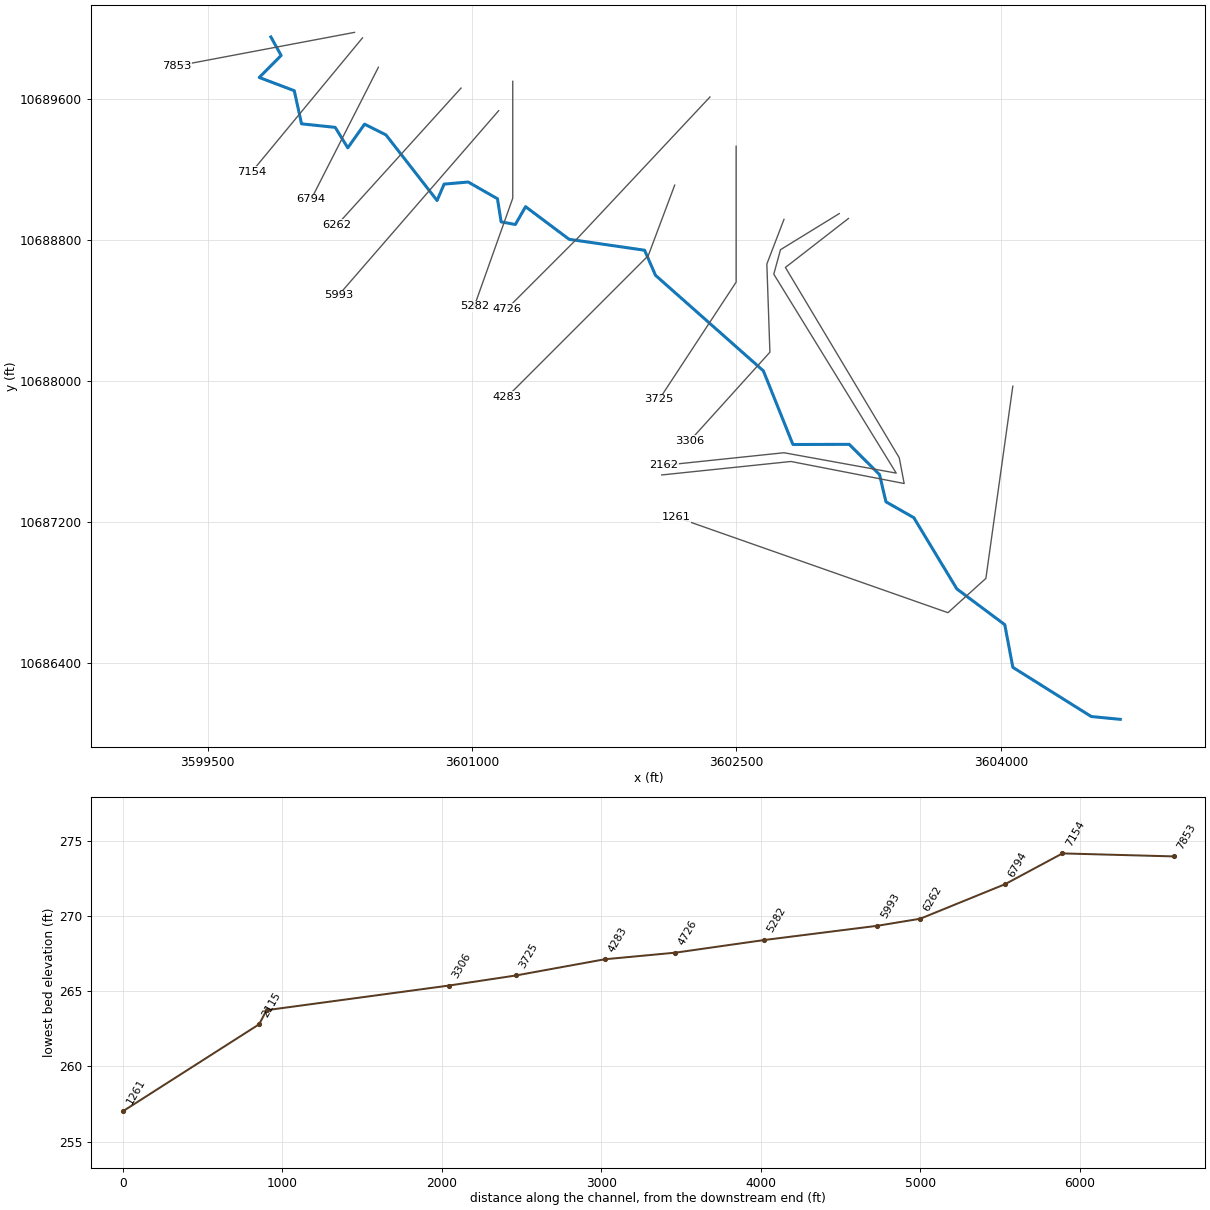
--- LITTLE SANDY CREEK.prj (project) ---

Proj Title=LITTLE SANDY CREEK Base Level Engineering
Current Plan=p01
Default Exp/Contr=0.3,0.1
English Units
Geom File=g01
Flow File=f01
Plan File=p01
Y Axis Title=Elevation
X Axis Title(PF)=Main Channel Distance
X Axis Title(XS)=Station
BEGIN DESCRIPTION:
LITTLE SANDY CREEK
END DESCRIPTION:
DSS Export Rating Curves= 0
DSS Export Rating Curve Sorted= 0
DSS Export Volume Flow Curves= 0
DXF OffsetX= 0
DXF OffsetY= 0
DXF ScaleX= 1
DXF ScaleY= 10

--- LITTLE SANDY CREEK.p01 (plan) ---

Plan Title=Multiple Run
Short Identifier=Multiple
Geom File=g01
Flow File=f01
Subcritical Flow
K Sum by GR= 0
Std Step Tol= 0.01
Critical Tol= 0.01
Num of Std Step Trials= 20
Max Error Tol= 0.3
Flow Tol Ratio= 0.001
Split Flow NTrial= 30
Split Flow Tol= 0.02
Split Flow Ratio= 0.02
Log Output Level= 0
Friction Slope Method= 1
Unsteady Friction Slope Method= 2
Unsteady Bridges Friction Slope Method= 1
Parabolic Critical Depth
Global Vel Dist=  1 , 1 , 1
Global Log Level= 0
CheckData=True
Encroach Param= -1, 0, 0, 0
BEGIN DESCRIPTION:
Multiple Run
END DESCRIPTION:

--- LITTLE SANDY CREEK.f01 (steady flow) ---

Flow Title=Multiple
Number of Profiles=7
Profile Names=10-year,25-year,50-year,1pct_min,100-year,1pct_plu,500-year
River Rch & RM= LITTLE SANDY CRE,Reach-1,7853
    1187    1616    1966    1746    2361    3193    3394
River Rch & RM= LITTLE SANDY CRE,Reach-1,5282
    1784    2476    3052    2741    3707    5014    5455
Boundary for River Rch & Prof#=LITTLE SANDY CRE,Reach-1,1
Up Type=0
Dn Type=3
Dn Slope=0.005
Boundary for River Rch & Prof#=LITTLE SANDY CRE,Reach-1,2
Up Type=0
Dn Type=3
Dn Slope=0.005
Boundary for River Rch & Prof#=LITTLE SANDY CRE,Reach-1,3
Up Type=0
Dn Type=3
Dn Slope=0.005
Boundary for River Rch & Prof#=LITTLE SANDY CRE,Reach-1,4
Up Type=0
Dn Type=3
Dn Slope=0.005
Boundary for River Rch & Prof#=LITTLE SANDY CRE,Reach-1,5
Up Type=0
Dn Type=3
Dn Slope=0.005
Boundary for River Rch & Prof#=LITTLE SANDY CRE,Reach-1,6
Up Type=0
Dn Type=3
Dn Slope=0.005
Boundary for River Rch & Prof#=LITTLE SANDY CRE,Reach-1,7
Up Type=0
Dn Type=3
Dn Slope=0.005

--- LITTLE SANDY CREEK.g01 (geometry) ---

Geom Title=Existing Conditions
Program Version=4.10

River Reach=LITTLE SANDY CRE,Reach-1
Reach XY= 30
        3599859.       10689951.      3599917.25       10689846.
        3599793.       10689721.       3599991.5       10689646.
        3600033.       10689458.      3600223.75       10689438.
      3600295.25       10689322.       3600390.5       10689456.
        3600512.       10689395.      3600801.75       10689023.
       3600841.5       10689116.      3600978.25       10689128.
      3601144.25       10689033.        3601165.       10688902.
      3601245.75       10688887.      3601303.75       10688988.
        3601551.       10688803.        3601979.       10688741.
       3602040.5       10688599.       3602652.5       10688057.
      3602820.25       10687639.       3603139.5       10687640.
      3603311.75       10687468.      3603347.75       10687314.
        3603506.       10687224.        3603750.       10686820.
        3604022.       10686617.      3604067.75       10686375.
       3604512.5       10686096.      3604677.25       10686080.

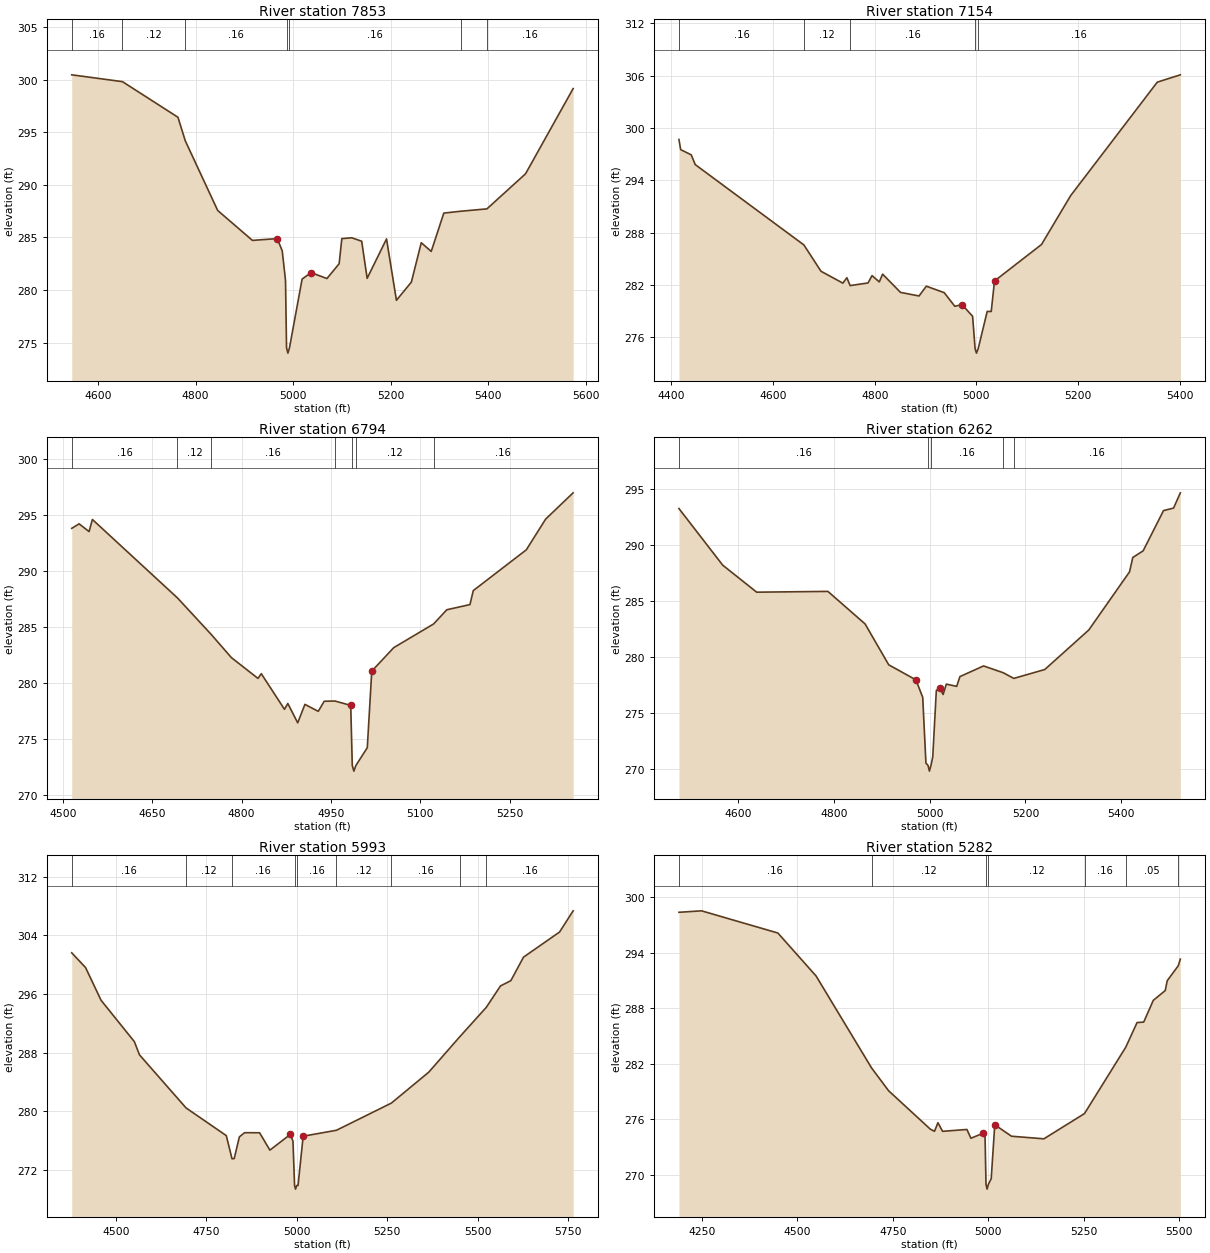
Type RM Length L Ch R = 1 ,7853    ,699,699,699
BEGIN DESCRIPTION:
LITTLE SANDY CREEK 15.0
END DESCRIPTION:
XS GIS Cut Line= 2
      3600333.48     10689976.87      3599323.85     10689786.05
#Sta/Elev= 30
  4546.3  300.48  4650.3  299.83    4764  296.44    4779   294.2  4845.4  287.57
  4916.6  284.72  4967.5  284.89  4977.7  283.72  4984.4  280.91  4986.5  274.49
  4989.3  273.99  4992.5  274.49  5018.4  281.04  5036.8  281.65  5069.3  281.09
  5094.3   282.5  5099.8  284.89  5120.2  284.97  5140.5  284.64  5151.7  281.11
  5191.4  284.86  5211.7  279.02  5242.3  280.75  5262.6   284.5    5283  283.67
  5308.8  287.32  5344.4   287.5  5397.1  287.72  5476.3  291.06  5573.8  299.17
#Mann= 7 ,-1 , 0
  4546.3     .16       0  4650.3     .12       0    4779     .16       0
  4986.5     .07       0  4992.5     .16       0  5344.4     .12       0
  5397.1     .16       0
Bank Sta=4967.5,5036.8
XS Rating Curve= 0 ,0
Exp/Cntr=0.3,0.1

Type RM Length L Ch R = 1 ,7154    ,360,360,360
BEGIN DESCRIPTION:
Mapping XS 19fcf88b
END DESCRIPTION:
XS GIS Cut Line= 2
      3600378.61     10689945.59      3599750.15     10689185.18
#Sta/Elev= 30
  4414.8  298.67  4418.2  297.51    4439  296.91  4446.9  295.79  4660.6  286.59
  4694.3  283.57  4737.3  282.21  4745.2  282.83  4751.6  281.93  4786.8  282.23
  4794.7  283.07    4809  282.35  4815.5  283.24  4850.7  281.15  4887.2  280.74
  4901.5  281.86  4936.7  281.12  4957.5  279.56  4971.8  279.75  4992.6  278.41
  4997.5  274.69  5000.2  274.19  5003.5  274.69  5021.3  278.97  5029.2  278.96
  5035.7  282.46  5128.2  286.64  5185.5  292.24  5355.9  305.24  5401.3  306.08
#Mann= 5 ,-1 , 0
  4414.8     .16       0  4660.6     .12       0  4751.6     .16       0
  4997.5     .07       0  5003.5     .16       0
Bank Sta=4971.8,5035.7
XS Rating Curve= 0 ,0
Exp/Cntr=0.3,0.1

Type RM Length L Ch R = 1 ,6794    ,532,532,532
BEGIN DESCRIPTION:
LITTLE SANDY CREEK 14.0
END DESCRIPTION:
XS GIS Cut Line= 2
       3600468.9     10689778.93      3600086.99     10689028.98
#Sta/Elev= 30
    4515  293.82  4527.4  294.22  4544.1  293.53  4549.7  294.61  4692.4  287.61
  4749.4  284.33  4782.9  282.28  4827.6  280.42  4833.2  280.84  4872.1  277.66
  4877.7  278.18  4894.3  276.45  4906.4   278.1  4928.8  277.48  4938.8  278.38
  4956.8   278.4  4983.3  278.01  4985.9  272.64  4988.6  272.14  4991.9  272.64
  5011.1  274.23  5018.6  281.07  5055.6  283.17  5122.4  285.28  5144.6  286.55
  5183.4  287.01    5189  288.26    5278   291.9  5310.4  294.64  5356.6  296.99
#Mann= 7 ,-1 , 0
    4515     .16       0  4692.4     .12       0  4749.4     .16       0
  4956.8     .12       0  4985.9     .07       0  4991.9     .12       0
  5122.4     .16       0
Bank Sta=4983.3,5018.6
XS Rating Curve= 0 ,0
Exp/Cntr=0.3,0.1

Type RM Length L Ch R = 1 ,6262    ,269,269,269
BEGIN DESCRIPTION:
LITTLE SANDY CREEK 13.0
END DESCRIPTION:
XS GIS Cut Line= 2
      3600937.68     10689660.91      3600234.66     10688885.17
#Sta/Elev= 30
  4476.5  293.23  4567.8  288.19  4638.8  285.78  4787.5  285.85  4865.2  282.95
  4914.5  279.31  4971.3  277.97  4985.5  276.41  4992.2  270.56  4996.7  270.34
  4999.4  269.84  5002.7  270.34  5006.4   271.1  5013.9  277.02  5020.6  277.24
  5028.1  276.67  5034.8  277.59  5056.4  277.39  5063.2  278.26  5112.5  279.21
  5153.3  278.61  5175.7   278.1  5240.3  278.89  5332.2  282.41  5417.3  287.59
  5424.1  288.87  5445.7  289.46  5488.3  293.05  5509.2  293.27  5523.4  294.63
#Mann= 5 ,-1 , 0
  4476.5     .16       0  4996.7     .07       0  5002.7     .16       0
  5153.3     .12       0  5175.7     .16       0
Bank Sta=4971.3,5020.6
XS Rating Curve= 0 ,0
Exp/Cntr=0.3,0.1

Type RM Length L Ch R = 1 ,5993    ,711,711,711
BEGIN DESCRIPTION:
LITTLE SANDY CREEK 12.0
END DESCRIPTION:
XS GIS Cut Line= 2
       3601151.1     10689532.61      3600241.92     10688484.62
#Sta/Elev= 30
  4377.1  301.61  4415.5  299.59  4458.2  295.14  4550.3   289.5  4564.6  287.69
  4693.4  280.45  4804.8  276.67  4820.6  273.51  4826.7  273.54  4840.9  276.49
  4855.2  277.07  4896.9  277.06  4925.4  274.69  4982.4  276.85  4989.3  275.89
  4993.7  269.87  4996.4  269.37  4999.7  269.87  5003.3  269.87  5017.5  276.59
  5109.6   277.4  5261.6  281.11  5365.1  285.33  5450.3  290.13    5524  294.16
  5563.6   297.1  5592.1  297.81  5627.2  301.02    5727  304.45  5764.5  307.34
#Mann= 9 ,-1 , 0
  4377.1     .16       0  4693.4     .12       0  4820.6     .16       0
  4993.7     .07       0  4999.7     .16       0  5109.6     .12       0
  5261.6     .16       0  5450.3     .12       0    5524     .16       0
Bank Sta=4982.4,5017.5
XS Rating Curve= 0 ,0
Exp/Cntr=0.3,0.1

Type RM Length L Ch R = 1 ,5282    ,556,556,556
BEGIN DESCRIPTION:
LITTLE SANDY CREEK 11.0
END DESCRIPTION:
XS GIS Cut Line= 3
      3601230.98     10689699.34      3601230.98     10689036.11
       3601012.9      10688423.4
#Sta/Elev= 30
  4189.6  298.35  4248.8  298.51  4448.8  296.11  4548.8  291.47  4694.3  281.52
  4738.8  279.06  4848.3   274.9  4859.1  274.67  4868.1   275.6  4880.3  274.67
    4944  274.87  4954.6  273.92  4986.2  274.46  4991.5  274.13  4994.1  268.92
  4996.9  268.42  5000.1  268.92  5007.7  269.55    5017  275.38  5060.8  274.14
  5145.7  273.86  5252.1  276.59  5360.4  283.78  5389.8  286.43  5407.2  286.48
  5432.3  288.83  5463.6  289.89  5468.9  290.96  5497.6  292.56  5503.2  293.29
#Mann= 7 ,-1 , 0
  4189.6     .16       0  4694.3     .12       0  4994.1     .07       0
  5000.1     .12       0  5252.1     .16       0  5360.4     .05       0
  5497.6     .16       0
Bank Sta=4986.2,5017
XS Rating Curve= 0 ,0
Exp/Cntr=0.3,0.1

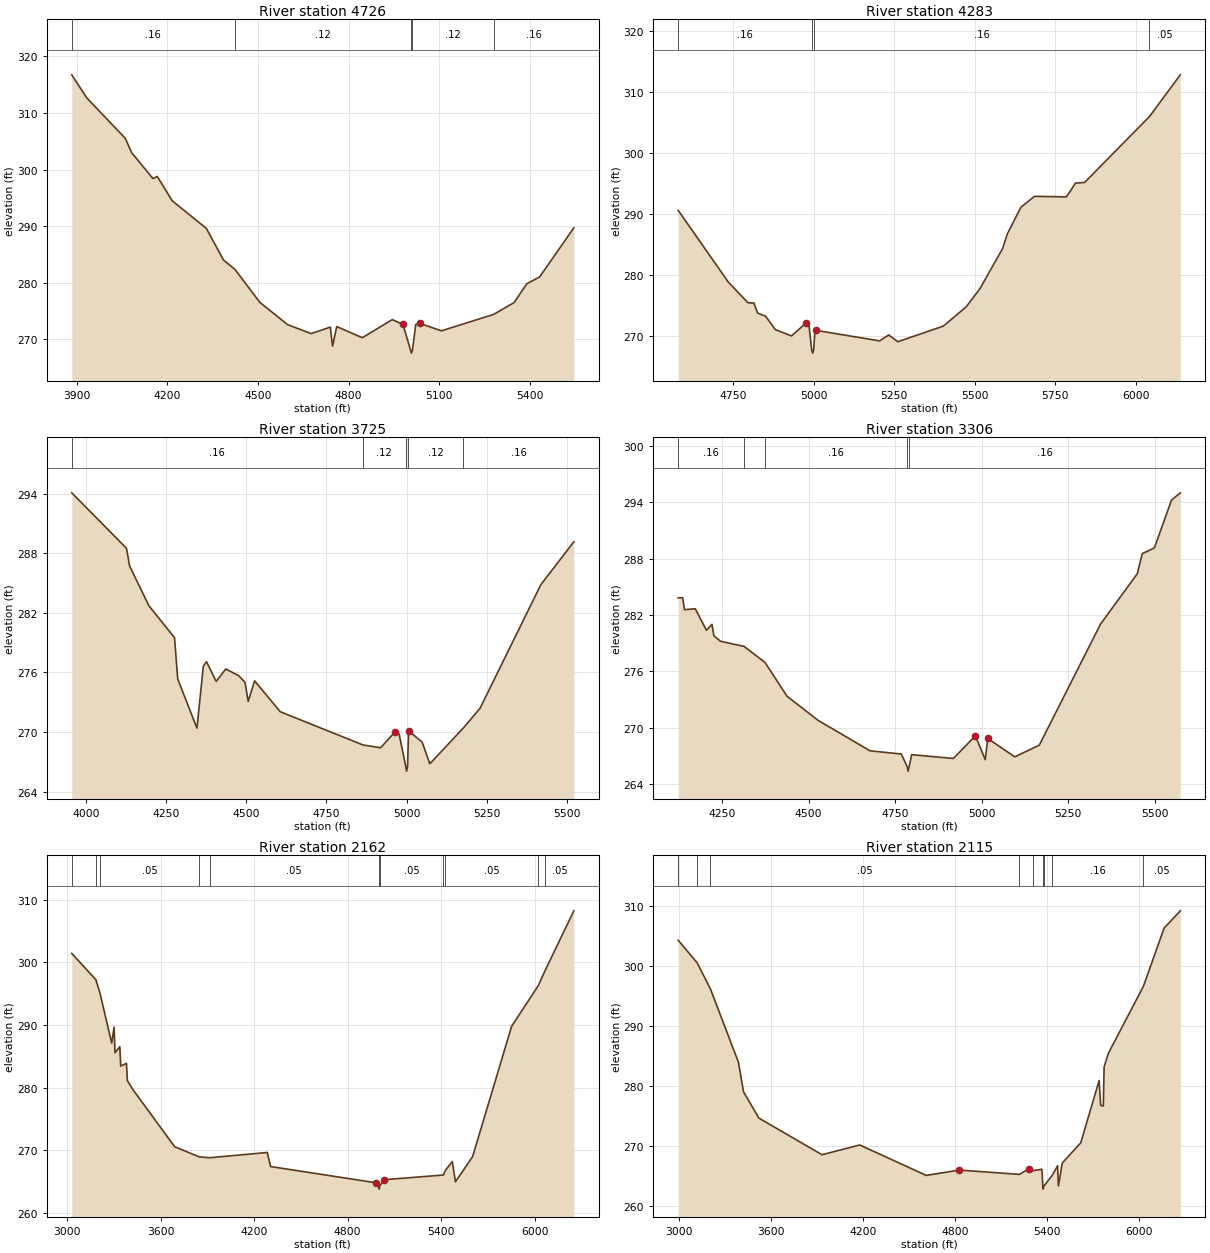
Type RM Length L Ch R = 1 ,4726    ,443,443,443
BEGIN DESCRIPTION:
LITTLE SANDY CREEK 10.0
END DESCRIPTION:
XS GIS Cut Line= 3
      3602349.61     10689610.19      3601599.61     10688810.19
      3601199.59     10688410.17
#Sta/Elev= 30
  3883.2  316.73  3932.8  312.66  4060.3  305.52  4081.3  302.99  4152.1  298.41
  4166.3  298.78  4215.6   294.5  4328.9   289.6  4385.6  284.02  4423.5  282.37
  4505.7  276.56  4597.6  272.62  4675.7  271.03  4739.2  272.17  4746.5  268.81
  4760.5  272.26  4845.2  270.31  4944.4   273.5  4979.8  272.64  5005.1  268.08
  5007.8  267.58  5011.1  268.08  5022.2  272.65  5036.4  272.82  5107.1  271.52
  5279.7  274.41  5347.5   276.5  5389.9  279.84  5432.3  281.04  5545.5  289.71
#Mann= 5 ,-1 , 0
  3883.2     .16       0  4423.5     .12       0  5005.1     .07       0
  5011.1     .12       0  5279.7     .16       0
Bank Sta=4979.8,5036.4
XS Rating Curve= 0 ,0
Exp/Cntr=0.3,0.1

Type RM Length L Ch R = 1 ,4283    ,558,558,558
BEGIN DESCRIPTION:
LITTLE SANDY CREEK 9.0
END DESCRIPTION:
XS GIS Cut Line= 3
       3602149.6     10689110.18      3601999.61     10688710.19
      3601199.58     10687910.16
#Sta/Elev= 30
  4579.9  290.55  4735.6  278.78  4796.2  275.41  4814.8  275.36  4826.4  273.71
  4851.3  273.18  4881.6  270.99  4931.4  269.96    4975     272  4985.7  271.77
  4994.3  267.64    4997  267.14  5000.3  267.64  5004.4  270.88  5007.1  270.88
  5205.1  269.15  5233.4  270.12  5261.6  269.01  5403.1  271.58  5473.8  274.73
  5516.2  277.69  5586.9   284.3  5601.1  286.64  5643.5  291.06  5685.9  292.86
  5784.9  292.77  5813.2  295.03  5841.5  295.14  6042.8  305.95  6138.5  312.79
#Mann= 4 ,-1 , 0
  4579.9     .16       0  4994.3     .07       0  5000.3     .16       0
  6042.8     .05       0
Bank Sta=4975,5007.1
XS Rating Curve= 0 ,0
Exp/Cntr=0.3,0.1

Type RM Length L Ch R = 1 ,3725    ,419,419,419
BEGIN DESCRIPTION:
LITTLE SANDY CREEK 8.0
END DESCRIPTION:
XS GIS Cut Line= 3
      3602498.16     10689330.89      3602498.16     10688560.08
      3602061.27     10687894.34
#Sta/Elev= 30
    3955  294.08  4125.7   288.5  4135.7   286.7  4195.7  282.71  4275.7   279.5
  4285.7  275.34  4345.7  270.39  4365.7  276.63  4375.7  277.07  4405.7   275.1
  4435.7  276.34  4475.7  275.68  4495.7     275  4505.7  273.08  4525.7  275.15
  4605.7  272.04  4863.5   268.7  4918.8  268.41  4964.1  270.01  4976.9  269.78
  4997.2  266.56    5000  266.06  5003.2  266.56  5006.2  270.12  5048.6  268.99
  5072.5   266.8  5177.5  270.41  5229.2  272.38  5419.2  284.84  5522.1  289.15
#Mann= 5 ,-1 , 0
    3955     .16       0  4863.5     .12       0  4997.2     .07       0
  5003.2     .12       0  5177.5     .16       0
Bank Sta=4964.1,5006.2
XS Rating Curve= 0 ,0
Exp/Cntr=0.3,0.1

Type RM Length L Ch R = 1 ,3306    ,1144,1144,1144
BEGIN DESCRIPTION:
LITTLE SANDY CREEK 7.0
END DESCRIPTION:
XS GIS Cut Line= 4
      3602769.57     10688916.16      3602672.34     10688662.64
       3602689.7     10688162.64      3602234.86      10687659.2
#Sta/Elev= 30
  4123.6  283.83  4136.4  283.84  4141.8  282.57  4172.8  282.67    4205  280.38
  4221.1  281.01  4226.5   279.8  4245.8  279.21  4313.5  278.67  4374.3  276.96
  4437.6  273.37  4527.7  270.79  4677.7  267.55  4767.8  267.21  4784.8  265.89
  4787.6  265.39  4790.8  265.89  4797.8  267.14  4918.4  266.74    4982  269.15
  5010.4  266.61  5017.8  268.87  5095.5  266.91  5166.5  268.15  5343.5  281.04
  5449.7   286.4  5463.9  288.54  5499.1  289.15  5548.4  294.23  5573.9  295.01
#Mann= 5 ,-1 , 0
  4123.6     .16       0  4313.5     .05       0  4374.3     .16       0
  4784.8     .07       0  4790.8     .16       0
Bank Sta=4982,5017.8
XS Rating Curve= 0 ,0
Exp/Cntr=0.3,0.1

Type RM Length L Ch R = 1 ,2162    ,47,47,47
BEGIN DESCRIPTION:
LITTLE SANDY CREEK 6.0
END DESCRIPTION:
XS GIS Cut Line= 6
      3603083.19     10688948.95       3602749.9     10688744.11
       3602711.7     10688605.22      3603406.15     10687476.75
      3602769.34     10687592.33      3602085.76     10687520.72
#Sta/Elev= 30
  3030.7  301.44  3185.2  297.24  3210.9  295.18  3286.7  287.11  3302.1  289.65
    3308  285.56  3338.8  286.53  3344.7  283.43  3381.4  283.86  3387.3  281.12
  3420.9  279.73  3690.8  270.53  3848.7   268.9  3915.3  268.77  4284.7  269.61
  4305.8  267.36  4980.4  264.77  4999.9  264.25  5002.7  263.75  5005.9  264.25
    5033  265.25  5414.1  266.01  5426.9  266.76  5471.2  268.16  5491.2  264.92
  5601.3  268.95  5851.6  289.79  6022.5  296.29  6065.4  298.66  6250.5  308.25
#Mann= 11 ,-1 , 0
  3030.7     .05       0  3185.2      .1       0  3210.9     .05       0
  3848.7     .16       0  3915.3     .05       0  4999.9     .04       0
  5005.9     .05       0  5414.1     .12       0  5426.9     .05       0
  6022.5      .1       0  6065.4     .05       0
Bank Sta=4980.4,5033
XS Rating Curve= 0 ,0
Exp/Cntr=0.3,0.1

Type RM Length L Ch R = 1 ,2115    ,854,854,854
BEGIN DESCRIPTION:
LITTLE SANDY CREEK 5.0
END DESCRIPTION:
XS GIS Cut Line= 6
      3603135.28     10688921.18      3602777.67     10688643.41
      3603423.51     10687563.55      3603451.28     10687417.72
      3602808.92     10687542.72       3602076.3     10687466.33
#Sta/Elev= 30
  2994.2  304.33    3118  300.57  3204.8   296.2  3387.4  283.98  3420.7  279.03
  3521.1  274.66  3933.1  268.55  4179.3  270.18  4613.3   265.1  4830.3  265.99
  5221.9  265.27  5285.6  266.23  5312.6  265.91  5368.8  266.12  5374.9  263.31
  5377.6  262.81  5380.9  263.31  5436.2  265.11  5471.5  266.71  5476.6  263.35
  5502.2  267.18  5622.5  270.54  5742.6  280.93  5752.6   276.8    5770  276.68
    5775   283.2  5802.6  285.46  6031.8  296.66  6166.9  306.37  6272.6  309.25
#Mann= 9 ,-1 , 0
  2994.2     .05       0    3118     .16       0  3204.8     .05       0
  5221.9     .16       0  5312.6     .05       0  5374.9     .04       0
  5380.9     .05       0  5436.2     .16       0  6031.8     .05       0
Bank Sta=4830.3,5285.6
XS Rating Curve= 0 ,0
Exp/Cntr=0.3,0.1

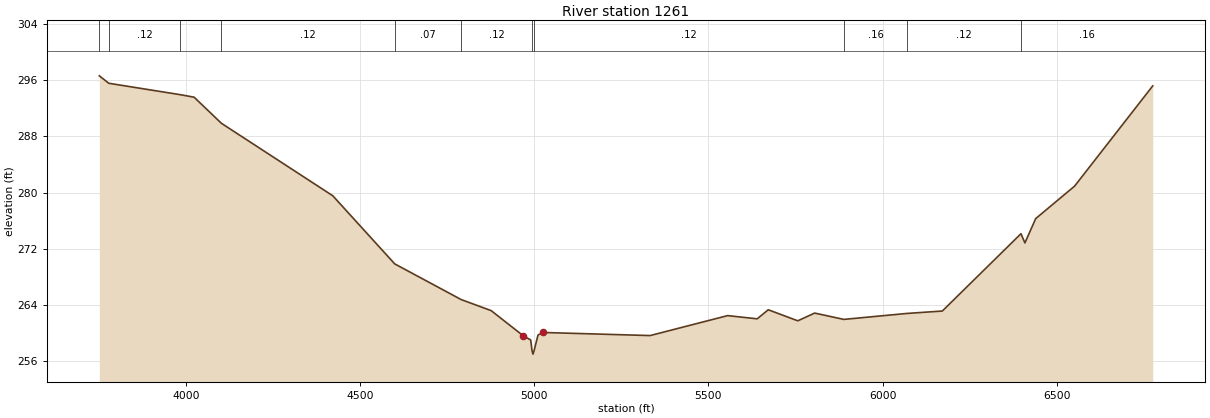
Type RM Length L Ch R = 1 ,1261    ,0,0,0
BEGIN DESCRIPTION:
LITTLE SANDY CREEK 4.0
END DESCRIPTION:
XS GIS Cut Line= 4
       3604067.6     10687969.76      3603914.83     10686879.53
      3603699.55     10686685.08      3602157.92     10687226.74
#Sta/Elev= 30
    3751  296.61  3778.2  295.55  3983.2  293.93  4023.2  293.57  4101.5  289.86
  4421.6  279.54  4599.2  269.86  4790.1  264.78  4876.2  263.21  4968.1  259.64
  4989.8  259.03  4993.5  257.52  4996.3  257.02  4999.5  257.52  5010.7  259.73
  5024.9   260.1  5332.7  259.66  5555.3   262.5  5640.1  262.04  5671.9  263.33
  5756.7  261.76  5805.2  262.86  5888.9  261.96  6070.6  262.81  6171.7  263.15
  6397.6  274.15  6408.9  272.84  6439.9   276.3  6551.6  280.92    6776  295.18
#Mann= 11 ,-1 , 0
    3751     .16       0  3778.2     .12       0  3983.2     .16       0
  4101.5     .12       0  4599.2     .07       0  4790.1     .12       0
  4993.5     .07       0  4999.5     .12       0  5888.9     .16       0
  6070.6     .12       0  6397.6     .16       0
Bank Sta=4968.1,5024.9
XS Rating Curve= 0 ,0
Exp/Cntr=0.3,0.1

Chan Stop Cuts=-1
Use User Specified Reach Order=0
Composite Channel Slope=5