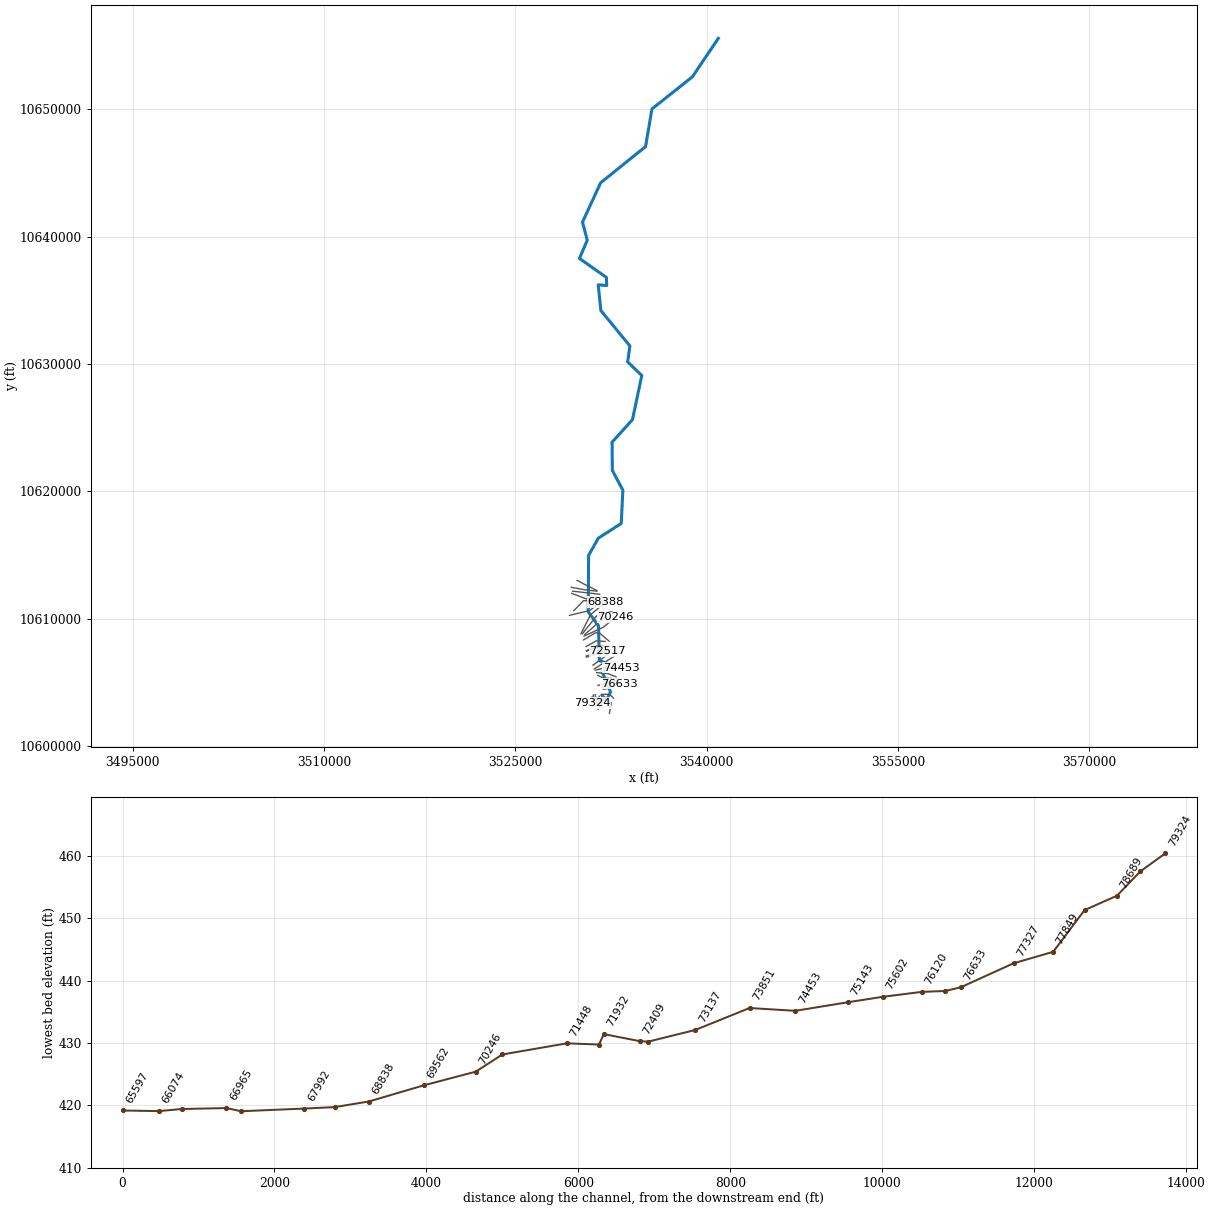
--- LITTLE TEHUACANA CREEK.prj (project) ---

Proj Title=LITTLE TEHUACANA CREEK Base Level Engineering
Current Plan=p01
Default Exp/Contr=0.3,0.1
English Units
Geom File=g01
Flow File=f01
Plan File=p01
Y Axis Title=Elevation
X Axis Title(PF)=Main Channel Distance
X Axis Title(XS)=Station
BEGIN DESCRIPTION:
LITTLE TEHUACANA CREEK
END DESCRIPTION:
DSS Export Rating Curves= 0
DSS Export Rating Curve Sorted= 0
DSS Export Volume Flow Curves= 0
DXF OffsetX= 0
DXF OffsetY= 0
DXF ScaleX= 1
DXF ScaleY= 10

--- LITTLE TEHUACANA CREEK.p01 (plan) ---

Plan Title=Multiple Run
Short Identifier=Multiple
Geom File=g01
Flow File=f01
Subcritical Flow
K Sum by GR= 0
Std Step Tol= 0.01
Critical Tol= 0.01
Num of Std Step Trials= 20
Max Error Tol= 0.3
Flow Tol Ratio= 0.001
Split Flow NTrial= 30
Split Flow Tol= 0.02
Split Flow Ratio= 0.02
Log Output Level= 0
Friction Slope Method= 1
Unsteady Friction Slope Method= 2
Unsteady Bridges Friction Slope Method= 1
Parabolic Critical Depth
Global Vel Dist=  1 , 1 , 1
Global Log Level= 0
CheckData=True
Encroach Param= -1, 0, 0, 0
BEGIN DESCRIPTION:
Multiple Run
END DESCRIPTION:

--- LITTLE TEHUACANA CREEK.f01 (steady flow) ---

Flow Title=Multiple
Program Version=4.10
Number of Profiles= 7
Profile Names=10-year,25-year,50-year,1pct_min,100-year,1pct_plu,500-year
River Rch & RM=LITTLE TEHUACANA,Reach-1         ,79324
    1215    1660    2025    1802    2437    3296    3520
River Rch & RM=LITTLE TEHUACANA,Reach-1         ,76633
    2181    3050    3778    3405    4605    6228    6828
River Rch & RM=LITTLE TEHUACANA,Reach-1         ,70246
    3263    4634    5798    5271    7129    9640   10755
River Rch & RM=LITTLE TEHUACANA,Reach-1         ,68838
    3263    4634    5798    5271    7129    9640   10755
River Rch & RM=LITTLE TEHUACANA,Reach-1         ,67992
    3979    5697    7165    6544    8850   11968   13477
River Rch & RM=LITTLE TEHUACANA,Reach-1         ,66965
    4243    6095    7684    7033    9511   12863   14548
River Rch & RM=LITTLE TEHUACANA,Reach-1         ,64302
    4243    6095    7684    7033    9511   12863   14548
River Rch & RM=LITTLE TEHUACANA,Reach-1         ,62878
    4489    6469    8172    7496   10138   13710   15572
River Rch & RM=LITTLE TEHUACANA,Reach-1         ,61700
    4675    6760    8559    7869   10641   14391   16420
River Rch & RM=LITTLE TEHUACANA,Reach-1         ,60166
    5672    8220   10425    9592   12972   17543   20044
River Rch & RM=LITTLE TEHUACANA,Reach-1         ,58616
    5672    8220   10425    9592   12972   17543   20044
River Rch & RM=LITTLE TEHUACANA,Reach-1         ,57613
    5672    8220   10425    9592   12972   17543   20044
River Rch & RM=LITTLE TEHUACANA,Reach-1         ,52460
    5833    8443   10696    9828   13292   17976   20487
River Rch & RM=LITTLE TEHUACANA,Reach-1         ,51499
    5833    8443   10696    9828   13292   17976   20487
River Rch & RM=LITTLE TEHUACANA,Reach-1         ,48445
    6176    8946   11339   10422   14094   19061   21735
River Rch & RM=LITTLE TEHUACANA,Reach-1         ,46624
    6176    8946   11339   10422   14094   19061   21735
River Rch & RM=LITTLE TEHUACANA,Reach-1         ,42532
    6898   10052   12797   11811   15973   21602   24839
River Rch & RM=LITTLE TEHUACANA,Reach-1         ,40675
    6898   10052   12797   11811   15973   21602   24839
River Rch & RM=LITTLE TEHUACANA,Reach-1         ,32247
    7084   10299   13088   12056   16305   22050   25253
River Rch & RM=LITTLE TEHUACANA,Reach-1         ,29558
    7350   10671   13547   12464   16856   22796   26041
Boundary for River Rch & Prof#=LITTLE TEHUACANA,Reach-1         , 1
Up Type= 0
Dn Type= 3
Dn Slope=0.00123
Boundary for River Rch & Prof#=LITTLE TEHUACANA,Reach-1         , 2
Up Type= 0
Dn Type= 3
Dn Slope=0.00123
Boundary for River Rch & Prof#=LITTLE TEHUACANA,Reach-1         , 3
Up Type= 0
Dn Type= 3
Dn Slope=0.00123
Boundary for River Rch & Prof#=LITTLE TEHUACANA,Reach-1         , 4
Up Type= 0
Dn Type= 3
Dn Slope=0.00123
Boundary for River Rch & Prof#=LITTLE TEHUACANA,Reach-1         , 5
Up Type= 0
Dn Type= 3
Dn Slope=0.00123
Boundary for River Rch & Prof#=LITTLE TEHUACANA,Reach-1         , 6
Up Type= 0
Dn Type= 3
Dn Slope=0.00123
Boundary for River Rch & Prof#=LITTLE TEHUACANA,Reach-1         , 7
Up Type= 0
Dn Type= 3
Dn Slope=0.00123
DSS Import GetInterval= 0
DSS Import GetPeak= 0
DSS Import FillOption= 0

--- LITTLE TEHUACANA CREEK.g01 (geometry) ---

Geom Title=Existing Conditions
Program Version=4.10

River Reach=LITTLE TEHUACANA,Reach-1
Reach XY= 30
      3531037.62     10603768.39       3532166.5       10603638.
        3532470.       10604242.       3531849.5       10605728.
      3532363.75       10606440.        3531592.       10606709.
        3531526.       10609442.      3530722.25       10610528.
      3530750.25       10614965.        3531507.       10616317.
      3533308.25       10617476.      3533435.75       10620095.
      3532610.25       10621640.       3532589.5       10623855.
      3534187.25       10625621.       3534919.5       10629091.
      3533810.75       10630160.      3533984.25       10631413.
       3531709.5       10634193.      3531504.75       10636209.
       3532166.5       10636154.      3532147.25       10636789.
        3530032.       10638282.      3530643.83     10639709.44
      3530271.75       10641139.       3531695.5       10644221.
       3535215.5       10647061.      3535714.25       10650013.
      3538881.75       10652534.       3540919.5       10655560.

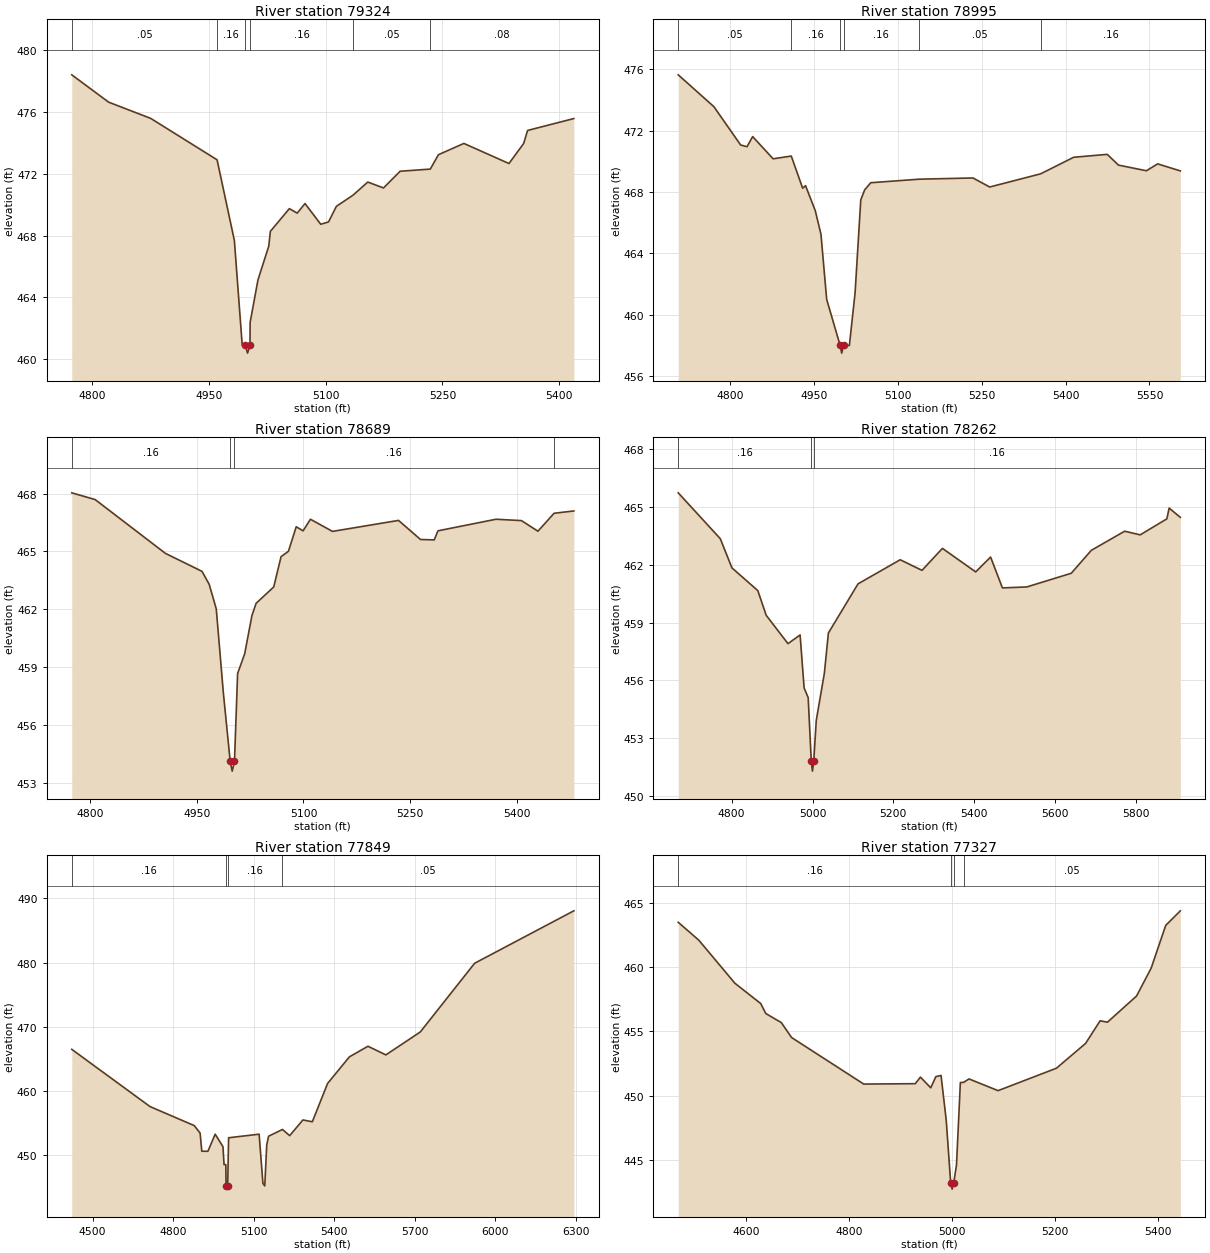
Type RM Length L Ch R = 1 ,79324   ,329,329,329
BEGIN DESCRIPTION:
LITTLE TEHUACANA CREEK 101.0
END DESCRIPTION:
XS GIS Cut Line= 3
      3531127.75     10604017.19      3531094.18     10603764.42
      3531047.31     10603377.54
#Sta/Elev= 30
  4774.1   478.4  4821.5  476.63  4875.5  475.58  4960.7   472.9  4982.9  467.68
    4993  460.89    4997  460.89  4999.8  460.39    5003  460.89  5003.1  462.37
  5013.2  465.13  5027.1  467.32  5029.1  468.27  5053.5  469.74  5063.6  469.45
  5073.6  470.07  5093.8  468.73  5103.8  468.88  5113.9  469.89  5135.2  470.61
  5154.2  471.46  5174.4  471.08  5195.7  472.16  5234.5   472.3  5244.9  473.23
  5277.6  473.96  5335.5  472.66  5354.4  473.96  5359.4   474.8  5418.8  475.57
#Mann= 6 ,-1 , 0
  4774.1     .05       0  4960.7     .16       0    4997     .07       0
    5003     .16       0  5135.2     .05       0  5234.5     .08       0
Bank Sta=4997,5003
XS Rating Curve= 0 ,0
Exp/Cntr=0.3,0.1

Type RM Length L Ch R = 1 ,78995   ,306,306,306
BEGIN DESCRIPTION:
Mapping XS 0055807e
END DESCRIPTION:
XS GIS Cut Line= 3
      3531273.58      10604031.1       3531336.7     10603690.22
      3531359.81     10603139.68
#Sta/Elev= 30
  4707.5  475.65  4771.3  473.57  4819.1  471.07  4830.5  470.96  4840.6  471.62
  4877.1  470.17  4909.6  470.35    4930  468.25  4935.1  468.42  4952.5  466.79
  4962.7  465.25  4972.9     461    4997  457.99  4999.8  457.49    5003  457.99
  5013.5  457.99  5023.7  461.42  5033.9  467.49  5040.8  468.14  5051.7  468.61
  5138.4  468.84  5234.4  468.92  5264.4  468.33  5355.5  469.19  5414.5  470.27
  5474.6  470.46  5494.6  469.76  5544.6  469.39  5564.7  469.84  5605.2  469.38
#Mann= 6 ,-1 , 0
  4707.5     .05       0  4909.6     .16       0    4997     .07       0
    5003     .16       0  5138.4     .05       0  5355.5     .16       0
Bank Sta=4997,5003
XS Rating Curve= 0 ,0
Exp/Cntr=0.3,0.1

Type RM Length L Ch R = 1 ,78689   ,427,427,427
BEGIN DESCRIPTION:
Mapping XS c92e2259
END DESCRIPTION:
XS GIS Cut Line= 3
      3531582.61     10603913.01      3531567.23     10603653.39
      3531457.04     10603221.29
#Sta/Elev= 30
  4774.2  468.04  4807.1  467.69  4905.9   464.9  4957.3  463.97  4967.4   463.3
  4977.4  462.02  4987.4  457.65    4997  454.11  4999.8  453.61    5003  454.11
  5007.4  458.67  5017.4   459.7  5027.5  461.67  5033.4  462.31  5058.2  463.16
  5068.5  464.73  5078.9  465.01  5089.8  466.28  5099.5  466.07  5109.8  466.67
  5140.8  466.04  5233.7  466.61  5264.6  465.62  5283.9   465.6  5289.1  466.07
  5370.8  466.67  5406.5   466.6  5429.7  466.05  5452.4  466.98  5480.2   467.1
#Mann= 4 ,-1 , 0
  4774.2     .16       0    4997     .07       0    5003     .16       0
  5452.4     .05       0
Bank Sta=4997,5003
XS Rating Curve= 0 ,0
Exp/Cntr=0.3,0.1

Type RM Length L Ch R = 1 ,78262   ,413,413,413
BEGIN DESCRIPTION:
LITTLE TEHUACANA CREEK 100.0
END DESCRIPTION:
XS GIS Cut Line= 4
      3531728.42     10603965.12      3531888.17     10603767.17
      3531884.69     10603603.98       3531499.2     10602875.48
#Sta/Elev= 30
  4667.9  465.73    4772  463.35  4800.7  461.84  4864.7  460.66  4885.5  459.38
  4939.3  457.91  4969.3  458.36  4979.3  455.61  4989.3  455.11    4997   451.8
  4999.8   451.3    5003   451.8  5009.3  453.93  5029.3  456.37  5039.3  458.46
  5112.6  461.01  5216.9  462.26  5270.8  461.71  5321.3  462.85  5403.6  461.63
  5440.5   462.4  5469.7   460.8    5530  460.85    5640  461.56  5689.7  462.75
  5772.1  463.74  5810.4  463.55  5876.4  464.38  5882.1  464.94  5909.7  464.46
#Mann= 3 ,-1 , 0
  4667.9     .16       0    4997     .07       0    5003     .16       0
Bank Sta=4997,5003
XS Rating Curve= 0 ,0
Exp/Cntr=0.3,0.1

Type RM Length L Ch R = 1 ,77849   ,522,522,522
BEGIN DESCRIPTION:
LITTLE TEHUACANA CREEK 99.0
END DESCRIPTION:
XS GIS Cut Line= 4
      3531749.59      10604060.2      3532199.61     10603710.19
       3532521.2     10603420.75        3532382.     10602565.58
#Sta/Elev= 30
  4422.6  466.44    4714   457.5  4878.7  454.53  4900.4  453.36  4906.7  450.53
  4929.4  450.52  4956.5  453.19  4985.5  451.24  4989.5  448.44  4996.1  448.44
    4997  445.11  4999.8  444.61    5003  445.11  5006.5  452.63  5120.1  453.19
  5134.3   445.5  5141.1  445.11  5148.5  451.52  5155.3  452.87    5207  453.93
  5233.8  452.96  5283.1  455.41  5318.2  455.13    5375  461.11  5456.3  465.27
  5525.4  466.92    5592  465.57  5720.1  469.15  5922.4  479.88  6291.8  488.07
#Mann= 4 ,-1 , 0
  4422.6     .16       0    4997     .07       0    5003     .16       0
    5207     .05       0
Bank Sta=4997,5003
XS Rating Curve= 0 ,0
Exp/Cntr=0.3,0.1

Type RM Length L Ch R = 1 ,77327   ,694,694,694
BEGIN DESCRIPTION:
LITTLE TEHUACANA CREEK 98.0
END DESCRIPTION:
XS GIS Cut Line= 3
      3531849.59     10604060.19      3532399.61     10604060.19
      3532699.62     10603760.18
#Sta/Elev= 30
  4468.3  463.47  4508.3  462.08  4578.3  458.74  4628.3  457.17  4638.3  456.39
  4668.3  455.69  4688.3  454.53  4828.3  450.92  4928.3  450.95  4938.3  451.46
  4958.3  450.63  4968.3   451.5  4978.3  451.59  4988.3  448.14    4997  443.27
  4999.8  442.77    5003  443.27  5008.3  444.66  5015.8  451.04  5022.1  451.05
  5032.5  451.32    5089  450.41  5202.2  452.15  5258.7  454.07    5287  455.83
  5301.2  455.72  5357.7  457.75    5386  459.91  5414.3  463.23  5442.6  464.36
#Mann= 4 ,-1 , 0
  4468.3     .16       0    4997     .07       0    5003     .16       0
  5022.1     .05       0
Bank Sta=4997,5003
XS Rating Curve= 0 ,0
Exp/Cntr=0.3,0.1

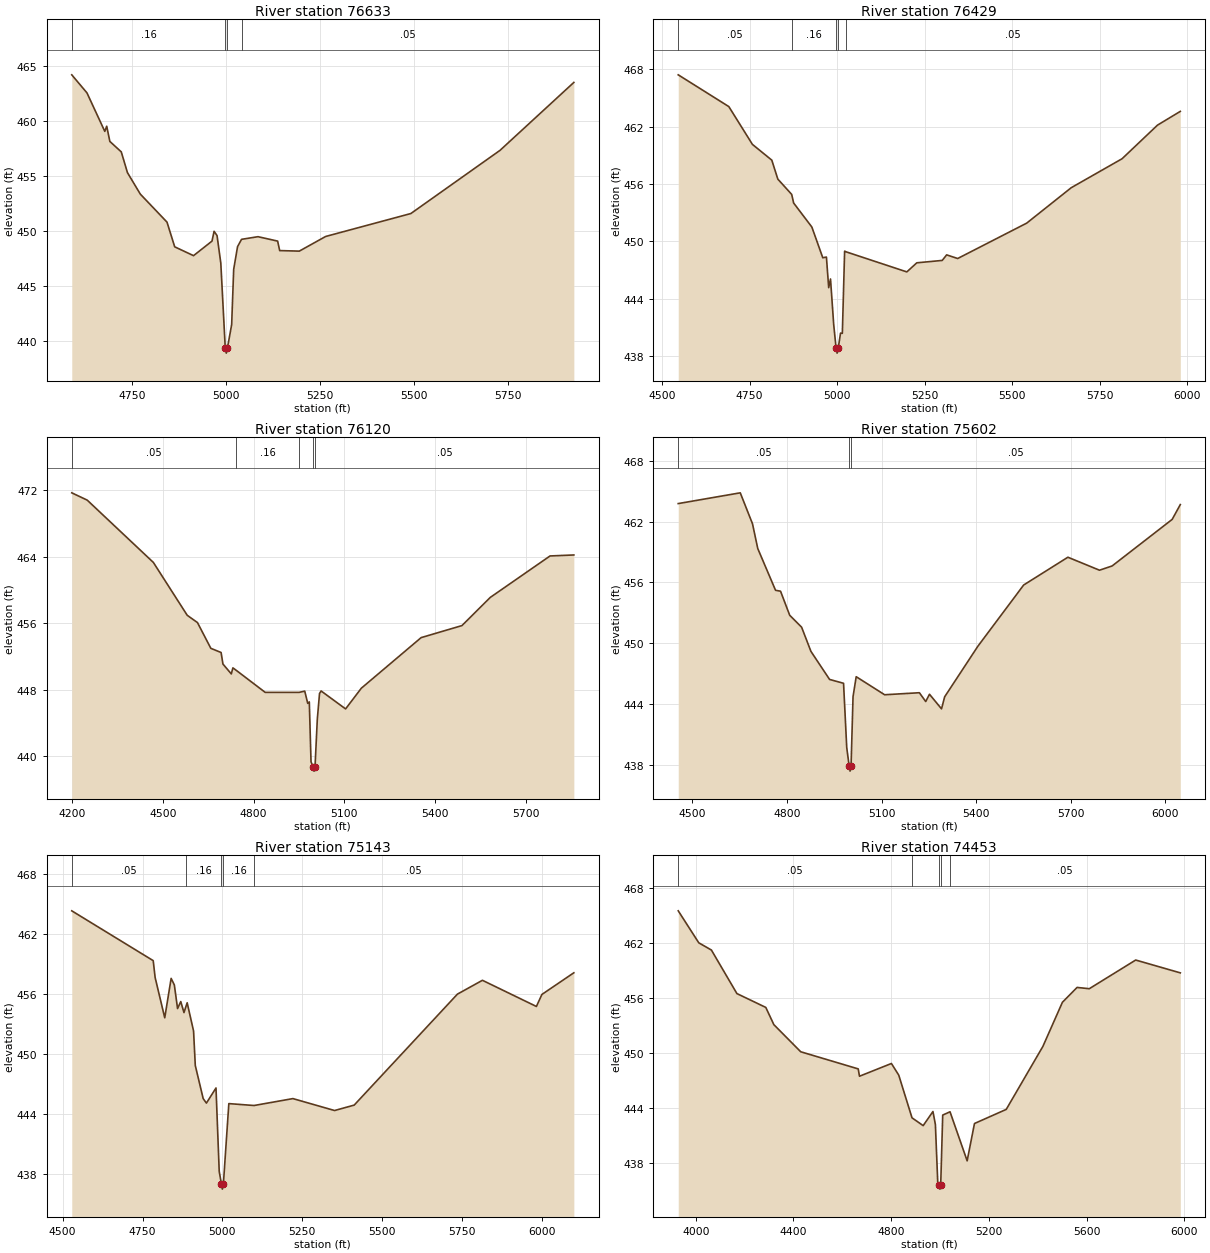
Type RM Length L Ch R = 1 ,76633   ,204,204,204
BEGIN DESCRIPTION:
LITTLE TEHUACANA CREEK 97.0
END DESCRIPTION:
XS GIS Cut Line= 3
      3531899.66      10604460.2      3532261.98     10604521.65
      3533149.57     10604910.17
#Sta/Elev= 30
  4588.5  464.17    4629  462.53  4676.4  459.04  4681.5  459.51  4689.9  458.13
  4720.3  457.18  4736.7   455.3    4771  453.35    4842  450.81  4862.5  448.57
  4912.6  447.77  4961.8  449.09  4967.3  449.98  4975.2  449.59  4985.2   447.1
    4997  439.43  4999.8  438.93    5003  439.43  5014.1  441.52  5019.5  446.53
  5029.8  448.59  5040.4  449.25  5084.2  449.49  5136.5  449.09  5141.9  448.23
  5194.1  448.18  5264.3  449.51  5491.1  451.59  5728.4  457.32  5924.9  463.48
#Mann= 4 ,-1 , 0
  4588.5     .16       0    4997     .07       0    5003     .16       0
  5040.4     .05       0
Bank Sta=4997,5003
XS Rating Curve= 0 ,0
Exp/Cntr=0.3,0.1

Type RM Length L Ch R = 1 ,76429   ,309,309,309
BEGIN DESCRIPTION:
LITTLE TEHUACANA CREEK 96.0
END DESCRIPTION:
XS GIS Cut Line= 2
      3531752.73     10604576.19      3533131.23     10604972.03
#Sta/Elev= 30
    4546  467.42  4690.5   464.1  4757.9  460.15  4813.3   458.5  4830.5  456.52
  4870.1  454.92  4875.7  454.02  4927.7  451.51  4958.9   448.3  4969.3  448.37
  4975.8  445.17    4981  446.08  4990.1  441.31    4997  438.83  4999.8  438.33
    5003  438.83  5009.6  440.42  5014.8   440.4  5021.3  448.99  5025.3  448.92
    5199  446.82  5227.5  447.77  5300.1  448.02  5312.7   448.6  5344.3  448.22
  5541.5  451.92  5668.6  455.62  5813.9  458.65    5915  462.16  5980.2   463.6
#Mann= 5 ,-1 , 0
    4546     .05       0  4870.1     .16       0    4997     .07       0
    5003     .16       0  5025.3     .05       0
Bank Sta=4997,5003
XS Rating Curve= 0 ,0
Exp/Cntr=0.3,0.1

Type RM Length L Ch R = 1 ,76120   ,518,518,518
BEGIN DESCRIPTION:
LITTLE TEHUACANA CREEK 95.0
END DESCRIPTION:
XS GIS Cut Line= 2
       3531488.9     10604760.23      3533085.32     10605214.87
#Sta/Elev= 30
  4198.8  471.69  4249.9  470.81  4468.6  463.31  4580.5  456.95  4614.4  456.07
  4658.6  452.97  4692.5  452.47  4698.6  451.08  4726.3  449.89  4731.5  450.62
  4742.7  450.32  4838.3  447.67  4950.4  447.67    4969  447.82  4978.9  446.35
  4984.1  446.52  4989.8  439.31    4997  438.69  4999.8  438.19    5003  438.69
  5010.6  444.45  5017.9  447.53  5023.1  447.84  5104.1  445.68  5156.1  448.17
  5353.8  454.26  5488.8  455.71  5582.4   459.1    5780  464.09  5858.7  464.21
#Mann= 5 ,-1 , 0
  4198.8     .05       0  4742.7     .16       0  4950.4     .05       0
    4997     .03       0    5003     .05       0
Bank Sta=4997,5003
XS Rating Curve= 0 ,0
Exp/Cntr=0.3,0.1

Type RM Length L Ch R = 1 ,75602   ,459,459,459
BEGIN DESCRIPTION:
Mapping XS 13ba7c99
END DESCRIPTION:
XS GIS Cut Line= 3
      3531464.53     10605551.91      3531867.33     10605347.03
      3533005.39     10605274.17
#Sta/Elev= 30
  4454.9  463.77  4651.6  464.83  4690.4  461.78  4707.1  459.34  4763.5  455.22
  4779.4  455.13  4808.4  452.76  4846.2  451.58  4875.7   449.2  4934.9  446.43
  4979.2  446.05  4989.3  439.71    4997  437.89  4999.8  437.39    5003  437.89
  5009.3  444.74  5019.3   446.7  5109.5  444.92  5219.7  445.12  5239.8  444.25
  5251.7  444.97  5289.9  443.53  5299.9  444.72  5405.1   449.7  5550.4  455.74
  5690.7  458.48  5790.9   457.2    5831  457.62  6021.4  462.21  6047.2  463.67
#Mann= 3 ,-1 , 0
  4454.9     .05       0    4997     .03       0    5003     .05       0
Bank Sta=4997,5003
XS Rating Curve= 0 ,0
Exp/Cntr=0.3,0.1

Type RM Length L Ch R = 1 ,75143   ,690,690,690
BEGIN DESCRIPTION:
LITTLE TEHUACANA CREEK 94.0
END DESCRIPTION:
XS GIS Cut Line= 3
      3531379.44     10605764.28       3532243.2     10605699.17
      3532898.55     10605438.77
#Sta/Elev= 30
  4528.5  464.28  4783.4  459.31  4789.4  457.63  4819.5  453.61  4839.5  457.54
  4849.6  456.88  4859.6  454.53  4869.6  455.23  4879.7  454.13    4885  454.65
  4889.7  455.11  4909.7  452.29  4915.1  448.85  4939.8  445.55  4949.9   445.1
  4979.9  446.61    4990  438.29    4997  437.02  4999.8  436.52    5003  437.02
  5020.1  445.05  5098.9  444.86  5220.6  445.55    5351  444.36  5412.4   444.9
  5735.5  455.97  5813.8  457.35  5982.7  454.74    6000  455.94  6099.9   458.1
#Mann= 5 ,-1 , 0
  4528.5     .05       0    4885     .16       0    4997     .07       0
    5003     .16       0  5098.9     .05       0
Bank Sta=4997,5003
XS Rating Curve= 0 ,0
Exp/Cntr=0.3,0.1

Type RM Length L Ch R = 1 ,74453   ,602,602,602
BEGIN DESCRIPTION:
LITTLE TEHUACANA CREEK 93.0
END DESCRIPTION:
XS GIS Cut Line= 3
      3531279.63     10605942.22      3532013.17     10606163.58
      3533302.19     10606150.56
#Sta/Elev= 30
  3928.5  465.52  4012.6  462.03  4064.3  461.24  4168.7  456.49  4286.9  454.98
  4319.9   453.1  4429.9  450.14  4665.3  448.27  4670.5  447.47  4801.2  448.86
  4831.2  447.59  4885.5  442.93  4931.2  442.08  4971.2  443.62  4981.2   442.2
  4991.2  435.65    4997  435.65  4999.8  435.15    5003  435.65  5011.2  443.23
  5041.1  443.59  5111.2  438.24  5141.2  442.31  5271.2  443.85  5421.2  450.72
  5501.2  455.54  5561.2  457.16  5611.2  457.02  5801.2  460.15  5983.8  458.75
#Mann= 5 ,-1 , 0
  3928.5     .05       0  4885.5     .16       0    4997     .07       0
    5003     .16       0  5041.1     .05       0
Bank Sta=4997,5003
XS Rating Curve= 0 ,0
Exp/Cntr=0.3,0.1

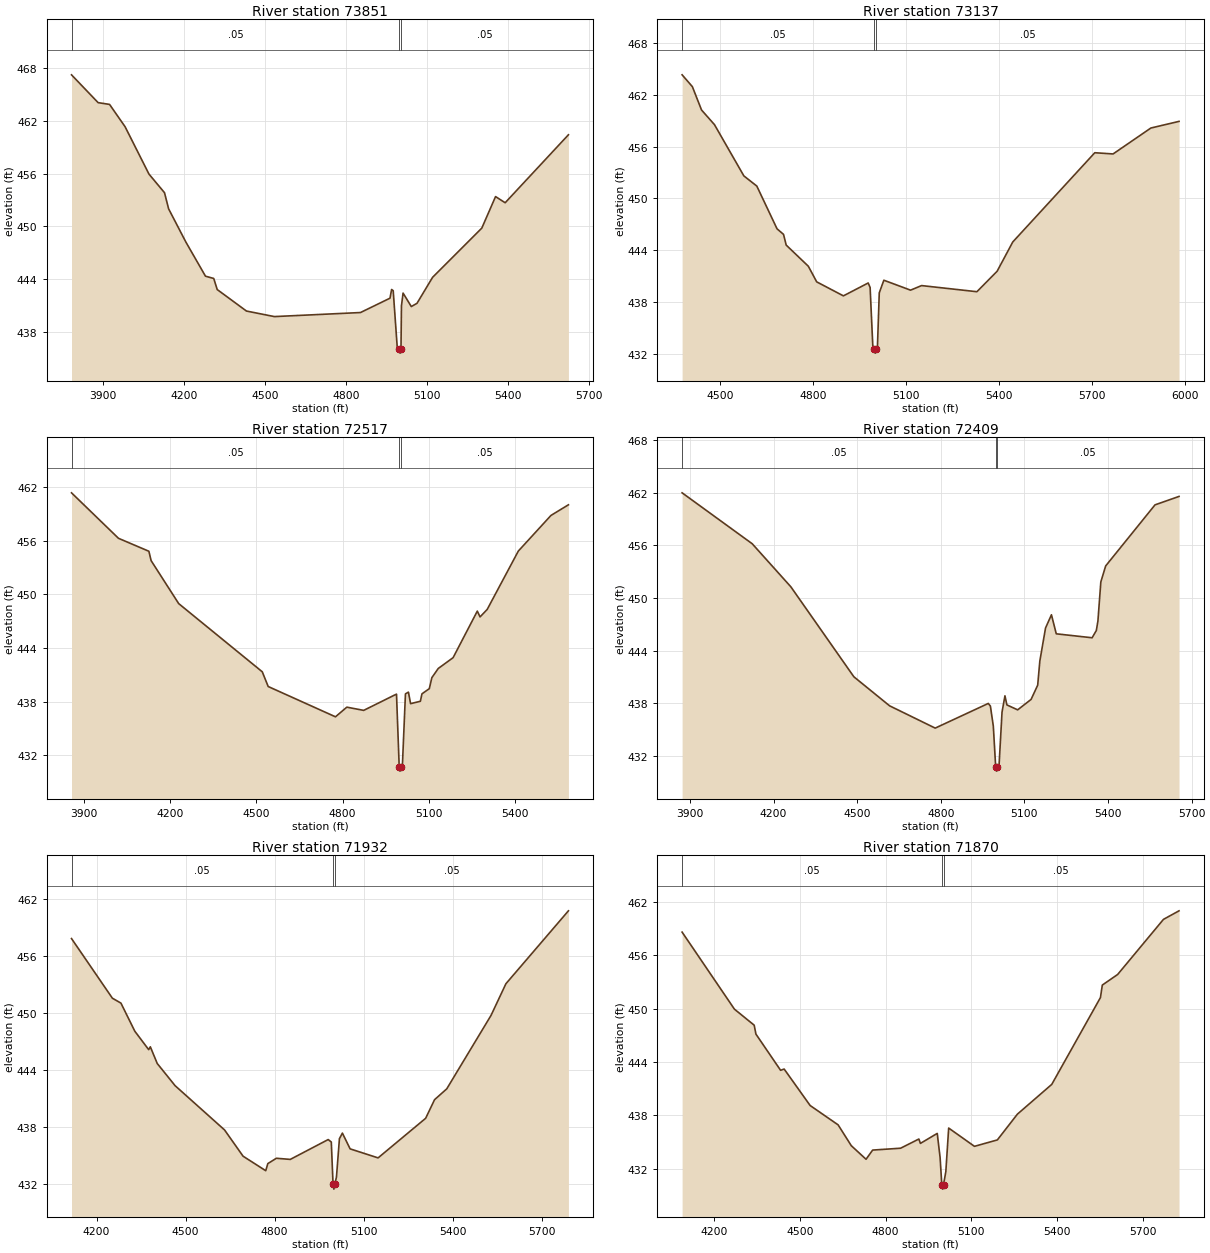
Type RM Length L Ch R = 1 ,73851   ,714,714,714
BEGIN DESCRIPTION:
LITTLE TEHUACANA CREEK 92.0
END DESCRIPTION:
XS GIS Cut Line= 2
      3531184.17     10606050.73      3532737.36     10607035.57
#Sta/Elev= 30
  3783.6  467.21  3882.1  464.05  3924.4  463.85    3982  461.31  4070.2  455.94
  4127.8  453.82    4143  451.99  4206.6  448.23  4279.4  444.34    4310  444.08
  4322.9  442.82  4431.1  440.38  4534.5  439.75  4853.1  440.21  4962.3  441.84
  4968.3  442.83  4974.2  442.69  4989.5   436.1    4997   436.1  4999.8   435.6
    5003   436.1  5004.7  440.96  5010.7  442.42  5041.2  440.89  5062.3  441.26
    5120  444.21  5302.1   449.8    5353  453.38  5388.6  452.68  5622.7   460.4
#Mann= 3 ,-1 , 0
  3783.6     .05       0    4997     .03       0    5003     .05       0
Bank Sta=4997,5003
XS Rating Curve= 0 ,0
Exp/Cntr=0.3,0.1

Type RM Length L Ch R = 1 ,73137   ,620,620,620
BEGIN DESCRIPTION:
LITTLE TEHUACANA CREEK 90.0
END DESCRIPTION:
XS GIS Cut Line= 2
      3531085.99     10606347.19      3532391.81     10607275.57
#Sta/Elev= 30
  4377.1   464.3  4410.2  462.93  4439.7  460.23  4481.5  458.53  4576.2   452.6
    4618  451.42  4683.2  446.47  4704.1  445.83  4712.7  444.59  4784.1  442.14
  4811.1  440.33  4897.2  438.71  4977.1   440.2  4983.3  439.68  4991.9  432.96
    4997  432.58  4999.8  432.08    5003  432.58  5006.7  432.58  5012.8  439.06
  5027.6  440.52  5113.7  439.37  5149.3   439.9  5327.6  439.19  5392.8  441.56
  5443.3  444.95  5707.7  455.28  5766.7  455.14  5888.5  458.14  5979.3  458.91
#Mann= 3 ,-1 , 0
  4377.1     .05       0    4997     .03       0    5003     .05       0
Bank Sta=4997,5003
XS Rating Curve= 0 ,0
Exp/Cntr=0.3,0.1

Type RM Length L Ch R = 1 ,72517   ,108,108,108
BEGIN DESCRIPTION:
LITTLE TEHUACANA CREEK 88.0
END DESCRIPTION:
XS GIS Cut Line= 2
      3530580.33     10606980.86      3532245.84     10607440.61
#Sta/Elev= 30
  3857.6  461.36  4020.9  456.27  4126.6  454.82  4134.4  453.77  4230.3  448.96
  4520.8  441.33  4541.5  439.68  4775.4  436.29  4814.9  437.37  4873.5  437.01
  4987.6  438.83    4997  430.71  4999.8  430.21    5003  430.71  5008.4  431.06
  5018.7  438.86  5029.1  439.05  5036.6  437.76  5070.6  438.03  5076.1  438.86
  5101.7  439.44  5110.5  440.67  5132.8   441.7  5184.4  442.91  5268.6  448.12
  5278.1  447.47    5303  448.31  5411.2  454.84  5524.7  458.83  5585.4  460.02
#Mann= 3 ,-1 , 0
  3857.6     .05       0    4997     .03       0    5003     .05       0
Bank Sta=4997,5003
XS Rating Curve= 0 ,0
Exp/Cntr=0.3,0.1

Type RM Length L Ch R = 1 ,72409   ,477,477,477
BEGIN DESCRIPTION:
Mapping XS 9c68cc65
END DESCRIPTION:
XS GIS Cut Line= 2
      3530558.59     10607065.58      3532268.72     10607569.07
#Sta/Elev= 30
  3872.1  461.98  4123.6  456.18  4262.1  451.28  4488.2  441.03  4616.4  437.72
  4780.1  435.18  4970.6  437.99  4978.1  437.69  4988.6   435.4    4997  430.78
  4999.8  430.28    5003  430.78  5009.4  431.07  5019.8  436.99  5030.3  438.86
  5037.3  437.82  5075.9  437.26  5124.1  438.45  5147.8  440.07  5155.4  442.81
  5175.9  446.58  5197.1  448.09  5214.4  445.92    5343  445.47  5358.2   446.3
  5363.8  447.37  5374.3  451.83  5391.6  453.65  5568.7  460.61  5654.8  461.57
#Mann= 3 ,-1 , 0
  3872.1     .05       0    4997     .03       0    5003     .05       0
Bank Sta=4997,5003
XS Rating Curve= 0 ,0
Exp/Cntr=0.3,0.1

Type RM Length L Ch R = 1 ,71932   ,62,62,62
BEGIN DESCRIPTION:
LITTLE TEHUACANA CREEK 87.0
END DESCRIPTION:
XS GIS Cut Line= 3
      3530599.87     10607439.35      3531399.87     10607789.36
      3532199.89     10607739.35
#Sta/Elev= 30
  4115.5  457.81  4253.2  451.53  4282.1  451.01  4328.9  448.05  4375.6  446.11
  4381.1  446.41  4404.5  444.65  4464.5  442.32  4631.4  437.65  4693.7  434.89
  4770.1  433.36  4777.2  434.11    4806  434.67  4852.8  434.55  4980.6  436.64
  4991.1  436.38    4997  431.92  4999.8  431.42    5003  431.92  5008.5   432.7
  5018.5  436.73  5028.5  437.32  5054.5  435.66  5148.8  434.71  5309.1  438.88
  5339.1  440.84  5380.2  441.98  5529.5  449.72  5579.6  453.05  5790.3  460.73
#Mann= 3 ,-1 , 0
  4115.5     .05       0    4997     .03       0    5003     .05       0
Bank Sta=4997,5003
XS Rating Curve= 0 ,0
Exp/Cntr=0.3,0.1

Type RM Length L Ch R = 1 ,71870   ,422,422,422
BEGIN DESCRIPTION:
Mapping XS 76396687
END DESCRIPTION:
XS GIS Cut Line= 4
       3530574.2     10607491.32      3531367.62      10607850.7
      3531450.95      10607850.7      3532233.95     10607796.88
#Sta/Elev= 30
  4088.1  458.57  4271.2  449.93  4340.4  448.13  4346.5  447.13  4432.8  443.07
  4445.3  443.21  4536.2  439.12  4634.1  436.95  4680.3  434.61  4731.9  433.09
    4755  434.12  4852.9  434.33  4916.7  435.36  4922.2  434.87  4981.1  435.99
  4991.1  433.27    4997  430.24  4999.8  429.74    5003  430.24  5011.1  431.69
  5021.1  436.59  5111.3  434.54  5191.5  435.26  5261.6  438.15  5381.9  441.49
  5552.3  451.23  5558.8  452.63  5612.5  453.82  5772.8     460  5827.3  460.96
#Mann= 3 ,-1 , 0
  4088.1     .05       0    4997     .03       0    5003     .05       0
Bank Sta=4997,5003
XS Rating Curve= 0 ,0
Exp/Cntr=0.3,0.1

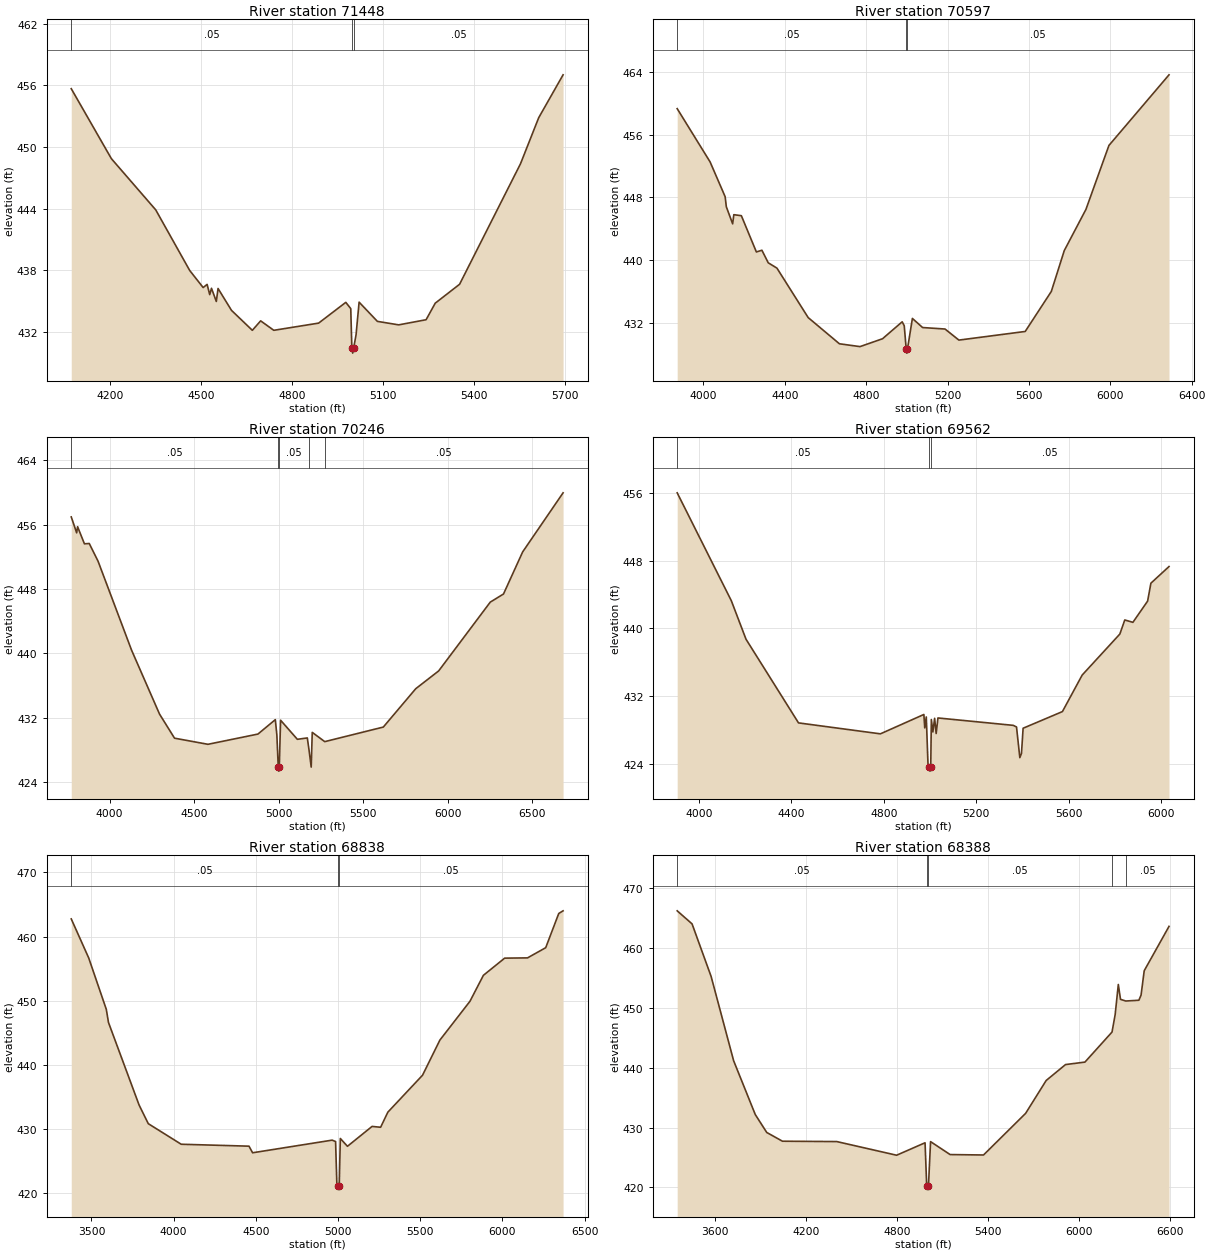
Type RM Length L Ch R = 1 ,71448   ,851,851,851
BEGIN DESCRIPTION:
LITTLE TEHUACANA CREEK 86.0
END DESCRIPTION:
XS GIS Cut Line= 3
      3530549.64      10607810.2      3531349.61     10608260.19
      3532049.58     10608210.19
#Sta/Elev= 30
    4073  455.67  4205.2  448.86  4351.2  443.88  4463.1  437.98  4507.4  436.32
  4520.4  436.63    4529  435.63  4534.8  436.25  4550.7  434.97  4556.4  436.23
  4600.7   434.1  4669.3  432.16  4696.7  433.08    4740  432.16  4887.6  432.86
  4977.1  434.88  4993.4  434.27    4997  430.44  4999.8  429.94    5003  430.44
  5010.9  431.73  5020.9   434.9  5081.1  433.03  5151.3  432.69  5241.5  433.19
  5271.6   434.8  5351.8  436.64  5552.3  448.36  5612.4  452.85  5692.6  457.02
#Mann= 3 ,-1 , 0
    4073     .05       0    4997     .03       0    5003     .05       0
Bank Sta=4997,5003
XS Rating Curve= 0 ,0
Exp/Cntr=0.3,0.1

Type RM Length L Ch R = 1 ,70597   ,351,351,351
BEGIN DESCRIPTION:
LITTLE TEHUACANA CREEK 85.0
END DESCRIPTION:
XS GIS Cut Line= 4
      3530353.91     10608333.11      3531256.72      10608874.8
      3531576.16     10608902.58      3532367.85     10608222.01
#Sta/Elev= 30
  3871.2   459.3    4033  452.51  4106.9  448.08  4112.7   446.8  4143.8  444.62
  4149.6  445.79  4186.6  445.66  4260.4  441.04  4287.6  441.26  4318.7  439.66
  4361.5  438.98    4515  432.68  4668.6  429.34  4769.7  428.98  4880.4  429.98
  4977.1  432.14  4987.2  431.64    4997  428.65  4999.8  428.15    5003  428.65
  5027.3  432.57  5077.5  431.41  5187.9  431.22  5255.9  429.81  5581.8  430.91
  5710.2  436.01  5773.9  441.22  5880.3  446.46  5993.3  454.61  6288.7  463.61
#Mann= 3 ,-1 , 0
  3871.2     .05       0    4997     .03       0    5003     .05       0
Bank Sta=4997,5003
XS Rating Curve= 0 ,0
Exp/Cntr=0.3,0.1

Type RM Length L Ch R = 1 ,70246   ,684,684,684
BEGIN DESCRIPTION:
LITTLE TEHUACANA CREEK 83.0
END DESCRIPTION:
XS GIS Cut Line= 3
      3530395.65     10608631.76      3531902.55     10609326.19
      3532867.82     10610117.84
#Sta/Elev= 30
  3773.2  456.95  3805.2  454.97  3810.7  455.73  3851.1  453.61  3879.6  453.65
  3931.7  451.45  4129.9   440.4  4295.1  432.47  4383.7  429.48  4581.3  428.72
  4876.8  429.99  4979.6  431.78  4988.7  429.89    4997  425.89  4999.8  425.39
    5003  425.89  5010.8  431.71  5109.9  429.34  5168.8  429.51  5179.6   427.9
  5191.8  425.89  5197.9   430.2  5271.9  429.05  5618.1  430.86  5809.7  435.62
  5945.3  437.83  6250.3  446.37  6328.6  447.38    6442  452.61  6680.8  459.94
#Mann= 5 ,-1 , 0
  3773.2     .05       0    4997     .03       0    5003     .05       0
  5179.6     .08       0  5271.9     .05       0
Bank Sta=4997,5003
XS Rating Curve= 0 ,0
Exp/Cntr=0.3,0.1

Type RM Length L Ch R = 1 ,69562   ,724,724,724
BEGIN DESCRIPTION:
LITTLE TEHUACANA CREEK 82.0
END DESCRIPTION:
XS GIS Cut Line= 3
      3530449.63     10608760.21      3531249.61     10609460.19
      3532049.61     10610160.19
#Sta/Elev= 30
    3907  455.97  4140.9  443.27  4204.5  438.73  4431.4  428.88  4785.4  427.59
  4973.3  429.87  4977.1  428.29  4983.7  429.58  4991.3  423.93    4997   423.7
  4999.8   423.2    5003   423.7  5005.6  429.28  5012.2  427.81  5019.8  429.42
  5026.5  427.63  5034.1  429.46  5359.6  428.59  5373.8   428.4  5388.1  424.79
  5395.2  425.28  5402.3  428.25  5572.2  430.21  5657.6  434.51  5820.4  439.34
  5841.8     441  5876.9  440.72  5940.5  443.22  5954.7  445.33    6033  447.29
#Mann= 3 ,-1 , 0
    3907     .05       0    4997     .03       0    5003     .05       0
Bank Sta=4997,5003
XS Rating Curve= 0 ,0
Exp/Cntr=0.3,0.1

Type RM Length L Ch R = 1 ,68838   ,450,450,450
BEGIN DESCRIPTION:
LITTLE TEHUACANA CREEK 80.0
END DESCRIPTION:
XS GIS Cut Line= 3
      3530277.55     10608833.13      3531367.83     10610208.13
      3532554.73     10610555.18
#Sta/Elev= 30
  3377.3  462.76  3483.6  456.66  3590.5  448.65  3603.8   446.6  3789.7  433.74
  3845.8  430.82  4046.1  427.61  4458.3  427.31  4480.3  426.28  4964.2  428.25
    4985  428.03  4993.1  421.11    4997  421.11  4999.8  420.61    5003  421.11
  5007.1  421.13  5013.9  428.51  5057.2  427.29  5206.9  430.39    5259  430.26
  5302.8  432.61  5513.9  438.38  5619.5  443.86  5802.3  449.91  5884.1  453.96
  6013.4  456.64  6152.4  456.68  6263.1  458.27  6342.5  463.61  6368.7  464.02
#Mann= 3 ,-1 , 0
  3377.3     .05       0    4997     .03       0    5003     .05       0
Bank Sta=4997,5003
XS Rating Curve= 0 ,0
Exp/Cntr=0.3,0.1

Type RM Length L Ch R = 1 ,68388   ,396,396,396
BEGIN DESCRIPTION:
LITTLE TEHUACANA CREEK 79.0
END DESCRIPTION:
XS GIS Cut Line= 3
       3530149.6     10608810.16      3530899.61     10610310.19
      3532099.59     10611310.17
#Sta/Elev= 30
  3353.7  466.18  3451.6     464  3577.3  455.21  3725.5  441.14    3868  432.16
  3943.5  429.17  4046.9  427.71  4404.7  427.65  4798.8  425.37  4986.1  427.45
    4997  420.21  4999.8  419.71    5003  420.21  5008.4  420.21  5022.4  427.64
  5151.2  425.48  5371.2  425.41  5648.4  432.36  5783.8  437.85  5911.4  440.51
    6039  440.92  6217.5  445.94  6238.1  448.85  6258.9  453.88  6273.3   451.4
  6307.8  451.12  6394.3  451.25  6408.6   452.1  6429.5  456.18  6592.8  463.58
#Mann= 5 ,-1 , 0
  3353.7     .05       0    4997     .03       0    5003     .05       0
  6217.5      .1       0  6307.8     .05       0
Bank Sta=4997,5003
XS Rating Curve= 0 ,0
Exp/Cntr=0.3,0.1

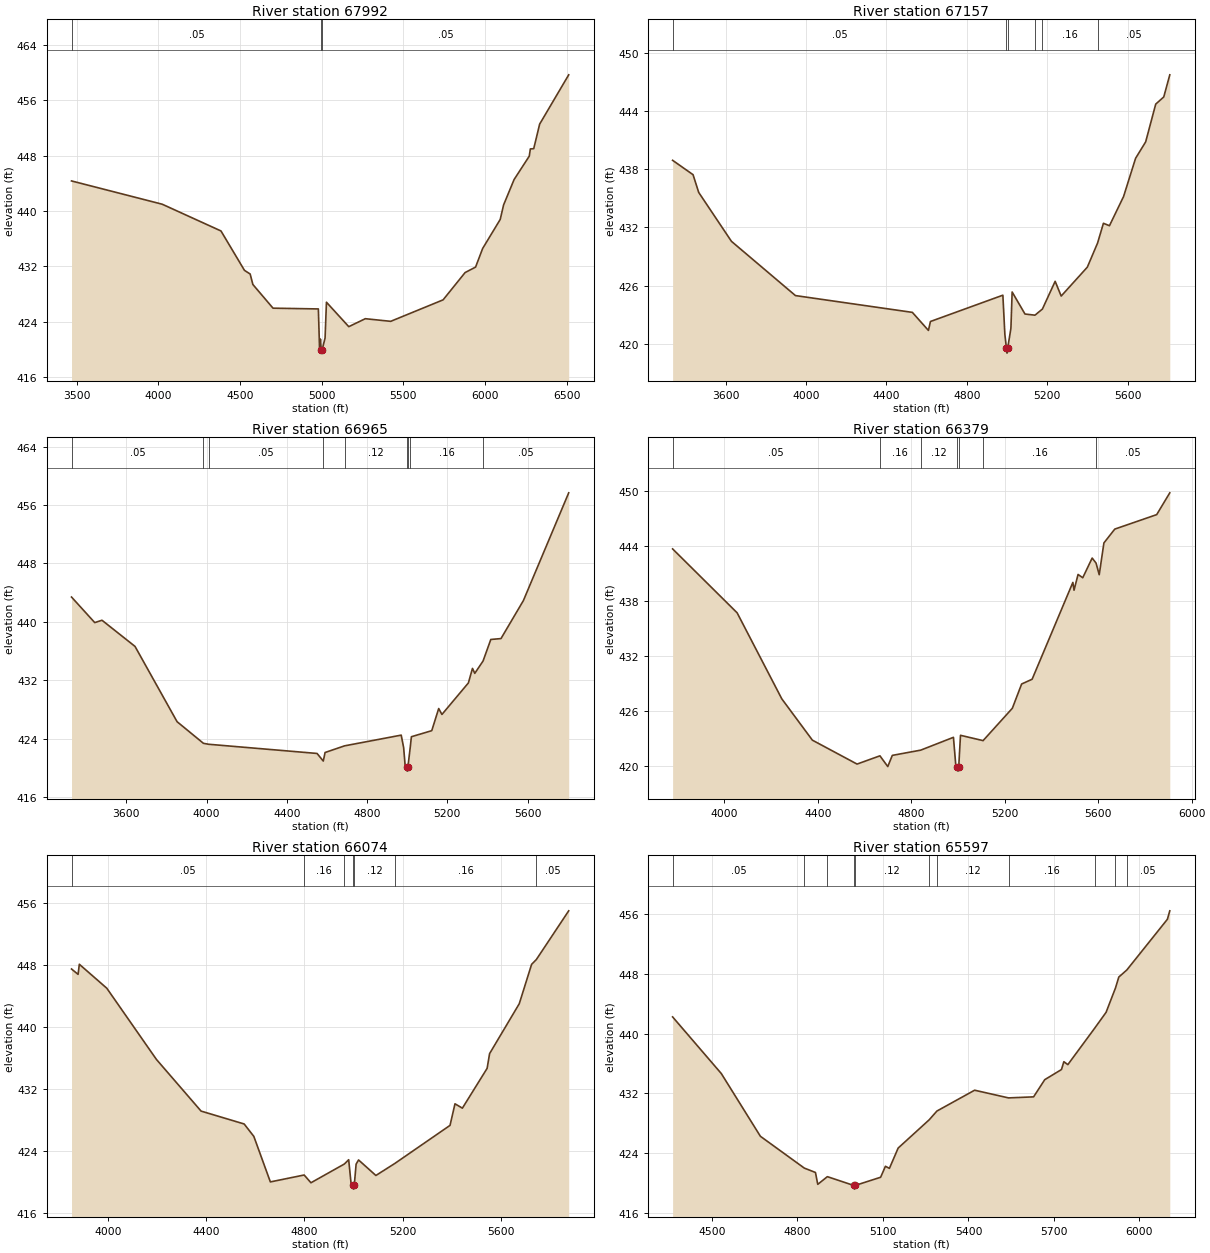
Type RM Length L Ch R = 1 ,67992   ,835,835,835
BEGIN DESCRIPTION:
LITTLE TEHUACANA CREEK 78.0
END DESCRIPTION:
XS GIS Cut Line= 3
      3529249.64      10610260.2      3530843.69     10610642.63
      3531949.62      10611510.2
#Sta/Elev= 30
  3467.9  444.34  4023.2  440.98  4383.1  437.12  4527.1  431.43    4562   430.9
  4578.5  429.39  4701.9  425.97  4979.6  425.86  4987.1  419.98  4992.3  421.51
    4997  419.98  4999.8  419.48    5003  419.98  5020.7  421.66  5029.1  426.83
  5165.9   423.3  5267.1  424.45  5422.6  424.07  5743.5  427.17  5878.2  431.11
  5942.4   431.9  5985.8  434.59  6093.3  438.78  6114.1  440.88  6178.3  444.54
  6271.3  447.92  6277.8  448.96  6298.6     449  6334.8  452.54  6512.8  459.66
#Mann= 3 ,-1 , 0
  3467.9     .05       0    4997     .03       0    5003     .05       0
Bank Sta=4997,5003
XS Rating Curve= 0 ,0
Exp/Cntr=0.3,0.1

Type RM Length L Ch R = 1 ,67157   ,192,192,192
BEGIN DESCRIPTION:
LITTLE TEHUACANA CREEK 77.0
END DESCRIPTION:
XS GIS Cut Line= 3
      3529588.95     10610627.17      3530344.13     10611408.39
      3531729.59     10611424.02
#Sta/Elev= 30
    3337  438.92  3438.6  437.44  3466.8  435.61  3629.6  430.57  3947.8  424.98
    4529  423.25    4609  421.39    4619  422.31  4979.1  425.02  4989.1  420.96
    4997  419.55  4999.8  419.05    5003  419.55  5019.1  421.61  5025.2  425.35
  5089.1  423.08  5138.6  422.96  5175.6  423.59  5239.1  426.45  5269.1  424.93
  5399.1  427.91  5449.9  430.39  5479.1  432.43  5509.1  432.18  5579.1  435.18
  5639.1  439.13  5689.1  440.82  5739.1  444.71  5779.1  445.45  5809.1  447.73
#Mann= 6 ,-1 , 0
    3337     .05       0    4997     .03       0    5003     .05       0
  5138.6     .12       0  5175.6     .16       0  5449.9     .05       0
Bank Sta=4997,5003
XS Rating Curve= 0 ,0
Exp/Cntr=0.3,0.1

Type RM Length L Ch R = 1 ,66965   ,586,586,586
BEGIN DESCRIPTION:
LITTLE TEHUACANA CREEK 76.0
END DESCRIPTION:
XS GIS Cut Line= 3
      3529427.48     10611986.51      3530682.67     10611512.56
      3531802.22     10611705.22
#Sta/Elev= 30
    3327   443.4  3442.7   439.9  3478.9  440.22  3643.4  436.64    3853  426.33
  3984.3  423.37  4009.7  423.24  4550.6  421.98  4581.6  420.94  4590.6  422.11
  4687.5  423.02    4970  424.49  4982.1  422.78  4990.3  420.09    4997  420.06
  4999.8  419.56    5003  420.06  5015.5  422.93  5020.7  424.27  5122.2   425.1
  5156.8  428.13  5172.9  427.32  5304.8  431.64  5325.1  433.63  5336.6  432.95
  5377.9  434.64  5416.5  437.59  5467.2  437.71  5578.8  442.91  5804.7  457.67
#Mann= 9 ,-1 , 0
    3327     .05       0  3984.3     .16       0  4009.7     .05       0
  4581.6     .16       0  4687.5     .12       0    4997     .07       0
    5003     .12       0  5015.5     .16       0  5377.9     .05       0
Bank Sta=4997,5003
XS Rating Curve= 0 ,0
Exp/Cntr=0.3,0.1

Type RM Length L Ch R = 1 ,66379   ,305,305,305
BEGIN DESCRIPTION:
LITTLE TEHUACANA CREEK 75.0
END DESCRIPTION:
XS GIS Cut Line= 2
      3529495.14      10612158.4      3531609.81      10611918.8
#Sta/Elev= 30
  3778.2  443.67  4054.4  436.69  4245.6   427.3  4376.5  422.79  4567.7  420.18
  4665.6  421.08  4699.2  419.91  4718.7  421.13  4840.2   421.7  4980.3   423.1
  4990.4  420.03    4997  419.91  4999.8  419.41    5003  419.91  5010.5  423.32
  5107.2  422.74  5232.4  426.27  5272.2  428.92  5317.1  429.44  5491.5  440.01
  5496.5  439.16  5513.7  440.88  5533.8  440.52  5574.1  442.67  5590.8  442.12
  5604.3  440.85  5624.4  444.32  5670.9  445.83  5850.3  447.41  5906.4  449.79
#Mann= 7 ,-1 , 0
  3778.2     .05       0  4665.6     .16       0  4840.2     .12       0
    4997     .07       0    5003     .12       0  5107.2     .16       0
  5590.8     .05       0
Bank Sta=4997,5003
XS Rating Curve= 0 ,0
Exp/Cntr=0.3,0.1

Type RM Length L Ch R = 1 ,66074   ,477,477,477
BEGIN DESCRIPTION:
LITTLE TEHUACANA CREEK 74.0
END DESCRIPTION:
XS GIS Cut Line= 3
      3529399.61     10612460.19      3530499.61     10612260.19
      3531399.64     10612160.19
#Sta/Elev= 30
  3852.2  447.45  3878.9  446.76    3884  448.06  3995.8  444.97  4197.8  435.79
  4379.5  429.13  4554.8  427.47  4594.2  425.87  4661.5     420    4799  420.89
  4826.7  419.89  4962.2   422.3  4980.3  422.86  4990.4  419.67    4997  419.57
  4999.8  419.07    5003  419.57  5010.5  422.29  5020.5  422.83    5091  420.83
  5168.1  422.38  5392.8  427.29  5412.9  430.07  5443.1  429.51  5543.7  434.64
  5553.8  436.54  5674.5  442.97  5724.8  448.05  5744.1  448.67  5875.8  454.95
#Mann= 7 ,-1 , 0
  3852.2     .05       0    4799     .16       0  4962.2     .12       0
    4997     .07       0    5003     .12       0  5168.1     .16       0
  5744.1     .05       0
Bank Sta=4997,5003
XS Rating Curve= 0 ,0
Exp/Cntr=0.3,0.1

Type RM Length L Ch R = 1 ,65597   ,448,448,448
BEGIN DESCRIPTION:
LITTLE TEHUACANA CREEK 73.0
END DESCRIPTION:
XS GIS Cut Line= 3
      3529849.61     10613010.19      3530399.61     10612710.19
      3531399.58      10612210.2
#Sta/Elev= 30
    4362  442.24  4532.9  434.65    4670  426.25    4824  421.99  4863.2   421.4
  4871.3  419.81    4905  420.84    4997  419.67  4999.8  419.17    5003  419.67
  5091.9  420.76  5108.7  422.23  5122.7  421.95  5153.4  424.67  5262.4  428.46
  5289.4  429.63  5421.7  432.42  5540.7  431.39  5628.6  431.53  5667.7  433.83
  5726.4  435.19  5734.8  436.24  5748.8  435.85  5842.8  440.72  5882.9  442.85
  5915.8   446.1  5927.6  447.58  5955.6  448.52  6098.1  455.32  6106.5  456.45
#Mann= 11 ,-1 , 0
    4362     .05       0    4824     .16       0    4905     .12       0
    4997     .07       0    5003     .12       0  5262.4     .16       0
  5289.4     .12       0  5540.7     .16       0  5842.8     .12       0
  5915.8     .16       0  5955.6     .05       0
Bank Sta=4997,5003
XS Rating Curve= 0 ,0
Exp/Cntr=0.3,0.1