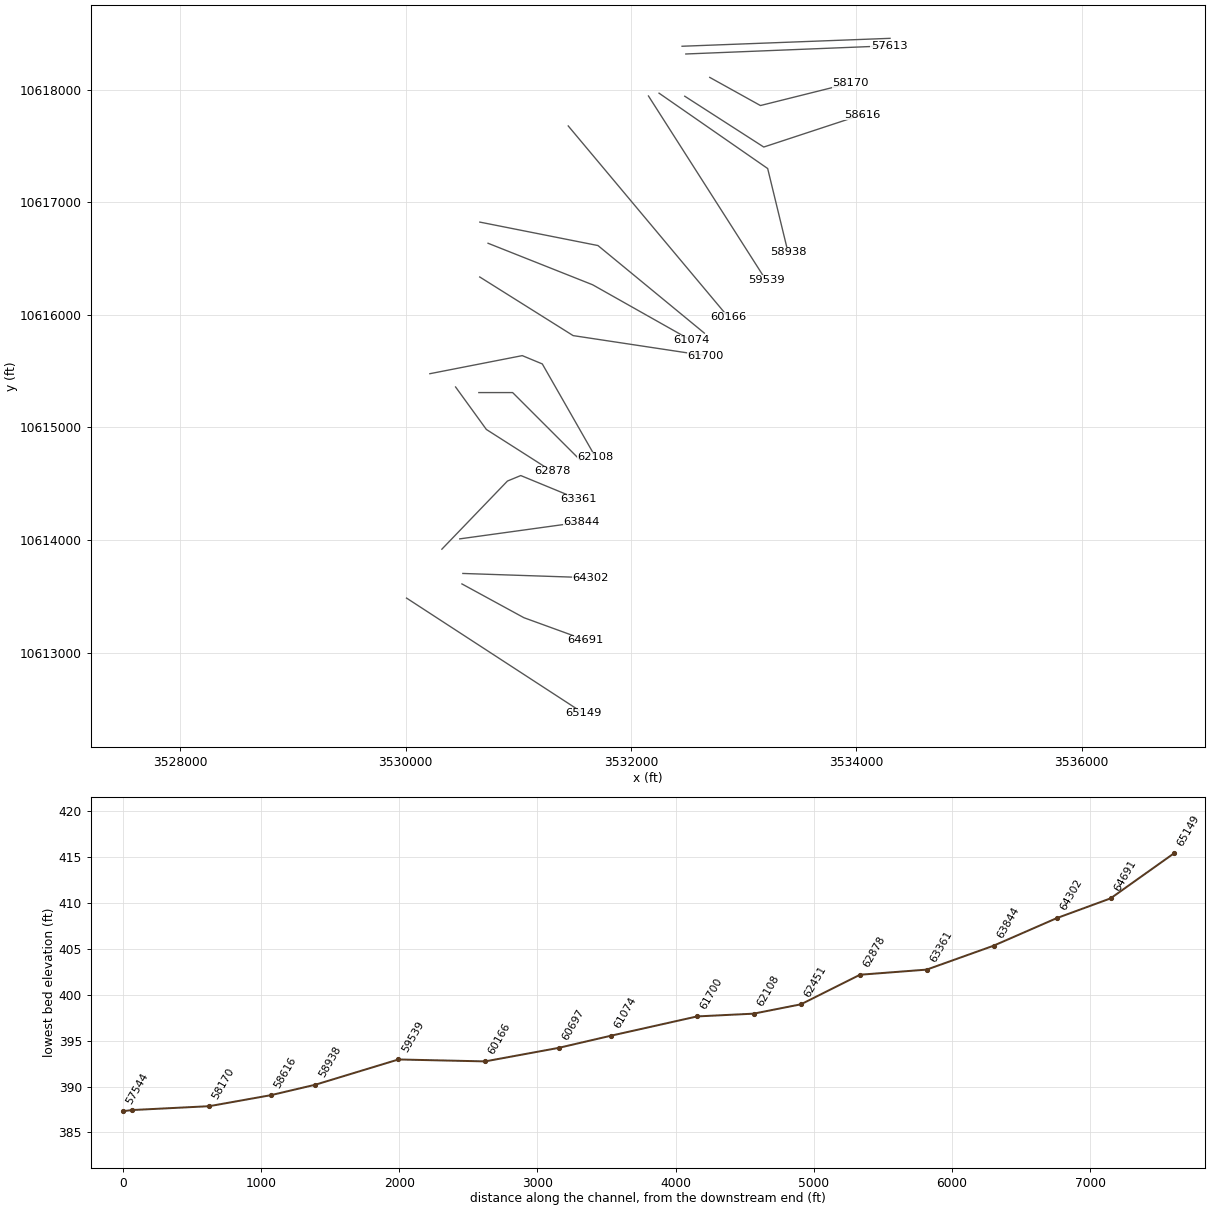
HEC-RAS study LITTLE TEHUACANA CREEK.prj: LITTLE TEHUACANA CREEK Base Level Engineering

--- LITTLE TEHUACANA CREEK.g01 (geometry) --- (continued)

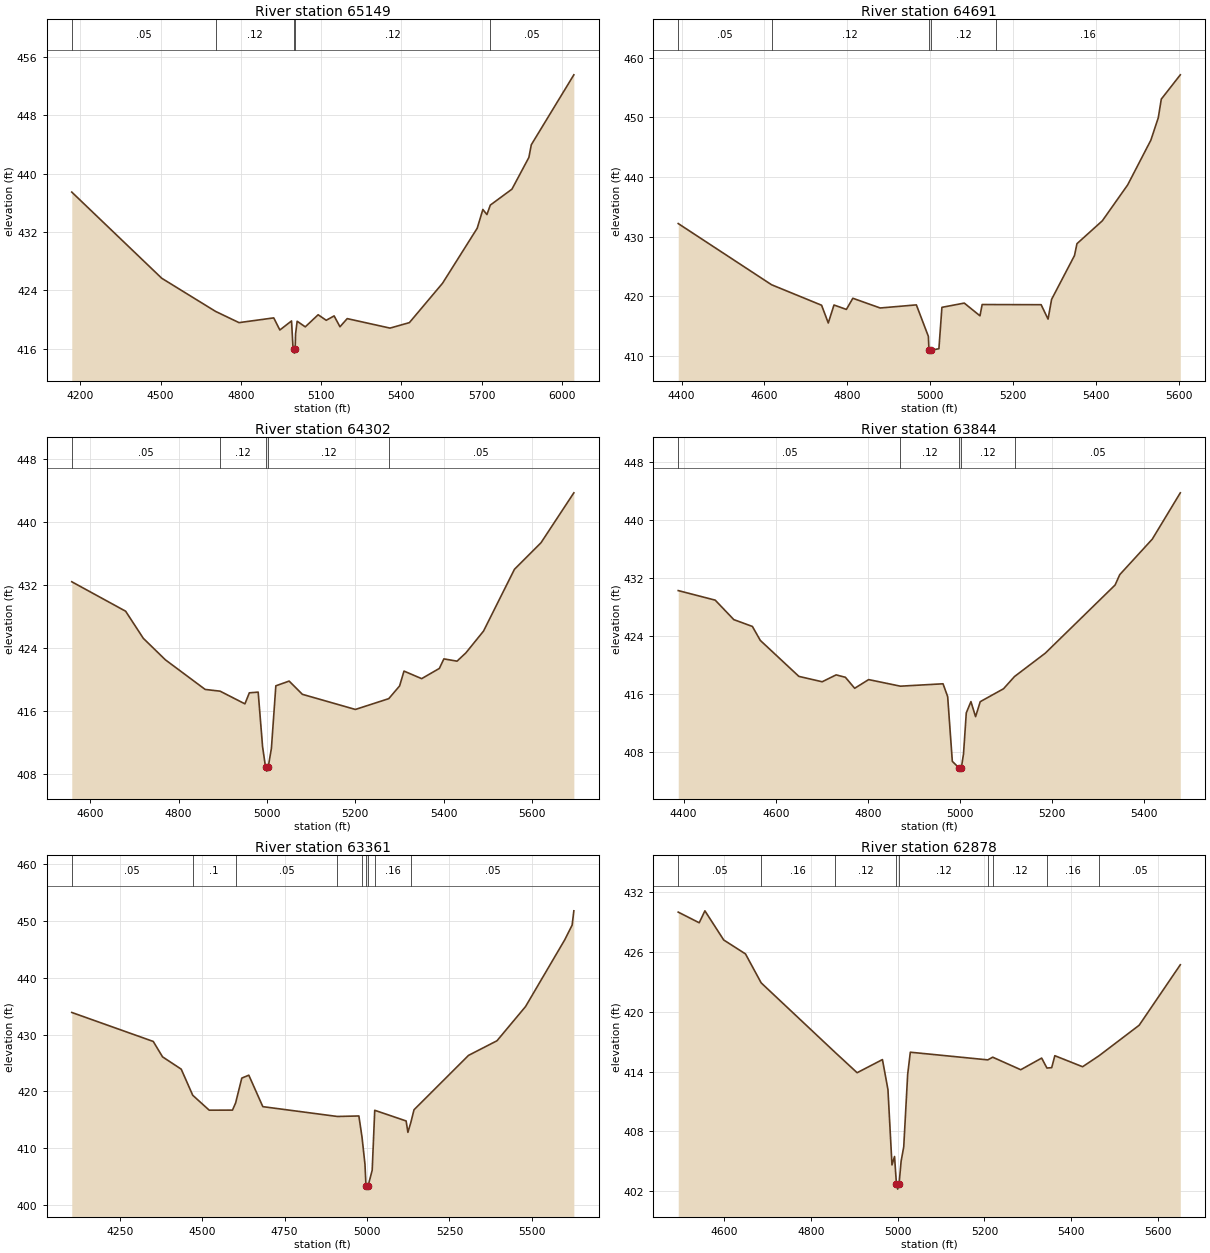
Type RM Length L Ch R = 1 ,65149   ,458,458,458
BEGIN DESCRIPTION:
LITTLE TEHUACANA CREEK 72.0
END DESCRIPTION:
XS GIS Cut Line= 2
      3530007.71     10613484.51      3531580.59     10612460.23
#Sta/Elev= 30
  4167.9  437.47  4504.3  425.66  4705.4  421.12  4793.2  419.58    4923  420.23
  4945.8  418.57  4989.5  419.81  4995.4   415.9    4997   415.9  4999.8   415.4
    5003   415.9  5004.6  418.04  5010.5  419.77  5040.8     419    5089  420.66
  5119.2   419.9  5148.7   420.5  5170.6  419.01  5197.6  420.13  5357.7  418.83
  5430.1  419.58  5553.9  424.97  5683.7  432.52  5704.8  435.09  5719.9  434.39
  5732.7  435.69  5813.5  437.87  5876.8  442.22  5885.9  443.96  6044.9  453.54
#Mann= 5 ,-1 , 0
  4167.9     .05       0  4705.4     .12       0    4997     .07       0
    5003     .12       0  5732.7     .05       0
Bank Sta=4997,5003
XS Rating Curve= 0 ,0
Exp/Cntr=0.3,0.1

Type RM Length L Ch R = 1 ,64691   ,389,389,389
BEGIN DESCRIPTION:
LITTLE TEHUACANA CREEK 71.0
END DESCRIPTION:
XS GIS Cut Line= 3
      3530499.64     10613610.17      3531049.61     10613310.19
      3531599.61     10613110.19
#Sta/Elev= 30
  4391.9   432.2  4617.2  421.95  4737.9  418.52    4754  415.55  4767.8  418.56
  4797.7  417.82  4813.3  419.69  4879.3  418.06  4966.6  418.58  4995.6   413.3
    4997     411  4999.8   410.5    5003     411    5021  411.24  5028.3  418.17
  5082.2  418.88  5120.1  416.75  5125.4  418.64  5159.4  418.63  5267.7  418.61
  5284.4   416.2    5293  419.51  5348.2  426.84  5354.2  428.83  5415.4  432.66
  5476.6  438.68  5532.4  446.15  5550.4  449.91  5557.7  453.04  5603.6  457.11
#Mann= 5 ,-1 , 0
  4391.9     .05       0  4617.2     .12       0    4997     .07       0
    5003     .12       0  5159.4     .16       0
Bank Sta=4997,5003
XS Rating Curve= 0 ,0
Exp/Cntr=0.3,0.1

Type RM Length L Ch R = 1 ,64302   ,458,458,458
BEGIN DESCRIPTION:
LITTLE TEHUACANA CREEK 70.0
END DESCRIPTION:
XS GIS Cut Line= 2
      3530507.73     10613703.27      3531643.99     10613665.17
#Sta/Elev= 30
  4558.2  432.39  4680.2  428.65  4720.2  425.21  4770.2  422.48  4860.3  418.72
  4894.1   418.5  4950.3  416.89  4960.3  418.29  4980.3  418.38  4990.3  411.44
    4997  408.85  4999.8  408.35    5003  408.85  5010.3  411.26  5020.3  419.18
  5050.4  419.78  5080.4   418.1  5200.4  416.18    5276  417.55  5300.5  419.16
  5310.5  421.05  5350.5  420.09  5390.6  421.39  5400.8   422.6  5430.6  422.31
  5450.6  423.36  5490.6  426.13  5560.6  433.97  5620.7  437.34  5695.1  443.68
#Mann= 5 ,-1 , 0
  4558.2     .05       0  4894.1     .12       0    4997     .07       0
    5003     .12       0    5276     .05       0
Bank Sta=4997,5003
XS Rating Curve= 0 ,0
Exp/Cntr=0.3,0.1

Type RM Length L Ch R = 1 ,63844   ,483,483,483
BEGIN DESCRIPTION:
LITTLE TEHUACANA CREEK 69.0
END DESCRIPTION:
XS GIS Cut Line= 2
      3530480.08      10614010.5      3531559.91      10614159.8
#Sta/Elev= 30
  4388.2  430.27  4468.5  428.95  4508.9  426.26  4549.2  425.32  4566.4  423.39
  4650.2  418.42  4700.7  417.68    4731  418.63  4751.1   418.3  4771.3  416.78
  4801.6  417.98  4870.6  417.07  4963.1   417.4  4973.2  415.63  4983.3  406.69
    4997  405.84  4999.8  405.34    5003  405.84  5007.6  407.72  5013.6  413.38
  5023.7  414.94  5033.8  412.86  5043.9  414.93  5094.4  416.71  5118.3   418.4
  5185.2  421.63  5336.7  431.04  5346.8  432.47  5417.4  437.37  5478.3  443.77
#Mann= 5 ,-1 , 0
  4388.2     .05       0  4870.6     .12       0    4997     .07       0
    5003     .12       0  5118.3     .05       0
Bank Sta=4997,5003
XS Rating Curve= 0 ,0
Exp/Cntr=0.3,0.1

Type RM Length L Ch R = 1 ,63361   ,483,483,483
BEGIN DESCRIPTION:
LITTLE TEHUACANA CREEK 68.0
END DESCRIPTION:
XS GIS Cut Line= 4
      3530321.46     10613919.05      3530903.67     10614524.38
      3531021.72     10614572.99      3531535.09     10614361.41
#Sta/Elev= 30
  4104.6  433.89  4351.7  428.78    4380  426.06  4436.6  423.89  4471.5  419.29
  4521.5  416.66    4592  416.67  4601.5  417.92  4620.3  422.32  4641.6  422.83
  4684.1  417.28  4910.2  415.55  4975.4  415.64  4984.9  411.92  4993.9  407.12
    4997  403.24  4999.8  402.74    5003  403.24  5015.8  406.08  5023.5  416.64
  5118.7  414.76  5124.1  412.75  5133.1  414.52  5142.6  416.73  5307.9  426.32
  5394.3   428.9  5480.9  434.93  5599.8   446.7  5622.2  449.29  5627.4  451.81
#Mann= 9 ,-1 , 0
  4104.6     .05       0  4471.5      .1       0  4601.5     .05       0
  4910.2     .16       0  4984.9     .12       0    4997     .07       0
    5003     .12       0  5023.5     .16       0  5133.1     .05       0
Bank Sta=4997,5003
XS Rating Curve= 0 ,0
Exp/Cntr=0.3,0.1

Type RM Length L Ch R = 1 ,62878   ,427,427,427
BEGIN DESCRIPTION:
LITTLE TEHUACANA CREEK 67.0
END DESCRIPTION:
XS GIS Cut Line= 3
      3530443.05     10615360.02      3530716.46     10614982.45
       3531299.6     10614610.19
#Sta/Elev= 30
  4493.7  430.02  4542.1  428.95  4555.2  430.15  4598.6  427.22  4648.8  425.82
    4685  422.91  4854.4  415.97  4906.3  413.88  4964.7   415.2  4977.4  412.18
  4986.7  404.61  4992.6  405.46    4997  402.68  4999.8  402.18    5003  402.68
  5007.8     405  5013.8  406.43  5022.9  413.72    5029  415.94  5207.7  415.17
    5219  415.44  5283.7  414.18  5331.9  415.35  5344.1  414.35  5355.1  414.39
  5362.3  415.59  5426.3  414.48  5464.4  415.59  5556.8  418.65  5651.7  424.73
#Mann= 9 ,-1 , 0
  4493.7     .05       0    4685     .16       0  4854.4     .12       0
    4997     .07       0    5003     .12       0  5207.7     .16       0
    5219     .12       0  5344.1     .16       0  5464.4     .05       0
Bank Sta=4997,5003
XS Rating Curve= 0 ,0
Exp/Cntr=0.3,0.1

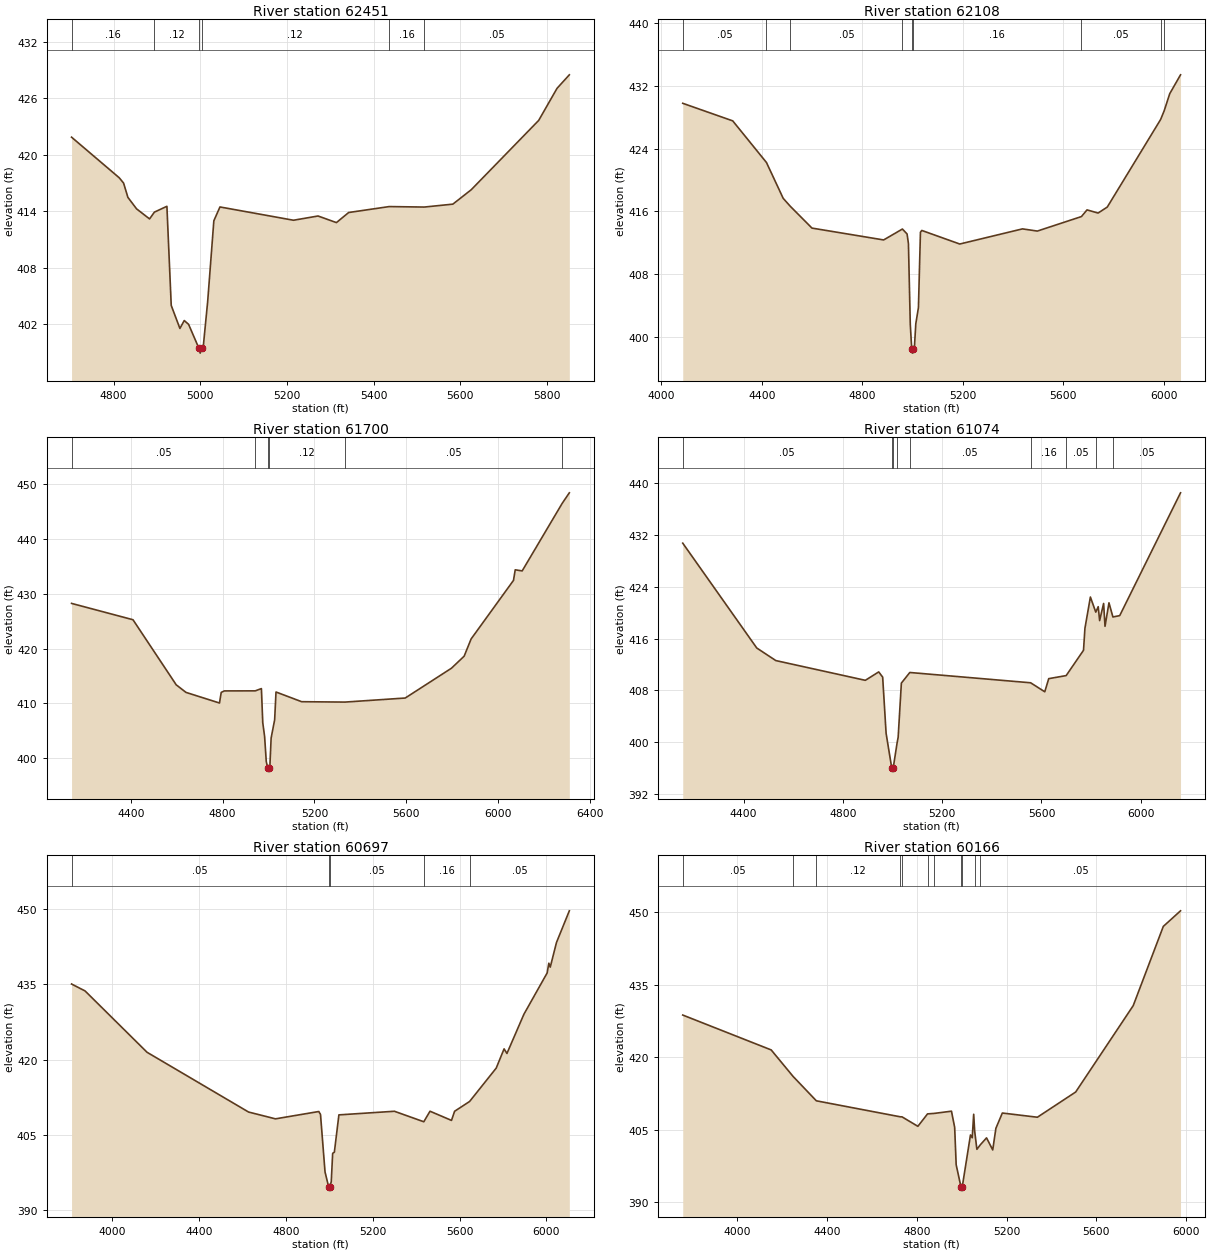
Type RM Length L Ch R = 1 ,62451   ,343,343,343
BEGIN DESCRIPTION:
LITTLE TEHUACANA CREEK 66.0
END DESCRIPTION:
XS GIS Cut Line= 3
      3530649.64     10615310.19      3530949.61     10615310.19
      3531549.61     10614710.19
#Sta/Elev= 30
    4703  421.89    4813  417.58    4823  417.02    4833   415.5    4853  414.28
    4883  413.21  4894.1  413.93    4923  414.55    4933  404.02    4953  401.58
    4963  402.42    4973  402.02    4997  399.46  4999.8  398.96    5003  399.46
  5006.5  399.46  5017.1  404.46  5031.3  413.01  5045.4  414.48  5215.1  413.07
  5271.7  413.52  5314.1  412.82  5342.4  413.89  5435.8  414.52    5517  414.47
  5582.8  414.78  5625.2  416.31  5780.8  423.67  5823.2  427.08  5851.5  428.51
#Mann= 6 ,-1 , 0
    4703     .16       0  4894.1     .12       0    4997     .07       0
    5003     .12       0  5435.8     .16       0    5517     .05       0
Bank Sta=4997,5003
XS Rating Curve= 0 ,0
Exp/Cntr=0.3,0.1

Type RM Length L Ch R = 1 ,62108   ,408,408,408
BEGIN DESCRIPTION:
LITTLE TEHUACANA CREEK 65.0
END DESCRIPTION:
XS GIS Cut Line= 4
      3530214.79     10615477.84       3531035.1     10615638.43
      3531213.06     10615564.64       3531685.4     10614736.96
#Sta/Elev= 30
  4085.5  429.79  4284.5  427.55  4418.8  422.24  4485.4  417.67  4513.9  416.65
  4599.9  413.88  4885.2  412.37  4959.9  413.76  4978.5  413.13  4983.9   411.9
  4991.2  401.65    4997  398.44  4999.8  397.94    5003  398.44  5007.8  398.74
  5013.2  401.68  5023.7  403.75  5031.7  413.35  5037.1  413.58  5188.2  411.85
  5437.9  413.78  5496.9   413.5  5672.6  415.35  5694.8   416.2  5738.9   415.8
  5775.4  416.56  5987.7  427.72    6002  428.84    6024  431.01    6067  433.42
#Mann= 9 ,-1 , 0
  4085.5     .05       0  4418.8     .16       0  4513.9     .05       0
  4959.9     .16       0    4997     .07       0    5003     .16       0
  5672.6     .05       0  5987.7     .08       0    6002     .05       0
Bank Sta=4997,5003
XS Rating Curve= 0 ,0
Exp/Cntr=0.3,0.1

Type RM Length L Ch R = 1 ,61700   ,626,626,626
BEGIN DESCRIPTION:
LITTLE TEHUACANA CREEK 64.0
END DESCRIPTION:
XS GIS Cut Line= 3
      3530657.51      10616337.2      3531486.49     10615816.38
       3532662.7     10615638.43
#Sta/Elev= 30
  4141.7  428.25  4409.3  425.27  4597.7  413.39  4640.2  412.01  4786.2  410.07
  4793.7  412.01  4807.4  412.28    4942  412.29  4968.8   412.7  4974.7  406.48
  4982.7  403.99    4990  399.37    4997  398.14  4999.8  397.64    5003  398.14
  5005.3  398.17  5011.2  403.69  5026.5  407.01  5032.4  412.08  5144.1  410.31
  5332.8  410.24  5595.4  410.98  5796.8  416.42  5852.1  418.62  5882.4  421.76
    6067  432.45  6074.6  434.38  6104.9  434.18  6279.2  446.51  6310.3  448.43
#Mann= 6 ,-1 , 0
  4141.7     .05       0    4942     .12       0    4997     .07       0
    5003     .12       0  5332.8     .05       0  6279.2     .16       0
Bank Sta=4997,5003
XS Rating Curve= 0 ,0
Exp/Cntr=0.3,0.1

Type RM Length L Ch R = 1 ,61074   ,377,377,377
BEGIN DESCRIPTION:
LITTLE TEHUACANA CREEK 63.0
END DESCRIPTION:
XS GIS Cut Line= 3
       3530731.3     10616636.68       3531660.1     10616267.77
       3532535.7     10615773.62
#Sta/Elev= 30
  4155.3  430.73  4453.4  414.54  4530.1   412.6  4890.7  409.55  4944.6  410.85
  4960.5  410.04  4974.3  401.37    4997  396.03  4999.8  395.53    5003  396.03
  5018.4  399.83  5022.9  400.77  5035.8  409.12  5069.8  410.76  5556.4  409.17
  5613.4  407.78  5629.3  409.81  5699.5  410.28  5769.4  414.19  5775.1  417.58
  5797.1  422.41  5818.8  420.08  5828.6  420.92  5834.3  418.77  5850.3  421.42
    5856  417.89  5871.9  421.52  5887.8  419.33  5915.2  419.54  6160.1   438.5
#Mann= 9 ,-1 , 0
  4155.3     .05       0    4997     .03       0    5003     .05       0
  5018.4     .08       0  5069.8     .05       0  5556.4     .16       0
  5699.5     .05       0  5818.8     .16       0  5887.8     .05       0
Bank Sta=4997,5003
XS Rating Curve= 0 ,0
Exp/Cntr=0.3,0.1

Type RM Length L Ch R = 1 ,60697   ,531,531,531
BEGIN DESCRIPTION:
LITTLE TEHUACANA CREEK 62.0
END DESCRIPTION:
XS GIS Cut Line= 3
      3530658.51      10616824.7      3531707.12     10616616.36
      3532651.58     10615838.58
#Sta/Elev= 30
  3813.2  435.04  3875.5  433.66    4161  421.45  4628.3  409.56  4752.3   408.2
  4951.9  409.66  4959.8  409.08  4980.6  397.64    4997  394.71  4999.8  394.21
    5003  394.71  5009.3  395.69  5015.8  401.33  5023.6  401.57  5044.5  408.99
  5300.1  409.71  5435.5  407.62  5464.1  409.72  5563.1  407.89  5577.4  409.71
  5646.5  411.66    5769   418.3  5805.3  422.13  5818.5  421.22  5896.7  429.03
  6003.6  437.24  6011.4  439.18  6017.9   438.4  6046.6   443.3  6105.8  449.61
#Mann= 5 ,-1 , 0
  3813.2     .05       0    4997     .03       0    5003     .05       0
  5435.5     .16       0  5646.5     .05       0
Bank Sta=4997,5003
XS Rating Curve= 0 ,0
Exp/Cntr=0.3,0.1

Type RM Length L Ch R = 1 ,60166   ,627,627,627
BEGIN DESCRIPTION:
LITTLE TEHUACANA CREEK 61.0
END DESCRIPTION:
XS GIS Cut Line= 2
      3531443.21     10617678.89      3532865.72     10615978.82
#Sta/Elev= 30
  3758.2  428.77  4152.1  421.55  4249.3  416.08  4353.1  411.02  4726.8  407.71
  4734.7   407.7  4805.3  405.74  4848.3  408.31  4877.4  408.41  4954.9  408.87
  4969.1  405.53  4975.8  397.79    4997  393.24  4999.8  392.74    5003  393.24
  5039.5  403.95  5047.3  403.37  5053.8  408.23  5058.3   404.7  5068.1  400.98
  5083.6  401.93  5111.1  403.35  5138.6  400.85  5152.7  405.33  5181.4  408.49
  5337.5  407.62    5508  412.84  5764.3  430.72  5898.3  447.12  5974.9  450.34
#Mann= 11 ,-1 , 0
  3758.2     .05       0  4249.3     .16       0  4353.1     .12       0
  4726.8     .05       0  4734.7     .16       0  4848.3     .05       0
  4877.4     .16       0    4997     .07       0    5003     .16       0
  5058.3     .12       0  5083.6     .05       0
Bank Sta=4997,5003
XS Rating Curve= 0 ,0
Exp/Cntr=0.3,0.1

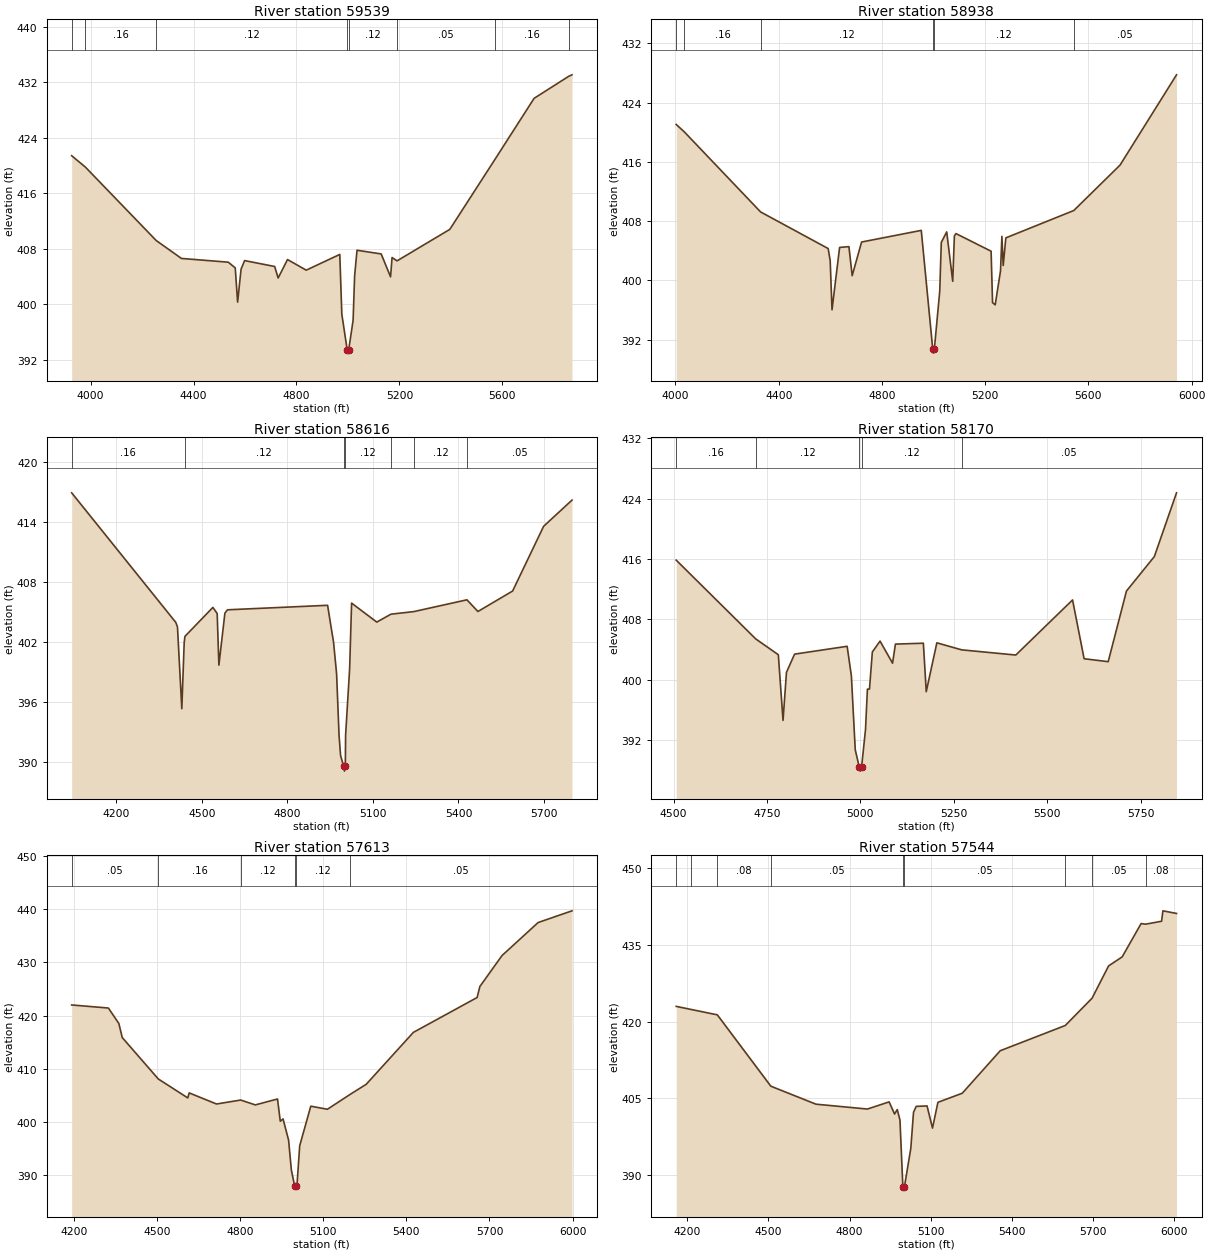
Type RM Length L Ch R = 1 ,59539   ,601,601,601
BEGIN DESCRIPTION:
LITTLE TEHUACANA CREEK 60.0
END DESCRIPTION:
XS GIS Cut Line= 2
      3532155.57     10617945.06      3533200.67     10616306.24
#Sta/Elev= 30
  3926.7  421.41  3979.9  419.77  4254.9  409.19  4353.1   406.6    4535  406.06
  4562.1  405.24  4571.4   400.3  4584.8  405.06  4598.5  406.29  4715.3  405.44
  4728.8  403.78  4765.2  406.44    4838  404.91  4968.3  407.18  4976.2  398.56
    4997  393.45  4999.8  392.95    5003  393.45    5020  397.67  5025.9  404.07
  5035.2  407.78  5129.1  407.25  5165.5  403.95  5171.4  406.73  5190.8  406.25
  5395.7  410.79  5572.5  420.96  5723.2  429.68  5858.7  432.88  5870.4  433.07
#Mann= 8 ,-1 , 0
  3926.7     .05       0  3979.9     .16       0  4254.9     .12       0
    4997     .07       0    5003     .12       0  5190.8     .05       0
  5572.5     .16       0  5858.7     .05       0
Bank Sta=4997,5003
XS Rating Curve= 0 ,0
Exp/Cntr=0.3,0.1

Type RM Length L Ch R = 1 ,58938   ,322,322,322
BEGIN DESCRIPTION:
LITTLE TEHUACANA CREEK 59.0
END DESCRIPTION:
XS GIS Cut Line= 3
      3532249.52       10617970.      3533213.78     10617300.61
      3533394.33     10616557.57
#Sta/Elev= 30
  4002.9  421.05  4034.4  420.05  4329.9  409.25  4591.7  404.31  4599.5  402.67
  4606.6  396.05    4636  404.46  4672.1  404.57  4684.7  400.65  4721.2  405.19
  4952.4  406.76    4997   390.7  4999.8   390.2    5003   390.7    5024  398.56
    5030  405.13    5051  406.56  5074.3  399.89  5080.7  406.01  5086.8  406.33
    5223  403.95  5228.6  397.01  5238.9  396.72  5259.5  401.31  5264.8  405.96
  5269.9  402.02  5280.1  405.75  5543.3  409.44  5722.6  415.57  5941.4  427.75
#Mann= 6 ,-1 , 0
  4002.9     .05       0  4034.4     .16       0  4329.9     .12       0
    4997     .07       0    5003     .12       0  5543.3     .05       0
Bank Sta=4997,5003
XS Rating Curve= 0 ,0
Exp/Cntr=0.3,0.1

Type RM Length L Ch R = 1 ,58616   ,446,446,446
BEGIN DESCRIPTION:
LITTLE TEHUACANA CREEK 58.0
END DESCRIPTION:
XS GIS Cut Line= 3
      3532477.63     10617942.99      3533179.06     10617491.58
      3534054.09     10617779.78
#Sta/Elev= 30
  4042.9  416.92  4408.2  403.95  4414.1  403.49  4429.3  395.31  4437.7  401.95
  4440.3  402.55  4538.3  405.45  4553.4  404.84  4559.4  399.67  4580.5  404.88
  4589.8  405.21  4940.8  405.66  4961.8  401.94  4972.4   398.8    4981  392.64
  4986.3  390.63    4997  389.56  4999.8  389.06    5003  389.56    5004  392.67
  5018.1  399.29    5025  405.88  5113.4  403.98  5162.9  404.77  5243.4  405.03
  5429.7  406.21  5468.2  405.04    5590  407.09  5698.8  413.57  5798.3  416.19
#Mann= 7 ,-1 , 0
  4042.9     .16       0  4440.3     .12       0    4997     .07       0
    5003     .12       0  5162.9     .16       0  5243.4     .12       0
  5429.7     .05       0
Bank Sta=4997,5003
XS Rating Curve= 0 ,0
Exp/Cntr=0.3,0.1

Type RM Length L Ch R = 1 ,58170   ,557,557,557
BEGIN DESCRIPTION:
LITTLE TEHUACANA CREEK 57.0
END DESCRIPTION:
XS GIS Cut Line= 3
       3532699.6     10618110.19      3533149.61     10617860.19
       3533949.6     10618060.19
#Sta/Elev= 30
  4506.8  415.85  4719.7   405.4  4780.2   403.3  4792.8  394.59    4802  400.97
  4823.7  403.38  4964.4  404.42  4975.8  400.48  4986.1   390.7    4997  388.36
  4999.8  387.86    5003  388.36  5013.6   393.4  5018.7  398.74  5024.2  398.74
  5031.9  403.67  5052.5  405.11    5086  402.18  5093.7  404.71  5168.5  404.83
  5176.2   398.4  5204.6  404.88  5270.9  403.95  5415.9  403.26  5567.9  410.57
  5598.8  402.77  5663.3  402.38  5712.2  411.75  5786.9  416.33  5846.2  424.78
#Mann= 5 ,-1 , 0
  4506.8     .16       0  4719.7     .12       0    4997     .07       0
    5003     .12       0  5270.9     .05       0
Bank Sta=4997,5003
XS Rating Curve= 0 ,0
Exp/Cntr=0.3,0.1

Type RM Length L Ch R = 1 ,57613   ,69,69,69
BEGIN DESCRIPTION:
LITTLE TEHUACANA CREEK 56.0
END DESCRIPTION:
XS GIS Cut Line= 2
      3532487.13     10618318.21      3534291.85     10618391.13
#Sta/Elev= 30
  4191.7  422.01  4324.3  421.43  4361.9  418.54  4374.3  415.89  4504.4  408.12
  4610.9  404.56  4615.9   405.5  4714.6  403.42  4801.8  404.16  4854.7  403.25
  4934.8  404.36  4944.8  400.19  4954.8  400.62  4974.8  396.63  4984.8  391.02
    4997  387.94  4999.8  387.44    5003  387.94  5004.8  387.94  5014.9  395.59
  5054.9  403.01  5114.9  402.43  5197.2  405.23  5255.1  407.12  5425.2  416.86
  5655.4  423.41  5665.4  425.48  5745.4  431.29  5875.6  437.48  5997.9  439.68
#Mann= 6 ,-1 , 0
  4191.7     .05       0  4504.4     .16       0  4801.8     .12       0
    4997     .07       0    5003     .12       0  5197.2     .05       0
Bank Sta=4997,5003
XS Rating Curve= 0 ,0
Exp/Cntr=0.3,0.1

Type RM Length L Ch R = 1 ,57544   ,865,865,865
BEGIN DESCRIPTION:
LITTLE TEHUACANA CREEK 55.0
END DESCRIPTION:
XS GIS Cut Line= 2
      3532453.84     10618386.96       3534300.2     10618457.27
#Sta/Elev= 30
    4160  422.98    4213   422.4  4311.8  421.33  4509.5   407.4  4676.1  403.89
  4866.3  402.94  4946.3  404.34  4966.4  401.97  4976.4  402.83  4986.4  400.78
    4997  387.81  4999.8  387.31    5003  387.81  5026.4  395.27  5036.4  402.31
  5046.4  403.46  5086.4  403.55  5106.5  399.22  5126.5  404.25  5216.5  406.03
  5356.6  414.32  5596.9  419.25  5695.7  424.57  5756.9  430.88    5807  432.64
    5877  439.15  5893.4  439.02  5952.5   439.6  5957.5  441.63  6007.7  441.12
#Mann= 9 ,-1 , 0
    4160     .08       0    4213     .05       0  4311.8     .08       0
  4509.5     .05       0    4997     .04       0    5003     .05       0
  5596.9     .08       0  5695.7     .05       0  5893.4     .08       0
Bank Sta=4997,5003
XS Rating Curve= 0 ,0
Exp/Cntr=0.3,0.1