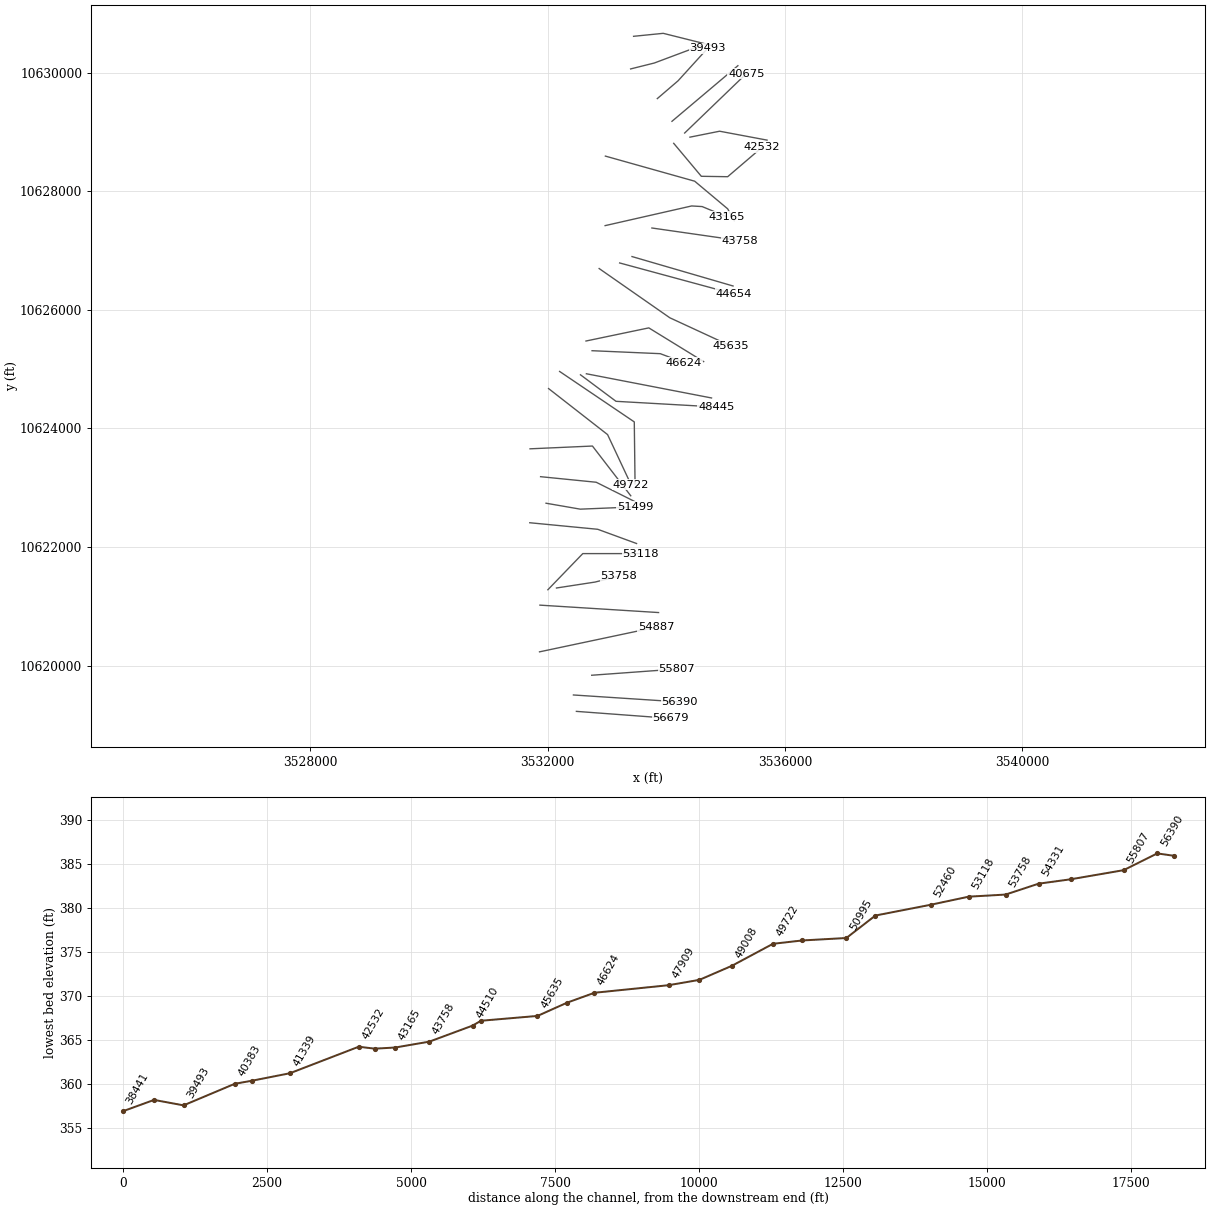
HEC-RAS study LITTLE TEHUACANA CREEK.prj: LITTLE TEHUACANA CREEK Base Level Engineering

--- LITTLE TEHUACANA CREEK.g01 (geometry) --- (continued)

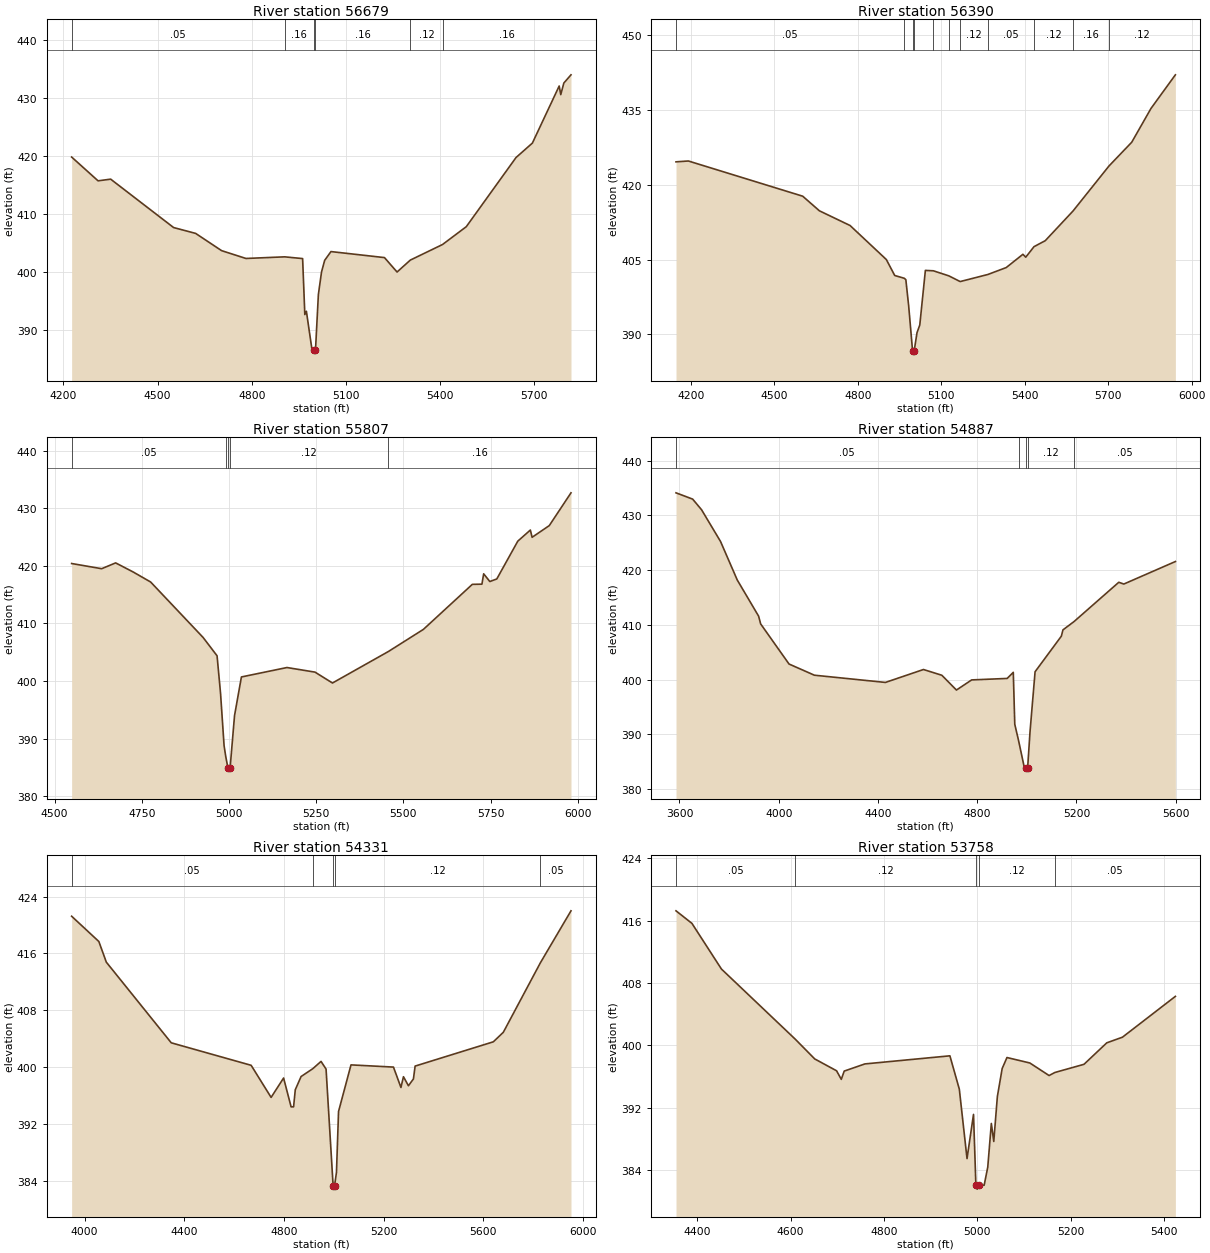
Type RM Length L Ch R = 1 ,56679   ,289,289,289
BEGIN DESCRIPTION:
LITTLE TEHUACANA CREEK 54.0
END DESCRIPTION:
XS GIS Cut Line= 2
       3532485.6     10619230.46      3534072.31     10619112.41
#Sta/Elev= 30
    4226  419.84  4310.2  415.73  4350.4  416.02  4550.9  407.66  4621.1  406.65
  4703.9  403.67  4781.5  402.32  4904.9   402.6    4962   402.3    4969  392.63
    4974   393.2  4992.1  386.47    4997  386.47  4999.8  385.97    5003  386.47
  5012.2  396.09  5022.2  399.97  5032.2  401.99  5052.3  403.51  5222.8  402.47
  5262.9  399.98  5305.2  402.04  5407.8  404.73  5483.5  407.81  5641.9  419.75
  5694.1  422.25  5779.5  432.11  5784.5  430.62  5794.3  432.62  5817.1  434.04
#Mann= 6 ,-1 , 0
    4226     .05       0  4904.9     .16       0    4997     .07       0
    5003     .16       0  5305.2     .12       0  5407.8     .16       0
Bank Sta=4997,5003
XS Rating Curve= 0 ,0
Exp/Cntr=0.3,0.1

Type RM Length L Ch R = 1 ,56390   ,583,583,583
BEGIN DESCRIPTION:
LITTLE TEHUACANA CREEK 53.0
END DESCRIPTION:
XS GIS Cut Line= 2
      3532435.33     10619506.84      3534226.21     10619389.76
#Sta/Elev= 30
  4146.9   424.6  4191.3  424.77  4602.2  417.71  4662.3  414.78  4772.5  411.83
  4902.8  405.01  4932.9  401.81  4967.3  401.25  4972.9  400.97    4983  395.75
    4997  386.74  4999.8  386.24    5003  386.74    5013  390.33    5023  391.88
  5043.1  402.83  5071.8  402.75  5127.2  401.74  5168.2  400.59  5267.6  402.01
  5333.7   403.4  5393.7  406.06  5403.9  405.48  5433.5  407.59    5474  408.79
  5573.4  414.72  5702.9  423.76  5784.7  428.53  5854.1  435.32  5941.6  442.05
#Mann= 11 ,-1 , 0
  4146.9     .05       0  4967.3     .12       0    4997     .07       0
    5003     .12       0  5071.8     .05       0  5127.2     .16       0
  5168.2     .12       0  5267.6     .05       0  5433.5     .12       0
  5573.4     .16       0  5702.9     .12       0
Bank Sta=4997,5003
XS Rating Curve= 0 ,0
Exp/Cntr=0.3,0.1

Type RM Length L Ch R = 1 ,55807   ,920,920,920
BEGIN DESCRIPTION:
LITTLE TEHUACANA CREEK 52.0
END DESCRIPTION:
XS GIS Cut Line= 2
       3532743.7     10619839.43      3534171.71      10619943.6
#Sta/Elev= 30
  4548.7  420.42  4634.8  419.52  4674.9  420.53  4725.1  418.95  4775.2  417.21
  4925.6  407.57  4965.7  404.38  4975.7  397.84  4985.8  388.76  4990.6  386.87
    4997  384.83  4999.8  384.33    5003  384.83  5015.8  393.99  5035.5   400.7
  5166.2  402.34  5246.5  401.54  5296.6  399.65  5457.1  405.13  5557.3  408.97
  5697.6   416.8  5725.1  416.83  5730.1  418.63  5747.8  417.29  5767.8  417.74
    5828  424.31    5864  426.24    5869  424.98  5918.2  427.01  5980.5  432.71
#Mann= 5 ,-1 , 0
  4548.7     .05       0  4990.6     .12       0    4997     .07       0
    5003     .12       0  5457.1     .16       0
Bank Sta=4997,5003
XS Rating Curve= 0 ,0
Exp/Cntr=0.3,0.1

Type RM Length L Ch R = 1 ,54887   ,556,556,556
BEGIN DESCRIPTION:
LITTLE TEHUACANA CREEK 51.0
END DESCRIPTION:
XS GIS Cut Line= 2
      3531863.98     10620233.93      3533832.77      10620650.6
#Sta/Elev= 30
  3586.1  434.12  3653.2  432.97  3688.9  431.04  3765.6  425.23  3832.9   418.2
  3918.9   411.6  3927.2  410.18  4041.6  402.85  4143.8  400.81    4430  399.49
  4583.3  401.85  4657.4   400.8  4716.2   398.1  4777.5  399.95  4920.6  400.22
  4945.3  401.33  4951.3  391.84  4966.5  388.89  4989.9  383.91    4997  383.79
  4999.8  383.29    5003  383.79  5012.6   390.4  5033.1  401.44    5139  407.94
  5145.5  409.09  5190.2  410.61  5370.4  417.78  5390.8  417.46  5598.5  421.57
#Mann= 5 ,-1 , 0
  3586.1     .05       0  4966.5     .12       0    4997     .07       0
    5003     .12       0  5190.2     .05       0
Bank Sta=4997,5003
XS Rating Curve= 0 ,0
Exp/Cntr=0.3,0.1

Type RM Length L Ch R = 1 ,54331   ,573,573,573
BEGIN DESCRIPTION:
LITTLE TEHUACANA CREEK 50.0
END DESCRIPTION:
XS GIS Cut Line= 2
      3531870.64     10621021.28      3533870.64     10620896.28
#Sta/Elev= 30
  3947.7  421.23  4056.9  417.67  4086.9  414.76  4347.4   403.4  4668.1  400.23
  4748.2  395.71  4798.3  398.44  4828.4  394.38  4838.4  394.38  4845.2  396.79
  4868.5  398.65  4915.3  399.75  4948.6  400.78  4968.7   399.7    4997  383.29
  4999.8  382.79    5003  383.29  5010.5  385.17  5018.8  393.73  5068.8  400.29
  5239.2  399.98  5269.2  397.11  5279.3  398.62  5299.3  397.35  5319.3  398.31
  5326.1  400.12    5640  403.54    5680  404.88  5828.9  414.68  5951.6  421.99
#Mann= 5 ,-1 , 0
  3947.7     .05       0  4915.3     .12       0    4997     .07       0
    5003     .12       0  5828.9     .05       0
Bank Sta=4997,5003
XS Rating Curve= 0 ,0
Exp/Cntr=0.3,0.1

Type RM Length L Ch R = 1 ,53758   ,640,640,640
BEGIN DESCRIPTION:
LITTLE TEHUACANA CREEK 49.0
END DESCRIPTION:
XS GIS Cut Line= 3
      3532149.65     10621310.19      3532799.61     10621410.19
      3533199.59     10621510.18
#Sta/Elev= 30
  4354.5  417.27  4388.6  415.66  4451.8   409.8  4609.9   400.8  4651.7  398.26
  4698.5  396.74  4708.6  395.64  4714.9   396.7  4759.2  397.62  4941.3  398.66
  4961.5  394.38    4978  385.47  4991.9  391.14    4997  382.05  4999.8  381.55
    5003  382.05  5014.7  382.05  5022.4  384.36  5030.1  389.98  5035.3  387.67
    5043  393.43  5053.3  397.03  5063.6  398.44  5112.6  397.74  5153.8  396.13
  5166.2  396.52  5228.6  397.57  5277.5  400.33    5311  401.05  5424.4  406.29
#Mann= 5 ,-1 , 0
  4354.5     .05       0  4609.9     .12       0    4997     .07       0
    5003     .12       0  5166.2     .05       0
Bank Sta=4997,5003
XS Rating Curve= 0 ,0
Exp/Cntr=0.3,0.1

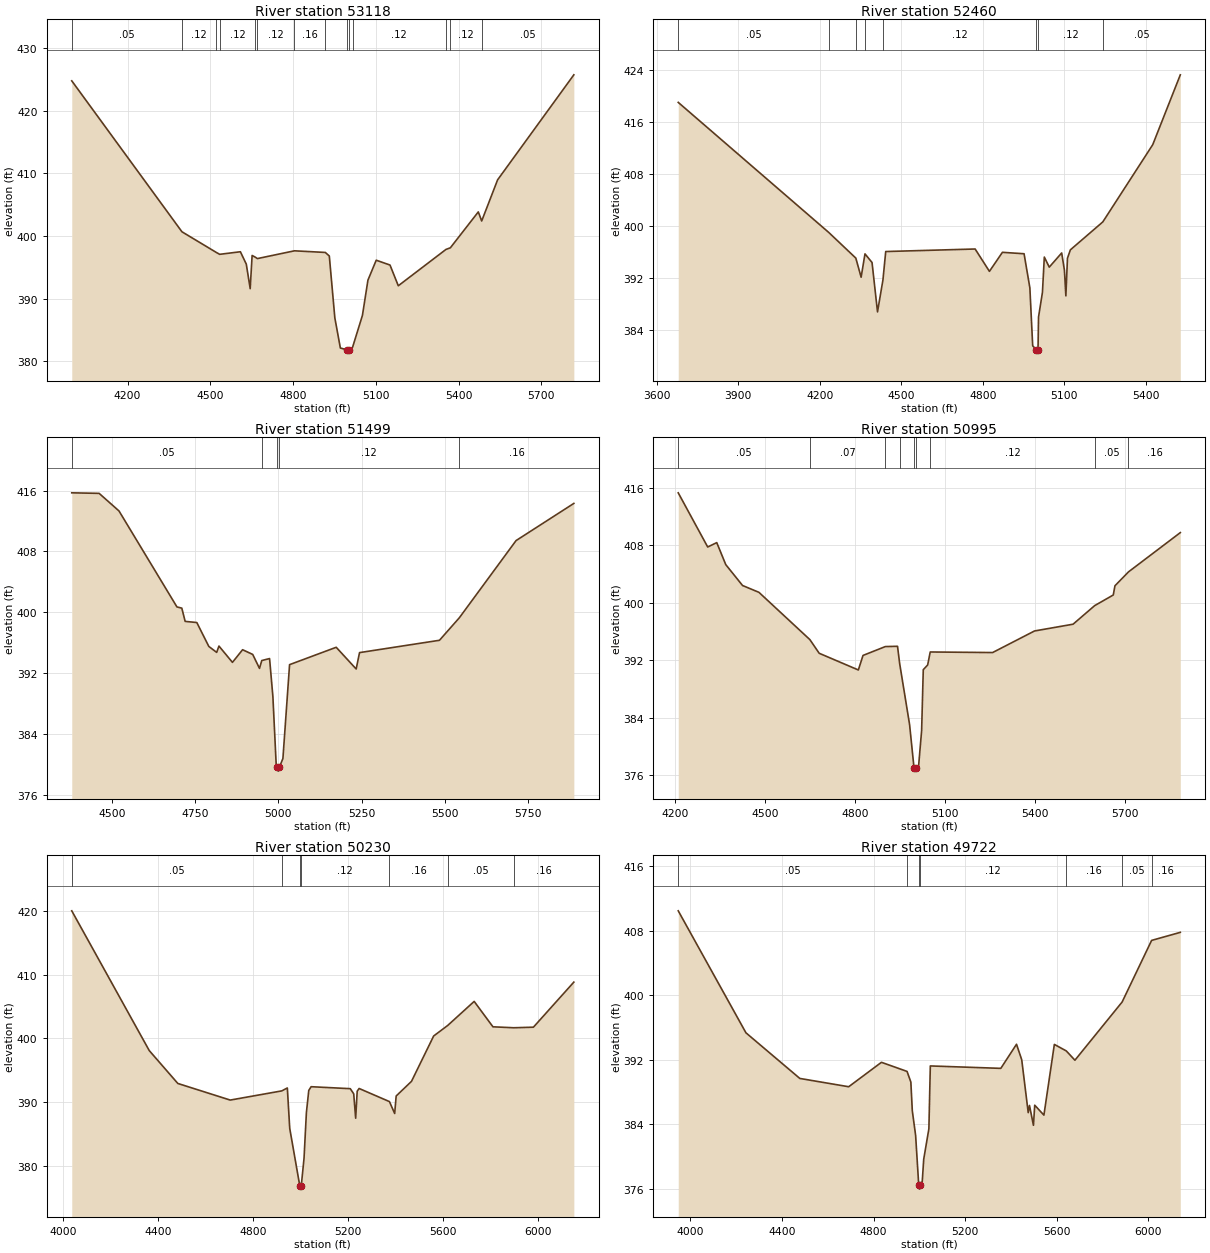
Type RM Length L Ch R = 1 ,53118   ,658,658,658
BEGIN DESCRIPTION:
LITTLE TEHUACANA CREEK 48.0
END DESCRIPTION:
XS GIS Cut Line= 3
      3532004.73     10621280.62      3532593.28       10621890.
      3533565.89       10621890.
#Sta/Elev= 30
    3998  424.77  4397.3  400.68  4521.6  397.39  4534.1  397.08  4609.2  397.49
  4630.6  395.51  4644.7   391.6  4651.7   396.9  4663.3  396.62  4670.9   396.4
  4805.1  397.64    4917  397.38  4931.5  396.81  4951.5  386.94  4971.5  382.13
    4997  381.81  4999.8  381.31    5003  381.81  5015.9  382.26  5051.5  387.33
  5071.5  392.96  5101.5  396.14  5151.5  395.37  5181.5  392.06  5354.3  397.86
  5370.2  398.12  5471.5  403.85  5483.8   402.4  5541.5  408.97  5817.8  425.73
#Mann= 14 ,-1 , 0
    3998     .05       0  4397.3     .12       0  4521.6     .07       0
  4534.1     .12       0  4663.3     .07       0  4670.9     .12       0
  4805.1     .16       0    4917     .05       0    4997    .035       0
    5003     .05       0  5015.9     .12       0  5354.3     .07       0
  5370.2     .12       0  5483.8     .05       0
Bank Sta=4997,5003
XS Rating Curve= 0 ,0
Exp/Cntr=0.3,0.1

Type RM Length L Ch R = 1 ,52460   ,961,961,961
BEGIN DESCRIPTION:
LITTLE TEHUACANA CREEK 47.0
END DESCRIPTION:
XS GIS Cut Line= 3
      3531699.57     10622410.19      3532844.63     10622299.92
      3533499.58      10622060.2
#Sta/Elev= 30
  3678.9  418.97  4232.8  398.96  4332.5  395.01    4352  392.07  4366.2  395.66
  4392.2  394.33  4412.3  386.73  4432.3  391.65  4442.5  396.02  4771.6  396.41
  4824.2  392.97    4872   395.9  4951.7  395.68    4973  390.44  4983.4  381.52
    4997  380.89  4999.8  380.39    5003  380.89  5004.9  385.94  5019.3  389.74
  5026.2  395.17  5044.4  393.62  5090.1   395.8  5100.2  393.16  5105.5   389.2
  5111.4  394.99  5122.1  396.28  5241.5  400.58  5425.2  412.46  5526.7  423.21
#Mann= 8 ,-1 , 0
  3678.9     .05       0  4232.8      .1       0  4332.5     .12       0
  4366.2     .07       0  4432.3     .12       0    4997     .07       0
    5003     .12       0  5241.5     .05       0
Bank Sta=4997,5003
XS Rating Curve= 0 ,0
Exp/Cntr=0.3,0.1

Type RM Length L Ch R = 1 ,51499   ,504,504,504
BEGIN DESCRIPTION:
LITTLE TEHUACANA CREEK 46.0
END DESCRIPTION:
XS GIS Cut Line= 3
       3531973.9     10622739.27      3532551.09     10622639.21
      3533473.01     10622677.18
#Sta/Elev= 30
  4379.3   415.7  4461.5  415.63  4521.2  413.32  4695.3  400.72  4709.9  400.56
    4720  398.82    4755  398.67  4791.1  395.53  4814.7  394.75  4821.5  395.58
  4862.1  393.44  4892.5   395.1    4923  394.48  4943.3  392.65  4950.2  393.68
  4973.6  393.94  4983.6  388.94  4993.6  379.91    4997  379.66  4999.8  379.16
    5003  379.66  5013.7  380.82  5033.7  393.14  5173.8  395.42  5233.8  392.57
  5243.9  394.72  5484.1  396.34  5543.7  399.29  5714.2  409.43  5887.8  414.31
#Mann= 5 ,-1 , 0
  4379.3     .05       0  4950.2     .12       0    4997     .07       0
    5003     .12       0  5543.7     .16       0
Bank Sta=4997,5003
XS Rating Curve= 0 ,0
Exp/Cntr=0.3,0.1

Type RM Length L Ch R = 1 ,50995   ,765,765,765
BEGIN DESCRIPTION:
LITTLE TEHUACANA CREEK 45.0
END DESCRIPTION:
XS GIS Cut Line= 3
      3531881.78     10623186.58      3532819.27     10623092.83
      3533474.56     10622765.19
#Sta/Elev= 30
  4210.6  415.28  4308.9  407.75  4339.1  408.36  4369.2   405.3  4425.1   402.4
  4479.8  401.45  4649.7  394.88  4680.8  392.98  4811.4  390.66    4827  392.68
  4901.4  393.91  4942.1  393.95  4949.2  391.56  4982.3  383.08    4997   377.1
  4999.8   376.6    5003   377.1  5012.4  377.32  5022.5  382.24    5028   390.7
  5042.6  391.35  5051.2  393.16  5259.3  393.08  5399.1  396.08  5527.7  397.02
  5599.7   399.6  5661.8  401.08  5667.4  402.36  5712.5  404.29  5885.4  409.75
#Mann= 9 ,-1 , 0
  4210.6     .05       0  4649.7     .07       0  4901.4     .05       0
  4949.2     .07       0    4997     .07       0    5003     .07       0
  5051.2     .12       0  5599.7     .05       0  5712.5     .16       0
Bank Sta=4997,5003
XS Rating Curve= 0 ,0
Exp/Cntr=0.3,0.1

Type RM Length L Ch R = 1 ,50230   ,508,508,508
BEGIN DESCRIPTION:
LITTLE TEHUACANA CREEK 44.0
END DESCRIPTION:
XS GIS Cut Line= 3
      3531704.01     10623656.35      3532756.09     10623703.23
      3533401.72     10622864.96
#Sta/Elev= 30
  4038.1  420.04    4364  398.08  4484.1  392.92  4704.4  390.31    4921  391.75
  4944.6  392.21  4954.6  385.87    4997  376.82  4999.8  376.32    5003  376.82
  5014.7  381.13  5024.7  388.34  5034.7  391.83  5044.7  392.41  5209.2   392.1
  5223.7  391.29  5231.9  387.46  5238.3   391.7  5246.4  392.13  5373.9  390.07
  5395.9   388.2  5402.2  390.95  5466.6  393.25  5559.9  400.38  5618.9  402.03
  5730.2  405.81  5809.1  401.82  5896.9  401.67  5979.3  401.76  6149.3  408.84
#Mann= 7 ,-1 , 0
  4038.1     .05       0    4921     .12       0    4997     .07       0
    5003     .12       0  5373.9     .16       0  5618.9     .05       0
  5896.9     .16       0
Bank Sta=4997,5003
XS Rating Curve= 0 ,0
Exp/Cntr=0.3,0.1

Type RM Length L Ch R = 1 ,49722   ,714,714,714
BEGIN DESCRIPTION:
LITTLE TEHUACANA CREEK 43.0
END DESCRIPTION:
XS GIS Cut Line= 3
      3532016.53     10624671.97       3533011.3     10623895.94
      3533406.43     10623053.68
#Sta/Elev= 30
    3947  410.46  4242.6  395.33  4477.8  389.67  4691.2  388.64  4834.2  391.67
    4946  390.54  4962.6  389.22  4968.9  385.66  4983.4  382.61    4997  376.44
  4999.8  375.94    5003  376.44  5012.4  376.91  5018.7  379.64  5041.3  383.43
  5047.6  391.22  5355.4  390.92  5423.9  393.91  5446.7  391.98    5475  385.43
  5480.5  386.32  5497.8  383.86  5503.4  386.35  5543.5  385.12  5589.1  393.89
  5641.3  393.08  5678.9  391.93    5885  399.15  6013.7  406.79    6139  407.79
#Mann= 7 ,-1 , 0
    3947     .05       0    4946     .12       0    4997     .07       0
    5003     .12       0  5641.3     .16       0    5885     .05       0
  6013.7     .16       0
Bank Sta=4997,5003
XS Rating Curve= 0 ,0
Exp/Cntr=0.3,0.1

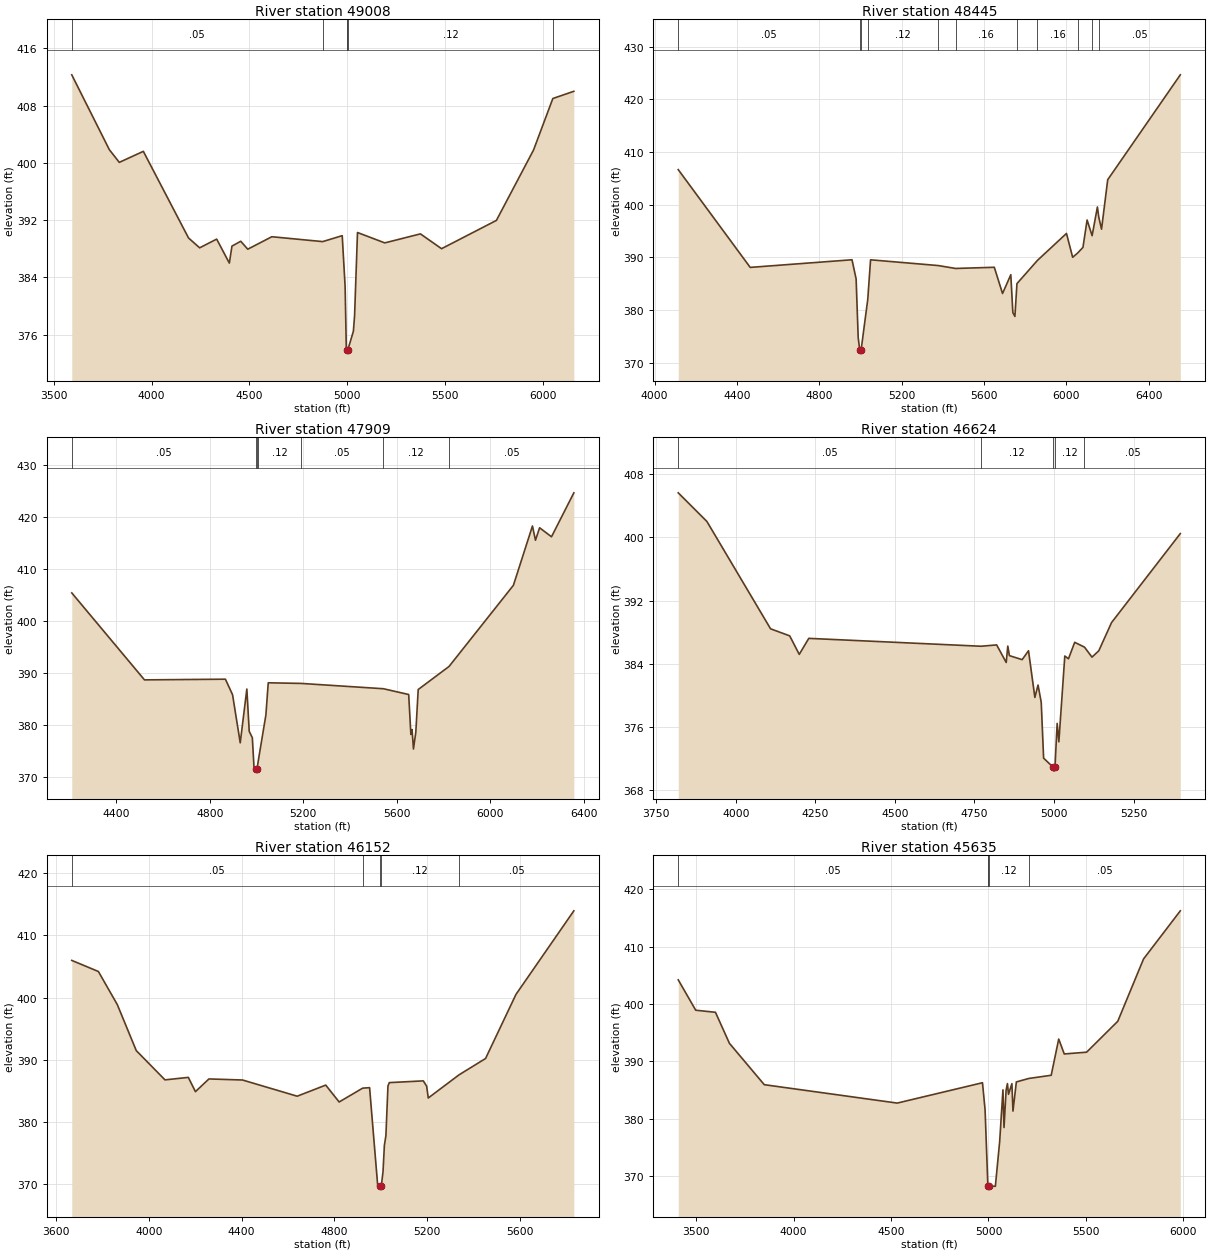
Type RM Length L Ch R = 1 ,49008   ,563,563,563
BEGIN DESCRIPTION:
LITTLE TEHUACANA CREEK 42.0
END DESCRIPTION:
XS GIS Cut Line= 3
      3532202.71      10624960.6      3533461.39     10624109.91
       3533474.4     10623064.58
#Sta/Elev= 30
  3592.4  412.31  3784.2  401.86  3835.2  400.08    3958  401.62  4188.8  389.52
  4245.7  388.14  4332.6  389.36  4397.3  386.01  4410.6  388.38  4455.5  389.06
  4491.4  387.95  4614.3  389.69    4874  389.01  4973.9  389.84  4988.7  382.72
  4994.9  373.93  4996.7  373.93    4997  373.93  4999.8  373.43    5003  373.93
  5030.9  376.49    5037  378.65  5051.9  390.28  5191.3  388.83  5373.3  390.09
  5481.3  388.02  5761.4  391.97  5951.4  401.82  6049.7     409    6157  410.01
#Mann= 6 ,-1 , 0
  3592.4     .05       0    4874     .16       0  4996.7     .12       0
    4997     .07       0    5003     .12       0  6049.7     .16       0
Bank Sta=4997,5003
XS Rating Curve= 0 ,0
Exp/Cntr=0.3,0.1

Type RM Length L Ch R = 1 ,48445   ,536,536,536
BEGIN DESCRIPTION:
LITTLE TEHUACANA CREEK 41.0
END DESCRIPTION:
XS GIS Cut Line= 3
      3532554.26      10624904.2      3533153.23     10624457.14
      3534841.61     10624361.65
#Sta/Elev= 30
  4115.1  406.68  4464.7  388.11  4959.1  389.56  4979.1  385.91  4989.1   374.8
    4997  372.33  4999.8  371.83    5003  372.33  5035.7  382.07  5049.2  389.55
  5377.8  388.46  5462.3  387.91  5650.2  388.13  5690.2  383.15  5730.3  386.72
  5740.3  379.52  5750.3   378.8  5760.2  385.03  5859.5  389.43  6000.7  394.56
  6030.8  390.03  6054.7  390.83  6080.8  391.91  6100.9  397.11  6125.2  394.13
    6151  399.58  6157.5  397.66    6171  395.37    6201  404.76  6553.6  424.68
#Mann= 11 ,-1 , 0
  4115.1     .05       0    4997     .03       0    5003     .05       0
  5035.7     .12       0  5377.8     .05       0  5462.3     .16       0
  5760.2     .12       0  5859.5     .16       0  6054.7     .05       0
  6125.2     .12       0  6157.5     .05       0
Bank Sta=4997,5003
XS Rating Curve= 0 ,0
Exp/Cntr=0.3,0.1

Type RM Length L Ch R = 1 ,47909   ,1285,1285,1285
BEGIN DESCRIPTION:
LITTLE TEHUACANA CREEK 40.0
END DESCRIPTION:
XS GIS Cut Line= 2
      3532654.06     10624921.55      3534763.47     10624513.56
#Sta/Elev= 30
  4209.8   405.4    4521  388.72  4867.3  388.85  4897.9  385.87  4930.7  376.65
    4959  386.96  4969.2  378.84  4982.5  377.63  4989.5  372.06    4997  371.72
  4999.8  371.22    5003  371.72  5008.1  373.24  5040.5  381.99  5050.6  388.16
  5190.9  388.04  5543.5  387.02  5651.6  385.91  5660.9  378.25    5666  379.19
    5672  375.47  5682.1   378.7  5692.3  386.87  5824.2  391.29  6099.7  406.86
  6181.2  418.23  6194.1   415.5  6211.8  417.89  6262.7  416.16  6358.3  424.59
#Mann= 7 ,-1 , 0
  4209.8     .05       0    4997     .03       0    5003     .05       0
  5008.1     .12       0  5190.9     .05       0  5543.5     .12       0
  5824.2     .05       0
Bank Sta=4997,5003
XS Rating Curve= 0 ,0
Exp/Cntr=0.3,0.1

Type RM Length L Ch R = 1 ,46624   ,472,472,472
BEGIN DESCRIPTION:
LITTLE TEHUACANA CREEK 38.0
END DESCRIPTION:
XS GIS Cut Line= 3
      3532749.58     10625310.19      3533899.61     10625260.19
      3534299.59      10625110.2
#Sta/Elev= 30
  3818.7  405.66  3908.8  402.03    4109  388.41  4169.1  387.52  4199.1  385.17
  4229.1   387.2  4770.6   386.2  4819.7  386.37  4849.7  384.14  4854.7  386.22
  4859.7  385.01  4899.8   384.5  4919.8  385.63  4939.8  379.71  4949.8  381.28
  4959.8  379.09  4967.3  372.01    4997  370.86  4999.8  370.36    5003  370.86
  5009.9  376.41  5015.2  374.08  5033.9  384.96  5045.5  384.61    5065   386.7
  5095.7  386.09  5119.3  384.82  5140.7  385.62  5180.8   389.2    5397  400.49
#Mann= 5 ,-1 , 0
  3818.7     .05       0  4770.6     .12       0    4997     .07       0
    5003     .12       0  5095.7     .05       0
Bank Sta=4997,5003
XS Rating Curve= 0 ,0
Exp/Cntr=0.3,0.1

Type RM Length L Ch R = 1 ,46152   ,517,517,517
BEGIN DESCRIPTION:
LITTLE TEHUACANA CREEK 37.0
END DESCRIPTION:
XS GIS Cut Line= 3
      3532647.11     10625473.62      3533706.18     10625694.98
      3534630.67      10625126.4
#Sta/Elev= 30
  3666.8  405.96  3781.7  404.18  3863.5  398.86  3945.2  391.48  4069.2  386.78
  4169.9  387.18  4200.6  384.89  4258.9  386.93  4403.7  386.76  4639.9  384.16
  4763.1  385.94    4821  383.23  4922.5  385.45  4952.4  385.53  4987.6  369.74
    4997  369.74  4999.8  369.24    5003  369.74  5010.4  372.06  5016.3  376.28
  5022.8  377.81  5031.7   385.8  5037.6  386.34  5184.4  386.62  5198.9  385.75
  5205.6  383.87  5338.6  387.59    5453  390.21  5584.4  400.51  5834.1  413.92
#Mann= 5 ,-1 , 0
  3666.8     .05       0  4922.5     .12       0    4997     .07       0
    5003     .12       0  5338.6     .05       0
Bank Sta=4997,5003
XS Rating Curve= 0 ,0
Exp/Cntr=0.3,0.1

Type RM Length L Ch R = 1 ,45635   ,981,981,981
BEGIN DESCRIPTION:
LITTLE TEHUACANA CREEK 36.0
END DESCRIPTION:
XS GIS Cut Line= 3
      3532869.13     10626695.32      3534060.07     10625865.48
       3535080.9     10625393.26
#Sta/Elev= 30
  3408.1  404.23  3497.9  398.93  3599.2  398.57  3670.7  393.16  3849.6  385.94
  4531.9  382.73  4969.3  386.28  4982.6  381.56  4996.2  369.01    4997  368.22
  4999.8  367.72    5003  368.22  5035.4  368.22  5057.5  376.04  5074.3  385.04
  5079.8  378.47  5090.5  384.98  5097.3  386.13  5102.8  384.26  5120.2  386.12
  5125.7  381.33  5143.1  386.42  5207.7  387.03  5321.9  387.58  5360.5   393.9
  5388.9   391.3  5503.6  391.61  5663.5     397  5795.7  407.87  5984.4  416.27
#Mann= 5 ,-1 , 0
  3408.1     .05       0  4996.2     .12       0    4997     .07       0
    5003     .12       0  5207.7     .05       0
Bank Sta=4997,5003
XS Rating Curve= 0 ,0
Exp/Cntr=0.3,0.1

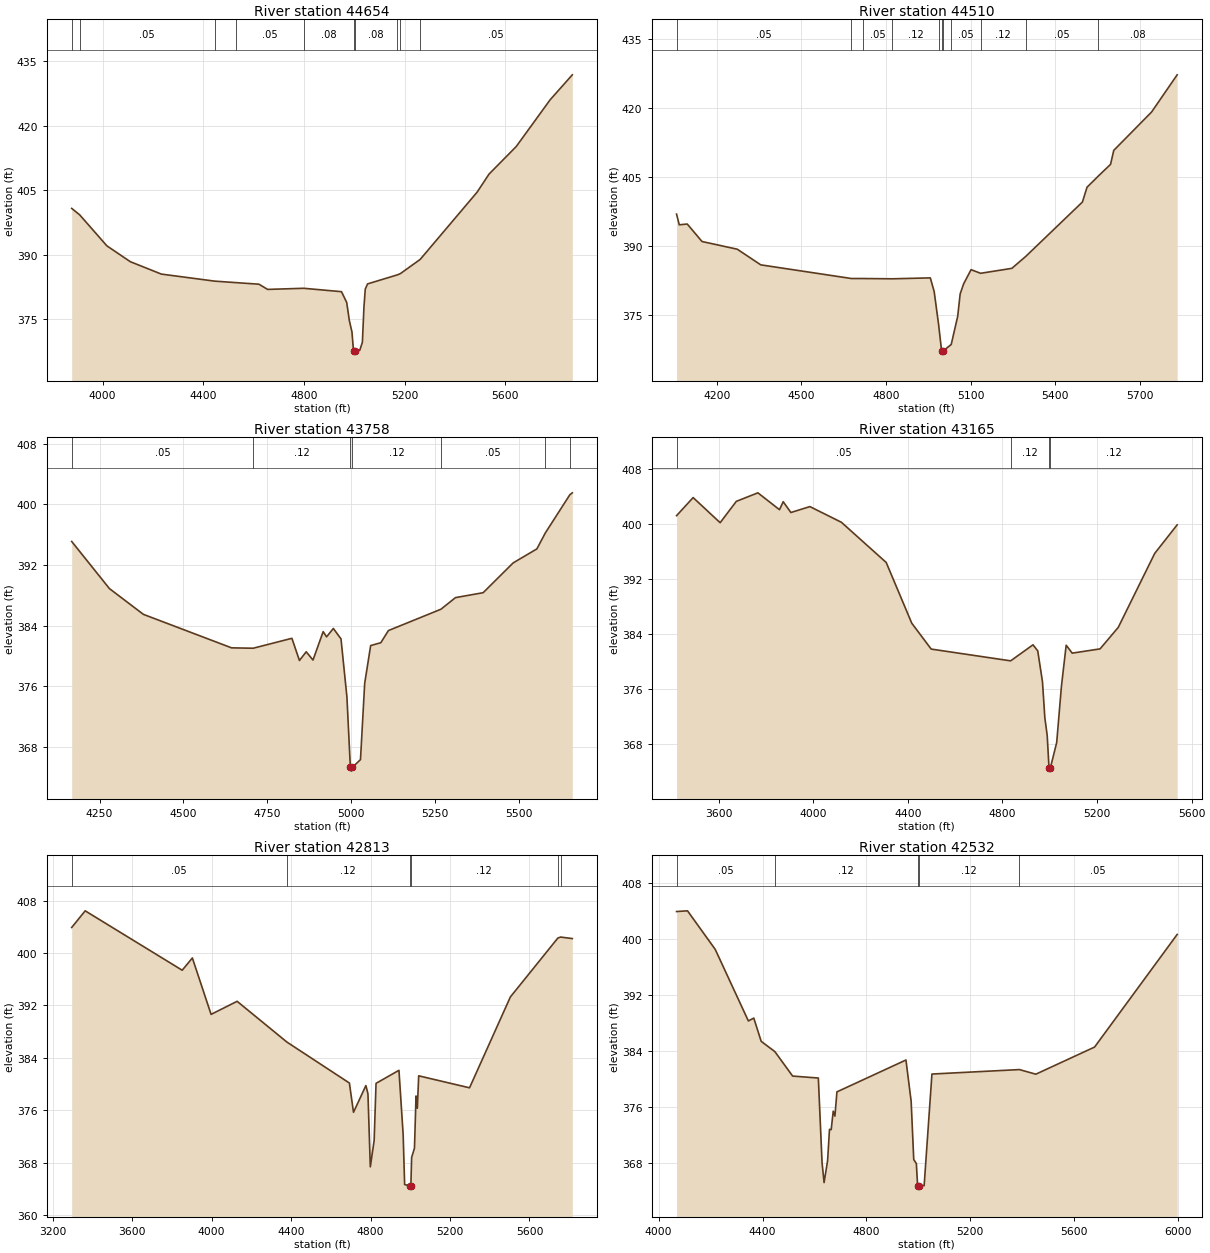
Type RM Length L Ch R = 1 ,44654   ,144,144,144
BEGIN DESCRIPTION:
LITTLE TEHUACANA CREEK 35.0
END DESCRIPTION:
XS GIS Cut Line= 2
      3533214.78     10626789.53      3535134.71     10626268.76
#Sta/Elev= 30
  3877.1  400.81  3908.8  399.31  4016.8  392.11  4110.1  388.42  4233.3  385.54
  4445.4   383.9  4528.9  383.56  4621.2  383.19  4655.8  381.98  4799.1  382.24
  4949.3  381.45    4970  378.93  4980.4  374.74  4990.8  372.08    4997  367.67
  4999.8  367.17    5003  367.67  5021.8  367.83  5032.2   369.7  5038.5  377.96
  5043.7  382.06  5052.9  383.26  5170.8  385.35    5183  385.64  5261.9  388.95
  5488.1  404.58  5535.5  408.78  5643.5  415.18  5778.2  426.04  5866.4  431.85
#Mann= 10 ,-1 , 0
  3877.1     .08       0  3908.8     .05       0  4445.4     .08       0
  4528.9     .05       0  4799.1     .08       0    4997     .07       0
    5003     .08       0  5170.8     .05       0    5183     .12       0
  5261.9     .05       0
Bank Sta=4997,5003
XS Rating Curve= 0 ,0
Exp/Cntr=0.3,0.1

Type RM Length L Ch R = 1 ,44510   ,752,752,752
BEGIN DESCRIPTION:
LITTLE TEHUACANA CREEK 34.0
END DESCRIPTION:
XS GIS Cut Line= 2
      3533423.03      10626897.2      3535126.27     10626401.14
#Sta/Elev= 30
  4057.8  396.92  4067.4  394.59  4095.7  394.76    4148  390.95    4273  389.27
  4356.3  385.86  4677.7  382.88  4718.4  382.88  4822.6  382.82  4957.1  383.02
  4970.8  380.02  4986.6  372.76    4997  367.12  4999.8  366.62    5003  367.12
  5031.1   368.5  5054.1  374.65  5062.8  379.52    5075   381.7  5101.5  384.81
  5135.3  384.02    5246   385.1  5295.4  387.71  5496.1  399.56  5512.4  402.78
  5552.3  405.21  5595.7  407.76  5607.1  410.81  5741.1  419.17  5831.8  427.28
#Mann= 11 ,-1 , 0
  4057.8     .05       0  4677.7     .08       0  4718.4     .05       0
  4822.6     .12       0  4986.6     .08       0    4997     .07       0
    5003     .08       0  5031.1     .05       0  5135.3     .12       0
  5295.4     .05       0  5552.3     .08       0
Bank Sta=4997,5003
XS Rating Curve= 0 ,0
Exp/Cntr=0.3,0.1

Type RM Length L Ch R = 1 ,43758   ,593,593,593
BEGIN DESCRIPTION:
LITTLE TEHUACANA CREEK 33.0
END DESCRIPTION:
XS GIS Cut Line= 2
      3533758.31     10627378.78      3535233.99     10627166.98
#Sta/Elev= 30
  4167.1   395.1  4279.5  388.88  4380.6  385.48  4643.2  381.06  4707.6  381.01
  4822.9  382.32  4845.3  379.39  4865.5  380.54  4885.7  379.45    4916   383.2
  4926.1  382.51  4946.3  383.62  4969.1  382.24  4986.7  374.58    4997  365.29
  4999.8  364.79    5003  365.29  5027.1  366.31  5039.6  376.37  5057.4  381.36
  5087.7  381.74  5110.2  383.34  5266.8  386.16    5310  387.69  5392.4  388.34
  5481.7  392.27  5552.4  394.12  5577.5  396.22  5650.3  401.25  5657.9  401.52
#Mann= 7 ,-1 , 0
  4167.1     .05       0  4707.6     .12       0    4997     .07       0
    5003     .12       0  5266.8     .05       0  5577.5     .12       0
  5650.3     .05       0
Bank Sta=4997,5003
XS Rating Curve= 0 ,0
Exp/Cntr=0.3,0.1

Type RM Length L Ch R = 1 ,43165   ,352,352,352
BEGIN DESCRIPTION:
LITTLE TEHUACANA CREEK 32.0
END DESCRIPTION:
XS GIS Cut Line= 4
       3532969.9     10627418.81      3534428.42     10627750.32
       3534605.5      10627739.9       3535014.9     10627569.89
#Sta/Elev= 30
  3422.4  401.23  3492.5  403.86  3606.7  400.21  3675.1  403.31  3766.3  404.55
  3857.6   402.1  3873.3  403.26  3905.8  401.69  3986.1  402.55  4119.4  400.27
  4308.8  394.43  4416.8  385.61  4498.9  381.85  4834.8  380.14  4929.3  382.47
  4949.4  381.59  4969.4   377.1  4979.4  371.87  4989.4  369.29    4997  364.62
  4999.8  364.12    5003  364.62  5029.5  368.28  5049.5  376.44  5069.6  382.41
  5095.1  381.26  5212.9  381.88  5289.9  385.01  5443.9  395.75  5538.8   399.9
#Mann= 4 ,-1 , 0
  3422.4     .05       0  4834.8     .12       0    4997     .07       0
    5003     .12       0
Bank Sta=4997,5003
XS Rating Curve= 0 ,0
Exp/Cntr=0.3,0.1

Type RM Length L Ch R = 1 ,42813   ,281,281,281
BEGIN DESCRIPTION:
LITTLE TEHUACANA CREEK 31.0
END DESCRIPTION:
XS GIS Cut Line= 4
      3532974.26     10628590.69      3534479.42     10628167.76
      3535035.81      10627701.7      3535146.94     10627500.27
#Sta/Elev= 30
  3296.2  403.89  3364.1  406.43  3852.3  397.37  3903.5  399.24  3997.7  390.64
  4128.7  392.63  4379.1  386.42  4693.7  380.17  4714.4  375.71  4776.7  379.78
  4787.1  378.53    4799  367.39  4818.3  371.42  4827.8  380.12  4943.1  382.11
  4964.3  372.28  4971.7  364.69    4997  364.49  4999.8  363.99    5003  364.49
  5006.9  368.82  5021.2  370.23    5029   378.2  5035.5  376.32  5042.5  381.27
  5298.3  379.44  5503.9   393.3  5742.8  402.28  5756.6  402.43  5815.5   402.2
#Mann= 6 ,-1 , 0
  3296.2     .05       0  4379.1     .12       0    4997     .07       0
    5003     .12       0  5742.8     .05       0  5756.6     .07       0
Bank Sta=4997,5003
XS Rating Curve= 0 ,0
Exp/Cntr=0.3,0.1

Type RM Length L Ch R = 1 ,42532   ,1193,1193,1193
BEGIN DESCRIPTION:
LITTLE TEHUACANA CREEK 30.0
END DESCRIPTION:
XS GIS Cut Line= 4
      3534126.12     10628805.83      3534591.37     10628250.31
      3535035.81     10628243.36      3535611.51     10628735.83
#Sta/Elev= 30
  4069.2  403.94  4111.4  404.04  4218.1  398.52  4345.6  388.28  4366.4  388.69
    4395  385.36  4447.6  383.89    4516  380.39  4614.9  380.11  4629.2     368
    4637  365.15  4650.5  368.28  4657.8  372.76  4664.4  372.73  4672.2  375.37
  4678.7  374.66  4686.5  378.13  4952.1  382.69  4972.1  376.77  4982.1  368.44
  4992.1  367.87    4997  364.71  4999.8  364.21    5003  364.71  5022.1  364.71
  5052.1  380.68  5388.8  381.32  5451.9  380.66    5678  384.54  5995.9  400.66
#Mann= 5 ,-1 , 0
  4069.2     .05       0  4447.6     .12       0    4997     .07       0
    5003     .12       0  5388.8     .05       0
Bank Sta=4997,5003
XS Rating Curve= 0 ,0
Exp/Cntr=0.3,0.1

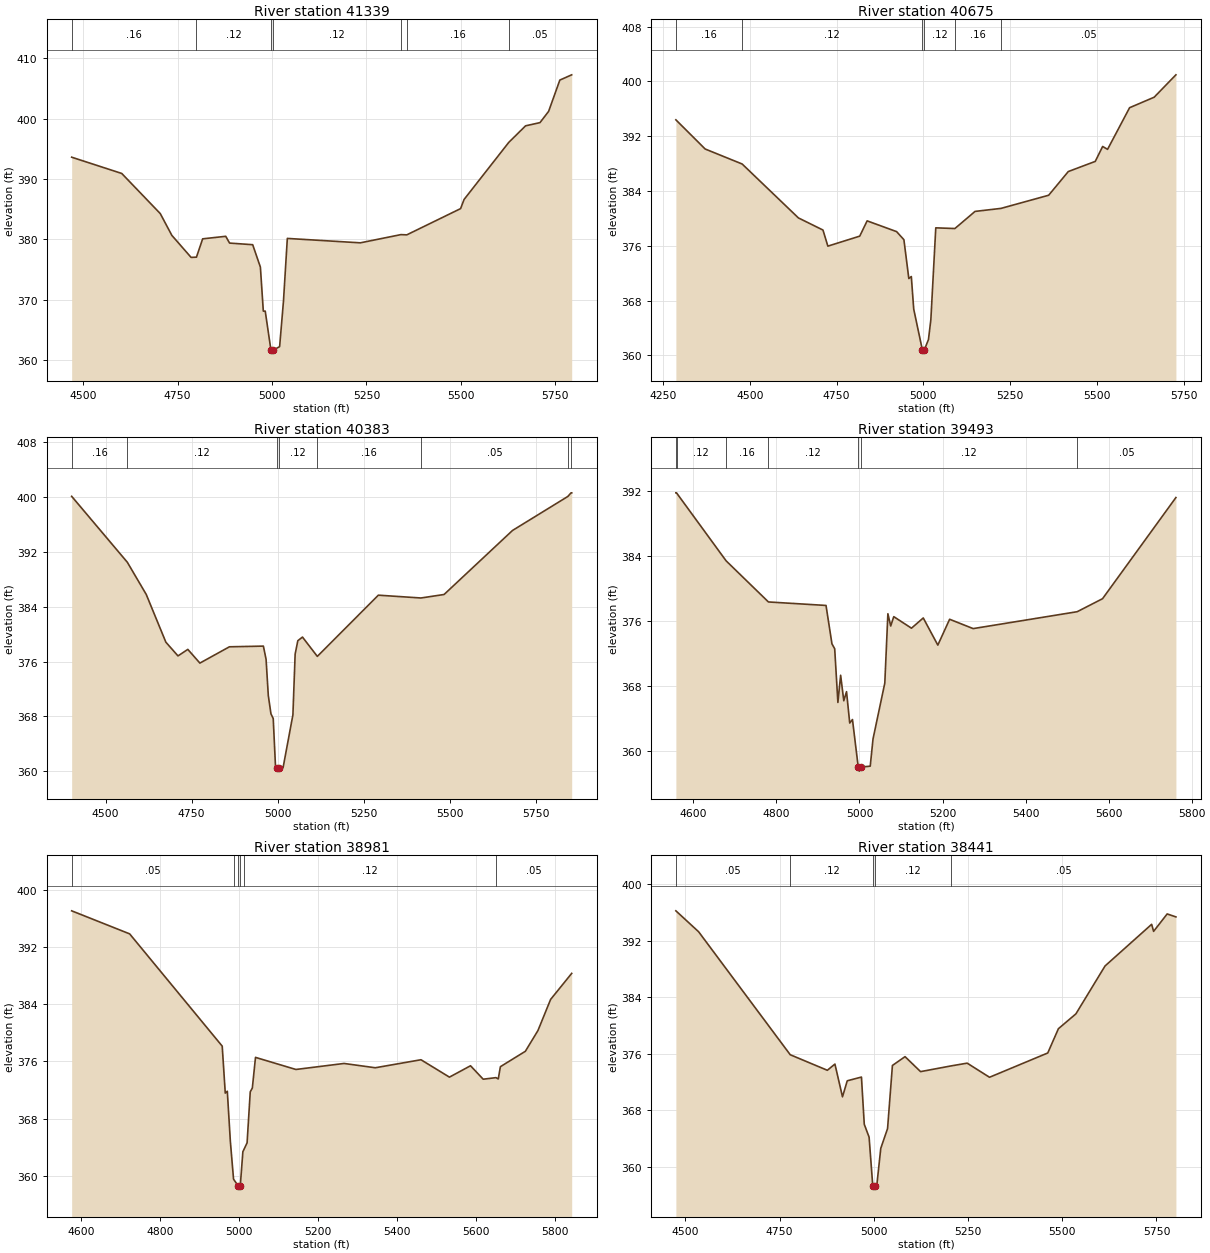
Type RM Length L Ch R = 1 ,41339   ,664,664,664
BEGIN DESCRIPTION:
LITTLE TEHUACANA CREEK 29.0
END DESCRIPTION:
XS GIS Cut Line= 3
      3534399.59     10628910.19      3534899.61     10629010.19
      3535699.65     10628860.18
#Sta/Elev= 30
  4469.4  393.61    4602  390.92    4704  384.28  4734.6  380.68  4785.6  377.03
  4799.8  377.07  4816.2   380.1  4877.3  380.52  4887.5   379.4  4948.7  379.13
  4969.1  375.42  4976.8  368.14  4981.9  368.14    4997  361.69  4999.8  361.19
    5003  361.69    5020  362.26  5030.2   369.8  5040.4  380.17  5233.7  379.44
  5341.1   380.8  5356.7  380.76  5499.1   385.1  5508.4  386.62  5626.7  396.06
  5671.2   398.8  5709.3  399.33  5732.2  401.19  5761.9  406.37  5793.3  407.24
#Mann= 7 ,-1 , 0
  4469.4     .16       0  4799.8     .12       0    4997     .07       0
    5003     .12       0  5341.1     .05       0  5356.7     .16       0
  5626.7     .05       0
Bank Sta=4997,5003
XS Rating Curve= 0 ,0
Exp/Cntr=0.3,0.1

Type RM Length L Ch R = 1 ,40675   ,292,292,292
BEGIN DESCRIPTION:
LITTLE TEHUACANA CREEK 28.0
END DESCRIPTION:
XS GIS Cut Line= 2
      3534310.62     10628979.74      3535348.76     10629979.69
#Sta/Elev= 30
  4286.6  394.39    4371  390.13  4477.7  387.94  4639.8  380.07  4710.6   378.3
  4724.7  375.95  4816.6  377.41  4837.9  379.64  4922.8  378.07  4943.9  376.89
  4958.1  371.22  4965.3  371.51  4972.2  366.76    4997  360.83  4999.8  360.33
    5003  360.83  5014.7  362.31  5021.6  365.22  5035.8  378.62  5090.9  378.52
    5149  381.02  5223.8  381.46  5361.2  383.38  5417.8  386.84  5495.5  388.32
  5516.8   390.5    5531  390.08  5594.5  396.16  5665.3  397.69    5728  400.96
#Mann= 6 ,-1 , 0
  4286.6     .16       0  4477.7     .12       0    4997     .07       0
    5003     .12       0  5090.9     .16       0  5223.8     .05       0
Bank Sta=4997,5003
XS Rating Curve= 0 ,0
Exp/Cntr=0.3,0.1

Type RM Length L Ch R = 1 ,40383   ,890,890,890
BEGIN DESCRIPTION:
LITTLE TEHUACANA CREEK 27.0
END DESCRIPTION:
XS GIS Cut Line= 2
      3534096.77     10629177.24      3535207.82     10630114.69
#Sta/Elev= 30
  4401.3  400.13  4563.1   390.5  4618.1   385.8  4675.2  378.82  4710.4  376.82
    4739  377.77  4774.1  375.77  4859.9  378.15  4958.7  378.25  4966.5  376.32
    4973  371.02  4980.7  368.36  4987.3  367.67  4993.9  360.66    4997  360.49
  4999.8  359.99    5003  360.49  5015.9  360.49  5044.5  368.21    5051  377.08
  5058.8  379.04  5072.3  379.57  5115.5  376.75  5292.9  385.69  5416.8  385.28
    5484  385.79  5682.9  395.14  5843.8  400.11  5853.2  400.64    5855  400.64
#Mann= 8 ,-1 , 0
  4401.3     .16       0  4563.1     .12       0    4997     .07       0
    5003     .12       0  5115.5     .16       0  5416.8     .05       0
  5843.8     .16       0  5853.2     .05       0
Bank Sta=4997,5003
XS Rating Curve= 0 ,0
Exp/Cntr=0.3,0.1

Type RM Length L Ch R = 1 ,39493   ,512,512,512
BEGIN DESCRIPTION:
LITTLE TEHUACANA CREEK 26.0
END DESCRIPTION:
XS GIS Cut Line= 3
      3533849.62      10629560.2      3534199.61     10629860.19
      3534699.63     10630410.21
#Sta/Elev= 30
  4557.8  391.78  4559.3  391.78  4678.8  383.41  4780.7  378.35  4919.4  377.92
  4933.7  373.19  4940.3  372.59    4948  365.98  4954.6  369.33  4962.2  366.19
  4968.8  367.31  4976.5  363.45  4983.1  363.88    4997  358.03  4999.8  357.53
    5003  358.03  5025.9  358.14  5032.6  361.49    5061  368.37  5068.4   376.9
  5075.2  375.39  5082.6  376.54  5125.2  375.12  5153.6  376.38  5188.7  373.04
  5217.1  376.22  5273.8  375.07  5524.4  377.15  5585.4  378.75  5762.1   391.2
#Mann= 7 ,-1 , 0
  4557.8     .16       0  4559.3     .12       0  4678.8     .16       0
  4780.7     .12       0    4997     .07       0    5003     .12       0
  5524.4     .05       0
Bank Sta=4997,5003
XS Rating Curve= 0 ,0
Exp/Cntr=0.3,0.1

Type RM Length L Ch R = 1 ,38981   ,540,540,540
BEGIN DESCRIPTION:
LITTLE TEHUACANA CREEK 25.0
END DESCRIPTION:
XS GIS Cut Line= 3
      3533399.58     10630060.18      3533799.61     10630160.19
      3534599.57     10630460.17
#Sta/Elev= 30
  4575.8  397.04  4722.7  393.82  4957.2  378.13  4964.9  371.57  4970.1  371.83
  4977.8  364.83  4985.9  359.54    4997  358.65  4999.8  358.15    5003  358.65
  5009.5  363.38  5011.7  363.63  5020.2  364.62  5028.2  371.75  5033.5  372.28
  5041.5  376.56  5143.9  374.87  5265.8  375.71    5345  375.11  5460.7  376.23
  5532.8   373.8  5586.2  375.39  5618.3  373.51  5650.6  373.73  5656.5  373.55
  5661.9  375.26  5725.1  377.41  5757.1  380.32  5789.1  384.66  5842.5   388.3
#Mann= 6 ,-1 , 0
  4575.8     .05       0  4985.9     .16       0    4997     .07       0
    5003     .16       0  5011.7     .12       0  5650.6     .05       0
Bank Sta=4997,5003
XS Rating Curve= 0 ,0
Exp/Cntr=0.3,0.1

Type RM Length L Ch R = 1 ,38441   ,1202,1202,1202
BEGIN DESCRIPTION:
LITTLE TEHUACANA CREEK 24.0
END DESCRIPTION:
XS GIS Cut Line= 3
      3533449.58     10630610.19      3533949.61     10630660.19
      3534749.57      10630460.2
#Sta/Elev= 30
  4474.5  396.27  4534.8  393.31    4778  375.89  4876.5  373.69  4896.6  374.57
  4916.7  369.93  4929.3   372.2    4967  372.73  4974.5  366.04  4987.3  364.22
    4997  357.36  4999.8  356.86    5003  357.36  5007.9  357.46  5018.3  362.64
  5036.3  365.43  5049.2  374.37  5082.7  375.62  5123.9   373.5    5205  374.31
  5247.6   374.7  5306.9   372.7  5461.5  376.14  5489.8  379.58  5536.2  381.68
  5613.5  388.46  5737.2  394.36  5742.4  393.36  5778.4  395.83  5801.6  395.41
#Mann= 5 ,-1 , 0
  4474.5     .05       0    4778     .12       0    4997     .07       0
    5003     .12       0    5205     .05       0
Bank Sta=4997,5003
XS Rating Curve= 0 ,0
Exp/Cntr=0.3,0.1