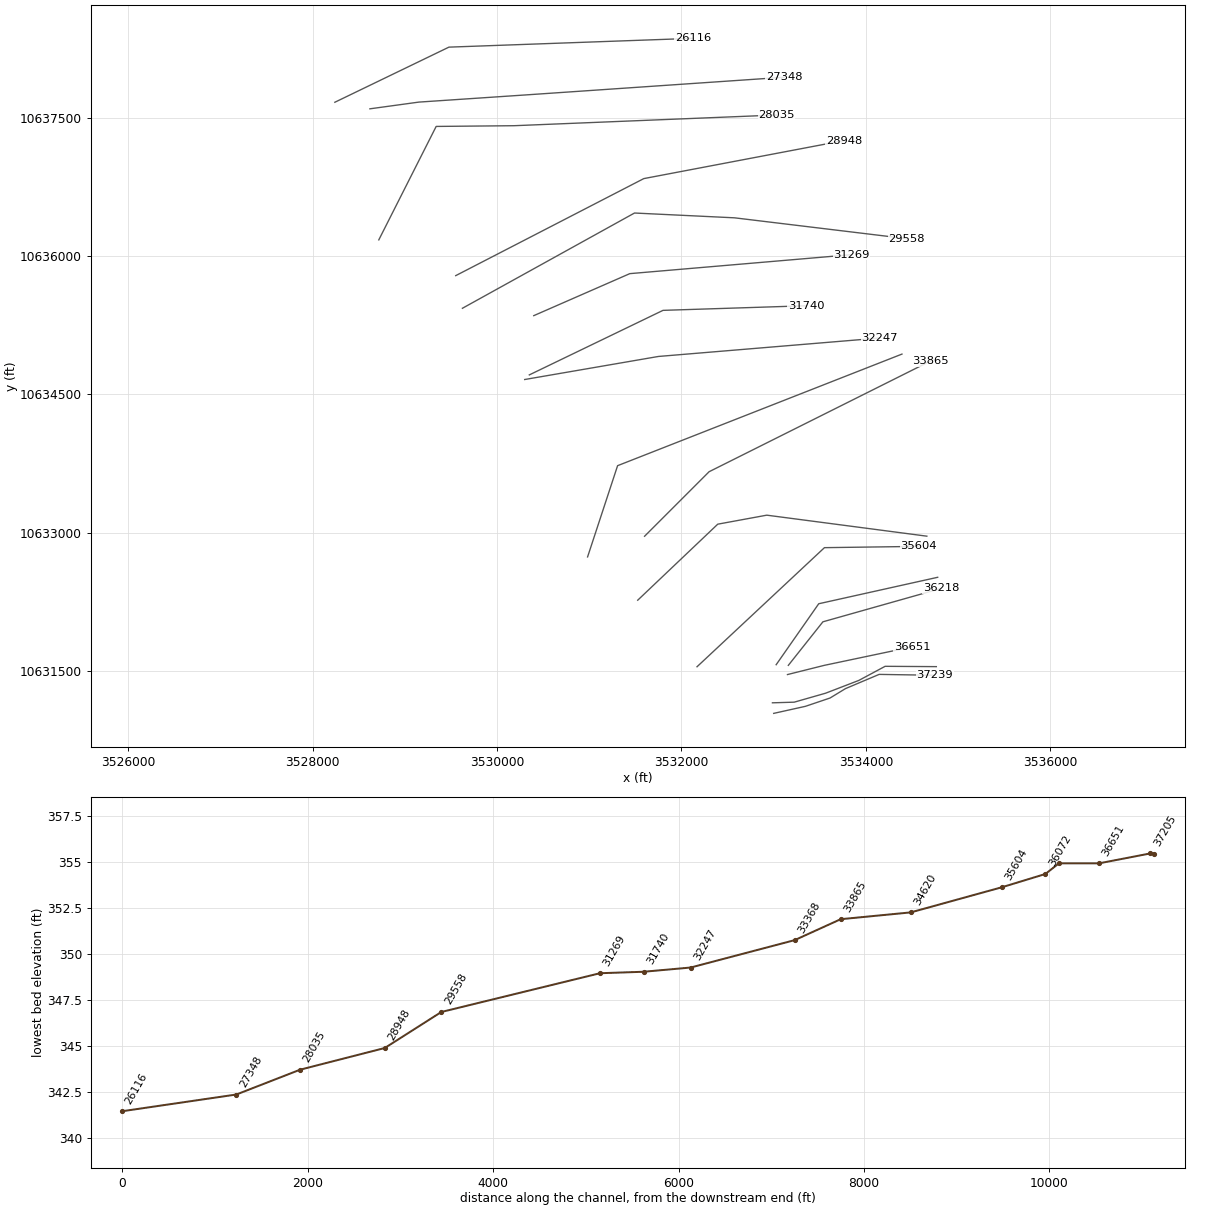
HEC-RAS study LITTLE TEHUACANA CREEK.prj: LITTLE TEHUACANA CREEK Base Level Engineering

--- LITTLE TEHUACANA CREEK.g01 (geometry) --- (continued)

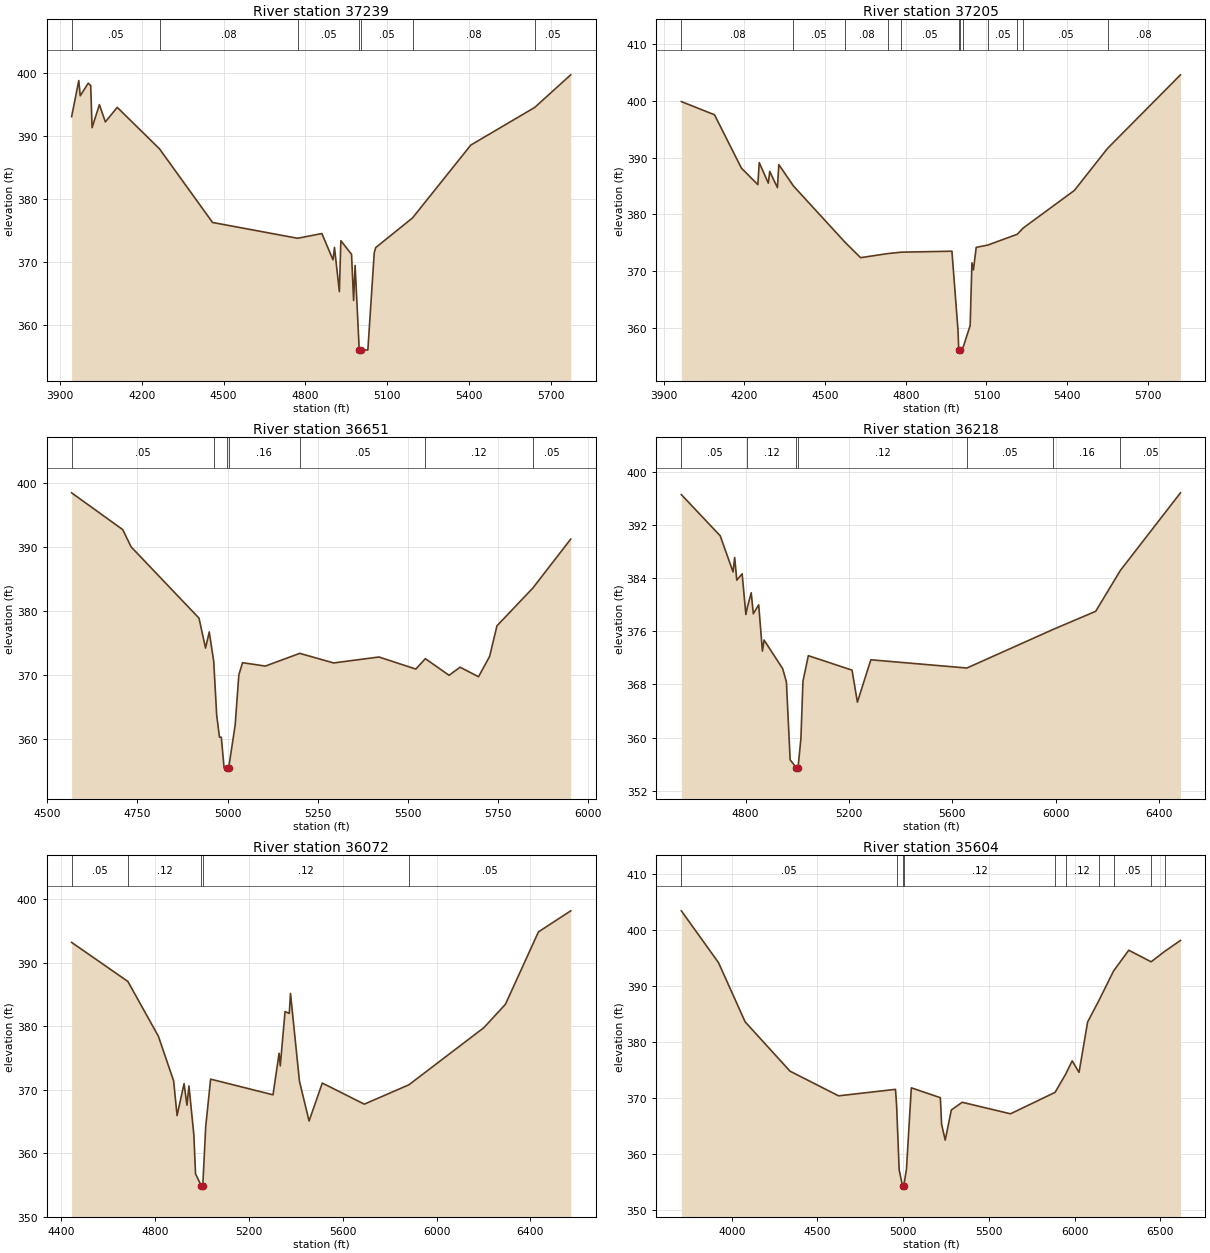
Type RM Length L Ch R = 1 ,37239   ,34,34,34
BEGIN DESCRIPTION:
LITTLE TEHUACANA CREEK 23.0
END DESCRIPTION:
XS GIS Cut Line= 6
      3533000.21     10631039.19        3533344.     10631115.59
      3533611.36     10631205.86       3533778.3      10631307.5
      3534143.75     10631462.02      3534745.69     10631452.41
#Sta/Elev= 30
  3943.2  393.05  3969.5  398.79  3974.7  396.37  4004.1  398.37  4013.1  397.99
  4018.2  391.31    4045  394.96  4066.8  392.22  4110.4  394.53  4265.2  387.94
  4459.6  376.24  4771.1  373.73  4860.1  374.48  4900.9  370.31  4906.3  372.27
  4924.2  365.25  4929.7  373.35  4968.8  371.18  4976.4  363.85  4981.9  369.42
    4997  355.98  4999.8  355.48    5003  355.98  5028.6  355.98    5052  371.44
  5057.4  372.25  5192.4  376.97  5405.8  388.54  5639.6  394.51  5771.9   399.7
#Mann= 7 ,-1 , 0
  3943.2     .05       0  4265.2     .08       0  4771.1     .05       0
    4997     .04       0    5003     .05       0  5192.4     .08       0
  5639.6     .05       0
Bank Sta=4997,5003
XS Rating Curve= 0 ,0
Exp/Cntr=0.3,0.1

Type RM Length L Ch R = 1 ,37205   ,554,554,554
BEGIN DESCRIPTION:
LITTLE TEHUACANA CREEK 22.0
END DESCRIPTION:
XS GIS Cut Line= 6
      3532986.37     10631153.78      3533222.47     10631160.72
      3533562.75     10631257.95      3533923.86     10631396.84
      3534208.58     10631549.61      3534764.13     10631546.14
#Sta/Elev= 30
  3965.6  399.87  4088.9  397.54  4188.9  388.13    4250  385.22  4255.2  389.11
    4289  385.48  4294.2  387.55  4322.8   384.7    4328  388.75  4382.4  384.98
  4574.6  375.03  4632.1  372.33  4732.7  373.05  4783.5   373.3  4971.6  373.47
  4994.2  359.55    4997  355.99  4999.8  355.49    5003  355.99  5013.7   356.6
  5039.4  360.36    5046  371.43  5051.6  370.18  5061.9  374.15    5104  374.54
  5214.5  376.46  5236.8  377.57  5426.8  384.19  5550.2  391.61  5821.3  404.59
#Mann= 12 ,-1 , 0
  3965.6     .08       0  4382.4     .05       0  4574.6     .08       0
  4732.7     .12       0  4783.5     .05       0    4997     .04       0
    5003     .05       0  5013.7     .08       0    5104     .05       0
  5214.5     .08       0  5236.8     .05       0  5550.2     .08       0
Bank Sta=4997,5003
XS Rating Curve= 0 ,0
Exp/Cntr=0.3,0.1

Type RM Length L Ch R = 1 ,36651   ,433,433,433
BEGIN DESCRIPTION:
LITTLE TEHUACANA CREEK 21.0
END DESCRIPTION:
XS GIS Cut Line= 3
      3533149.63     10631460.19      3533549.61     10631560.19
      3534499.59     10631760.19
#Sta/Elev= 30
  4567.8   398.5  4709.5  392.74  4732.7  390.04  4920.8  378.89  4938.9  374.21
  4949.2  376.73  4961.6  372.11  4969.8  363.72  4977.5  360.26  4982.6  360.26
  4990.3  355.45    4997  355.45  4999.8  354.95    5003  355.45    5021  362.16
  5031.2  370.02  5041.4  371.92  5104.6  371.39    5200  373.38  5293.7  371.88
  5419.5  372.81  5521.7  370.92    5548  372.55  5613.7  369.95  5644.3  371.21
  5695.4  369.72  5726.1   372.9  5746.5  377.69  5845.9   383.6  5950.9  391.26
#Mann= 7 ,-1 , 0
  4567.8     .05       0  4961.6     .16       0    4997     .07       0
    5003     .16       0    5200     .05       0    5548     .12       0
  5845.9     .05       0
Bank Sta=4997,5003
XS Rating Curve= 0 ,0
Exp/Cntr=0.3,0.1

Type RM Length L Ch R = 1 ,36218   ,146,146,146
BEGIN DESCRIPTION:
LITTLE TEHUACANA CREEK 20.0
END DESCRIPTION:
XS GIS Cut Line= 3
      3533158.84     10631560.06      3533533.81     10632032.25
       3534813.4     10632393.62
#Sta/Elev= 30
  4551.2   396.6  4701.7   390.4  4751.4  384.96  4757.7  387.14  4765.8  383.72
  4786.6  384.67    4801  378.54  4807.3  379.72  4821.8  381.81  4829.9  378.65
  4850.7     380  4865.1  373.03  4871.5  374.69  4943.6  370.38    4958  368.39
  4972.5  356.65    4997  355.45  4999.8  354.95    5003  355.45  5014.1  359.84
  5022.1  368.49  5042.9  372.34  5212.1  370.16  5232.9  365.34  5284.9  371.72
  5656.8  370.48  5989.9  376.28  6155.5  379.02  6251.3  385.19  6483.8  396.87
#Mann= 7 ,-1 , 0
  4551.2     .05       0  4807.3     .12       0    4997     .07       0
    5003     .12       0  5656.8     .05       0  5989.9     .16       0
  6251.3     .05       0
Bank Sta=4997,5003
XS Rating Curve= 0 ,0
Exp/Cntr=0.3,0.1

Type RM Length L Ch R = 1 ,36072   ,468,468,468
BEGIN DESCRIPTION:
LITTLE TEHUACANA CREEK 19.0
END DESCRIPTION:
XS GIS Cut Line= 3
      3533026.85     10631566.94      3533488.53     10632228.17
      3534778.74     10632515.16
#Sta/Elev= 30
  4443.8  393.22  4683.7  387.07  4813.7  378.45  4878.7  371.42  4893.5  365.95
  4923.2  370.98  4935.6  367.59  4944.1  370.61    4965  362.92  4972.2  356.78
    4997  354.87  4999.8  354.37    5003  354.87  5015.6  364.23  5036.5  371.69
  5302.6  369.22  5328.4  375.77  5333.5  373.77  5353.8  382.33  5371.9  382.04
  5377.1  385.17  5415.3  371.36  5456.3   365.1  5512.7  371.07  5691.9  367.75
  5881.6  370.79  6201.3  379.78  6293.5  383.47  6434.3  394.87    6572  398.19
#Mann= 5 ,-1 , 0
  4443.8     .05       0  4683.7     .12       0    4997     .07       0
    5003     .12       0  5881.6     .05       0
Bank Sta=4997,5003
XS Rating Curve= 0 ,0
Exp/Cntr=0.3,0.1

Type RM Length L Ch R = 1 ,35604   ,984,984,984
BEGIN DESCRIPTION:
LITTLE TEHUACANA CREEK 18.0
END DESCRIPTION:
XS GIS Cut Line= 3
      3532168.55     10631544.81       3533550.5     10632836.49
      3534571.39     10632850.38
#Sta/Elev= 30
  3705.6  403.38  3922.5  394.12  4077.9  383.54  4339.7  374.73    4623  370.32
  4955.2  371.48  4961.9  368.57  4976.7  357.09    4997  354.15  4999.8  353.65
    5003  354.15  5019.2   357.2  5047.6  371.75  5217.1  369.99  5224.4  365.22
  5245.4  362.41  5281.1  367.79  5344.6  369.17  5626.3  367.11  5886.5  370.94
  5948.1  374.18  5986.4  376.57  6026.4  374.51  6076.4  383.51    6141  387.27
  6227.5  392.61  6316.4  396.34  6447.2  394.27  6525.5  396.12  6618.2  398.09
#Mann= 10 ,-1 , 0
  3705.6     .05       0  4961.9     .12       0    4997     .07       0
    5003     .12       0  5886.5     .16       0  5948.1     .12       0
    6141     .16       0  6227.5     .05       0  6447.2     .16       0
  6525.5     .05       0
Bank Sta=4997,5003
XS Rating Curve= 0 ,0
Exp/Cntr=0.3,0.1

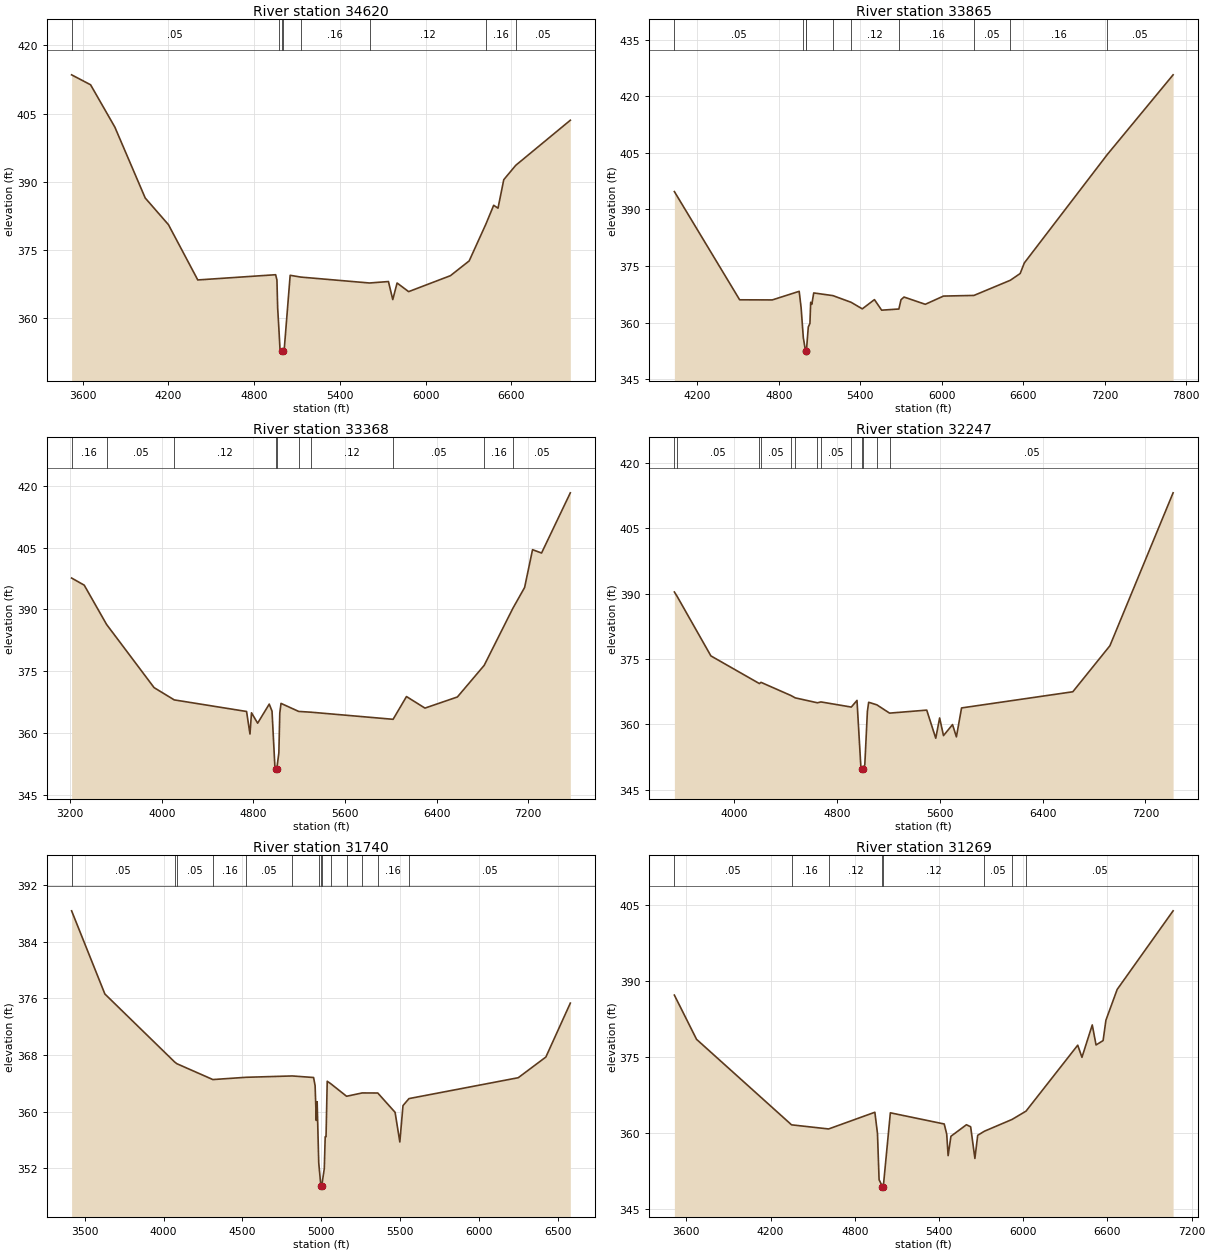
Type RM Length L Ch R = 1 ,34620   ,755,755,755
BEGIN DESCRIPTION:
LITTLE TEHUACANA CREEK 17.0
END DESCRIPTION:
XS GIS Cut Line= 4
      3531525.33      10632266.6      3532393.39     10633091.26
      3532925.07     10633188.92      3534661.18     10632961.05
#Sta/Elev= 30
  3523.6  413.51  3656.4  411.32  3826.3     402  4038.6  386.41  4201.2  380.54
  4406.3  368.38  4950.9  369.53    4960  368.38  4965.1  362.27  4973.2  357.93
  4981.4  353.21    4997  352.78  4999.8  352.28    5003  352.78  5011.9  353.41
  5052.6   369.4  5127.3  369.01  5607.6  367.71  5740.1  368.03  5770.4  364.06
  5800.6  367.71  5881.3  365.81  6173.8  369.32  6304.9  372.57  6420.9   380.6
  6476.4  384.81  6506.6  384.17    6547  390.45    6631  393.61  7012.5  403.52
#Mann= 8 ,-1 , 0
  3523.6     .05       0  4973.2     .12       0    4997     .07       0
    5003     .12       0  5127.3     .16       0  5607.6     .12       0
  6420.9     .16       0    6631     .05       0
Bank Sta=4997,5003
XS Rating Curve= 0 ,0
Exp/Cntr=0.3,0.1

Type RM Length L Ch R = 1 ,33865   ,497,497,497
BEGIN DESCRIPTION:
LITTLE TEHUACANA CREEK 16.0
END DESCRIPTION:
XS GIS Cut Line= 3
      3531599.62      10632960.2      3532299.61     10633660.19
       3534699.6     10634860.18
#Sta/Elev= 30
  4030.9  394.75  4511.7  366.05  4752.1  366.02  4950.1   368.3  4964.3  363.97
  4980.6  355.99    4997  352.41  4999.8  351.91    5003  352.41  5017.3  358.86
  5029.2  359.78  5034.8  365.39  5043.2  364.84  5057.2  367.87  5198.6  367.16
  5332.5  365.39  5414.9  363.65  5504.4   366.1  5557.5   363.3  5684.4  363.61
    5700  366.07  5722.4  366.78  5878.9  364.86  6013.1  367.04  6237.4  367.21
  6505.1  371.23  6577.7  373.02  6608.4  375.83  7219.7  404.59  7704.1  425.71
#Mann= 10 ,-1 , 0
  4030.9     .05       0  4980.6     .12       0    4997     .07       0
    5003     .12       0  5198.6     .16       0  5332.5     .12       0
  5684.4     .16       0  6237.4     .05       0  6505.1     .16       0
  7219.7     .05       0
Bank Sta=4997,5003
XS Rating Curve= 0 ,0
Exp/Cntr=0.3,0.1

Type RM Length L Ch R = 1 ,33368   ,1121,1121,1121
BEGIN DESCRIPTION:
LITTLE TEHUACANA CREEK 15.0
END DESCRIPTION:
XS GIS Cut Line= 3
      3530981.57     10632736.11      3531307.08     10633725.65
      3534391.22     10634935.89
#Sta/Elev= 30
  3211.8  397.61  3322.1  395.88  3516.9  386.37  3931.9  371.03    4108  368.05
  4739.6  365.24  4769.4  359.77  4782.6  364.92  4836.3   362.4  4937.5  367.03
  4961.9  365.32  4986.4  352.11    4997  351.27  4999.8  350.77    5003  351.27
  5021.5  355.19  5029.7  364.86  5040.4   367.2  5194.8  365.25  5300.4  365.07
    6019  363.34    6136  368.86  6297.3  366.06  6580.6  368.76  6814.5  376.43
  7063.8  390.21  7167.4  395.32  7236.7  404.49  7315.4  403.68  7566.6  418.28
#Mann= 10 ,-1 , 0
  3211.8     .16       0  3516.9     .05       0    4108     .12       0
    4997     .07       0    5003     .12       0  5194.8     .16       0
  5300.4     .12       0    6019     .05       0  6814.5     .16       0
  7063.8     .05       0
Bank Sta=4997,5003
XS Rating Curve= 0 ,0
Exp/Cntr=0.3,0.1

Type RM Length L Ch R = 1 ,32247   ,507,507,507
BEGIN DESCRIPTION:
LITTLE TEHUACANA CREEK 13.0
END DESCRIPTION:
XS GIS Cut Line= 3
      3530299.63     10634660.19      3531749.61     10634910.19
      3534149.62     10635110.19
#Sta/Elev= 30
    3536  390.38  3556.8  389.41  3820.1  375.72  4197.5  369.37    4210  369.65
  4442.9  366.63  4476.4  366.09  4648.8  364.96    4676  365.16  4912.4  363.98
  4956.6  365.51  4987.1  350.06    4997  349.78  4999.8  349.28    5003  349.78
  5017.4  350.75  5037.5  362.99  5047.5  365.08  5111.1  364.49    5210  362.59
  5499.1  363.28  5569.3  356.83  5599.4  361.48  5629.5  357.43  5699.8  359.96
  5729.9  357.14    5770  363.78  6635.5  367.49    6924  378.05  7415.7  413.14
#Mann= 13 ,-1 , 0
    3536     .16       0  3556.8     .05       0  4197.5     .12       0
    4210     .05       0  4442.9     .16       0  4476.4     .05       0
  4648.8     .16       0    4676     .05       0  4912.4     .12       0
    4997     .07       0    5003     .12       0  5111.1     .07       0
    5210     .05       0
Bank Sta=4997,5003
XS Rating Curve= 0 ,0
Exp/Cntr=0.3,0.1

Type RM Length L Ch R = 1 ,31740   ,471,471,471
BEGIN DESCRIPTION:
LITTLE TEHUACANA CREEK 12.0
END DESCRIPTION:
XS GIS Cut Line= 3
      3530349.65     10634710.21      3531799.61     10635410.19
      3533349.63     10635460.19
#Sta/Elev= 30
  3417.4  388.37  3628.3  376.62  4070.2  367.02  4084.5  366.77  4312.8  364.53
  4522.8  364.85  4815.9  365.04  4951.1  364.82  4960.8  363.65  4968.2  358.75
  4973.7   361.4  4983.7  352.79    4997  349.55  4999.8  349.05    5003  349.55
  5018.9  351.94  5024.7  356.45    5030  356.45  5037.5  364.29  5061.3  363.92
  5160.2  362.17  5259.1  362.64  5357.9  362.63  5467.7   359.9  5497.7  355.71
  5517.7  360.85  5555.6  361.84  6248.1  364.79  6423.2  367.71  6578.3  375.33
#Mann= 14 ,-1 , 0
  3417.4     .05       0  4070.2     .16       0  4084.5     .05       0
  4312.8     .16       0  4522.8     .05       0  4815.9     .16       0
  4983.7     .12       0    4997     .07       0    5003     .12       0
  5061.3     .05       0  5160.2     .16       0  5259.1     .12       0
  5357.9     .16       0  5555.6     .05       0
Bank Sta=4997,5003
XS Rating Curve= 0 ,0
Exp/Cntr=0.3,0.1

Type RM Length L Ch R = 1 ,31269   ,1711,1711,1711
BEGIN DESCRIPTION:
LITTLE TEHUACANA CREEK 9.0
END DESCRIPTION:
XS GIS Cut Line= 3
      3530397.83     10635352.74      3531439.46     10635808.45
      3533846.51     10636014.45
#Sta/Elev= 30
  3514.6  387.18  3672.6  378.47  4349.4  361.63  4613.3  360.82  4942.8  364.11
  4961.5  359.91  4972.9  350.82    4997  349.47  4999.8  348.97    5003  349.47
  5053.2     364  5436.9   361.8  5454.6  359.81  5464.7  355.56  5484.7  359.38
  5595.1  361.65  5625.2  361.25  5655.4  355.01  5675.4  359.57  5722.7  360.37
  5920.6   362.7  6019.6  364.33    6388  377.32  6418.1  374.93  6491.5  381.31
  6518.5  377.36  6568.7  378.23  6588.8  382.24    6669   388.3  7067.4  403.78
#Mann= 8 ,-1 , 0
  3514.6     .05       0  4349.4     .16       0  4613.3     .12       0
    4997     .07       0    5003     .12       0  5722.7     .05       0
  5920.6     .07       0  6019.6     .05       0
Bank Sta=4997,5003
XS Rating Curve= 0 ,0
Exp/Cntr=0.3,0.1

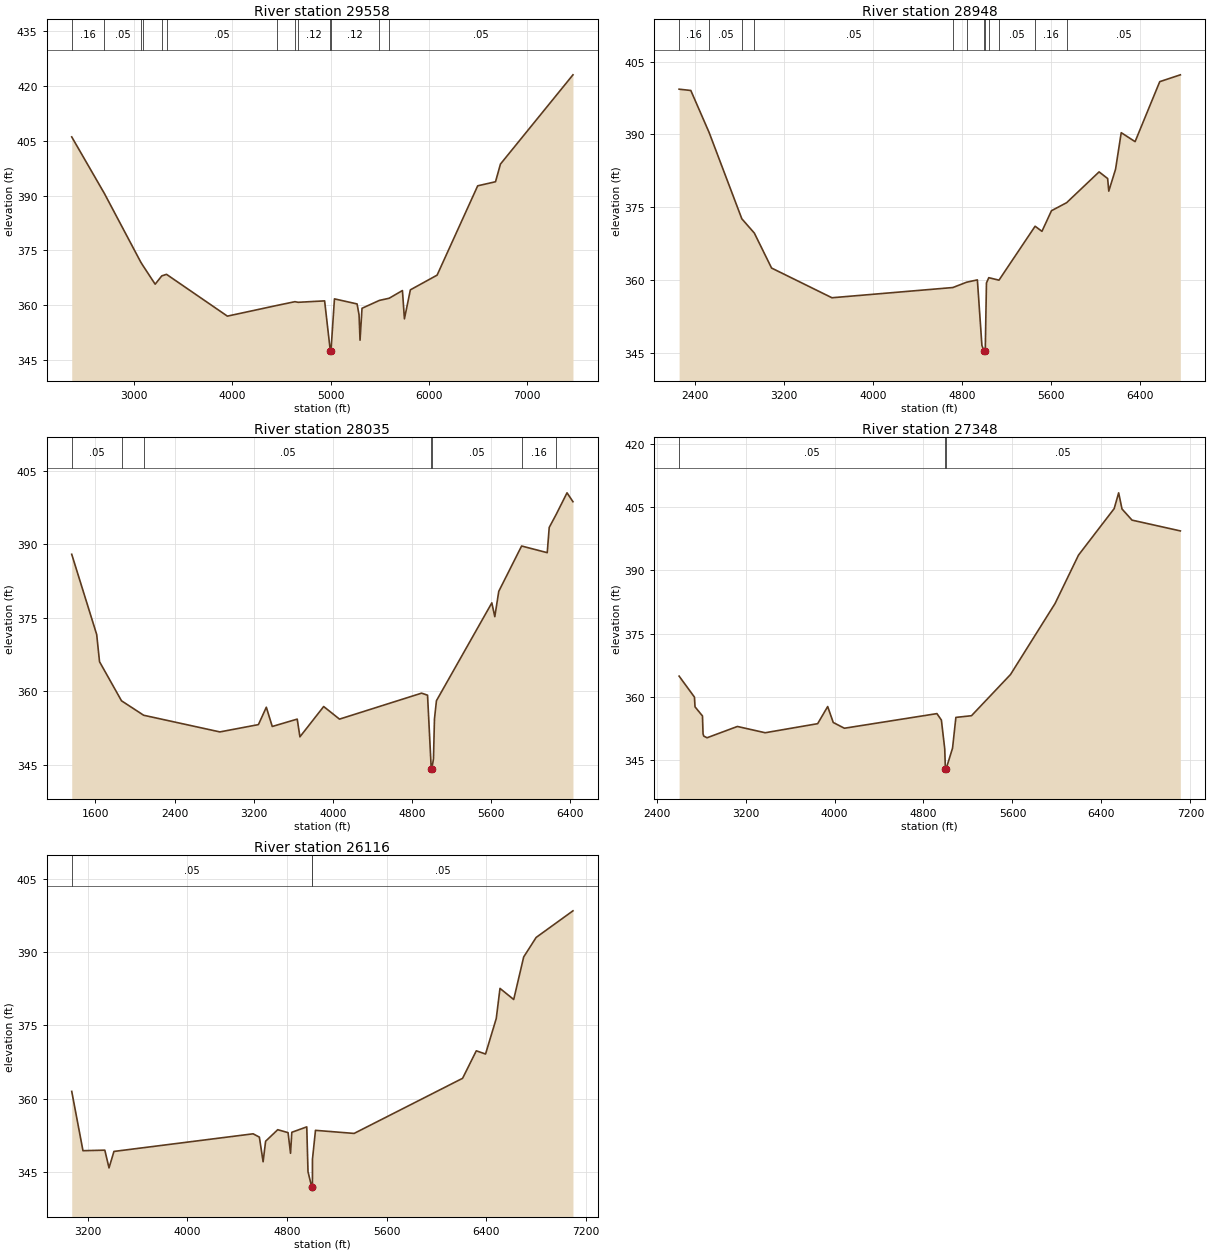
Type RM Length L Ch R = 1 ,29558   ,610,610,610
BEGIN DESCRIPTION:
Mapping XS acbedec3
END DESCRIPTION:
XS GIS Cut Line= 4
      3529624.09      10635432.9      3531490.45     10636465.91
      3532575.52     10636413.83      3534441.84     10636188.13
#Sta/Elev= 30
  2365.7  406.08    2699  390.54  3068.8  371.75  3088.9  370.89  3214.6  365.74
  3281.7  368.01    3330  368.44  3949.3  356.99  4458.5  359.95  4636.4  360.95
  4669.4  360.78  4938.5  361.17    4997  347.36  4999.8  346.86    5003  347.36
  5038.6  361.72  5268.9  360.33  5288.9  357.34  5298.9   350.4    5319  359.14
  5495.7   361.3  5595.1  361.89  5730.3     364  5750.5  356.25  5810.9  364.19
  6082.9  368.22  6495.9  392.68  6677.2   393.8  6727.5  398.64  7465.1  423.08
#Mann= 13 ,-1 , 0
  2365.7     .16       0    2699     .05       0  3068.8     .16       0
  3088.9     .12       0  3281.7     .16       0    3330     .05       0
  4458.5     .12       0  4636.4     .16       0  4669.4     .12       0
    4997     .07       0    5003     .12       0  5495.7     .16       0
  5595.1     .05       0
Bank Sta=4997,5003
XS Rating Curve= 0 ,0
Exp/Cntr=0.3,0.1

Type RM Length L Ch R = 1 ,28948   ,913,913,913
BEGIN DESCRIPTION:
LITTLE TEHUACANA CREEK 8.0
END DESCRIPTION:
XS GIS Cut Line= 3
      3529551.47     10635786.76      3531591.37     10636839.26
      3533761.53     10637251.59
#Sta/Elev= 30
    2258  399.34  2363.2  399.07  2527.6  390.41  2821.5  372.61  2934.1  369.66
  3088.8  362.45  3631.4  356.32  4718.1  358.43  4840.9  359.52  4938.4  360.01
  4979.1  346.49    4997   345.4  4999.8   344.9    5003   345.4  5009.2   345.4
  5019.9  359.37  5040.8  360.46  5132.4  359.95  5457.2  371.07  5518.6  370.02
  5604.1  374.27  5740.5  375.93  6032.1  382.28    6109  380.91  6119.2  378.31
  6180.2  382.84  6231.1  390.37  6355.7  388.52  6577.2  400.89  6762.4   402.3
#Mann= 12 ,-1 , 0
    2258     .16       0  2527.6     .05       0  2821.5     .12       0
  2934.1     .05       0  4718.1     .16       0  4840.9     .12       0
    4997     .07       0    5003     .12       0  5040.8     .16       0
  5132.4     .05       0  5457.2     .16       0  5740.5     .05       0
Bank Sta=4997,5003
XS Rating Curve= 0 ,0
Exp/Cntr=0.3,0.1

Type RM Length L Ch R = 1 ,28035   ,687,687,687
BEGIN DESCRIPTION:
LITTLE TEHUACANA CREEK 6.0
END DESCRIPTION:
XS GIS Cut Line= 4
      3528717.24     10636174.77      3529339.39     10637405.09
      3530183.24     10637412.89      3533029.71     10637528.93
#Sta/Elev= 30
  1359.6  387.96  1612.2  371.59    1641  366.04  1863.2  358.07  2087.5  355.12
  2858.5  351.72  3248.5  353.21  3328.5  356.76  3388.5  352.83  3641.1  354.33
  3668.6  350.72  3908.8   356.9  4068.9  354.33  4899.6  359.63  4959.7  359.21
    4997  344.22  4999.8  343.72    5003  344.22  5019.7  346.21  5029.7  354.36
  5049.8  358.09  5610.2  378.05  5640.2  375.23  5680.3   380.4  5911.4  389.65
  6170.7  388.29  6190.7  393.43  6263.4  396.18  6370.9   400.5    6431  398.69
#Mann= 7 ,-1 , 0
  1359.6     .05       0  1863.2     .16       0  2087.5     .05       0
    4997     .03       0    5003     .05       0  5911.4     .16       0
  6263.4     .05       0
Bank Sta=4997,5003
XS Rating Curve= 0 ,0
Exp/Cntr=0.3,0.1

Type RM Length L Ch R = 1 ,27348   ,1232,1232,1232
BEGIN DESCRIPTION:
LITTLE TEHUACANA CREEK 5.0
END DESCRIPTION:
XS GIS Cut Line= 4
       3528620.6     10637596.06      3529151.89     10637668.98
      3530332.72     10637748.22      3533113.05     10637938.65
#Sta/Elev= 30
  2602.9  364.92  2740.9  359.93  2745.9  357.63    2813  355.46    2818  351.25
    2824  350.69  2854.2  350.29  3126.8  352.97  3376.8  351.48  3848.5  353.63
  3938.7   357.7  3988.8  353.91    4089  352.55  4920.9  356.02    4961  354.49
  4991.1  347.66    4997  342.87  4999.8  342.37    5003  342.87  5061.3  347.83
  5091.3  355.12  5231.7  355.52  5582.5   365.3  5983.4  382.17  6193.9  393.64
  6514.7  404.68  6554.8  408.42  6584.8  404.59    6675  401.94  7109.5  399.38
#Mann= 3 ,-1 , 0
  2602.9     .05       0    4997     .03       0    5003     .05       0
Bank Sta=4997,5003
XS Rating Curve= 0 ,0
Exp/Cntr=0.3,0.1

Type RM Length L Ch R = 1 ,26116   ,0,0,0
BEGIN DESCRIPTION:
LITTLE TEHUACANA CREEK 7.0
END DESCRIPTION:
XS GIS Cut Line= 3
      3528240.44     10637667.25      3529477.65     10638265.04
      3532124.87     10638360.52
#Sta/Elev= 30
  3071.3  361.48  3161.6  349.33  3336.9  349.44  3370.6  345.81  3410.2  349.18
  4527.4  352.79  4577.4  352.11  4607.4  347.06  4627.4  351.27  4724.7  353.63
  4807.6  353.03  4827.6   348.8  4837.6   353.1  4957.7  354.21  4967.7  345.03
    4997  341.96  4999.8  341.46    5003  341.96  5003.5  347.58  5027.7   353.5
  5337.9  352.87  6208.5  364.16  6318.5  369.79  6392.6  369.13  6478.6   376.4
  6508.7  382.57  6618.7   380.3  6698.8  389.01  6798.8  393.01  7094.3  398.46
#Mann= 3 ,-1 , 0
  3071.3     .05       0    4997     .03       0    5003     .05       0
Bank Sta=4997,5003
XS Rating Curve= 0 ,0
Exp/Cntr=0.3,0.1

Chan Stop Cuts=-1
Use User Specified Reach Order=0
Composite Channel Slope=5