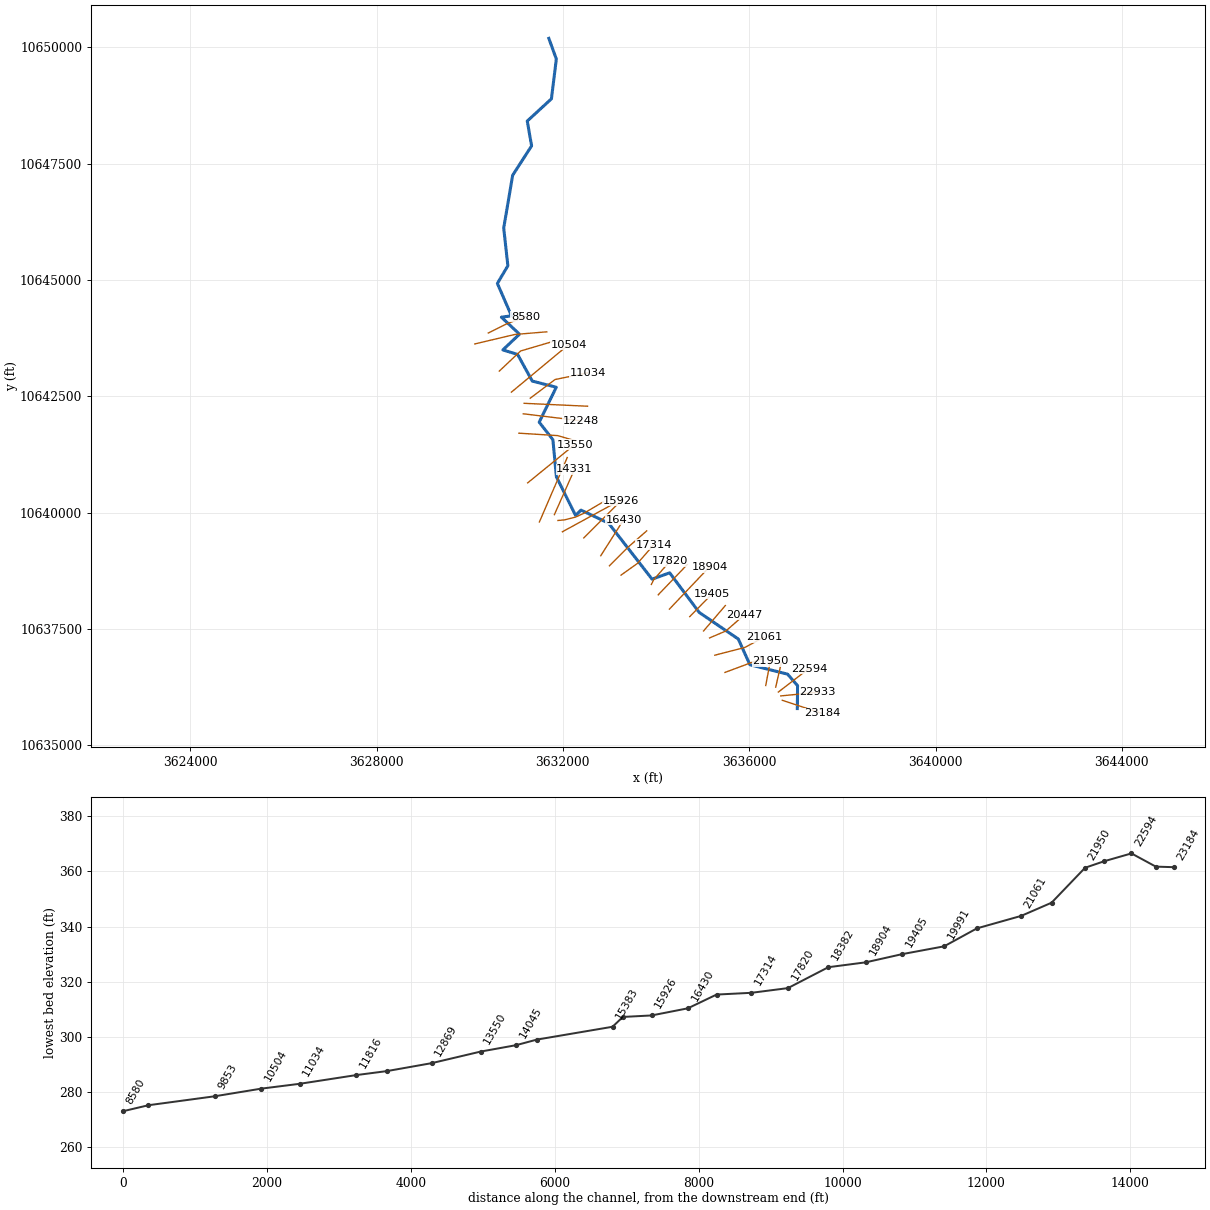
--- MALONE BRANCH.prj (project) ---

Proj Title=MALONE BRANCH Base Level Engineering
Current Plan=p01
Default Exp/Contr=0.3,0.1
English Units
Geom File=g01
Flow File=f01
Plan File=p01
Y Axis Title=Elevation
X Axis Title(PF)=Main Channel Distance
X Axis Title(XS)=Station
BEGIN DESCRIPTION:
MALONE BRANCH
END DESCRIPTION:
DSS Export Rating Curves= 0
DSS Export Rating Curve Sorted= 0
DSS Export Volume Flow Curves= 0
DXF OffsetX= 0
DXF OffsetY= 0
DXF ScaleX= 1
DXF ScaleY= 10

--- MALONE BRANCH.p01 (plan) ---

Plan Title=Multiple Run
Short Identifier=Multiple
Geom File=g01
Flow File=f01
Subcritical Flow
K Sum by GR= 0
Std Step Tol= 0.01
Critical Tol= 0.01
Num of Std Step Trials= 20
Max Error Tol= 0.3
Flow Tol Ratio= 0.001
Split Flow NTrial= 30
Split Flow Tol= 0.02
Split Flow Ratio= 0.02
Log Output Level= 0
Friction Slope Method= 1
Unsteady Friction Slope Method= 2
Unsteady Bridges Friction Slope Method= 1
Parabolic Critical Depth
Global Vel Dist=  1 , 1 , 1
Global Log Level= 0
CheckData=True
Encroach Param= -1, 0, 0, 0
BEGIN DESCRIPTION:
Multiple Run
END DESCRIPTION:

--- MALONE BRANCH.f01 (steady flow) ---

Flow Title=Multiple
Number of Profiles=7
Profile Names=10-year,25-year,50-year,1pct_min,100-year,1pct_plu,500-year
River Rch & RM= MALONE BRANCH,Reach-1,23184
    1829    2568    3193    2896    3916    5297    5874
River Rch & RM= MALONE BRANCH,Reach-1,21061
    2744    3934    4960    4557    6162    8334    9484
River Rch & RM= MALONE BRANCH,Reach-1,15926
    3238    4665    5898    5429    7342    9930   11348
River Rch & RM= MALONE BRANCH,Reach-1,8580
    3705    5358    6791    6262    8469   11453   13138
Boundary for River Rch & Prof#=MALONE BRANCH,Reach-1,1
Up Type=0
Dn Type=3
Dn Slope=0.005
Boundary for River Rch & Prof#=MALONE BRANCH,Reach-1,2
Up Type=0
Dn Type=3
Dn Slope=0.005
Boundary for River Rch & Prof#=MALONE BRANCH,Reach-1,3
Up Type=0
Dn Type=3
Dn Slope=0.005
Boundary for River Rch & Prof#=MALONE BRANCH,Reach-1,4
Up Type=0
Dn Type=3
Dn Slope=0.005
Boundary for River Rch & Prof#=MALONE BRANCH,Reach-1,5
Up Type=0
Dn Type=3
Dn Slope=0.005
Boundary for River Rch & Prof#=MALONE BRANCH,Reach-1,6
Up Type=0
Dn Type=3
Dn Slope=0.005
Boundary for River Rch & Prof#=MALONE BRANCH,Reach-1,7
Up Type=0
Dn Type=3
Dn Slope=0.005

--- MALONE BRANCH.g01 (geometry) ---

Geom Title=Existing Conditions
Program Version=4.10

River Reach=MALONE BRANCH   ,Reach-1
Reach XY= 30
       3637033.1     10635793.31      3637038.25       10636285.
      3636824.25       10636532.      3636014.25       10636735.
        3635766.       10637287.      3634926.75       10637858.
      3634292.25       10638709.        3633915.       10638573.
        3632980.       10639777.      3632388.75       10640056.
      3632274.25       10639941.      3631861.25       10640770.
        3631786.       10641569.        3631492.       10641945.
      3631858.25       10642695.      3631343.25       10642828.
       3631028.5       10643400.       3630711.5       10643497.
      3631068.75       10643835.        3630680.       10644201.
      3630897.25       10644229.      3630594.25       10644925.
       3630819.5       10645305.      3630730.25       10646115.
       3630922.5       10647249.        3631329.       10647880.
       3631235.5       10648413.      3631754.75       10648891.
       3631859.5       10649746.      3631698.75       10650190.

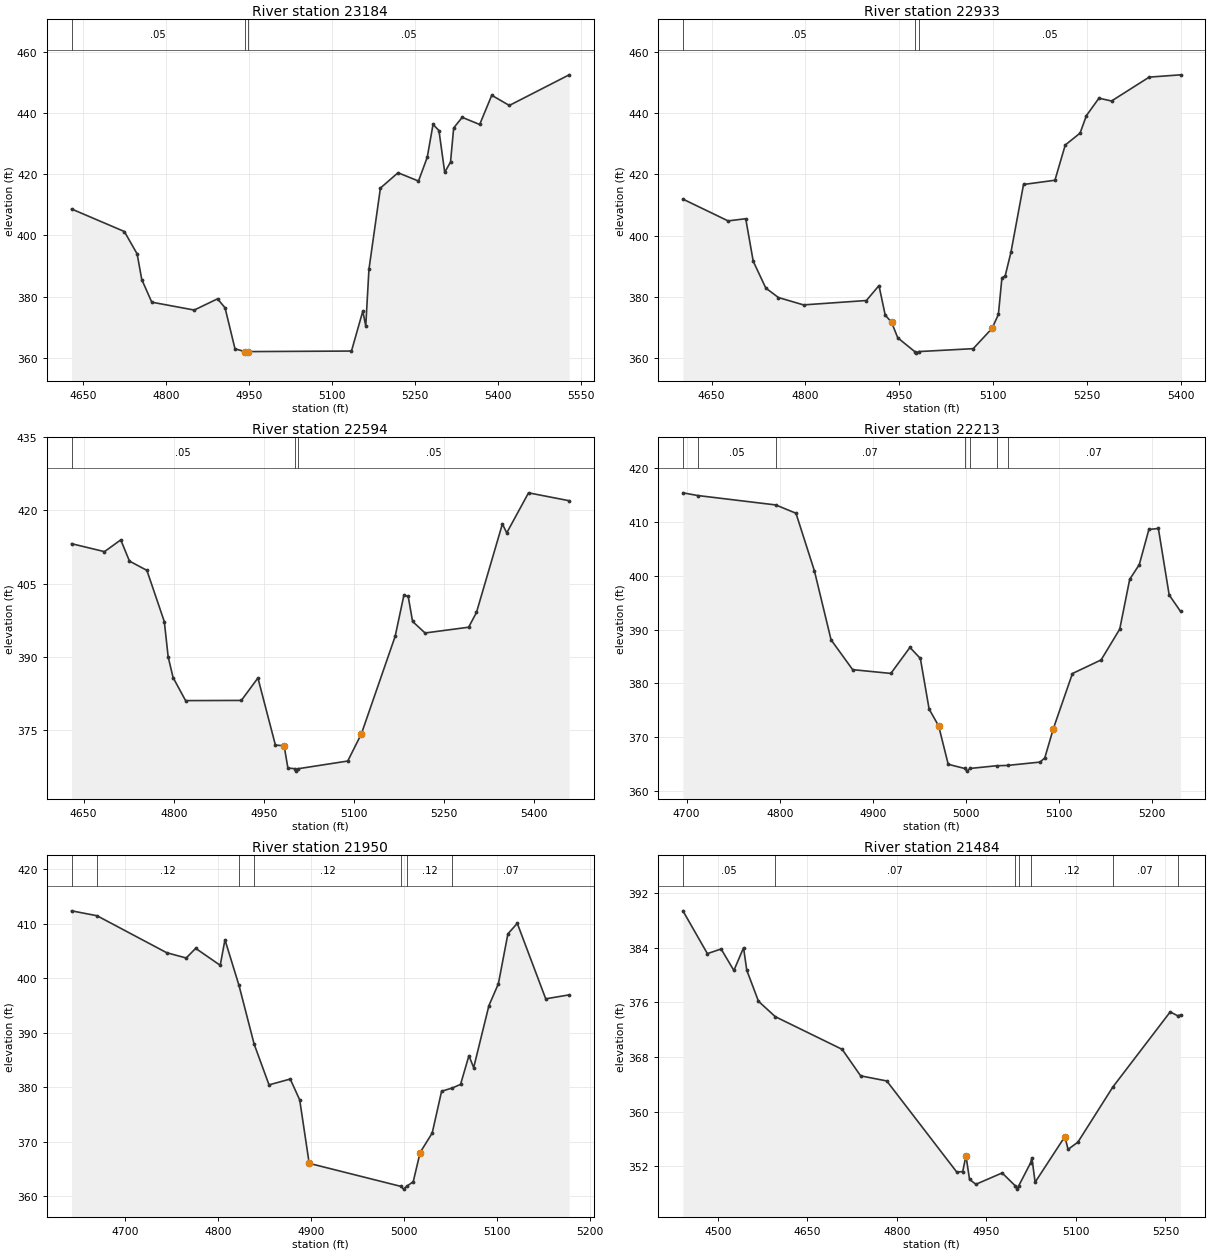
Type RM Length L Ch R = 1 ,23184   ,251,251,251
BEGIN DESCRIPTION:
MALONE BRANCH 42.0
END DESCRIPTION:
XS GIS Cut Line= 2
      3636709.04     10635971.27      3637563.23     10635690.02
#Sta/Elev= 30
  4628.9  408.63  4724.3  401.27  4747.4  393.97  4755.8  385.59  4773.9  378.19
  4850.6  375.62  4892.7  379.28  4906.3  376.36  4924.3  362.95  4942.3  362.05
  4945.1  361.55  4948.3  362.05  5134.8  362.23  5155.3  375.27  5160.6  370.41
  5166.4  388.95  5187.1  415.46  5218.9  420.46  5255.9  417.75  5271.7  425.48
  5282.2  436.24  5292.9  434.25  5303.3   420.6  5313.8  423.97  5319.5  435.09
  5334.9  438.56  5366.5  436.22  5388.3  445.76  5420.1  442.44  5528.2  452.44
#Mann= 3 ,-1 , 0
  4628.9     .05       0  4942.3     .03       0  4948.3     .05       0
Bank Sta=4942.3,4948.3
XS Rating Curve= 0 ,0
Exp/Cntr=0.3,0.1

Type RM Length L Ch R = 1 ,22933   ,339,339,339
BEGIN DESCRIPTION:
Mapping XS 906c51ca
END DESCRIPTION:
XS GIS Cut Line= 2
      3636677.77     10636065.03      3637469.42     10636143.15
#Sta/Elev= 30
  4604.1  411.95  4676.3  404.85  4704.5  405.56  4716.5  391.69  4736.6  382.96
  4756.7  379.88  4796.9  377.47  4897.4   378.9  4917.5  383.77  4927.5  374.15
  4937.6  371.81  4947.6  366.73  4974.7  362.25  4977.5  361.75  4980.7  362.25
  5068.2  363.21  5098.3  369.82  5108.4  374.35  5114.1  386.33  5119.2  386.86
  5128.5  394.64  5148.6  416.72  5198.8   418.1  5215.3  429.58    5239  433.46
  5249.1  439.16  5269.2  444.85  5289.3  443.93  5349.5  451.71  5399.6  452.46
#Mann= 3 ,-1 , 0
  4604.1     .05       0  4974.7    .035       0  4980.7     .05       0
Bank Sta=4937.6,5098.3
XS Rating Curve= 0 ,0
Exp/Cntr=0.3,0.1

Type RM Length L Ch R = 1 ,22594   ,381,381,381
BEGIN DESCRIPTION:
Mapping XS 7c638e67
END DESCRIPTION:
XS GIS Cut Line= 2
      3636625.65     10636148.33      3637281.91     10636653.55
#Sta/Elev= 30
  4629.9  413.19  4684.7  411.56  4711.8  413.97  4726.3  409.62  4755.3  407.72
  4784.3  397.21  4790.7  389.99  4798.9  385.74  4819.7  381.01  4912.5  381.05
  4940.1  385.65  4969.2  371.89  4983.7  371.75    4990  367.18  5001.5  367.05
  5004.2  366.55  5007.5  367.05  5089.6  368.62  5112.3   374.2  5168.5  394.19
    5183   402.6  5190.2  402.39  5197.5  397.24  5218.3  394.88  5290.8  396.06
  5303.8  399.08    5347  417.24  5354.2  415.41  5390.5  423.62  5458.1     422
#Mann= 3 ,-1 , 0
  4629.9     .05       0  5001.5    .035       0  5007.5     .05       0
Bank Sta=4983.7,5112.3
XS Rating Curve= 0 ,0
Exp/Cntr=0.3,0.1

Type RM Length L Ch R = 1 ,22213   ,263,263,263
BEGIN DESCRIPTION:
MALONE BRANCH 41.0
END DESCRIPTION:
XS GIS Cut Line= 2
      3636568.41     10636252.56      3636688.19     10636773.36
#Sta/Elev= 30
    4696  415.39  4711.9  414.89  4795.7  413.14  4817.4   411.6  4837.2   400.9
  4855.1  388.08  4878.3  382.54  4919.3  381.84  4939.8  386.67    4951  384.62
  4960.4  375.21  4970.6   372.1  4980.9  364.96  4998.4  364.19  5001.2  363.69
  5004.4  364.19  5032.9  364.69  5044.6  364.75  5079.5  365.37  5084.6  366.14
  5093.8  371.58  5114.3  381.82  5145.1  384.35  5165.1  390.07  5175.8  399.32
  5186.1  402.06  5196.4  408.58  5206.6  408.77  5218.2  396.42  5230.4  393.36
#Mann= 7 ,-1 , 0
    4696     .12       0  4711.9     .05       0  4795.7     .07       0
  4998.4     .07       0  5004.4     .07       0  5032.9     .16       0
  5044.6     .07       0
Bank Sta=4970.6,5093.8
XS Rating Curve= 0 ,0
Exp/Cntr=0.3,0.1

Type RM Length L Ch R = 1 ,21950   ,466,466,466
BEGIN DESCRIPTION:
MALONE BRANCH 40.0
END DESCRIPTION:
XS GIS Cut Line= 2
      3636354.87     10636289.02      3636453.81       10636815.
#Sta/Elev= 30
  4642.2  412.38  4669.6  411.48  4744.5   404.7  4765.5  403.73  4775.7   405.5
  4802.1  402.39  4807.2  407.07  4822.3   398.7  4838.6  387.93  4854.6  380.46
  4877.4  381.53  4887.6   377.7  4897.8  366.07  4996.5  361.84  4999.3  361.34
  5002.5  361.84  5009.7   362.7  5017.1  368.05  5030.1  371.63  5040.2  379.29
  5051.7  379.89  5060.6  380.55  5069.6  385.82  5074.7  383.62  5091.1     395
  5101.3  399.01  5111.5  408.15  5121.6  410.09  5152.2  396.24  5177.4  396.97
#Mann= 7 ,-1 , 0
  4642.2     .07       0  4669.6     .12       0  4822.3     .07       0
  4838.6     .12       0  4996.5     .07       0  5002.5     .12       0
  5051.7     .07       0
Bank Sta=4897.8,5017.1
XS Rating Curve= 0 ,0
Exp/Cntr=0.3,0.1

Type RM Length L Ch R = 1 ,21484   ,423,423,423
BEGIN DESCRIPTION:
MALONE BRANCH 39.0
END DESCRIPTION:
XS GIS Cut Line= 2
      3635479.61     10636569.57      3636260.84     10636861.23
#Sta/Elev= 30
  4441.4  389.43  4482.4  383.16  4505.4  383.84  4526.8  380.69    4543  384.02
  4548.4  380.73    4568  376.18  4596.2  373.92  4708.3  369.13  4739.2  365.25
    4783   364.5  4900.4  351.14  4910.3  351.23  4915.7  353.54  4921.7  350.08
  4932.4  349.36  4976.3  351.02  4998.2  349.15    5001  348.65  5004.2  349.15
  5023.9  352.48  5026.2  353.24  5031.6  349.66  5081.5  356.35  5086.8  354.48
  5103.2  355.52  5161.9  363.62    5258  374.62  5270.3  374.06  5275.3  374.17
#Mann= 7 ,-1 , 0
  4441.4     .05       0  4596.2     .07       0  4998.2     .07       0
  5004.2     .07       0  5023.9     .12       0  5161.9     .07       0
  5270.3     .12       0
Bank Sta=4915.7,5081.5
XS Rating Curve= 0 ,0
Exp/Cntr=0.3,0.1

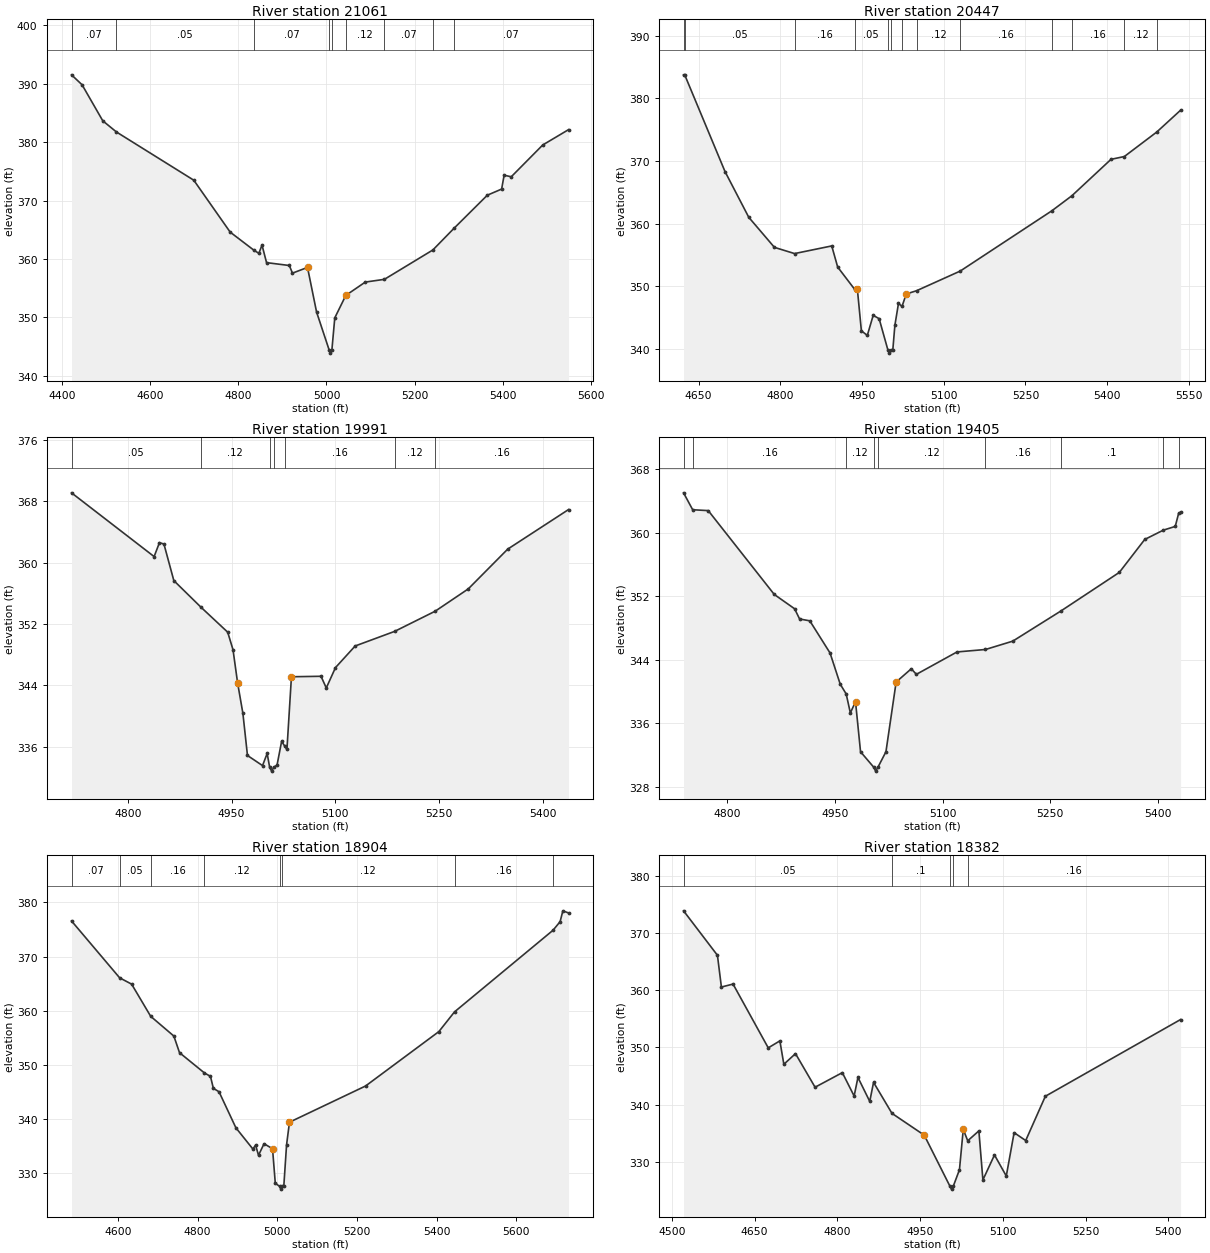
Type RM Length L Ch R = 1 ,21061   ,614,614,614
BEGIN DESCRIPTION:
MALONE BRANCH 38.0
END DESCRIPTION:
XS GIS Cut Line= 3
      3635260.82     10636939.36       3635906.7     10637106.03
      3636312.92     10637324.77
#Sta/Elev= 30
  4421.1  391.53  4445.1  389.82  4492.1  383.65  4523.1  381.74  4698.7  373.48
  4781.3  364.59  4835.7  361.46  4846.5  360.96  4853.6  362.37  4863.9  359.36
  4915.6  358.87  4922.7  357.56  4956.9  358.54  4977.5  350.89  5006.2  344.36
  5008.9  343.86  5012.2  344.36  5018.8   349.9  5043.3  353.66  5044.7  353.79
  5088.1  356.03  5131.5   356.5  5241.5  361.53  5289.5  365.24  5365.1  370.91
  5397.6  371.96  5403.3  374.33  5419.5  374.07  5490.9  379.51  5549.5  382.14
#Mann= 9 ,-1 , 0
  4421.1     .07       0  4523.1     .05       0  4835.7     .07       0
  5006.2     .07       0  5012.2     .07       0  5043.3     .12       0
  5131.5     .07       0  5241.5     .12       0  5289.5     .07       0
Bank Sta=4956.9,5044.7
XS Rating Curve= 0 ,0
Exp/Cntr=0.3,0.1

Type RM Length L Ch R = 1 ,20447   ,456,456,456
BEGIN DESCRIPTION:
MALONE BRANCH 37.0
END DESCRIPTION:
XS GIS Cut Line= 3
      3635149.62     10637310.19      3635499.61     10637460.19
      3635899.62      10637810.2
#Sta/Elev= 30
  4622.5  383.76  4624.6  383.76  4698.6  368.32  4742.2  361.02  4789.3  356.22
  4826.3  355.23  4894.5  356.45  4905.4  353.08  4936.5  349.53  4941.6   349.5
  4948.9   342.9  4959.8  342.17  4970.6  345.37  4981.5  344.84  4997.6  339.84
  5000.3  339.34  5003.6  339.84  5006.6  339.84  5010.4  343.78    5017  347.27
  5023.5   346.8  5031.3  348.78  5050.2   349.3  5130.4  352.44  5298.4  362.05
  5335.2  364.45  5407.1  370.27  5431.6  370.72  5491.1  374.63  5534.8  378.11
#Mann= 13 ,-1 , 0
  4622.5     .07       0  4624.6     .05       0  4826.3     .16       0
  4936.5     .05       0  4997.6    .035       0  5003.6     .05       0
  5023.5     .16       0  5050.2     .12       0  5130.4     .16       0
  5298.4     .12       0  5335.2     .16       0  5431.6     .12       0
  5491.1     .16       0
Bank Sta=4941.6,5031.3
XS Rating Curve= 0 ,0
Exp/Cntr=0.3,0.1

Type RM Length L Ch R = 1 ,19991   ,586,586,586
BEGIN DESCRIPTION:
MALONE BRANCH 36.0
END DESCRIPTION:
XS GIS Cut Line= 2
      3635020.32     10637460.43      3635488.17     10638006.26
#Sta/Elev= 30
  4718.5  369.09    4838  360.78  4845.7   362.6  4852.2  362.41  4866.5  357.65
  4905.9  354.17  4944.4  350.93  4952.1  348.64  4958.7  344.34  4966.4  340.34
    4973  334.86  4994.8  333.54  5001.5  335.12  5005.1  333.32  5007.9  332.82
  5011.1  333.32  5015.8  333.61  5022.4   336.7    5027  336.07  5030.1  335.64
  5036.6  345.12  5079.4  345.18    5087  343.66  5100.3  346.31  5128.8  349.13
  5185.8  351.03  5244.5  353.66  5292.4  356.57  5349.4  361.75  5437.4  366.91
#Mann= 7 ,-1 , 0
  4718.5     .05       0  4905.9     .12       0  5005.1     .07       0
  5011.1     .12       0    5027     .16       0  5185.8     .12       0
  5244.5     .16       0
Bank Sta=4958.7,5036.6
XS Rating Curve= 0 ,0
Exp/Cntr=0.3,0.1

Type RM Length L Ch R = 1 ,19405   ,501,501,501
BEGIN DESCRIPTION:
MALONE BRANCH 35.0
END DESCRIPTION:
XS GIS Cut Line= 2
       3634723.4     10637767.68      3635207.84     10638262.53
#Sta/Elev= 30
  4738.9  365.02  4751.6  362.89  4773.3  362.78  4865.3  352.22  4893.6  350.42
  4900.6  349.13  4914.8   348.9    4943  344.85  4957.2  340.92  4965.5  339.69
  4971.3   337.3  4978.5  338.71  4985.5  332.41  5003.8  330.47  5006.5  329.97
  5009.8  330.47  5020.9  332.41  5035.1  341.19  5056.2  342.86  5063.3  342.16
  5119.9  344.98  5159.6  345.29  5197.6  346.34  5264.7  350.14  5346.1     355
  5381.5  359.15  5407.4  360.32    5424  360.79  5428.7  362.43  5431.4  362.57
#Mann= 9 ,-1 , 0
  4738.9     .07       0  4751.6     .16       0  4965.5     .12       0
  5003.8     .07       0  5009.8     .12       0  5159.6     .16       0
  5264.7      .1       0  5407.4     .12       0  5428.7     .16       0
Bank Sta=4978.5,5035.1
XS Rating Curve= 0 ,0
Exp/Cntr=0.3,0.1

Type RM Length L Ch R = 1 ,18904   ,522,522,522
BEGIN DESCRIPTION:
MALONE BRANCH 34.0
END DESCRIPTION:
XS GIS Cut Line= 2
      3634287.15     10637929.61      3635145.27     10638834.54
#Sta/Elev= 30
  4483.7  376.59  4604.4  366.08  4634.5  364.91  4682.4  358.96  4740.5  355.31
  4754.7  352.24  4817.1   348.5  4832.4  347.86  4839.6  345.65  4853.8  345.02
  4896.2  338.35  4938.7  334.44  4945.6  335.15  4952.9  333.28  4966.8  335.41
  4988.1  334.49    4995  328.11  5006.1  327.52  5008.9  327.02  5012.1  327.52
  5016.4  327.58  5023.3   335.2  5030.6  339.39  5221.5  346.08  5405.5  356.14
  5444.7  359.78  5691.9  374.87  5709.7  376.46  5716.6  378.46  5730.8  378.07
#Mann= 8 ,-1 , 0
  4483.7     .07       0  4604.4     .05       0  4682.4     .16       0
  4817.1     .12       0  5006.1     .07       0  5012.1     .12       0
  5444.7     .16       0  5691.9     .12       0
Bank Sta=4988.1,5030.6
XS Rating Curve= 0 ,0
Exp/Cntr=0.3,0.1

Type RM Length L Ch R = 1 ,18382   ,562,562,562
BEGIN DESCRIPTION:
MALONE BRANCH 33.0
END DESCRIPTION:
XS GIS Cut Line= 2
      3634046.34     10638236.44      3634670.24     10638886.34
#Sta/Elev= 30
  4521.1  373.88  4582.5  366.11  4589.7  360.56  4610.8  361.08  4674.6  349.93
  4695.7  351.15  4702.9  347.06    4724  348.92  4759.5  343.05  4808.9   345.6
  4830.3  341.51  4837.2  344.76  4858.6  340.57  4865.5   343.9  4898.9  338.48
  4957.4  334.67    5004  325.74  5006.8  325.24    5010  325.74  5021.2  328.62
  5028.1  335.67  5036.2  333.69  5056.4  335.42  5063.7  326.85  5084.7  331.21
  5106.1  327.53  5120.3  335.11  5141.3  333.73  5176.9  341.47    5422  354.88
#Mann= 5 ,-1 , 0
  4521.1     .05       0  4898.9      .1       0    5004     .07       0
    5010      .1       0  5036.2     .16       0
Bank Sta=4957.4,5028.1
XS Rating Curve= 0 ,0
Exp/Cntr=0.3,0.1

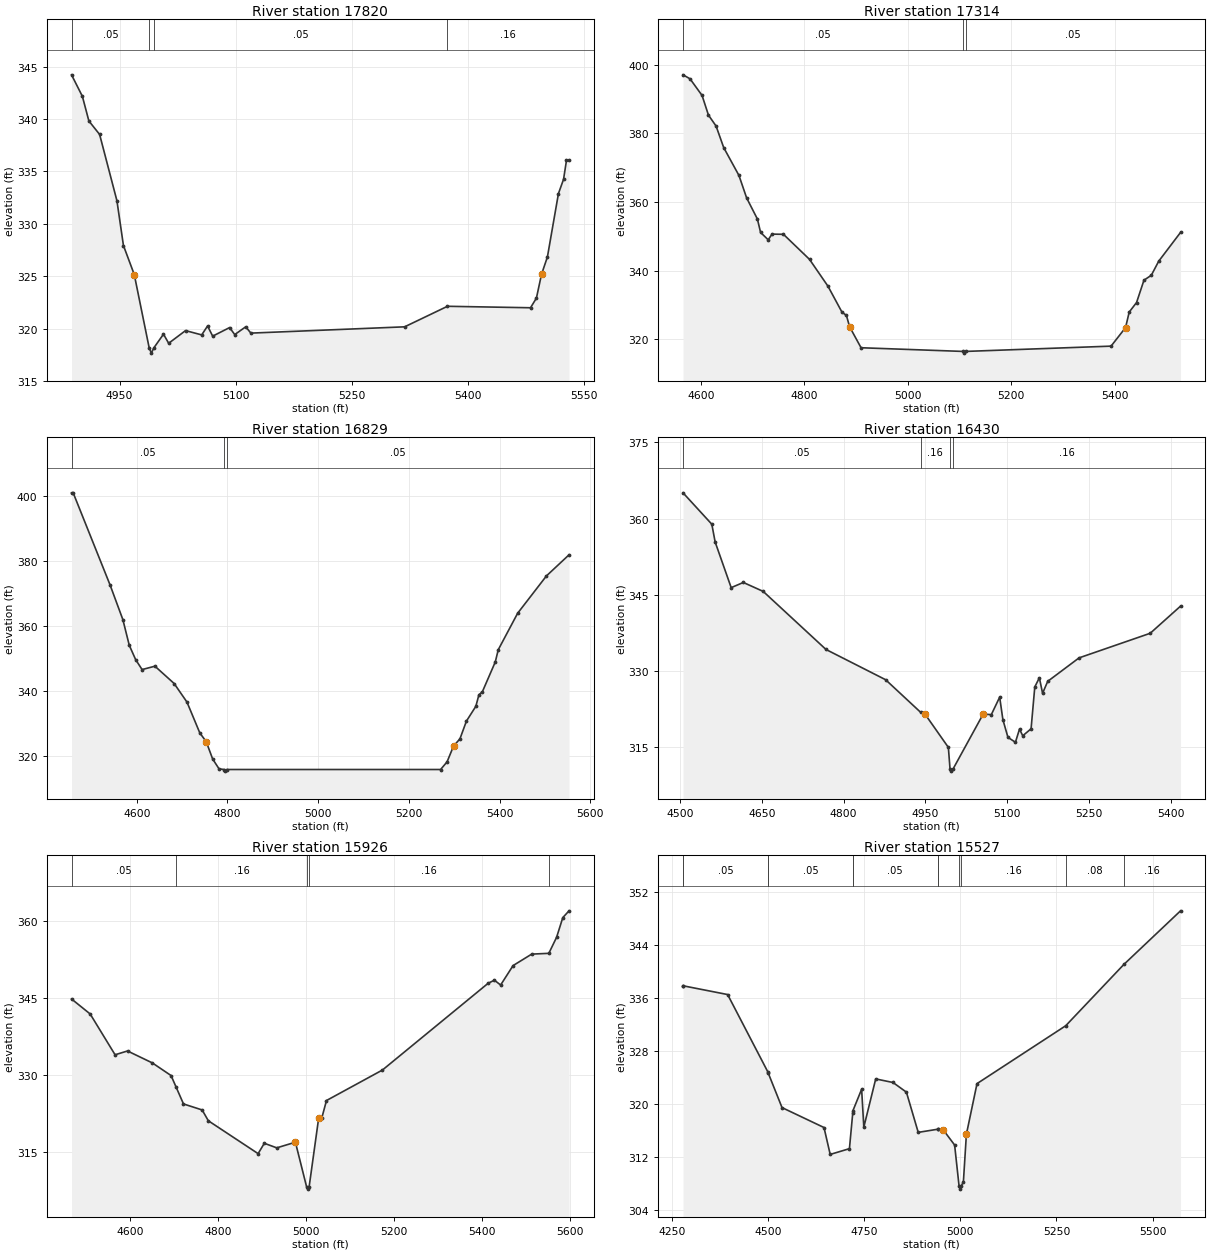
Type RM Length L Ch R = 1 ,17820   ,506,506,506
BEGIN DESCRIPTION:
MALONE BRANCH 32.0
END DESCRIPTION:
XS GIS Cut Line= 3
      3633899.61     10638460.18      3633949.61     10638560.19
       3634299.6     10638960.17
#Sta/Elev= 30
  4887.9  344.21  4901.9  342.16  4910.3  339.81  4924.2  338.52  4946.6  332.19
    4955  327.92    4969  325.15  4988.3  318.15  4991.1  317.65  4994.3  318.15
  5006.8  319.46  5013.5  318.59  5035.3   319.8  5056.2  319.39  5063.8  320.24
  5070.4  319.27  5092.3  320.09  5098.9  319.42  5113.1  320.16  5119.8  319.56
  5318.6  320.16    5374  322.12  5481.4  321.98    5489   322.9  5495.6  325.17
  5503.2  326.82  5517.5  332.88  5524.1  334.24  5527.9  336.05  5531.2  336.05
#Mann= 4 ,-1 , 0
  4887.9     .05       0  4988.3    .035       0  4994.3     .05       0
    5374     .16       0
Bank Sta=4969,5495.6
XS Rating Curve= 0 ,0
Exp/Cntr=0.3,0.1

Type RM Length L Ch R = 1 ,17314   ,485,485,485
BEGIN DESCRIPTION:
MALONE BRANCH 31.0
END DESCRIPTION:
XS GIS Cut Line= 3
      3633249.64     10638660.21      3633599.61     10638910.19
      3633949.61     10639310.19
#Sta/Elev= 30
  4565.4  397.11  4578.9  395.95  4602.2  391.09  4614.5  385.37  4629.3  382.16
    4644  375.89  4673.5  367.76  4688.3  361.22  4709.1  355.07  4715.3  351.15
    4730     349  4737.4  350.66  4759.5   350.6  4809.9  343.29  4845.6  335.45
  4872.6   327.9  4881.2  326.95  4887.3  323.65  4909.5  317.52  5105.9  316.45
  5108.7  315.95  5111.9  316.45  5392.7  317.99  5420.7  323.39  5427.8  327.93
    5442  330.71  5456.3  337.22  5470.5  338.65  5484.8  342.76    5527  351.15
#Mann= 3 ,-1 , 0
  4565.4     .05       0  5105.9    .033       0  5111.9     .05       0
Bank Sta=4887.3,5420.7
XS Rating Curve= 0 ,0
Exp/Cntr=0.3,0.1

Type RM Length L Ch R = 1 ,16829   ,399,399,399
BEGIN DESCRIPTION:
MALONE BRANCH 30.0
END DESCRIPTION:
XS GIS Cut Line= 3
      3632999.58     10638860.16      3633399.61     10639260.19
      3633799.59     10639610.17
#Sta/Elev= 30
  4456.1  401.08  4459.7  401.08    4541  372.71  4569.3     362  4583.4   354.1
  4597.6  349.64  4611.7  346.61    4640  347.65  4682.4  342.31  4710.7  336.58
    4739  327.08  4753.1  324.39  4767.3  319.05  4781.4  316.01  4792.5  315.81
  4795.3  315.31  4798.5  315.81    5270  315.81  5284.3  318.17  5298.5  323.01
  5312.7  325.27    5327  330.73  5347.8   335.3  5354.5  338.83  5362.1  339.76
  5390.6  348.95  5397.2  352.73  5439.9  363.96  5503.5  375.48  5553.3  381.98
#Mann= 3 ,-1 , 0
  4456.1     .05       0  4792.5    .033       0  4798.5     .05       0
Bank Sta=4753.1,5298.5
XS Rating Curve= 0 ,0
Exp/Cntr=0.3,0.1

Type RM Length L Ch R = 1 ,16430   ,504,504,504
BEGIN DESCRIPTION:
MALONE BRANCH 29.0
END DESCRIPTION:
XS GIS Cut Line= 2
      3632812.93     10639075.61       3633302.1      10639845.8
#Sta/Elev= 30
  4505.4  365.09  4558.2  358.91  4564.3  355.41  4593.7  346.43    4616  347.45
  4652.4  345.69  4767.6  334.26  4876.9  328.31  4940.9  321.92  4949.1  321.55
    4992  314.99    4995  310.82  4997.7  310.32    5001  310.82  5055.8  321.54
  5070.8  321.44  5086.1  324.88    5092  320.45  5101.3  316.96    5115     316
  5122.5   318.6  5128.4  317.28  5143.7  318.65  5150.5  326.89  5158.9  328.69
  5164.8  325.64  5174.2  327.99  5231.7  332.61  5362.2  337.45  5417.8  342.79
#Mann= 4 ,-1 , 0
  4505.4     .05       0  4940.9     .16       0    4995     .07       0
    5001     .16       0
Bank Sta=4949.1,5055.8
XS Rating Curve= 0 ,0
Exp/Cntr=0.3,0.1

Type RM Length L Ch R = 1 ,15926   ,399,399,399
BEGIN DESCRIPTION:
MALONE BRANCH 28.0
END DESCRIPTION:
XS GIS Cut Line= 3
      3632449.61     10639460.19      3632849.61     10639860.19
      3633249.63     10640260.21
#Sta/Elev= 30
  4466.2  344.81  4508.6  341.88  4565.2  333.93  4593.5  334.67    4650  332.34
  4692.5  329.88  4704.3  327.57  4720.8  324.34  4763.2  323.17  4777.3  321.06
  4890.5  314.65  4904.6  316.67  4932.9  315.78  4975.3  316.88  5000.6  308.23
  5003.3  307.73  5006.6  308.23  5028.3  321.64  5035.4  321.64    5046  325.01
  5173.3  330.96  5413.7  347.88  5427.9  348.47    5442  347.53  5470.3  351.32
  5512.7  353.56  5551.6  353.71  5569.3  356.84  5583.4  360.68  5597.6     362
#Mann= 5 ,-1 , 0
  4466.2     .05       0  4704.3     .16       0  5000.6     .07       0
  5006.6     .16       0  5551.6     .08       0
Bank Sta=4975.3,5028.3
XS Rating Curve= 0 ,0
Exp/Cntr=0.3,0.1

Type RM Length L Ch R = 1 ,15527   ,144,144,144
BEGIN DESCRIPTION:
MALONE BRANCH 27.0
END DESCRIPTION:
XS GIS Cut Line= 2
      3631990.01     10639591.26      3633125.01     10640210.83
#Sta/Elev= 30
  4279.4  337.89  4279.7  337.89  4395.3  336.57  4500.1  324.86  4500.4  324.78
  4536.7   319.5  4645.8  316.49  4661.9  312.43  4711.9   313.3  4720.6  318.74
  4721.1  319.05  4743.6  322.27  4749.3  316.55  4780.2  323.83  4825.2  323.29
    4860  321.83  4890.7  315.76    4941  316.23  4941.9  316.23  4956.1  316.11
  4985.3  313.85  4996.8  307.69  4999.6  307.19  5002.8  307.69  5008.1   308.3
  5015.9  315.47  5043.5  323.12  5274.1  331.86  5425.3  341.12  5572.5  349.21
#Mann= 12 ,-1 , 0
  4279.4     .16       0  4279.7     .05       0  4500.1     .08       0
  4500.4     .05       0  4720.6     .08       0  4721.1     .05       0
    4941     .08       0  4941.9     .16       0  4996.8     .07       0
  5002.8     .16       0  5274.1     .08       0  5425.3     .16       0
Bank Sta=4956.1,5015.9
XS Rating Curve= 0 ,0
Exp/Cntr=0.3,0.1

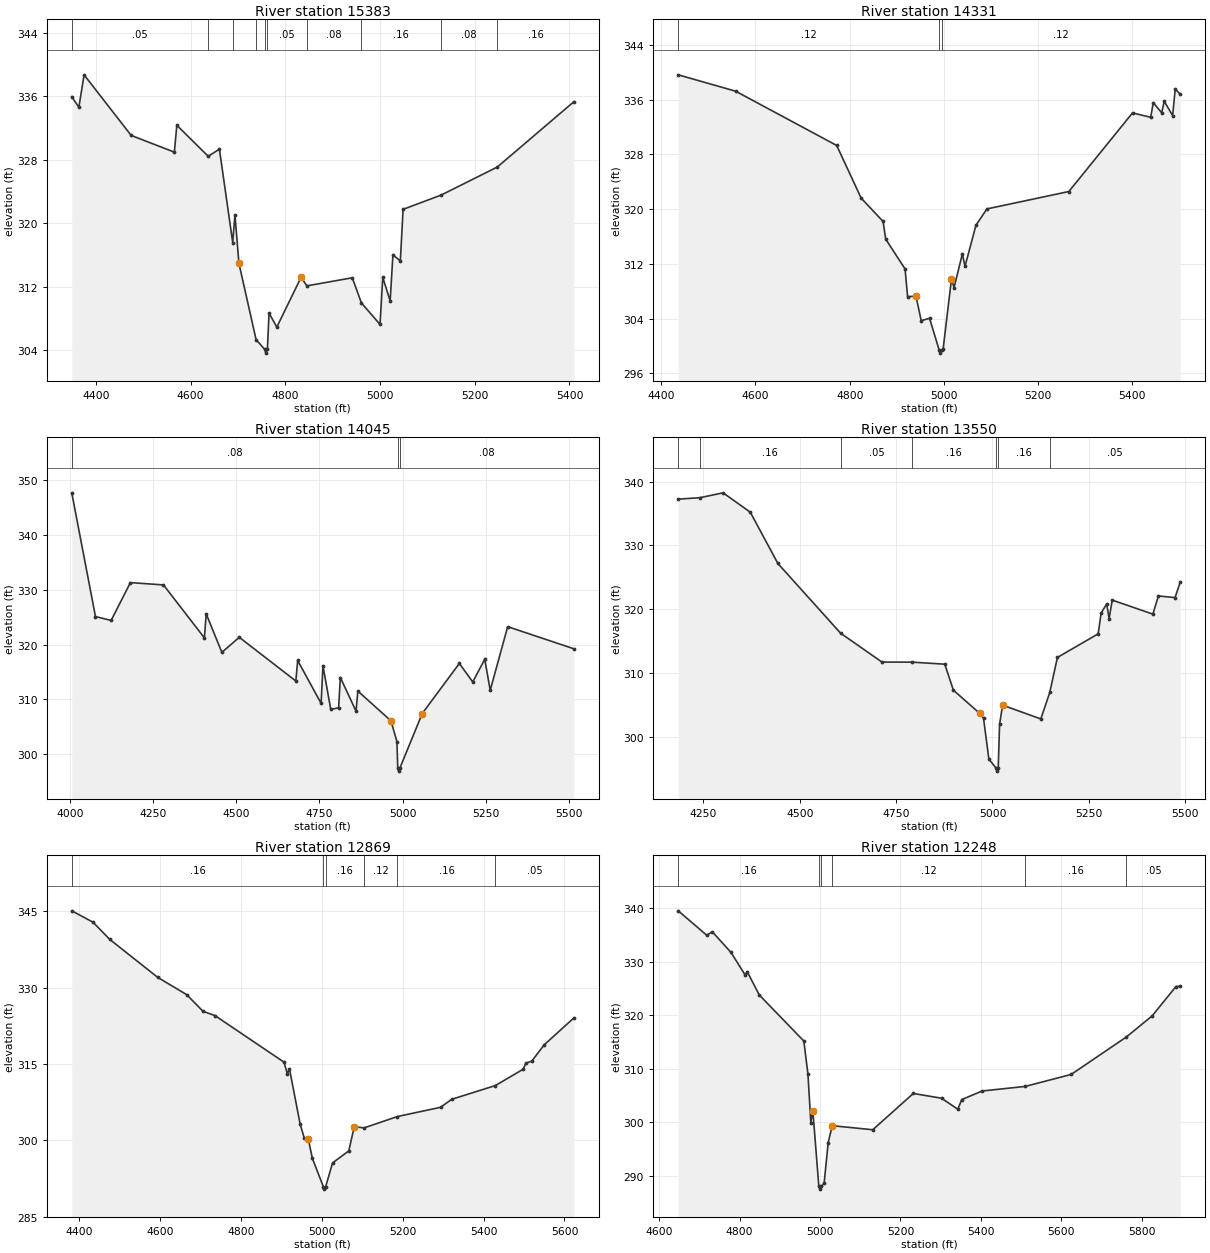
Type RM Length L Ch R = 1 ,15383   ,1052,1052,1052
BEGIN DESCRIPTION:
MALONE BRANCH 26.0
END DESCRIPTION:
XS GIS Cut Line= 5
      3631893.72     10639833.47      3632036.91     10639846.49
      3632275.63     10639907.25      3632453.58     10639989.72
      3632861.53     10640230.58
#Sta/Elev= 30
  4349.2  335.91  4364.2  334.59  4375.2  338.67  4474.6  331.04  4565.8  328.93
    4571  332.32  4637.3  328.41  4660.9  329.31    4689  317.55  4693.7  321.04
  4702.1  314.93  4738.4  305.31  4756.2  304.12    4759  303.62  4762.2  304.12
  4765.7  308.66  4782.1   306.9  4833.5  313.19  4845.4  312.09  4941.4  313.11
  4960.8  309.93    5000  307.24  5005.8  313.16  5021.4  310.19  5027.2     316
  5042.9  315.23  5048.7  321.73  5128.8  323.52  5247.7  327.06  5409.2  335.28
#Mann= 10 ,-1 , 0
  4349.2     .05       0  4637.3     .08       0    4689     .16       0
  4738.4     .05       0  4756.2     .07       0  4762.2     .05       0
  4845.4     .08       0  4960.8     .16       0  5128.8     .08       0
  5247.7     .16       0
Bank Sta=4702.1,4833.5
XS Rating Curve= 0 ,0
Exp/Cntr=0.3,0.1

Type RM Length L Ch R = 1 ,14331   ,286,286,286
BEGIN DESCRIPTION:
MALONE BRANCH 25.0
END DESCRIPTION:
XS GIS Cut Line= 2
      3631817.72     10639958.87      3632250.01     10640932.84
#Sta/Elev= 30
  4436.1  339.62  4557.9  337.23  4772.4   329.3  4824.4   321.6  4870.9   318.2
  4876.4  315.62  4917.5  311.26  4922.9  307.21  4940.7  307.28  4951.8   303.7
  4969.5  304.05  4989.7  299.46  4992.5  298.96  4995.7  299.46  4998.2   299.5
    5016  309.78  5021.5  308.54  5039.2  313.47  5044.7  311.63    5068  317.65
  5091.3  320.03  5265.1  322.57  5400.3  334.06  5438.8  333.41  5444.3  335.56
  5462.1  334.08  5467.6  335.75  5485.4  333.67  5490.9  337.54  5501.7  336.78
#Mann= 3 ,-1 , 0
  4436.1     .12       0  4989.7    .035       0  4995.7     .12       0
Bank Sta=4940.7,5016
XS Rating Curve= 0 ,0
Exp/Cntr=0.3,0.1

Type RM Length L Ch R = 1 ,14045   ,495,495,495
BEGIN DESCRIPTION:
MALONE BRANCH 24.0
END DESCRIPTION:
XS GIS Cut Line= 2
      3631495.68     10639801.36      3632094.26      10641185.9
#Sta/Elev= 30
  4006.1  347.63  4077.3   325.1  4124.3  324.39  4182.2  331.28  4281.6  330.86
  4404.5  321.22    4410  325.58    4457  318.58  4509.4  321.32  4679.3  313.36
  4684.8   317.1  4755.2  309.29  4760.7  316.15  4784.2   308.2  4807.7  308.48
  4813.1  313.99  4860.1  307.88  4865.6  311.53    4965  306.11    4983  302.33
  4985.5  297.45  4988.2  296.95  4991.5  297.45    5059  307.44  5170.5  316.56
  5210.8  313.19  5246.8  317.32  5263.3  311.67  5315.7  323.26  5514.5  319.23
#Mann= 3 ,-1 , 0
  4006.1     .08       0  4985.5    .035       0  4991.5     .08       0
Bank Sta=4965,5059
XS Rating Curve= 0 ,0
Exp/Cntr=0.3,0.1

Type RM Length L Ch R = 1 ,13550   ,681,681,681
BEGIN DESCRIPTION:
MALONE BRANCH 23.0
END DESCRIPTION:
XS GIS Cut Line= 2
      3631244.61     10640641.41      3632254.85     10641464.19
#Sta/Elev= 30
  4184.5  337.26    4241  337.49  4300.9  338.25  4371.5  335.21  4443.1  327.17
    4606  316.23  4713.2  311.71  4791.1   311.7  4876.2  311.38  4898.5  307.31
  4966.4  303.69  4976.7  302.92  4990.6  296.51  5008.9  295.11  5011.7  294.61
  5014.9  295.11  5018.4  301.98  5026.3  304.96  5125.4  302.79  5148.6  306.94
  5168.5  312.44  5274.3  316.14  5281.9  319.39  5296.3  320.83  5302.7  318.54
  5310.7  321.43  5416.2  319.23  5430.6  322.08  5473.7  321.82  5487.4  324.29
#Mann= 7 ,-1 , 0
  4184.5     .05       0    4241     .16       0    4606     .05       0
  4791.1     .16       0  5008.9     .07       0  5014.9     .16       0
  5148.6     .05       0
Bank Sta=4966.4,5026.3
XS Rating Curve= 0 ,0
Exp/Cntr=0.3,0.1

Type RM Length L Ch R = 1 ,12869   ,621,621,621
BEGIN DESCRIPTION:
MALONE BRANCH 22.0
END DESCRIPTION:
XS GIS Cut Line= 3
      3631055.67     10641708.68      3631889.02      10641656.6
      3632279.69       10641542.
#Sta/Elev= 30
  4381.1  345.07  4433.6  342.84  4475.2  339.45  4593.9  331.99  4665.6   328.6
  4705.7  325.34  4735.7  324.48  4906.1  315.35  4914.6  313.02  4919.6  314.06
  4946.1  303.18  4956.2  300.46  4966.2  300.28  4976.2  296.48  5003.3  290.91
    5006  290.41  5009.3  290.91  5026.3  295.56  5066.4  297.92  5079.9  302.66
  5104.4  302.44  5186.8  304.67  5293.5  306.48  5320.9  308.05    5429  310.75
  5498.1  313.97  5504.3  315.16  5518.9  315.53  5550.2  318.78  5623.2  324.03
#Mann= 6 ,-1 , 0
  4381.1     .16       0  5003.3     .07       0  5009.3     .16       0
  5104.4     .12       0  5186.8     .16       0    5429     .05       0
Bank Sta=4966.2,5079.9
XS Rating Curve= 0 ,0
Exp/Cntr=0.3,0.1

Type RM Length L Ch R = 1 ,12248   ,432,432,432
BEGIN DESCRIPTION:
MALONE BRANCH 21.0
END DESCRIPTION:
XS GIS Cut Line= 2
      3631149.47     10642125.34        3632389.     10641974.31
#Sta/Elev= 30
  4647.4  339.55  4718.1     335  4732.3  335.62  4778.5  331.79  4813.9  327.54
  4818.9  328.18    4849  323.82  4959.8  315.21  4969.9   309.1  4977.2  299.97
  4982.2  302.21  4997.1  288.03  4999.9  287.53  5003.1  288.03  5010.2  288.59
  5020.3  296.21  5029.8   299.2  5030.4  299.39  5131.1  298.63  5232.1  305.41
  5302.3  304.52  5342.6  302.47  5352.7  304.27  5403.1  305.87  5510.5  306.73
  5624.7  308.97    5762  315.97  5826.2  319.92  5885.2   325.4  5896.1  325.45
#Mann= 6 ,-1 , 0
  4647.4     .16       0  4997.1     .07       0  5003.1     .16       0
  5029.8     .12       0  5510.5     .16       0    5762     .05       0
Bank Sta=4982.2,5030.4
XS Rating Curve= 0 ,0
Exp/Cntr=0.3,0.1

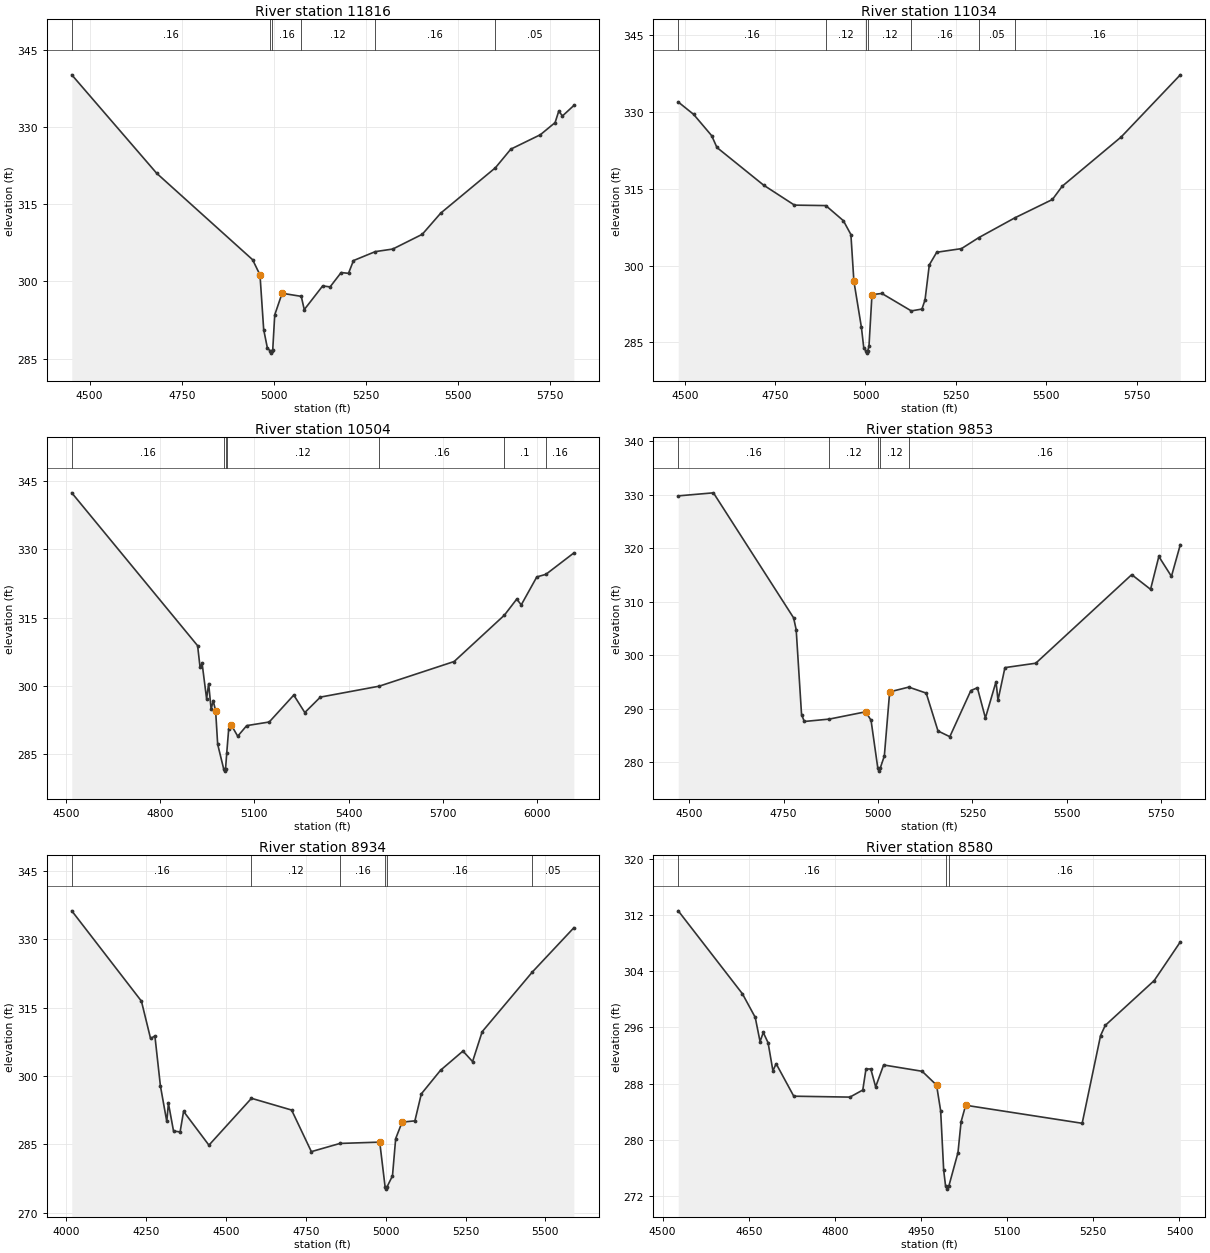
Type RM Length L Ch R = 1 ,11816   ,782,782,782
BEGIN DESCRIPTION:
MALONE BRANCH 20.0
END DESCRIPTION:
XS GIS Cut Line= 2
       3631169.4     10642350.18      3632530.46     10642287.69
#Sta/Elev= 30
  4451.5  340.18    4682  321.03  4942.2  304.23  4962.3  301.27  4972.3  290.64
  4982.3  287.07  4988.9  286.56  4991.6  286.06  4994.9  286.56  4996.9  286.73
  5002.3   293.5  5022.3   297.7  5074.3   297.1  5082.4  294.52  5132.4  299.13
  5152.5  298.94  5182.5  301.73  5202.5  301.58    5216  304.06  5275.2   305.8
  5322.6   306.3  5402.7  309.17  5452.8  313.29  5601.2  322.11    5643  325.73
  5723.1  328.53  5763.1  330.89  5773.1  333.13  5783.1  332.18    5814  334.22
#Mann= 6 ,-1 , 0
  4451.5     .16       0  4988.9     .07       0  4994.9     .16       0
  5074.3     .12       0  5275.2     .16       0  5601.2     .05       0
Bank Sta=4962.3,5022.3
XS Rating Curve= 0 ,0
Exp/Cntr=0.3,0.1

Type RM Length L Ch R = 1 ,11034   ,530,530,530
BEGIN DESCRIPTION:
MALONE BRANCH 19.0
END DESCRIPTION:
XS GIS Cut Line= 3
      3631300.04     10642459.99      3631831.29     10642861.03
      3632539.61     10643006.86
#Sta/Elev= 30
  4482.1  331.98  4524.7  329.56  4574.6   325.4  4589.2  323.09  4718.2  315.74
  4803.6  311.83  4890.3  311.74  4938.9  308.79  4959.7  306.08    4968  296.95
  4988.8  287.94  4995.3  283.95  5000.4  283.41  5003.1  282.91  5006.4  283.41
  5009.7  284.23    5018  294.34  5045.4  294.57  5126.8  291.16  5156.2  291.52
  5164.8  293.32  5176.6  300.16  5197.1  302.62  5265.5  303.33  5313.7  305.49
  5413.6  309.36  5517.1  312.93  5544.2  315.52  5707.5  325.16  5870.9  337.29
#Mann= 7 ,-1 , 0
  4482.1     .16       0  4890.3     .12       0  5000.4     .07       0
  5006.4     .12       0  5126.8     .16       0  5313.7     .05       0
  5413.6     .16       0
Bank Sta=4968,5018
XS Rating Curve= 0 ,0
Exp/Cntr=0.3,0.1

Type RM Length L Ch R = 1 ,10504   ,651,651,651
BEGIN DESCRIPTION:
MALONE BRANCH 18.0
END DESCRIPTION:
XS GIS Cut Line= 2
      3630895.43     10642590.23       3632124.6     10643611.07
#Sta/Elev= 30
  4518.9  342.46  4919.4  308.79  4927.2  304.01  4933.7   304.9    4948  297.09
  4954.5  300.45  4962.4  294.77  4968.9  296.71  4976.7  294.46  4983.2   287.1
  5002.3  281.67    5005  281.17  5008.3  281.67    5012  285.08  5018.3  290.47
  5026.2  291.36    5047  288.86  5075.6  291.19  5147.3  291.99  5225.4  297.92
  5260.5  294.07    5310  297.47  5497.4  299.88  5735.8  305.31  5895.8  315.53
    5935  319.06  5949.3  317.78  5998.8  323.94  6027.8  324.51  6116.7  329.22
#Mann= 7 ,-1 , 0
  4518.9     .16       0  5002.3     .07       0  5008.3     .16       0
    5012     .12       0  5497.4     .16       0  5895.8      .1       0
  6027.8     .16       0
Bank Sta=4976.7,5026.2
XS Rating Curve= 0 ,0
Exp/Cntr=0.3,0.1

Type RM Length L Ch R = 1 ,9853    ,919,919,919
BEGIN DESCRIPTION:
MALONE BRANCH 17.0
END DESCRIPTION:
XS GIS Cut Line= 3
      3630635.63      10643042.4      3631093.95     10643474.67
      3631765.22     10643672.41
#Sta/Elev= 30
  4470.9  329.78  4564.1  330.35  4776.5     307  4783.3  304.79  4797.5  288.95
  4804.8  287.65  4871.1   288.1  4967.4  289.46  4981.6  287.87  4999.6  278.88
  5002.4  278.38  5005.6  278.88  5016.8  281.21  5030.9  293.18  5081.5  294.07
  5127.7  292.95  5158.9  285.88  5190.2  284.81  5245.9  293.42  5263.2  293.95
  5284.5   288.3  5312.6  295.08  5317.8  291.62  5336.2  297.71  5417.8  298.53
    5672  315.07  5721.9  312.33  5743.8  318.46  5777.2  314.75  5800.7  320.67
#Mann= 5 ,-1 , 0
  4470.9     .16       0  4871.1     .12       0  4999.6     .07       0
  5005.6     .12       0  5081.5     .16       0
Bank Sta=4967.4,5030.9
XS Rating Curve= 0 ,0
Exp/Cntr=0.3,0.1

Type RM Length L Ch R = 1 ,8934    ,354,354,354
BEGIN DESCRIPTION:
MALONE BRANCH 15.0
END DESCRIPTION:
XS GIS Cut Line= 3
      3630109.53      10643625.7      3630968.95     10643828.84
      3631655.57     10643886.06
#Sta/Elev= 30
  4017.1  336.24  4235.2  316.41  4263.8  308.21  4277.4  308.76  4294.6  297.83
  4314.6  289.99  4319.7     294  4335.7   287.9  4356.3   287.7  4367.2  292.21
  4446.6  284.79  4579.8  295.08  4705.5   292.5  4767.3  283.37  4856.8  285.17
  4981.4  285.46  4998.2  275.64    5001  275.14  5004.2  275.64  5021.3  278.05
  5031.3  286.23  5051.4  289.85  5091.5  290.13  5111.6  296.05  5171.8  301.24
    5242  305.45  5272.1  303.14  5302.2  309.71  5459.4  322.82  5589.2  332.52
#Mann= 6 ,-1 , 0
  4017.1     .16       0  4579.8     .12       0  4856.8     .16       0
  4998.2     .07       0  5004.2     .16       0  5459.4     .05       0
Bank Sta=4981.4,5051.4
XS Rating Curve= 0 ,0
Exp/Cntr=0.3,0.1

Type RM Length L Ch R = 1 ,8580    ,618,618,618
BEGIN DESCRIPTION:
MALONE BRANCH 14.0
END DESCRIPTION:
XS GIS Cut Line= 3
      3630399.64      10643860.2      3630799.61     10644060.19
      3631199.62     10644210.19
#Sta/Elev= 30
  4527.1  312.61  4638.9  300.79  4661.2  297.43  4669.6  293.98  4675.2  295.28
  4683.6  293.81    4692  289.81  4697.6  290.83  4728.3   286.2  4826.1  286.07
  4848.5  287.08  4854.1  290.09  4862.5  290.07  4870.9  287.53  4884.8  290.65
  4951.9  289.75    4977  287.78  4984.1  284.13  4989.4  275.65  4992.6  273.46
  4995.4  272.96  4998.6  273.46  5014.3  278.17  5019.7  282.56  5027.7  284.91
  5230.6  282.34  5262.6  294.83  5270.7  296.28  5356.1  302.68  5401.5  308.18
#Mann= 3 ,-1 , 0
  4527.1     .16       0  4992.6     .07       0  4998.6     .16       0
Bank Sta=4977,5027.7
XS Rating Curve= 0 ,0
Exp/Cntr=0.3,0.1