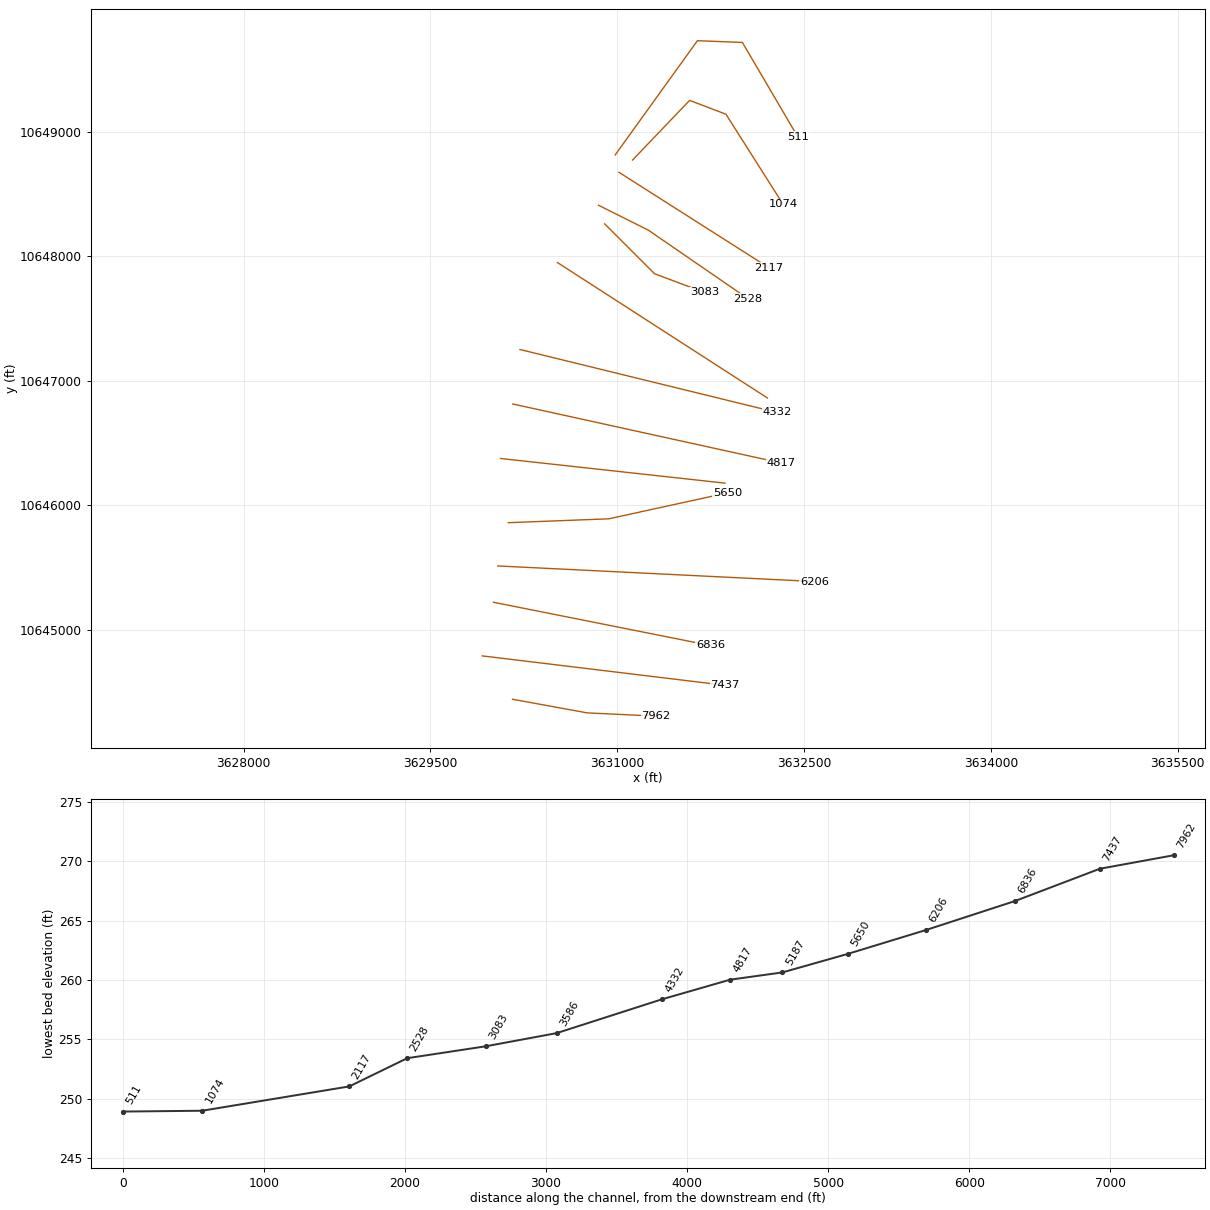
HEC-RAS study MALONE BRANCH.prj: MALONE BRANCH Base Level Engineering

--- MALONE BRANCH.g01 (geometry) --- (continued)

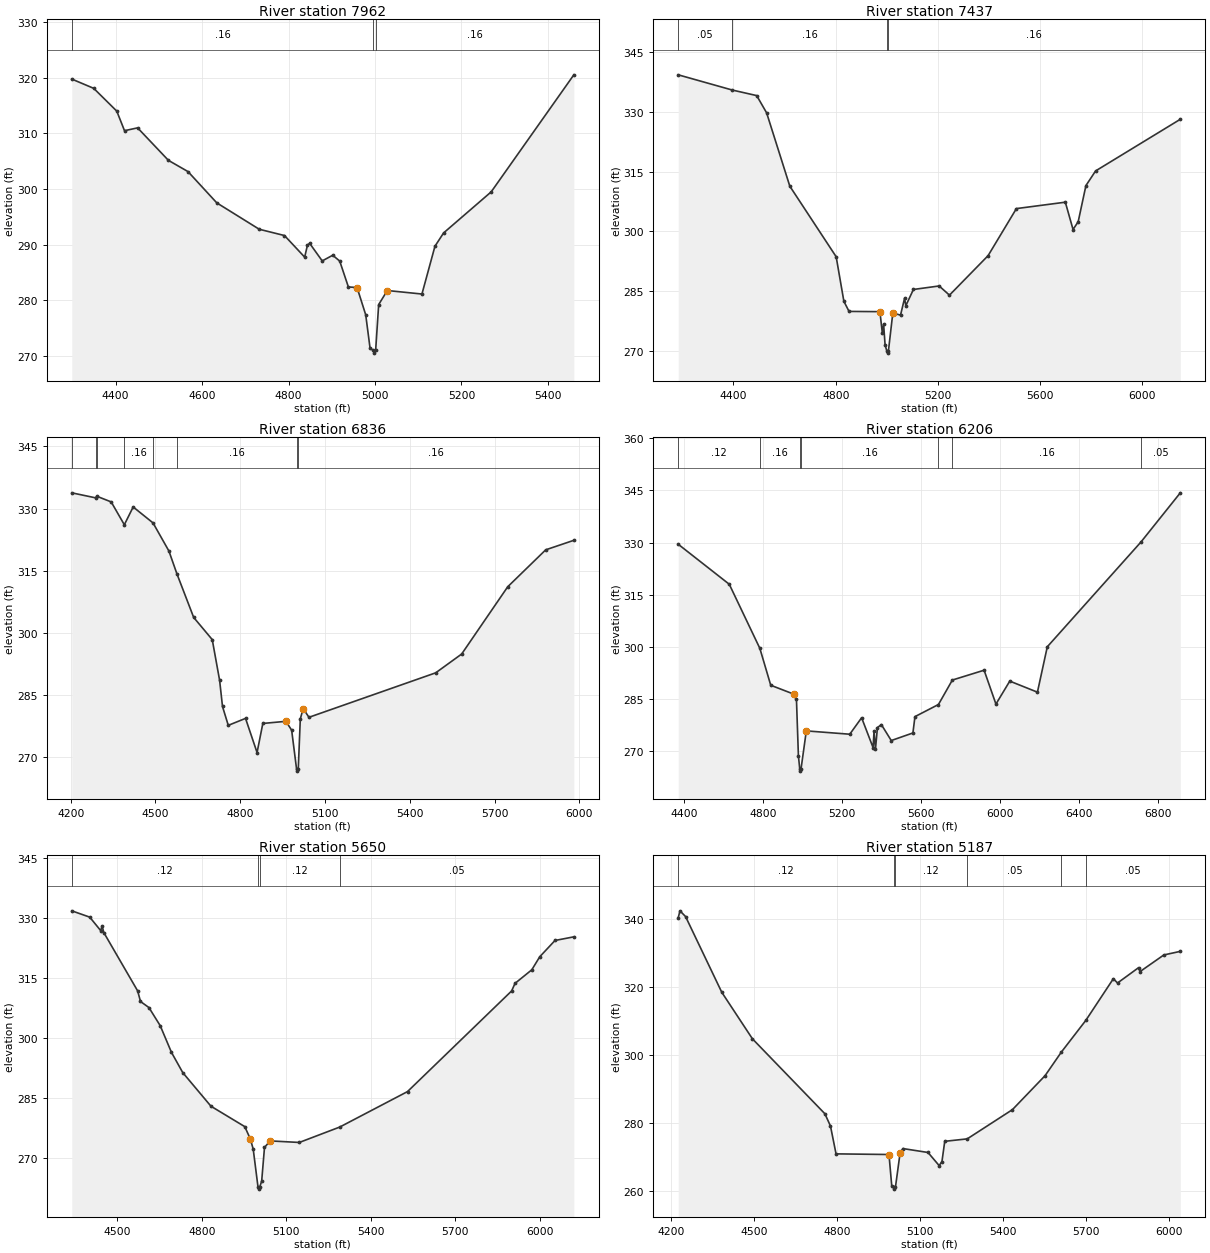
Type RM Length L Ch R = 1 ,7962    ,525,525,525
BEGIN DESCRIPTION:
MALONE BRANCH 13.0
END DESCRIPTION:
XS GIS Cut Line= 3
      3630159.61     10644443.41      3630758.53     10644334.05
      3631310.59     10644308.01
#Sta/Elev= 30
  4298.5  319.77  4349.3   318.1  4402.6  314.01  4420.5  310.49  4450.8     311
  4522.1  305.16  4567.4  303.14    4634  297.52  4732.2  292.78  4790.6  291.65
  4837.3  287.77  4843.8  289.94  4848.9  290.24  4877.9  287.09  4902.2  288.11
  4918.4  287.06  4938.4  282.41  4958.5  282.31  4978.5  277.41  4988.5  271.45
  4995.5  271.02  4998.3  270.52  5001.5  271.02  5008.5  279.25  5028.5  281.77
  5108.6  281.14  5138.7  289.73  5158.7  292.12  5268.8   299.5    5460  320.53
#Mann= 3 ,-1 , 0
  4298.5     .16       0  4995.5     .07       0  5001.5     .16       0
Bank Sta=4958.5,5028.5
XS Rating Curve= 0 ,0
Exp/Cntr=0.3,0.1

Type RM Length L Ch R = 1 ,7437    ,601,601,601
BEGIN DESCRIPTION:
MALONE BRANCH 12.0
END DESCRIPTION:
XS GIS Cut Line= 2
      3629916.29     10644791.62      3631866.17     10644555.69
#Sta/Elev= 30
    4184  339.37  4395.6  335.54  4490.9  334.15  4529.8   329.8  4620.5  311.36
  4801.8  293.62    4832  282.41  4852.2  279.87    4973  279.81  4982.4  274.41
  4987.4  276.67  4993.2  271.42  5000.2  269.88    5003  269.38  5006.2  269.88
  5023.4  279.46  5053.6  278.94  5069.4  283.17  5074.4  281.32    5104  285.39
  5204.7  286.27    5245  283.96  5396.1  293.89  5506.9  305.73  5698.3  307.34
  5728.5  300.47  5748.6  302.43  5778.9  311.52  5816.7   315.2  6148.1  328.19
#Mann= 4 ,-1 , 0
    4184     .05       0  4395.6     .16       0  5000.2     .07       0
  5006.2     .16       0
Bank Sta=4973,5023.4
XS Rating Curve= 0 ,0
Exp/Cntr=0.3,0.1

Type RM Length L Ch R = 1 ,6836    ,630,630,630
BEGIN DESCRIPTION:
MALONE BRANCH 11.0
END DESCRIPTION:
XS GIS Cut Line= 2
      3630006.53     10645222.18      3631748.99     10644875.07
#Sta/Elev= 30
    4204  333.78  4288.3  332.57  4292.4  332.96  4343.5  331.59    4390  326.08
  4421.3  330.37  4491.6  326.52  4547.8  319.74    4576  314.26  4635.4  303.73
  4701.1  298.38  4727.2  288.55  4737.4  282.25  4757.8   277.7  4818.9  279.38
  4859.7  271.14  4880.1  278.16  4961.7  278.67  4982.1  276.54  4999.5  267.16
  5002.2  266.66  5005.5  267.16  5012.7  279.23  5022.9  281.76  5043.3  279.64
  5491.9  290.37  5583.7   294.9  5746.8  311.13  5881.1  320.03  5980.7  322.33
#Mann= 8 ,-1 , 0
    4204     .05       0  4288.3     .16       0  4292.4     .05       0
    4390     .16       0  4491.6     .12       0    4576     .16       0
  4999.5     .07       0  5005.5     .16       0
Bank Sta=4961.7,5022.9
XS Rating Curve= 0 ,0
Exp/Cntr=0.3,0.1

Type RM Length L Ch R = 1 ,6206    ,556,556,556
BEGIN DESCRIPTION:
MALONE BRANCH 10.0
END DESCRIPTION:
XS GIS Cut Line= 2
      3630041.23     10645513.84      3632582.95     10645388.84
#Sta/Elev= 30
  4368.5   329.5  4627.2  317.99  4782.2  299.54  4837.4  288.93  4957.6   286.3
  4967.6  285.03  4977.6  268.64  4984.6  264.72  4987.4  264.22  4990.6  264.72
  5017.7   275.8  5237.9  274.84    5298  279.58    5356     271  5361.1  275.77
  5368.1  270.48  5378.1  276.75  5398.1  277.61  5448.2  273.02    5558   275.2
  5568.3   279.9  5687.4  283.39  5757.9  290.43  5918.8  293.26  5978.8  283.51
  6048.9  290.12  6189.1  286.94  6239.1     300  6713.6  330.13  6913.3   344.3
#Mann= 7 ,-1 , 0
  4368.5     .12       0  4782.2     .16       0  4984.6     .07       0
  4990.6     .16       0  5687.4     .12       0  5757.9     .16       0
  6713.6     .05       0
Bank Sta=4957.6,5017.7
XS Rating Curve= 0 ,0
Exp/Cntr=0.3,0.1

Type RM Length L Ch R = 1 ,5650    ,463,463,463
BEGIN DESCRIPTION:
MALONE BRANCH 9.0
END DESCRIPTION:
XS GIS Cut Line= 3
      3630125.81     10645861.07      3630933.08     10645892.31
      3631885.42     10646100.48
#Sta/Elev= 30
  4338.1  331.85  4401.9  330.27  4440.8   326.9  4445.8  328.02    4452  326.39
  4572.1   311.8  4582.1  309.16  4612.1  307.64  4652.1  303.11  4692.2  296.41
  4732.2  291.36  4832.3  282.95  4952.4  277.84  4972.4  274.71  4982.4  272.19
  4999.4   262.7  5002.1   262.2  5005.4   262.7  5012.4   264.2  5022.4  272.63
  5042.4  274.27    5146  273.88  5289.4  277.73  5530.2  286.61  5899.9   311.8
    5912   313.7  5971.5  317.09  5999.8  320.36  6053.9  324.43  6120.8  325.34
#Mann= 4 ,-1 , 0
  4338.1     .12       0  4999.4     .07       0  5005.4     .12       0
  5289.4     .05       0
Bank Sta=4972.4,5042.4
XS Rating Curve= 0 ,0
Exp/Cntr=0.3,0.1

Type RM Length L Ch R = 1 ,5187    ,370,370,370
BEGIN DESCRIPTION:
MALONE BRANCH 8.0
END DESCRIPTION:
XS GIS Cut Line= 2
      3630063.31     10646376.69      3631864.97     10646178.82
#Sta/Elev= 30
    4227  340.48  4233.3  342.49  4253.5   340.8  4384.2  318.53  4494.9  304.84
  4756.5   282.8  4776.6  279.19  4796.7  271.01  4987.8  270.82  4997.9  261.48
    5005  261.14  5007.7  260.64    5011  261.14  5028.1  271.39  5038.2  272.57
  5128.7  271.42  5168.9  267.56    5179  268.74  5189.1   274.7  5270.3  275.42
  5433.5  284.02  5551.2     294  5610.2  300.96  5698.4  310.27  5797.8  322.53
  5812.8  321.26  5888.9  325.78  5893.9  324.61    5980  329.51  6039.5  330.57
#Mann= 6 ,-1 , 0
    4227     .12       0    5005     .07       0    5011     .12       0
  5270.3     .05       0  5610.2     .16       0  5698.4     .05       0
Bank Sta=4987.8,5028.1
XS Rating Curve= 0 ,0
Exp/Cntr=0.3,0.1

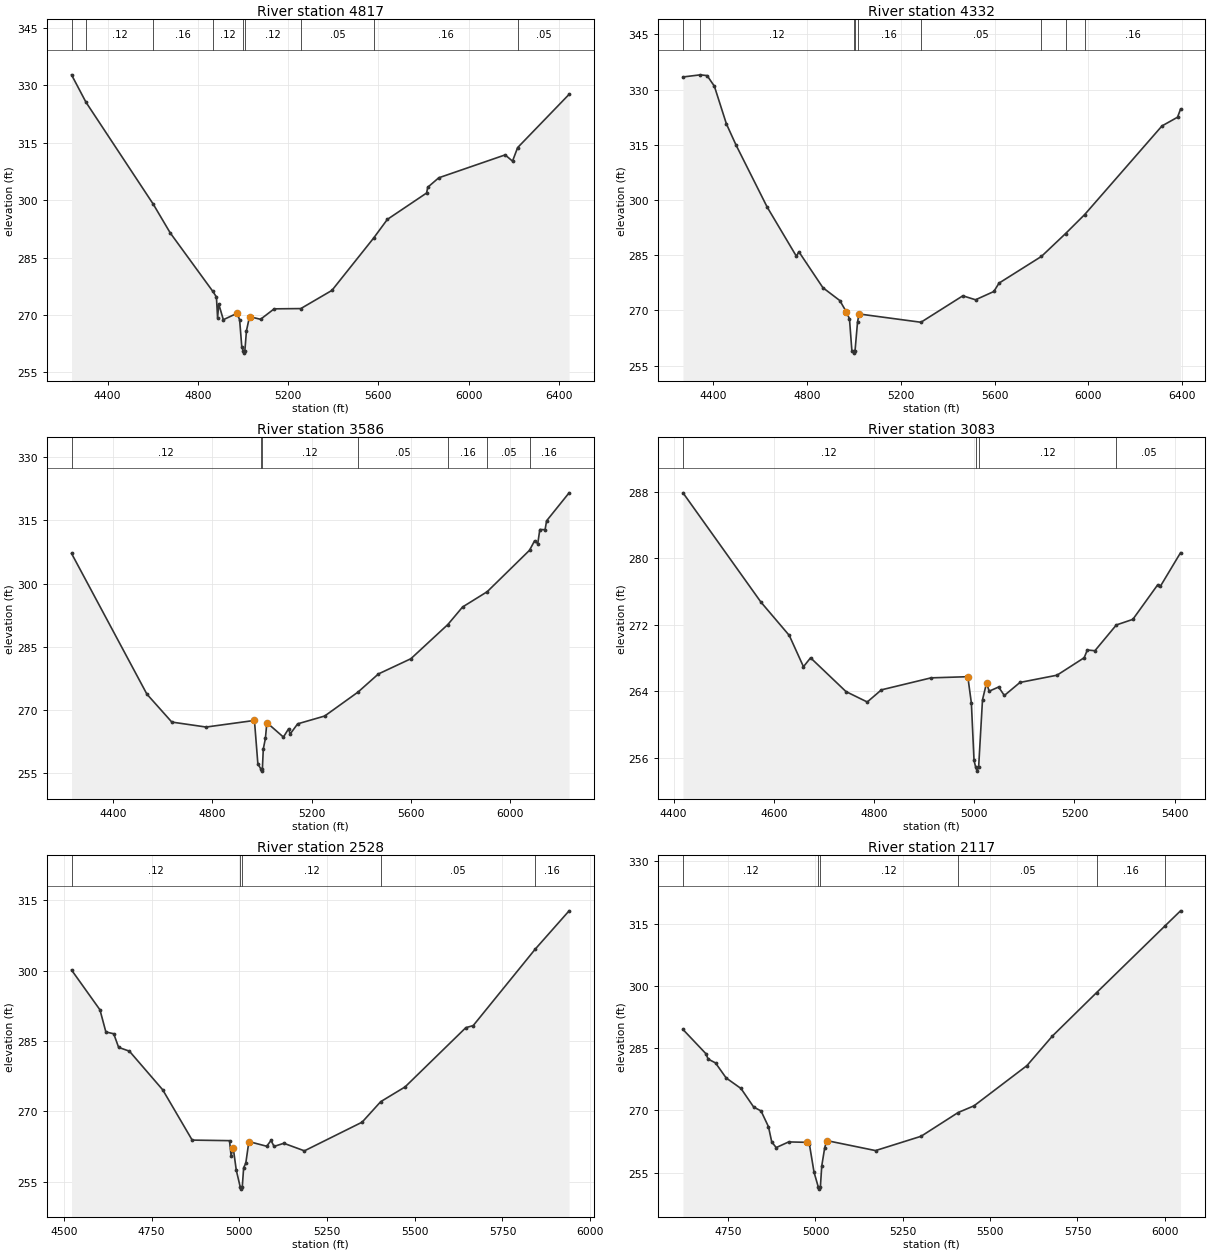
Type RM Length L Ch R = 1 ,4817    ,485,485,485
BEGIN DESCRIPTION:
MALONE BRANCH 7.0
END DESCRIPTION:
XS GIS Cut Line= 2
      3630162.27     10646814.18      3632316.54     10646340.66
#Sta/Elev= 30
  4239.8  332.74  4303.8  325.58  4601.9  298.96  4677.3  291.44  4866.4  276.14
  4882.1   274.7  4887.2  269.25  4892.4  272.84  4912.8  268.76  4974.3  270.46
    4985  268.67  4994.7  261.53    5002  260.53  5004.7  260.03    5008  260.53
  5015.2  265.87  5028.8  269.56  5077.7  268.87  5138.1   271.6  5256.2  271.67
  5394.1  276.42    5580  290.17  5639.8  294.97  5813.8  301.86  5818.9  303.37
  5867.8  305.84    6162  311.82  6194.7  310.19  6217.3  313.72  6445.5  327.64
#Mann= 9 ,-1 , 0
  4239.8     .16       0  4303.8     .12       0  4601.9     .16       0
  4866.4     .12       0    5002     .07       0    5008     .12       0
  5256.2     .05       0    5580     .16       0  6217.3     .05       0
Bank Sta=4974.3,5028.8
XS Rating Curve= 0 ,0
Exp/Cntr=0.3,0.1

Type RM Length L Ch R = 1 ,4332    ,746,746,746
BEGIN DESCRIPTION:
MALONE BRANCH 6.0
END DESCRIPTION:
XS GIS Cut Line= 2
      3630219.54     10647251.69      3632282.06     10646746.47
#Sta/Elev= 30
  4270.2  333.43  4344.4  334.01  4373.2   333.8  4404.1  330.92  4455.6  320.66
  4496.8   314.9  4629.6  298.05  4754.2   284.7  4764.7  285.93  4867.4  276.15
  4939.5  272.66  4967.6  269.55  4980.7   267.7    4991  259.05  4998.3  258.87
    5001  258.37  5004.3  258.87  5015.3  266.92  5021.9  269.01  5285.8  266.76
  5464.6  273.95  5518.8  272.87  5596.9  275.12    5619   277.4  5800.1  284.66
  5902.9  290.86  5984.7  296.04  6314.5  320.12  6380.9  322.49  6393.7  324.69
#Mann= 9 ,-1 , 0
  4270.2     .05       0  4344.4     .12       0  4998.3     .07       0
  5004.3     .12       0  5015.3     .16       0  5285.8     .05       0
  5800.1     .16       0  5902.9     .12       0  5984.7     .16       0
Bank Sta=4967.6,5021.9
XS Rating Curve= 0 ,0
Exp/Cntr=0.3,0.1

Type RM Length L Ch R = 1 ,3586    ,503,503,503
BEGIN DESCRIPTION:
MALONE BRANCH 5.0
END DESCRIPTION:
XS GIS Cut Line= 2
      3630519.74     10647950.28      3632205.87     10646862.62
#Sta/Elev= 30
  4232.3  307.18  4536.2  273.79  4636.7  267.16  4775.1  265.98  4969.9  267.55
  4983.7  257.24  4995.9  256.02  4998.6  255.52  5001.9  256.02  5005.6  260.78
  5014.1  263.28    5020  267.03  5086.7   263.6  5107.8  265.59  5113.7  264.31
  5144.1  266.74    5253  268.59  5387.6  274.28  5469.8  278.58  5600.7  282.19
  5749.9  290.31  5809.3  294.47  5908.6   298.1  6079.2  307.93  6099.7  310.18
  6112.4   309.5  6120.8  312.85    6142  312.82  6148.1  314.92  6238.8  321.56
#Mann= 7 ,-1 , 0
  4232.3     .12       0  4995.9     .07       0  5001.9     .12       0
  5387.6     .05       0  5749.9     .16       0  5908.6     .05       0
  6079.2     .16       0
Bank Sta=4969.9,5020
XS Rating Curve= 0 ,0
Exp/Cntr=0.3,0.1

Type RM Length L Ch R = 1 ,3083    ,555,555,555
BEGIN DESCRIPTION:
MALONE BRANCH 4.0
END DESCRIPTION:
XS GIS Cut Line= 3
      3630899.61     10648260.19      3631299.61     10647860.19
      3631699.62     10647710.18
#Sta/Elev= 30
  4418.8  287.86  4574.4  274.72  4630.9  270.72  4659.2  266.96  4673.4  268.03
  4744.1  263.97  4786.5  262.72  4814.8  264.18  4913.8  265.62  4987.2  265.76
  4994.3  262.59  4999.6  255.69  5002.8  254.91  5005.6  254.41  5008.8  254.91
  5016.5  262.99  5024.5  264.99  5029.9  264.02  5048.6  264.52  5060.1   263.5
  5091.3  265.07  5165.2  265.94  5219.4  268.04  5225.7  268.97  5240.8  268.88
  5283.6  271.98  5316.5  272.65  5366.3  276.82  5371.6  276.64  5411.7  280.66
#Mann= 4 ,-1 , 0
  4418.8     .12       0  5002.8     .07       0  5008.8     .12       0
  5283.6     .05       0
Bank Sta=4987.2,5024.5
XS Rating Curve= 0 ,0
Exp/Cntr=0.3,0.1

Type RM Length L Ch R = 1 ,2528    ,411,411,411
BEGIN DESCRIPTION:
MALONE BRANCH 3.0
END DESCRIPTION:
XS GIS Cut Line= 3
      3630849.62     10648410.18      3631249.61     10648210.19
      3632049.58     10647660.21
#Sta/Elev= 30
  4521.9  300.11  4602.9  291.62  4619.7  286.91  4642.1  286.52  4656.1  283.62
  4686.8  282.81  4781.8  274.57  4865.7  263.86  4972.1  263.74  4976.6  260.54
  4982.6  262.25  4991.4  257.45  5002.5  253.91  5005.3  253.41  5008.5  253.91
  5012.4  257.98  5018.5  258.93  5027.3  263.55    5078  262.55  5090.5  263.79
    5099  262.51  5126.9  263.18  5185.6  261.57    5350  267.68    5403  272.05
  5472.4  275.19  5645.6  287.82  5666.6  288.26  5843.3  304.55  5939.9  312.72
#Mann= 5 ,-1 , 0
  4521.9     .12       0  5002.5     .07       0  5008.5     .12       0
    5403     .05       0  5843.3     .16       0
Bank Sta=4982.6,5027.3
XS Rating Curve= 0 ,0
Exp/Cntr=0.3,0.1

Type RM Length L Ch R = 1 ,2117    ,1043,1043,1043
BEGIN DESCRIPTION:
MALONE BRANCH 2.0
END DESCRIPTION:
XS GIS Cut Line= 2
      3631014.53     10648674.24      3632216.15     10647909.57
#Sta/Elev= 30
  4620.7  289.51    4686   283.7  4692.7  282.38  4713.8  281.45  4744.3  277.82
  4786.7  275.29  4823.1  270.81  4844.2  269.87  4865.4  266.07  4874.7  262.42
  4887.5  261.04  4923.1  262.41  4974.6  262.31  4982.3     262  4995.8  255.13
    5008  251.53  5010.8  251.03    5014  251.53  5017.9   256.6  5026.3  260.98
  5032.2  262.73  5171.9  260.32  5302.3  263.77  5408.3  269.49  5453.8  271.11
  5605.4  280.81  5678.2  287.93  5804.7   298.4  5999.7  314.41    6045  318.11
#Mann= 6 ,-1 , 0
  4620.7     .12       0    5008     .07       0    5014     .12       0
  5408.3     .05       0  5804.7     .16       0  5999.7     .12       0
Bank Sta=4974.6,5032.2
XS Rating Curve= 0 ,0
Exp/Cntr=0.3,0.1

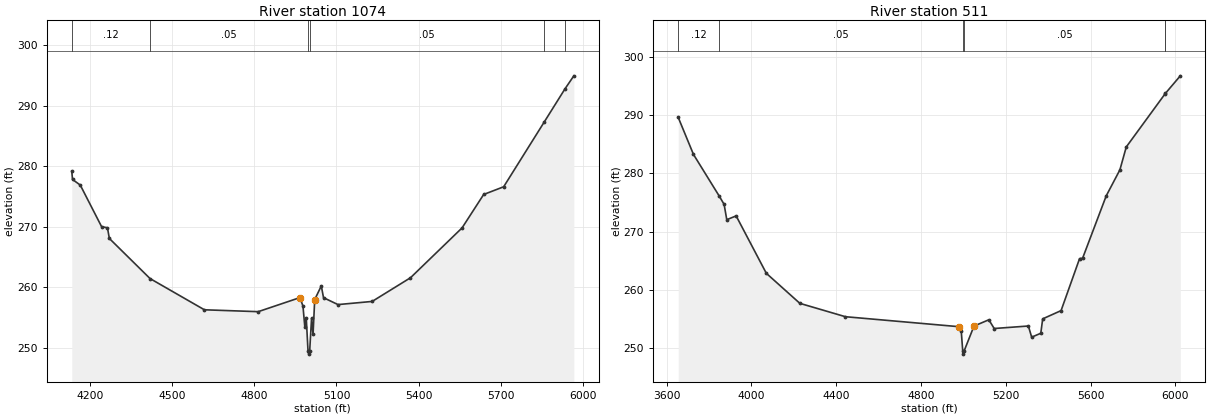
Type RM Length L Ch R = 1 ,1074    ,563,563,563
BEGIN DESCRIPTION:
Mapping XS 54d78112
END DESCRIPTION:
XS GIS Cut Line= 4
      3631123.11     10648772.85      3631581.45     10649252.02
      3631873.11      10649140.9      3632331.46     10648418.66
#Sta/Elev= 30
  4134.9  279.18  4137.6  277.82  4165.9  276.89  4243.6  270.03    4265  269.84
  4271.9  268.08  4420.2  261.46  4618.5   256.3  4814.6  255.99  4967.2  258.32
  4977.9  256.89  4984.5  253.53  4989.8     255  4996.3  249.48  4999.1  248.98
  5002.3  249.48  5009.2   254.9  5014.6  252.23  5020.7  257.99  5044.7  260.24
  5052.8   258.3  5105.5  257.16  5230.1  257.68  5369.9  261.59  5557.9  269.82
  5636.7  275.34  5709.6  276.61  5858.4  287.37  5933.2  292.78  5965.5  294.93
#Mann= 6 ,-1 , 0
  4134.9     .12       0  4420.2     .05       0  4996.3     .03       0
  5002.3     .05       0  5858.4     .07       0  5933.2     .05       0
Bank Sta=4967.2,5020.7
XS Rating Curve= 0 ,0
Exp/Cntr=0.3,0.1

Type RM Length L Ch R = 1 ,511     ,0,0,0
BEGIN DESCRIPTION:
MALONE BRANCH 1.0
END DESCRIPTION:
XS GIS Cut Line= 4
      3630984.25     10648814.55      3631643.95     10649731.18
      3632005.06     10649717.29       3632449.5     10648960.35
#Sta/Elev= 30
    3655  289.65  3726.9  283.28  3846.9   276.2  3871.4  274.69    3884  272.05
  3928.2   272.7  4070.6  262.82  4228.7  257.65  4443.7  255.35  4980.1  253.63
  4990.2  252.84  4997.2  249.41  4999.9  248.91  5003.2  249.41  5050.2  253.74
  5120.2  254.82  5145.5  253.32  5306.7  253.75  5322.3  251.83  5365.3   252.5
  5374.3  254.98    5461   256.4  5548.2  265.34  5562.6  265.42    5674  276.15
  5738.5  280.63  5768.6  284.57  5952.4  293.75  5952.8  293.77  6023.5  296.81
#Mann= 6 ,-1 , 0
    3655     .12       0  3846.9     .05       0  4997.2     .03       0
  5003.2     .05       0  5952.4     .16       0  5952.8     .05       0
Bank Sta=4980.1,5050.2
XS Rating Curve= 0 ,0
Exp/Cntr=0.3,0.1

Chan Stop Cuts=-1
Use User Specified Reach Order=0
Composite Channel Slope=5