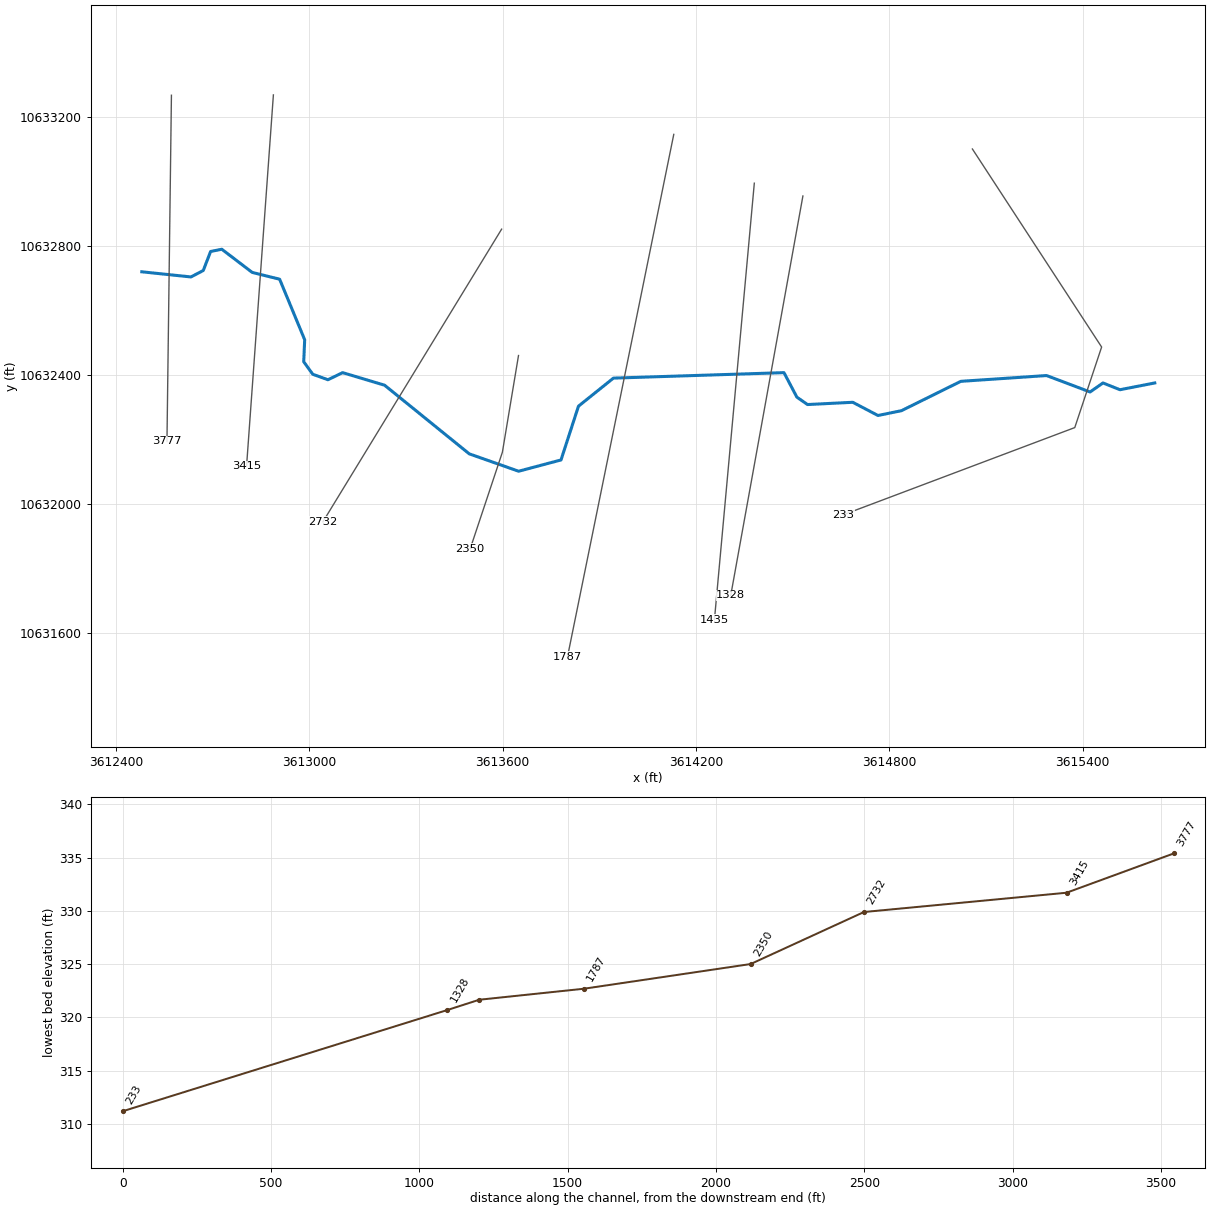
--- POWELL BRANCH.prj (project) ---

Proj Title=POWELL BRANCH Base Level Engineering
Current Plan=p01
Default Exp/Contr=0.3,0.1
English Units
Geom File=g01
Flow File=f01
Plan File=p01
Y Axis Title=Elevation
X Axis Title(PF)=Main Channel Distance
X Axis Title(XS)=Station
BEGIN DESCRIPTION:
POWELL BRANCH
END DESCRIPTION:
DSS Export Rating Curves= 0
DSS Export Rating Curve Sorted= 0
DSS Export Volume Flow Curves= 0
DXF OffsetX= 0
DXF OffsetY= 0
DXF ScaleX= 1
DXF ScaleY= 10

--- POWELL BRANCH.p01 (plan) ---

Plan Title=Multiple Run
Short Identifier=Multiple
Geom File=g01
Flow File=f01
Subcritical Flow
K Sum by GR= 0
Std Step Tol= 0.01
Critical Tol= 0.01
Num of Std Step Trials= 20
Max Error Tol= 0.3
Flow Tol Ratio= 0.001
Split Flow NTrial= 30
Split Flow Tol= 0.02
Split Flow Ratio= 0.02
Log Output Level= 0
Friction Slope Method= 1
Unsteady Friction Slope Method= 2
Unsteady Bridges Friction Slope Method= 1
Parabolic Critical Depth
Global Vel Dist=  1 , 1 , 1
Global Log Level= 0
CheckData=True
Encroach Param= -1, 0, 0, 0
BEGIN DESCRIPTION:
Multiple Run
END DESCRIPTION:

--- POWELL BRANCH.f01 (steady flow) ---

Flow Title=Multiple
Number of Profiles=7
Profile Names=10-year,25-year,50-year,1pct_min,100-year,1pct_plu,500-year
River Rch & RM= POWELL BRANCH,Reach-1,3777
    1456    2017    2484    2234    3022    4086    4454
River Rch & RM= POWELL BRANCH,Reach-1,2732
    2210    3131    3915    3569    4827    6528    7314
Boundary for River Rch & Prof#=POWELL BRANCH,Reach-1,1
Up Type=0
Dn Type=3
Dn Slope=0.005
Boundary for River Rch & Prof#=POWELL BRANCH,Reach-1,2
Up Type=0
Dn Type=3
Dn Slope=0.005
Boundary for River Rch & Prof#=POWELL BRANCH,Reach-1,3
Up Type=0
Dn Type=3
Dn Slope=0.005
Boundary for River Rch & Prof#=POWELL BRANCH,Reach-1,4
Up Type=0
Dn Type=3
Dn Slope=0.005
Boundary for River Rch & Prof#=POWELL BRANCH,Reach-1,5
Up Type=0
Dn Type=3
Dn Slope=0.005
Boundary for River Rch & Prof#=POWELL BRANCH,Reach-1,6
Up Type=0
Dn Type=3
Dn Slope=0.005
Boundary for River Rch & Prof#=POWELL BRANCH,Reach-1,7
Up Type=0
Dn Type=3
Dn Slope=0.005

--- POWELL BRANCH.g01 (geometry) ---

Geom Title=Existing Conditions
Program Version=4.10

River Reach=POWELL BRANCH   ,Reach-1
Reach XY= 30
      3612480.53     10632719.97        3612633.       10632704.
      3612671.25       10632724.        3612694.       10632783.
      3612728.75       10632790.      3612823.25       10632718.
      3612908.25       10632697.        3612986.       10632509.
        3612983.       10632441.        3613011.       10632402.
      3613058.25       10632385.      3613103.75       10632407.
        3613234.       10632368.      3613496.75       10632155.
        3613650.       10632101.       3613781.5       10632136.
      3613835.75       10632303.      3613944.25       10632390.
       3614473.5       10632407.       3614513.5       10632331.
       3614546.5       10632308.        3614687.       10632315.
      3614765.25       10632274.      3614838.25       10632289.
      3615022.25       10632380.       3615288.5       10632398.
       3615423.5       10632347.       3615463.5       10632375.
      3615516.25       10632354.      3615624.25       10632375.

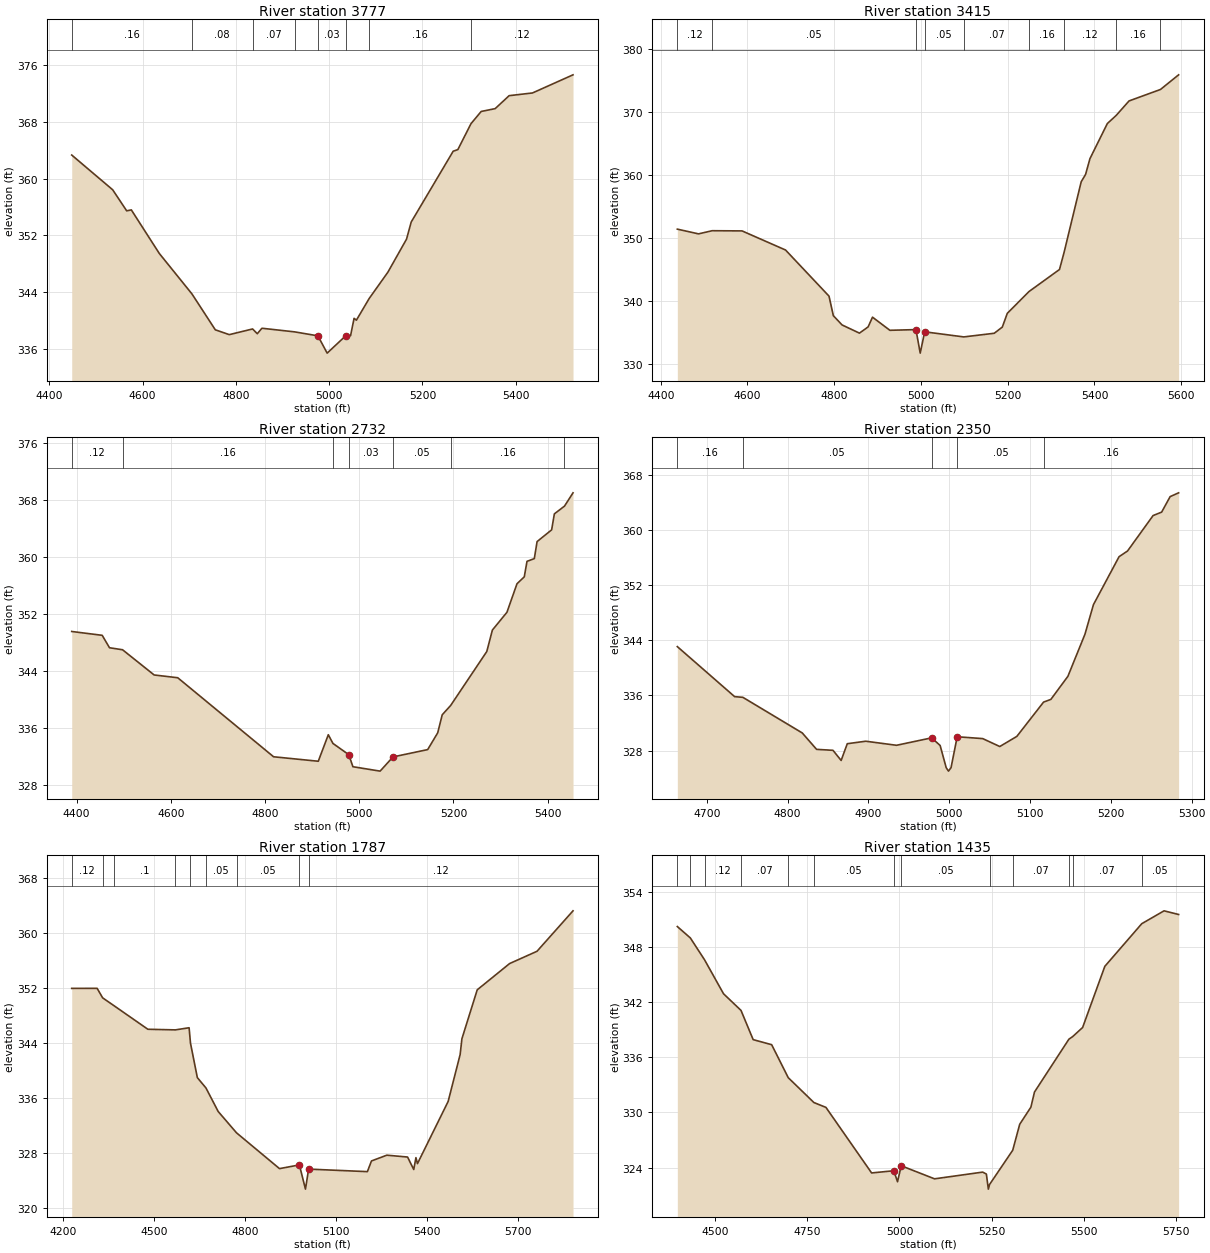
Type RM Length L Ch R = 1 ,3777    ,362,362,362
BEGIN DESCRIPTION:
POWELL BRANCH 6.0
END DESCRIPTION:
XS GIS Cut Line= 2
      3612572.45     10633267.95      3612558.58     10632193.34
#Sta/Elev= 30
  4448.2  363.34    4536  358.44    4566  355.47    4576   355.6    4636  349.45
    4706  343.74    4756  338.68    4786     338    4836   338.8    4846  338.13
    4856   338.9    4926  338.39    4976  337.83  4995.8  335.39    5036  337.86
    5046  337.85  5053.5   340.3  5058.5  340.04    5086  343.11    5126  346.81
    5166  351.48    5176  353.89    5266  363.88    5276  364.11  5304.2  367.77
    5326  369.49    5356  369.89    5386  371.72    5436   372.1  5522.9  374.66
#Mann= 8 ,-1 , 0
  4448.2     .16       0    4706     .08       0    4836     .07       0
    4926     .05       0    4976     .03       0    5036     .05       0
    5086     .16       0  5304.2     .12       0
Bank Sta=4976,5036
XS Rating Curve= 0 ,0
Exp/Cntr=0.3,0.1

Type RM Length L Ch R = 1 ,3415    ,683,683,683
BEGIN DESCRIPTION:
POWELL BRANCH 5.0
END DESCRIPTION:
XS GIS Cut Line= 2
      3612888.89     10633268.99      3612805.56      10632116.2
#Sta/Elev= 30
  4438.3  351.36  4487.2  350.61  4518.5  351.11  4587.5  351.08  4687.8  348.05
    4788  340.74    4798  337.64  4818.1  336.17  4858.2  334.87  4878.2  335.86
  4888.3   337.4  4928.4  335.32  4988.5  335.43  4998.3   331.7  5008.6  335.08
  5098.8  334.27    5169  334.85  5187.6  335.83  5199.1  338.01  5249.2  341.47
  5319.4  344.96    5330  347.67  5369.5  358.88  5379.6  360.04  5389.6  362.53
  5429.7   368.1  5450.1  369.39  5479.8  371.69  5552.3  373.51  5594.1  375.83
#Mann= 9 ,-1 , 0
  4438.3     .12       0  4518.5     .05       0  4988.5     .03       0
  5008.6     .05       0  5098.8     .07       0  5249.2     .16       0
    5330     .12       0  5450.1     .16       0  5552.3     .12       0
Bank Sta=4988.5,5008.6
XS Rating Curve= 0 ,0
Exp/Cntr=0.3,0.1

Type RM Length L Ch R = 1 ,2732    ,382,382,382
BEGIN DESCRIPTION:
POWELL BRANCH 4.0
END DESCRIPTION:
XS GIS Cut Line= 2
       3613597.2     10632852.32      3613042.45     10631943.91
#Sta/Elev= 30
  4389.6  349.54  4454.3     349  4469.8  347.25  4497.5  346.97  4564.6  343.42
  4614.7  343.03  4818.2  331.91  4913.1  331.28  4934.4  335.01  4944.2  333.79
    4978   332.2  4986.6  330.51  5044.4  329.89  5071.8  331.89  5145.4  332.92
  5166.7  335.28  5176.3  337.82  5194.2  339.13  5270.9  346.72  5282.8  349.74
  5313.7  352.24    5335  356.25  5350.5  357.23  5356.3  359.41  5371.8  359.79
  5377.7  362.19  5408.6  363.84  5414.4  366.09  5435.9  367.18    5454  369.05
#Mann= 7 ,-1 , 0
  4389.6     .12       0  4497.5     .16       0  4944.2     .05       0
    4978     .03       0  5071.8     .05       0  5194.2     .16       0
  5435.9     .12       0
Bank Sta=4978,5071.8
XS Rating Curve= 0 ,0
Exp/Cntr=0.3,0.1

Type RM Length L Ch R = 1 ,2350    ,563,563,563
BEGIN DESCRIPTION:
POWELL BRANCH 3.0
END DESCRIPTION:
XS GIS Cut Line= 3
      3613649.61     10632460.17      3613599.61     10632160.19
      3613499.62     10631860.23
#Sta/Elev= 30
  4663.6  343.08  4734.5  335.82  4744.7  335.72  4818.2  330.55  4835.9  328.17
  4856.2  328.03  4866.3  326.56  4873.9  328.99  4896.8  329.35  4934.8  328.76
  4978.3  329.84  4988.8  328.73  4996.3  325.51  4999.1  325.01  5002.3  325.51
  5009.9     330  5041.5  329.73  5062.6  328.58  5083.7  330.05  5116.8  335.03
  5125.8  335.42  5146.9  338.77    5168  344.88  5178.5  349.17  5210.2  356.13
  5220.7  356.96  5252.3   362.1  5262.9   362.6  5273.4  364.85  5283.9   365.4
#Mann= 5 ,-1 , 0
  4663.6     .16       0  4744.7     .05       0  4978.3     .03       0
  5009.9     .05       0  5116.8     .16       0
Bank Sta=4978.3,5009.9
XS Rating Curve= 0 ,0
Exp/Cntr=0.3,0.1

Type RM Length L Ch R = 1 ,1787    ,352,352,352
BEGIN DESCRIPTION:
Mapping XS d95a9878
END DESCRIPTION:
XS GIS Cut Line= 2
      3614131.48     10633146.47      3613801.65     10631525.08
#Sta/Elev= 30
  4228.3  351.96  4312.1  351.97  4330.4  350.58  4368.7  349.41  4479.6     346
  4570.5  345.91  4615.7  346.22  4620.3  343.97  4642.9  338.95  4671.4  337.44
  4711.7  334.01  4772.2   330.9  4914.1  325.68  4979.7  326.22  4999.8  322.69
  5010.2  325.61  5204.2  325.24  5217.7   326.8  5268.3  327.64  5336.8  327.37
  5357.2  325.55  5364.4  327.28  5369.5  326.41  5470.7  335.47  5510.3  342.31
  5516.2  344.62  5566.7  351.75  5673.6  355.58    5764  357.37  5882.9  363.27
#Mann= 9 ,-1 , 0
  4228.3     .12       0  4330.4     .05       0  4368.7      .1       0
  4570.5     .15       0  4620.3      .1       0  4671.4     .05       0
  4772.2     .05       0  4979.7     .03       0  5010.2     .12       0
Bank Sta=4979.7,5010.2
XS Rating Curve= 0 ,0
Exp/Cntr=0.3,0.1

Type RM Length L Ch R = 1 ,1435    ,107,107,107
BEGIN DESCRIPTION:
Mapping XS dc47be4e
END DESCRIPTION:
XS GIS Cut Line= 2
      3614381.43       10632995.      3614257.74     10631640.84
#Sta/Elev= 30
  4397.5  350.22  4432.8  348.98  4471.4   346.6  4522.8  342.91  4570.2   341.1
  4603.2  337.92  4653.4  337.37  4698.4  333.78  4767.9  331.08  4800.6  330.55
  4924.5  323.42  4984.7  323.66  4994.8  322.46  5004.8   324.2  5095.2  322.78
  5225.7  323.51  5235.8   323.3  5241.2  321.66  5244.4  322.16  5307.3  325.89
  5326.2  328.71  5356.6  330.58  5366.3  332.22  5459.7  337.97  5469.9  338.25
  5496.9  339.24  5557.1  345.89  5657.3  350.53  5717.8  351.93  5757.3  351.53
#Mann= 13 ,-1 , 0
  4397.5     .12       0  4432.8     .16       0  4471.4     .12       0
  4570.2     .07       0  4698.4     .05       0  4767.9     .05       0
  4984.7     .03       0  5004.8     .05       0  5244.4     .07       0
  5307.3     .07       0  5459.7     .05       0  5469.9     .07       0
  5657.3     .05       0
Bank Sta=4984.7,5004.8
XS Rating Curve= 0 ,0
Exp/Cntr=0.3,0.1

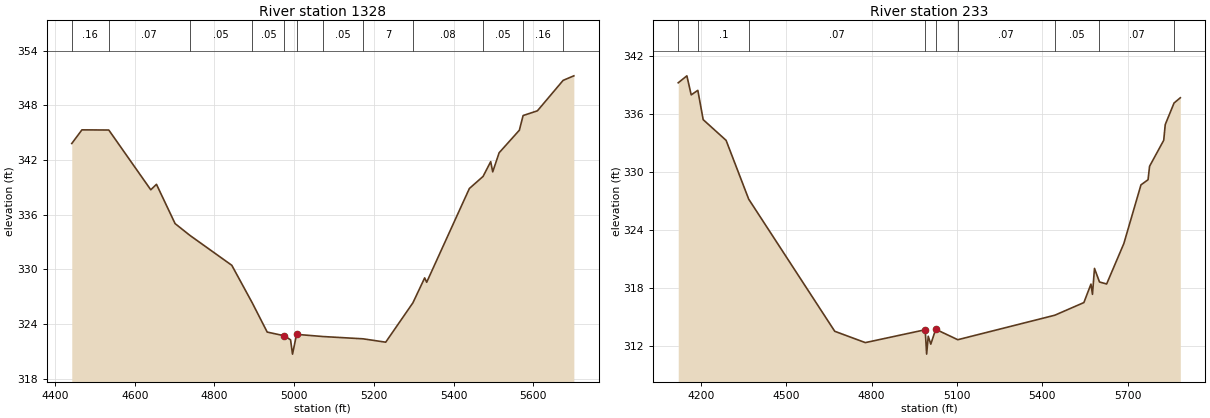
Type RM Length L Ch R = 1 ,1328    ,1095,1095,1095
BEGIN DESCRIPTION:
POWELL BRANCH 2.0
END DESCRIPTION:
XS GIS Cut Line= 2
      3614532.24     10632955.24      3614308.29     10631715.71
#Sta/Elev= 30
    4442  343.82  4467.5  345.32  4534.9   345.3  4640.2  338.74  4654.5  339.34
  4701.2  335.03  4737.9  333.75  4843.5  330.45  4894.9  326.32  4932.3  323.12
  4975.6  322.71  4990.9  322.27  4995.8   320.7    5006  322.87  5072.5  322.63
  5172.9  322.38  5229.6  322.01  5297.8  326.33  5327.4  329.07  5332.4  328.59
  5439.5  338.88  5473.9  340.21    5493  341.83  5498.1  340.71  5514.1   342.8
  5564.9  345.28  5574.3  346.89  5610.2  347.41  5674.7  350.75  5701.6  351.25
#Mann= 12 ,-1 , 0
    4442     .16       0  4534.9     .07       0  4737.9     .05       0
  4894.9     .05       0  4975.6     .03       0    5006     .05       0
  5072.5     .05       0  5172.9       7       0  5297.8     .08       0
  5473.9     .05       0  5574.3     .16       0  5674.7     .05       0
Bank Sta=4975.6,5006
XS Rating Curve= 0 ,0
Exp/Cntr=0.3,0.1

Type RM Length L Ch R = 1 ,233     ,0,0,0
BEGIN DESCRIPTION:
POWELL BRANCH 1.0
END DESCRIPTION:
XS GIS Cut Line= 4
      3615058.26     10633101.11      3615459.32      10632486.5
      3615375.99      10632236.5      3614657.23     10631965.67
#Sta/Elev= 30
  4120.2  339.25  4150.6  339.97  4165.8     338  4189.1  338.47  4207.9  335.44
  4288.5   333.3    4368  327.22  4670.6  313.56  4778.1  312.39 4988.64  313.72
  4993.7   311.2  4999.3  313.05  5008.3  312.23  5025.6  313.77  5103.2  312.69
  5444.2  315.22  5546.6  316.53  5571.5  318.44  5576.8  317.38  5583.9  320.06
  5601.5  318.66  5626.6  318.45    5687  322.62  5747.4   328.7  5772.3  329.23
  5777.6  330.62  5827.4  333.31  5832.7  334.93  5863.7  337.16  5885.7   337.7
#Mann= 9 ,-1 , 0
  4120.2     .12       0  4189.1      .1       0    4368     .07       0
  4987.2     .03       0  5025.6     .05       0  5103.2     .07       0
  5444.2     .05       0  5601.5     .07       0  5863.7     .05       0
Bank Sta=4988.64,5025.6
XS Rating Curve= 0 ,0
Exp/Cntr=0.3,0.1

Chan Stop Cuts=-1
Use User Specified Reach Order=0
Composite Channel Slope=5