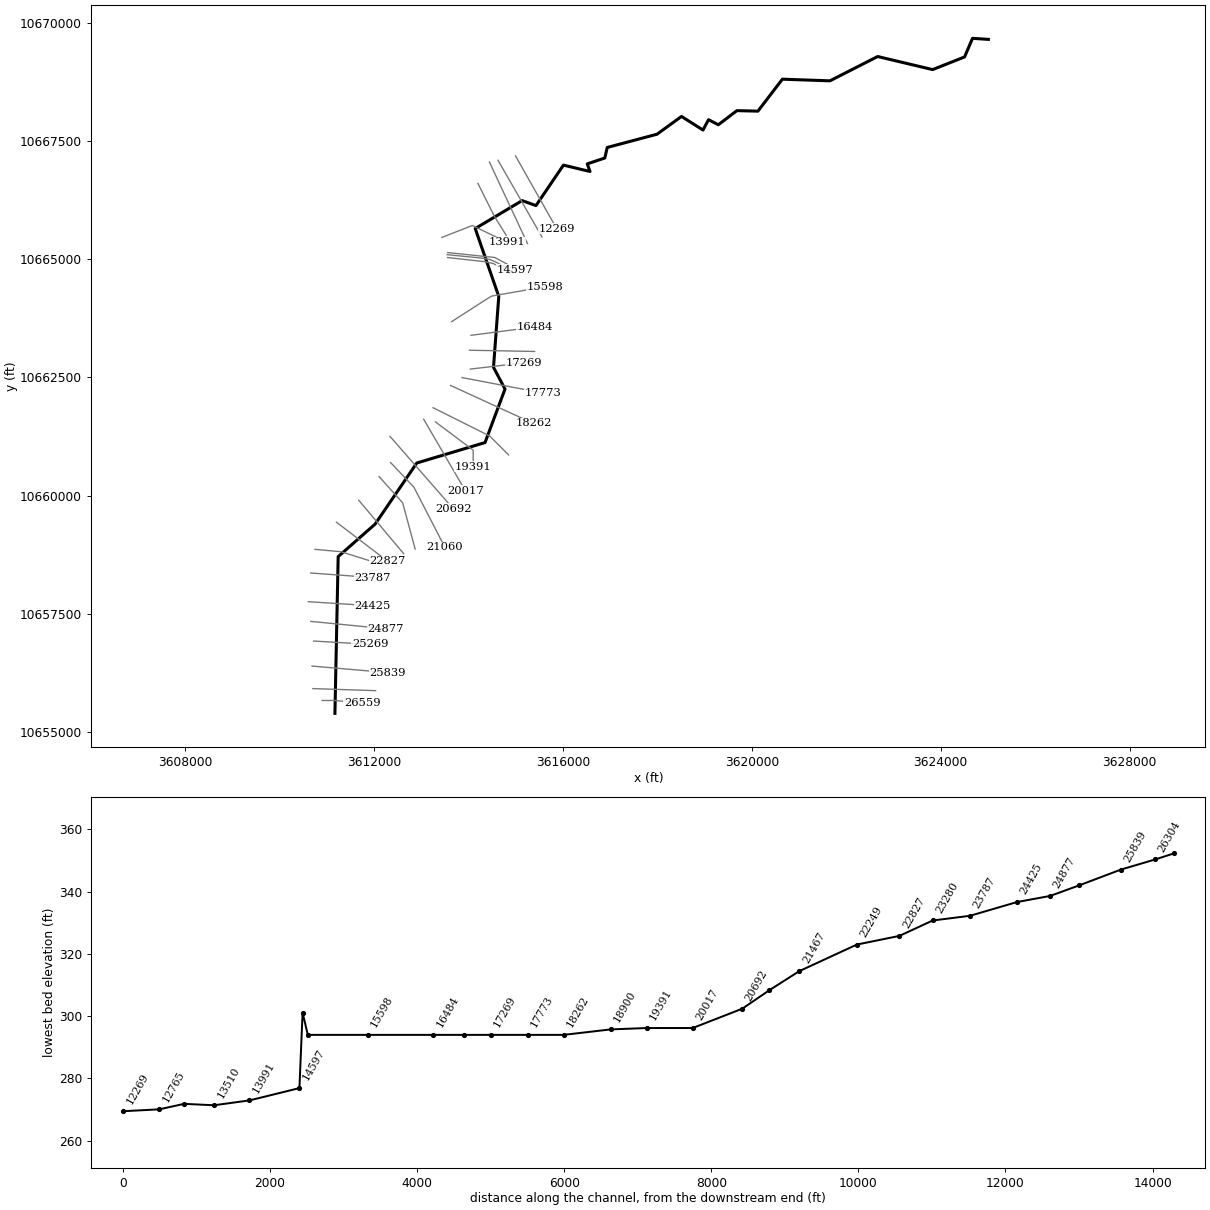
--- PRAIRIE CREEK.prj (project) ---

Proj Title=PRAIRIE CREEK Base Level Engineering
Current Plan=p01
Default Exp/Contr=0.3,0.1
English Units
Geom File=g01
Flow File=f01
Plan File=p01
Y Axis Title=Elevation
X Axis Title(PF)=Main Channel Distance
X Axis Title(XS)=Station
BEGIN DESCRIPTION:
PRAIRIE CREEK
END DESCRIPTION:
DSS Export Rating Curves= 0
DSS Export Rating Curve Sorted= 0
DSS Export Volume Flow Curves= 0
DXF OffsetX= 0
DXF OffsetY= 0
DXF ScaleX= 1
DXF ScaleY= 10

--- PRAIRIE CREEK.p01 (plan) ---

Plan Title=Multiple Run
Short Identifier=Multiple
Geom File=g01
Flow File=f01
Subcritical Flow
K Sum by GR= 0
Std Step Tol= 0.01
Critical Tol= 0.01
Num of Std Step Trials= 20
Max Error Tol= 0.3
Flow Tol Ratio= 0.001
Split Flow NTrial= 30
Split Flow Tol= 0.02
Split Flow Ratio= 0.02
Log Output Level= 0
Friction Slope Method= 1
Unsteady Friction Slope Method= 2
Unsteady Bridges Friction Slope Method= 1
Parabolic Critical Depth
Global Vel Dist=  1 , 1 , 1
Global Log Level= 0
CheckData=True
Encroach Param= -1, 0, 0, 0
BEGIN DESCRIPTION:
Multiple Run
END DESCRIPTION:

--- PRAIRIE CREEK.f01 (steady flow) ---

Flow Title=Multiple
Number of Profiles=7
Profile Names=10-year,25-year,50-year,1pct_min,100-year,1pct_plu,500-year
River Rch & RM= PRAIRIE CREEK,Reach-1,26559
    1104    1482    1786    1571    2124    2872    2992
River Rch & RM= PRAIRIE CREEK,Reach-1,25269
    1924    2673    3296    2961    4004    5415    5892
River Rch & RM= PRAIRIE CREEK,Reach-1,18262
    2436    3418    4243    3834    5185    7012    7720
River Rch & RM= PRAIRIE CREEK,Reach-1,13510
    3043    4318    5402    4914    6646    8988   10035
River Rch & RM= PRAIRIE CREEK,Reach-1,11273
    3457    4927    6181    5636    7622   10308   11564
River Rch & RM= PRAIRIE CREEK,Reach-1,6843
    3904    5592    7038    6437    8705   11772   13285
River Rch & RM= PRAIRIE CREEK,Reach-1,1418
    4880    7069    8966    8260   11170   15107   17297
Boundary for River Rch & Prof#=PRAIRIE CREEK,Reach-1,1
Up Type=0
Dn Type=3
Dn Slope=0.005
Boundary for River Rch & Prof#=PRAIRIE CREEK,Reach-1,2
Up Type=0
Dn Type=3
Dn Slope=0.005
Boundary for River Rch & Prof#=PRAIRIE CREEK,Reach-1,3
Up Type=0
Dn Type=3
Dn Slope=0.005
Boundary for River Rch & Prof#=PRAIRIE CREEK,Reach-1,4
Up Type=0
Dn Type=3
Dn Slope=0.005
Boundary for River Rch & Prof#=PRAIRIE CREEK,Reach-1,5
Up Type=0
Dn Type=3
Dn Slope=0.005
Boundary for River Rch & Prof#=PRAIRIE CREEK,Reach-1,6
Up Type=0
Dn Type=3
Dn Slope=0.005
Boundary for River Rch & Prof#=PRAIRIE CREEK,Reach-1,7
Up Type=0
Dn Type=3
Dn Slope=0.005

--- PRAIRIE CREEK.g01 (geometry) ---

Geom Title=Existing Conditions
Program Version=4.10

River Reach=PRAIRIE CREEK   ,Reach-1
Reach XY= 30
      3611171.75       10655387.       3611240.5       10658707.
      3612021.75       10659394.      3612905.25       10660689.
      3614350.75       10661122.       3614773.5       10662255.
      3614529.75       10662716.       3614641.5       10664217.
       3614142.5       10665654.      3615136.75       10666246.
      3615429.25       10666140.      3616010.75       10666997.
        3616574.       10666862.      3616514.75       10667023.
      3616886.25       10667148.        3616939.       10667371.
       3617993.5       10667652.      3618510.75       10668028.
        3618966.       10667740.        3619083.       10667959.
        3619291.       10667852.      3619683.75       10668151.
       3620129.5       10668140.        3620647.       10668817.
        3621654.       10668782.       3622664.5       10669297.
      3623828.75       10669020.       3624505.5       10669288.
       3624673.5       10669682.       3625009.5       10669660.

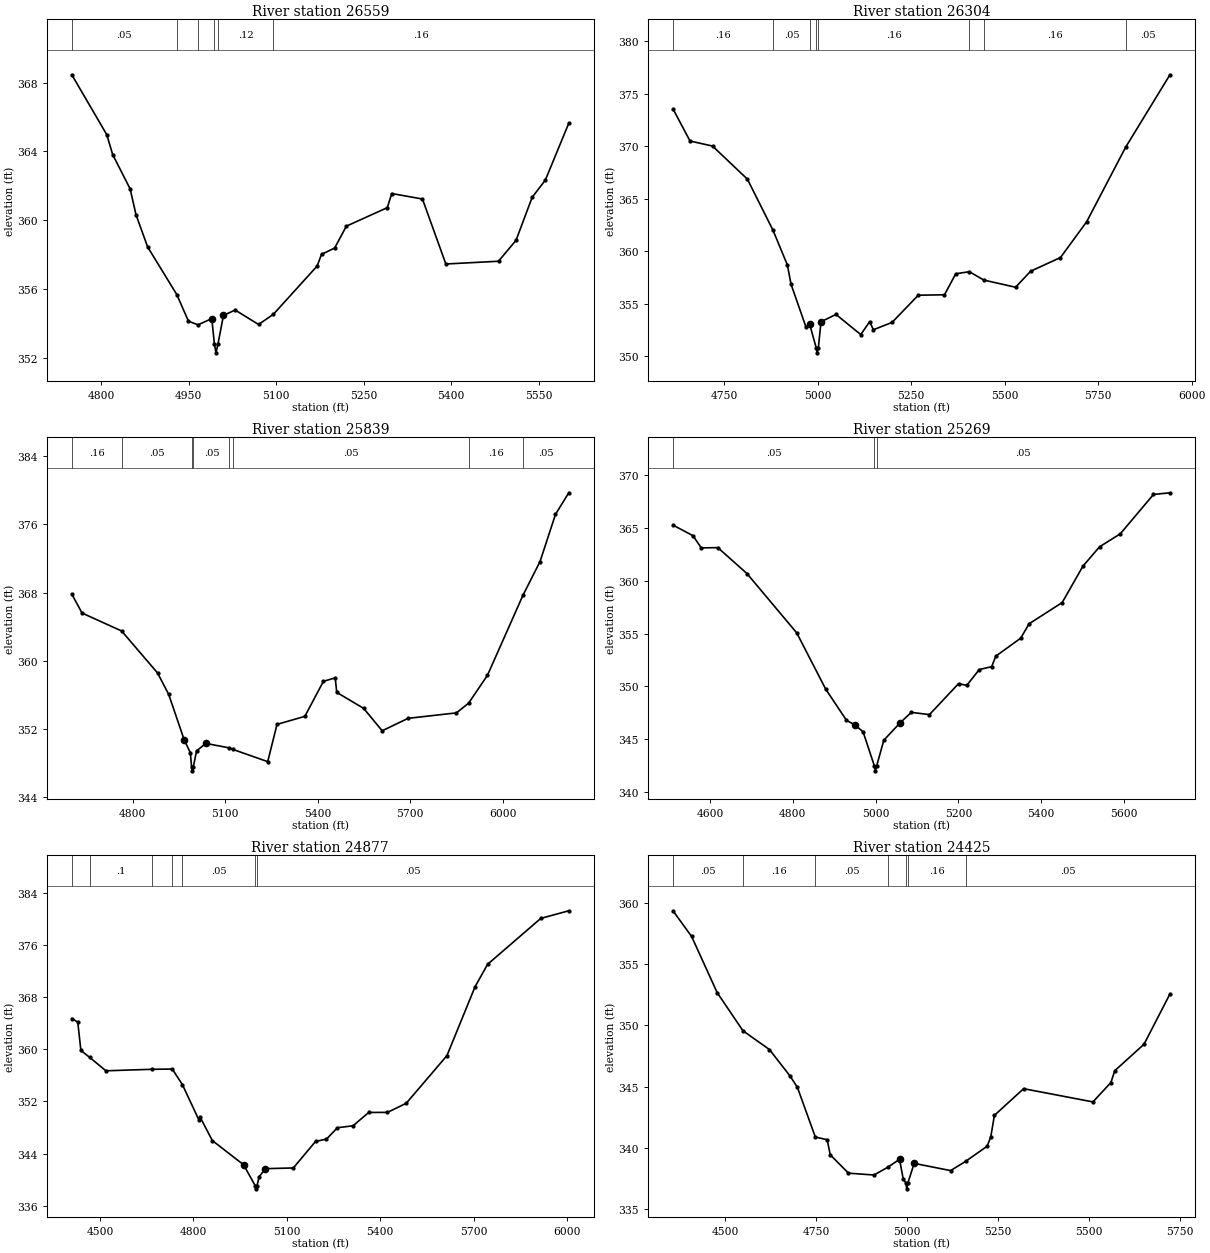
Type RM Length L Ch R = 1 ,26559   ,255,255,255
BEGIN DESCRIPTION:
PRAIRIE CREEK 51.0
END DESCRIPTION:
XS GIS Cut Line= 3
      3610899.64     10655660.19      3611149.61     10655660.19
      3611749.66     10655610.18
#Sta/Elev= 30
  4749.4  368.46  4809.4  364.97  4819.4  363.82  4849.4  361.82  4859.4  360.32
  4879.4  358.44  4929.4  355.67  4949.4  354.12  4965.7  353.91  4989.4  354.27
  4993.9  352.78  4996.6  352.28  4999.9  352.78  5009.4  354.46  5029.5  354.77
  5069.6  353.93  5094.9  354.52    5170  357.33  5177.5  358.01  5200.1  358.38
  5220.1  359.65  5290.4  360.73  5297.9  361.55  5350.6  361.23  5390.7  357.45
    5481  357.61  5511.1  358.83  5538.7  361.33  5561.3  362.33  5601.5  365.64
#Mann= 6 ,-1 , 0
  4749.4     .05       0  4929.4     .16       0  4965.7     .12       0
  4993.9     .07       0  4999.9     .12       0  5094.9     .16       0
Bank Sta=4989.4,5009.4
XS Rating Curve= 0 ,0
Exp/Cntr=0.3,0.1

Type RM Length L Ch R = 1 ,26304   ,465,465,465
BEGIN DESCRIPTION:
PRAIRIE CREEK 50.0
END DESCRIPTION:
XS GIS Cut Line= 2
      3610704.01     10655911.63       3612032.1     10655868.23
#Sta/Elev= 30
  4613.1  373.57  4658.7  370.51  4718.8  370.03    4812  366.88  4880.4  362.02
  4918.9  358.71  4928.9  356.85  4968.9  352.77  4978.9  353.03  4979.5  352.94
  4995.9  350.83  4998.7  350.33  5001.9  350.83  5008.9  353.29  5048.9  353.99
  5115.2  352.07    5139   353.3    5149  352.53    5199  353.23    5269  355.82
  5339.1  355.86  5369.1  357.86  5405.5  358.06  5444.5  357.26  5529.2  356.58
  5569.2   358.1  5649.2  359.41  5719.3  362.82  5823.5  369.92  5941.9  376.82
#Mann= 8 ,-1 , 0
  4613.1     .16       0  4880.4     .05       0  4979.5     .16       0
  4995.9     .07       0  5001.9     .16       0  5405.5      .1       0
  5444.5     .16       0  5823.5     .05       0
Bank Sta=4978.9,5008.9
XS Rating Curve= 0 ,0
Exp/Cntr=0.3,0.1

Type RM Length L Ch R = 1 ,25839   ,570,570,570
BEGIN DESCRIPTION:
PRAIRIE CREEK 49.0
END DESCRIPTION:
XS GIS Cut Line= 2
      3610686.62     10656389.06      3612292.52     10656250.17
#Sta/Elev= 30
  4602.3  367.82  4635.4   365.6  4763.7   363.5  4880.4  358.57  4916.5  356.06
  4966.6  350.74  4986.7  349.22  4990.6  347.59  4993.3  347.09  4996.6  347.59
  5006.8  349.42  5036.9  350.31  5113.3  349.78    5125   349.6  5237.7  348.17
  5267.8  352.54  5358.1  353.48  5418.3  357.59  5456.6     358  5461.6  356.29
  5548.8  354.42    5609  351.79  5693.1  353.25  5849.9  353.89  5889.3  355.03
  5950.3  358.29  6065.5  367.68  6120.9  371.64  6171.1  377.18  6214.2  379.71
#Mann= 8 ,-1 , 0
  4602.3     .16       0  4763.7     .05       0  4990.6     .03       0
  4996.6     .05       0  5113.3     .16       0    5125     .05       0
  5889.3     .16       0  6065.5     .05       0
Bank Sta=4966.6,5036.9
XS Rating Curve= 0 ,0
Exp/Cntr=0.3,0.1

Type RM Length L Ch R = 1 ,25269   ,392,392,392
BEGIN DESCRIPTION:
PRAIRIE CREEK 48.0
END DESCRIPTION:
XS GIS Cut Line= 2
      3610721.39     10656918.57      3611919.27     10656849.13
#Sta/Elev= 30
  4510.9  365.28  4559.2  364.27  4579.2  363.12  4619.3  363.14  4689.4  360.69
  4809.6  355.07  4879.7  349.73  4929.8  346.78  4949.9  346.35  4969.9  345.69
  4996.9  342.49  4999.7  341.99  5002.9  342.49    5020  344.89    5060  346.57
  5086.4  347.53  5130.2  347.32  5200.3  350.25  5220.3  350.09  5250.4  351.59
  5280.4  351.86  5290.4  352.86  5350.5  354.56  5370.6  355.92  5450.7  357.94
  5500.8  361.39  5540.8  363.22  5590.9  364.45  5671.1  368.18  5710.8  368.34
#Mann= 3 ,-1 , 0
  4510.9     .05       0  4996.9     .03       0  5002.9     .05       0
Bank Sta=4949.9,5060
XS Rating Curve= 0 ,0
Exp/Cntr=0.3,0.1

Type RM Length L Ch R = 1 ,24877   ,452,452,452
BEGIN DESCRIPTION:
PRAIRIE CREEK 47.0
END DESCRIPTION:
XS GIS Cut Line= 2
      3610660.61     10657335.24      3612249.14     10657178.99
#Sta/Elev= 30
  4409.6   364.7  4428.7  364.16  4438.7  359.82  4466.7  358.76  4519.1   356.7
  4666.3  356.93  4732.2  356.97  4764.8  354.58  4817.2  349.23  4822.2  349.55
  4860.8  346.02  4961.2  342.31  4998.4  339.12  5001.2  338.62  5004.4  339.12
  5011.5  340.49  5031.6  341.71  5121.1  341.82  5192.4  345.88  5227.5  346.24
  5262.7  347.98  5312.9  348.28  5363.2  350.32  5423.5  350.33  5483.8  351.73
  5614.4  359.02  5704.8  369.58    5745  373.01  5915.8  380.04  6005.8  381.21
#Mann= 7 ,-1 , 0
  4409.6     .05       0  4466.7      .1       0  4666.3     .08       0
  4732.2      .1       0  4764.8     .05       0  4998.4     .03       0
  5004.4     .05       0
Bank Sta=4961.2,5031.6
XS Rating Curve= 0 ,0
Exp/Cntr=0.3,0.1

Type RM Length L Ch R = 1 ,24425   ,638,638,638
BEGIN DESCRIPTION:
PRAIRIE CREEK 46.0
END DESCRIPTION:
XS GIS Cut Line= 2
      3610608.55     10657751.91      3611970.69     10657665.14
#Sta/Elev= 30
    4357  359.36  4408.2  357.26  4478.3  352.68  4549.2  349.56  4621.8  348.03
  4678.7  345.86  4698.7  344.94    4748  340.88  4780.6  340.66  4788.9  339.43
    4839  337.93  4909.2  337.78  4946.7  338.41  4979.3  339.06  4989.3  337.46
  4996.4  337.15  4999.1  336.65  5002.4  337.15  5019.4  338.73  5119.6  338.14
  5160.6  338.89  5219.8  340.13  5229.8  340.89  5239.8  342.65    5320  344.83
  5510.4  343.75  5559.7  345.33  5570.5   346.3  5650.7  348.46  5721.9  352.56
#Mann= 7 ,-1 , 0
    4357     .05       0  4549.2     .16       0    4748     .05       0
  4946.7     .16       0  4996.4     .07       0  5002.4     .16       0
  5160.6     .05       0
Bank Sta=4979.3,5019.4
XS Rating Curve= 0 ,0
Exp/Cntr=0.3,0.1

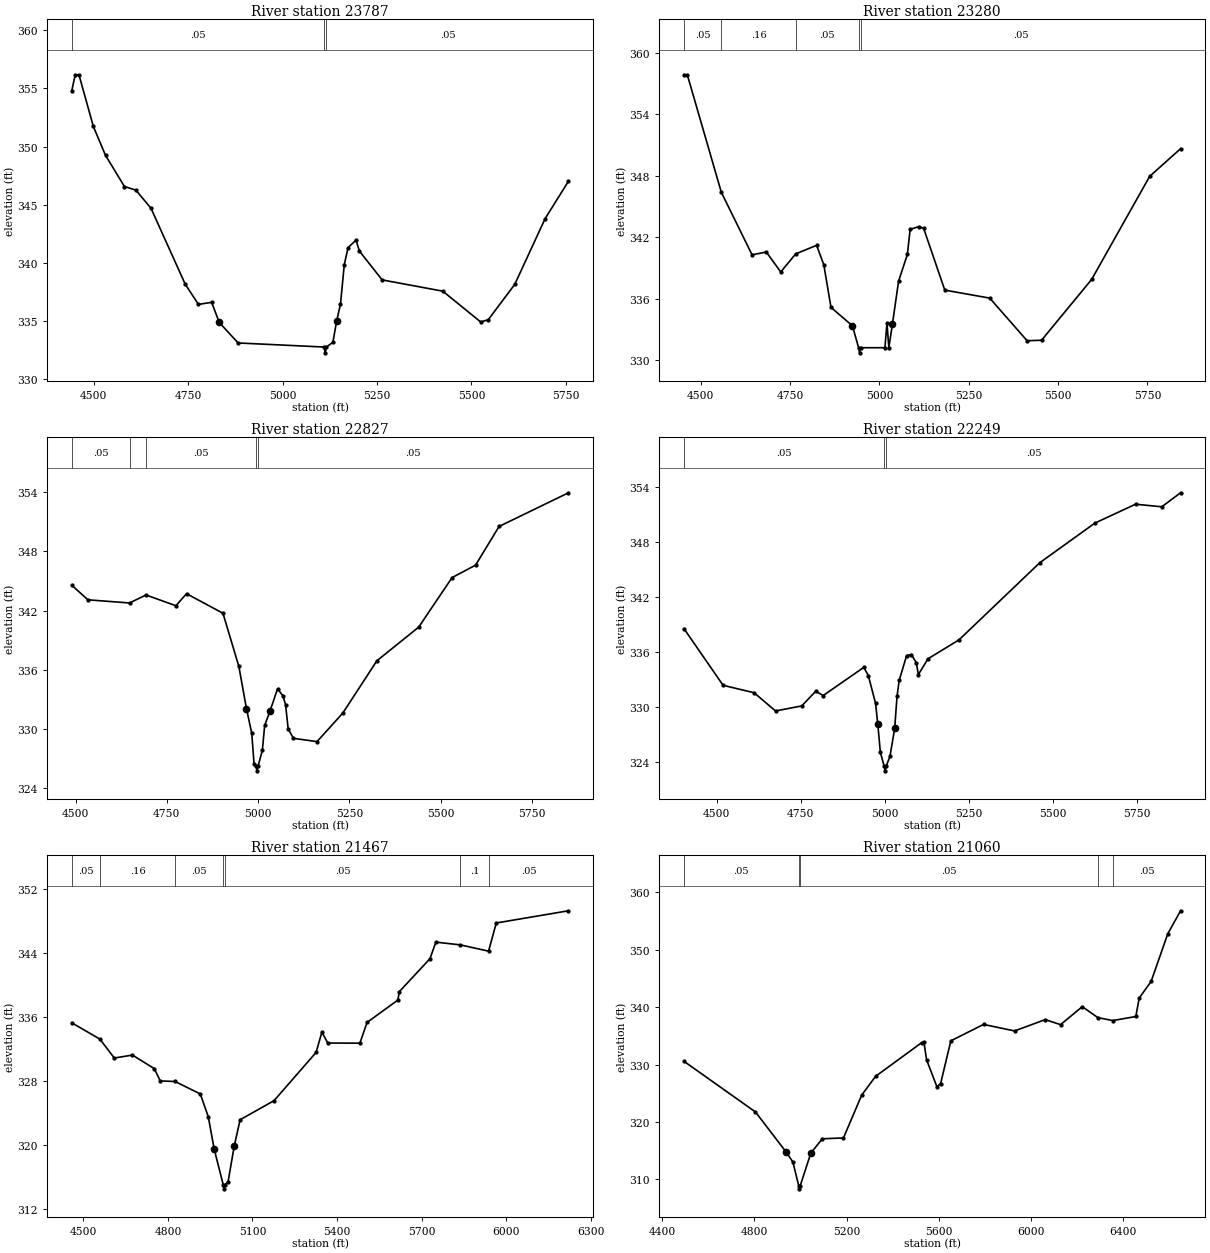
Type RM Length L Ch R = 1 ,23787   ,507,507,507
BEGIN DESCRIPTION:
PRAIRIE CREEK 45.0
END DESCRIPTION:
XS GIS Cut Line= 2
      3610660.64     10658359.54      3611971.36     10658264.06
#Sta/Elev= 30
  4442.5  354.82  4451.5  356.18  4461.5  356.17  4499.5  351.73  4531.7  349.24
  4581.8  346.56  4611.9  346.25    4652  344.69  4742.3  338.17  4777.5  336.41
  4812.5  336.59  4832.5  334.86  4882.6  333.09  5110.2  332.74    5113  332.24
  5116.2  332.74  5133.3  333.15  5143.3  334.98  5153.4  336.44  5163.4  339.82
  5173.4   341.3  5194.5  341.94  5203.5     341  5263.6  338.52  5424.1  337.55
  5524.3   334.9  5544.4  335.09  5614.6  338.14  5694.8  343.79  5756.7  347.02
#Mann= 3 ,-1 , 0
  4442.5     .05       0  5110.2    .033       0  5116.2     .05       0
Bank Sta=4832.5,5143.3
XS Rating Curve= 0 ,0
Exp/Cntr=0.3,0.1

Type RM Length L Ch R = 1 ,23280   ,453,453,453
BEGIN DESCRIPTION:
PRAIRIE CREEK 44.0
END DESCRIPTION:
XS GIS Cut Line= 3
      3610749.65     10658860.19      3611299.61     10658810.19
      3612099.63     10658560.18
#Sta/Elev= 30
  4452.5  357.86  4462.5   357.8  4557.3  346.39  4643.2   340.3  4683.4  340.56
  4723.6  338.62  4765.3  340.38    4824  341.22  4844.1  339.33  4864.2  335.17
  4924.4  333.36  4941.5  331.23  4944.2  330.73  4947.5  331.23  5015.2  331.23
    5021  333.62  5026.2  331.23  5036.2  333.52  5053.4  337.71  5078.1  340.34
  5085.9  342.78  5109.5  343.04  5123.6  342.88  5182.8  336.85  5308.6  336.07
  5413.3  331.91  5453.7  331.96  5594.1   337.9  5756.4  347.95  5842.9  350.65
#Mann= 5 ,-1 , 0
  4452.5     .05       0  4557.3     .16       0  4765.3     .05       0
  4941.5    .033       0  4947.5     .05       0
Bank Sta=4924.4,5036.2
XS Rating Curve= 0 ,0
Exp/Cntr=0.3,0.1

Type RM Length L Ch R = 1 ,22827   ,578,578,578
BEGIN DESCRIPTION:
PRAIRIE CREEK 43.0
END DESCRIPTION:
XS GIS Cut Line= 2
      3611204.03      10659435.3      3612285.97     10658609.97
#Sta/Elev= 30
  4489.7  344.57  4533.8   343.1  4647.8  342.78  4692.9  343.59  4774.9   342.5
    4804  343.72  4903.8  341.74  4947.4  336.35  4968.2  332.08  4982.7  329.58
    4989   326.5  4994.3  326.28    4997  325.78  5000.3  326.28  5011.8  327.88
  5018.1  330.38  5032.6  331.82  5053.4  334.09    5068  333.38  5075.3  332.49
  5082.5  330.02    5097  329.07  5161.5  328.74  5232.2  331.63  5325.6  336.93
    5440  340.33  5531.5  345.35  5595.9  346.61  5660.3  350.53  5850.5  353.94
#Mann= 5 ,-1 , 0
  4489.7     .05       0  4647.8     .16       0  4692.9     .05       0
  4994.3     .03       0  5000.3     .05       0
Bank Sta=4968.2,5032.6
XS Rating Curve= 0 ,0
Exp/Cntr=0.3,0.1

Type RM Length L Ch R = 1 ,22249   ,782,782,782
BEGIN DESCRIPTION:
PRAIRIE CREEK 42.0
END DESCRIPTION:
XS GIS Cut Line= 2
      3611676.25     10659900.57       3612627.6     10658768.67
#Sta/Elev= 30
  4402.3  338.54    4519  332.34  4611.3  331.53    4675  329.54  4753.1  330.09
  4794.8   331.7  4816.8  331.22  4937.8   334.3  4951.4   333.4  4972.9  330.36
  4979.5  328.09  4987.2  325.01  4998.5   323.5  5001.3     323  5004.5   323.5
  5015.8  324.59  5029.8  327.64  5036.7  331.12  5043.2  332.87  5065.3  335.59
  5079.6   335.7  5093.9  334.82  5100.4  333.52    5129  335.24  5221.4  337.31
    5462  345.74  5625.9  350.06  5746.8  352.12  5824.9  351.84  5880.9  353.37
#Mann= 3 ,-1 , 0
  4402.3     .05       0  4998.5     .03       0  5004.5     .05       0
Bank Sta=4979.5,5029.8
XS Rating Curve= 0 ,0
Exp/Cntr=0.3,0.1

Type RM Length L Ch R = 1 ,21467   ,407,407,407
BEGIN DESCRIPTION:
PRAIRIE CREEK 40.0
END DESCRIPTION:
XS GIS Cut Line= 3
      3612106.81     10660400.57      3612606.79     10659845.03
      3612870.68     10658865.86
#Sta/Elev= 30
  4459.3  335.27  4558.8  333.23    4610  330.86  4674.3  331.23    4752  329.53
  4772.9  327.99  4825.4  327.92    4915  326.36  4943.4  323.49  4964.3  319.43
  4996.4  314.97  4999.2  314.47  5002.4  314.97  5013.6  315.37  5035.3  319.82
  5056.2  323.13  5176.6  325.52  5325.6  331.56  5346.3  334.11  5367.1  332.74
    5481  332.72  5506.3  335.32  5615.6  338.12  5620.9  339.18  5729.6  343.31
  5750.3  345.38  5836.8  345.04  5937.3  344.25  5964.7  347.78  6220.8  349.31
#Mann= 7 ,-1 , 0
  4459.3     .05       0  4558.8     .16       0  4825.4     .05       0
  4996.4     .03       0  5002.4     .05       0  5836.8      .1       0
  5937.3     .05       0
Bank Sta=4964.3,5035.3
XS Rating Curve= 0 ,0
Exp/Cntr=0.3,0.1

Type RM Length L Ch R = 1 ,21060   ,368,368,368
BEGIN DESCRIPTION:
PRAIRIE CREEK 39.0
END DESCRIPTION:
XS GIS Cut Line= 3
      3612349.86     10660699.18       3612842.9     10660178.37
      3613502.62      10658900.6
#Sta/Elev= 30
  4493.7  330.58  4804.1  321.75  4938.4  314.71  4966.7  313.01  4992.1  308.85
  4994.8  308.35  4998.1  308.85  5044.4  314.57  5094.2  317.07    5186  317.22
  5265.1  324.67  5325.3  327.95  5524.7   333.8  5535.2  333.87  5546.8  330.83
  5591.5  326.14  5607.7   326.7    5652  334.14    5794     337  5928.7  335.86
  6061.6  337.84  6128.1  336.96  6222.3  340.09  6290.2  338.18  6354.8  337.67
  6454.7  338.38  6469.3  341.59  6521.2   344.5  6593.3  352.79  6648.9   356.8
#Mann= 5 ,-1 , 0
  4493.7     .05       0  4992.1     .03       0  4998.1     .05       0
  6290.2     .16       0  6354.8     .05       0
Bank Sta=4938.4,5044.4
XS Rating Curve= 0 ,0
Exp/Cntr=0.3,0.1

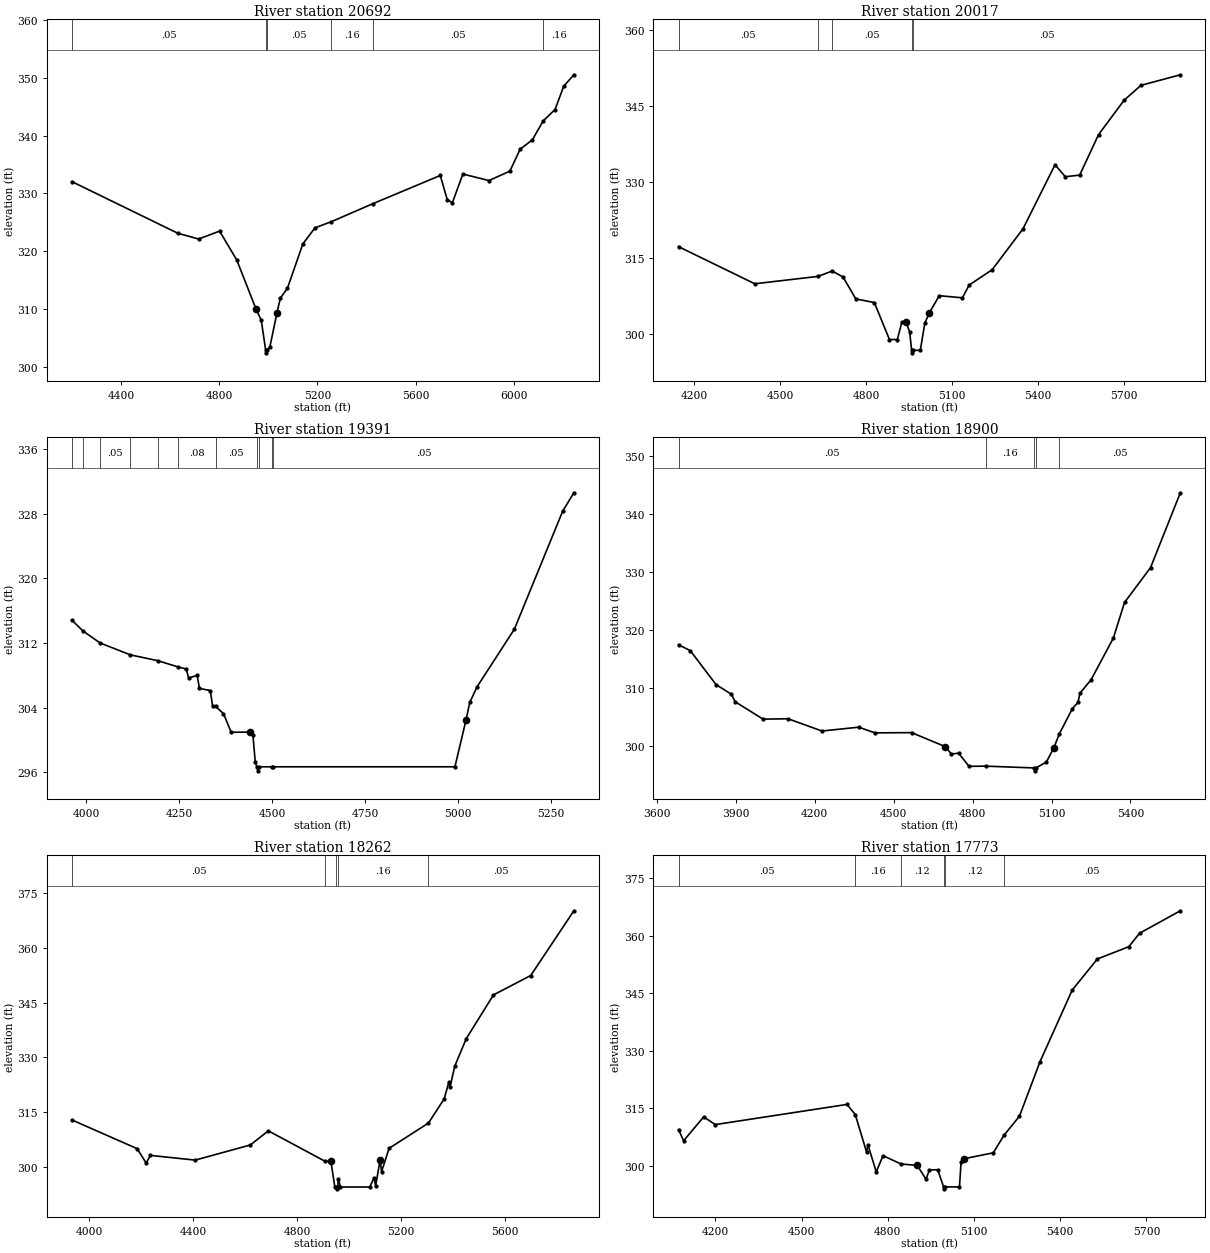
Type RM Length L Ch R = 1 ,20692   ,675,675,675
BEGIN DESCRIPTION:
PRAIRIE CREEK 38.0
END DESCRIPTION:
XS GIS Cut Line= 2
      3612335.93     10661254.79      3613682.24     10659714.15
#Sta/Elev= 30
  4199.3  332.03  4630.4  323.11  4715.3  322.11  4800.8  323.48    4871  318.46
  4949.1  310.02  4970.7  308.05  4988.6  302.91  4991.3  302.41  4994.6  302.91
  5005.8  303.42  5034.3  309.25  5048.5  311.87    5077  313.55  5140.6  321.29
  5189.9  324.05  5255.9   325.1  5425.4  328.22  5700.6  333.11  5729.1  328.92
    5750  328.39  5792.7  333.36    5899  332.23  5984.4  333.86  6026.2  337.65
  6076.5   339.3  6120.1  342.55  6168.6  344.53  6203.7  348.54  6245.3  350.54
#Mann= 6 ,-1 , 0
  4199.3     .05       0  4988.6     .03       0  4994.6     .05       0
  5255.9     .16       0  5425.4     .05       0  6120.1     .16       0
Bank Sta=4949.1,5034.3
XS Rating Curve= 0 ,0
Exp/Cntr=0.3,0.1

Type RM Length L Ch R = 1 ,20017   ,626,626,626
BEGIN DESCRIPTION:
PRAIRIE CREEK 36.0
END DESCRIPTION:
XS GIS Cut Line= 2
      3613051.23     10661615.86      3613932.25     10660103.57
#Sta/Elev= 30
  4145.7  317.21  4411.7  309.86  4631.9  311.32  4681.6  312.38  4719.4  311.21
    4764  306.86  4828.6  306.15  4881.4  298.82  4908.8  298.83  4924.5  302.23
  4939.2  302.31  4951.8  300.32  4958.8  296.69  4961.5  296.19  4964.8  296.69
    4989  296.69  5004.8  302.09  5020.3  304.07    5055   307.5    5136  307.08
  5159.1   309.6  5239.7  312.65  5347.2  320.75  5458.9  333.42  5494.8  331.05
  5544.9  331.37  5610.5  339.37  5699.6  346.18  5758.3  349.13  5895.9  351.23
#Mann= 5 ,-1 , 0
  4145.7     .05       0  4631.9     .08       0  4681.6     .05       0
  4958.8     .03       0  4964.8     .05       0
Bank Sta=4939.2,5020.3
XS Rating Curve= 0 ,0
Exp/Cntr=0.3,0.1

Type RM Length L Ch R = 1 ,19391   ,491,491,491
BEGIN DESCRIPTION:
PRAIRIE CREEK 35.0
END DESCRIPTION:
XS GIS Cut Line= 3
      3613299.59      10661560.2      3614099.61     10660960.19
      3614099.61     10660610.21
#Sta/Elev= 30
  3961.7   314.8    3991  313.48  4037.1     312  4118.5  310.53  4192.4  309.81
  4245.9  309.05    4269  308.78  4275.3  307.66  4298.2     308  4304.4  306.38
  4333.6  306.12  4339.8  304.19  4347.8  304.15    4369  303.27  4389.8  300.96
  4439.8  300.98  4448.2  300.64  4454.4  297.34  4458.7  296.69  4461.5  296.19
  4464.7  296.69  4500.7  296.69  4503.1  296.69  4991.7  296.69  5021.7   302.5
  5031.7  304.66  5051.7  306.61  5151.7  313.71  5281.7   328.3  5311.7  330.57
#Mann= 11 ,-1 , 0
  3961.7     .05       0    3991     .08       0  4037.1     .05       0
  4118.5     .08       0  4192.4     .05       0  4245.9     .08       0
  4347.8     .05       0  4458.7     .03       0  4464.7     .05       0
  4500.7     .08       0  4503.1     .05       0
Bank Sta=4439.8,5021.7
XS Rating Curve= 0 ,0
Exp/Cntr=0.3,0.1

Type RM Length L Ch R = 1 ,18900   ,638,638,638
BEGIN DESCRIPTION:
PRAIRIE CREEK 34.0
END DESCRIPTION:
XS GIS Cut Line= 3
      3613249.63     10661860.18      3614449.61     10661260.19
      3614849.61     10660860.19
#Sta/Elev= 30
  3682.2  317.49  3726.9  316.47  3824.7  310.62  3883.4  308.94  3897.4  307.65
  4003.6  304.66  4098.6  304.72  4227.2  302.61    4367  303.27  4428.5  302.29
  4568.2  302.33  4696.8   299.9  4719.1  298.65  4747.1  298.78  4786.2  296.52
  4849.9  296.55    5035  296.24  5037.7  295.74    5041  296.24  5080.4  297.27
  5108.7   299.7  5129.6  302.12  5179.4  306.49  5200.6  307.54  5207.7  309.11
  5250.1  311.44  5334.9  318.63  5377.4  324.78  5476.4   330.8  5589.5   343.7
#Mann= 5 ,-1 , 0
  3682.2     .05       0  4849.9     .16       0    5035     .07       0
    5041     .16       0  5129.6     .05       0
Bank Sta=4696.8,5108.7
XS Rating Curve= 0 ,0
Exp/Cntr=0.3,0.1

Type RM Length L Ch R = 1 ,18262   ,489,489,489
BEGIN DESCRIPTION:
PRAIRIE CREEK 33.0
END DESCRIPTION:
XS GIS Cut Line= 2
      3613620.64     10662331.16      3615376.11     10661526.28
#Sta/Elev= 30
  3933.8  312.85  4184.1     305  4218.7  301.08  4235.6  303.15  4407.6  301.86
  4620.1  306.01  4689.1  309.88  4907.5  301.54  4930.1   301.5  4944.8  294.59
  4950.1  294.49  4952.8  293.99  4956.1  294.49  4958.6  296.68  4966.8  294.49
  5079.1  294.49  5096.5  297.02    5102  294.77  5119.5  301.98    5125   298.7
  5153.8  305.09  5305.2     312    5366  318.64  5383.5  323.16    5389  322.02
  5406.5  327.59  5450.8  335.12  5555.5  347.12    5699  352.43    5865  370.17
#Mann= 5 ,-1 , 0
  3933.8     .05       0  4907.5     .16       0  4950.1     .07       0
  4956.1     .16       0  5305.2     .05       0
Bank Sta=4930.1,5119.5
XS Rating Curve= 0 ,0
Exp/Cntr=0.3,0.1

Type RM Length L Ch R = 1 ,17773   ,504,504,504
BEGIN DESCRIPTION:
PRAIRIE CREEK 32.0
END DESCRIPTION:
XS GIS Cut Line= 2
      3613863.75     10662497.81      3615578.98     10662171.43
#Sta/Elev= 30
  4072.1  309.45  4089.7  306.53  4159.5  312.76  4200.2  310.76  4658.3  316.02
  4687.1  313.37  4726.3  303.59  4731.3  305.45  4760.1  298.39  4783.5  302.65
  4846.4  300.47  4902.6  300.11  4933.1   296.5  4945.2  298.94  4973.9  298.97
  4994.4  294.49  4997.2  293.99  5000.4  294.49  5049.6  294.49  5055.3     301
  5065.5  301.85  5167.3  303.39  5204.4  307.95  5258.4  312.96  5330.1  327.22
  5442.1  345.89  5529.6  353.99    5639  357.19  5676.2  360.69  5818.1  366.56
#Mann= 6 ,-1 , 0
  4072.1     .05       0  4687.1     .16       0  4846.4     .12       0
  4994.4     .07       0  5000.4     .12       0  5204.4     .05       0
Bank Sta=4902.6,5065.5
XS Rating Curve= 0 ,0
Exp/Cntr=0.3,0.1

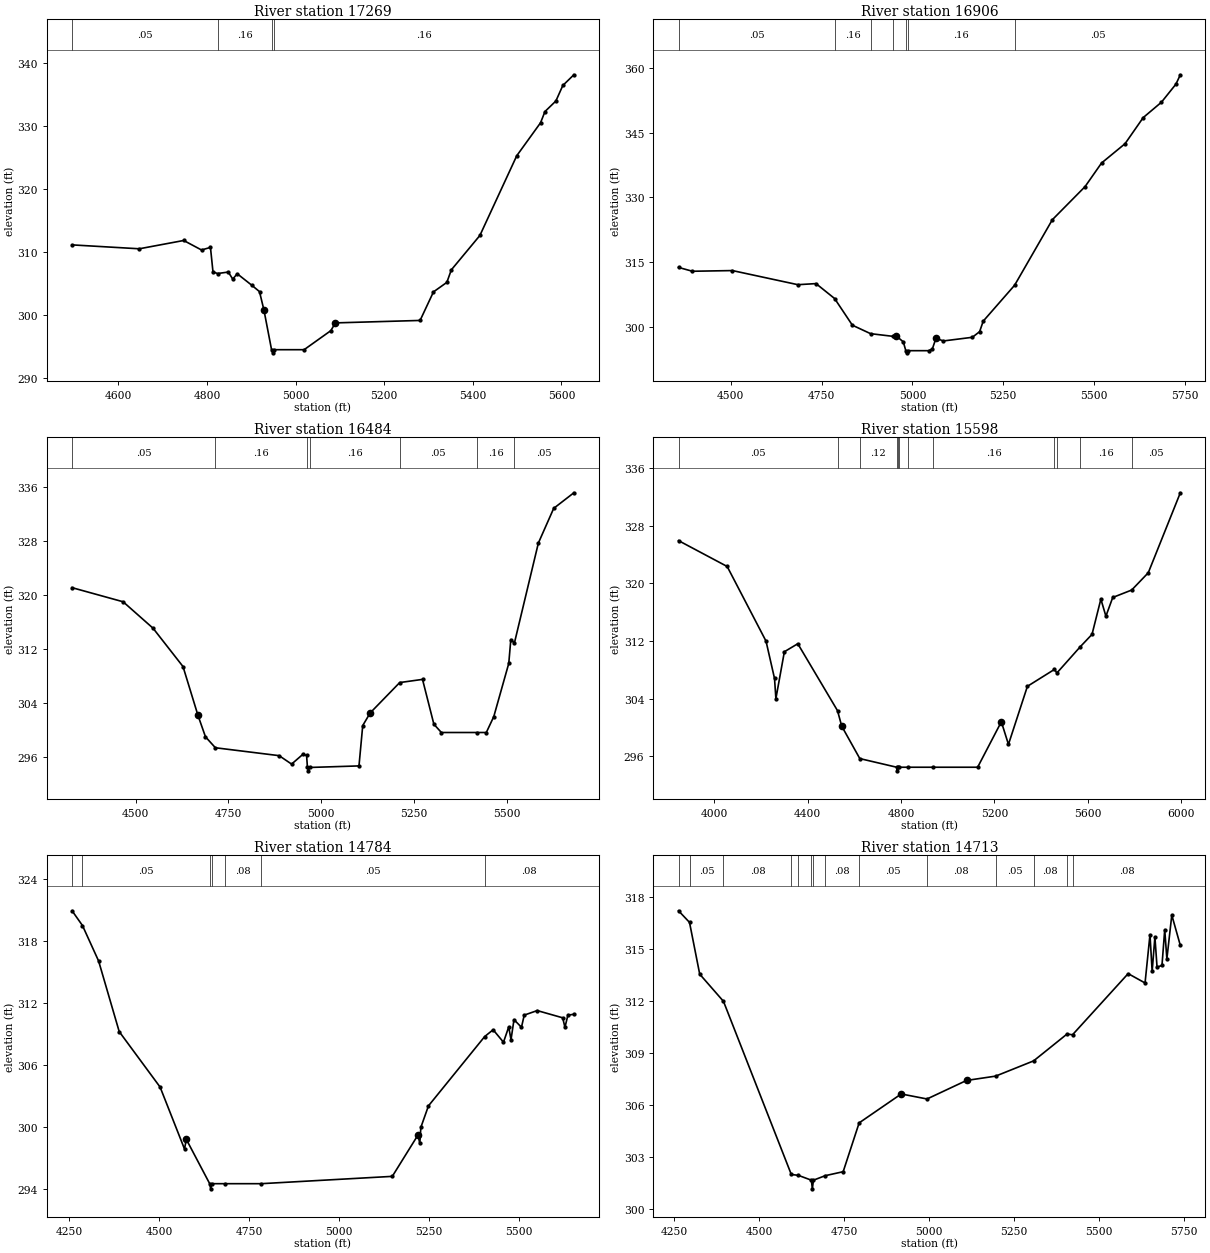
Type RM Length L Ch R = 1 ,17269   ,363,363,363
BEGIN DESCRIPTION:
PRAIRIE CREEK 30.0
END DESCRIPTION:
XS GIS Cut Line= 2
      3614039.35     10662678.05      3615164.34     10662809.99
#Sta/Elev= 30
  4495.3  311.15    4647  310.53  4747.3  311.85  4787.5  310.34  4807.7  310.75
  4813.4  306.85  4823.8   306.6    4848  306.83    4858  305.71  4868.1  306.56
  4901.6   304.7  4918.4  303.72  4928.5  300.76  4945.6  294.49  4948.4  293.99
  4951.6  294.49  5019.1  294.49  5079.5  297.52  5089.6  298.75  5280.9  299.14
  5311.1  303.68  5341.3  305.19  5351.4  307.18  5415.9  312.65  5499.1  325.32
  5552.8  330.56  5562.8  332.35  5587.4  334.02  5603.1  336.49    5628  338.19
#Mann= 4 ,-1 , 0
  4495.3     .05       0  4823.8     .16       0  4945.6     .07       0
  4951.6     .16       0
Bank Sta=4928.5,5089.6
XS Rating Curve= 0 ,0
Exp/Cntr=0.3,0.1

Type RM Length L Ch R = 1 ,16906   ,422,422,422
BEGIN DESCRIPTION:
PRAIRIE CREEK 29.0
END DESCRIPTION:
XS GIS Cut Line= 2
      3614021.43     10663077.15      3615401.69     10663051.11
#Sta/Elev= 30
  4356.5  313.78  4394.7  312.89  4504.7  313.05  4684.7  309.78  4734.7  310.03
  4785.9  306.57  4834.8  300.39  4884.9  298.43  4947.8   297.8  4954.8  297.95
  4974.8  296.54  4981.8  294.49  4984.5  293.99  4987.8  294.49  5044.8  294.49
  5054.8   294.9  5064.8  297.38  5084.8  296.74  5164.8  297.59  5184.8   298.9
  5194.8  301.34  5281.1  309.65  5384.9  324.83  5474.9   332.5  5520.3  337.97
  5584.9  342.44  5634.9  348.49  5684.9  352.04  5724.9  356.24    5737  358.41
#Mann= 7 ,-1 , 0
  4356.5     .05       0  4785.9     .16       0  4884.9     .12       0
  4947.8     .16       0  4981.8     .07       0  4987.8     .16       0
  5281.1     .05       0
Bank Sta=4954.8,5064.8
XS Rating Curve= 0 ,0
Exp/Cntr=0.3,0.1

Type RM Length L Ch R = 1 ,16484   ,886,886,886
BEGIN DESCRIPTION:
PRAIRIE CREEK 28.0
END DESCRIPTION:
XS GIS Cut Line= 2
      3614053.28     10663393.33      3615393.49     10663566.94
#Sta/Elev= 30
    4329  321.13  4466.5  319.04  4547.1  315.12  4627.8  309.44  4668.1   302.2
  4688.3  299.03    4715  297.41  4886.6  296.24  4920.2  294.99  4950.5  296.43
  4960.6  296.27  4962.9  294.49  4965.6  293.99  4968.9  294.49  5101.7  294.72
  5111.8   300.7    5132  302.58  5211.4  307.07  5272.8  307.54  5303.4   300.9
  5323.6  299.67    5419  299.67  5444.6  299.67  5464.7  302.02  5505.1  309.91
  5510.6  313.44  5520.3  312.93  5584.8  327.74  5626.1  332.88  5680.4  335.19
#Mann= 7 ,-1 , 0
    4329     .05       0    4715     .16       0  4962.9     .07       0
  4968.9     .16       0  5211.4     .05       0    5419     .16       0
  5520.3     .05       0
Bank Sta=4668.1,5132
XS Rating Curve= 0 ,0
Exp/Cntr=0.3,0.1

Type RM Length L Ch R = 1 ,15598   ,814,814,814
BEGIN DESCRIPTION:
PRAIRIE CREEK 27.0
END DESCRIPTION:
XS GIS Cut Line= 3
      3613641.29     10663681.34        3614485.     10664222.98
      3615614.89     10664420.85
#Sta/Elev= 30
  3846.4  325.94  4054.8  322.35  4221.2  311.99  4257.6  306.81  4263.5  304.02
  4299.8  310.52  4357.3  311.63  4527.5  302.34  4545.5  300.19    4623  295.69
  4781.1  294.49  4783.8  293.99  4787.1  294.49    4793  294.49  4828.7  294.49
  4934.6  294.49  5127.8  294.49  5229.3   300.8  5259.8  297.66    5341  305.72
    5457  308.07  5467.3  307.57  5567.1   311.2  5617.8  312.93  5655.7  317.82
  5677.3  315.45  5706.5  318.05  5787.6  319.08  5858.8  321.48  5996.1  332.58
#Mann= 12 ,-1 , 0
  3846.4     .05       0  4527.5     .16       0    4623     .12       0
  4781.1     .07       0  4787.1     .12       0    4793     .16       0
  4828.7     .12       0  4934.6     .16       0    5457     .05       0
  5467.3     .08       0  5567.1     .16       0  5787.6     .05       0
Bank Sta=4545.5,5229.3
XS Rating Curve= 0 ,0
Exp/Cntr=0.3,0.1

Type RM Length L Ch R = 1 ,14784   ,71,71,71
BEGIN DESCRIPTION:
PRAIRIE CREEK 25.0
END DESCRIPTION:
XS GIS Cut Line= 5
      3613556.24      10665039.8      3614341.87     10664952.99
      3614519.82     10664913.93      3614706.45     10664827.12
      3614880.03     10664696.94
#Sta/Elev= 30
  4257.9  320.96  4286.8  319.53  4331.7  316.09    4389  309.24  4502.7  303.86
  4570.6  297.85  4575.6  298.79  4640.6  294.49  4643.4  293.99  4646.6  294.49
  4683.9  294.49  4783.9  294.49  5148.4   295.2  5219.8  299.21  5224.9  298.39
  5227.8  299.95    5249  302.04  5405.3  308.76  5428.8  309.42  5457.6  308.21
  5472.2   309.7  5478.5  308.45  5486.8   310.4  5507.6  309.66  5515.3  310.84
  5551.4  311.28  5622.2  310.58  5628.5  309.66  5636.8  310.84  5653.3  310.92
#Mann= 7 ,-1 , 0
  4257.9     .16       0  4286.8     .05       0  4640.6     .03       0
  4646.6     .05       0  4683.9     .08       0  4783.9     .05       0
  5405.3     .08       0
Bank Sta=4575.6,5219.8
XS Rating Curve= 0 ,0
Exp/Cntr=0.3,0.1

Type RM Length L Ch R = 1 ,14713   ,43,43,43
BEGIN DESCRIPTION:
PRAIRIE CREEK 26.0
END DESCRIPTION:
XS GIS Cut Line= 6
       3613547.6     10665100.56      3614294.12     10665026.78
      3614459.06     10664996.39      3614597.94     10664935.63
       3614775.9      10664835.8      3614935.58     10664710.65
#Sta/Elev= 30
  4263.1  317.23  4295.4  316.56  4325.4  313.57  4395.3     312  4594.9     302
  4615.4  301.95    4654  301.67  4656.8  301.17    4660  301.67  4694.7  301.93
  4747.5  302.16  4794.5  304.98  4918.3  306.65  4994.2  306.36  5110.4  307.43
  5196.1  307.68  5307.8  308.56  5406.1  310.11  5422.4  310.07    5586   313.6
  5635.7  313.06  5650.2  315.85  5656.6  313.73  5664.7  315.72    5671  313.98
  5685.5  314.07  5693.6  316.14  5699.9  314.45  5714.4  316.98  5739.5  315.23
#Mann= 14 ,-1 , 0
  4263.1     .08       0  4295.4     .05       0  4395.3     .08       0
  4594.9      .1       0  4615.4     .05       0    4654     .07       0
    4660     .05       0  4694.7     .08       0  4794.5     .05       0
  4994.2     .08       0  5196.1     .05       0  5307.8     .08       0
  5406.1     .05       0  5422.4     .08       0
Bank Sta=4918.3,5110.4
XS Rating Curve= 0 ,0
Exp/Cntr=0.3,0.1

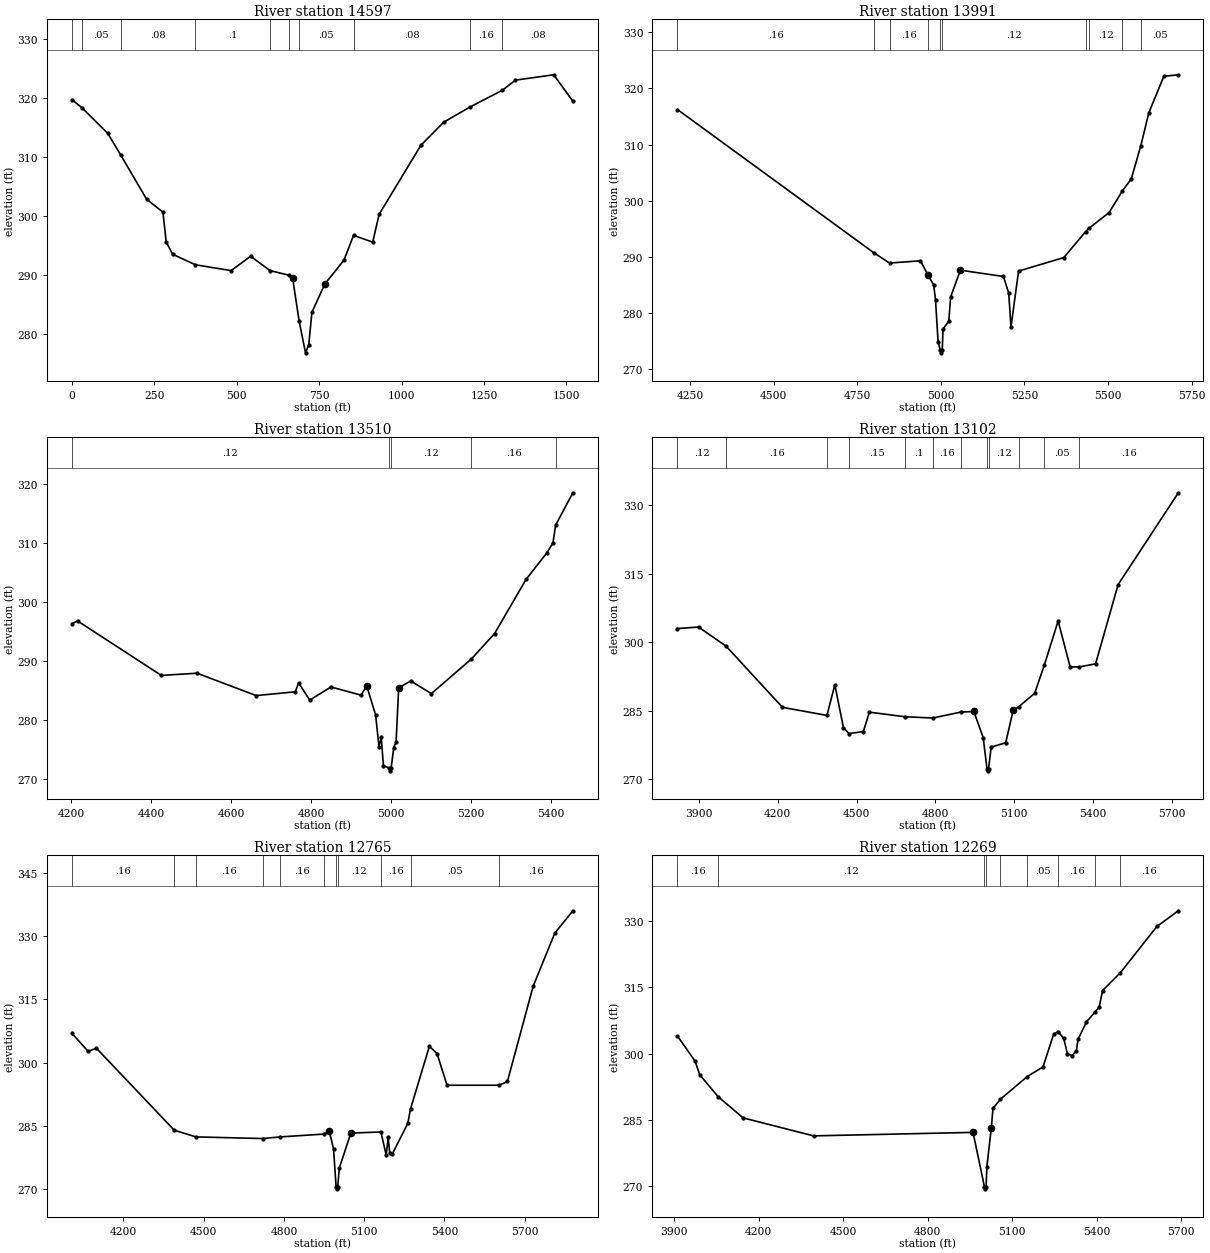
Type RM Length L Ch R = 1 ,14597   ,679,679,679
BEGIN DESCRIPTION:
PRAIRIE CREEK 24.0
END DESCRIPTION:
XS GIS Cut Line= 4
      3613557.64     10665145.32       3614555.9     10665041.15
      3614824.99     10664897.92      3614975.77     10664777.31
#Sta/Elev= 30
       0  319.76   29.55  318.44  108.36  314.08  147.76  310.41  226.56  302.89
  275.82  300.73  285.67  295.69  305.37  293.59  374.32  291.81  482.68  290.82
  541.78  293.25  600.89  290.82  659.75  290.02  669.48  289.49  688.94   282.3
   708.4  276.89  718.13  278.22  727.85  283.77  766.77  288.53  825.02  292.59
  854.11  296.79  912.29  295.64  931.69  300.35 1058.38  312.05 1127.71  315.97
 1206.95  318.52 1306.01  321.39  1345.2  323.09  1461.5     324 1519.64  319.51
#Mann= 10 ,-1 , 0
       0     .08       0   29.55     .05       0  147.76     .08       0
  374.32      .1       0  600.89     .05       0  659.75     .04       0
  688.94     .05       0  854.11     .08       0 1206.95     .16       0
 1306.01     .08       0
Bank Sta=669.48,766.77
XS Rating Curve= 0 ,0
Exp/Cntr=0.3,0.1

Type RM Length L Ch R = 1 ,13991   ,481,481,481
BEGIN DESCRIPTION:
PRAIRIE CREEK 23.0
END DESCRIPTION:
XS GIS Cut Line= 3
      3613436.13     10665466.51      3614082.81     10665718.24
      3614806.17     10665367.39
#Sta/Elev= 30
  4212.4  316.24  4799.1  290.77  4846.6  288.92    4939  289.32  4961.5  286.78
  4961.8  286.76  4978.6  285.02  4984.1  282.35  4991.7   274.9  4998.1  273.44
  5000.9  272.94  5004.1  273.44  5006.7   277.2  5023.7  278.58  5029.3  282.88
  5058.4  287.65  5187.3  286.53  5202.9  283.58  5209.8  277.54  5232.4  287.49
  5367.8   289.9  5432.6  294.48  5442.6  295.09    5503  297.89  5542.1  301.69
  5569.6  303.92    5598   309.8  5621.7  315.62  5666.8  322.16  5710.3  322.43
#Mann= 10 ,-1 , 0
  4212.4     .16       0  4799.1     .12       0  4846.6     .16       0
  4961.8     .12       0  4998.1     .07       0  5004.1     .12       0
  5432.6     .16       0  5442.6     .12       0  5542.1     .16       0
    5598     .05       0
Bank Sta=4961.5,5058.4
XS Rating Curve= 0 ,0
Exp/Cntr=0.3,0.1

Type RM Length L Ch R = 1 ,13510   ,408,408,408
BEGIN DESCRIPTION:
PRAIRIE CREEK 22.0
END DESCRIPTION:
XS GIS Cut Line= 3
       3614199.6     10666610.21      3614549.61     10665910.19
      3614799.59     10665510.23
#Sta/Elev= 30
  4201.4  296.34  4215.4  296.77    4425  287.55  4514.5  287.92  4662.6  284.13
  4760.4  284.77  4768.8  286.26  4796.8  283.37  4849.9  285.59  4925.3   284.2
  4939.3  285.79  4961.7  280.84  4970.1  275.43  4975.7  277.06  4981.2  272.26
  4994.6  271.88  4997.4  271.38  5000.6  271.88    5007  275.29  5012.9  276.25
  5019.4  285.45  5049.5   286.6  5101.4  284.47  5201.6  290.34  5259.4  294.62
  5338.4  303.81  5390.3   308.3  5405.6  309.96  5412.6  313.04  5455.7  318.49
#Mann= 5 ,-1 , 0
  4201.4     .12       0  4994.6     .07       0  5000.6     .12       0
  5201.6     .16       0  5412.6     .05       0
Bank Sta=4939.3,5019.4
XS Rating Curve= 0 ,0
Exp/Cntr=0.3,0.1

Type RM Length L Ch R = 1 ,13102   ,337,337,337
BEGIN DESCRIPTION:
PRAIRIE CREEK 21.0
END DESCRIPTION:
XS GIS Cut Line= 2
      3614443.33     10667062.83      3615250.27     10665334.42
#Sta/Elev= 30
  3818.2  303.02  3898.4  303.35  4003.4  299.15    4218  285.75  4387.4  283.98
  4417.4   290.7  4450.2  281.31  4471.6  279.99  4526.1  280.45    4549  284.69
  4684.2  283.69  4790.4  283.41  4896.7   284.7  4946.8  284.85  4982.5  279.09
  4996.8  272.33  4999.6  271.83  5002.8  272.33    5013  277.03  5068.2  277.99
  5096.7  285.11  5117.1  285.85  5178.6  288.84  5215.5  295.04  5267.8  304.67
  5313.5  294.62  5348.7  294.62  5410.4  295.28  5496.3  312.66  5725.7  332.78
#Mann= 12 ,-1 , 0
  3818.2     .12       0  4003.4     .16       0  4387.4     .12       0
  4471.6     .15       0  4684.2      .1       0  4790.4     .16       0
  4896.7     .12       0  4996.8     .07       0  5002.8     .12       0
  5117.1     .16       0  5215.5     .05       0  5348.7     .16       0
Bank Sta=4946.8,5096.7
XS Rating Curve= 0 ,0
Exp/Cntr=0.3,0.1

Type RM Length L Ch R = 1 ,12765   ,496,496,496
BEGIN DESCRIPTION:
PRAIRIE CREEK 20.0
END DESCRIPTION:
XS GIS Cut Line= 2
      3614625.62     10667099.29      3615557.64     10665474.76
#Sta/Elev= 30
  4007.8  306.89  4068.1  302.66    4099  303.39  4390.3  283.96  4471.2  282.38
  4720.7  281.99  4784.4  282.37  4948.5  283.04  4969.9  283.69  4985.7  279.52
  4995.2  270.57    4998  270.07  5001.2  270.57  5007.3  275.01  5050.4  283.28
  5162.9  283.55  5182.7     278  5189.9  282.26  5195.7  278.64  5205.7  278.37
  5263.4  285.59  5273.5  289.02  5344.1  303.85  5372.6  302.14    5410  294.62
  5605.2  294.62  5635.8  295.51  5732.1  318.08  5812.7  330.64  5880.7  335.97
#Mann= 11 ,-1 , 0
  4007.8     .16       0  4390.3     .12       0  4471.2     .16       0
  4720.7     .08       0  4784.4     .16       0  4948.5     .12       0
  4995.2     .07       0  5001.2     .12       0  5162.9     .16       0
  5273.5     .05       0  5605.2     .16       0
Bank Sta=4969.9,5050.4
XS Rating Curve= 0 ,0
Exp/Cntr=0.3,0.1

Type RM Length L Ch R = 1 ,12269   ,520,520,520
BEGIN DESCRIPTION:
PRAIRIE CREEK 19.0
END DESCRIPTION:
XS GIS Cut Line= 2
      3614995.44       10667193.      3615870.43     10665646.13
#Sta/Elev= 30
  3912.4  303.96  3975.2  298.26  3991.1  295.23  4056.2   290.3  4145.4  285.48
  4395.3  281.42  4961.1  282.21  5001.4  269.96  5004.2  269.46  5007.4  269.96
  5010.2  274.48  5026.1   283.3  5031.8  287.61  5057.4  289.65    5153   294.8
  5209.4  296.99  5246.9  304.35  5263.2  304.97  5282.8  303.42    5296  299.96
  5311.9  299.55  5327.8  300.55  5333.5  303.21  5363.2  307.12  5394.5  309.44
  5408.6   310.5  5420.7  314.24  5483.6  318.24  5613.5  328.71  5689.6  332.25
#Mann= 9 ,-1 , 0
  3912.4     .16       0  4056.2     .12       0  5001.4     .07       0
  5007.4     .12       0  5057.4     .16       0    5153     .05       0
  5263.2     .16       0  5394.5     .05       0  5483.6     .16       0
Bank Sta=4961.1,5026.1
XS Rating Curve= 0 ,0
Exp/Cntr=0.3,0.1