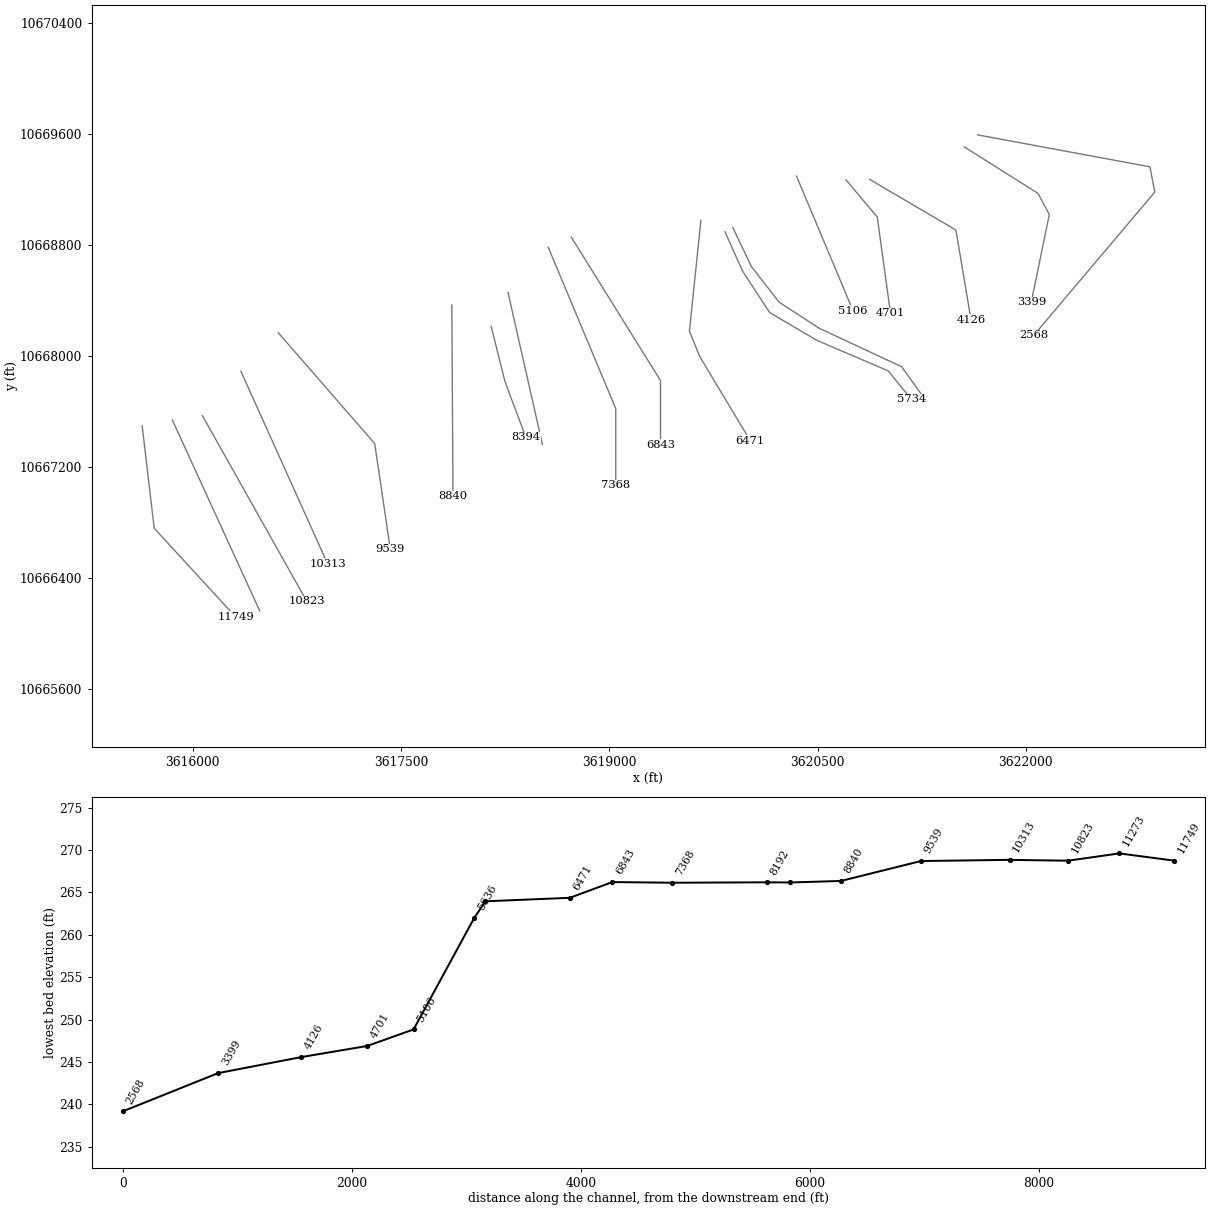
HEC-RAS study PRAIRIE CREEK.prj: PRAIRIE CREEK Base Level Engineering

--- PRAIRIE CREEK.g01 (geometry) --- (continued)

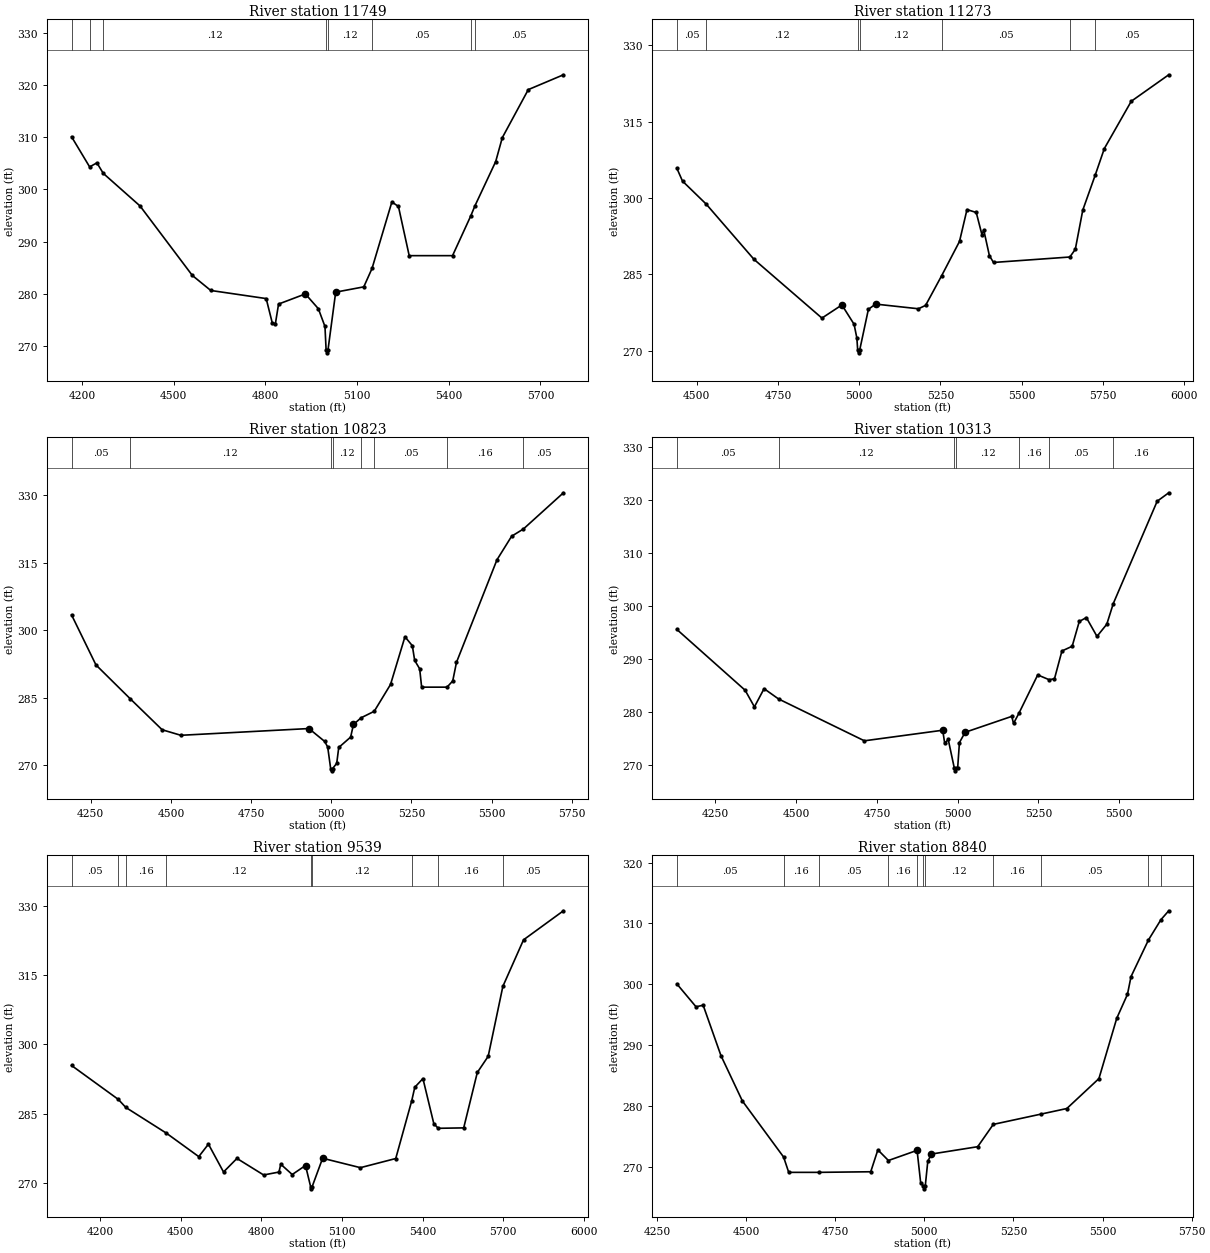
Type RM Length L Ch R = 1 ,11749   ,476,476,476
BEGIN DESCRIPTION:
PRAIRIE CREEK 18.0
END DESCRIPTION:
XS GIS Cut Line= 3
      3615636.04     10667492.51      3615722.85     10666754.67
      3616308.79     10666116.64
#Sta/Elev= 30
    4166  310.08  4225.1  304.32  4248.9  305.09  4269.7  303.08  4389.9  296.85
    4561  283.56  4621.4  280.68  4802.7  279.13  4822.8  274.43  4832.9  274.35
  4843.2  278.08  4930.9  280.02  4973.4  277.19    4995  273.79  4998.8  269.25
  5001.5  268.75  5004.8  269.25  5030.1  280.36    5122  281.37    5149  284.89
  5213.9  297.61  5235.4  296.75  5270.6  287.34  5412.4  287.34  5472.2  294.96
  5485.6  296.86  5553.6  305.34  5575.2  309.91  5660.2   319.1  5775.2  321.94
#Mann= 8 ,-1 , 0
    4166     .05       0  4225.1     .16       0  4269.7     .12       0
  4998.8     .07       0  5004.8     .12       0    5149     .05       0
  5472.2     .16       0  5485.6     .05       0
Bank Sta=4930.9,5030.1
XS Rating Curve= 0 ,0
Exp/Cntr=0.3,0.1

Type RM Length L Ch R = 1 ,11273   ,450,450,450
BEGIN DESCRIPTION:
PRAIRIE CREEK 17.0
END DESCRIPTION:
XS GIS Cut Line= 2
      3615853.05     10667535.93       3616482.4     10666160.03
#Sta/Elev= 30
  4439.1  305.82  4456.4  303.31  4529.2   298.8  4676.3  287.95  4885.3  276.42
  4946.7     279  4984.2  275.21  4992.8  272.48  4995.3   270.1    4998   269.6
  5001.3   270.1  5028.2  278.14  5050.2  279.17  5182.2  278.25  5204.2  278.92
  5253.9  284.78  5308.5  291.47  5331.5  297.72    5360  297.15  5377.5  292.79
    5383  293.73  5400.5  288.66  5413.1  287.34  5647.9  288.41  5664.7  289.92
  5687.7  297.62  5725.8  304.46    5754   309.7  5836.8  318.98  5952.1  324.18
#Mann= 7 ,-1 , 0
  4439.1     .05       0  4529.2     .12       0  4995.3     .07       0
  5001.3     .12       0  5253.9     .05       0  5647.9     .16       0
  5725.8     .05       0
Bank Sta=4946.7,5050.2
XS Rating Curve= 0 ,0
Exp/Cntr=0.3,0.1

Type RM Length L Ch R = 1 ,10823   ,510,510,510
BEGIN DESCRIPTION:
PRAIRIE CREEK 16.0
END DESCRIPTION:
XS GIS Cut Line= 2
      3616070.08     10667566.28      3616820.92     10666229.52
#Sta/Elev= 30
  4190.4  303.39  4266.4  292.28  4372.9  284.78  4472.7  277.87  4531.1  276.64
  4930.2  278.14  4979.3  275.28  4988.8  274.03    4998  269.24  5000.8  268.74
    5004  269.24  5016.9   270.4  5023.2  273.93  5060.3  276.24  5069.1  279.05
  5092.9  280.53  5133.8  281.97  5184.6  287.93  5229.6  298.54  5252.6  296.55
  5259.9  293.28  5275.5  291.41  5281.6  287.34  5360.7  287.34  5378.5  288.71
  5390.2  292.85  5516.4  315.64  5562.1  320.88    5599   322.5  5723.6  330.54
#Mann= 8 ,-1 , 0
  4190.4     .05       0  4372.9     .12       0    4998     .07       0
    5004     .12       0  5092.9     .16       0  5133.8     .05       0
  5360.7     .16       0    5599     .05       0
Bank Sta=4930.2,5069.1
XS Rating Curve= 0 ,0
Exp/Cntr=0.3,0.1

Type RM Length L Ch R = 1 ,10313   ,774,774,774
BEGIN DESCRIPTION:
PRAIRIE CREEK 15.0
END DESCRIPTION:
XS GIS Cut Line= 2
      3616347.12      10667886.4      3616972.11     10666497.54
#Sta/Elev= 30
  4130.5  295.58  4341.9  284.08  4370.6  280.94  4400.5  284.38  4445.2  282.44
  4711.1  274.52  4953.6  276.52  4959.8  274.05  4970.7  274.77  4989.6  269.34
  4992.4  268.84  4995.6  269.34  4999.9  269.37  5005.4  274.18    5023  276.13
  5167.4  279.14  5172.9   277.8  5189.7  279.74  5247.8  286.98    5283  286.08
  5299.7  286.25  5322.8  291.51  5354.5   292.4  5376.5  297.09  5398.4  297.83
  5431.3  294.27  5461.7  296.57  5481.8  300.48  5617.7  319.83  5653.5  321.43
#Mann= 7 ,-1 , 0
  4130.5     .05       0  4445.2     .12       0  4989.6     .07       0
  4995.6     .12       0  5189.7     .16       0    5283     .05       0
  5481.8     .16       0
Bank Sta=4953.6,5023
XS Rating Curve= 0 ,0
Exp/Cntr=0.3,0.1

Type RM Length L Ch R = 1 ,9539    ,699,699,699
BEGIN DESCRIPTION:
PRAIRIE CREEK 14.0
END DESCRIPTION:
XS GIS Cut Line= 3
      3616616.19     10668164.21      3617310.67     10667365.56
      3617423.26      10666603.4
#Sta/Elev= 30
  4094.6  295.39  4268.5  288.05  4296.1  286.32  4446.8  280.76  4567.5  275.67
  4603.5  278.37  4659.6  272.34  4709.5  275.28  4808.7   271.7  4865.7  272.33
  4872.3  274.03    4915   271.8  4964.4  273.75  4983.3   269.2    4986   268.7
  4989.3   269.2    5028  275.32  5168.5  273.28  5299.9  275.26  5359.2  287.72
  5370.7  290.68    5401  292.56  5441.4  282.82  5457.7   281.8  5552.6  281.89
  5603.2  293.88  5643.6  297.37  5698.2  312.51    5775  322.58  5923.4  328.87
#Mann= 9 ,-1 , 0
  4094.6     .05       0  4268.5     .12       0  4296.1     .16       0
  4446.8     .12       0  4983.3     .07       0  4989.3     .12       0
  5359.2     .05       0  5457.7     .16       0  5698.2     .05       0
Bank Sta=4964.4,5028
XS Rating Curve= 0 ,0
Exp/Cntr=0.3,0.1

Type RM Length L Ch R = 1 ,8840    ,446,446,446
BEGIN DESCRIPTION:
PRAIRIE CREEK 12.0
END DESCRIPTION:
XS GIS Cut Line= 2
      3617866.22     10668363.86       3617874.9     10666984.39
#Sta/Elev= 30
  4306.2  300.05  4359.9  296.29  4379.9  296.55  4429.9  288.25  4489.9   280.8
  4605.5  271.58  4619.9  269.06  4703.5  269.06  4849.9  269.16  4869.9  272.76
  4899.5  271.01  4979.9  272.68  4980.2  272.52  4989.9  267.37  4996.9  266.85
  4999.6  266.35  5002.9  266.85  5009.9  270.86  5019.9  272.07  5149.9  273.28
  5193.6  276.95  5326.6  278.63  5399.9  279.56  5489.9  284.48  5539.9   294.4
  5569.9  298.33  5579.9  301.25  5628.8  307.28  5663.9  310.62  5685.7  312.08
#Mann= 11 ,-1 , 0
  4306.2     .05       0  4605.5     .16       0  4703.5     .05       0
  4899.5     .16       0  4980.2     .12       0  4996.9     .07       0
  5002.9     .12       0  5193.6     .16       0  5326.6     .05       0
  5628.8     .16       0  5663.9     .05       0
Bank Sta=4979.9,5019.9
XS Rating Curve= 0 ,0
Exp/Cntr=0.3,0.1

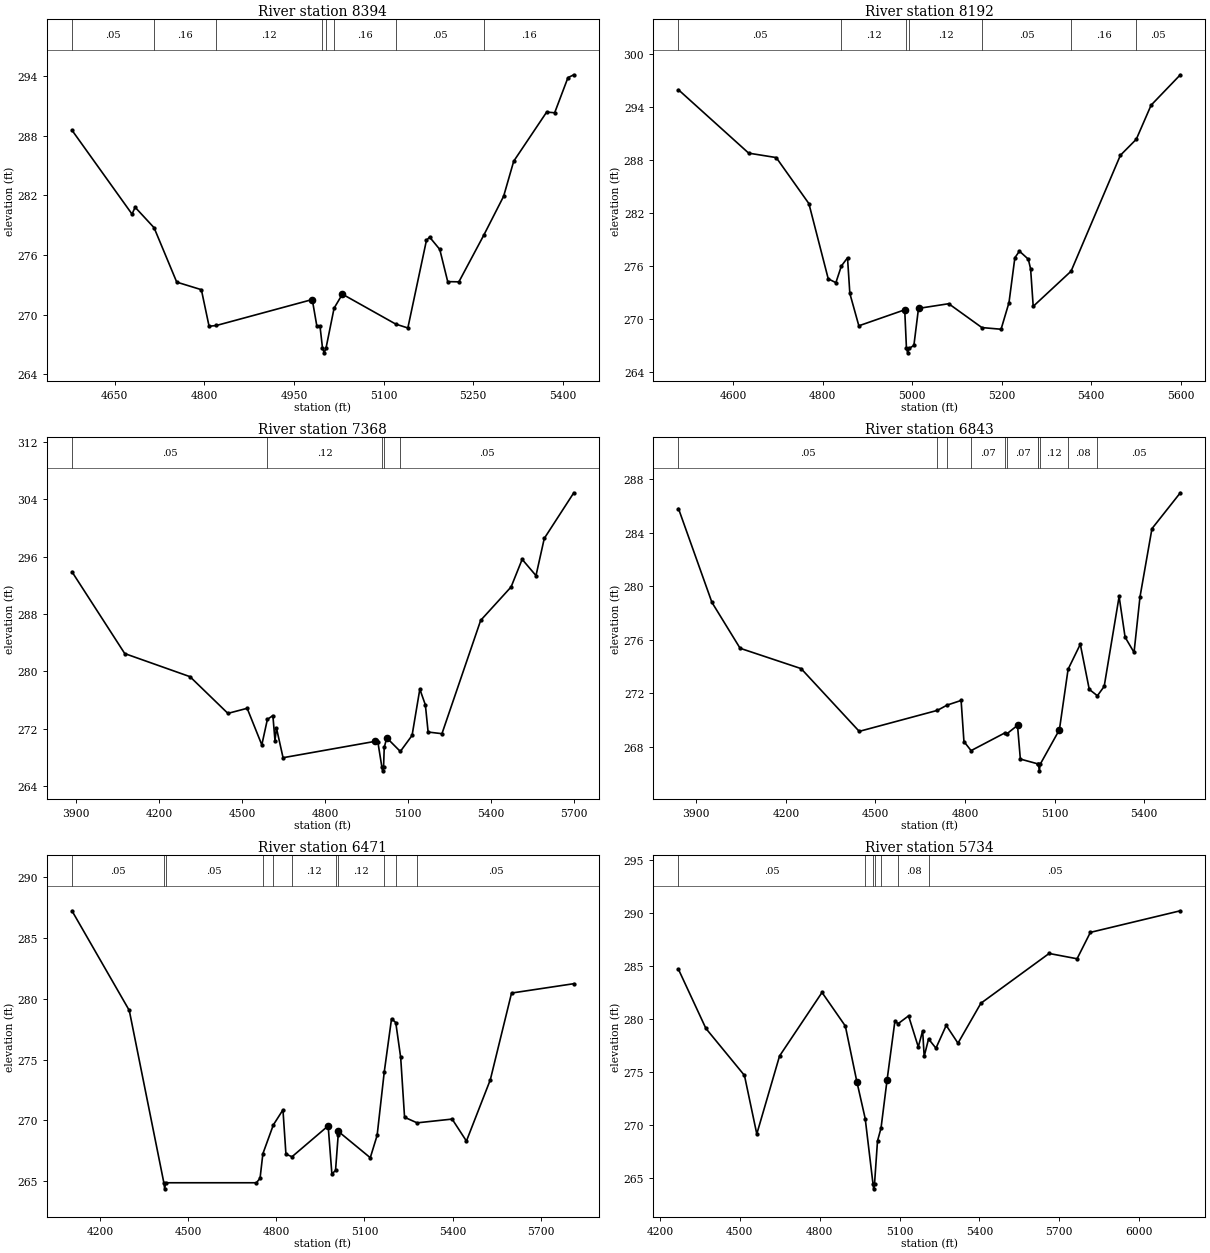
Type RM Length L Ch R = 1 ,8394    ,202,202,202
BEGIN DESCRIPTION:
PRAIRIE CREEK 11.0
END DESCRIPTION:
XS GIS Cut Line= 3
       3618149.6     10668210.21      3618249.61     10667810.19
       3618399.6     10667410.22
#Sta/Elev= 30
  4578.6  288.56  4679.1  280.12  4684.3  280.81    4716  278.75  4753.9  273.28
  4795.1  272.52    4808  268.84  4820.2  268.92  4980.6  271.53  4988.4  268.82
  4993.6  268.82  4997.7  266.67  5000.5  266.17  5003.7  266.67  5017.1  270.66
    5031  272.07  5120.3  269.06  5140.5  268.67  5171.6  277.48  5176.9  277.81
  5193.9  276.57  5207.2  273.33  5225.9  273.31  5267.6  278.01  5300.7  281.91
  5317.6  285.44  5372.7  290.38  5386.1  290.31  5408.3  293.84  5418.1  294.13
#Mann= 8 ,-1 , 0
  4578.6     .05       0    4716     .16       0  4820.2     .12       0
  4997.7     .07       0  5003.7     .12       0  5017.1     .16       0
  5120.3     .05       0  5267.6     .16       0
Bank Sta=4980.6,5031
XS Rating Curve= 0 ,0
Exp/Cntr=0.3,0.1

Type RM Length L Ch R = 1 ,8192    ,824,824,824
BEGIN DESCRIPTION:
PRAIRIE CREEK 10.0
END DESCRIPTION:
XS GIS Cut Line= 2
      3618271.18     10668453.23      3618518.56     10667359.56
#Sta/Elev= 30
  4477.6  295.96  4634.5  288.79    4696  288.29    4769  283.08  4812.2  274.57
  4829.3  274.13  4841.5  276.01  4855.3  276.95  4860.5  272.91  4880.6  269.25
  4983.1  271.06    4987  266.69  4989.7  266.19    4993  266.69  5003.6  267.03
  5013.9  271.22  5081.4  271.75  5155.5  269.05  5198.4  268.86  5216.1  271.88
  5229.2  276.95  5239.4   277.7  5259.2  276.79  5264.4  275.69  5270.2  271.45
  5354.8  275.43    5465  288.55  5500.5  290.36  5533.6  294.22  5598.9  297.66
#Mann= 7 ,-1 , 0
  4477.6     .05       0  4841.5     .12       0    4987     .07       0
    4993     .12       0  5155.5     .05       0  5354.8     .16       0
  5500.5     .05       0
Bank Sta=4983.1,5013.9
XS Rating Curve= 0 ,0
Exp/Cntr=0.3,0.1

Type RM Length L Ch R = 1 ,7368    ,525,525,525
BEGIN DESCRIPTION:
PRAIRIE CREEK 9.0
END DESCRIPTION:
XS GIS Cut Line= 3
      3618560.68     10668780.47      3619046.78      10667617.3
      3619046.78     10667063.46
#Sta/Elev= 30
  3885.3   293.9  4076.2  282.49  4312.1  279.27  4449.2  274.15  4518.8  274.86
  4571.8  269.76  4591.9  273.31  4611.8  273.85  4619.4  270.36  4624.8   272.1
  4648.6  267.97  4979.8  270.24  4991.1  270.23    5006  266.64  5008.8  266.14
    5012  266.64  5014.4   269.4  5023.6  270.74  5072.6  268.84  5115.1  271.08
  5143.1  277.53  5163.1  275.34  5173.1  271.55  5223.1  271.32  5363.1  287.12
  5473.1  291.78  5513.1  295.63  5563.1  293.36  5593.1  298.55  5699.8  304.91
#Mann= 5 ,-1 , 0
  3885.3     .05       0  4591.9     .12       0    5006     .07       0
    5012     .12       0  5072.6     .05       0
Bank Sta=4979.8,5023.6
XS Rating Curve= 0 ,0
Exp/Cntr=0.3,0.1

Type RM Length L Ch R = 1 ,6843    ,372,372,372
BEGIN DESCRIPTION:
PRAIRIE CREEK 8.0
END DESCRIPTION:
XS GIS Cut Line= 3
      3618726.91     10668852.56      3619369.27     10667819.58
      3619369.27      10667355.2
#Sta/Elev= 30
  3840.5  285.82  3952.5  278.81  4046.9  275.38  4251.2  273.86  4445.9  269.17
  4707.8  270.74  4739.9  271.13  4787.1  271.48  4796.6  268.41  4820.5  267.73
  4933.2  269.05  4939.9  268.98    4976  269.62  4985.5   267.1  5045.9  266.73
  5046.2  266.72    5049  266.22  5052.2  266.72  5116.3  269.29  5145.4  273.81
  5186.3  275.68  5216.3  272.31  5243.5  271.83  5266.3  272.53  5316.3  279.25
  5336.3  276.21  5366.3  275.07  5386.3  279.23  5426.3  284.32  5521.3     287
#Mann= 11 ,-1 , 0
  3840.5     .05       0  4707.8     .07       0  4739.9     .05       0
  4820.5     .07       0  4933.2     .12       0  4939.9     .07       0
  5045.9     .12       0  5046.2     .07       0  5052.2     .12       0
  5145.4     .08       0  5243.5     .05       0
Bank Sta=4976,5116.3
XS Rating Curve= 0 ,0
Exp/Cntr=0.3,0.1

Type RM Length L Ch R = 1 ,6471    ,737,737,737
BEGIN DESCRIPTION:
PRAIRIE CREEK 7.0
END DESCRIPTION:
XS GIS Cut Line= 4
      3619660.07     10668974.14       3619577.6     10668175.49
      3619651.38     10667993.19      3620015.31     10667386.65
#Sta/Elev= 30
  4105.1  287.24  4300.1  279.04  4417.7  264.86  4420.5  264.36  4423.7  264.86
  4732.4  264.86  4744.9  265.23  4754.5  267.25  4790.1  269.62  4822.8  270.86
  4832.9  267.22  4853.5     267  4976.5  269.54  4989.2  265.59  5001.6  265.87
  5010.8  268.83  5011.4  269.08  5119.8  266.92  5143.1  268.76  5167.3  273.97
  5192.1  278.36  5206.5  278.04  5223.2  275.17  5236.4  270.25    5279  269.79
  5398.2   270.1  5446.8  268.29    5528  273.33  5600.3  280.47    5812  281.24
#Mann= 11 ,-1 , 0
  4105.1     .05       0  4417.7     .07       0  4423.7     .05       0
  4754.5     .12       0  4790.1     .05       0  4853.5     .12       0
  5001.6     .07       0  5010.8     .12       0  5167.3     .05       0
  5206.5     .08       0    5279     .05       0
Bank Sta=4976.5,5011.4
XS Rating Curve= 0 ,0
Exp/Cntr=0.3,0.1

Type RM Length L Ch R = 1 ,5734    ,98,98,98
BEGIN DESCRIPTION:
PRAIRIE CREEK 6.0
END DESCRIPTION:
XS GIS Cut Line= 6
      3619833.67     10668891.65      3619959.54     10668609.51
      3620154.86     10668310.03       3620493.4     10668110.38
      3621009.89     10667889.03      3621174.63     10667685.27
#Sta/Elev= 30
  4269.4  284.67  4372.5  279.09  4517.3  274.66  4563.7  269.13  4649.2  276.49
  4808.8  282.49  4896.4  279.32  4940.1  274.02  4971.1  270.58  5000.2  264.45
  5002.9  263.95  5006.2  264.45  5017.3  268.47  5030.5  269.68    5053  274.18
  5082.5  279.75  5095.2  279.55    5134  280.28  5170.5  277.35    5187  278.87
  5192.7  276.45  5209.1   278.1  5236.9  277.23  5275.5  279.38  5319.7   277.7
  5405.8  281.47  5662.2  286.17  5767.2  285.67  5817.1  288.16  6155.2   290.2
#Mann= 7 ,-1 , 0
  4269.4     .05       0  4971.1     .08       0  5000.2     .07       0
  5006.2     .08       0  5030.5     .05       0  5095.2     .08       0
  5209.1     .05       0
Bank Sta=4940.1,5053
XS Rating Curve= 0 ,0
Exp/Cntr=0.3,0.1

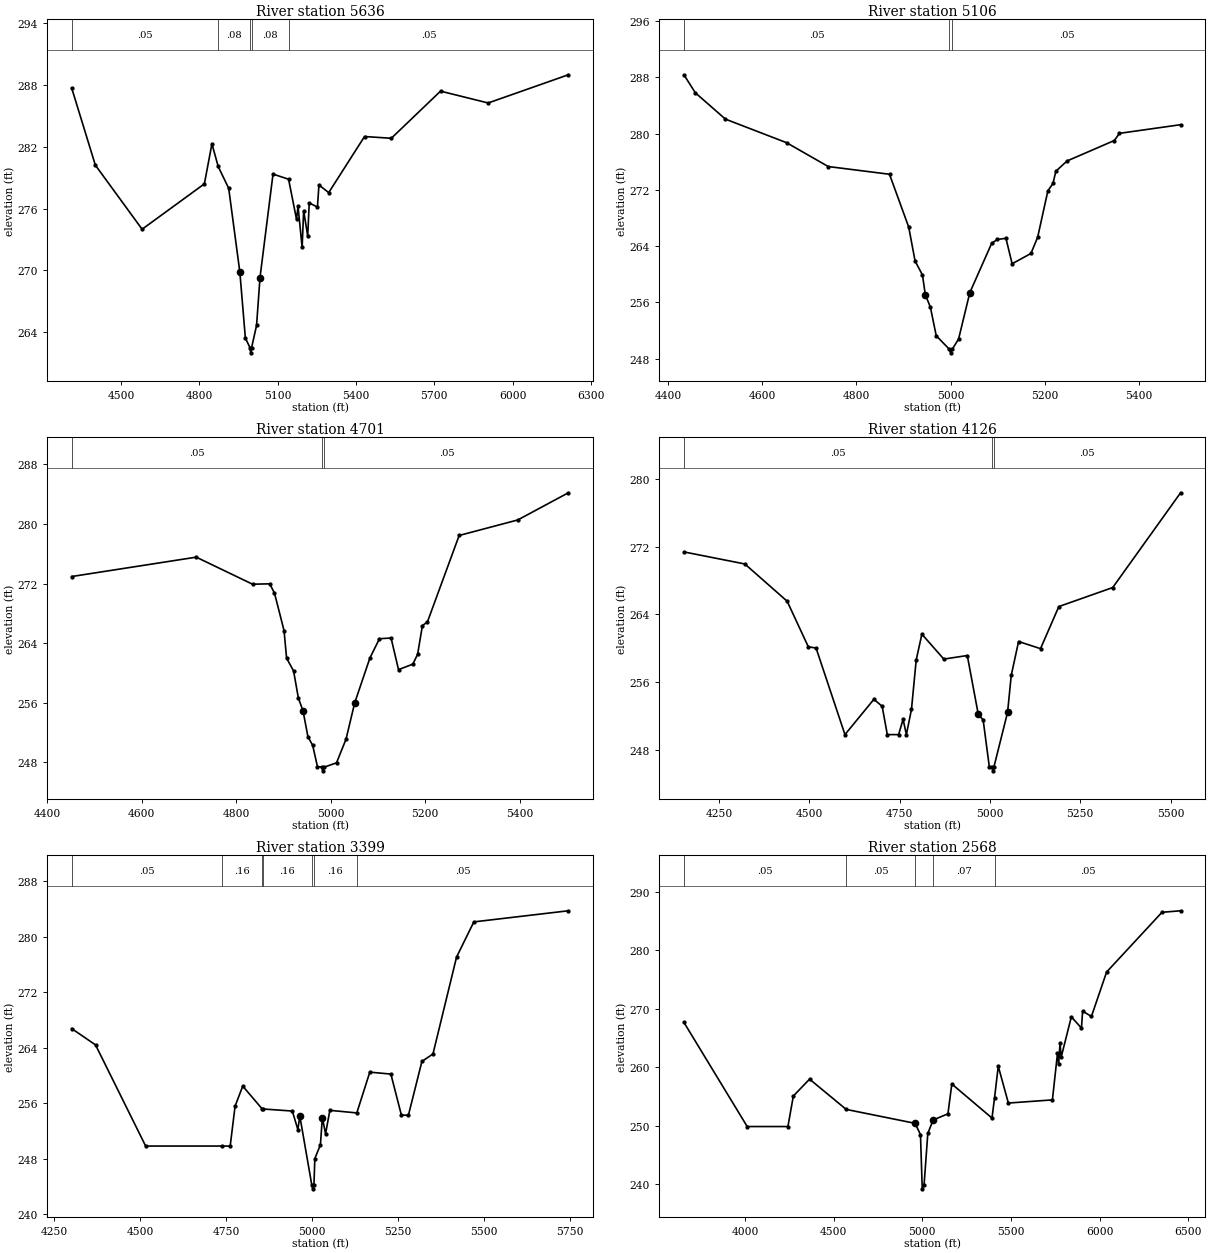
Type RM Length L Ch R = 1 ,5636    ,530,530,530
BEGIN DESCRIPTION:
PRAIRIE CREEK 5.0
END DESCRIPTION:
XS GIS Cut Line= 6
       3619890.1       10668922.      3620024.65      10668639.9
       3620224.3     10668383.82      3620510.76     10668197.19
      3621105.38     10667919.41      3621260.74     10667703.76
#Sta/Elev= 30
  4311.2  287.71  4401.8  280.22  4580.9  273.99  4819.4   278.4  4848.3  282.29
  4872.3  280.09  4912.6  277.96  4955.3  269.81  4976.4  263.41  4994.2  262.48
  4996.9  261.98  5000.2  262.48  5019.3  264.65  5032.4  269.29  5082.3  279.35
  5141.9  278.85  5172.3  274.96  5178.1  276.21  5193.8  272.22  5199.6  275.79
  5215.2  273.33    5221  276.55  5252.4  276.14  5258.2  278.29  5295.6  277.55
  5432.8     283  5535.4  282.83  5723.8  287.41  5906.3  286.26  6213.4     289
#Mann= 5 ,-1 , 0
  4311.2     .05       0  4872.3     .08       0  4994.2     .07       0
  5000.2     .08       0  5141.9     .05       0
Bank Sta=4955.3,5032.4
XS Rating Curve= 0 ,0
Exp/Cntr=0.3,0.1

Type RM Length L Ch R = 1 ,5106    ,405,405,405
BEGIN DESCRIPTION:
PRAIRIE CREEK 4.0
END DESCRIPTION:
XS GIS Cut Line= 2
      3620348.87     10669292.63      3620756.83     10668320.46
#Sta/Elev= 30
  4433.7  288.38    4458  285.81  4521.9  282.07  4651.6  278.72    4740  275.33
  4870.1  274.23  4910.9  266.71  4924.4  261.89  4940.1   259.9  4946.1   257.1
  4956.9  255.33  4969.3  251.26  4997.3  249.33    5000  248.83  5003.3  249.33
  5016.8  250.81  5040.6  257.39    5087  264.41    5099  264.96  5117.3  265.12
  5130.4   261.5  5170.3  262.96  5184.6  265.27  5206.3  271.88  5217.2  272.93
  5223.2  274.66    5247  276.12  5347.3  279.03  5358.3  280.05    5488  281.28
#Mann= 3 ,-1 , 0
  4433.7     .05       0  4997.3     .03       0  5003.3     .05       0
Bank Sta=4946.1,5040.6
XS Rating Curve= 0 ,0
Exp/Cntr=0.3,0.1

Type RM Length L Ch R = 1 ,4701    ,575,575,575
BEGIN DESCRIPTION:
PRAIRIE CREEK 3.0
END DESCRIPTION:
XS GIS Cut Line= 3
      3620704.78     10669266.59      3620930.46     10668997.51
       3621025.8     10668304.12
#Sta/Elev= 30
  4452.2  272.96  4715.8  275.56  4834.9  271.93  4871.3  271.98  4881.4  270.73
  4901.6  265.71    4907     262  4921.8  260.29  4931.9  256.66    4942  254.87
  4952.1  251.47  4962.2   250.3  4972.3  247.45  4981.1  247.38  4983.8  246.88
  4987.1  247.38  5012.7  247.96  5032.8  251.13    5051  255.97  5083.3  262.02
  5103.5  264.61  5128.1  264.71  5143.9  260.46  5174.2   261.2  5184.3  262.53
  5194.4  266.36  5205.2  266.89  5272.2  278.47  5396.2  280.55  5503.3   284.2
#Mann= 3 ,-1 , 0
  4452.2     .05       0  4981.1     .03       0  4987.1     .05       0
Bank Sta=4942,5051
XS Rating Curve= 0 ,0
Exp/Cntr=0.3,0.1

Type RM Length L Ch R = 1 ,4126    ,727,727,727
BEGIN DESCRIPTION:
Mapping XS 8b52c19a
END DESCRIPTION:
XS GIS Cut Line= 3
      3620876.23     10669268.88      3621496.87      10668904.3
      3621605.37     10668257.65
#Sta/Elev= 30
  4152.3  271.37    4321  269.95  4438.2  265.56  4496.8  260.19  4518.3  260.04
  4598.3  249.84  4678.4     254  4701.3  253.18  4715.6  249.84  4746.9  249.84
  4759.3  251.64  4768.4  249.84  4782.5  252.81  4795.6  258.63  4811.3  261.68
  4872.1  258.74  4937.1  259.16  4967.5  252.23    4981  251.57    4998  246.08
  5005.1  246.07  5007.8  245.57  5011.1  246.07  5048.7  252.47  5058.8  256.82
  5079.1  260.81  5139.9  259.97  5190.6  264.93  5339.8  267.17  5527.8  278.34
#Mann= 3 ,-1 , 0
  4152.3     .05       0  5005.1     .03       0  5011.1     .05       0
Bank Sta=4967.5,5048.7
XS Rating Curve= 0 ,0
Exp/Cntr=0.3,0.1

Type RM Length L Ch R = 1 ,3399    ,831,831,831
BEGIN DESCRIPTION:
PRAIRIE CREEK 2.0
END DESCRIPTION:
XS GIS Cut Line= 4
       3621557.6     10669503.28      3622087.15     10669169.06
      3622169.61     10669017.15      3622039.58     10668384.32
#Sta/Elev= 30
  4300.5  266.75  4369.9   264.4  4515.7  249.84  4736.5  249.84  4761.7  249.84
  4775.9  255.58  4798.2  258.47  4854.5   255.2  4855.8  255.18  4942.4  254.88
  4958.6  252.22  4964.3  254.16  4999.3  244.18    5002  243.68  5005.3  244.18
    5008  248.04  5024.2  250.02  5029.8  253.91  5039.2  251.62  5051.7  254.98
  5130.1  254.61  5167.9  260.48  5229.2   260.2  5259.8   254.3  5280.2  254.27
  5319.5  262.02  5351.7   263.1  5420.3  277.04  5470.6  282.11  5745.6  283.71
#Mann= 7 ,-1 , 0
  4300.5     .05       0  4736.5     .16       0  4854.5     .05       0
  4855.8     .16       0  4999.3     .07       0  5005.3     .16       0
  5130.1     .05       0
Bank Sta=4964.3,5029.8
XS Rating Curve= 0 ,0
Exp/Cntr=0.3,0.1

Type RM Length L Ch R = 1 ,2568    ,1150,1150,1150
BEGIN DESCRIPTION:
PRAIRIE CREEK 1.0
END DESCRIPTION:
XS GIS Cut Line= 4
      3621653.15     10669590.06      3622894.44     10669360.03
      3622929.16     10669177.74      3622056.95     10668144.97
#Sta/Elev= 30
  3656.1  267.66  4012.8  249.84  4242.4  249.84  4272.9  255.06  4364.4  257.95
  4571.1  252.77  4959.1  250.39  4989.6  248.47  4999.6  239.18    5010  239.91
  5030.9  248.65  5060.9  250.96  5144.4  252.02  5166.3  257.12  5392.8  251.29
  5407.1  254.74  5428.1  260.16  5485.1  253.86  5733.4   254.4    5762  262.36
  5768.5  260.55  5776.3  264.17  5782.8  261.71    5840  268.61  5897.2  266.69
  5903.7   269.6  5953.2  268.67  6038.9  276.28    6351   286.5  6455.9  286.76
#Mann= 5 ,-1 , 0
  3656.1     .05       0  4571.1     .05       0  4959.1     .03       0
  5060.9     .07       0  5407.1     .05       0
Bank Sta=4959.1,5060.9
XS Rating Curve= 0 ,0
Exp/Cntr=0.3,0.1