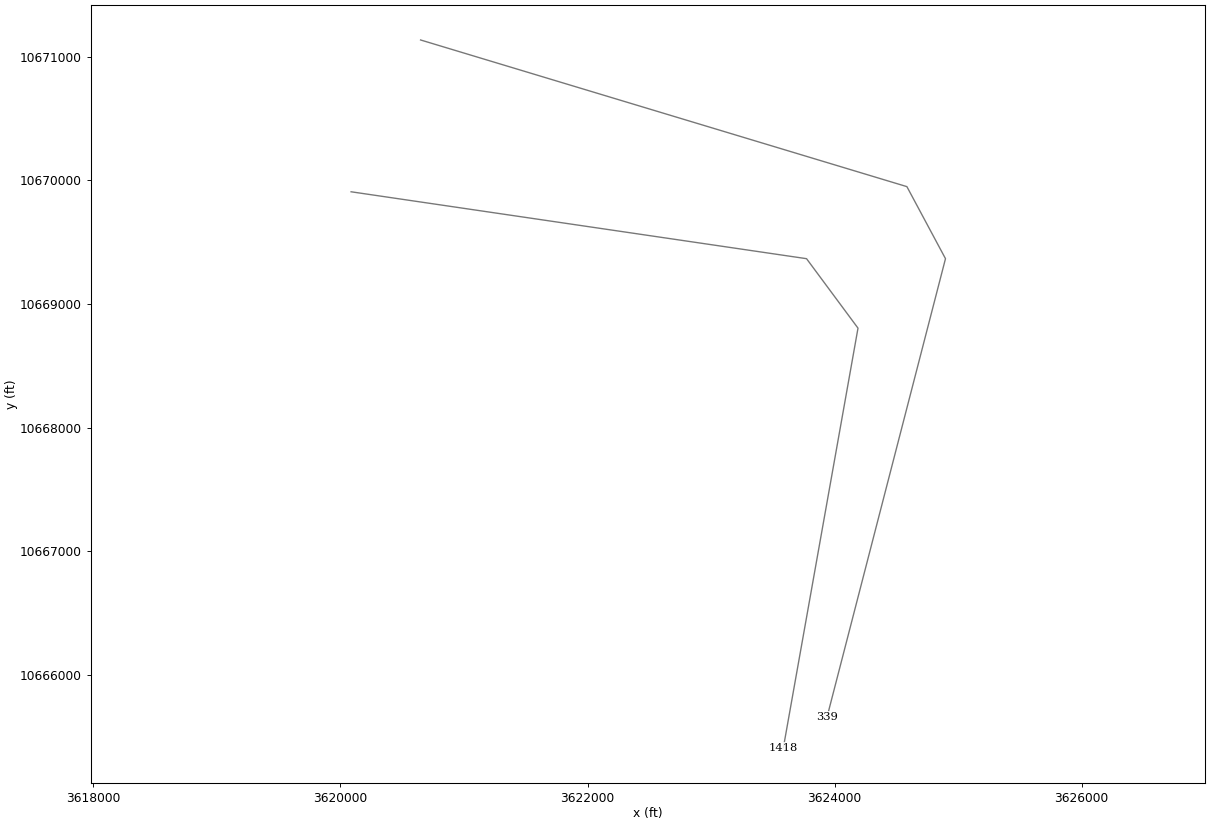
HEC-RAS study PRAIRIE CREEK.prj: PRAIRIE CREEK Base Level Engineering

--- PRAIRIE CREEK.g01 (geometry) --- (continued)

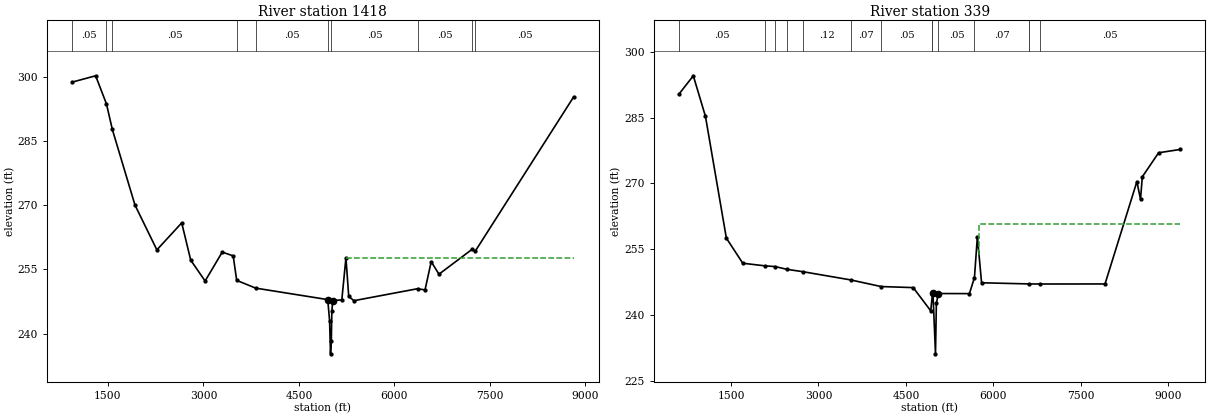
Type RM Length L Ch R = 1 ,1418    ,1079,1079,1079
BEGIN DESCRIPTION:
UNT237 IN CCTC 2.0
END DESCRIPTION:
XS GIS Cut Line= 4
      3620085.82     10669908.65      3623773.35     10669366.98
      3624190.01     10668804.48      3623585.84     10665408.62
#Sta/Elev= 30
   937.7  298.69    1308  300.18  1478.2   293.6  1570.1  287.66  1925.9     270
  2269.7  259.54  2659.8  265.84  2801.3  257.14  3027.2  252.27  3296.2  259.02
  3468.4  258.14    3523  252.42  3822.1  250.61  4952.9  247.93  4982.1  242.99
  4996.5  235.27  5009.3  238.26  5017.6  245.23  5032.2  247.72  5174.1  247.86
  5238.8  257.68  5282.7  248.67  5364.4  247.68  6362.8  250.47  6480.9  250.19
  6577.9  256.79  6699.7  253.86  7220.1  259.67  7268.7  259.22    8814  295.23
#Mann= 10 ,-1 , 0
   937.7     .05       0  1478.2     .08       0  1570.1     .05       0
    3523     .07       0  3822.1     .05       0  4952.9     .03       0
  5009.3     .05       0  6362.8     .05       0  7220.1     .08       0
  7268.7     .05       0
#XS Ineff= 2 , 0
                         5238.64          257.73
Permanent Ineff=
       F       F
Bank Sta=4952.9,5032.2
XS Rating Curve= 0 ,0
Exp/Cntr=0.3,0.1

Type RM Length L Ch R = 1 ,339     ,0,0,0
BEGIN DESCRIPTION:
UNT237 IN CCTC 1.0
END DESCRIPTION:
XS GIS Cut Line= 4
      3620648.37     10671137.81      3624585.85     10669950.31
      3624898.35     10669366.98      3623940.01     10665658.62
#Sta/Elev= 30
   604.1  290.29   853.2  294.51  1061.6  285.25  1420.1  257.52  1702.1   251.8
  2086.9   251.2  2259.5  251.04  2456.2  250.42  2734.5  249.87  3550.6  248.01
    4074  246.49    4626  246.25  4926.3  240.96  4955.1  244.68  4964.5  244.98
  5008.1  231.16  5023.2  242.68  5057.9   244.9  5590.1  244.88  5676.6  248.55
  5726.4  257.84  5798.7  247.35  6610.8  247.09  6799.8  247.07  7916.3  247.08
  8463.4   270.4  8525.4  266.37  8556.4  271.49  8835.5  276.97  9208.7  277.73
#Mann= 14 ,-1 , 0
   604.1     .05       0  2086.9     .12       0  2259.5     .12       0
  2456.2     .16       0  2734.5     .12       0  3550.6     .07       0
    4074     .05       0  4955.1     .05       0  4955.1     .03       0
  5057.9     .05       0  5676.6     .07       0  6610.8     .07       0
  6610.8     .05       0  6799.8     .05       0
#XS Ineff= 2 , 0
                         5755.68          260.84
Permanent Ineff=
       F       F
Bank Sta=4964.5,5057.9
XS Rating Curve= 0 ,0
Exp/Cntr=0.3,0.1

Chan Stop Cuts=-1
Use User Specified Reach Order=0
Composite Channel Slope=5