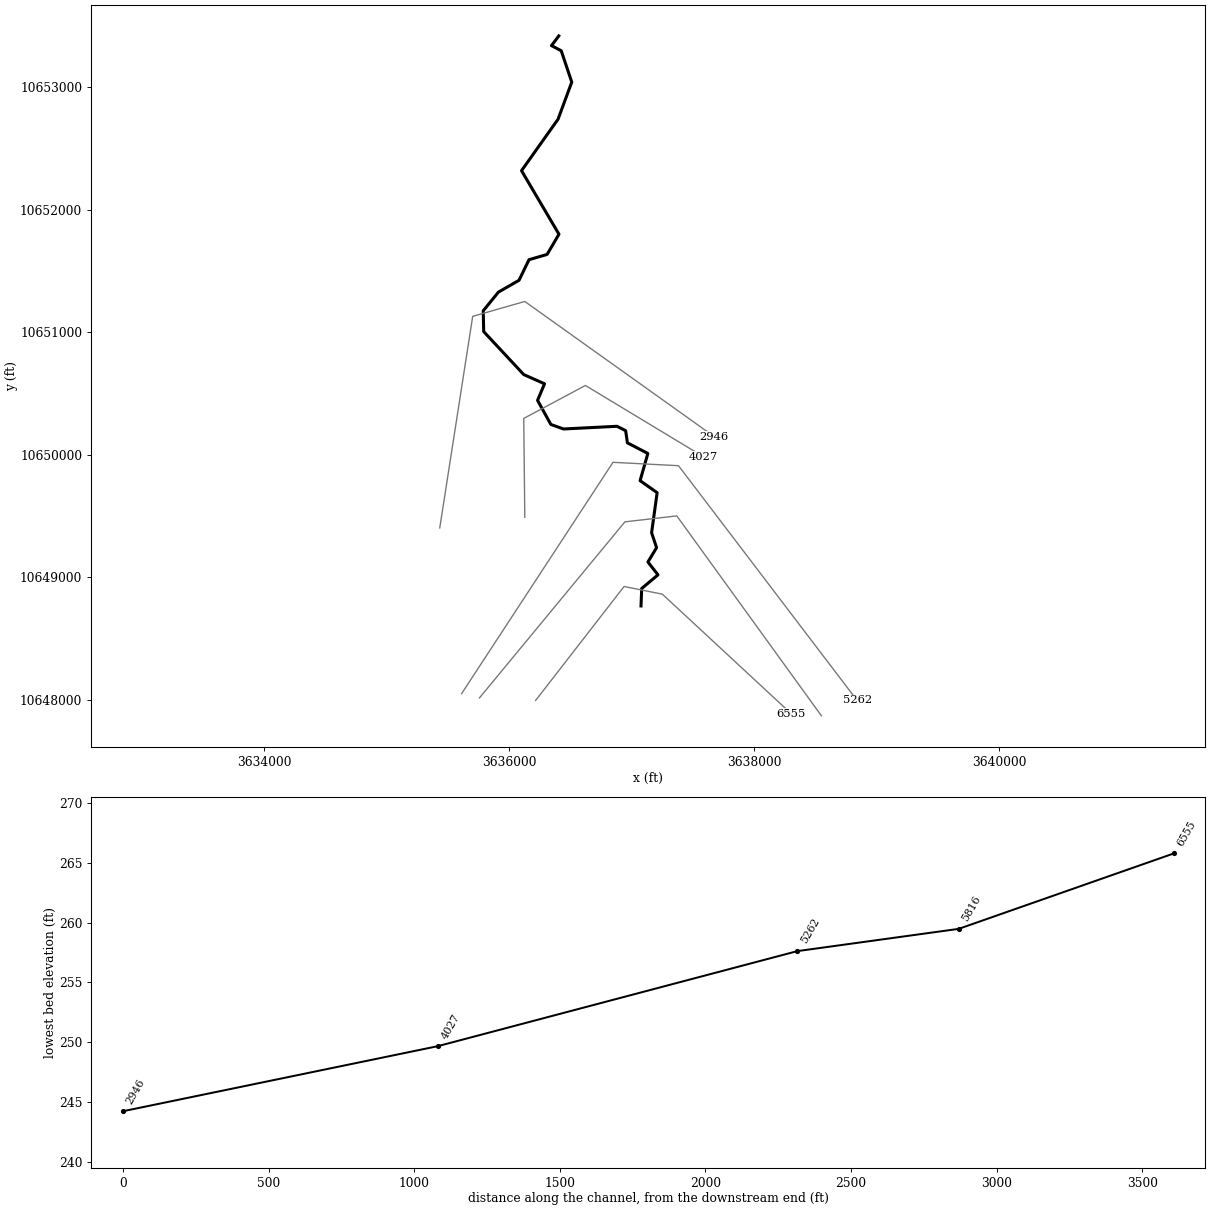
--- ROCK SPRINGS BRANCH.prj (project) ---

Proj Title=ROCK SPRINGS BRANCH Base Level Engineering
Current Plan=p01
Default Exp/Contr=0.3,0.1
English Units
Geom File=g01
Flow File=f01
Plan File=p01
BEGIN DESCRIPTION:
ROCK SPRINGS BRANCH
END DESCRIPTION:

--- ROCK SPRINGS BRANCH.p01 (plan) ---

Plan Title=Multiple Run
Short Identifier=Multiple
Geom File=g01
Flow File=f01
Subcritical Flow
K Sum by GR= 0
Std Step Tol= 0.01
Critical Tol= 0.01
Num of Std Step Trials= 20
Max Error Tol= 0.3
Flow Tol Ratio= 0.001
Split Flow NTrial= 30
Split Flow Tol= 0.02
Split Flow Ratio= 0.02
Log Output Level= 0
Friction Slope Method= 1
Unsteady Friction Slope Method= 2
Unsteady Bridges Friction Slope Method= 1
Parabolic Critical Depth
Global Vel Dist=  1 , 1 , 1
Global Log Level= 0
CheckData=True
Encroach Param= -1, 0, 0, 0
BEGIN DESCRIPTION:
Multiple Run
END DESCRIPTION:

--- ROCK SPRINGS BRANCH.f01 (steady flow) ---

Flow Title=Multiple
Number of Profiles=7
Profile Names=10-year,25-year,50-year,1pct_min,100-year,1pct_plu,500-year
River Rch & RM= ROCK SPRINGS BRA,Reach-1,6555
    2208    3158    3976    3654    4941    6682    7607
Boundary for River Rch & Prof#=ROCK SPRINGS BRA,Reach-1,1
Up Type=0
Dn Type=3
Dn Slope=0.005
Boundary for River Rch & Prof#=ROCK SPRINGS BRA,Reach-1,2
Up Type=0
Dn Type=3
Dn Slope=0.005
Boundary for River Rch & Prof#=ROCK SPRINGS BRA,Reach-1,3
Up Type=0
Dn Type=3
Dn Slope=0.005
Boundary for River Rch & Prof#=ROCK SPRINGS BRA,Reach-1,4
Up Type=0
Dn Type=3
Dn Slope=0.005
Boundary for River Rch & Prof#=ROCK SPRINGS BRA,Reach-1,5
Up Type=0
Dn Type=3
Dn Slope=0.005
Boundary for River Rch & Prof#=ROCK SPRINGS BRA,Reach-1,6
Up Type=0
Dn Type=3
Dn Slope=0.005
Boundary for River Rch & Prof#=ROCK SPRINGS BRA,Reach-1,7
Up Type=0
Dn Type=3
Dn Slope=0.005

--- ROCK SPRINGS BRANCH.g01 (geometry) ---

Geom Title=Existing Conditions

River Reach=ROCK SPRINGS BRA,Reach-1
Reach XY= 30
      3637077.04     10648766.28      3637082.75     10648909.00
      3637215.75     10649020.00      3637133.50     10649125.00
      3637204.25     10649242.00      3637163.50     10649364.00
      3637208.75     10649691.00      3637069.50     10649789.00
      3637133.00     10650011.00      3636966.00     10650098.00
      3636951.75     10650197.00      3636881.25     10650233.00
      3636444.25     10650211.00      3636341.00     10650248.00
      3636232.50     10650445.00      3636289.50     10650580.00
      3636120.00     10650655.00      3635792.75     10651006.00
      3635789.00     10651176.00      3635912.50     10651328.00
      3636081.25     10651425.00      3636162.50     10651593.00
      3636310.25     10651636.00      3636407.25     10651801.00
      3636101.50     10652320.00      3636399.75     10652740.00
      3636511.75     10653043.00      3636425.75     10653299.00
      3636346.00     10653341.00      3636406.00     10653420.00

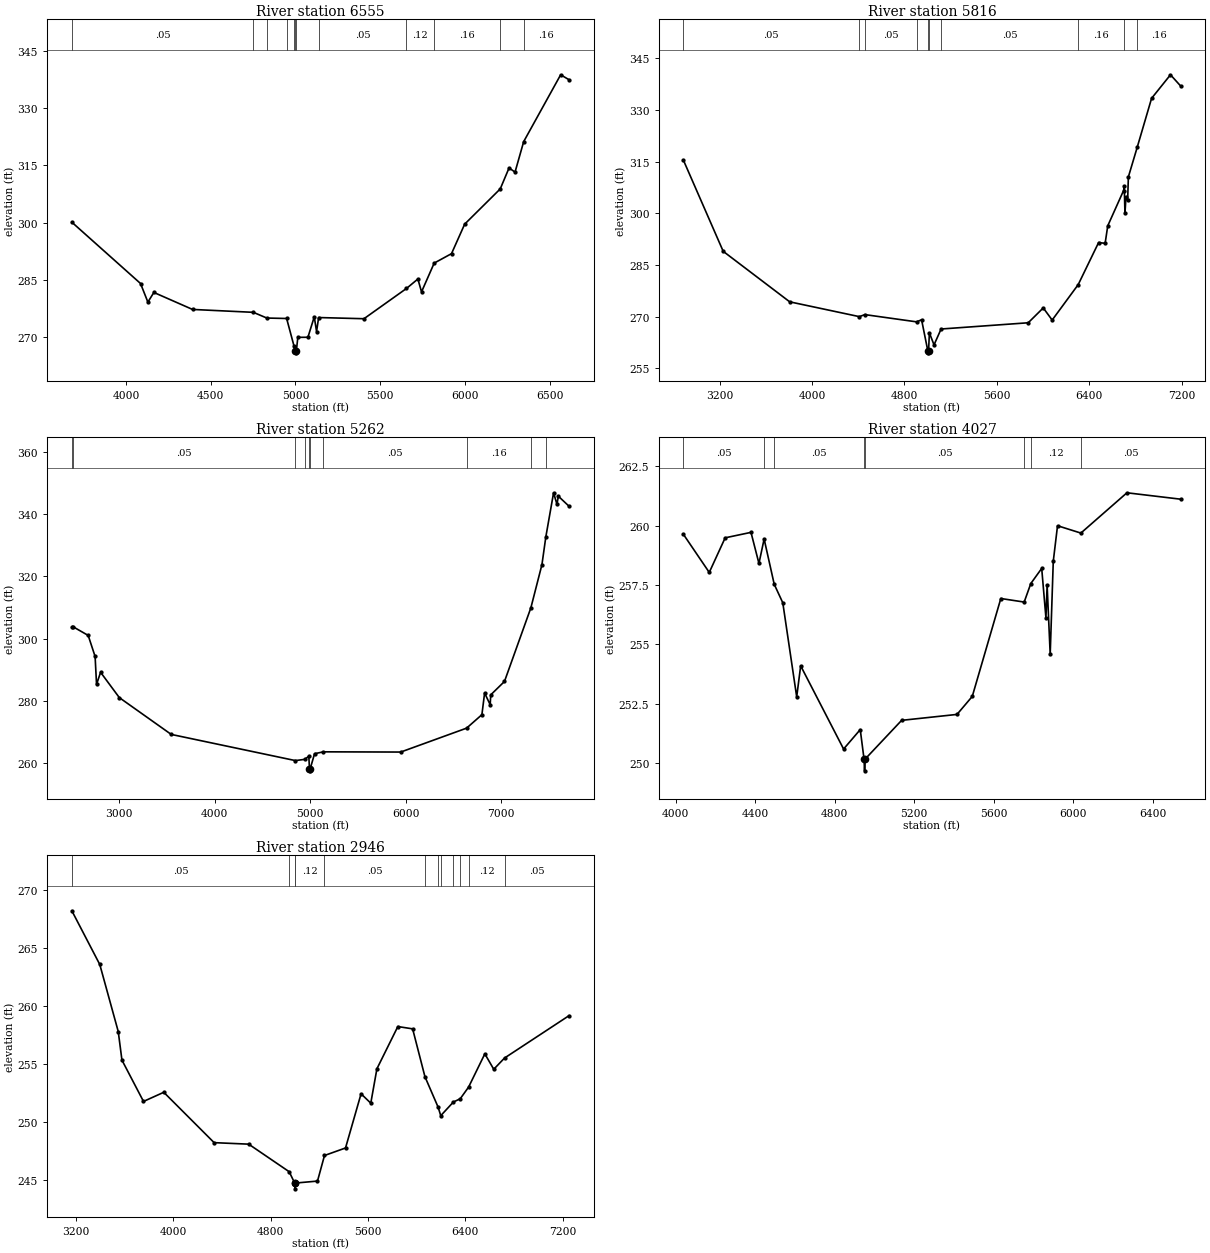
Type RM Length L Ch R = 1,6555,739,739,739
BEGIN DESCRIPTION:
ROCK SPRINGS BRANCH 3.0
END DESCRIPTION:
XS GIS Cut Line= 4
      3636216.50     10647994.51      3636938.70     10648925.04
      3637251.20     10648862.54      3638304.72     10647885.25
#Sta/Elev= 30
  3680.4  300.09  4085.7  283.99  4129.1  279.10  4164.4  281.64  4392.5  277.18
  4751.3  276.42  4830.9  274.92  4947.8  274.80  4990.8  267.65  4999.0  266.28
  5001.8  265.78  5005.0  266.28  5013.9  269.85  5073.4  269.87  5110.8  275.24
  5124.4  271.38  5136.6  275.05  5404.1  274.74  5654.7  282.68  5722.2  285.17
  5743.7  281.79  5818.4  289.35  5920.6  291.83  5998.3  299.58  6208.2  308.84
  6260.2  314.35  6295.4  313.24  6346.5  321.26  6564.6  338.81  6614.0  337.51
#Mann=12,-1,0
  3680.4    0.05       0  4751.3    0.08       0  4830.9    0.05       0
  4947.8    0.16       0  4990.8    0.12       0  4999.0    0.07       0
  5005.0    0.12       0  5136.6    0.05       0  5654.7    0.12       0
  5818.4    0.16       0  6208.2    0.08       0  6346.5    0.16       0
Bank Sta=4999,5005
Exp/Cntr=0.3,0.1

Type RM Length L Ch R = 1,5816,554,554,554
BEGIN DESCRIPTION:
ROCK SPRINGS BRANCH 2.0
END DESCRIPTION:
XS GIS Cut Line= 4
      3635758.13     10648015.29      3636945.64     10649452.81
      3637369.25     10649501.42      3638549.83     10647869.45
#Sta/Elev= 30
  2886.6  315.43  3231.6  288.94  3807.4  274.28  4410.3  269.98  4458.2  270.57
  4905.4  268.47  4949.4  269.07  5003.8  259.97  5006.6  259.47  5009.8  259.97
  5016.9  265.28  5057.1  261.78  5118.3  266.39  5872.8  268.20  6002.8  272.51
  6080.1  268.99  6305.6  279.28  6482.3  291.50  6538.7  291.26  6561.4  296.35
  6698.4  306.59  6704.3  307.81  6710.4  299.95  6719.0  304.61  6733.7  303.74
  6739.8  310.53  6816.1  319.10  6940.9  333.36  7104.5  340.20  7191.8  336.97
#Mann=10,-1,0
  2886.6    0.05       0  4410.3    0.08       0  4458.2    0.05       0
  4905.4    0.12       0  5003.8    0.07       0  5009.8    0.12       0
  5118.3    0.05       0  6305.6    0.16       0  6698.4    0.08       0
  6816.1    0.16       0
Bank Sta=5003.8,5009.8
Exp/Cntr=0.3,0.1

Type RM Length L Ch R = 1,5262,1235,1235,1235
BEGIN DESCRIPTION:
Mapping XS 7edab0ce
END DESCRIPTION:
XS GIS Cut Line= 4
      3635612.30     10648050.02      3636848.42     10649938.92
      3637383.14     10649911.15      3638841.20     10647994.85
#Sta/Elev= 30
  2507.6  303.68  2516.9  303.91  2678.6  301.07  2751.0  294.31  2766.1  285.36
  2808.3  289.24  3004.3  281.11  3547.2  269.30  4846.0  260.90  4945.3  261.30
  4986.5  262.33  4993.5  258.11  4996.3  257.61  4999.5  258.11  5046.6  263.11
  5139.9  263.71  5947.9  263.64  6636.7  271.31  6797.0  275.63  6825.3  282.59
  6883.5  278.84  6889.8  282.00  7033.2  286.30  7309.5  309.95  7425.2  323.82
  7465.6  332.67  7546.8  346.85  7582.1  343.15  7596.7  345.75  7708.4  342.53
#Mann=10,-1,0
  2507.6    0.16       0  2516.9    0.05       0  4846.0    0.16       0
  4945.3    0.12       0  4993.5    0.07       0  4999.5    0.12       0
  5139.9    0.05       0  6636.7    0.16       0  7309.5    0.05       0
  7465.6    0.16       0
Bank Sta=4993.5,4999.5
Exp/Cntr=0.3,0.1

Type RM Length L Ch R = 1,4027,1081,1081,1081
BEGIN DESCRIPTION:
Mapping XS df0887b0
END DESCRIPTION:
XS GIS Cut Line= 4
      3636128.32     10649489.91      3636119.64     10650297.15
      3636623.11     10650566.25      3637585.18     10649985.55
#Sta/Elev= 30
  4038.7  259.64  4169.0  258.03  4249.0  259.49  4379.0  259.72  4419.0  258.41
  4445.1  259.44  4495.9  257.53  4539.0  256.75  4609.0  252.78  4629.0  254.09
  4845.0  250.58  4928.8  251.40  4947.8  250.16  4950.5  249.66  4953.8  250.16
  5137.0  251.79  5415.7  252.04  5492.5  252.80  5636.2  256.93  5753.7  256.78
  5787.0  257.56  5841.9  258.20  5863.2  256.11  5869.1  257.49  5884.6  254.58
  5900.1  258.50  5921.5  260.00  6039.0  259.69  6270.8  261.39  6540.6  261.12
#Mann=8,-1,0
  4038.7    0.05       0  4445.1    0.16       0  4495.9    0.05       0
  4947.8    0.03       0  4953.8    0.05       0  5753.7    0.16       0
  5787.0    0.12       0  6039.0    0.05       0
Bank Sta=4947.8,4953.8
Exp/Cntr=0.3,0.1

Type RM Length L Ch R = 1,2946,0,0,0
BEGIN DESCRIPTION:
ROCK SPRINGS BRANCH 1.0
END DESCRIPTION:
XS GIS Cut Line= 4
      3635433.88     10649403.10      3635702.97     10651130.49
      3636128.32     10651252.02      3637673.46     10650149.58
#Sta/Elev= 30
  3164.6  268.24  3394.4  263.60  3546.2  257.81  3576.6  255.34  3753.9  251.77
  3920.7  252.56  4334.7  248.21  4619.0  248.08  4951.8  245.70  4997.2  244.72
  5000.0  244.22  5003.2  244.72  5184.8  244.89  5242.3  247.10  5415.3  247.75
  5543.1  252.43  5623.0  251.62  5673.4  254.59  5845.5  258.24  5967.2  258.04
  6068.3  253.91  6177.4  251.26  6198.3  250.54  6302.4  251.72  6358.4  252.00
  6427.4  253.01  6560.9  255.88  6634.3  254.55  6723.0  255.52  7253.3  259.18
#Mann=12,-1,0
  3164.6    0.05       0  4951.8    0.12       0  4997.2    0.07       0
  5003.2    0.12       0  5242.3    0.05       0  6068.3    0.16       0
  6177.4    0.12       0  6198.3    0.16       0  6302.4    0.12       0
  6358.4    0.16       0  6427.4    0.12       0  6723.0    0.05       0
Bank Sta=4997.2,5003.2
Exp/Cntr=0.3,0.1

Chan Stop Cuts=-1