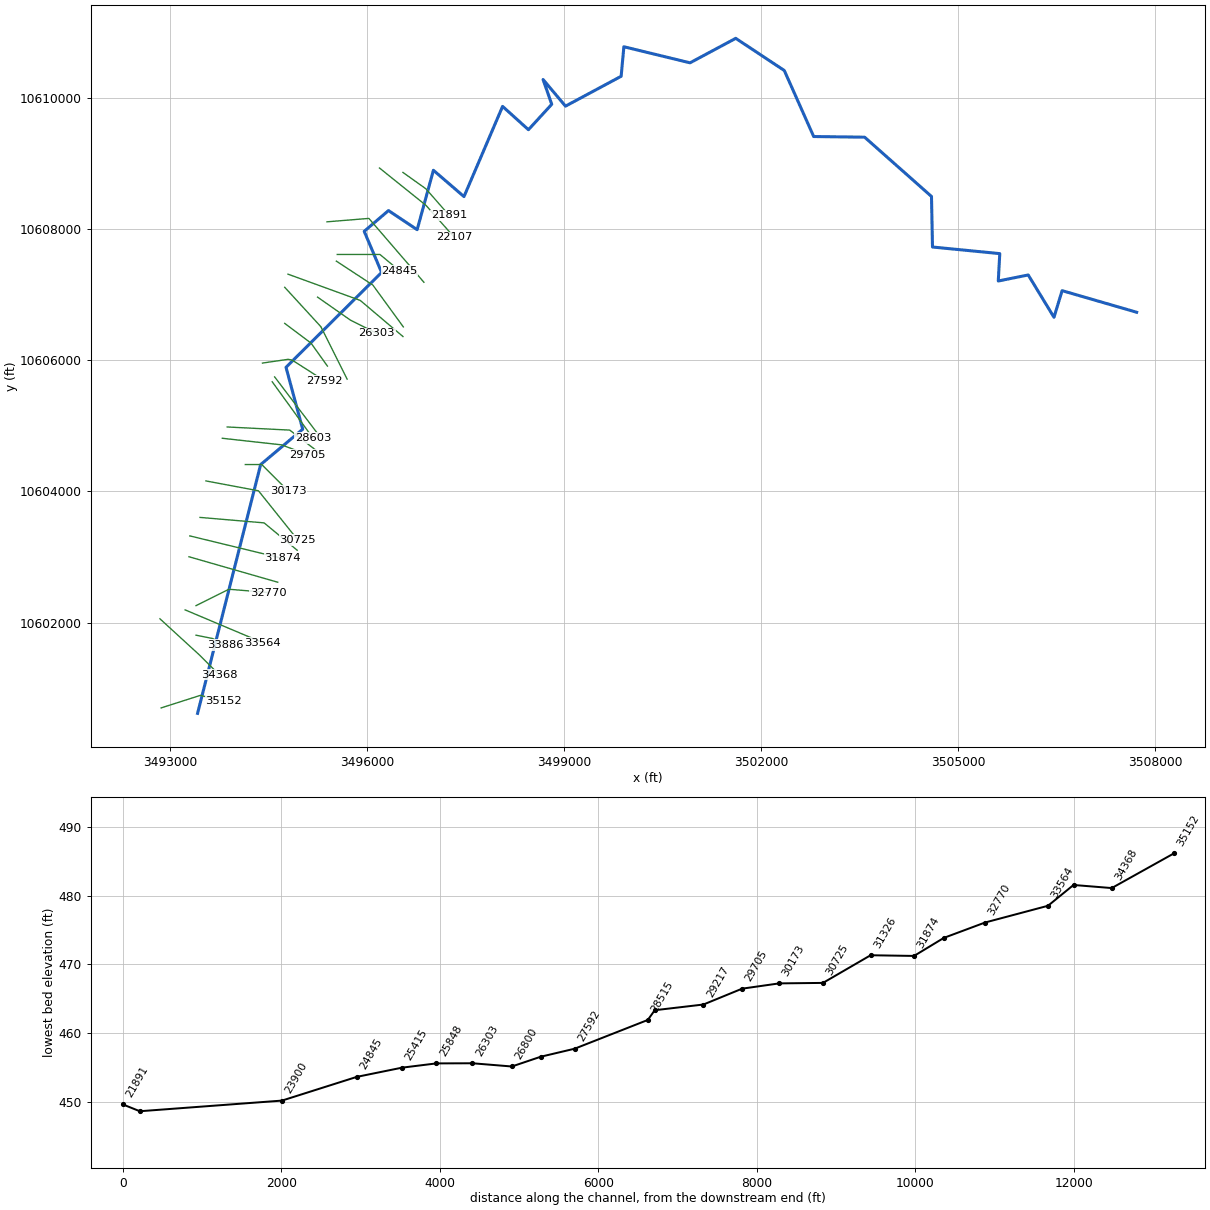
--- SALT CREEK 1.prj (project) ---

Proj Title=SALT CREEK 1 Base Level Engineering
Current Plan=p01
Default Exp/Contr=0.3,0.1
English Units
Geom File=g01
Flow File=f01
Flow File=f02
Plan File=p01
Plan File=p02
Y Axis Title=Elevation
X Axis Title(PF)=Main Channel Distance
X Axis Title(XS)=Station
BEGIN DESCRIPTION:
SALT CREEK 1
END DESCRIPTION:
DSS Export Rating Curves= 0
DSS Export Rating Curve Sorted= 0
DSS Export Volume Flow Curves= 0
DXF OffsetX= 0
DXF OffsetY= 0
DXF ScaleX= 1
DXF ScaleY= 10

--- SALT CREEK 1.p01 (plan) ---

Plan Title=Multiple Run
Short Identifier=Multiple
Geom File=g01
Flow File=f01
Subcritical Flow
K Sum by GR= 0
Std Step Tol= 0.01
Critical Tol= 0.01
Num of Std Step Trials= 20
Max Error Tol= 0.3
Flow Tol Ratio= 0.001
Split Flow NTrial= 30
Split Flow Tol= 0.02
Split Flow Ratio= 0.02
Log Output Level= 0
Friction Slope Method= 1
Unsteady Friction Slope Method= 2
Unsteady Bridges Friction Slope Method= 1
Parabolic Critical Depth
Global Vel Dist=  1 , 1 , 1
Global Log Level= 0
CheckData=True
Encroach Param= -1, 0, 0, 0
BEGIN DESCRIPTION:
Multiple Run
END DESCRIPTION:

--- SALT CREEK 1.p02 (plan) ---

Plan Title=OLD MULTI
Program Version=4.10
Short Identifier=old
Geom File=g01
Flow File=f02
Subcritical Flow
K Sum by GR= 0
Std Step Tol= 0.01
Critical Tol= 0.01
Num of Std Step Trials= 20
Max Error Tol= 0.3
Flow Tol Ratio= 0.001
Split Flow NTrial= 30
Split Flow Tol= 0.02
Split Flow Ratio= 0.02
Log Output Level= 0
Friction Slope Method= 1
Unsteady Friction Slope Method= 2
Unsteady Bridges Friction Slope Method= 1
Parabolic Critical Depth
Global Vel Dist= 1 , 1 , 1
Global Log Level= 0
CheckData=True
Encroach Param=-1 ,0,0, 0
BEGIN DESCRIPTION:
Multiple Run
END DESCRIPTION:
Computation Interval=1HOUR
Output Interval=1HOUR
Run HTab= 0
Run UNet= 0
Run PostProcess= 0
Run WQNet= 0
UNET Theta= 1
UNET Theta Warmup= 1
UNET ZTol= 0.02
UNET ZSATol= 0.05
UNET MxIter= 20
UNET MaxInSteps= 0
UNET DtIC= 0
UNET DtMin= 0
UNET MaxCRTS= 20
UNET WFStab= 2
UNET SFStab= 1
UNET WFX= 1
UNET SFX= 1
UNET DSS MLevel= 4
UNET DZMax Abort= 100
UNET Convert EG Bridges= 0
UNET Use Existing IB Tables=-1
UNET Froude Reduction=False
UNET Froude Limit= 1
UNET Froude Power= 10
UNET Time Slicing=0,0, 5
UNET Junction Losses=0
Instantaneous Interval=1HOUR
Write IC File= 0
Write IC File at Sim End=0
Echo Input=False
Echo Parameters=False
Echo Output=False
Write Detailed= 0
WQ AD Non Conservative
WQ ULTIMATE=-1
WQ Max Comp Step=1HOUR
WQ Output Interval=15MIN
WQ Output Selected Increments= 0
WQ Output face flow=0
WQ Output face velocity=0
WQ Output face area=0
WQ Output face dispersion=0
WQ Output cell volume=0
WQ Output cell surface area=0
WQ Output cell continuity=0
WQ Output cumulative cell continuity=0
WQ Output face conc=0
WQ Output face dconc_dx=0
WQ Output face courant=0
WQ Output face peclet=0
WQ Output face adv mass=0
WQ Output face disp mass=0
WQ Output cell mass=0
WQ Output cell source sink temp=0
WQ Output cell source sink nsm=0
WQ Output MaxMinRange=-1
WQ Daily Max Min Mean=-1
WQ Daily Range=0
WQ Daily Time=0
WQ Create Restart=0
WQ Fixed Restart=0
WQ System Summary=0
WQ Use Fixed Temperature=0
Sorting and Armoring Iterations= 10
XS Update Threshold= 0.02
Hydraulics Update Threshold= 0.02
Energy Slope Method= 1
Volume Change Method= 0
XS Weighting Method= 0
Number of US Weighted Cross Sections= 1
Number of DS Weighted Cross Sections= 1
Upstream XS Weight=0.25
Main XS Weight=0.5
Downstream XS Weight=0.25
Number of DS XS's Weighted with US Boundary= 1
Upstream Boundary Weight= 1
Weight of XSs Associated with US Boundary= 0
Number of US XS's Weighted with DS Boundary= 1
Downstream Boundary Weight= 0.5
Weight of XSs Associated with DS Boundary= 0.5
Sediment Output Level= 4
Mass or Volume Output= 0
Output Increment Type= 1
Profile and TS Output Increment= 10
XS Output Flag= 0
XS Output Increment= 10
Disregard all LS=0
Disregard all Conn=0
Disregard all Breaches=0
Disregard all Pumps=0

--- SALT CREEK 1.f01 (steady flow) ---

Flow Title=Multiple
Program Version=4.10
Number of Profiles= 7
Profile Names=10-year,25-year,50-year,1pct_min,100-year,1pct_plu,500-year
River Rch & RM=SALT CREEK 1,Reach-1         ,35152
    1339    1834    2239    1994    2697    3647    3900
River Rch & RM=SALT CREEK 1,Reach-1         ,27164
    2723    3851    4804    4358    5893    7970    8852
River Rch & RM=SALT CREEK 1,Reach-1         ,26800
    2723    3851    4804    4358    5893    7970    8852
River Rch & RM=SALT CREEK 1,Reach-1         ,15491
    3252    4625    5791    5268    7124    9634   10765
River Rch & RM=SALT CREEK 1,Reach-1         ,13352
    3252    4625    5791    5268    7124    9634   10765
River Rch & RM=SALT CREEK 1,Reach-1         ,5736
    3774    5389    6766    6167    8341   11280   12655
Boundary for River Rch & Prof#=SALT CREEK 1,Reach-1         , 1
Up Type= 0
Dn Type= 3
Dn Slope=0.005
Boundary for River Rch & Prof#=SALT CREEK 1,Reach-1         , 2
Up Type= 0
Dn Type= 3
Dn Slope=0.005
Boundary for River Rch & Prof#=SALT CREEK 1,Reach-1         , 3
Up Type= 0
Dn Type= 3
Dn Slope=0.005
Boundary for River Rch & Prof#=SALT CREEK 1,Reach-1         , 4
Up Type= 0
Dn Type= 3
Dn Slope=0.005
Boundary for River Rch & Prof#=SALT CREEK 1,Reach-1         , 5
Up Type= 0
Dn Type= 3
Dn Slope=0.005
Boundary for River Rch & Prof#=SALT CREEK 1,Reach-1         , 6
Up Type= 0
Dn Type= 3
Dn Slope=0.005
Boundary for River Rch & Prof#=SALT CREEK 1,Reach-1         , 7
Up Type= 0
Dn Type= 3
Dn Slope=0.005
DSS Import GetInterval= 0
DSS Import GetPeak= 0
DSS Import FillOption= 0

--- SALT CREEK 1.f02 (steady flow) ---

Flow Title=OLD Multiple
Program Version=4.10
Number of Profiles= 7
Profile Names=10-year,25-year,50-year,1pct_min,100-year,1pct_plu,500-year
River Rch & RM=SALT CREEK 1,Reach-1         ,35152
    1339    1834    2239    1994    2697    3647    3900
River Rch & RM=SALT CREEK 1,Reach-1         ,26800
    2723    3851    4804    4358    5893    7970    8852
River Rch & RM=SALT CREEK 1,Reach-1         ,13352
    3252    4625    5791    5268    7124    9634   10765
River Rch & RM=SALT CREEK 1,Reach-1         ,5736
    3774    5389    6766    6167    8341   11280   12655
Boundary for River Rch & Prof#=SALT CREEK 1,Reach-1         , 1
Up Type= 0
Dn Type= 3
Dn Slope=0.005
Boundary for River Rch & Prof#=SALT CREEK 1,Reach-1         , 2
Up Type= 0
Dn Type= 3
Dn Slope=0.005
Boundary for River Rch & Prof#=SALT CREEK 1,Reach-1         , 3
Up Type= 0
Dn Type= 3
Dn Slope=0.005
Boundary for River Rch & Prof#=SALT CREEK 1,Reach-1         , 4
Up Type= 0
Dn Type= 3
Dn Slope=0.005
Boundary for River Rch & Prof#=SALT CREEK 1,Reach-1         , 5
Up Type= 0
Dn Type= 3
Dn Slope=0.005
Boundary for River Rch & Prof#=SALT CREEK 1,Reach-1         , 6
Up Type= 0
Dn Type= 3
Dn Slope=0.005
Boundary for River Rch & Prof#=SALT CREEK 1,Reach-1         , 7
Up Type= 0
Dn Type= 3
Dn Slope=0.005
DSS Import GetInterval= 0
DSS Import GetPeak= 0
DSS Import FillOption= 0

--- SALT CREEK 1.g01 (geometry) ---

Geom Title=Existing Conditions
Program Version=4.10

River Reach=SALT CREEK 1    ,Reach-1
Reach XY= 30
      3493422.75       10600619.        3494383.       10604409.
      3495023.25       10604948.      3494769.25       10605891.
      3496224.25       10607337.      3495959.75       10607963.
       3496329.5       10608279.      3496765.75       10607988.
      3497013.25       10608893.      3497478.75       10608492.
       3498066.5       10609866.        3498460.       10609511.
      3498814.75       10609898.       3498682.5       10610276.
        3499024.       10609870.      3499871.25       10610325.
        3499913.       10610775.      3500920.25       10610530.
        3501616.       10610903.        3502355.       10610413.
       3502802.5       10609407.        3503578.       10609397.
        3504596.       10608494.      3504611.25       10607724.
      3505635.75       10607623.      3505612.75       10607206.
      3506068.75       10607298.        3506461.       10606653.
       3506584.5       10607059.       3507719.5       10606730.

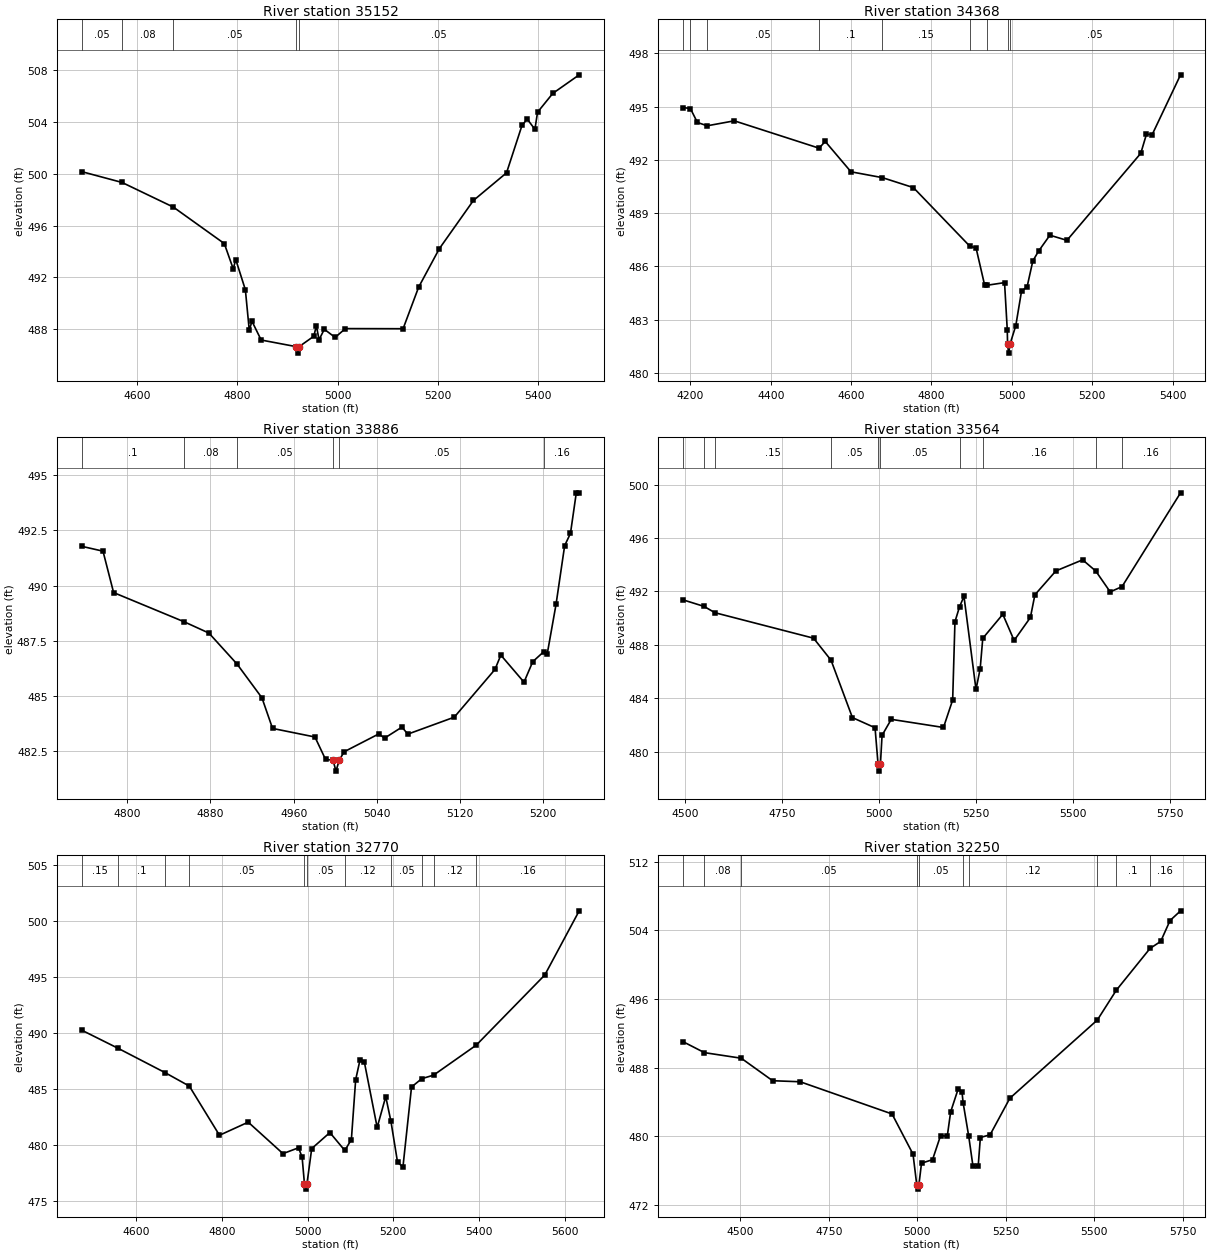
Type RM Length L Ch R = 1 ,35152   ,784,784,784
BEGIN DESCRIPTION:
SALT CREEK 1 60.0
END DESCRIPTION:
XS GIS Cut Line= 3
      3492868.74      10600702.6      3493465.96     10600893.57
      3493820.13     10600803.29
#Sta/Elev= 30
  4489.6  500.15  4569.8  499.32  4672.3  497.42    4774  494.61  4791.7  492.67
  4796.9  493.37    4816  491.05  4823.8  487.92  4829.1  488.63  4847.5  487.18
  4917.3  486.67  4920.1  486.17  4923.3  486.67  4952.5  487.47  4957.7  488.28
    4963   487.2  4973.5  488.01  4995.1  487.38  5015.5  488.06  5130.7  488.05
  5161.7  491.25  5202.9  494.21    5271  497.93  5337.1  500.06    5368  503.72
  5378.4   504.2  5393.7  503.41    5399  504.73  5429.4  506.18  5482.1  507.61
#Mann= 5 ,-1 , 0
  4489.6     .05       0  4569.8     .08       0  4672.3     .05       0
  4917.3    .035       0  4923.3     .05       0
Bank Sta=4917.3,4923.3
XS Rating Curve= 0 ,0
Exp/Cntr=0.3,0.1

Type RM Length L Ch R = 1 ,34368   ,482,482,482
BEGIN DESCRIPTION:
SALT CREEK 1 59.0
END DESCRIPTION:
XS GIS Cut Line= 3
      3492849.59     10602060.21      3493449.61     10601510.19
      3493749.58     10601210.21
#Sta/Elev= 30
  4181.8  494.95  4199.9  494.89  4217.3  494.11  4241.6  493.92  4309.2   494.2
  4520.2  492.66  4535.5  493.04  4599.6  491.33    4678     491    4755  490.44
  4895.5  487.14    4911  487.04    4932  484.98    4938  484.94  4981.9  485.09
  4988.7  482.42  4989.4  481.62  4992.1  481.12  4995.4  481.62  5009.9  482.67
  5024.1   484.6  5038.2  484.87  5052.3  486.31  5066.5  486.86  5094.8  487.76
  5137.2  487.47    5321  492.37  5335.2  493.45  5349.3  493.42    5420  496.79
#Mann= 9 ,-1 , 0
  4181.8      .1       0  4199.9     .08       0  4241.6     .05       0
  4520.2      .1       0    4678     .15       0  4895.5      .1       0
    4938     .05       0  4989.4    .035       0  4995.4     .05       0
Bank Sta=4989.4,4995.4
XS Rating Curve= 0 ,0
Exp/Cntr=0.3,0.1

Type RM Length L Ch R = 1 ,33886   ,322,322,322
BEGIN DESCRIPTION:
SALT CREEK 1 58.0
END DESCRIPTION:
XS GIS Cut Line= 3
      3493399.64     10601810.18      3493649.61     10601760.19
      3493849.59      10601660.2
#Sta/Elev= 30
  4756.2  491.78  4776.6  491.56  4786.8  489.68  4854.8  488.35  4878.5  487.84
  4905.6  486.43  4929.5   484.9  4939.7  483.51  4980.5  483.12  4990.7   482.1
  4997.9  482.07  5000.7  481.57  5003.9  482.07  5008.6  482.45  5041.9  483.26
  5047.5  483.07  5064.2  483.57  5069.8  483.25  5114.5  484.02  5153.7  486.19
  5159.3  486.84  5181.6  485.61    5190  486.54  5200.5  486.99    5204  486.91
  5212.4  489.14  5220.7  491.81  5226.3  492.37  5231.9  494.21  5234.7  494.21
#Mann= 6 ,-1 , 0
  4756.2      .1       0  4854.8     .08       0  4905.6     .05       0
  4997.9    .035       0  5003.9     .05       0  5200.5     .16       0
Bank Sta=4997.9,5003.9
XS Rating Curve= 0 ,0
Exp/Cntr=0.3,0.1

Type RM Length L Ch R = 1 ,33564   ,794,794,794
BEGIN DESCRIPTION:
SALT CREEK 1 57.0
END DESCRIPTION:
XS GIS Cut Line= 2
      3493233.36     10602195.64      3494415.94     10601696.25
#Sta/Elev= 30
  4494.6  491.37  4548.7  490.88  4576.5  490.41  4831.2   488.5  4876.3  486.85
  4931.5  482.55  4989.9  481.79  4997.7  479.04  5000.5  478.54  5003.7  479.04
    5008  481.22  5031.7  482.42  5166.5  481.81  5190.2  483.87  5196.1  489.73
    5208  490.86  5219.4  491.63  5250.4  484.66  5261.2  486.21  5267.9  488.49
  5319.6  490.29  5348.8  488.33  5390.8  490.05  5402.4  491.75  5456.6  493.54
  5525.6  494.37  5559.5  493.53  5596.7  491.97  5627.2  492.36  5778.3  499.39
#Mann= 10 ,-1 , 0
  4494.6     .05       0  4548.7     .16       0  4576.5     .15       0
  4876.3     .05       0  4997.7    .035       0  5003.7     .05       0
    5208     .12       0  5267.9     .16       0  5559.5     .12       0
  5627.2     .16       0
Bank Sta=4997.7,5003.7
XS Rating Curve= 0 ,0
Exp/Cntr=0.3,0.1

Type RM Length L Ch R = 1 ,32770   ,520,520,520
BEGIN DESCRIPTION:
SALT CREEK 1 56.0
END DESCRIPTION:
XS GIS Cut Line= 3
      3493399.61     10602260.19      3493899.61     10602510.19
      3494499.62     10602460.19
#Sta/Elev= 30
  4472.7  490.29  4558.2  488.66  4666.7  486.51  4723.7   485.3  4794.1  480.91
  4861.2  482.08  4942.3  479.27  4978.6  479.79    4987  478.96  4992.4   476.6
  4995.1   476.1  4998.4   476.6  5009.4  479.72  5051.8  481.15  5086.7  479.55
    5102  480.53    5112  485.87    5122  487.61  5132.1  487.48  5162.2  481.61
  5182.2  484.36  5194.4  482.14  5209.8  478.49  5222.4  478.09  5242.4  485.22
  5266.2  485.96    5294  486.28  5393.6  488.96  5553.5  495.22  5633.8  500.95
#Mann= 11 ,-1 , 0
  4472.7     .15       0  4558.2      .1       0  4666.7     .16       0
  4723.7     .05       0  4992.4     .03       0  4998.4     .05       0
  5086.7     .12       0  5194.4     .05       0  5266.2     .16       0
    5294     .12       0  5393.6     .16       0
Bank Sta=4992.4,4998.4
XS Rating Curve= 0 ,0
Exp/Cntr=0.3,0.1

Type RM Length L Ch R = 1 ,32250   ,376,376,376
BEGIN DESCRIPTION:
SALT CREEK 1 55.0
END DESCRIPTION:
XS GIS Cut Line= 2
      3493291.91     10603005.12      3494643.52     10602617.09
#Sta/Elev= 30
  4338.1  491.02  4398.3  489.75  4502.4   489.1  4591.1  486.48  4668.9  486.36
  4928.7  482.61    4988  477.93  4998.6  474.36  5001.3  473.86  5004.6  474.36
    5012  476.88  5043.2  477.29  5065.9  480.09  5084.8  480.02  5094.4  482.85
    5116  485.57  5126.4  485.19  5129.6  483.93  5145.4  480.04  5157.6   476.5
  5172.3  476.57  5178.4  479.87    5206  480.19  5261.7  484.44  5509.1  493.55
  5562.6  497.01    5658  501.88  5688.2   502.7  5714.6  505.13  5744.3  506.26
#Mann= 10 ,-1 , 0
  4338.1      .1       0  4398.3     .08       0  4502.4     .05       0
  4998.6     .03       0  5004.6     .05       0  5129.6     .16       0
  5145.4     .12       0  5509.1     .16       0  5562.6      .1       0
    5658     .16       0
Bank Sta=4998.6,5004.6
XS Rating Curve= 0 ,0
Exp/Cntr=0.3,0.1

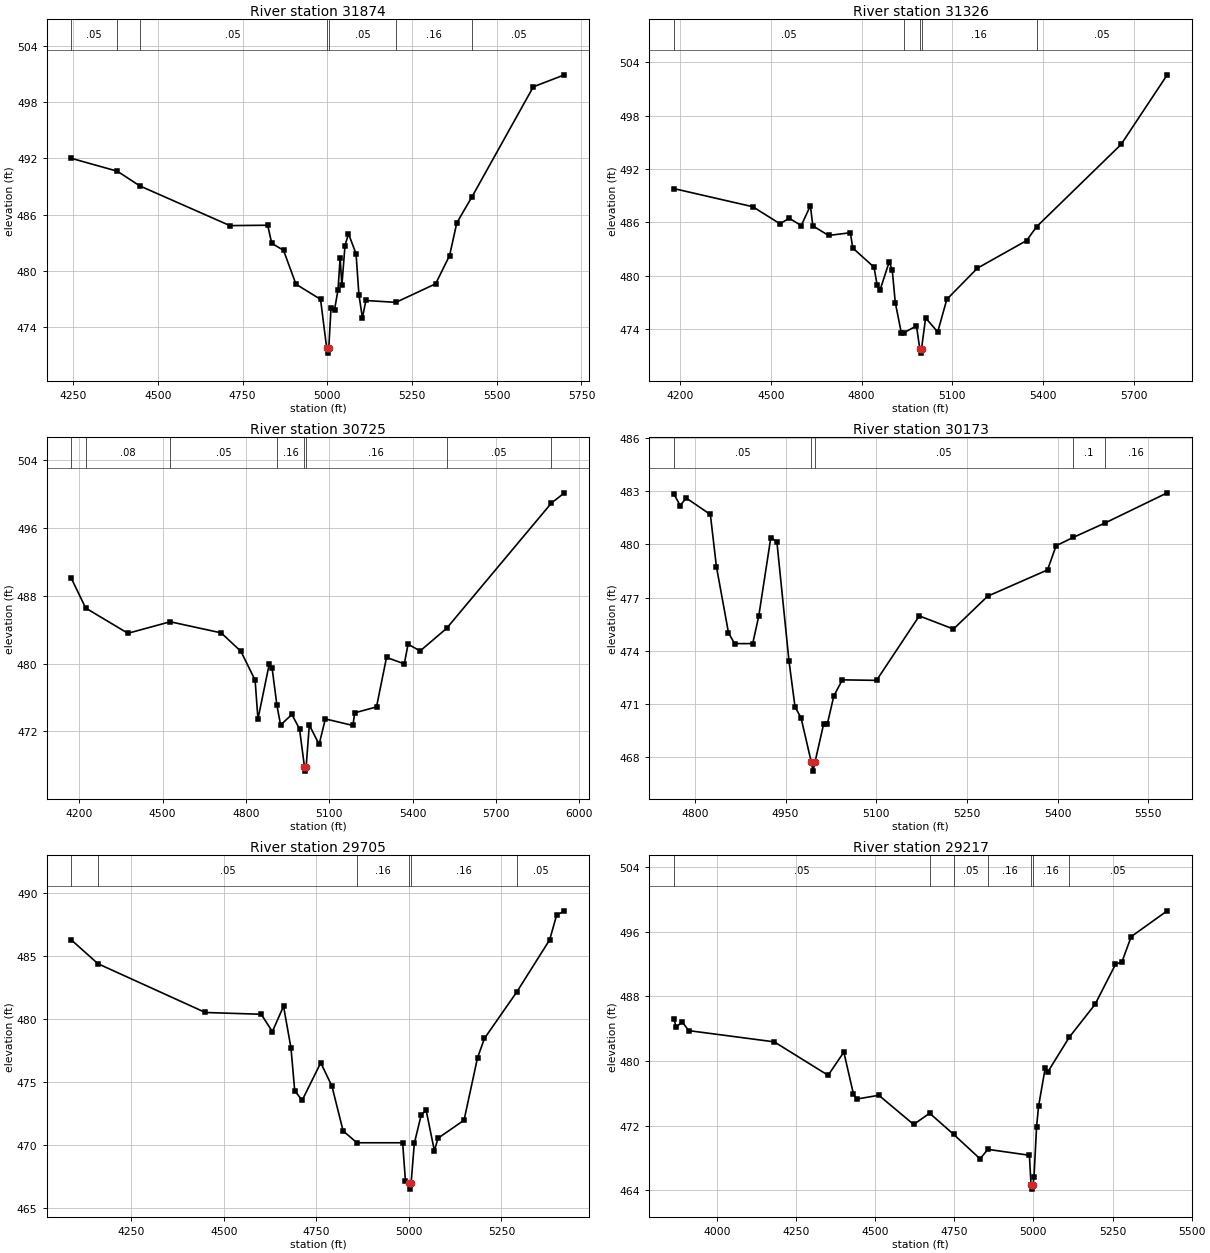
Type RM Length L Ch R = 1 ,31874   ,548,548,548
BEGIN DESCRIPTION:
SALT CREEK 1 54.0
END DESCRIPTION:
XS GIS Cut Line= 2
       3493304.9     10603322.84      3494719.01     10602979.07
#Sta/Elev= 30
  4244.5  491.99  4380.1  490.62  4446.7  489.05  4712.5  484.82  4823.9  484.86
  4835.9  482.94  4870.8  482.18  4907.4  478.58    4980  476.96  4998.2  471.73
  5000.9  471.23  5004.2  471.73  5010.9  476.06  5021.2  475.86  5031.5  477.96
  5037.8   481.4  5042.9  478.44  5052.1  482.68  5062.4  483.95  5084.7  481.83
  5093.2  477.45  5103.5  474.99  5113.8  476.84  5202.5  476.64  5319.6  478.62
  5360.8  481.63    5382  485.11  5427.4  487.92  5607.8  499.61  5699.8  500.89
#Mann= 7 ,-1 , 0
  4244.5     .05       0  4380.1      .1       0  4446.7     .05       0
  4998.2    .035       0  5004.2     .05       0  5202.5     .16       0
  5427.4     .05       0
Bank Sta=4998.2,5004.2
XS Rating Curve= 0 ,0
Exp/Cntr=0.3,0.1

Type RM Length L Ch R = 1 ,31326   ,601,601,601
BEGIN DESCRIPTION:
SALT CREEK 1 53.0
END DESCRIPTION:
XS GIS Cut Line= 3
      3493460.18     10603604.54      3494435.84      10603521.2
       3494938.9     10603104.88
#Sta/Elev= 30
  4179.2   489.8  4439.6  487.77  4529.9  485.85    4560  486.48  4600.2  485.65
  4630.3  487.89  4638.4  485.62  4690.5  484.54  4762.4  484.85  4770.8  483.13
    4841  480.98  4851.1     479  4861.1  478.44  4891.2  481.57  4901.2  480.67
  4911.3  477.01  4931.4  473.59  4939.9  473.62  4981.5  474.39  4992.3  471.83
  4995.1  471.33  4998.3  471.83  5011.6  475.28  5051.8  473.71  5081.9  477.37
  5183.2  480.87  5345.9  483.97  5379.2  485.53  5658.6  494.76  5811.4  502.58
#Mann= 5 ,-1 , 0
  4179.2     .05       0  4939.9     .16       0  4992.3     .07       0
  4998.3     .16       0  5379.2     .05       0
Bank Sta=4992.3,4998.3
XS Rating Curve= 0 ,0
Exp/Cntr=0.3,0.1

Type RM Length L Ch R = 1 ,30725   ,552,552,552
BEGIN DESCRIPTION:
SALT CREEK 1 52.0
END DESCRIPTION:
XS GIS Cut Line= 3
      3493549.63     10604160.19      3494349.61     10604010.19
      3494949.61     10603260.18
#Sta/Elev= 30
  4171.7  490.06  4223.3  486.55  4375.2  483.57  4527.5  484.93  4710.9  483.62
  4782.1  481.43    4833  478.03  4843.2  473.44  4883.9  479.94  4894.1  479.47
  4911.5  475.07  4924.6  472.74  4965.3  473.99  4992.8  472.28  5010.6   467.8
  5013.4   467.3  5016.6   467.8    5028  472.74  5063.3  470.45  5085.7  473.46
  5184.9  472.69  5191.3  474.18  5269.8  474.88  5305.8  480.72  5369.8  479.96
  5383.4  482.29  5426.6  481.48  5521.9  484.15  5899.1  498.94  5946.1  500.15
#Mann= 8 ,-1 , 0
  4171.7      .1       0  4223.3     .08       0  4527.5     .05       0
  4911.5     .16       0  5010.6     .07       0  5016.6     .16       0
  5521.9     .05       0  5899.1     .16       0
Bank Sta=5010.6,5016.6
XS Rating Curve= 0 ,0
Exp/Cntr=0.3,0.1

Type RM Length L Ch R = 1 ,30173   ,468,468,468
BEGIN DESCRIPTION:
SALT CREEK 1 51.0
END DESCRIPTION:
XS GIS Cut Line= 3
      3494149.59     10604410.19      3494399.61     10604410.19
      3494799.61     10604010.19
#Sta/Elev= 30
  4765.7  482.82  4775.7  482.18  4785.7  482.61  4825.7  481.68  4835.7  478.75
  4855.7  475.02  4865.7  474.41  4895.7  474.41  4905.7  475.95  4925.7  480.38
  4935.7  480.15  4955.7  473.45  4965.7  470.85  4975.7  470.23  4992.7  467.73
  4995.5  467.23  4998.7  467.73  5013.2   469.9  5019.3   469.9  5029.9  471.46
    5044  472.37  5100.6  472.34  5171.3  475.97  5227.8  475.23  5284.4  477.08
  5383.4  478.56  5397.6  479.92  5425.9  480.39  5477.8  481.19  5581.4   482.9
#Mann= 5 ,-1 , 0
  4765.7     .05       0  4992.7     .07       0  4998.7     .05       0
  5425.9      .1       0  5477.8     .16       0
Bank Sta=4992.7,4998.7
XS Rating Curve= 0 ,0
Exp/Cntr=0.3,0.1

Type RM Length L Ch R = 1 ,29705   ,488,488,488
BEGIN DESCRIPTION:
SALT CREEK 1 50.0
END DESCRIPTION:
XS GIS Cut Line= 3
      3493799.64     10604810.19      3494699.61     10604710.19
       3495099.6     10604560.19
#Sta/Elev= 30
  4087.7  486.24  4159.7  484.35  4449.9  480.48  4600.8  480.34    4631  478.96
  4661.2  480.98  4681.3  477.66  4691.4  474.27  4711.5  473.51  4761.8  476.49
    4792  474.63  4822.2  471.08  4859.5  470.14  4983.1  470.14  4990.7  467.07
    5000  466.96  5002.7  466.46    5006  466.96  5014.6  470.09  5033.3  472.36
  5046.6  472.71  5068.9   469.5  5078.6   470.5    5149  471.93  5185.4  476.88
  5204.1  478.42    5292  482.13  5380.4  486.25  5399.1   488.2  5420.4  488.55
#Mann= 6 ,-1 , 0
  4087.7      .1       0  4159.7     .05       0  4859.5     .16       0
    5000     .07       0    5006     .16       0    5292     .05       0
Bank Sta=5000,5006
XS Rating Curve= 0 ,0
Exp/Cntr=0.3,0.1

Type RM Length L Ch R = 1 ,29217   ,614,614,614
BEGIN DESCRIPTION:
SALT CREEK 1 49.0
END DESCRIPTION:
XS GIS Cut Line= 3
      3493873.52     10604982.26      3494826.23     10604934.51
      3495305.21     10604566.07
#Sta/Elev= 30
  3864.6  485.24  3870.7  484.19  3890.7  484.83  3910.7  483.76  4181.1  482.37
  4351.3  478.23  4400.9   481.1  4431.4  475.91  4441.4  475.29  4511.5  475.76
  4621.6  472.15  4672.1  473.54  4748.3  470.91  4831.4   467.9  4856.1  469.07
  4987.3  468.34  4992.5  464.65  4995.2  464.15  4998.5  464.65  5001.8  465.65
    5010  471.89  5016.3  474.42  5037.2  479.12  5045.3  478.64  5113.6  482.96
  5194.8  487.01  5259.1  491.94  5279.9  492.29    5309  495.39  5422.8  498.58
#Mann= 7 ,-1 , 0
  3864.6     .05       0  4672.1     .16       0  4748.3     .05       0
  4856.1     .16       0  4992.5     .07       0  4998.5     .16       0
  5113.6     .05       0
Bank Sta=4992.5,4998.5
XS Rating Curve= 0 ,0
Exp/Cntr=0.3,0.1

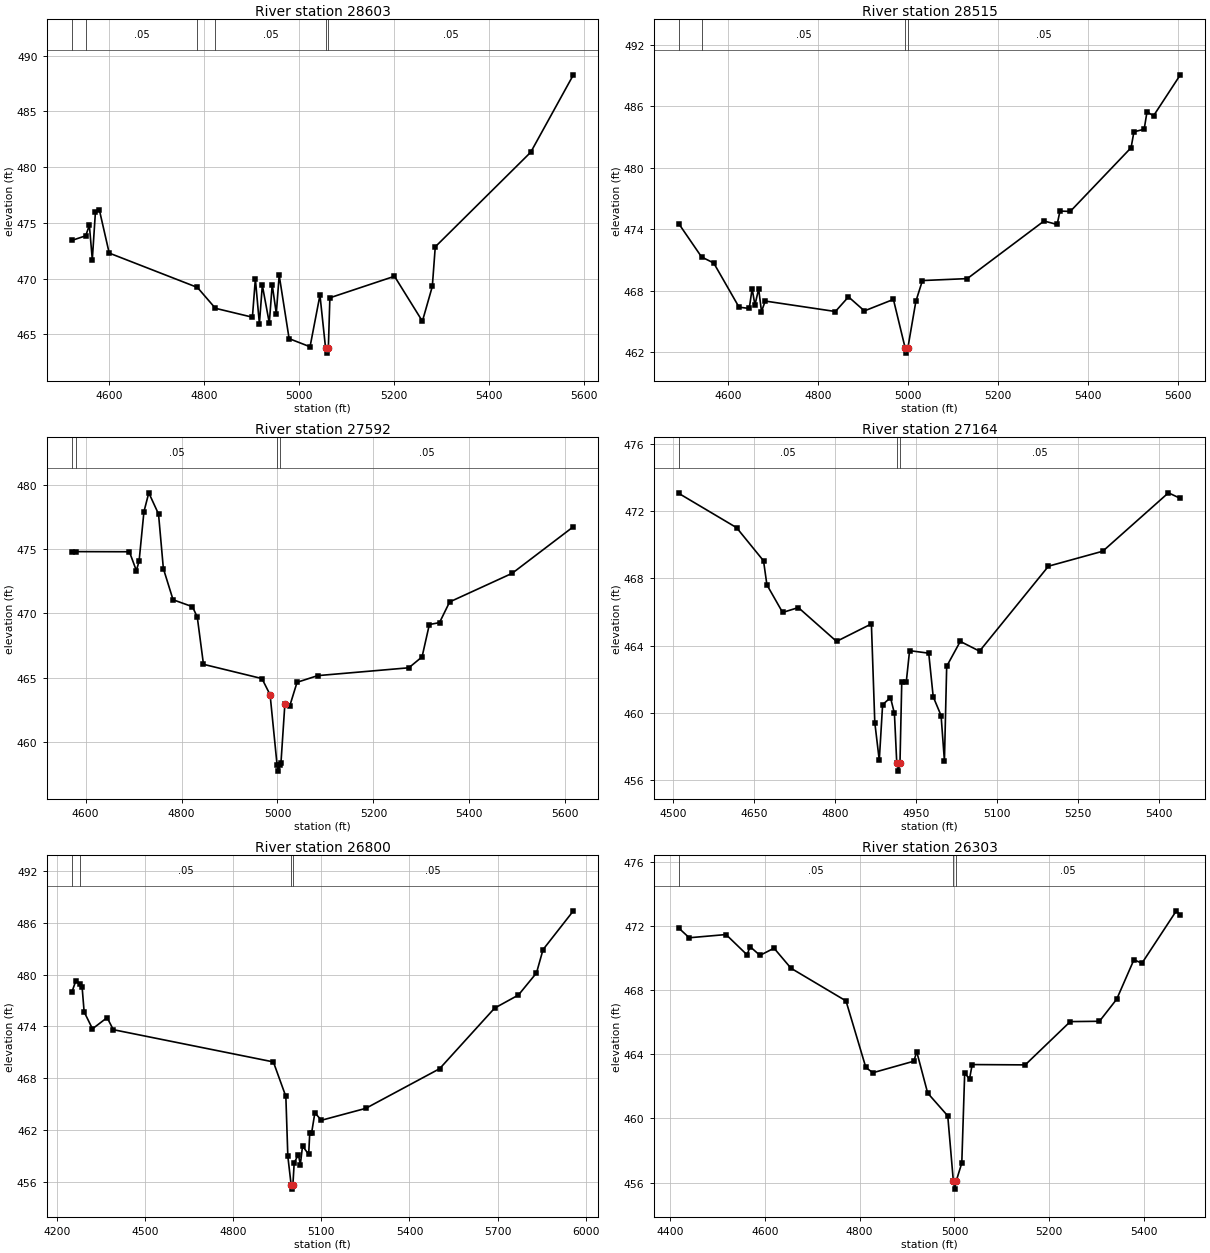
Type RM Length L Ch R = 1 ,28603   ,88,88,88
BEGIN DESCRIPTION:
SALT CREEK 1 48.0
END DESCRIPTION:
XS GIS Cut Line= 2
      3494559.49      10605670.6      3495178.49     10604814.06
#Sta/Elev= 30
  4521.9  473.42  4551.3  473.84    4559  474.78  4565.2  471.71  4571.8  475.99
  4579.9  476.19  4600.8  472.29  4786.6  469.21  4824.5  467.34  4902.5  466.54
  4908.7  469.97  4917.2  465.96  4923.4   469.4  4938.1  466.02  4944.2  469.46
  4952.8  466.87  4958.9   470.3  4979.8  464.62  5023.9  463.89  5044.8  468.52
  5056.5  463.82  5059.3  463.32  5062.5  463.82  5065.7  468.28  5201.8  470.21
  5260.6  466.18  5281.5   469.3  5287.7  472.85  5488.8  481.33  5578.7  488.27
#Mann= 6 ,-1 , 0
  4521.9     .08       0  4551.3     .05       0  4786.6      .1       0
  4824.5     .05       0  5056.5     .04       0  5062.5     .05       0
Bank Sta=5056.5,5062.5
XS Rating Curve= 0 ,0
Exp/Cntr=0.3,0.1

Type RM Length L Ch R = 1 ,28515   ,923,923,923
BEGIN DESCRIPTION:
SALT CREEK 1 47.0
END DESCRIPTION:
XS GIS Cut Line= 2
      3494595.96     10605745.24      3495269.58     10604856.34
#Sta/Elev= 30
    4490  474.54  4540.9  471.28  4567.9  470.69  4624.2  466.38  4646.9  466.26
  4653.3  468.19  4659.5  466.59  4667.8  468.17  4674.1  465.96  4682.4  466.98
  4838.4  465.96  4867.5  467.39  4902.9  466.02  4967.4  467.14  4993.5   462.4
  4996.2   461.9  4999.5   462.4  5017.3  466.95  5031.9  468.98  5131.7  469.17
  5302.3  474.79  5331.4  474.45  5337.7  475.76  5360.5  475.72  5495.8  481.94
  5502.1  483.49  5524.9  483.74  5531.2  485.44  5545.7  485.05  5605.3  489.05
#Mann= 4 ,-1 , 0
    4490     .08       0  4540.9     .05       0  4993.5     .04       0
  4999.5     .05       0
Bank Sta=4993.5,4999.5
XS Rating Curve= 0 ,0
Exp/Cntr=0.3,0.1

Type RM Length L Ch R = 1 ,27592   ,428,428,428
BEGIN DESCRIPTION:
SALT CREEK 1 46.0
END DESCRIPTION:
XS GIS Cut Line= 4
      3494410.65     10605955.84      3494803.02     10606013.13
      3494865.52     10605999.24      3495358.77     10605684.25
#Sta/Elev= 30
  4571.1  474.78  4579.3  474.81  4691.3   474.8  4705.8  473.33  4711.5  474.07
  4721.6  477.92  4731.7  479.39    4752  477.74  4762.1  473.49  4782.3  471.06
  4822.7  470.52  4832.8  469.71  4845.7  466.03  4967.6  464.92  4984.6  463.66
  4999.1  458.21  5001.9  457.71  5005.1  458.21  5007.2  458.32  5015.4  462.93
  5025.6  462.79  5040.8  464.63    5084  465.15  5273.8  465.76  5301.4  466.61
  5316.6  469.13  5337.8  469.28  5358.9  470.89  5489.2  473.12  5616.9  476.75
#Mann= 4 ,-1 , 0
  4571.1     .15       0  4579.3     .05       0  4999.1     .03       0
  5005.1     .05       0
Bank Sta=4984.6,5015.4
XS Rating Curve= 0 ,0
Exp/Cntr=0.3,0.1

Type RM Length L Ch R = 1 ,27164   ,364,364,364
BEGIN DESCRIPTION:
SALT CREEK 1 45.0
END DESCRIPTION:
XS GIS Cut Line= 3
       3494749.6      10606560.2      3495149.61     10606260.19
      3495399.59     10605910.21
#Sta/Elev= 30
    4510  473.05  4617.3  471.01  4667.3  469.04  4673.6  467.61  4702.7  465.97
  4731.9  466.26  4802.7  464.25  4867.3  465.29  4873.6  459.43  4881.9  457.18
  4888.1  460.49  4902.7  460.91    4910  459.97  4914.3  457.04  4917.1  456.54
  4920.3  457.04  4923.6  461.84  4931.9  461.82  4938.1   463.7  4973.6  463.55
  4981.9  460.96  4996.5  459.84  5002.7  457.15  5006.9  462.77  5032.1  464.25
  5067.8  463.67  5195.6  468.72  5296.3  469.61    5418  473.08  5440.1  472.75
#Mann= 3 ,-1 , 0
    4510     .05       0  4914.3     .03       0  4920.3     .05       0
Bank Sta=4914.3,4920.3
XS Rating Curve= 0 ,0
Exp/Cntr=0.3,0.1

Type RM Length L Ch R = 1 ,26800   ,497,497,497
BEGIN DESCRIPTION:
SALT CREEK 1 44.0
END DESCRIPTION:
XS GIS Cut Line= 3
      3494749.62     10607110.17      3495299.61     10606510.19
      3495699.59     10605710.23
#Sta/Elev= 30
    4250  477.94  4263.9  479.29  4279.4  478.89  4285.4  478.52  4292.2  475.68
  4320.6  473.72  4370.5  475.02  4391.5  473.62  4936.6  469.88  4979.1  465.87
  4985.9  458.91  4997.1  455.62  4999.8  455.12  5003.1  455.62  5007.5  458.18
  5021.7  459.12  5028.5  457.97  5035.9  460.12  5056.8  459.16  5060.5  461.62
  5066.7  461.62  5077.9  463.97  5100.3  463.11  5251.2  464.49  5502.7  469.09
    5690  476.12  5771.1  477.64  5832.6   480.2  5854.9  482.91  5958.3  487.41
#Mann= 4 ,-1 , 0
    4250     .08       0  4279.4     .05       0  4997.1     .03       0
  5003.1     .05       0
Bank Sta=4997.1,5003.1
XS Rating Curve= 0 ,0
Exp/Cntr=0.3,0.1

Type RM Length L Ch R = 1 ,26303   ,455,455,455
BEGIN DESCRIPTION:
SALT CREEK 1 43.0
END DESCRIPTION:
XS GIS Cut Line= 3
      3495249.62     10606960.18      3495749.61     10606610.19
      3496149.59      10606410.2
#Sta/Elev= 30
  4418.6  471.88  4440.8  471.27  4518.4  471.47  4562.9   470.2    4569  470.72
  4589.9  470.17  4619.6  470.62  4655.3  469.37  4771.3  467.33  4813.1  463.18
  4827.9  462.85  4914.3  463.57  4920.4  464.16  4943.5  461.58  4985.8  460.16
  4997.6  456.09  5000.3  455.59  5003.6  456.09  5015.4  457.22  5021.5  462.83
  5031.7  462.46  5037.3  463.36  5149.1  463.34  5244.1  466.04  5305.6  466.06
    5342  467.44  5378.3   469.9  5395.1  469.68  5467.7  472.95  5476.1  472.68
#Mann= 3 ,-1 , 0
  4418.6     .05       0  4997.6     .03       0  5003.6     .05       0
Bank Sta=4997.6,5003.6
XS Rating Curve= 0 ,0
Exp/Cntr=0.3,0.1

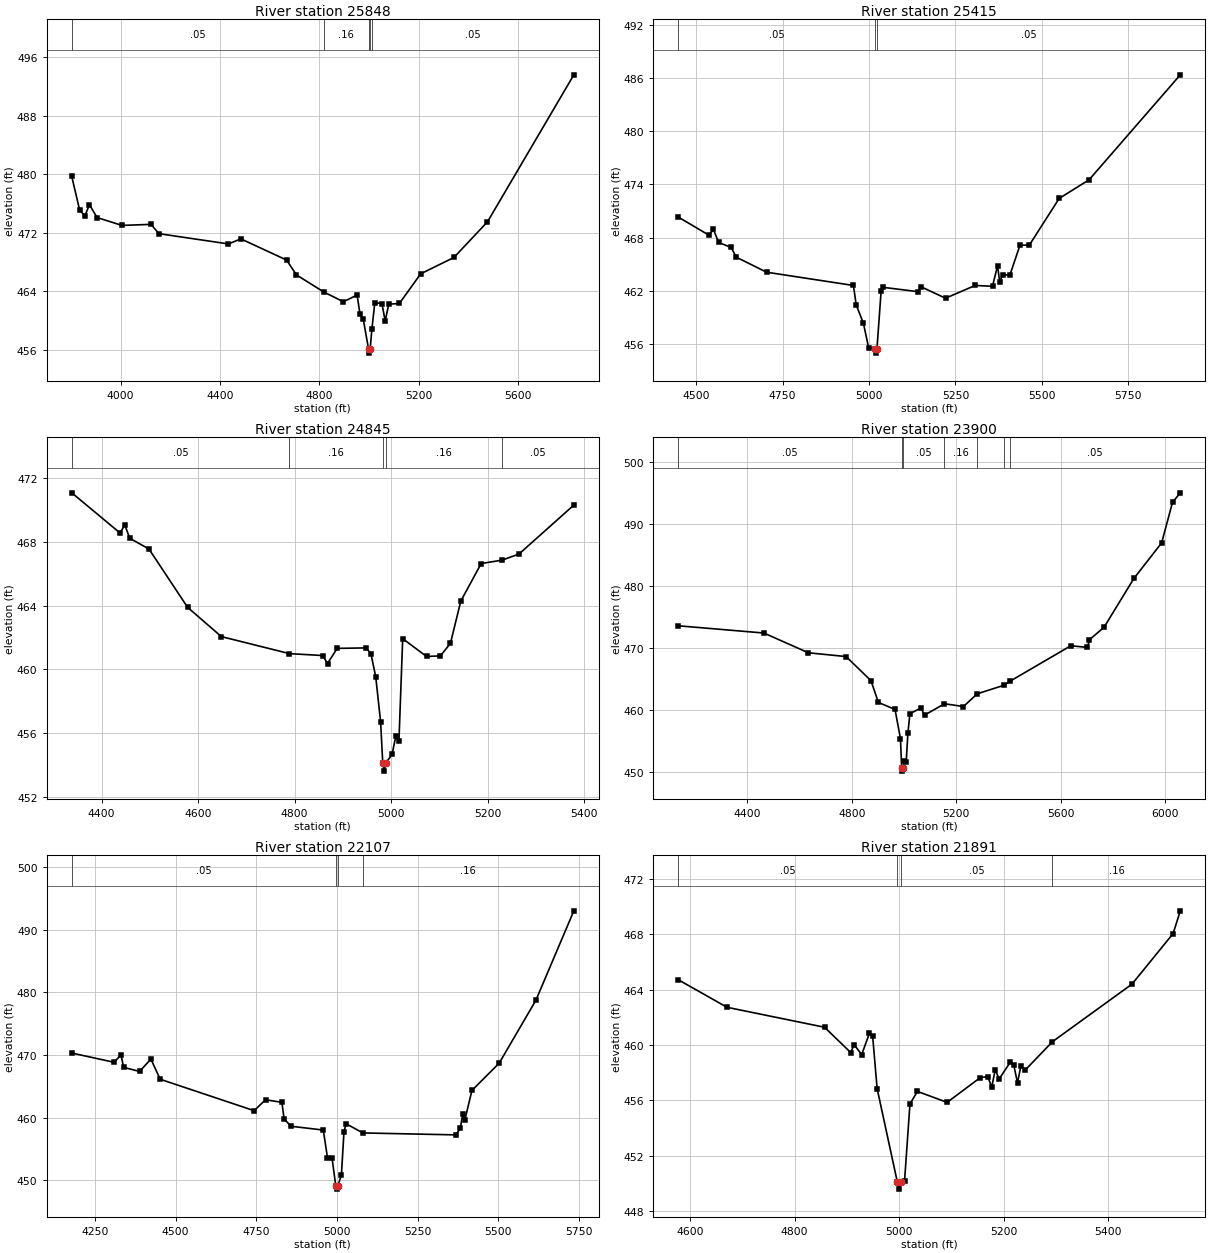
Type RM Length L Ch R = 1 ,25848   ,433,433,433
BEGIN DESCRIPTION:
SALT CREEK 1 42.0
END DESCRIPTION:
XS GIS Cut Line= 3
      3494799.59      10607310.2      3495899.61     10606910.19
      3496549.64     10606360.17
#Sta/Elev= 30
  3803.4  479.69  3835.3  475.07  3856.6  474.33  3874.6  475.85  3905.2  474.08
  4005.6  473.01  4122.6  473.15  4154.6  471.88  4434.5  470.48  4484.4  471.17
  4668.6  468.28  4707.9  466.26  4819.2   463.9  4897.4  462.59  4952.6   463.5
  4963.9  460.96  4977.2  460.23  4998.9  456.07  5001.6  455.57  5004.9  456.07
  5012.3  458.92  5023.9  462.47  5052.5  462.34  5065.6  459.96  5079.9  462.25
  5122.8  462.35  5208.5   466.4  5342.5  468.63  5477.6   473.5  5825.4  493.57
#Mann= 5 ,-1 , 0
  3803.4     .05       0  4819.2     .16       0  4998.9     .07       0
  5004.9     .16       0  5012.3     .05       0
Bank Sta=4998.9,5004.9
XS Rating Curve= 0 ,0
Exp/Cntr=0.3,0.1

Type RM Length L Ch R = 1 ,25415   ,570,570,570
BEGIN DESCRIPTION:
SALT CREEK 1 41.0
END DESCRIPTION:
XS GIS Cut Line= 3
      3495535.74     10607508.64      3496091.32     10607144.04
      3496555.15     10606506.81
#Sta/Elev= 30
  4448.1  470.32  4536.5  468.28    4550  468.92  4565.1  467.45  4601.2  466.88
  4616.3  465.78  4703.7  464.09  4955.1  462.59  4962.9  460.41    4984  458.31
  4999.1  455.53  5017.1  455.45  5019.9  454.95  5023.1  455.45  5035.2  461.99
  5041.2  462.38  5142.1  461.89  5150.3  462.45  5221.4  461.15  5307.1  462.59
  5357.4   462.5    5372  464.82  5378.2  462.99  5386.7   463.8  5407.6  463.76
  5436.9  467.14    5464  467.15  5550.3  472.42  5636.9  474.53  5900.8  486.38
#Mann= 3 ,-1 , 0
  4448.1     .05       0  5017.1     .03       0  5023.1     .05       0
Bank Sta=5017.1,5023.1
XS Rating Curve= 0 ,0
Exp/Cntr=0.3,0.1

Type RM Length L Ch R = 1 ,24845   ,945,945,945
BEGIN DESCRIPTION:
SALT CREEK 1 40.0
END DESCRIPTION:
XS GIS Cut Line= 3
      3495549.61     10607610.19      3496199.61     10607610.19
       3496499.6      10607360.2
#Sta/Elev= 30
  4338.2  471.09  4438.2  468.57  4448.2  469.07  4458.2  468.24  4498.2  467.56
  4578.2   463.9  4648.2  462.06  4789.4  460.99  4858.2  460.87  4868.2  460.37
  4888.2  461.32  4948.2  461.35  4958.2  460.98  4968.2  459.52  4978.2  456.72
  4982.7  454.11  4985.5  453.61  4988.7  454.11  5001.9  454.66  5009.7  455.79
  5016.2  455.48    5024  461.93  5073.5  460.81  5102.1  460.85  5122.9  461.63
  5144.4  464.29  5186.7  466.65  5229.7  466.86  5264.8  467.24  5378.7  470.32
#Mann= 5 ,-1 , 0
  4338.2     .05       0  4789.4     .16       0  4982.7     .07       0
  4988.7     .16       0  5229.7     .05       0
Bank Sta=4982.7,4988.7
XS Rating Curve= 0 ,0
Exp/Cntr=0.3,0.1

Type RM Length L Ch R = 1 ,23900   ,1793,1793,1793
BEGIN DESCRIPTION:
SALT CREEK 1 39.0
END DESCRIPTION:
XS GIS Cut Line= 3
      3495392.58     10608107.59      3496030.55     10608159.67
      3496868.21     10607187.46
#Sta/Elev= 30
    4135  473.62  4463.1  472.45  4633.7  469.26  4778.1  468.65  4873.3  464.76
  4901.8  461.24  4965.5  460.11  4986.3   455.4    4991  450.65  4993.7  450.15
    4997  450.65  5000.6  451.81  5008.3  451.63  5014.9  456.33  5022.5  459.43
  5064.8  460.34  5078.5  459.19  5154.9  461.03  5227.7  460.58  5280.1  462.63
  5382.4  464.01  5405.3  464.65  5639.1   470.4  5702.8  470.12  5710.4  471.37
  5766.4  473.39  5880.5  481.26  5986.9  487.01  6028.6  493.56  6058.4  495.09
#Mann= 7 ,-1 , 0
    4135     .05       0    4991    .035       0    4997     .05       0
  5154.9     .16       0  5280.1     .05       0  5382.4     .16       0
  5405.3     .05       0
Bank Sta=4991,4997
XS Rating Curve= 0 ,0
Exp/Cntr=0.3,0.1

Type RM Length L Ch R = 1 ,22107   ,216,216,216
BEGIN DESCRIPTION:
SALT CREEK 1 37.0
END DESCRIPTION:
XS GIS Cut Line= 3
      3496191.98     10608927.77       3496900.3     10608358.33
      3497329.53     10607873.72
#Sta/Elev= 30
  4178.2   470.3  4309.9  468.82  4330.8  470.06  4338.7  468.02  4388.3  467.37
  4423.5  469.33  4452.3  466.12  4743.5  461.11  4778.7  462.85  4829.5  462.44
  4836.3  459.83  4857.1  458.63  4957.8  458.02  4970.7  453.64  4985.1  453.49
  4996.5   449.1  4999.3   448.6  5002.5   449.1  5013.9   450.8  5021.9  457.73
  5028.3  459.03  5080.5  457.56  5368.4  457.25  5382.6  458.29  5390.1  460.64
  5396.8  459.67  5418.5  464.34    5503  468.69  5616.8  478.72  5734.4  492.98
#Mann= 4 ,-1 , 0
  4178.2     .05       0  4996.5    .035       0  5002.5     .05       0
  5080.5     .16       0
Bank Sta=4996.5,5002.5
XS Rating Curve= 0 ,0
Exp/Cntr=0.3,0.1

Type RM Length L Ch R = 1 ,21891   ,1388,1388,1388
BEGIN DESCRIPTION:
SALT CREEK 1 36.0
END DESCRIPTION:
XS GIS Cut Line= 3
      3496549.64     10608860.17      3496899.61     10608610.19
      3497249.62     10608210.18
#Sta/Elev= 30
    4577  464.71  4670.4  462.72  4857.2  461.28  4907.5  459.45  4913.7  460.03
  4928.4  459.31  4943.2  460.85  4949.3  460.66  4957.9  456.86  4996.7   450.1
  4999.5   449.6  5002.7   450.1  5010.4  450.16  5020.8  455.75  5035.1  456.65
    5092  455.86  5155.6  457.65  5169.9  457.71  5177.4  456.96  5184.1  458.21
  5191.7  457.55  5212.6  458.74  5219.7  458.54  5226.8  457.27  5233.4  458.52
    5241  458.17  5293.8  460.24    5446  464.39  5524.8  468.04  5538.6  469.68
#Mann= 4 ,-1 , 0
    4577     .05       0  4996.7    .035       0  5002.7     .05       0
  5293.8     .16       0
Bank Sta=4996.7,5002.7
XS Rating Curve= 0 ,0
Exp/Cntr=0.3,0.1