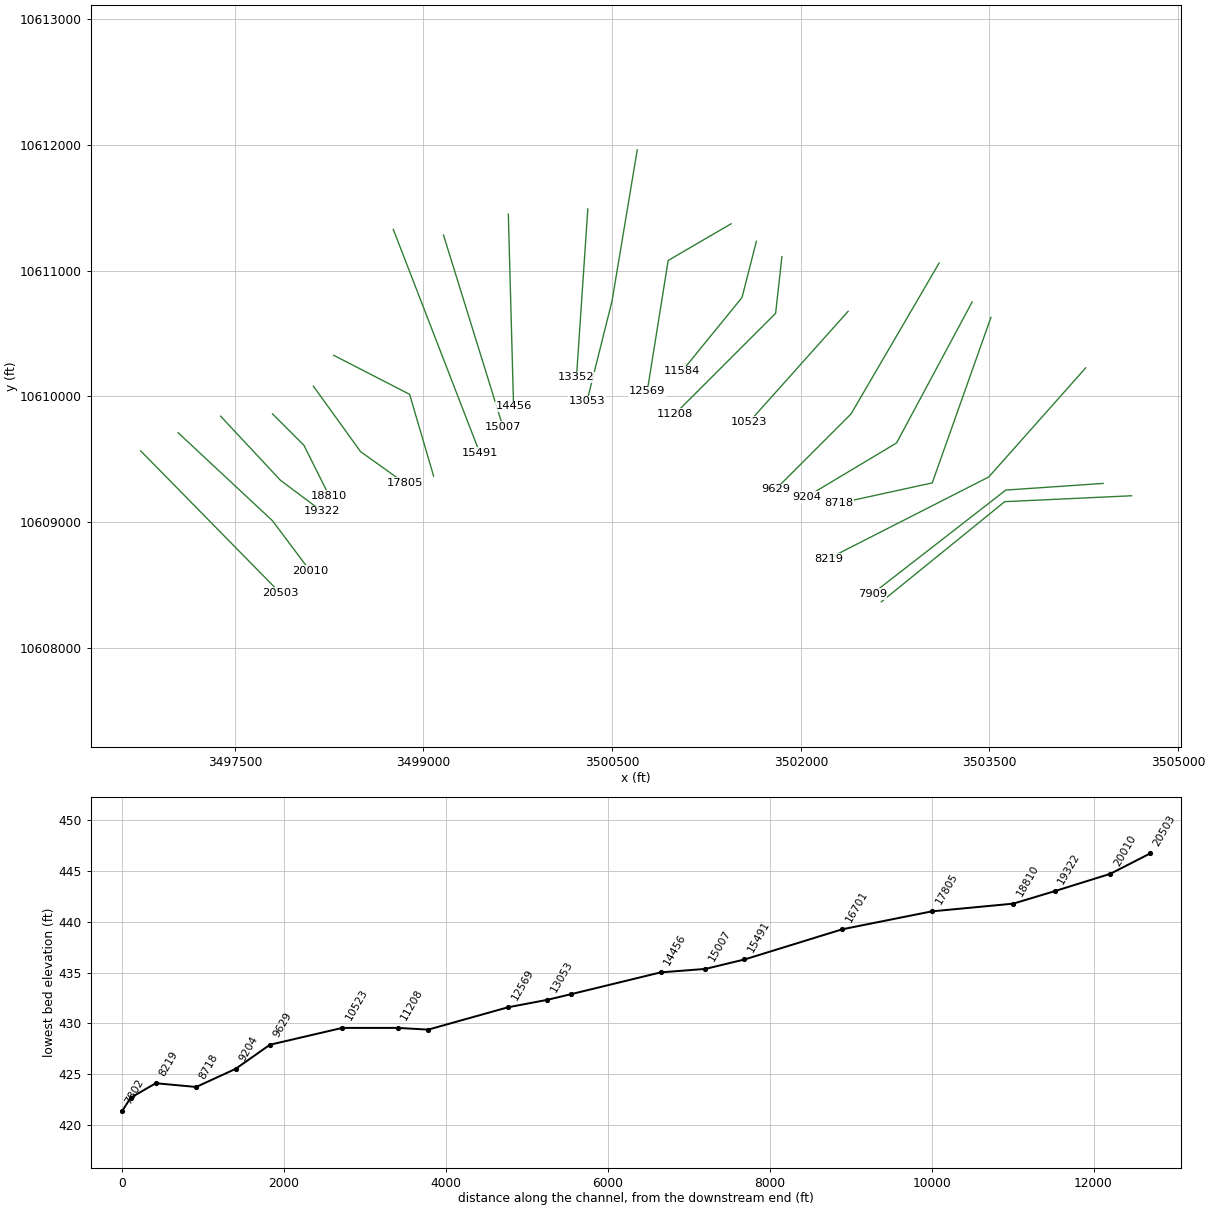
HEC-RAS study SALT CREEK 1.prj: SALT CREEK 1 Base Level Engineering

--- SALT CREEK 1.g01 (geometry) --- (continued)

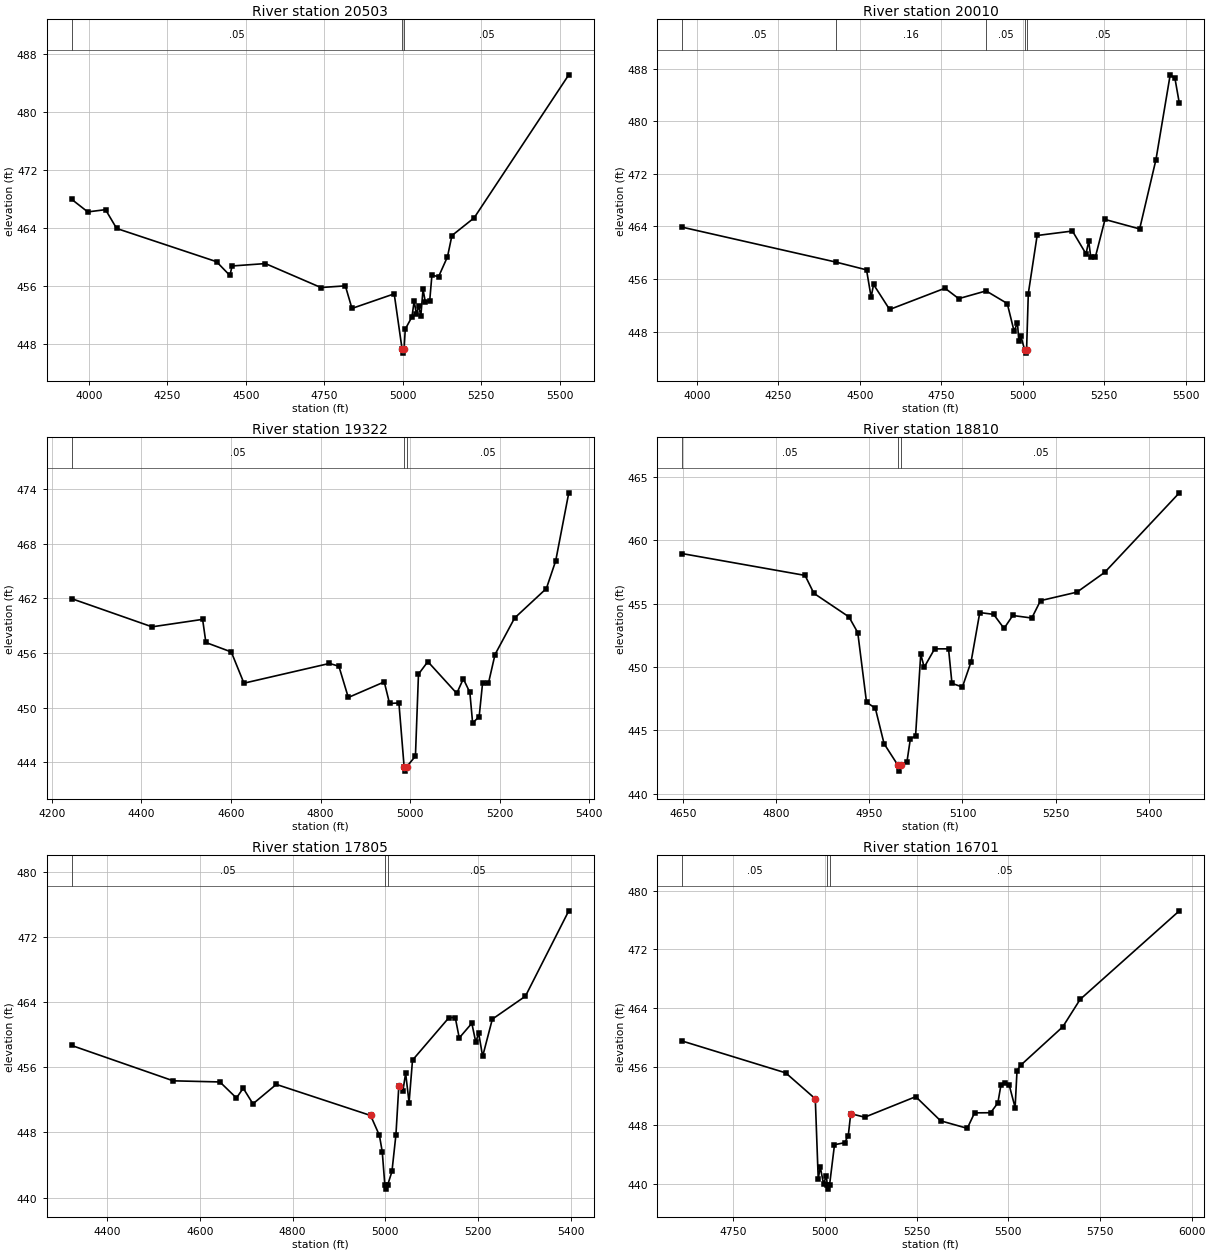
Type RM Length L Ch R = 1 ,20503   ,493,493,493
BEGIN DESCRIPTION:
SALT CREEK 1 35.0
END DESCRIPTION:
XS GIS Cut Line= 2
       3496751.9     10609565.71      3497861.28     10608435.49
#Sta/Elev= 30
  3945.3  467.95    3997   466.2  4053.6  466.51    4089  463.92  4407.2  459.34
  4449.6  457.44  4456.8  458.75  4562.8  459.08  4739.5  455.78  4817.4  456.01
  4838.5   452.9    4973  454.91  4998.3  447.24    5001  446.74  5004.3  447.24
  5008.3  450.06  5029.5  451.73  5036.6  453.93  5043.7  452.09  5050.7  453.25
  5057.8  451.85  5064.8  455.54    5072  453.81  5086.1  453.96  5093.1  457.48
  5114.4  457.28  5142.7  460.02  5156.8  462.94  5227.6  465.38    5529  485.09
#Mann= 3 ,-1 , 0
  3945.3     .05       0  4998.3    .035       0  5004.3     .05       0
Bank Sta=4998.3,5004.3
XS Rating Curve= 0 ,0
Exp/Cntr=0.3,0.1

Type RM Length L Ch R = 1 ,20010   ,688,688,688
BEGIN DESCRIPTION:
SALT CREEK 1 34.0
END DESCRIPTION:
XS GIS Cut Line= 3
       3497049.6      10609710.2      3497799.61     10609010.19
      3498099.59     10608610.21
#Sta/Elev= 30
  3954.8   463.9    4428  458.57  4520.8   457.4  4534.9  453.24  4542.3  455.18
  4591.6  451.37  4761.6  454.61  4803.6  453.02  4887.7   454.2  4952.6  452.28
  4973.6  448.07  4983.9  449.36    4988  446.65  4994.3  447.35  5005.9  445.23
  5008.6  444.73  5011.9  445.23  5017.2  453.79  5044.3  462.63  5152.6  463.31
  5194.3  459.83  5202.6  461.77  5208.9  459.33  5223.4  459.43  5252.6  465.07
  5358.9  463.63  5408.9  474.17  5452.6  487.08  5467.2  486.54  5480.7  482.74
#Mann= 5 ,-1 , 0
  3954.8     .05       0    4428     .16       0  4887.7     .05       0
  5005.9    .035       0  5011.9     .05       0
Bank Sta=5005.9,5011.9
XS Rating Curve= 0 ,0
Exp/Cntr=0.3,0.1

Type RM Length L Ch R = 1 ,19322   ,512,512,512
BEGIN DESCRIPTION:
SALT CREEK 1 33.0
END DESCRIPTION:
XS GIS Cut Line= 3
      3497387.32     10609841.74      3497863.89     10609331.32
      3498193.79     10609084.55
#Sta/Elev= 30
  4243.9  461.97  4423.7  458.87  4536.6  459.69  4543.9  457.15  4600.6  456.11
  4628.9  452.68  4819.9  454.85  4840.9  454.54  4861.9  451.11  4942.2  452.82
    4954  450.45  4974.9  450.51  4986.5  443.52  4989.2  443.02  4992.5  443.52
  5011.8  444.66  5018.6  453.67  5039.5  455.05  5104.1  451.56  5118.7  453.16
  5133.3  451.67  5139.5  448.31  5154.1     449  5161.7  452.69  5174.9  452.69
  5189.5  455.83  5233.3  459.84  5304.2  463.08    5325  466.12  5354.2  473.59
#Mann= 3 ,-1 , 0
  4243.9     .05       0  4986.5    .035       0  4992.5     .05       0
Bank Sta=4986.5,4992.5
XS Rating Curve= 0 ,0
Exp/Cntr=0.3,0.1

Type RM Length L Ch R = 1 ,18810   ,1005,1005,1005
BEGIN DESCRIPTION:
SALT CREEK 1 32.0
END DESCRIPTION:
XS GIS Cut Line= 3
      3497799.58     10609860.21      3498049.61     10609610.19
      3498249.61     10609210.19
#Sta/Elev= 30
  4648.5  458.94  4846.5  457.22  4860.7  455.81  4917.2  453.95  4931.4  452.71
  4945.5  447.22  4959.7  446.75  4973.8  443.95  4995.6  442.29  4998.3  441.79
  5001.6  442.29  5010.5  442.48  5016.1  444.33  5024.5  444.57  5032.8  451.01
  5038.4  449.98  5055.2  451.43  5077.6  451.43  5083.1  448.71  5099.9  448.42
  5113.9  450.41  5127.9  454.29  5150.2  454.15    5167  453.04    5181  454.06
  5211.7  453.86  5225.7  455.23  5284.4   455.9  5329.1  457.46  5449.3  463.73
#Mann= 3 ,-1 , 0
  4648.5     .05       0  4995.6    .035       0  5001.6     .05       0
Bank Sta=4995.6,5001.6
XS Rating Curve= 0 ,0
Exp/Cntr=0.3,0.1

Type RM Length L Ch R = 1 ,17805   ,1104,1104,1104
BEGIN DESCRIPTION:
SALT CREEK 1 31.0
END DESCRIPTION:
XS GIS Cut Line= 3
      3498124.76     10610080.51      3498499.61     10609560.19
      3498849.61     10609310.19
#Sta/Elev= 30
  4323.7  458.69  4542.8  454.34  4643.4   454.2    4679  452.23  4693.7  453.43
  4714.6  451.51  4764.9   453.9  4968.1  450.08  4987.1  447.63  4993.2  445.63
  4998.8  441.53  5001.6  441.03  5004.8  441.53  5014.1   443.2  5022.7  447.73
  5028.9   453.7  5037.5  453.04  5043.6  455.27    5051  451.67  5058.4  456.88
    5137  462.11  5150.5  462.12  5159.1  459.61  5186.2  461.41  5194.8  459.07
  5200.9  460.22  5209.5  457.34  5230.4  461.92  5301.7  464.74  5395.1  475.23
#Mann= 3 ,-1 , 0
  4323.7     .05       0  4998.8    .035       0  5004.8     .05       0
Bank Sta=4968.1,5028.9
XS Rating Curve= 0 ,0
Exp/Cntr=0.3,0.1

Type RM Length L Ch R = 1 ,16701   ,1210,1210,1210
BEGIN DESCRIPTION:
Mapping XS 846bd60a
END DESCRIPTION:
XS GIS Cut Line= 3
      3498286.46     10610326.18      3498889.75     10610015.86
      3499080.67     10609365.01
#Sta/Elev= 30
  4609.8  459.49  4892.5  455.14  4973.2   451.6  4981.2  440.68  4986.8  442.28
  4995.7  439.99  5003.4   441.1    5006  439.77  5008.8  439.27    5012  439.77
  5025.6  445.33  5053.4  445.61  5063.2  446.58  5069.9  449.57  5108.1  449.09
  5247.3  451.89    5315   448.6  5387.9  447.57  5407.8  449.68  5451.6   449.7
  5471.3  451.03  5479.8   453.5  5492.1  453.75  5502.6  453.42  5518.4   450.4
  5523.6  455.45  5533.8  456.19  5648.5  461.43  5695.8  465.17  5966.5  477.26
#Mann= 3 ,-1 , 0
  4609.8     .05       0    5006    .035       0    5012     .05       0
Bank Sta=4973.2,5069.9
XS Rating Curve= 0 ,0
Exp/Cntr=0.3,0.1

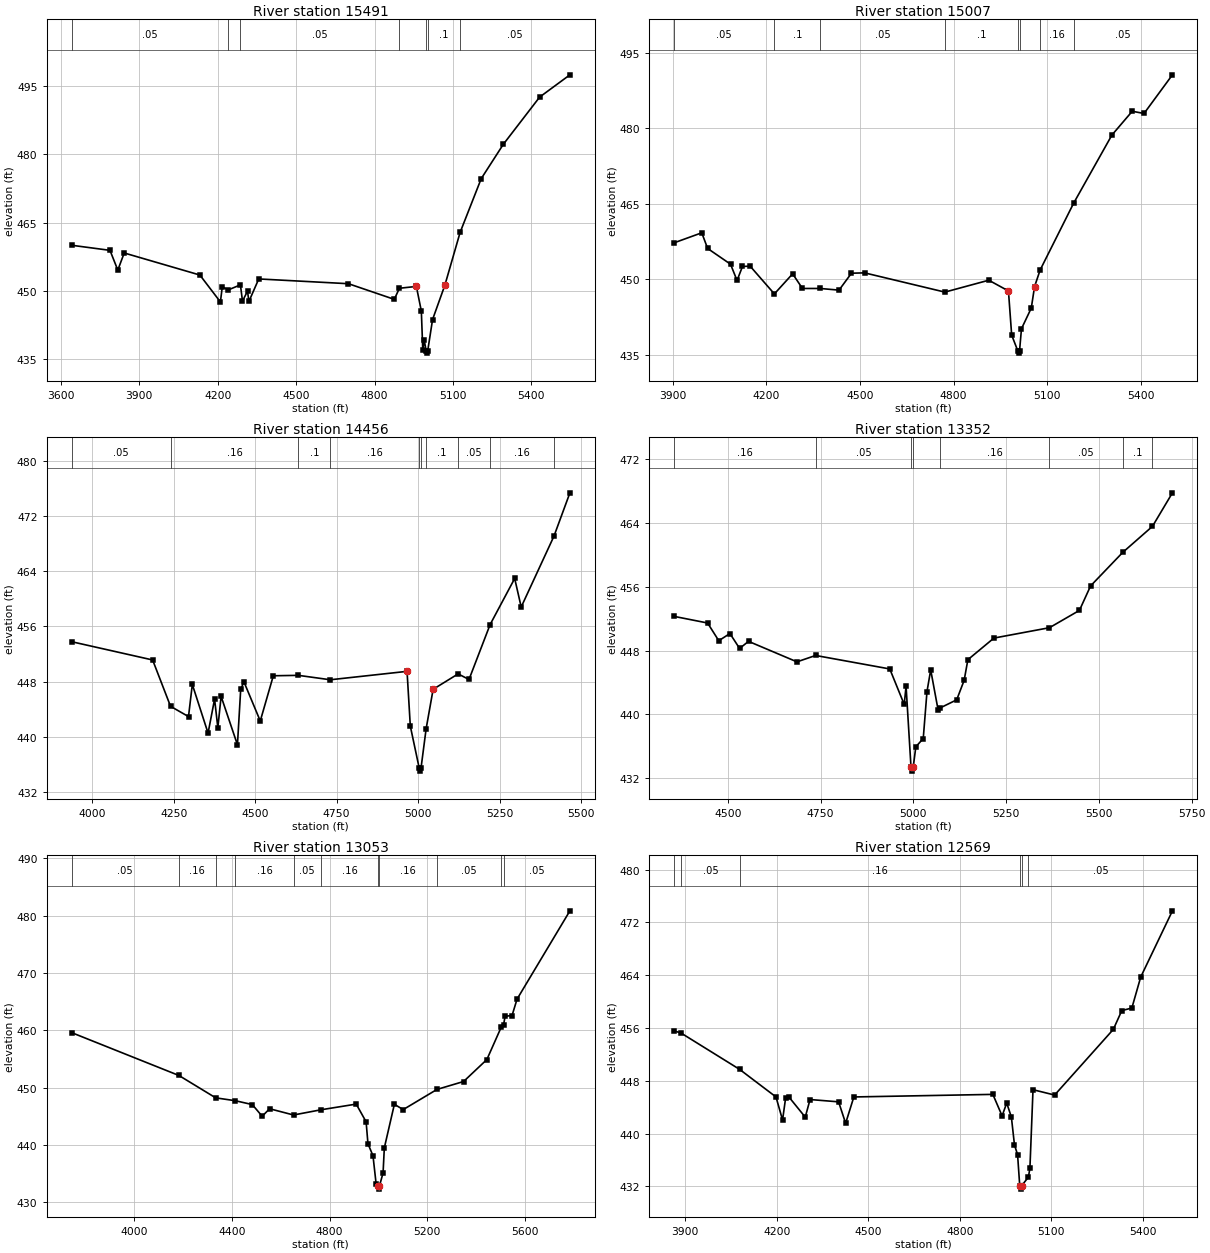
Type RM Length L Ch R = 1 ,15491   ,484,484,484
BEGIN DESCRIPTION:
SALT CREEK 1 30.0
END DESCRIPTION:
XS GIS Cut Line= 2
      3498759.99      10611327.9      3499447.49     10609550.11
#Sta/Elev= 30
  3641.3  460.02  3788.2   458.9  3818.1  454.55  3842.6  458.32    4132  453.47
  4210.5  447.55  4217.8  450.91  4239.9  450.18  4287.1  451.31    4295  447.74
  4314.2  449.91  4319.6  447.66  4357.2  452.61  4700.3  451.56  4875.6  448.12
  4895.2  450.56  4960.1  450.96  4979.1  445.54  4984.7  436.91    4990  439.19
  4997.5  436.79  5000.3  436.29  5003.5  436.79    5022  443.67  5069.1  451.23
  5127.3  462.83  5208.1  474.67  5292.6  482.22  5431.6  492.61  5547.4  497.51
#Mann= 7 ,-1 , 0
  3641.3     .05       0  4239.9      .1       0  4287.1     .05       0
  4895.2      .1       0  4997.5     .07       0  5003.5      .1       0
  5127.3     .05       0
Bank Sta=4960.1,5069.1
XS Rating Curve= 0 ,0
Exp/Cntr=0.3,0.1

Type RM Length L Ch R = 1 ,15007   ,551,551,551
BEGIN DESCRIPTION:
SALT CREEK 1 27.0
END DESCRIPTION:
XS GIS Cut Line= 2
      3499159.28     10611282.79      3499631.51     10609758.46
#Sta/Elev= 30
  3904.9  457.25  3993.5  459.24  4012.3  456.13  4085.6  453.01  4106.5  449.78
  4123.9  452.56  4148.4  452.62    4226  447.11  4284.5   451.1  4315.9  448.19
  4372.9  448.19    4433  447.86  4472.9  451.22  4514.8  451.29    4772  447.47
  4912.6  449.83  4975.6   447.7  4985.9  438.94  5005.2  435.86  5007.9  435.36
  5011.2  435.86  5017.3   440.2  5048.7   444.3  5059.2  448.56    5077  451.85
  5184.3  465.11  5306.8  478.63    5372  483.36  5409.8  482.92  5500.7  490.59
#Mann= 8 ,-1 , 0
  3904.9     .05       0    4226      .1       0  4372.9     .05       0
    4772      .1       0  5005.2     .07       0  5011.2      .1       0
    5077     .16       0  5184.3     .05       0
Bank Sta=4975.6,5059.2
XS Rating Curve= 0 ,0
Exp/Cntr=0.3,0.1

Type RM Length L Ch R = 1 ,14456   ,1104,1104,1104
BEGIN DESCRIPTION:
SALT CREEK 1 25.0
END DESCRIPTION:
XS GIS Cut Line= 2
      3499674.61     10611448.66      3499716.27     10609920.83
#Sta/Elev= 30
    3937  453.79  4185.6  451.14  4240.5  444.42  4295.6  442.93  4307.3  447.59
  4355.6  440.53  4375.6  445.46  4385.6  441.31  4395.6  445.86  4445.7  438.84
  4455.7  446.89  4465.7  447.96  4515.7  442.29  4555.7  448.85  4632.5  448.91
  4730.5  448.27  4965.9  449.49  4975.9  441.55  5002.9  435.52  5005.6  435.02
  5008.9  435.52  5024.5  441.19  5045.9  446.89  5122.5  449.12  5155.9  448.31
  5220.6  456.27    5296  462.96    5316  458.82  5416.6  469.11  5465.4  475.38
#Mann= 10 ,-1 , 0
    3937     .05       0  4240.5     .16       0  4632.5      .1       0
  4730.5     .16       0  5002.9     .07       0  5008.9     .16       0
  5024.5      .1       0  5122.5     .05       0  5220.6     .16       0
  5416.6     .05       0
Bank Sta=4965.9,5045.9
XS Rating Curve= 0 ,0
Exp/Cntr=0.3,0.1

Type RM Length L Ch R = 1 ,13352   ,299,299,299
BEGIN DESCRIPTION:
SALT CREEK 1 23.0
END DESCRIPTION:
XS GIS Cut Line= 2
      3500306.55     10611490.31      3500216.28     10610150.05
#Sta/Elev= 30
  4354.9  452.28  4445.2  451.45  4475.3  449.23  4505.4  450.13  4531.5  448.26
  4555.5  449.15  4686.1  446.58  4736.4  447.38  4936.3  445.69  4975.2  441.24
  4980.2  443.54  4993.5  433.38  4996.2  432.88  4999.5  433.38  5006.5  435.93
  5026.5  436.97  5036.6  442.86  5046.6  445.57  5066.6  440.54    5071  440.78
  5116.7  441.82  5136.8  444.27  5146.8  446.85    5217  449.56  5366.7  450.86
  5447.5  453.03  5477.6   456.1  5564.2   460.3  5644.4  463.57  5698.2  467.77
#Mann= 8 ,-1 , 0
  4354.9     .16       0  4736.4     .05       0  4993.5    .035       0
  4999.5     .05       0    5071     .16       0  5366.7     .05       0
  5564.2      .1       0  5644.4     .05       0
Bank Sta=4993.5,4999.5
XS Rating Curve= 0 ,0
Exp/Cntr=0.3,0.1

Type RM Length L Ch R = 1 ,13053   ,484,484,484
BEGIN DESCRIPTION:
SALT CREEK 1 22.0
END DESCRIPTION:
XS GIS Cut Line= 3
      3500699.61     10611960.22      3500499.61     10610760.19
      3500299.61     10609960.19
#Sta/Elev= 30
  3743.2  459.61    4183  452.13  4333.6  448.23  4413.9  447.73  4483.3  447.06
  4523.9  445.02  4554.3  446.33  4652.3  445.24  4764.8  446.15  4909.1  447.14
  4949.6  444.05  4957.2  440.22  4977.8  438.13  4990.7  433.19    4998  432.81
  5000.8  432.31    5004  432.81  5019.1  435.15  5024.2   439.5  5065.4  447.11
  5101.5  446.18  5239.9   449.7  5348.9  451.08  5444.2  454.91  5503.9  460.64
  5512.6  460.96    5519  462.47  5547.3  462.58  5567.9  465.45  5784.4  480.85
#Mann= 11 ,-1 , 0
  3743.2     .05       0    4183     .16       0  4333.6     .05       0
  4413.9     .16       0  4652.3     .05       0  4764.8     .16       0
    4998     .07       0    5004     .16       0  5239.9     .05       0
  5503.9      .1       0  5512.6     .05       0
Bank Sta=4998,5004
XS Rating Curve= 0 ,0
Exp/Cntr=0.3,0.1

Type RM Length L Ch R = 1 ,12569   ,985,985,985
BEGIN DESCRIPTION:
SALT CREEK 1 21.0
END DESCRIPTION:
XS GIS Cut Line= 3
      3501445.43     10611372.22      3500945.44     10611080.55
      3500778.77     10610038.85
#Sta/Elev= 30
  3863.6  455.57  3886.6  455.23  4078.4  449.73  4197.7  445.55  4219.2  442.05
  4229.1  445.35  4240.8   445.5  4293.6  442.49  4309.3  445.16  4402.9  444.81
    4426  441.56  4452.9  445.55  4908.7  445.94    4939  442.68  4954.1  444.63
  4969.4   442.5  4979.6  438.26  4989.7  436.82  4996.8  432.08  4999.6  431.58
  5002.8  432.08  5025.2   433.4  5030.2  434.77  5040.3  446.65  5111.2  445.84
  5303.6  455.79  5331.4  458.64  5364.4  459.03  5393.4  463.72  5497.4  473.76
#Mann= 6 ,-1 , 0
  3863.6      .1       0  3886.6     .05       0  4078.4     .16       0
  4996.8     .07       0  5002.8     .16       0  5025.2     .05       0
Bank Sta=4996.8,5002.8
XS Rating Curve= 0 ,0
Exp/Cntr=0.3,0.1

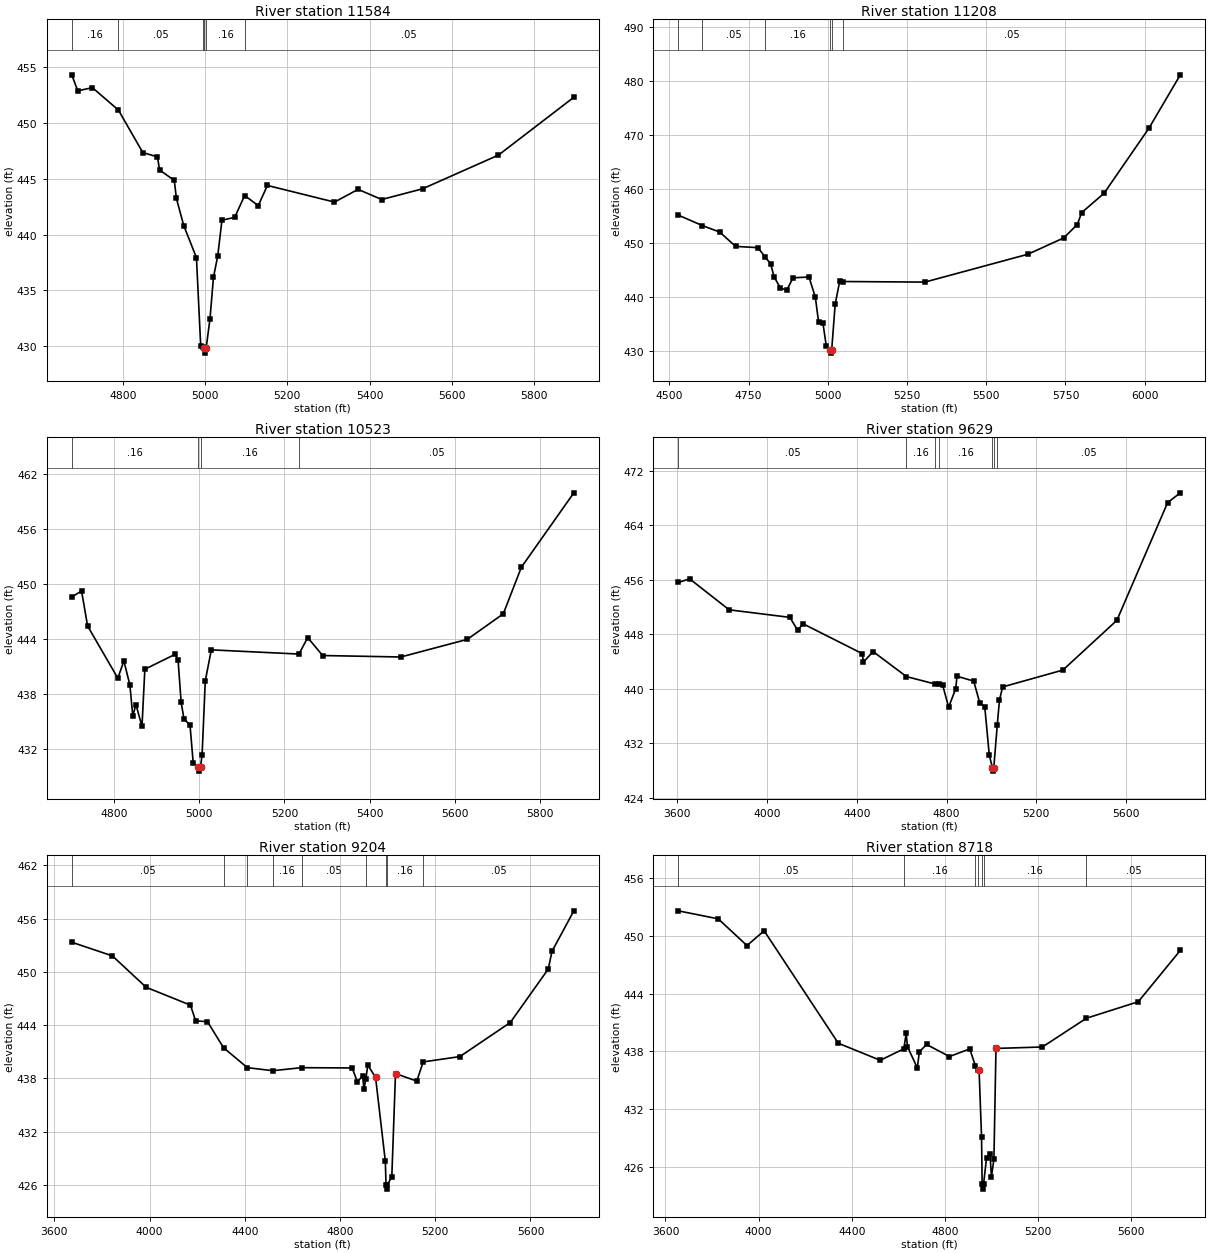
Type RM Length L Ch R = 1 ,11584   ,376,376,376
BEGIN DESCRIPTION:
SALT CREEK 1 20.0
END DESCRIPTION:
XS GIS Cut Line= 3
      3501647.05     10611233.78      3501532.46     10610785.85
      3501053.98     10610198.15
#Sta/Elev= 30
  4676.2  454.31  4690.7  452.88  4726.4  453.16  4789.6  451.15  4848.8  447.35
  4884.5  446.96  4889.6  445.78  4925.3  444.86  4930.5  443.24  4948.3  440.81
  4979.2  437.93  4989.6  429.99  4994.1  429.92  4996.9  429.88  4999.6  429.38
  5002.9  429.88  5012.1  432.44  5020.5  436.16  5030.9  438.08  5041.2  441.29
  5072.1  441.54  5096.4   443.5  5129.4  442.59  5151.6   444.4  5314.7  442.91
  5372.1  444.05  5429.5  443.14  5528.7   444.1  5713.2  447.12  5896.4   452.3
#Mann= 6 ,-1 , 0
  4676.2     .16       0  4789.6     .05       0  4994.1     .16       0
  4996.9     .07       0  5002.9     .16       0  5096.4     .05       0
Bank Sta=4996.9,5002.9
XS Rating Curve= 0 ,0
Exp/Cntr=0.3,0.1

Type RM Length L Ch R = 1 ,11208   ,685,685,685
BEGIN DESCRIPTION:
SALT CREEK 1 19.0
END DESCRIPTION:
XS GIS Cut Line= 3
      3501849.61     10611110.24      3501799.61     10610660.19
       3500999.6     10609860.18
#Sta/Elev= 30
  4528.2  455.15  4604.2  453.21    4659     452  4709.4  449.34  4779.8  449.11
  4802.5  447.35    4820  446.11  4830.1  443.76  4850.2  441.66  4870.3  441.21
  4890.5  443.52  4940.8  443.66  4960.9   439.9    4971   435.3  4984.6  435.18
  4995.2  430.94  5006.3  430.05  5009.1  429.55  5012.3  430.05  5023.4  438.63
  5037.6  442.87  5048.3  442.83  5306.3  442.72  5631.6  447.89  5744.7  450.92
  5787.1  453.38  5801.3  455.61    5872  459.21  6013.4  471.26  6112.4  481.16
#Mann= 6 ,-1 , 0
  4528.2      .1       0  4604.2     .05       0  4802.5     .16       0
  5006.3     .07       0  5012.3     .16       0  5048.3     .05       0
Bank Sta=5006.3,5012.3
XS Rating Curve= 0 ,0
Exp/Cntr=0.3,0.1

Type RM Length L Ch R = 1 ,10523   ,894,894,894
BEGIN DESCRIPTION:
SALT CREEK 1 18.0
END DESCRIPTION:
XS GIS Cut Line= 2
      3502376.24      10610676.5      3501589.76     10609796.28
#Sta/Elev= 30
    4700  448.59    4723  449.25  4737.2  445.42  4808.3  439.71  4822.5   441.6
  4836.7  438.95  4843.4  435.59  4850.9  436.82  4865.1  434.44  4871.8  440.69
  4942.9  442.32  4949.9  441.72  4957.1  437.09  4963.8  435.26    4978  434.59
  4985.5  430.45  4996.7  430.05  4999.5  429.55  5002.7  430.05  5006.4  431.32
  5013.9  439.42  5028.1  442.81  5234.1  442.35  5254.7  444.15  5289.8  442.19
  5473.7  442.03    5630  443.96  5714.5  446.75  5757.1  451.85  5880.4  459.98
#Mann= 4 ,-1 , 0
    4700     .16       0  4996.7     .07       0  5002.7     .16       0
  5234.1     .05       0
Bank Sta=4996.7,5002.7
XS Rating Curve= 0 ,0
Exp/Cntr=0.3,0.1

Type RM Length L Ch R = 1 ,9629    ,425,425,425
BEGIN DESCRIPTION:
SALT CREEK 1 16.0
END DESCRIPTION:
XS GIS Cut Line= 3
      3503099.61     10611060.18      3502399.61     10609860.19
      3501799.59     10609260.17
#Sta/Elev= 30
  3604.3  455.61  3655.2  456.14  3831.3  451.59  4102.1  450.48  4136.8  448.57
    4160  449.55  4424.2  445.16    4430  443.93    4473  445.45  4621.5  441.78
  4750.3  440.68  4765.6  440.74  4782.3  440.59  4809.5  437.29    4841  439.99
  4846.8  441.83  4921.2  441.12  4948.5  437.88  4970.4  437.38  4990.6  430.25
  5004.7  428.39  5007.4  427.89  5010.7  428.39  5026.4  434.72    5036  438.32
  5050.1  440.26  5318.8  442.74  5559.2  450.04  5785.5  467.34  5842.1  468.78
#Mann= 7 ,-1 , 0
  3604.3     .05       0  4621.5     .16       0  4750.3     .05       0
  4765.6     .16       0  5004.7     .07       0  5010.7     .16       0
  5026.4     .05       0
Bank Sta=5004.7,5010.7
XS Rating Curve= 0 ,0
Exp/Cntr=0.3,0.1

Type RM Length L Ch R = 1 ,9204    ,486,486,486
BEGIN DESCRIPTION:
SALT CREEK 1 15.0
END DESCRIPTION:
XS GIS Cut Line= 3
       3503362.1      10610750.7      3502761.43     10609629.21
      3502043.68     10609199.25
#Sta/Elev= 30
  3673.2  453.34  3843.9   451.8  3985.7  448.26  4171.7  446.25  4193.7  444.47
  4243.2  444.39  4310.6  441.45  4410.9   439.2    4518  438.86  4638.2   439.2
  4850.9  439.17  4872.9  437.61  4894.8  438.26  4900.5   436.8  4908.1  437.87
  4916.7  439.49  4949.3   438.1  4990.3  428.64  4993.1  426.01  4995.8  425.51
  4999.1  426.01  5017.5  426.91    5033  438.53  5122.4  437.69  5149.2  439.85
  5303.3  440.45  5515.2  444.29  5674.7  450.32  5690.2  452.31  5782.1  456.88
#Mann= 9 ,-1 , 0
  3673.2     .05       0  4310.6     .16       0  4410.9     .05       0
    4518     .16       0  4638.2     .05       0  4908.1     .16       0
  4993.1     .07       0  4999.1     .16       0  5149.2     .05       0
Bank Sta=4949.3,5033
XS Rating Curve= 0 ,0
Exp/Cntr=0.3,0.1

Type RM Length L Ch R = 1 ,8718    ,499,499,499
BEGIN DESCRIPTION:
SALT CREEK 1 14.0
END DESCRIPTION:
XS GIS Cut Line= 3
      3503511.56     10610627.99      3503045.05     10609311.46
      3502303.25     10609149.14
#Sta/Elev= 30
  3654.8  452.57  3826.4  451.74    3950  448.97  4023.8   450.5  4342.1  438.85
  4522.4  437.08  4623.4  438.27  4633.8  439.88  4639.1  438.49  4681.6   436.3
  4690.2  437.95  4721.1  438.72  4819.5  437.47  4906.4  438.26  4931.2   436.5
    4940  436.11  4946.8  436.05  4957.4  429.09  4959.9  424.23  4962.6  423.73
  4965.9  424.23  4978.6  426.93  4993.8  427.32  4999.8  424.98  5010.5  426.86
  5019.3  438.31  5218.5  438.46  5407.8  441.44  5630.4  443.15  5810.9  448.47
#Mann= 7 ,-1 , 0
  3654.8     .05       0  4623.4     .16       0  4931.2     .05       0
    4940     .16       0  4959.9     .07       0  4965.9     .16       0
  5407.8     .05       0
Bank Sta=4946.8,5019.3
XS Rating Curve= 0 ,0
Exp/Cntr=0.3,0.1

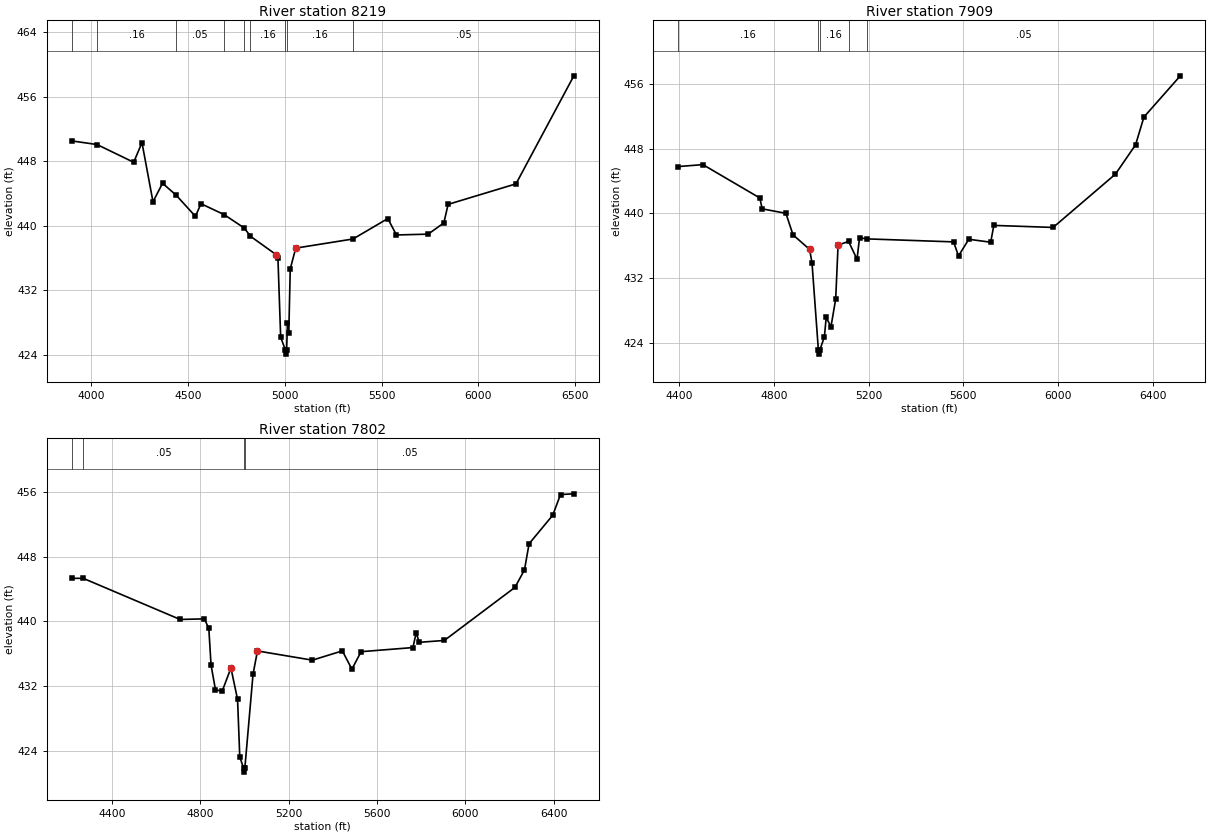
Type RM Length L Ch R = 1 ,8219    ,310,310,310
BEGIN DESCRIPTION:
Mapping XS a4e463ed
END DESCRIPTION:
XS GIS Cut Line= 3
      3504264.87      10610226.4      3503494.06     10609358.38
      3502219.72     10608709.05
#Sta/Elev= 30
  3901.2  450.51  4031.6  450.06  4220.8  447.86  4263.5   450.3  4320.3  442.97
  4369.7  445.26  4439.9  443.79  4539.4  441.16  4567.9  442.73  4686.8  441.39
    4792  439.71  4822.8  438.71  4957.6  436.39  4965.1  436.04  4979.3  426.19
  5003.9   424.6  5006.7   424.1  5009.9   424.6  5014.4   427.9  5021.1  426.66
  5028.7  434.65  5057.1  437.23  5352.5  438.36  5532.2  440.89  5576.7  438.86
  5740.5  438.96  5821.3  440.35  5843.5  442.65  6193.7  445.19  6492.3  458.57
#Mann= 9 ,-1 , 0
  3901.2     .05       0  4031.6     .16       0  4439.9     .05       0
  4686.8     .16       0    4792      .1       0  4822.8     .16       0
  5003.9     .07       0  5009.9     .16       0  5352.5     .05       0
Bank Sta=4957.6,5057.1
XS Rating Curve= 0 ,0
Exp/Cntr=0.3,0.1

Type RM Length L Ch R = 1 ,7909    ,107,107,107
BEGIN DESCRIPTION:
SALT CREEK 1 13.0
END DESCRIPTION:
XS GIS Cut Line= 3
      3504403.56     10609307.12      3503629.48     10609254.21
        3502567.     10608427.84
#Sta/Elev= 30
  4394.7  445.78  4498.9  446.02  4739.5  441.91  4749.5  440.57  4849.7  440.02
  4879.8  437.37  4949.9  435.57    4960  433.93    4987  423.17  4989.8  422.67
    4993  423.17  5012.3  424.79  5020.1  427.19  5040.2  426.05  5060.2  429.47
  5070.2   436.1  5114.5  436.56  5150.4  434.36  5160.8  437.01  5191.3  436.87
  5558.4   436.5  5579.2  434.77  5622.6  436.82  5715.2  436.46  5728.5  438.53
  5979.1  438.28  6242.5  444.85  6327.5  448.46  6362.8  451.88  6516.6  456.96
#Mann= 5 ,-1 , 0
  4394.7     .16       0    4987     .07       0    4993     .16       0
  5114.5      .1       0  5191.3     .05       0
Bank Sta=4949.9,5070.2
XS Rating Curve= 0 ,0
Exp/Cntr=0.3,0.1

Type RM Length L Ch R = 1 ,7802    ,508,508,508
BEGIN DESCRIPTION:
SALT CREEK 1 12.0
END DESCRIPTION:
XS GIS Cut Line= 3
       3504629.5     10609209.07      3503621.09     10609161.98
       3502639.9     10608365.32
#Sta/Elev= 30
  4218.5  445.33  4270.3  445.33  4708.9  440.24    4819  440.31  4839.1  439.12
  4849.1   434.6  4869.1  431.55  4899.1  431.33  4939.2  434.23  4969.2  430.34
  4979.2  423.24  4996.2  421.84    4999  421.34  5002.2  421.84  5039.3  433.47
  5059.3  436.34  5307.9   435.2  5443.7  436.35  5486.9  434.08  5528.5  436.25
  5763.4  436.76  5777.8  438.57  5792.2  437.41  5905.6  437.64  6225.3  444.21
  6268.4  446.38  6289.2  449.61  6396.3  453.14  6431.5   455.7  6491.9  455.79
#Mann= 4 ,-1 , 0
  4218.5     .08       0  4270.3     .05       0  4996.2     .04       0
  5002.2     .05       0
Bank Sta=4939.2,5059.3
XS Rating Curve= 0 ,0
Exp/Cntr=0.3,0.1