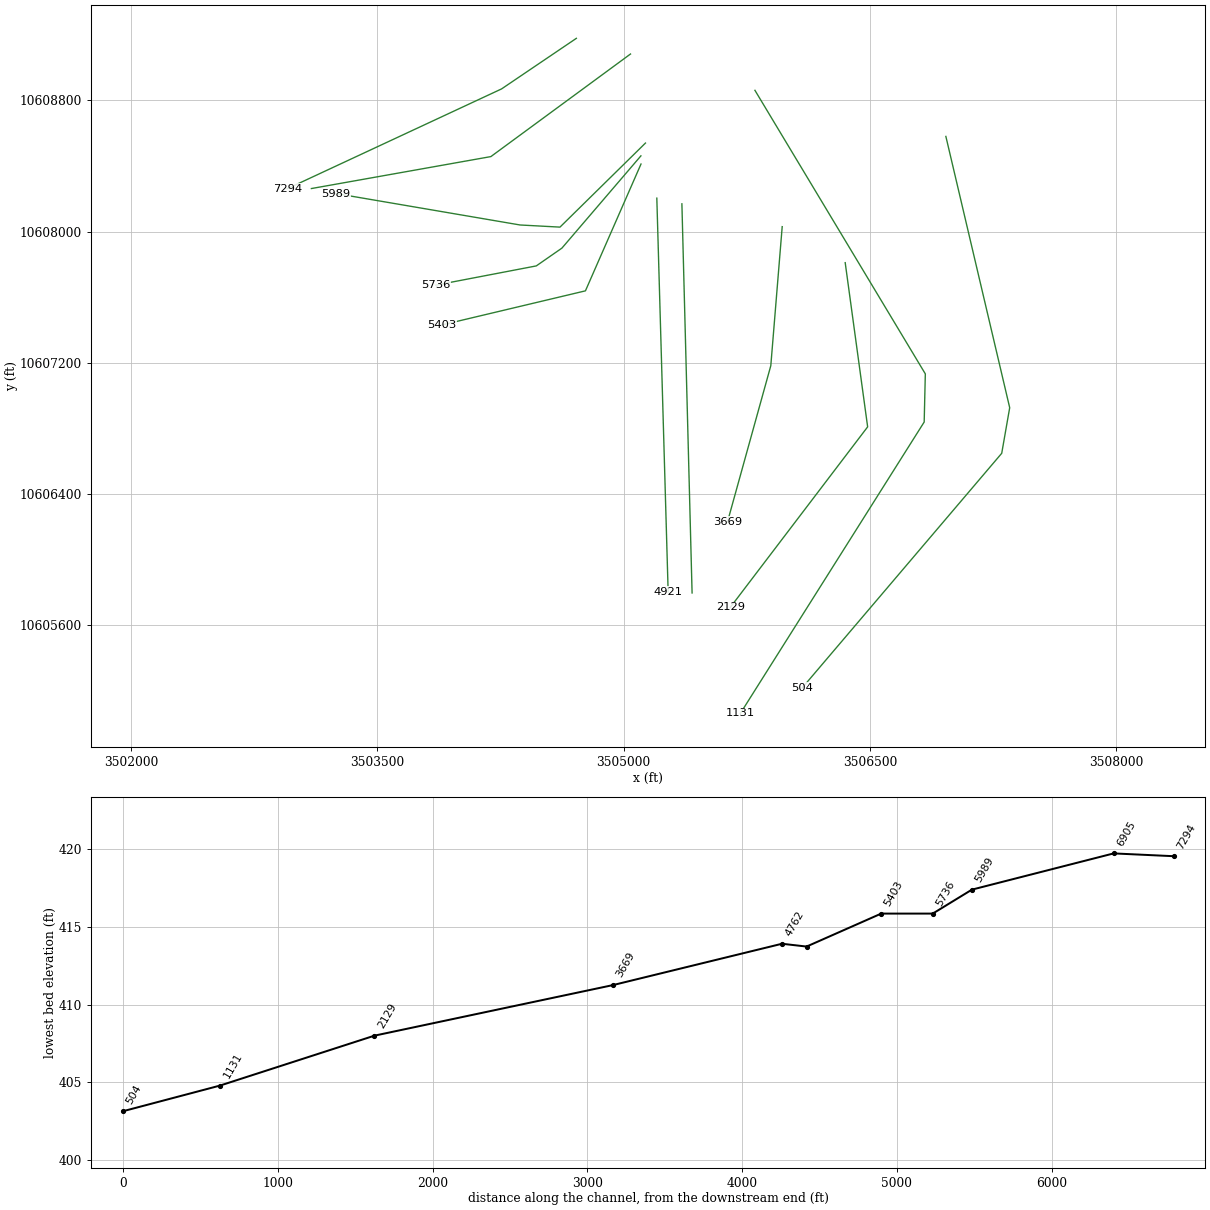
HEC-RAS study SALT CREEK 1.prj: SALT CREEK 1 Base Level Engineering

--- SALT CREEK 1.g01 (geometry) --- (continued)

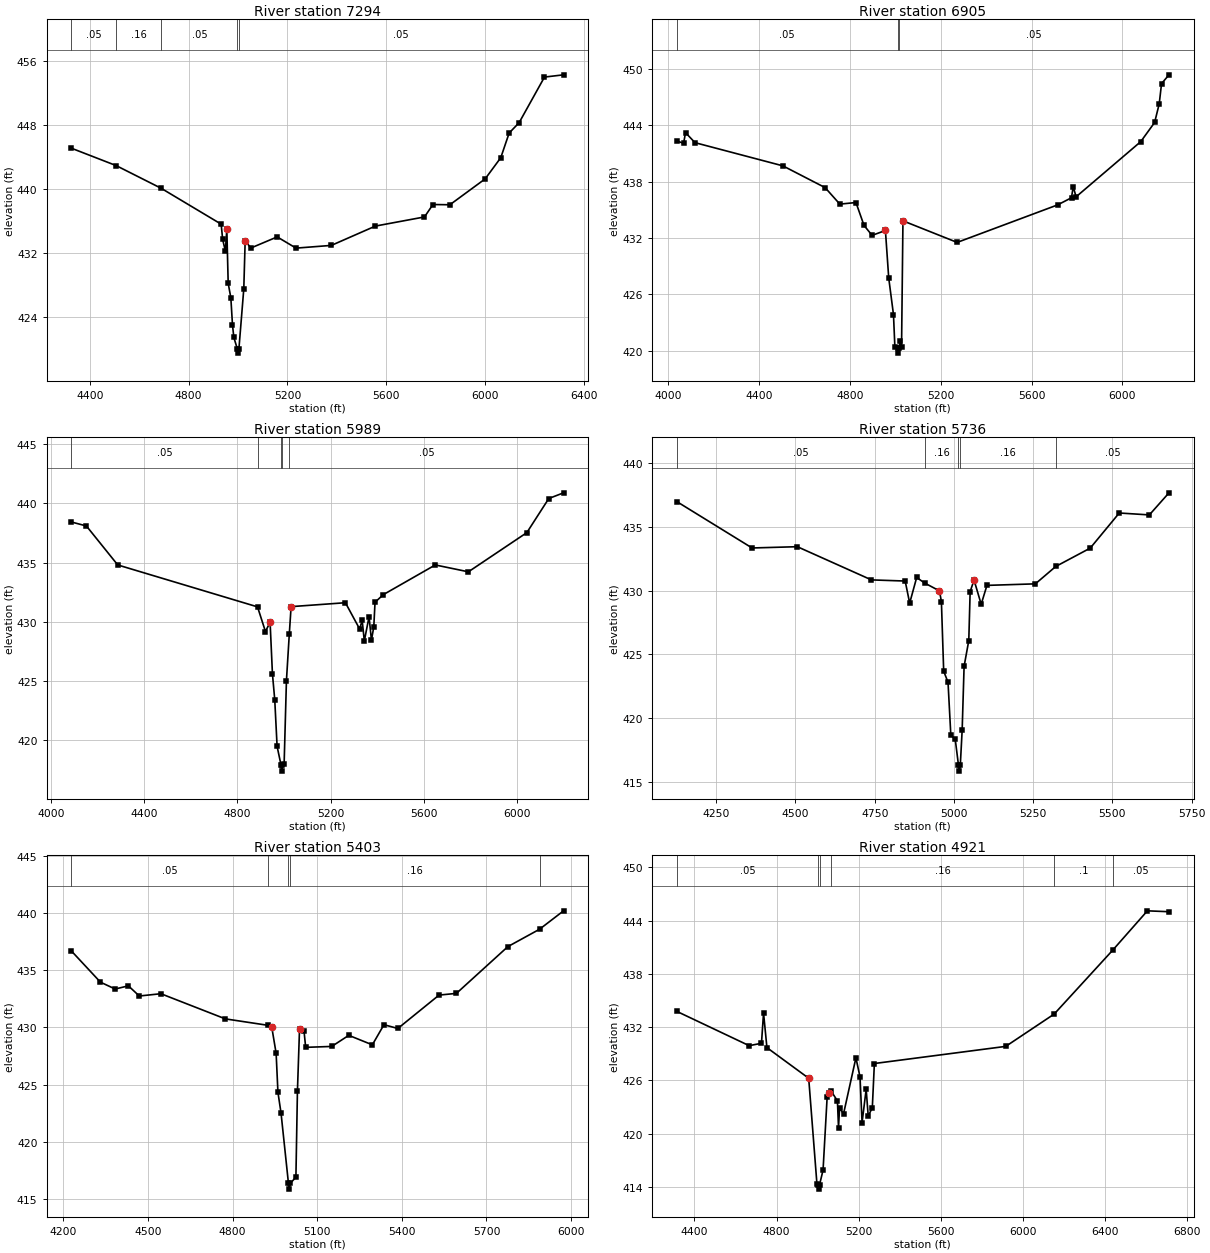
Type RM Length L Ch R = 1 ,7294    ,389,389,389
BEGIN DESCRIPTION:
SALT CREEK 1 11.0
END DESCRIPTION:
XS GIS Cut Line= 3
      3504711.69     10609176.89      3504255.99     10608868.75
      3502949.59     10608260.18
#Sta/Elev= 30
  4325.5  445.12  4506.8  442.95  4689.4  440.11  4931.8  435.64  4937.8  433.74
  4948.8  432.28  4954.7  434.99  4960.2  428.27  4970.9  426.46  4977.6  423.06
  4983.1   421.5  4997.5  420.05  5000.2  419.55  5003.5  420.05  5023.3  427.57
  5028.9  433.59  5051.7  432.66  5158.4  434.05  5234.7  432.65  5377.5  432.99
  5555.6   435.4  5754.2  436.54  5788.4  438.09    5857  438.06  5999.7  441.29
  6062.8  443.93  6096.7  447.01    6137   448.3  6239.6  453.99  6316.8  454.27
#Mann= 5 ,-1 , 0
  4325.5     .05       0  4506.8     .16       0  4689.4     .05       0
  4997.5    .035       0  5003.5     .05       0
Bank Sta=4954.7,5028.9
XS Rating Curve= 0 ,0
Exp/Cntr=0.3,0.1

Type RM Length L Ch R = 1 ,6905    ,916,916,916
BEGIN DESCRIPTION:
SALT CREEK 1 10.0
END DESCRIPTION:
XS GIS Cut Line= 3
      3505041.57     10609081.42      3504190.88     10608456.42
      3503097.38     10608261.71
#Sta/Elev= 30
  4038.5  442.35  4068.9  442.09  4077.4  443.23  4119.1  442.16  4505.7  439.69
  4691.6  437.37  4756.4  435.61  4827.4  435.78  4862.9  433.34  4898.4  432.28
    4957   432.8  4971.6  427.73  4992.5  423.84  4998.7  420.36  5010.4  420.23
  5013.1  419.73  5016.4  420.23  5021.2     421    5028  420.37  5034.2  433.83
  5272.7  431.53    5715  435.53  5775.9  436.29  5783.3  437.47  5796.2  436.39
  6080.6  442.27  6141.6  444.31  6161.9   446.3  6172.1  448.45  6204.8  449.39
#Mann= 3 ,-1 , 0
  4038.5     .05       0  5010.4     .03       0  5016.4     .05       0
Bank Sta=4957,5034.2
XS Rating Curve= 0 ,0
Exp/Cntr=0.3,0.1

Type RM Length L Ch R = 1 ,5989    ,253,253,253
BEGIN DESCRIPTION:
SALT CREEK 1 9.0
END DESCRIPTION:
XS GIS Cut Line= 4
      3505132.72     10608538.88      3504611.89     10608026.73
      3504368.83     10608039.76      3503247.12     10608231.31
#Sta/Elev= 30
  4087.8  438.44  4152.7   438.1  4287.1  434.81  4886.8  431.27  4920.7  429.19
  4940.7  429.97  4950.7  425.62  4960.7  423.41  4970.7  419.49  4987.8   417.9
  4990.5   417.4  4993.8   417.9  5000.8  417.97  5010.8  425.05  5023.2  429.02
  5030.8  431.29  5263.8  431.62  5324.6  429.41  5335.7  430.12  5344.9  428.39
  5365.2  430.44  5375.4  428.46  5385.5  429.58  5390.8  431.66  5426.1   432.3
  5649.3  434.81  5791.3  434.23  6042.1  437.54  6136.2  440.42  6199.6   440.9
#Mann= 5 ,-1 , 0
  4087.8     .05       0  4886.8     .16       0  4987.8     .07       0
  4993.8     .16       0  5023.2     .05       0
Bank Sta=4940.7,5030.8
XS Rating Curve= 0 ,0
Exp/Cntr=0.3,0.1

Type RM Length L Ch R = 1 ,5736    ,333,333,333
BEGIN DESCRIPTION:
Mapping XS a93e55ce
END DESCRIPTION:
XS GIS Cut Line= 4
      3505105.02     10608460.92      3504623.79     10607898.88
      3504467.54     10607790.38       3503855.6      10607673.2
#Sta/Elev= 30
  4125.2  436.98  4363.1  433.34  4505.8  433.44  4739.6  430.84  4846.1  430.75
  4860.3  429.02  4882.4  431.03  4907.1   430.6  4954.3  429.98  4960.4  429.14
  4967.6  423.69  4981.3  422.82  4990.1  418.69  5004.1  418.34  5014.1  416.36
  5016.9  415.86  5020.1  416.36  5025.9  419.07    5032  424.07  5046.8  426.09
  5051.1  429.92  5063.4  430.83  5085.9  428.93  5104.1  430.41  5256.9  430.53
  5321.1  431.89    5430  433.33  5521.6  436.08  5616.5  435.93  5678.4  437.66
#Mann= 5 ,-1 , 0
  4125.2     .05       0  4907.1     .16       0  5014.1     .07       0
  5020.1     .16       0  5321.1     .05       0
Bank Sta=4954.3,5063.4
XS Rating Curve= 0 ,0
Exp/Cntr=0.3,0.1

Type RM Length L Ch R = 1 ,5403    ,482,482,482
BEGIN DESCRIPTION:
SALT CREEK 1 8.0
END DESCRIPTION:
XS GIS Cut Line= 3
      3505105.57     10608411.05      3504767.02     10607638.47
      3503890.24     10607430.12
#Sta/Elev= 30
  4228.6   436.7    4332  433.96  4384.2  433.36  4430.9  433.64  4469.7  432.75
  4546.2  432.95  4774.6  430.75    4925  430.19  4939.2  430.02  4954.6  427.74
    4961  424.33    4972  422.51  4998.3  416.36  5001.1  415.86  5004.3  416.36
  5024.7   416.9  5030.1  424.43  5037.5  429.84  5053.5  429.67  5059.3  428.26
  5151.7  428.34  5212.1  429.31  5295.6  428.48  5336.7  430.24    5386  429.91
    5532  432.83  5593.6  432.98  5775.9  437.07  5888.2  438.59  5973.3   440.2
#Mann= 5 ,-1 , 0
  4228.6     .05       0    4925     .16       0  4998.3     .07       0
  5004.3     .16       0  5888.2     .05       0
Bank Sta=4939.2,5037.5
XS Rating Curve= 0 ,0
Exp/Cntr=0.3,0.1

Type RM Length L Ch R = 1 ,4921    ,159,159,159
BEGIN DESCRIPTION:
SALT CREEK 1 7.0
END DESCRIPTION:
XS GIS Cut Line= 2
      3505201.91     10608203.31      3505270.94       10605805.
#Sta/Elev= 30
  4313.4  433.77  4666.7   429.9  4726.7  430.17  4736.7  433.58  4753.2  429.68
  4956.8  426.23  4996.8  414.37  5003.8  414.24  5006.6  413.74  5009.8  414.24
  5026.8  415.89  5046.8  424.15  5056.8  424.58  5066.4  424.78  5096.8  423.68
  5102.1  420.68  5107.1  422.83  5126.9  422.25  5186.9  428.53  5206.9  426.39
  5216.9  421.24  5236.9  424.99  5246.9  421.96  5266.9  422.93  5276.9  427.89
  5917.2  429.82  6153.2  433.46  6438.2  440.65  6607.5  445.09  6712.7  444.99
#Mann= 6 ,-1 , 0
  4313.4     .05       0  5003.8    .035       0  5009.8     .05       0
  5066.4     .16       0  6153.2      .1       0  6438.2     .05       0
Bank Sta=4956.8,5056.8
XS Rating Curve= 0 ,0
Exp/Cntr=0.3,0.1

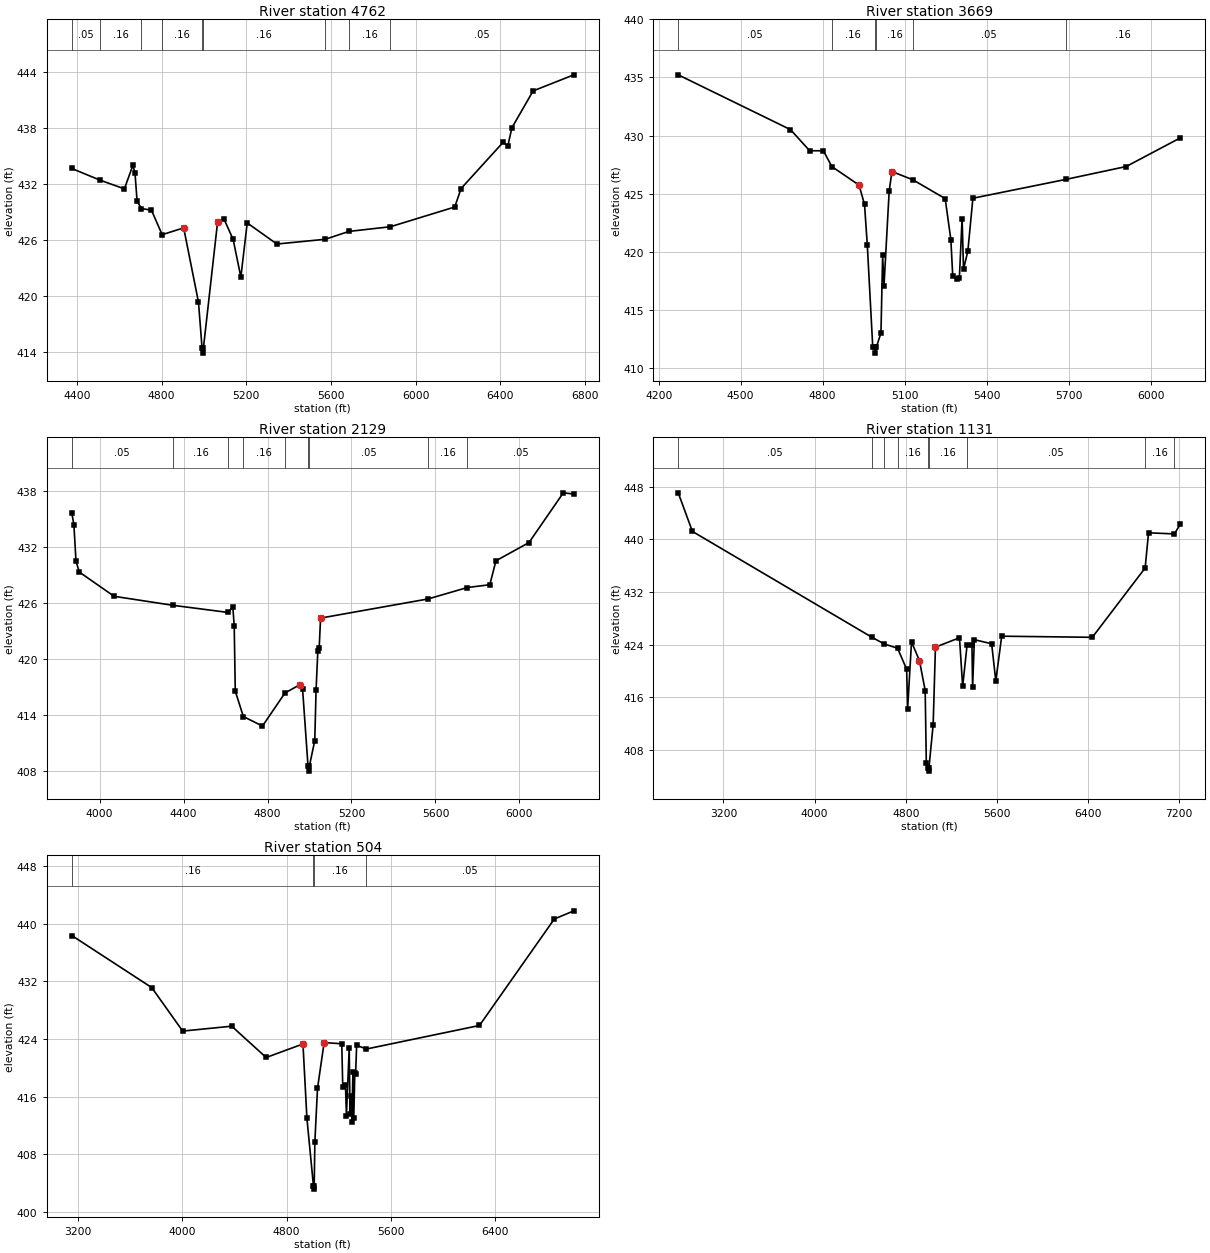
Type RM Length L Ch R = 1 ,4762    ,1093,1093,1093
BEGIN DESCRIPTION:
SALT CREEK 1 6.0
END DESCRIPTION:
XS GIS Cut Line= 2
      3505354.69     10608168.61      3505416.78     10605797.82
#Sta/Elev= 30
  4375.5  433.67  4508.5  432.43    4624  431.49    4664     434    4674  433.23
    4684  430.18  4704.5  429.38  4751.7  429.22  4802.5  426.59  4904.1  427.32
  4974.1  419.36  4991.1  414.42  4993.9  413.92  4997.1  414.42  5064.2  427.93
  5094.2  428.28  5137.8  426.08  5174.2  422.05  5204.2  427.85  5344.2  425.59
  5573.2   426.1  5684.6  426.94  5880.6  427.44  6184.5  429.55  6214.5  431.53
  6414.6  436.51  6434.6  436.03  6454.6  438.03  6554.7  441.97  6747.1  443.69
#Mann= 9 ,-1 , 0
  4375.5     .05       0  4508.5     .16       0  4704.5     .05       0
  4802.5     .16       0  4991.1     .07       0  4997.1     .16       0
  5573.2     .05       0  5684.6     .16       0  5880.6     .05       0
Bank Sta=4904.1,5064.2
XS Rating Curve= 0 ,0
Exp/Cntr=0.3,0.1

Type RM Length L Ch R = 1 ,3669    ,1540,1540,1540
BEGIN DESCRIPTION:
SALT CREEK 1 5.0
END DESCRIPTION:
XS GIS Cut Line= 3
       3505965.8     10608029.65      3505896.36     10607182.45
      3505632.46     10606231.01
#Sta/Elev= 30
  4271.7  435.23  4682.5  430.51  4752.8  428.69  4802.9  428.69  4833.8  427.33
  4933.4  425.73  4953.4  424.07  4963.5  420.61  4983.5  411.81  4990.6  411.76
  4993.3  411.26  4996.6  411.76  5013.6     413  5019.7  419.67  5024.7  417.06
  5043.7  425.23  5053.8   426.9  5130.3  426.19  5248.6  424.57  5269.4  421.04
  5276.3   417.9  5290.1  417.62  5300.5   417.7  5310.5  422.84  5315.7  418.49
  5331.6  420.05    5350   424.6  5689.6  426.22  5910.8  427.33  6109.1   429.8
#Mann= 6 ,-1 , 0
  4271.7     .05       0  4833.8     .16       0  4990.6     .07       0
  4996.6     .16       0  5130.3     .05       0  5689.6     .16       0
Bank Sta=4933.4,5053.8
XS Rating Curve= 0 ,0
Exp/Cntr=0.3,0.1

Type RM Length L Ch R = 1 ,2129    ,998,998,998
BEGIN DESCRIPTION:
SALT CREEK 1 3.0
END DESCRIPTION:
XS GIS Cut Line= 3
      3506349.61     10607810.17      3506486.35     10606809.76
      3505649.63     10605710.22
#Sta/Elev= 30
  3867.7  435.65  3877.8  434.37  3887.9  430.44  3903.8   429.3  4069.5  426.71
  4348.9  425.75  4613.8  424.98  4634.7  425.62  4641.4  423.55  4646.5  416.57
  4684.9  413.85    4776  412.83  4883.1  416.37  4952.4  417.23    4967  416.81
  4993.1  408.51  4995.8  408.01  4999.1  408.51  5025.1  411.28  5031.4  416.74
  5039.7  420.88    5046  421.13  5052.8  424.38    5565  426.43  5751.6  427.65
  5858.9  427.95    5888  430.51  6045.5  432.46  6208.9  437.78  6259.1  437.65
#Mann= 9 ,-1 , 0
  3867.7     .05       0  4348.9     .16       0  4613.8     .05       0
  4684.9     .16       0  4883.1     .05       0  4993.1     .03       0
  4999.1     .05       0    5565     .16       0  5751.6     .05       0
Bank Sta=4952.4,5052.8
XS Rating Curve= 0 ,0
Exp/Cntr=0.3,0.1

Type RM Length L Ch R = 1 ,1131    ,627,627,627
BEGIN DESCRIPTION:
SALT CREEK 1 2.0
END DESCRIPTION:
XS GIS Cut Line= 4
      3505799.63     10608860.15      3506837.77     10607132.65
      3506830.82     10606839.25      3505710.96      10605064.2
#Sta/Elev= 30
  2802.8  447.06  2927.1   441.2  4504.7  425.11  4609.8  424.12  4728.3  423.46
  4807.9  420.27  4816.8  414.31  4850.7  424.42  4920.7  421.57  4970.7  417.04
  4980.7     406  4997.7   405.3  5000.5   404.8  5003.7   405.3  5040.8  411.88
  5060.8  423.63  5271.8  425.05  5299.8  417.67  5338.7  423.98  5381.2  423.91
  5387.1  417.58  5402.4  424.76  5554.2  424.14  5590.7  418.49  5642.4  425.29
    6438  425.12  6901.8  435.65  6931.5  440.99  7158.1  440.82  7210.5  442.29
#Mann= 9 ,-1 , 0
  2802.8     .05       0  4504.7     .16       0  4609.8     .05       0
  4728.3     .16       0  4997.7     .07       0  5003.7     .16       0
  5338.7     .05       0  6901.8     .16       0  7158.1     .05       0
Bank Sta=4920.7,5060.8
XS Rating Curve= 0 ,0
Exp/Cntr=0.3,0.1

Type RM Length L Ch R = 1 ,504     ,0,0,0
BEGIN DESCRIPTION:
SALT CREEK 1 1.0
END DESCRIPTION:
XS GIS Cut Line= 4
      3506962.94     10608579.25      3507351.83     10606926.48
      3507303.22     10606648.71      3506087.97     10605219.92
#Sta/Elev= 30
  3150.3  438.39  3764.7  431.15    4002  425.11  4378.5  425.79  4643.1  421.44
  4925.7  423.32  4956.1  412.98    5006  403.65  5008.8  403.15    5012  403.65
    5017  409.68  5037.3  417.14  5088.1  423.51  5223.7  423.35  5231.4  417.32
  5252.3  417.59  5259.5  413.38  5280.8  422.74  5287.4  413.59  5295.1  416.12
  5301.7  412.48  5309.4  419.45  5315.9  413.09  5323.7  419.24  5330.2  419.17
  5337.9  423.13  5413.2  422.62  6281.3  425.89  6855.7  440.68  7005.9  441.82
#Mann= 4 ,-1 , 0
  3150.3     .16       0    5006     .07       0    5012     .16       0
  5413.2     .05       0
Bank Sta=4925.7,5088.1
XS Rating Curve= 0 ,0
Exp/Cntr=0.3,0.1

Chan Stop Cuts=-1
Use User Specified Reach Order=0
Composite Channel Slope=5