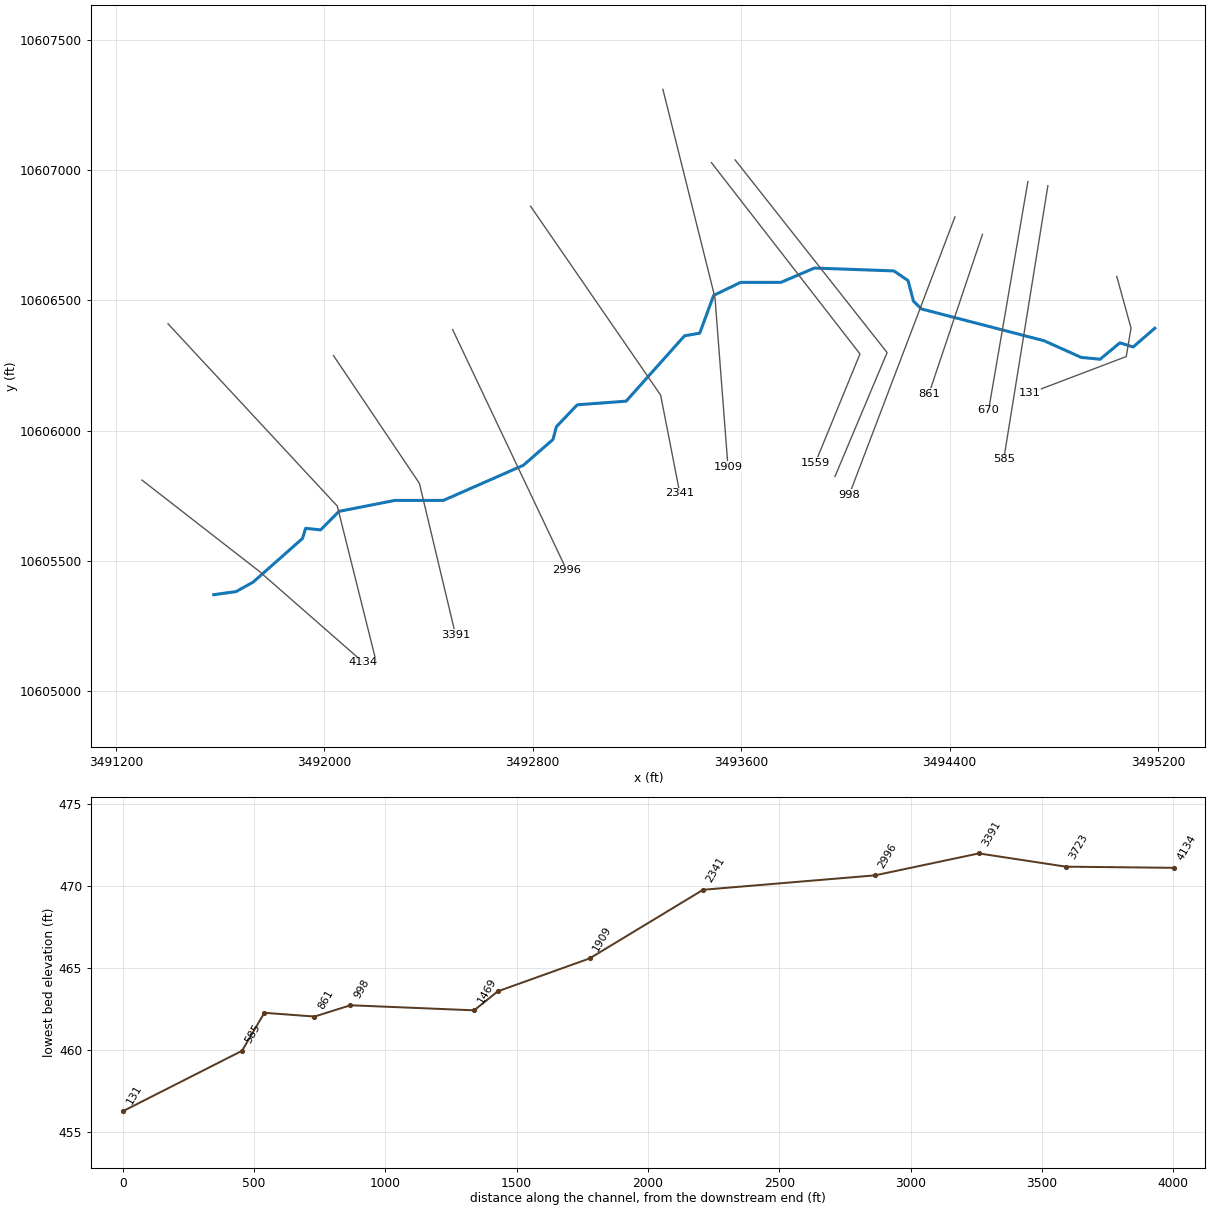
--- SALT CREEK 2.prj (project) ---

Proj Title=SALT CREEK 2 Base Level Engineering
Current Plan=p01
Default Exp/Contr=0.3,0.1
English Units
Geom File=g01
Flow File=f01
Plan File=p01
Y Axis Title=Elevation
X Axis Title(PF)=Main Channel Distance
X Axis Title(XS)=Station
BEGIN DESCRIPTION:
SALT CREEK 2
END DESCRIPTION:
DSS Export Rating Curves= 0
DSS Export Rating Curve Sorted= 0
DSS Export Volume Flow Curves= 0
DXF OffsetX= 0
DXF OffsetY= 0
DXF ScaleX= 1
DXF ScaleY= 10

--- SALT CREEK 2.p01 (plan) ---

Plan Title=Multiple Run
Short Identifier=Multiple
Geom File=g01
Flow File=f01
Subcritical Flow
K Sum by GR= 0
Std Step Tol= 0.01
Critical Tol= 0.01
Num of Std Step Trials= 20
Max Error Tol= 0.3
Flow Tol Ratio= 0.001
Split Flow NTrial= 30
Split Flow Tol= 0.02
Split Flow Ratio= 0.02
Log Output Level= 0
Friction Slope Method= 1
Unsteady Friction Slope Method= 2
Unsteady Bridges Friction Slope Method= 1
Parabolic Critical Depth
Global Vel Dist=  1 , 1 , 1
Global Log Level= 0
CheckData=True
Encroach Param= -1, 0, 0, 0
BEGIN DESCRIPTION:
Multiple Run
END DESCRIPTION:

--- SALT CREEK 2.f01 (steady flow) ---

Flow Title=Multiple
Number of Profiles=7
Profile Names=10-year,25-year,50-year,1pct_min,100-year,1pct_plu,500-year
River Rch & RM= SALT CREEK 2,Reach-1,4134
    1626    2255    2777    2492    3371    4558    4954
Boundary for River Rch & Prof#=SALT CREEK 2,Reach-1,1
Up Type=0
Dn Type=3
Dn Slope=0.005
Boundary for River Rch & Prof#=SALT CREEK 2,Reach-1,2
Up Type=0
Dn Type=3
Dn Slope=0.005
Boundary for River Rch & Prof#=SALT CREEK 2,Reach-1,3
Up Type=0
Dn Type=3
Dn Slope=0.005
Boundary for River Rch & Prof#=SALT CREEK 2,Reach-1,4
Up Type=0
Dn Type=3
Dn Slope=0.005
Boundary for River Rch & Prof#=SALT CREEK 2,Reach-1,5
Up Type=0
Dn Type=3
Dn Slope=0.005
Boundary for River Rch & Prof#=SALT CREEK 2,Reach-1,6
Up Type=0
Dn Type=3
Dn Slope=0.005
Boundary for River Rch & Prof#=SALT CREEK 2,Reach-1,7
Up Type=0
Dn Type=3
Dn Slope=0.005

--- SALT CREEK 2.g01 (geometry) ---

Geom Title=Existing Conditions
Program Version=4.10

River Reach=SALT CREEK 2    ,Reach-1
Reach XY= 30
      3491575.25       10605370.      3491660.75       10605382.
        3491726.       10605418.        3491916.       10605586.
      3491928.25       10605625.       3491985.5       10605619.
      3492056.25       10605690.      3492270.75       10605732.
      3492456.75       10605732.        3492764.       10605867.
      3492877.75       10605966.      3492890.75       10606015.
      3492970.75       10606099.       3493158.5       10606113.
      3493382.75       10606364.        3493441.       10606374.
       3493494.5       10606519.      3493597.75       10606569.
       3493752.5       10606569.      3493881.75       10606624.
       3494186.5       10606613.      3494240.75       10606576.
       3494261.5       10606497.      3494292.25       10606467.
        3494763.       10606345.       3494905.5       10606281.
      3494978.25       10606274.        3495054.       10606337.
        3495105.       10606321.        3495188.       10606393.

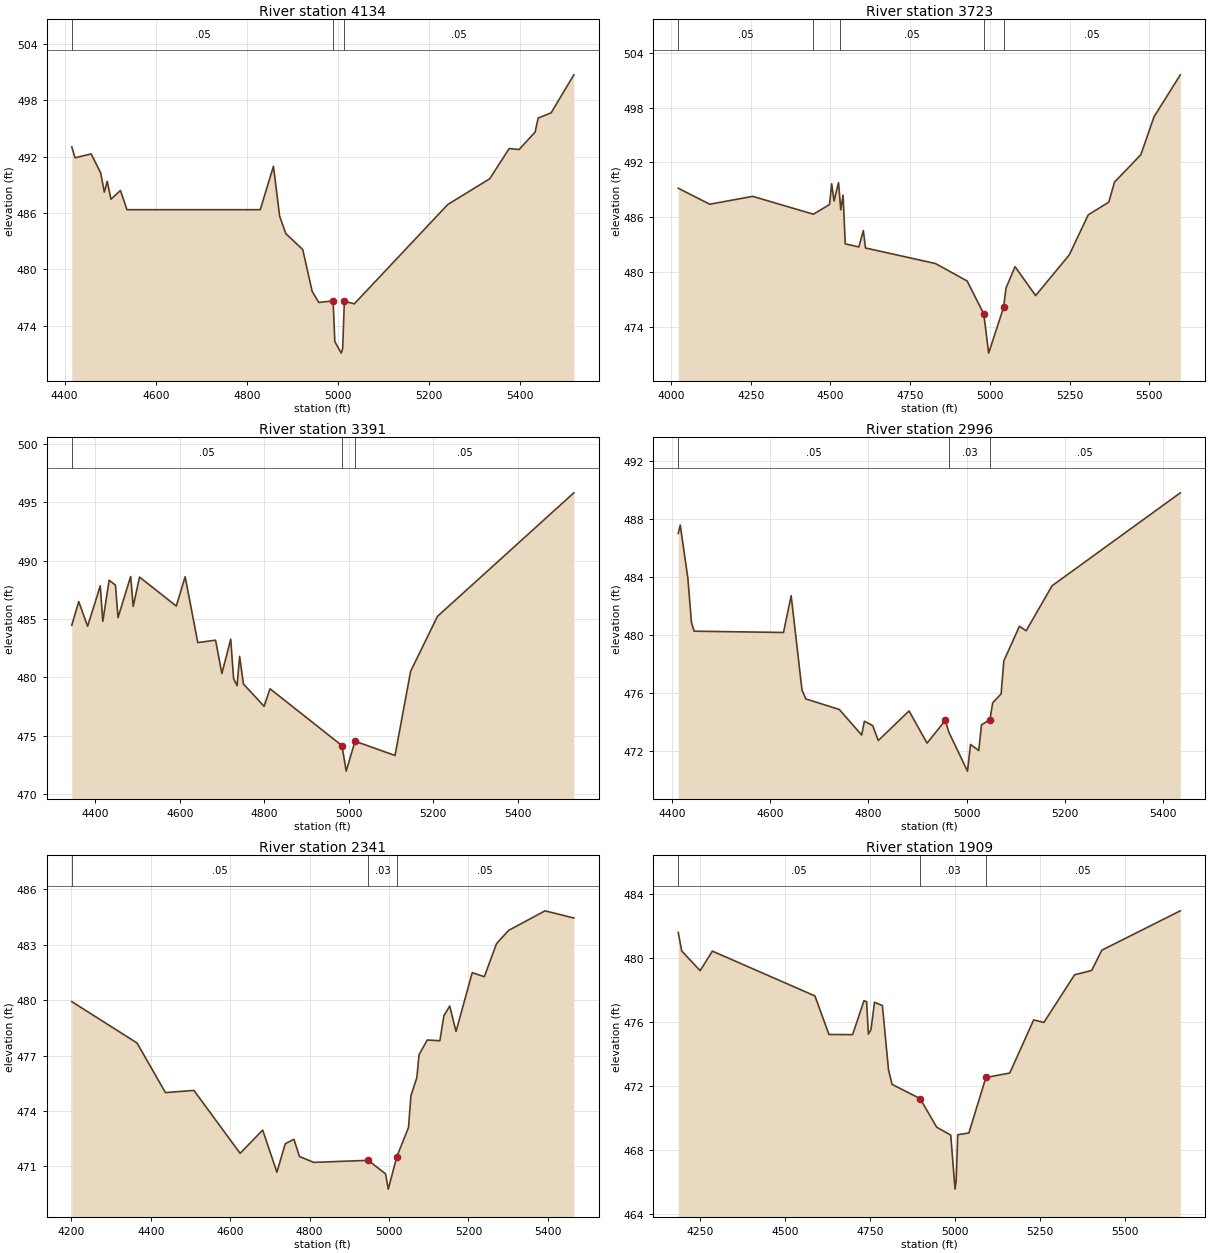
Type RM Length L Ch R = 1 ,4134    ,411,411,411
BEGIN DESCRIPTION:
SALT CREEK 2 9.0
END DESCRIPTION:
XS GIS Cut Line= 3
      3491299.62     10605810.18      3491749.61     10605460.19
      3492149.62     10605110.18
#Sta/Elev= 30
  4415.8  493.03    4423  491.87  4458.3  492.28  4479.1  490.28  4487.3  488.22
  4493.6  489.37  4501.8  487.47  4522.6  488.39    4537  486.35  4829.3  486.35
  4858.3  490.96  4871.9  485.66  4885.4  483.81  4922.5  482.12  4943.3  477.66
  4957.8  476.49  4989.2  476.65    4993  472.32    5007   471.1  5010.2   471.6
  5013.9  476.62  5035.7  476.34  5240.7   486.9  5332.8  489.64  5375.5  492.85
  5397.3  492.75  5432.4   494.6  5439.1  496.09  5467.6  496.65  5517.4  500.69
#Mann= 3 , 0 , 0
  4415.8     .05       0  4989.2     .03       0  5013.9     .05       0
Bank Sta=4989.2,5013.9
XS Rating Curve= 0 ,0
Exp/Cntr=0.3,0.1

Type RM Length L Ch R = 1 ,3723    ,332,332,332
BEGIN DESCRIPTION:
SALT CREEK 2 8.0
END DESCRIPTION:
XS GIS Cut Line= 3
      3491399.62     10606410.17      3492049.61     10605710.19
      3492199.61     10605110.18
#Sta/Elev= 30
  4023.1  489.19    4122  487.44  4256.4   488.3  4446.9  486.35  4497.3  487.41
  4504.1  489.67  4511.5  487.79  4525.6  489.81  4530.1  487.87  4532.5  486.83
  4539.8  488.43  4546.6  483.11  4589.1  482.77  4603.3  484.56  4610.1  482.66
  4829.5  480.96  4928.7  479.05  4980.9  475.45  4996.1  471.17  5042.8  476.16
  5050.5  478.28  5078.8  480.62  5143.3  477.46  5248.9  481.91  5308.2  486.28
  5372.6  487.67  5390.6  489.86  5473.1  492.85  5514.3  496.99  5596.8  501.58
#Mann= 5 ,-1 , 0
  4023.1     .05       0  4446.9     .07       0  4530.1     .05       0
  4980.9     .03       0  5042.8     .05       0
Bank Sta=4980.9,5042.8
XS Rating Curve= 0 ,0
Exp/Cntr=0.3,0.1

Type RM Length L Ch R = 1 ,3391    ,395,395,395
BEGIN DESCRIPTION:
SALT CREEK 2 7.0
END DESCRIPTION:
XS GIS Cut Line= 3
      3492034.88     10606288.16      3492364.75     10605797.69
      3492503.64     10605216.12
#Sta/Elev= 30
  4344.2  484.46  4360.7  486.49  4381.7  484.38  4411.7  487.84  4417.7   484.8
  4432.7  488.32  4447.7   487.9  4453.7  485.12  4483.7  488.64  4489.7  486.08
  4504.7  488.59  4591.7  486.11  4612.7  488.62  4642.7  482.98  4684.7  483.19
  4699.7  480.34  4720.7  483.27  4727.4   479.9  4735.7  479.29  4741.7   481.8
  4750.7  479.44  4799.7  477.53  4813.7  479.03  4984.1  474.16  4994.1  471.98
    5015  474.54  5109.7  473.32  5146.7  480.53  5210.3  485.23  5533.2   495.8
#Mann= 3 , 0 , 0
  4344.2     .05       0  4984.1     .03       0    5015     .05       0
Bank Sta=4984.1,5015
XS Rating Curve= 0 ,0
Exp/Cntr=0.3,0.1

Type RM Length L Ch R = 1 ,2996    ,655,655,655
BEGIN DESCRIPTION:
SALT CREEK 2 6.0
END DESCRIPTION:
XS GIS Cut Line= 2
      3492492.38     10606387.92      3492930.34      10605464.3
#Sta/Elev= 30
    4413  487.03  4417.1  487.61  4432.6  483.94  4439.9  480.89  4445.4  480.29
  4627.3   480.2  4642.9  482.73    4665  476.23  4672.8  475.62    4741  474.89
  4786.4  473.13    4792  474.08  4808.9  473.78  4820.3  472.75  4882.9  474.79
  4919.6  472.57  4956.7  474.14  4963.9  473.33  5001.9  470.64  5008.1  472.48
  5024.9  472.06  5030.4  473.83  5047.6  474.19  5053.2  475.35  5070.4  475.97
  5075.9  478.24  5107.7  480.63  5121.4  480.32  5174.1  483.42  5435.2  489.83
#Mann= 3 ,-1 , 0
    4413     .05       0  4963.9     .03       0  5047.6     .05       0
Bank Sta=4956.7,5047.6
XS Rating Curve= 0 ,0
Exp/Cntr=0.3,0.1

Type RM Length L Ch R = 1 ,2341    ,432,432,432
BEGIN DESCRIPTION:
SALT CREEK 2 5.0
END DESCRIPTION:
XS GIS Cut Line= 3
      3492791.85     10606861.04      3493290.97     10606136.23
      3493364.68     10605759.01
#Sta/Elev= 30
  4200.9  479.92  4365.2  477.68  4436.8  474.99  4508.5  475.11  4624.9   471.7
  4681.7  472.96  4717.5  470.68  4738.5  472.22  4760.5  472.46  4774.3  471.53
  4810.2  471.21  4947.5  471.32  4991.1  470.59    4998  469.76  5019.2   471.5
  5048.9   473.1    5055  474.82  5069.9   475.8  5075.5  477.04  5096.1  477.84
  5127.9   477.8    5138  479.15  5152.7  479.68  5168.6   478.3  5209.4  481.49
  5239.9  481.27  5270.5  483.06  5301.1  483.78  5392.8  484.84  5465.3  484.45
#Mann= 3 , 0 , 0
  4200.9     .05       0  4947.5     .03       0  5019.2     .05       0
Bank Sta=4947.5,5019.2
XS Rating Curve= 0 ,0
Exp/Cntr=0.3,0.1

Type RM Length L Ch R = 1 ,1909    ,350,350,350
BEGIN DESCRIPTION:
SALT CREEK 2 4.0
END DESCRIPTION:
XS GIS Cut Line= 3
      3493299.61     10607310.17      3493499.61     10606510.19
      3493549.61     10605860.21
#Sta/Elev= 30
  4186.3  481.62  4196.6  480.46  4250.7  479.23  4286.8  480.45  4588.3  477.65
  4629.5  475.24  4699.1  475.23  4732.6  477.35  4740.3  477.29  4745.5  475.26
  4753.2  475.55  4763.5  477.25  4786.7  477.05  4804.7  473.03  4815.1  472.12
  4897.5  471.23  4946.5  469.44  4987.7  468.95  5000.3  465.57  5003.6  466.07
  5008.3  468.97    5041  469.08  5091.1  472.55  5161.3  472.83  5231.6  476.15
  5261.6  475.99  5351.9  478.97  5402.1  479.24  5432.1  480.51  5662.8  482.97
#Mann= 3 , 0 , 0
  4186.3     .05       0  4897.5     .03       0  5091.1     .05       0
Bank Sta=4897.5,5091.1
XS Rating Curve= 0 ,0
Exp/Cntr=0.3,0.1

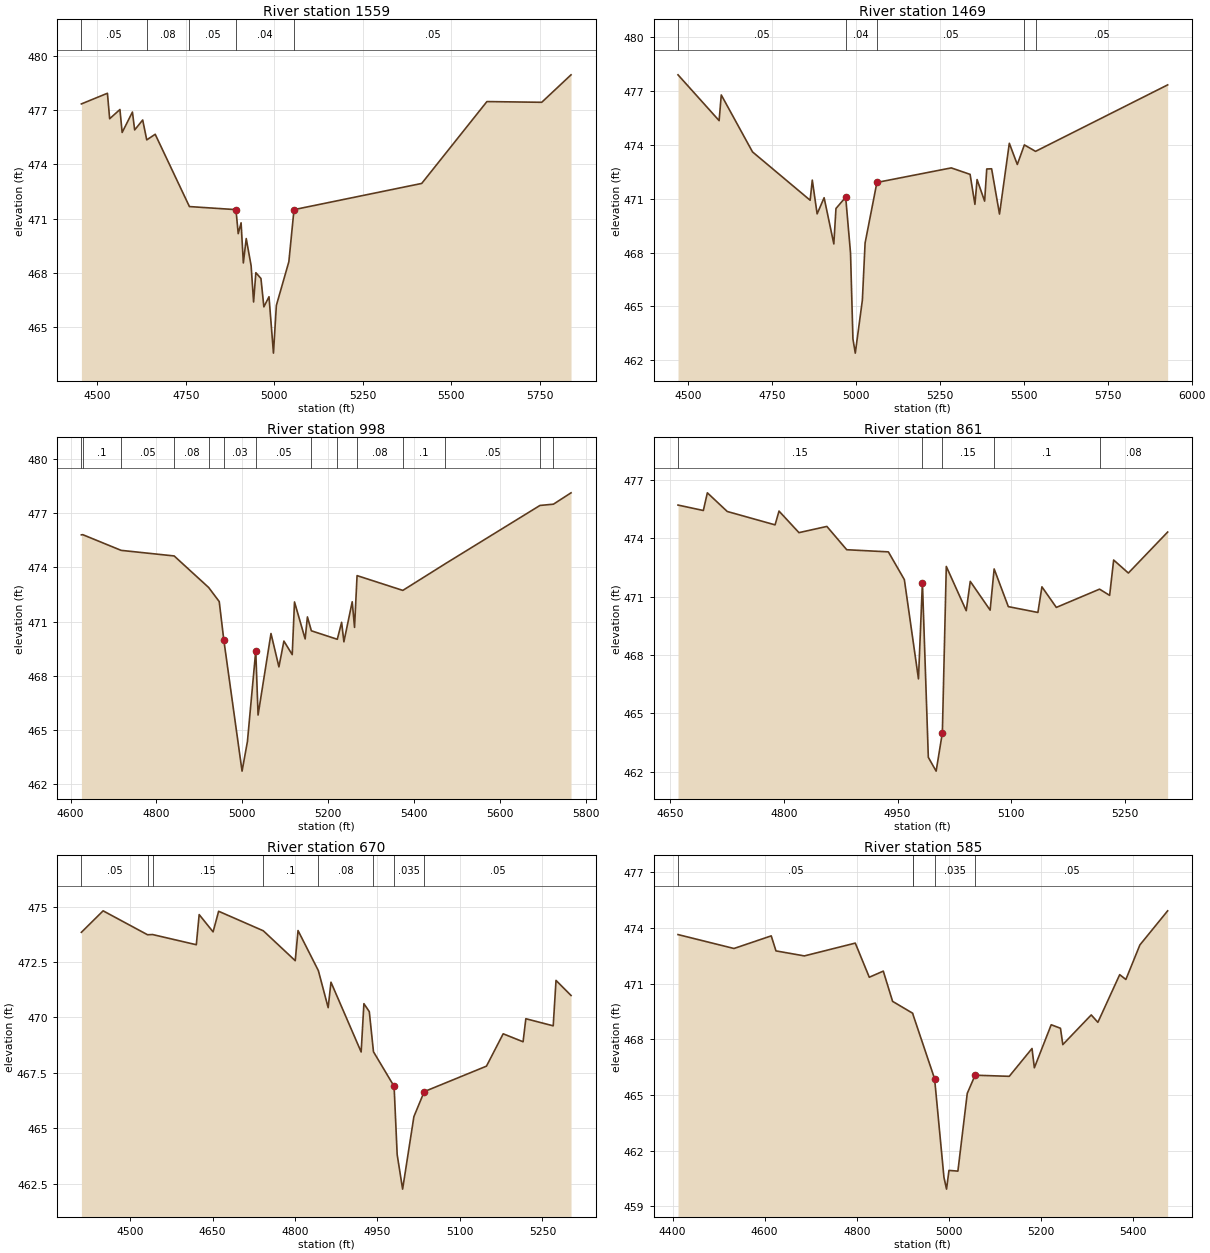
Type RM Length L Ch R = 1 ,1559    ,90,90,90
BEGIN DESCRIPTION:
Mapping XS 6357ea05
END DESCRIPTION:
XS GIS Cut Line= 3
      3493485.95     10607028.66      3494056.25      10606294.3
      3493884.53     10605875.43
#Sta/Elev= 30
  4455.5  477.35    4529  477.94  4535.3  476.53  4564.3  477.04  4570.6  475.77
  4599.6   476.9  4605.9  475.91  4628.6  476.46    4640  475.36  4663.9  475.67
  4760.5  471.67  4891.9   471.5  4898.3  470.17  4906.4  470.77  4912.8  468.55
  4920.9   469.9  4934.7   468.4  4941.7  466.39  4948.1  468.01  4962.5  467.69
  4970.7  466.12  4985.2  466.68  4997.8  463.56    5006   466.2  5041.3  468.62
  5055.8   471.5  5416.4  472.95  5600.5  477.48  5755.3  477.44    5838  478.96
#Mann= 5 ,-1 , 0
  4455.5     .05       0    4640     .08       0  4760.5     .05       0
  4891.9     .04       0  5055.8     .05       0
Bank Sta=4891.9,5055.8
XS Rating Curve= 0 ,0
Exp/Cntr=0.3,0.1

Type RM Length L Ch R = 1 ,1469    ,471,471,471
BEGIN DESCRIPTION:
SALT CREEK 2 3.0
END DESCRIPTION:
XS GIS Cut Line= 3
      3493577.05     10607039.13      3494160.41     10606299.51
      3493960.37     10605824.07
#Sta/Elev= 30
  4470.7  477.89  4593.1  475.34  4599.5  476.77  4692.5   473.6  4864.1  470.91
  4870.5  472.03  4884.9  470.15  4905.7  471.05  4934.6  468.48    4941  470.45
  4969.9  471.08  4984.3  467.98  4991.5  463.19  4998.5   462.4  5019.6  465.35
  5027.7  468.53  5062.9   471.9  5284.2  472.71  5340.3  472.35  5354.7  470.68
  5361.1  472.06  5383.6  470.86  5389.9  472.65  5404.4  472.66  5427.9  470.14
  5457.1  474.08  5480.9   472.9  5501.9  473.99  5535.2  473.63  5928.5  477.33
#Mann= 5 ,-1 , 0
  4470.7     .05       0  4969.9     .04       0  5062.9     .05       0
  5501.9     .08       0  5535.2     .05       0
Bank Sta=4969.9,5062.9
XS Rating Curve= 0 ,0
Exp/Cntr=0.3,0.1

Type RM Length L Ch R = 1 ,998     ,137,137,137
BEGIN DESCRIPTION:
Mapping XS 1c321e02
END DESCRIPTION:
XS GIS Cut Line= 2
      3494420.84     10606820.37      3494015.08     10605753.95
#Sta/Elev= 30
  4625.1  475.81  4628.3  475.82  4717.7  474.95  4841.3  474.64  4921.7  472.89
  4946.3  472.11  4957.1  469.96  4999.5  462.71    5012  464.35  5031.4  469.38
  5036.8  465.82  5066.9  470.34  5085.4  468.49    5097  469.92  5116.4  469.17
  5121.7  472.09  5146.5  470.04  5151.8  471.26    5161  470.49  5221.4  470.02
  5231.5  470.96  5236.8  469.88  5256.2   472.1  5261.6  470.68  5267.5  473.55
  5374.1  472.73  5473.2  474.21  5693.7  477.44  5725.1  477.51  5766.1  478.14
#Mann= 14 ,-1 , 0
  4625.1     .05       0  4628.3      .1       0  4717.7     .05       0
  4841.3     .08       0  4921.7      .1       0  4957.1     .03       0
  5031.4     .05       0    5161      .1       0  5221.4     .05       0
  5267.5     .08       0  5374.1      .1       0  5473.2     .05       0
  5693.7      .1       0  5725.1     .05       0
Bank Sta=4957.1,5031.4
XS Rating Curve= 0 ,0
Exp/Cntr=0.3,0.1

Type RM Length L Ch R = 1 ,861     ,191,191,191
BEGIN DESCRIPTION:
Mapping XS 1ad6a058
END DESCRIPTION:
XS GIS Cut Line= 2
      3494526.51     10606753.12      3494320.76     10606141.08
#Sta/Elev= 30
  4660.4  475.72  4693.8  475.44  4699.1  476.35  4725.3  475.39  4788.4   474.7
  4793.6  475.41  4819.9   474.3  4856.7  474.62  4882.9  473.42  4937.8  473.31
  4958.9  471.88  4977.5  466.77  4982.7  471.73  4990.5  462.73  5000.8  462.02
    5009  463.99  5014.2  472.56  5040.5  470.28  5045.8  471.79    5072  470.31
  5077.3  472.43    5096  470.49    5135  470.19  5140.3  471.51  5159.3  470.45
  5216.3  471.39  5229.6  471.07  5234.9  472.89  5254.3  472.22  5306.1  474.33
#Mann= 5 ,-1 , 0
  4660.4     .15       0  4982.7     .07       0    5009     .15       0
  5077.3      .1       0  5216.3     .08       0
Bank Sta=4982.7,5009
XS Rating Curve= 0 ,0
Exp/Cntr=0.3,0.1

Type RM Length L Ch R = 1 ,670     ,85,85,85
BEGIN DESCRIPTION:
SALT CREEK 2 2.0
END DESCRIPTION:
XS GIS Cut Line= 2
      3494700.97     10606956.17      3494549.93     10606078.57
#Sta/Elev= 30
  4411.5  473.84    4451  474.81  4531.8  473.73  4540.9  473.74  4620.5  473.28
  4625.7  474.64    4651  473.86  4661.1  474.79  4742.3  473.91  4800.4  472.56
  4805.5  473.92  4842.5  472.11  4860.3  470.44  4865.4  471.59  4920.3  468.44
  4925.3  470.62  4935.1  470.26  4942.7  468.45  4980.2  466.89  4985.8  463.81
  4995.7  462.25  5016.2  465.52    5035  466.65  5148.2   467.8  5178.6  469.26
  5214.8   468.9  5219.8  469.94  5269.6  469.62  5274.7  471.67    5302  470.99
#Mann= 8 ,-1 , 0
  4411.5     .05       0  4531.8      .1       0  4540.9     .15       0
  4742.3      .1       0  4842.5     .08       0  4942.7     .05       0
  4980.2    .035       0    5035     .05       0
Bank Sta=4980.2,5035
XS Rating Curve= 0 ,0
Exp/Cntr=0.3,0.1

Type RM Length L Ch R = 1 ,585     ,454,454,454
BEGIN DESCRIPTION:
Mapping XS 2660ba3e
END DESCRIPTION:
XS GIS Cut Line= 2
      3494777.61     10606940.18      3494608.33     10605890.64
#Sta/Elev= 30
  4411.9  473.65  4533.4   472.9  4614.3  473.58  4624.6  472.77  4686.2   472.5
  4796.8  473.19  4827.2  471.35  4857.6  471.68  4877.8  470.05  4921.4  469.41
  4922.5  469.31    4969  465.88  4989.3  460.57  4994.9  459.93  5000.2  460.94
  5019.6   460.9  5039.9  465.09  5056.9  466.07  5131.1  466.01  5180.5  467.51
  5185.6  466.47  5222.2  468.79  5242.3   468.6  5247.4  467.72  5309.1  469.32
  5323.5  468.92  5370.9  471.49  5384.3  471.23  5414.7  473.09    5475  474.93
#Mann= 5 ,-1 , 0
  4411.9     .05       0  4921.4     .08       0  4922.5     .05       0
    4969    .035       0  5056.9     .05       0
Bank Sta=4969,5056.9
XS Rating Curve= 0 ,0
Exp/Cntr=0.3,0.1

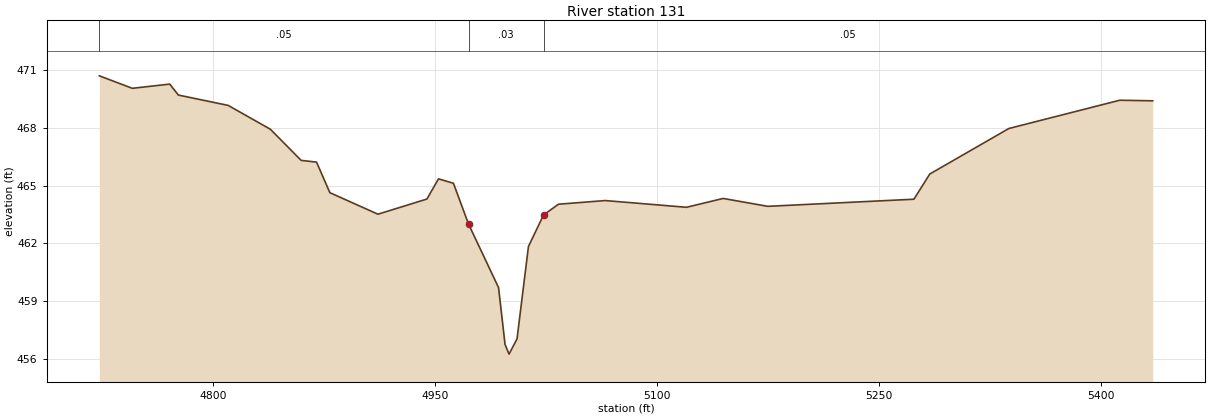
Type RM Length L Ch R = 1 ,131     ,0,0,0
BEGIN DESCRIPTION:
SALT CREEK 2 1.0
END DESCRIPTION:
XS GIS Cut Line= 4
      3495042.11     10606591.65      3495096.81     10606393.71
      3495078.58     10606284.33      3494708.76     10606143.69
#Sta/Elev= 30
  4723.2  470.72  4745.5  470.07  4770.8  470.29  4776.6  469.72  4810.3  469.18
  4838.8  467.94  4859.6  466.32    4870  466.23    4879  464.64  4911.5  463.52
  4944.6  464.31  4952.4  465.36  4962.5  465.13  4972.7  463.01    4993   459.7
  4997.4  456.74  5000.1  456.24  5005.5  457.04  5013.2  461.84  5023.4  463.48
  5033.5  464.04  5065.1  464.23    5120  463.88  5144.8  464.34  5174.9  463.93
  5273.7   464.3  5284.4  465.61  5337.9  467.98  5412.8  469.45  5435.1  469.42
#Mann= 3 , 0 , 0
  4723.2     .05       0  4972.7     .03       0  5023.4     .05       0
Bank Sta=4972.7,5023.4
XS Rating Curve= 0 ,0
Exp/Cntr=0.3,0.1

Chan Stop Cuts=-1
Use User Specified Reach Order=0
Composite Channel Slope=5