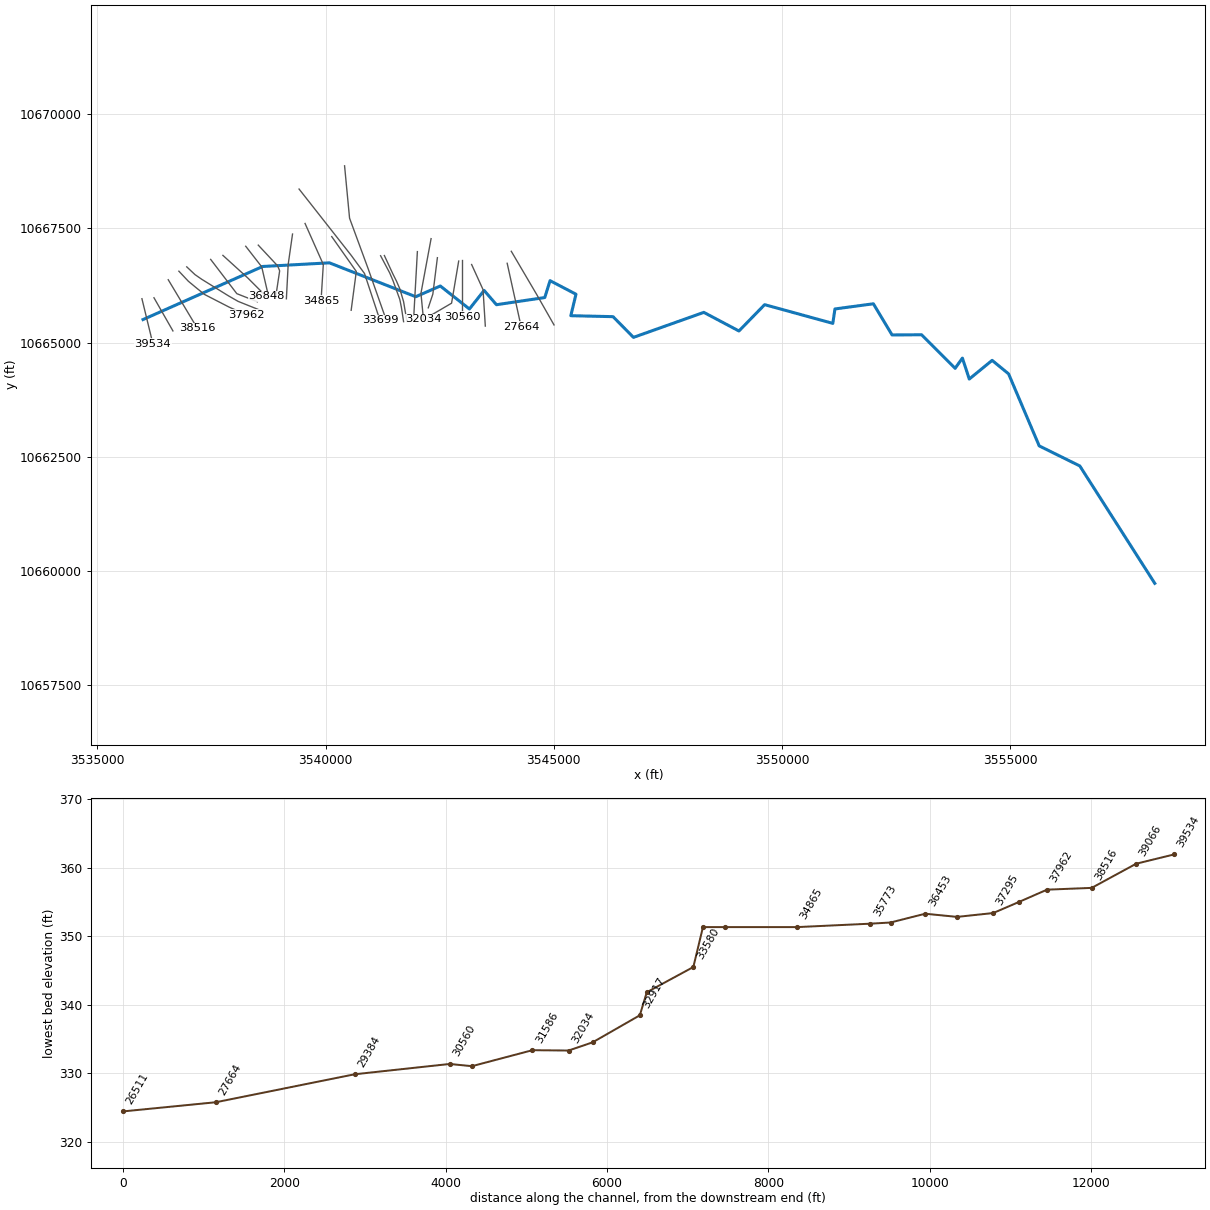
--- SLOAN CREEK.prj (project) ---

Proj Title=SLOAN CREEK Base Level Engineering
Current Plan=p01
Default Exp/Contr=0.3,0.1
English Units
Geom File=g01
Flow File=f01
Plan File=p01
Y Axis Title=Elevation
X Axis Title(PF)=Main Channel Distance
X Axis Title(XS)=Station
BEGIN DESCRIPTION:
SLOAN CREEK
END DESCRIPTION:
DSS File=dss
DSS Export Rating Curves= 0
DSS Export Rating Curve Sorted= 0
DSS Export Volume Flow Curves= 0
DXF OffsetX= 0
DXF OffsetY= 0
DXF ScaleX= 1
DXF ScaleY= 10

--- SLOAN CREEK.p01 (plan) ---

Plan Title=Multiple Run
Program Version=4.10
Short Identifier=Multiple Run
Geom File=g01
Flow File=f01
Subcritical Flow
K Sum by GR= 0
Std Step Tol= 0.01
Critical Tol= 0.01
Num of Std Step Trials= 20
Max Error Tol= 0.3
Flow Tol Ratio= 0.001
Split Flow NTrial= 30
Split Flow Tol= 0.02
Split Flow Ratio= 0.02
Log Output Level= 0
Friction Slope Method= 1
Unsteady Friction Slope Method= 2
Unsteady Bridges Friction Slope Method= 1
Parabolic Critical Depth
Global Vel Dist= 1 , 1 , 1
Global Log Level= 0
CheckData=True
Encroach Param=-1 ,0,0, 0
BEGIN DESCRIPTION:
Multiple Run
END DESCRIPTION:
Computation Interval=1HOUR
Output Interval=1HOUR
Run HTab= 0
Run UNet= 0
Run PostProcess= 0
Run WQNet= 0
UNET Theta= 1
UNET Theta Warmup= 1
UNET ZTol= 0.02
UNET ZSATol= 0.05
UNET MxIter= 20
UNET MaxInSteps= 0
UNET DtIC= 0
UNET DtMin= 0
UNET MaxCRTS= 20
UNET WFStab= 2
UNET SFStab= 1
UNET WFX= 1
UNET SFX= 1
UNET DSS MLevel= 4
UNET DZMax Abort= 100
UNET Convert EG Bridges= 0
UNET Use Existing IB Tables=-1
UNET Froude Reduction=False
UNET Froude Limit= 1
UNET Froude Power= 10
UNET Time Slicing=0,0, 5
UNET Junction Losses=0
Instantaneous Interval=1HOUR
DSS File=dss
Write IC File= 0
Write IC File at Sim End=0
Echo Input=False
Echo Parameters=False
Echo Output=False
Write Detailed= 0
WQ AD Non Conservative
WQ ULTIMATE=-1
WQ Max Comp Step=1HOUR
WQ Output Interval=15MIN
WQ Output Selected Increments= 0
WQ Output face flow=0
WQ Output face velocity=0
WQ Output face area=0
WQ Output face dispersion=0
WQ Output cell volume=0
WQ Output cell surface area=0
WQ Output cell continuity=0
WQ Output cumulative cell continuity=0
WQ Output face conc=0
WQ Output face dconc_dx=0
WQ Output face courant=0
WQ Output face peclet=0
WQ Output face adv mass=0
WQ Output face disp mass=0
WQ Output cell mass=0
WQ Output cell source sink temp=0
WQ Output cell source sink nsm=0
WQ Output MaxMinRange=-1
WQ Daily Max Min Mean=-1
WQ Daily Range=0
WQ Daily Time=0
WQ Create Restart=0
WQ Fixed Restart=0
WQ System Summary=0
WQ Use Fixed Temperature=0
Sorting and Armoring Iterations= 10
XS Update Threshold= 0.02
Hydraulics Update Threshold= 0.02
Energy Slope Method= 1
Volume Change Method= 0
XS Weighting Method= 0
Number of US Weighted Cross Sections= 1
Number of DS Weighted Cross Sections= 1
Upstream XS Weight=0.25
Main XS Weight=0.5
Downstream XS Weight=0.25
Number of DS XS's Weighted with US Boundary= 1
Upstream Boundary Weight= 1
Weight of XSs Associated with US Boundary= 0
Number of US XS's Weighted with DS Boundary= 1
Downstream Boundary Weight= 0.5
Weight of XSs Associated with DS Boundary= 0.5
Sediment Output Level= 4
Mass or Volume Output= 0
Output Increment Type= 1
Profile and TS Output Increment= 10
XS Output Flag= 0
XS Output Increment= 10
Disregard all LS=0
Disregard all Conn=0
Disregard all Breaches=0
Disregard all Pumps=0

--- SLOAN CREEK.f01 (steady flow) ---

Flow Title=Multiple
Program Version=4.10
Number of Profiles= 7
Profile Names=10-year,25-year,50-year,1pct_min,100-year,1pct_plu,500-year
River Rch & RM=SLOAN CREEK,Reach-1         ,39534
     936    1242    1483    1292    1747    2363    2417
River Rch & RM=SLOAN CREEK,Reach-1         ,37613
    1137    1533    1852    1630    2205    2982    3118
River Rch & RM=SLOAN CREEK,Reach-1         ,35773
    1838    2544    3127    2797    3783    5116    5527
River Rch & RM=SLOAN CREEK,Reach-1         ,33699
    2414    3384    4195    3782    5115    6917    7588
River Rch & RM=SLOAN CREEK,Reach-1         ,33003
    2414    3384    4195    3782    5115    6917    7588
River Rch & RM=SLOAN CREEK,Reach-1         ,24477
    3678    5228    6541    5942    8036   10868   12108
River Rch & RM=SLOAN CREEK,Reach-1         ,15368
    4090    5830    7308    6649    8992   12160   13589
River Rch & RM=SLOAN CREEK,Reach-1         ,14933
    4090    5830    7308    6649    8992   12160   13589
River Rch & RM=SLOAN CREEK,Reach-1         ,12242
    4636    6624    8318    7576   10246   13856   15520
River Rch & RM=SLOAN CREEK,Reach-1         ,10306
    4636    6624    8318    7576   10246   13856   15520
Boundary for River Rch & Prof#=SLOAN CREEK,Reach-1         , 1
Up Type= 0
Dn Type= 3
Dn Slope=0.00159
Boundary for River Rch & Prof#=SLOAN CREEK,Reach-1         , 2
Up Type= 0
Dn Type= 3
Dn Slope=0.00159
Boundary for River Rch & Prof#=SLOAN CREEK,Reach-1         , 3
Up Type= 0
Dn Type= 3
Dn Slope=0.00159
Boundary for River Rch & Prof#=SLOAN CREEK,Reach-1         , 4
Up Type= 0
Dn Type= 3
Dn Slope=0.00159
Boundary for River Rch & Prof#=SLOAN CREEK,Reach-1         , 5
Up Type= 0
Dn Type= 3
Dn Slope=0.00159
Boundary for River Rch & Prof#=SLOAN CREEK,Reach-1         , 6
Up Type= 0
Dn Type= 3
Dn Slope=0.00159
Boundary for River Rch & Prof#=SLOAN CREEK,Reach-1         , 7
Up Type= 0
Dn Type= 3
Dn Slope=0.00159
DSS Import GetInterval= 0
DSS Import GetPeak= 0
DSS Import FillOption= 0

--- SLOAN CREEK.g01 (geometry) ---

Geom Title=Existing Conditions
Program Version=4.10

River Reach=SLOAN CREEK     ,Reach-1
Reach XY= 30
      3535999.27     10665503.58        3538621.       10666667.
      3540083.25       10666747.      3541974.25       10666004.
       3542513.5       10666239.      3543151.25       10665735.
        3543473.       10666142.      3543743.75       10665829.
      3544802.25       10665986.       3544918.5       10666356.
      3545486.25       10666059.      3545373.25       10665588.
       3546298.5       10665567.      3546745.75       10665113.
      3548287.75       10665661.       3549057.5       10665253.
      3549620.25       10665830.       3551114.5       10665420.
        3551161.       10665736.      3552003.75       10665849.
       3552412.5       10665166.       3553059.5       10665170.
      3553794.75       10664434.        3553954.       10664659.
      3554104.75       10664199.       3554605.5       10664609.
        3554966.       10664313.        3555637.       10662734.
      3556526.75       10662294.       3558169.5       10659720.

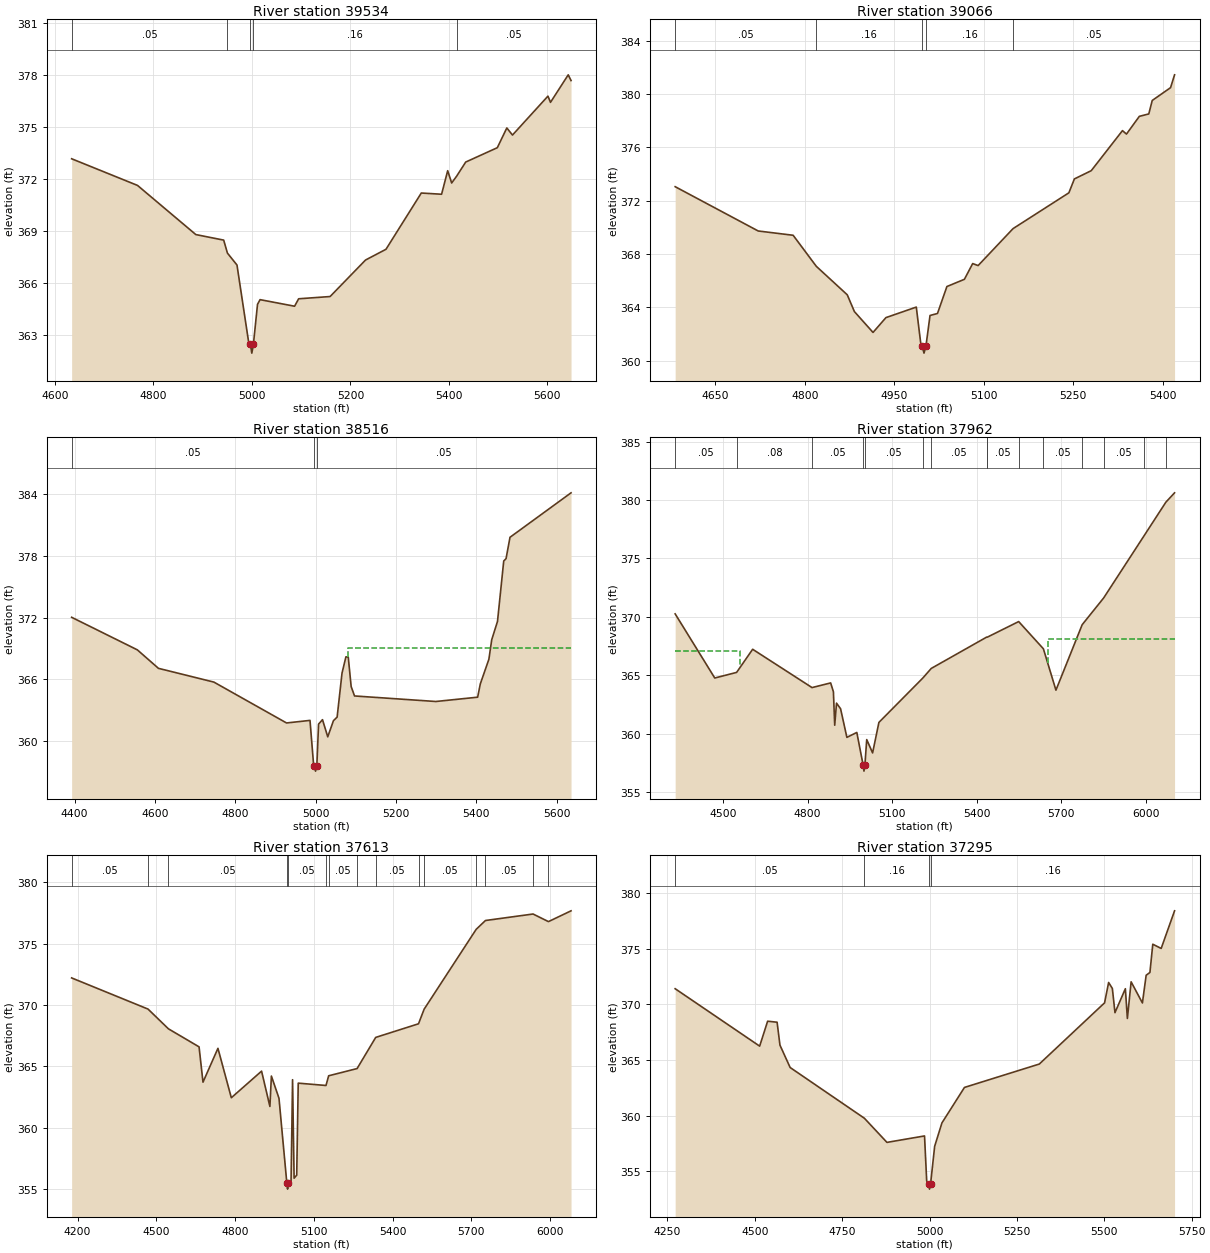
Type RM Length L Ch R = 1 ,39534   ,468,468,468
BEGIN DESCRIPTION:
SLOAN CREEK 64.0
END DESCRIPTION:
XS GIS Cut Line= 2
      3535975.03     10665960.21      3536214.48     10664974.68
#Sta/Elev= 30
  4633.9  373.16  4767.7  371.62  4886.1  368.78  4942.7  368.46  4950.3  367.71
  4969.7  367.02  4994.1  362.43    4997  362.43  4999.8  361.93    5003  362.43
  5011.4  364.75  5016.6  365.02  5086.7  364.64  5094.9  365.07  5158.8   365.2
  5230.8  367.31  5272.3  367.93    5344  371.18  5385.2  371.11  5397.6  372.47
  5405.7  371.76  5415.9  372.16  5434.2  372.97  5498.4   373.8  5517.7  374.94
  5529.2  374.53  5601.2  376.78  5606.4  376.42  5642.4  378.01  5648.1  377.68
#Mann= 5 ,-1 , 0
  4633.9     .05       0  4950.3     .16       0    4997     .07       0
    5003     .16       0  5415.9     .05       0
Bank Sta=4997,5003
XS Rating Curve= 0 ,0
Exp/Cntr=0.3,0.1

Type RM Length L Ch R = 1 ,39066   ,550,550,550
BEGIN DESCRIPTION:
SLOAN CREEK 63.0
END DESCRIPTION:
XS GIS Cut Line= 2
      3536238.92     10665981.04      3536654.14      10665254.4
#Sta/Elev= 30
  4582.8  373.05    4722  369.73  4780.5  369.41  4819.4  367.08  4871.2  364.95
  4883.2  363.69  4914.4  362.13    4936  363.24  4986.9  364.03    4995  361.08
    4997  361.08  4999.8  360.58    5003  361.08  5009.9   363.4  5022.4  363.55
  5038.2  365.57  5067.5  366.11  5081.4  367.29  5090.5  367.14  5149.1  369.91
  5242.6  372.59  5251.8  373.63  5280.1  374.25  5332.4  377.25  5339.1  376.99
  5360.7  378.32  5376.5   378.5  5382.3  379.51    5413  380.47  5419.7  381.43
#Mann= 5 ,-1 , 0
  4582.8     .05       0  4819.4     .16       0    4997     .07       0
    5003     .16       0  5149.1     .05       0
Bank Sta=4997,5003
XS Rating Curve= 0 ,0
Exp/Cntr=0.3,0.1

Type RM Length L Ch R = 1 ,38516   ,554,554,554
BEGIN DESCRIPTION:
Mapping XS 673ef40f
END DESCRIPTION:
XS GIS Cut Line= 2
      3536551.42     10666376.87      3537190.33     10665310.87
#Sta/Elev= 30
  4392.8  372.04  4556.3  368.87  4608.8  367.07  4746.8  365.73  4927.6  361.75
    4986     362  4995.2  357.56    4997  357.56  4999.8  357.06    5003  357.56
  5007.3  361.64  5017.1  362.07  5030.2   360.4  5044.3  361.97  5053.5  362.32
  5065.7  366.61  5075.4  368.19  5081.2  368.16  5088.4   365.3  5096.8  364.38
    5299  363.84  5403.2  364.26  5409.8  365.55  5431.2  367.96  5438.2  369.85
  5452.6  371.64  5468.1  377.52  5473.9  377.75  5483.7  379.83  5635.6  384.16
#Mann= 3 ,-1 , 0
  4392.8     .05       0    4997    .035       0    5003     .05       0
#XS Ineff= 2 , 0
                         5080.91          369.01
Permanent Ineff=
       F       F
Bank Sta=4997,5003
XS Rating Curve= 0 ,0
Exp/Cntr=0.3,0.1

Type RM Length L Ch R = 1 ,37962   ,349,349,349
BEGIN DESCRIPTION:
SLOAN CREEK 62.0
END DESCRIPTION:
XS GIS Cut Line= 6
      3536784.78     10666563.79      3536993.12     10666342.44
      3537188.43     10666180.98      3537347.28     10666053.37
      3537888.95     10665774.73      3538255.35     10665611.01
#Sta/Elev= 30
    4330  370.26  4470.5  364.77    4548  365.25  4604.9  367.23  4815.6  363.95
  4881.6  364.35  4891.4  363.59    4896  360.73  4902.4  362.62  4916.8  362.14
  4939.2  359.69  4974.4  360.11    4997   357.3  4999.8   356.8    5003   357.3
  5009.6   359.5  5030.4  358.36  5052.8  360.97  5207.9  364.75  5238.5  365.59
    5435  368.27  5437.7  368.27  5548.6   369.6  5636.3  367.27  5680.8  363.73
  5773.8  369.33    5850  371.62  5994.4  376.98  6070.8  379.82  6101.6  380.62
#Mann= 15 ,-1 , 0
    4330     .05       0    4548     .08       0  4815.6     .05       0
    4997    .035       0    5003     .05       0  5207.9     .08       0
  5238.5     .05       0    5435      .1       0  5437.7     .05       0
  5548.6     .08       0  5636.3     .05       0  5773.8     .08       0
    5850     .05       0  5994.4      .1       0  6070.8     .05       0
#XS Ineff= 2 , 0
         4561.08  367.05 5651.99           368.1
Permanent Ineff=
       F       F
Bank Sta=4997,5003
XS Rating Curve= 0 ,0
Exp/Cntr=0.3,0.1

Type RM Length L Ch R = 1 ,37613   ,318,318,318
BEGIN DESCRIPTION:
SLOAN CREEK 61.0
END DESCRIPTION:
XS GIS Cut Line= 6
      3536957.08     10666658.85      3537136.78     10666489.57
      3537282.61     10666388.01      3537871.15     10666023.42
       3538084.7     10665901.03      3538584.62     10665700.54
#Sta/Elev= 30
  4177.4  372.22  4468.3  369.68    4546  368.07  4662.7   366.6  4677.7  363.72
  4734.6  366.48  4785.6  362.45  4900.8  364.62  4932.5  361.74  4938.2  364.22
  4967.1  362.41    4997   355.5  4999.8     355    5003   355.5    5013   355.6
  5018.8  363.92  5024.7  355.89  5034.6  356.14  5040.4  363.64  5146.1  363.45
  5156.3  364.24  5264.6  364.83  5335.5  367.37  5498.5  368.48  5519.9  369.67
  5718.1  376.18  5753.5   376.9  5934.8  377.43  5993.4  376.81  6079.4  377.69
#Mann= 15 ,-1 , 0
  4177.4     .05       0  4468.3     .08       0    4546     .05       0
    4997     .04       0    5003     .05       0  5146.1     .16       0
  5156.3     .05       0  5264.6     .16       0  5335.5     .05       0
  5498.5     .16       0  5519.9     .05       0  5718.1     .16       0
  5753.5     .05       0  5934.8     .16       0  5993.4     .05       0
Bank Sta=4997,5003
XS Rating Curve= 0 ,0
Exp/Cntr=0.3,0.1

Type RM Length L Ch R = 1 ,37295   ,447,447,447
BEGIN DESCRIPTION:
SLOAN CREEK 60.0
END DESCRIPTION:
XS GIS Cut Line= 3
      3537481.42     10666822.01      3538054.31     10666071.17
       3538505.2     10665893.41
#Sta/Elev= 30
    4272   371.4  4513.8  366.24  4536.6  368.48  4563.7  368.39  4571.9  366.33
    4601  364.32  4813.5  359.76  4878.1  357.59  4985.6  358.17  4991.8  354.12
    4997  353.89  4999.8  353.39    5003  353.89  5014.6  357.24  5035.4  359.34
  5099.9  362.53    5314  364.63  5500.8  370.13  5512.4  371.96  5523.1  371.42
  5530.6  369.25  5560.3   371.4  5566.1  368.73  5576.8  372.02  5609.1  370.12
  5619.8  372.61  5630.6  372.86  5638.8   375.4  5662.8  375.02  5701.1   378.4
#Mann= 4 ,-1 , 0
    4272     .05       0  4813.5     .16       0    4997     .07       0
    5003     .16       0
Bank Sta=4997,5003
XS Rating Curve= 0 ,0
Exp/Cntr=0.3,0.1

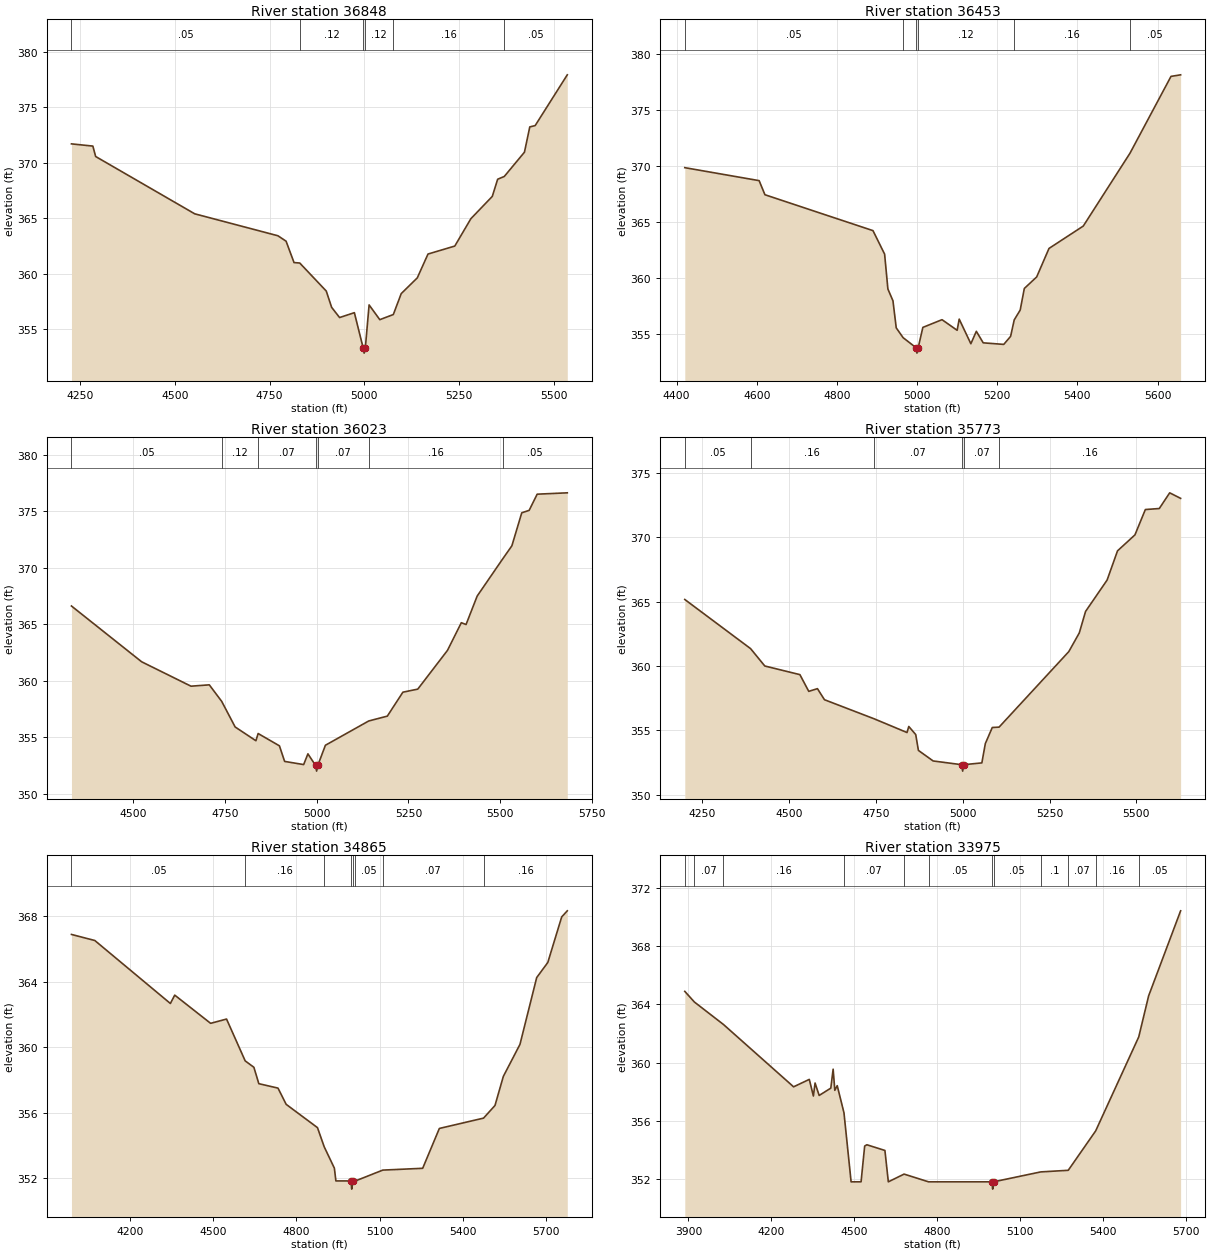
Type RM Length L Ch R = 1 ,36848   ,395,395,395
BEGIN DESCRIPTION:
SLOAN CREEK 59.0
END DESCRIPTION:
XS GIS Cut Line= 3
      3537749.59     10666910.21      3538299.61     10666410.19
      3538699.59      10666010.2
#Sta/Elev= 30
  4227.1  371.71  4283.6  371.51    4291  370.57  4552.5   365.4  4772.1  363.42
  4793.7  362.93  4814.7     361  4829.8  360.96  4899.8  358.43    4914  356.96
    4935  356.04    4974  356.48    4997  353.33  4999.8  352.83    5003  353.33
  5012.9  357.18  5041.1  355.85  5076.8  356.31  5097.7   358.2  5140.1  359.62
  5168.4  361.77  5239.1  362.49  5281.6  364.96  5338.1  366.97  5352.3  368.52
  5369.8  368.77    5423  370.96  5437.1  373.24  5451.3  373.36  5536.1  377.94
#Mann= 6 ,-1 , 0
  4227.1     .05       0  4829.8     .12       0    4997     .07       0
    5003     .12       0  5076.8     .16       0  5369.8     .05       0
Bank Sta=4997,5003
XS Rating Curve= 0 ,0
Exp/Cntr=0.3,0.1

Type RM Length L Ch R = 1 ,36453   ,430,430,430
BEGIN DESCRIPTION:
SLOAN CREEK 58.0
END DESCRIPTION:
XS GIS Cut Line= 3
      3538249.61     10667110.19      3538599.61     10666660.19
      3538749.61     10666010.17
#Sta/Elev= 30
  4420.5  369.87    4606  368.71  4620.5  367.45  4890.1  364.24  4919.1  362.14
  4927.3  359.02  4939.9  357.97  4948.1  355.55  4965.3  354.67    4997  353.79
  4999.8  353.29    5003  353.79  5014.5  355.59  5062.4  356.28  5100.1  355.33
  5105.2  356.33  5134.3  354.13    5148  355.24  5165.1  354.21  5216.4  354.07
  5233.5  354.79  5242.5  356.26  5257.4  357.14  5267.7  359.07  5298.5   360.1
  5329.3  362.65  5414.8  364.65  5531.3  371.16  5633.7  378.03  5657.7  378.17
#Mann= 6 ,-1 , 0
  4420.5     .05       0  4965.3     .12       0    4997     .07       0
    5003     .12       0  5242.5     .16       0  5531.3     .05       0
Bank Sta=4997,5003
XS Rating Curve= 0 ,0
Exp/Cntr=0.3,0.1

Type RM Length L Ch R = 1 ,36023   ,250,250,250
BEGIN DESCRIPTION:
SLOAN CREEK 57.0
END DESCRIPTION:
XS GIS Cut Line= 4
      3538524.24      10667135.1      3538949.58     10666679.37
      3538992.99     10666570.86      3538901.84     10665967.56
#Sta/Elev= 30
  4332.1  366.63  4523.3  361.69  4657.7  359.53  4707.5  359.65  4741.4  358.18
  4777.9  355.92  4834.5   354.7  4840.5  355.34  4898.5  354.25  4912.7  352.87
  4964.5  352.59  4976.1  353.54    4997  352.51  4999.8  352.01    5003  352.51
  5023.7   354.3  5141.7  356.45  5192.4  356.88  5234.8     359  5275.3  359.27
  5356.2   362.7  5393.9  365.15  5406.8  364.99  5437.1  367.51  5506.6   370.8
  5531.6  371.96  5558.5  374.88  5578.7   375.1  5600.5  376.53  5682.5  376.65
#Mann= 7 ,-1 , 0
  4332.1     .05       0  4741.4     .12       0  4840.5     .07       0
    4997     .07       0    5003     .07       0  5141.7     .16       0
  5506.6     .05       0
Bank Sta=4997,5003
XS Rating Curve= 0 ,0
Exp/Cntr=0.3,0.1

Type RM Length L Ch R = 1 ,35773   ,908,908,908
BEGIN DESCRIPTION:
SLOAN CREEK 56.0
END DESCRIPTION:
XS GIS Cut Line= 3
       3539275.1     10667378.16      3539179.62     10666709.75
      3539140.55     10665958.86
#Sta/Elev= 30
  4200.1  365.18  4389.5  361.36  4430.4  360.01  4531.4  359.34  4556.9  358.04
  4581.9  358.25  4602.1  357.39  4744.8  355.91  4839.7  354.84  4844.8  355.31
  4864.8  354.68  4872.5  353.45  4914.9  352.63    4997  352.34  4999.8  351.84
    5003  352.34  5055.1  352.48  5065.1  353.98  5085.1  355.23  5104.7  355.26
  5305.4  361.13  5335.5  362.58  5353.6  364.25  5415.6  366.69  5445.6  368.96
  5495.7   370.2  5525.7  372.17  5565.8  372.25  5595.8  373.47  5627.2  373.04
#Mann= 6 ,-1 , 0
  4200.1     .05       0  4389.5     .16       0  4744.8     .07       0
    4997     .07       0    5003     .07       0  5104.7     .16       0
Bank Sta=4997,5003
XS Rating Curve= 0 ,0
Exp/Cntr=0.3,0.1

Type RM Length L Ch R = 1 ,34865   ,890,890,890
BEGIN DESCRIPTION:
SLOAN CREEK 55.0
END DESCRIPTION:
XS GIS Cut Line= 3
       3539549.6     10667610.21      3539949.61     10666710.19
      3539899.61     10665910.16
#Sta/Elev= 30
    3990  366.87  4074.2   366.5  4346.4  362.66  4362.1  363.17  4491.4  361.45
  4548.8  361.71    4616  359.16  4647.3  358.77  4665.1  357.77  4734.2   357.5
  4763.6  356.51  4876.4  355.09  4900.7  353.92  4937.3  352.62  4942.8  351.84
    4997  351.84  4999.8  351.34    5003  351.84  5013.2  351.84  5111.7   352.5
  5255.5  352.61  5315.6  355.04  5474.8  355.67    5516  356.44    5546  358.21
  5606.1  360.17  5666.3  364.24  5706.3  365.16  5756.4  367.94  5776.5  368.31
#Mann= 8 ,-1 , 0
    3990     .05       0    4616     .16       0  4900.7     .07       0
    4997     .07       0    5003     .07       0  5013.2     .05       0
  5111.7     .07       0  5474.8     .16       0
Bank Sta=4997,5003
XS Rating Curve= 0 ,0
Exp/Cntr=0.3,0.1

Type RM Length L Ch R = 1 ,33975   ,276,276,276
BEGIN DESCRIPTION:
Mapping XS 27e49034
END DESCRIPTION:
XS GIS Cut Line= 3
      3540134.46     10667321.76      3540672.67     10666557.84
      3540559.83     10665707.18
#Sta/Elev= 30
  3886.7  364.89  3921.5  364.16  4026.6  362.62  4280.1  358.35  4336.8  358.86
  4351.6  357.72  4357.7  358.61  4372.5  357.76  4414.6  358.26    4423  359.56
  4429.1  358.11  4437.8  358.43  4462.2  356.57    4488  351.84    4524  351.84
    4537  354.29  4544.9  354.38  4610.2  353.99  4622.6  351.84  4679.5  352.37
    4768  351.84    4997  351.84  4999.8  351.34    5003  351.84  5173.6  352.52
    5273  352.63  5372.2  355.33  5527.9  361.77  5563.6  364.58  5679.3  370.41
#Mann= 12 ,-1 , 0
  3886.7     .05       0  3921.5     .07       0  4026.6     .16       0
  4462.2     .07       0  4679.5      .1       0    4768     .05       0
    4997    .033       0    5003     .05       0  5173.6      .1       0
    5273     .07       0  5372.2     .16       0  5527.9     .05       0
Bank Sta=4997,5003
XS Rating Curve= 0 ,0
Exp/Cntr=0.3,0.1

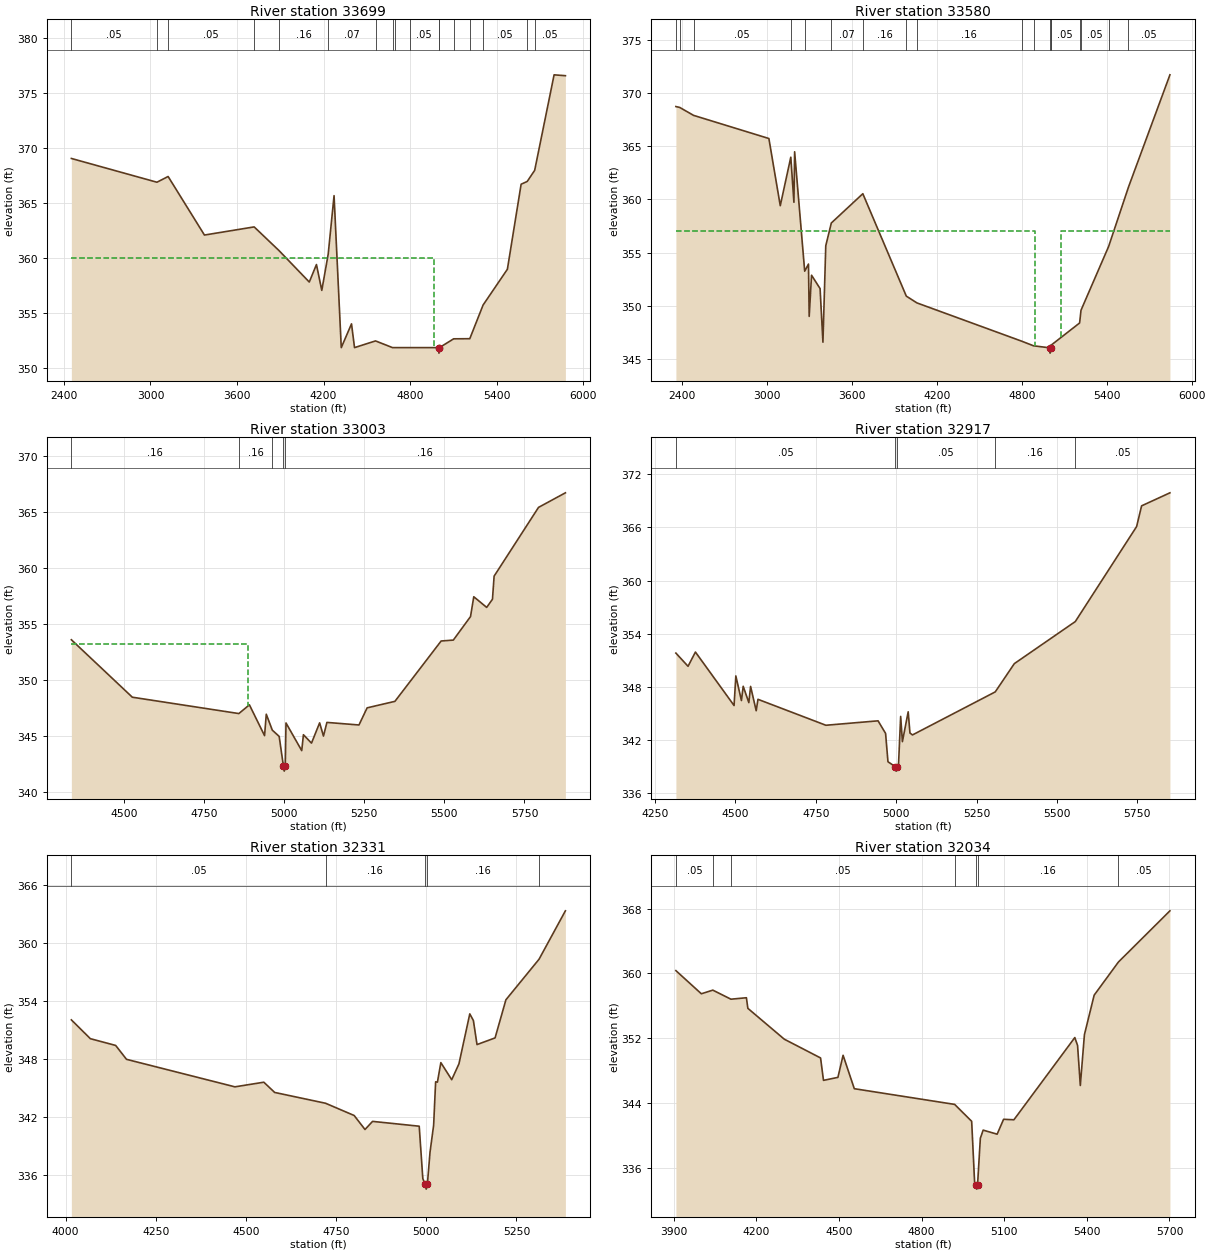
Type RM Length L Ch R = 1 ,33699   ,119,119,119
BEGIN DESCRIPTION:
SLOAN CREEK 54.0
END DESCRIPTION:
XS GIS Cut Line= 4
      3539418.07     10668364.95      3540560.46      10666911.3
      3540852.43     10666512.85      3541191.48     10665485.87
#Sta/Elev= 30
  2451.9  369.03    3045  366.87  3122.6  367.39  3374.4  362.07    3719  362.81
  3890.3  360.67    4101   357.8  4150.7  359.39  4187.7  357.04  4232.1  360.33
  4272.7  365.65  4322.7  351.84  4393.7     354  4414.6  351.84    4560  352.45
  4678.1  351.84  4692.5  351.84  4796.1  351.84    4997  351.84  4999.8  351.34
    5003  351.84  5101.8  352.64  5213.5  352.65  5305.7  355.71  5474.1  358.96
  5569.4  366.69  5611.5  366.94  5663.3  367.95  5797.9  376.63  5876.2  376.55
#Mann= 17 ,-1 , 0
  2451.9     .05       0    3045     .08       0  3122.6     .05       0
    3719     .07       0  3890.3     .16       0  4232.1     .07       0
    4560     .05       0  4678.1      .1       0  4692.5     .07       0
  4796.1     .05       0    4997     .07       0    5003     .05       0
  5101.8     .07       0  5213.5     .16       0  5305.7     .05       0
  5611.5     .08       0  5663.3     .05       0
#XS Ineff= 2 , 0
       0 4968.18     360               0
Permanent Ineff=
       F       F
Bank Sta=4997,5003
XS Rating Curve= 0 ,0
Exp/Cntr=0.3,0.1

Type RM Length L Ch R = 1 ,33580   ,577,577,577
BEGIN DESCRIPTION:
SLOAN CREEK 53.0
END DESCRIPTION:
XS GIS Cut Line= 4
      3540415.46     10668874.17      3540524.85     10667725.84
      3540933.69     10666613.74      3541316.49     10665527.51
#Sta/Elev= 30
  2356.4  368.75    2383  368.67  2481.2  367.92  3013.3  365.74  3093.7  359.41
  3168.1  363.98  3190.1  359.73  3195.1  364.49  3266.2  353.24    3293  353.91
    3298  348.98  3314.7  352.86    3375   351.6  3395.1  346.55  3415.2  355.64
  3454.4  357.78    3677  360.54  3984.1  350.89  4059.4  350.25  4798.3  346.65
    4883  346.21    4997  346.02  4999.8  345.52    5003  346.02  5003.4  346.23
  5208.5  348.36  5218.3  349.56  5413.5  355.57  5553.6  361.16  5846.5  371.74
#Mann= 18 ,-1 , 0
  2356.4     .15       0    2383     .08       0  2481.2     .05       0
  3168.1     .08       0  3266.2     .16       0  3454.4     .07       0
    3677     .16       0  3984.1     .07       0  4059.4     .16       0
  4798.3     .16       0    4883     .16       0    4997     .07       0
    5003     .16       0  5003.4     .05       0  5208.5     .16       0
  5218.3     .05       0  5413.5     .08       0  5553.6     .05       0
#XS Ineff= 2 , 0
       0 4894.89     357 5079.55       0     357
Permanent Ineff=
       F       F
Bank Sta=4997,5003
XS Rating Curve= 0 ,0
Exp/Cntr=0.3,0.1

Type RM Length L Ch R = 1 ,33003   ,86,86,86
BEGIN DESCRIPTION:
SLOAN CREEK 52.0
END DESCRIPTION:
XS GIS Cut Line= 6
      3541205.07     10666902.55      3541404.73     10666524.93
      3541478.52     10666351.32      3541626.09     10665943.33
      3541660.81     10665769.72      3541708.55     10665457.25
#Sta/Elev= 30
    4335  353.57  4525.4  348.44    4858  346.98    4891  347.76  4938.3  345.01
  4943.7  346.92  4962.5   345.5    4984  344.94    4997  342.34  4999.8  341.84
    5003  342.34  5005.3  346.14  5054.4  343.67  5059.7  345.09  5084.9  344.34
  5110.3  346.15  5122.3  344.97    5133  346.19  5233.2  345.96  5258.6  347.49
  5345.4  348.07  5489.8  353.46  5527.8  353.54  5581.5  355.64  5591.7  357.41
    5632  356.46  5650.1  357.19  5655.2  359.25  5793.9  365.39  5877.8  366.69
#Mann= 5 ,-1 , 0
    4335     .16       0    4858     .16       0  4962.5     .05       0
    4997     .04       0    5003     .16       0
#XS Ineff= 2 , 0
         4885.23  353.22
Permanent Ineff=
       F       F
Bank Sta=4997,5003
XS Rating Curve= 0 ,0
Exp/Cntr=0.3,0.1

Type RM Length L Ch R = 1 ,32917   ,586,586,586
BEGIN DESCRIPTION:
SLOAN CREEK 51.0
END DESCRIPTION:
XS GIS Cut Line= 6
      3541287.54     10666906.89      3541474.18     10666503.23
       3541552.3     10666346.98      3541626.09     10666177.71
      3541708.55     10665895.59      3541782.03     10665463.38
#Sta/Elev= 30
  4314.7  351.81  4352.5  350.32  4375.4  351.93  4495.6  345.89  4501.1  349.23
  4518.5  346.45    4524  348.06  4541.5  346.22    4547  348.05  4564.4   345.3
  4569.9  346.59  4781.2  343.66  4943.4  344.16  4966.8  342.74  4974.2  339.54
    4997  338.98  4999.8  338.48    5003  338.98    5007   339.2  5013.7  344.66
  5019.1  341.81  5037.1  345.18  5042.6  342.78  5050.6  342.57  5307.9  347.43
  5367.2  350.62  5556.8  355.37  5747.5   366.1    5763  368.44  5851.1  369.91
#Mann= 5 ,-1 , 0
  4314.7     .05       0    4997     .04       0    5003     .05       0
  5307.9     .16       0  5556.8     .05       0
Bank Sta=4997,5003
XS Rating Curve= 0 ,0
Exp/Cntr=0.3,0.1

Type RM Length L Ch R = 1 ,32331   ,297,297,297
BEGIN DESCRIPTION:
SLOAN CREEK 50.0
END DESCRIPTION:
XS GIS Cut Line= 2
      3542010.93     10666992.84      3541934.58     10665625.57
#Sta/Elev= 30
  4016.2  352.07  4068.9  350.12    4139  349.42  4169.1  347.98  4469.6  345.13
  4549.7  345.61  4579.7  344.55  4720.7  343.43  4800.1  342.16  4830.1  340.71
  4851.1  341.55  4980.4  341.05  4990.4  335.62    4997  335.03  4999.8  334.53
    5003  335.03  5010.4  338.37  5020.4  341.16  5025.9  345.65  5030.9  345.62
  5040.4  347.64  5070.5  345.87  5090.5  347.51  5120.6  352.69  5130.6     352
  5140.6  349.51  5190.7   350.2  5220.7  354.15  5312.5  358.35  5385.6  363.37
#Mann= 5 ,-1 , 0
  4016.2     .05       0  4720.7     .16       0    4997     .07       0
    5003     .16       0  5312.5     .05       0
Bank Sta=4997,5003
XS Rating Curve= 0 ,0
Exp/Cntr=0.3,0.1

Type RM Length L Ch R = 1 ,32034   ,448,448,448
BEGIN DESCRIPTION:
SLOAN CREEK 49.0
END DESCRIPTION:
XS GIS Cut Line= 3
      3542311.26     10667277.13      3542089.04     10666079.23
       3542144.6     10665506.36
#Sta/Elev= 30
  3907.7  360.34  4000.1  357.48  4041.7  357.93  4107.7  356.81  4163.7  356.99
    4169  355.68  4301.2  351.87    4433  349.55  4443.6  346.78    4496  347.15
  4514.8  349.88  4555.5  345.75  4919.9  343.81  4981.7  341.72  4992.8  333.84
    4997  333.84  4999.8  333.34    5003  333.84  5013.2  339.63  5023.4  340.63
  5074.2  340.13  5097.6  341.97  5135.1  341.91  5356.2  352.07  5366.2   351.1
  5376.2  346.15  5391.1  352.43  5426.5  357.31  5514.5   361.4  5701.6  367.73
#Mann= 7 ,-1 , 0
  3907.7     .05       0  4041.7     .08       0  4107.7     .05       0
  4919.9     .16       0    4997     .07       0    5003     .16       0
  5514.5     .05       0
Bank Sta=4997,5003
XS Rating Curve= 0 ,0
Exp/Cntr=0.3,0.1

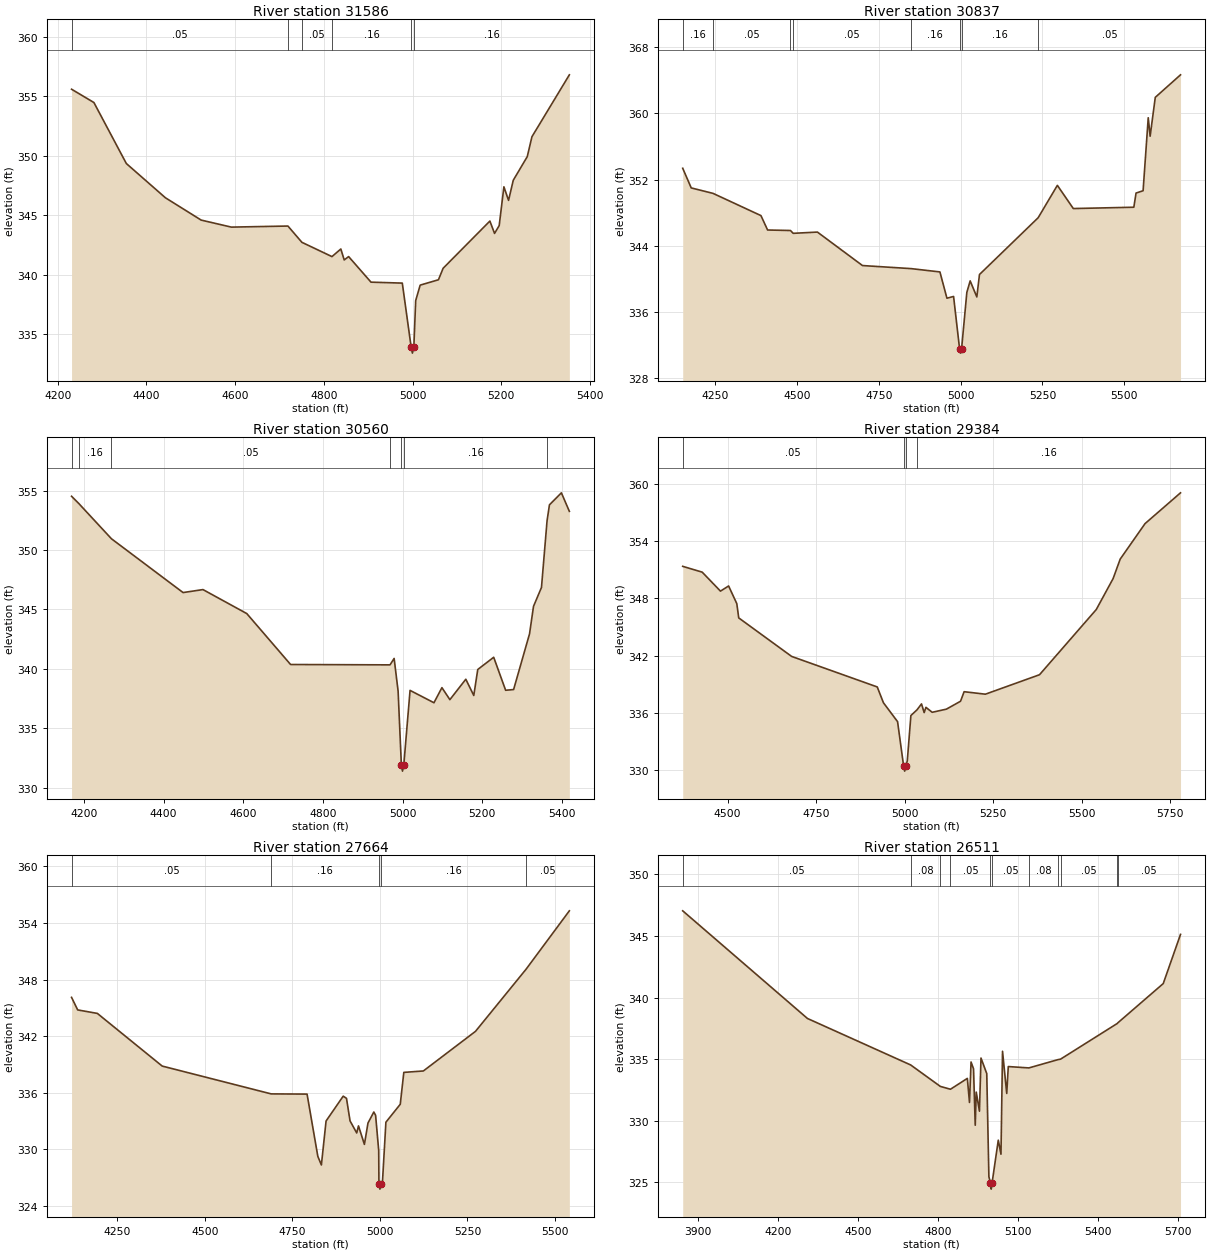
Type RM Length L Ch R = 1 ,31586   ,749,749,749
BEGIN DESCRIPTION:
SLOAN CREEK 48.0
END DESCRIPTION:
XS GIS Cut Line= 3
      3542449.61     10666860.19      3542349.61     10666060.19
       3542249.6     10665760.15
#Sta/Elev= 30
  4231.2  355.59  4281.6  354.47  4354.7  349.34  4442.8  346.46  4523.5  344.58
  4591.5  343.99  4719.1  344.08  4750.6  342.71  4818.4  341.51  4838.4  342.15
    4846  341.23    4856  341.51  4906.4  339.36    4977  339.28    4997  333.89
  4999.8  333.39    5003  333.89  5007.2  337.81  5017.3  339.11  5058.5  339.56
  5069.1  340.53  5174.5   344.5    5185  343.46  5195.5  344.12  5206.1  347.38
  5216.6  346.24  5227.2  347.93  5258.8  349.92  5269.3  351.59  5353.7   356.8
#Mann= 6 ,-1 , 0
  4231.2     .05       0  4719.1     .16       0  4750.6     .05       0
  4818.4     .16       0    4997     .07       0    5003     .16       0
Bank Sta=4997,5003
XS Rating Curve= 0 ,0
Exp/Cntr=0.3,0.1

Type RM Length L Ch R = 1 ,30837   ,277,277,277
BEGIN DESCRIPTION:
SLOAN CREEK 47.0
END DESCRIPTION:
XS GIS Cut Line= 3
      3542916.29     10666785.78      3542760.05     10665862.21
      3542256.57     10665567.07
#Sta/Elev= 30
  4151.4  353.37  4177.4     351    4244  350.34  4390.3  347.66  4410.6  345.92
  4480.5  345.86  4488.8  345.52  4562.8  345.67  4700.4  341.63  4848.9  341.26
  4936.9  340.86  4958.3  337.69  4978.6   337.9    4997  331.56  4999.8  331.06
    5003  331.56  5019.1  338.39  5029.3  339.78  5049.6  337.84  5057.7  340.55
  5236.9   347.4  5295.6  351.31  5344.3  348.51  5529.1  348.67  5535.9  350.38
  5557.4  350.66  5573.1  359.47  5578.9  357.24  5594.6  361.93  5671.7  364.65
#Mann= 8 ,-1 , 0
  4151.4     .16       0    4244     .05       0  4480.5     .16       0
  4488.8     .05       0  4848.9     .16       0    4997     .07       0
    5003     .16       0  5236.9     .05       0
Bank Sta=4997,5003
XS Rating Curve= 0 ,0
Exp/Cntr=0.3,0.1

Type RM Length L Ch R = 1 ,30560   ,1176,1176,1176
BEGIN DESCRIPTION:
SLOAN CREEK 46.0
END DESCRIPTION:
XS GIS Cut Line= 3
      3542999.61      10666810.2      3542999.61     10665910.19
      3542999.61      10665560.2
#Sta/Elev= 30
  4168.8  354.53  4186.7  353.93    4269  350.95  4448.8  346.42  4498.8  346.67
  4608.8  344.65  4718.8  340.36  4968.5  340.33  4978.8  340.87  4988.8  338.12
    4997  331.88  4999.8  331.38    5003  331.88  5018.8  338.18  5078.8  337.14
  5098.8  338.41  5118.8   337.4  5158.8  339.12  5178.8  337.75  5188.8  339.94
  5228.8  340.97  5258.8  338.19  5278.8  338.25  5318.8  342.94  5328.8  345.26
  5348.8  346.85  5362.8  352.47  5368.8  353.81  5398.8  354.82  5418.8  353.26
#Mann= 7 ,-1 , 0
  4168.8     .05       0  4186.7     .16       0    4269     .05       0
  4968.5     .16       0    4997     .07       0    5003     .16       0
  5362.8     .05       0
Bank Sta=4997,5003
XS Rating Curve= 0 ,0
Exp/Cntr=0.3,0.1

Type RM Length L Ch R = 1 ,29384   ,1720,1720,1720
BEGIN DESCRIPTION:
SLOAN CREEK 44.0
END DESCRIPTION:
XS GIS Cut Line= 3
       3543199.6     10666710.22      3543449.61     10666160.19
      3543499.61     10665360.23
#Sta/Elev= 30
  4373.1  351.36  4428.1  350.75  4479.7  348.76  4502.7   349.3  4525.8  347.45
  4531.3  345.95  4680.7  341.91  4922.4  338.71  4939.9  337.05  4979.8  335.07
    4997  330.38  4999.8  329.88    5003  330.38  5007.3  330.98  5017.4  335.71
  5034.7  336.31  5047.4  336.93  5054.9  336.02  5059.9  336.57  5077.5  336.05
  5117.6  336.38  5157.6  337.21  5167.7  338.21  5227.8  337.95  5380.6  339.99
  5540.9  346.83  5588.5  350.08  5608.5  352.12  5678.6  355.84  5778.8  359.07
#Mann= 4 ,-1 , 0
  4373.1     .05       0    4997    .035       0    5003     .05       0
  5034.7     .16       0
Bank Sta=4997,5003
XS Rating Curve= 0 ,0
Exp/Cntr=0.3,0.1

Type RM Length L Ch R = 1 ,27664   ,1153,1153,1153
BEGIN DESCRIPTION:
SLOAN CREEK 43.0
END DESCRIPTION:
XS GIS Cut Line= 2
       3543978.8     10666737.24      3544284.35     10665348.35
#Sta/Elev= 30
  4118.9  346.12  4136.4  344.79  4192.6  344.42  4377.8  338.84  4689.3  335.89
  4791.7  335.87  4822.4  329.28  4832.6  328.36    4846  333.02  4894.9  335.65
  4904.3  335.42  4914.5  333.03  4933.5  331.75  4938.6   332.5  4955.5  330.54
  4965.7   332.8  4982.4  333.97  4987.5  333.62  4996.4  329.88    4997   326.3
  4999.8   325.8    5003   326.3  5006.7   326.3  5016.9  332.89  5057.9  334.79
  5068.1  338.17  5123.9  338.32  5272.9  342.52  5417.3   349.1    5541  355.29
#Mann= 5 ,-1 , 0
  4118.9     .05       0  4689.3     .16       0    4997     .07       0
    5003     .16       0  5417.3     .05       0
Bank Sta=4997,5003
XS Rating Curve= 0 ,0
Exp/Cntr=0.3,0.1

Type RM Length L Ch R = 1 ,26511   ,72,72,72
BEGIN DESCRIPTION:
SLOAN CREEK 42.0
END DESCRIPTION:
XS GIS Cut Line= 3
      3544068.74     10667000.09      3544627.79     10666048.69
      3545004.87     10665385.72
#Sta/Elev= 30
  3843.3  347.03  4310.9   338.3  4697.9  334.53  4809.1  332.79    4847  332.56
  4910.3  333.44  4918.4  331.49  4924.2  334.77  4933.5  334.22  4939.9  329.64
  4943.7  332.33  4955.7  330.78  4961.5  335.09  4983.1  333.83  4991.1  325.47
    4997  324.96  4999.8  324.46    5003  324.96  5026.3  328.43  5036.4  327.29
  5042.2  335.64    5058  332.22  5063.8   334.4  5141.1  334.29  5251.4  334.97
  5259.7     335  5472.1  337.89  5474.7  337.95  5644.7  341.13  5709.5  345.12
#Mann= 11 ,-1 , 0
  3843.3     .05       0  4697.9     .08       0  4809.1     .16       0
    4847     .05       0    4997     .04       0    5003     .05       0
  5141.1     .08       0  5251.4     .16       0  5259.7     .05       0
  5472.1     .16       0  5474.7     .05       0
Bank Sta=4997,5003
XS Rating Curve= 0 ,0
Exp/Cntr=0.3,0.1