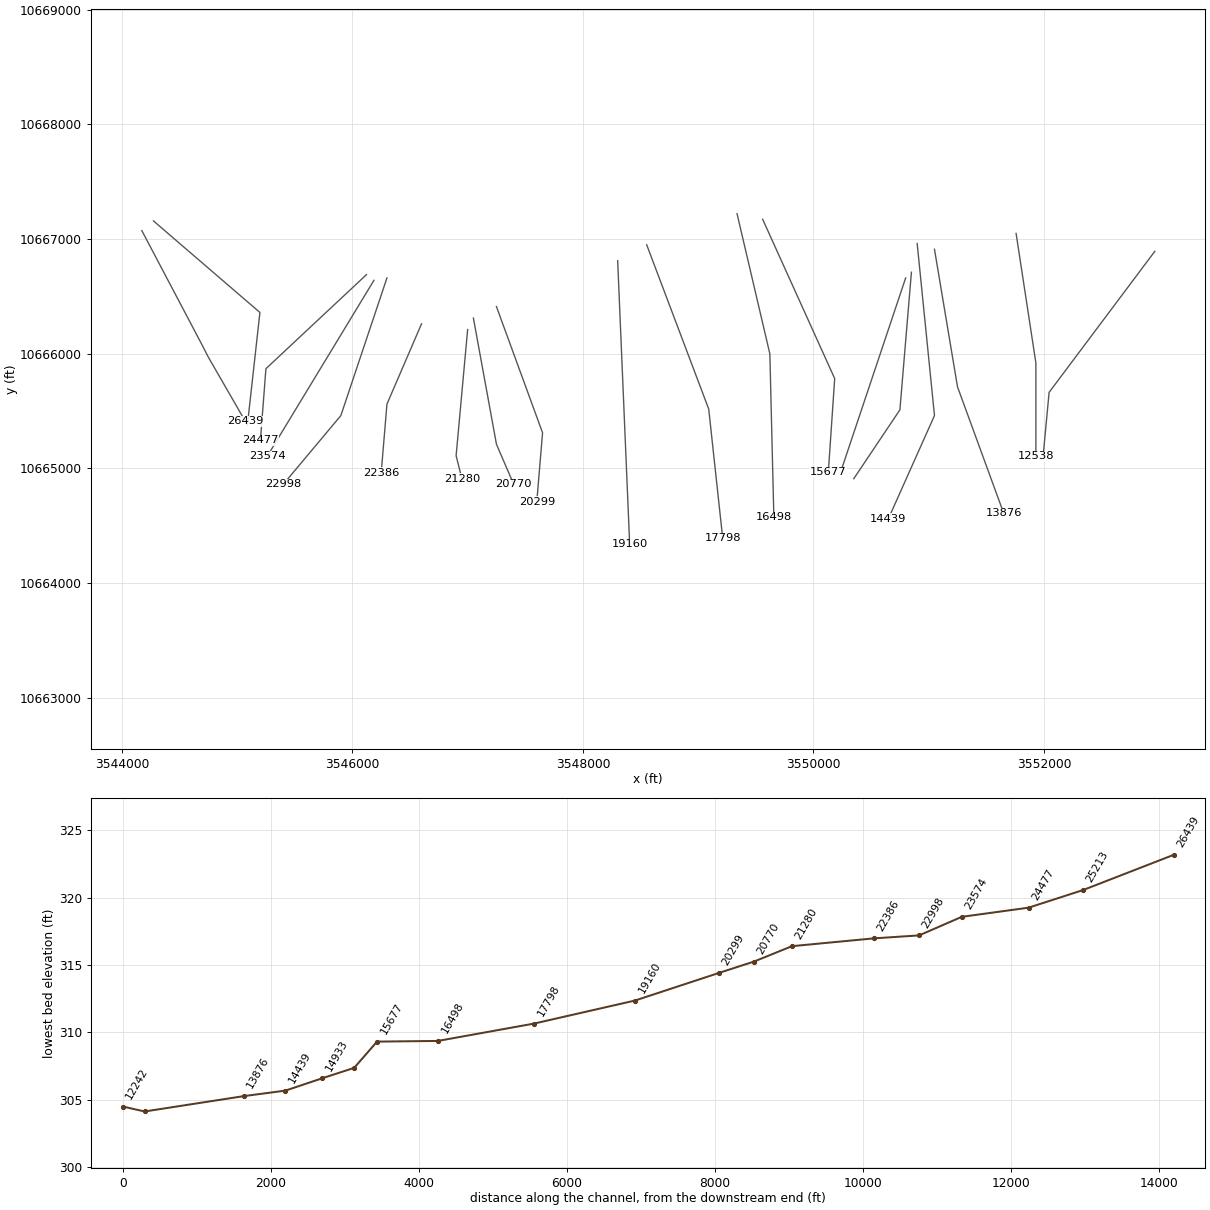
HEC-RAS study SLOAN CREEK.prj: SLOAN CREEK Base Level Engineering

--- SLOAN CREEK.g01 (geometry) --- (continued)

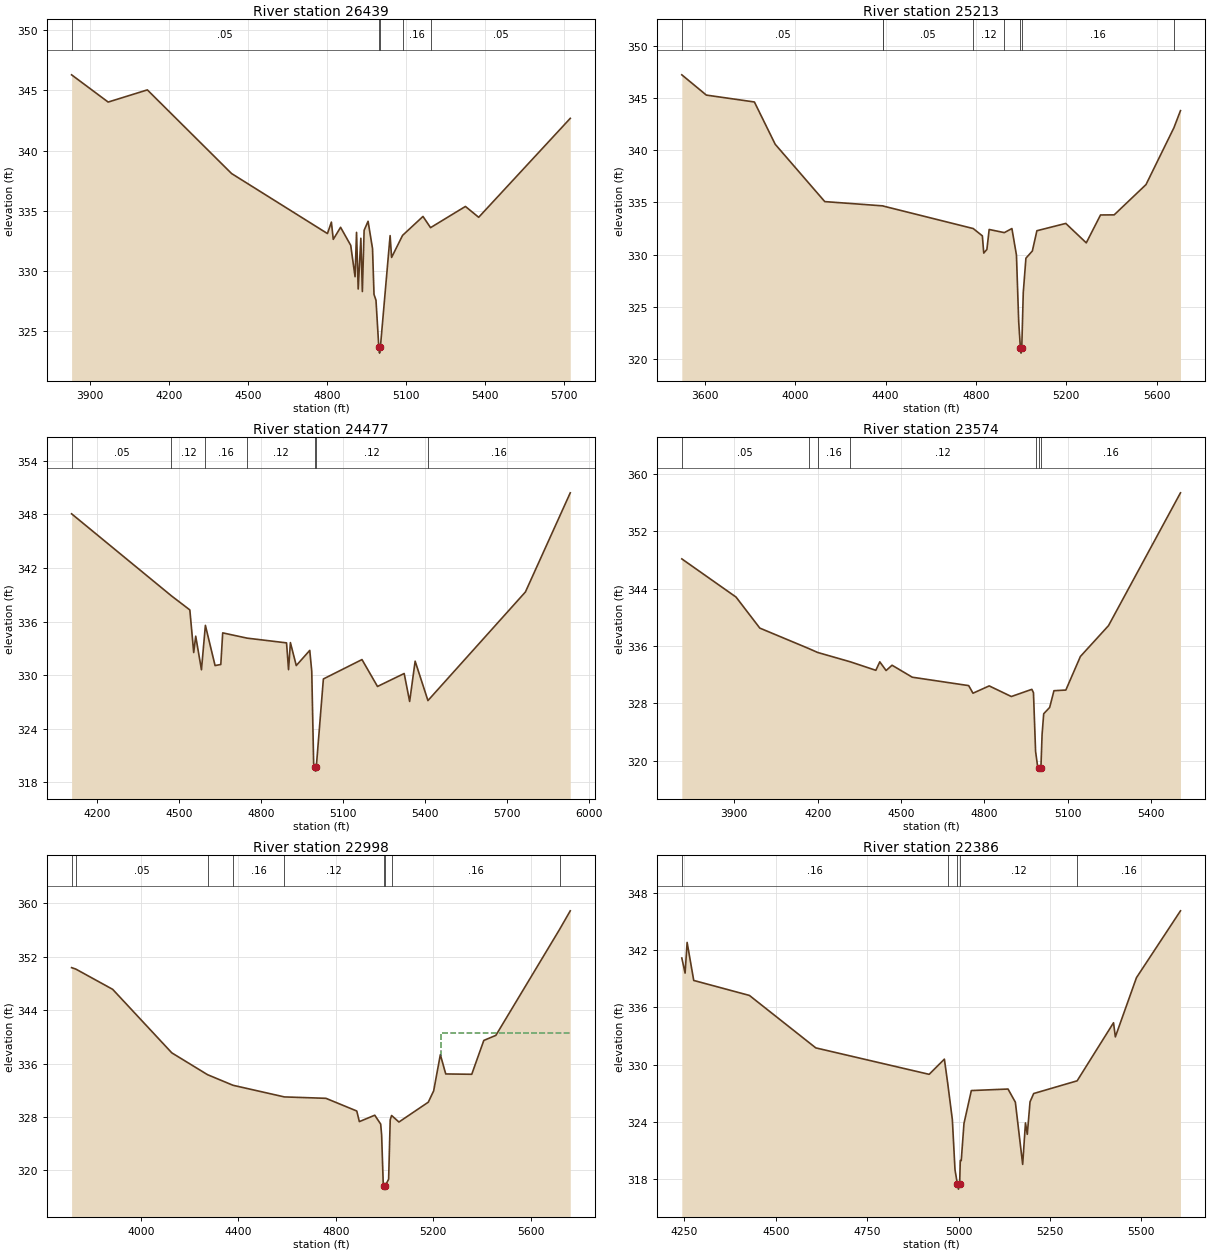
Type RM Length L Ch R = 1 ,26439   ,1226,1226,1226
BEGIN DESCRIPTION:
SLOAN CREEK 41.0
END DESCRIPTION:
XS GIS Cut Line= 4
      3544172.91       10667073.      3544695.85     10666075.76
      3544750.46     10665968.72      3545071.65     10665408.81
#Sta/Elev= 30
  3831.6  346.28  3970.3  344.02    4119  345.03  4438.5  338.09  4802.2  333.11
  4817.1  334.06  4824.3  332.63    4852  333.63  4890.5  332.13  4906.9  329.53
  4912.5  333.21  4918.8  328.51  4928.9  332.72  4934.6   328.3  4941.3  333.38
  4956.3  334.13  4973.2  331.86  4978.8  328.06  4986.3  327.58    4997  323.69
  4999.8  323.19    5003  323.69  5039.9  332.94  5045.5  331.13  5087.2  332.96
  5164.6  334.53  5193.3   333.6  5325.6  335.36  5375.9  334.46  5723.3  342.67
#Mann= 5 ,-1 , 0
  3831.6     .05       0    4997     .04       0    5003     .05       0
  5087.2     .16       0  5193.3     .05       0
Bank Sta=4997,5003
XS Rating Curve= 0 ,0
Exp/Cntr=0.3,0.1

Type RM Length L Ch R = 1 ,25213   ,736,736,736
BEGIN DESCRIPTION:
SLOAN CREEK 40.0
END DESCRIPTION:
XS GIS Cut Line= 3
      3544273.97     10667157.34      3545197.51     10666359.35
        3545089.     10665378.47
#Sta/Elev= 30
  3498.2  347.22  3606.7  345.28  3819.5  344.62  3911.6  340.57    4131  335.08
  4388.9  334.67  4390.2  334.65  4788.1   332.5  4828.6   331.8  4834.8  330.15
  4848.7   330.5  4858.7  332.41  4925.8  332.11  4959.4   332.5  4979.5  329.96
  4989.5  323.56    4997  321.07  4999.8  320.57    5003  321.07  5009.7  326.37
  5021.4  329.66  5049.9  330.35    5070  332.29  5197.8  332.99  5288.6  331.13
  5351.7   333.8  5412.1  333.81    5553  336.71  5676.7  342.16  5705.6  343.79
#Mann= 8 ,-1 , 0
  3498.2     .05       0  4388.9     .12       0  4390.2     .05       0
  4788.1     .12       0  4925.8     .16       0    4997     .07       0
    5003     .16       0  5676.7     .05       0
Bank Sta=4997,5003
XS Rating Curve= 0 ,0
Exp/Cntr=0.3,0.1

Type RM Length L Ch R = 1 ,24477   ,903,903,903
BEGIN DESCRIPTION:
SLOAN CREEK 39.0
END DESCRIPTION:
XS GIS Cut Line= 3
        3546122.     10666689.22      3545249.59      10665868.9
       3545201.9     10665244.52
#Sta/Elev= 30
    4108  348.07  4472.9  338.89  4540.4  337.31  4554.6  332.54  4561.9  334.37
  4582.9  330.61  4597.3  335.58  4632.7  331.08  4653.7   331.2  4660.6  334.74
  4749.9  334.15  4894.1  333.62  4901.4  330.62  4908.2  333.65  4929.7  331.08
    4979  332.78  4986.3  330.44  4993.2   320.1    4997  319.76  4999.8  319.26
    5003  319.76  5028.8  329.58    5170  331.75  5226.7  328.74  5324.3  330.19
  5344.3  327.06  5364.4  331.57  5411.2  327.16  5767.7  339.32  5931.7  350.42
#Mann= 7 ,-1 , 0
    4108     .05       0  4472.9     .12       0  4597.3     .16       0
  4749.9     .12       0    4997     .07       0    5003     .12       0
  5411.2     .16       0
Bank Sta=4997,5003
XS Rating Curve= 0 ,0
Exp/Cntr=0.3,0.1

Type RM Length L Ch R = 1 ,23574   ,576,576,576
BEGIN DESCRIPTION:
SLOAN CREEK 38.0
END DESCRIPTION:
XS GIS Cut Line= 2
       3546186.9     10666639.78      3545260.38     10665104.25
#Sta/Elev= 30
  3711.5  348.14  3906.6  342.82    3992   338.5  4167.6  335.66  4199.8  335.11
  4317.1  333.81  4409.3  332.62  4423.5   333.8  4446.2  332.59  4467.6  333.33
  4540.3  331.66  4743.2  330.49  4758.7  329.43    4817  330.45  4896.6  328.97
  4970.3  329.97  4976.2   329.5  4983.8  321.32  4991.7  319.08    4997  319.08
  4999.8  318.58    5003  319.08  5007.2   323.7    5013  326.57  5034.4  327.45
  5049.9  329.78  5092.6  329.87    5145  334.55    5246  338.84  5504.9  357.34
#Mann= 7 ,-1 , 0
  3711.5     .05       0  4167.6     .12       0  4199.8     .16       0
  4317.1     .12       0  4983.8     .16       0    4997     .07       0
    5003     .16       0
Bank Sta=4997,5003
XS Rating Curve= 0 ,0
Exp/Cntr=0.3,0.1

Type RM Length L Ch R = 1 ,22998   ,612,612,612
BEGIN DESCRIPTION:
SLOAN CREEK 37.0
END DESCRIPTION:
XS GIS Cut Line= 3
       3546299.6     10666660.17      3545899.61     10665460.19
      3545399.62      10664860.2
#Sta/Elev= 30
  3716.1  350.37  3733.2  350.16  3884.7  347.12  4127.2  337.61  4273.8  334.34
  4378.6  332.75    4589  331.01  4759.6   330.8  4886.1   328.9  4896.7  327.31
  4959.9  328.27  4984.2  326.94  4988.1   325.3  4994.7  317.96    4997   317.7
  4999.8   317.2    5003   317.7  5016.8  318.69  5023.3  327.58  5028.9  328.23
  5059.1  327.25  5179.5  330.22  5201.6  331.92    5229  337.34  5251.1  334.45
  5357.8   334.4  5407.3  339.47  5456.8  340.23  5717.9  356.08    5762  358.88
#Mann= 9 ,-1 , 0
  3716.1     .16       0  3733.2     .05       0  4273.8     .12       0
  4378.6     .16       0    4589     .12       0    4997     .07       0
    5003     .12       0  5028.9     .16       0  5717.9     .05       0
#XS Ineff= 2 , 0
                         5230.11          340.54
Permanent Ineff=
       F       F
Bank Sta=4997,5003
XS Rating Curve= 0 ,0
Exp/Cntr=0.3,0.1

Type RM Length L Ch R = 1 ,22386   ,1106,1106,1106
BEGIN DESCRIPTION:
SLOAN CREEK 36.0
END DESCRIPTION:
XS GIS Cut Line= 3
       3546599.6     10666260.16      3546299.61     10665560.19
      3546249.61     10664960.22
#Sta/Elev= 30
  4243.3  341.18  4252.3   339.6  4257.8  342.81  4275.9  338.83  4428.2  337.26
  4609.6  331.77  4919.6     329  4961.3  330.59  4970.2  328.12  4983.1  324.25
  4990.3  319.02    4997  317.48  4999.8  316.98    5003  317.48  5004.8  319.97
  5007.4  319.97  5014.9  323.86    5035   327.3  5135.3  327.46  5155.4  326.08
  5175.4  319.57    5183  323.91    5188  322.72  5195.5  326.12  5205.5  326.99
  5324.3  328.32  5423.8   334.4  5428.8  332.92  5486.5  339.12  5606.9  346.12
#Mann= 5 ,-1 , 0
  4243.3     .16       0  4970.2     .12       0    4997     .07       0
    5003     .12       0  5324.3     .16       0
#XS Ineff= 1 ,-1
 5138.18 5212.73  326.91
Permanent Ineff=
       F
Bank Sta=4997,5003
XS Rating Curve= 0 ,0
Exp/Cntr=0.3,0.1

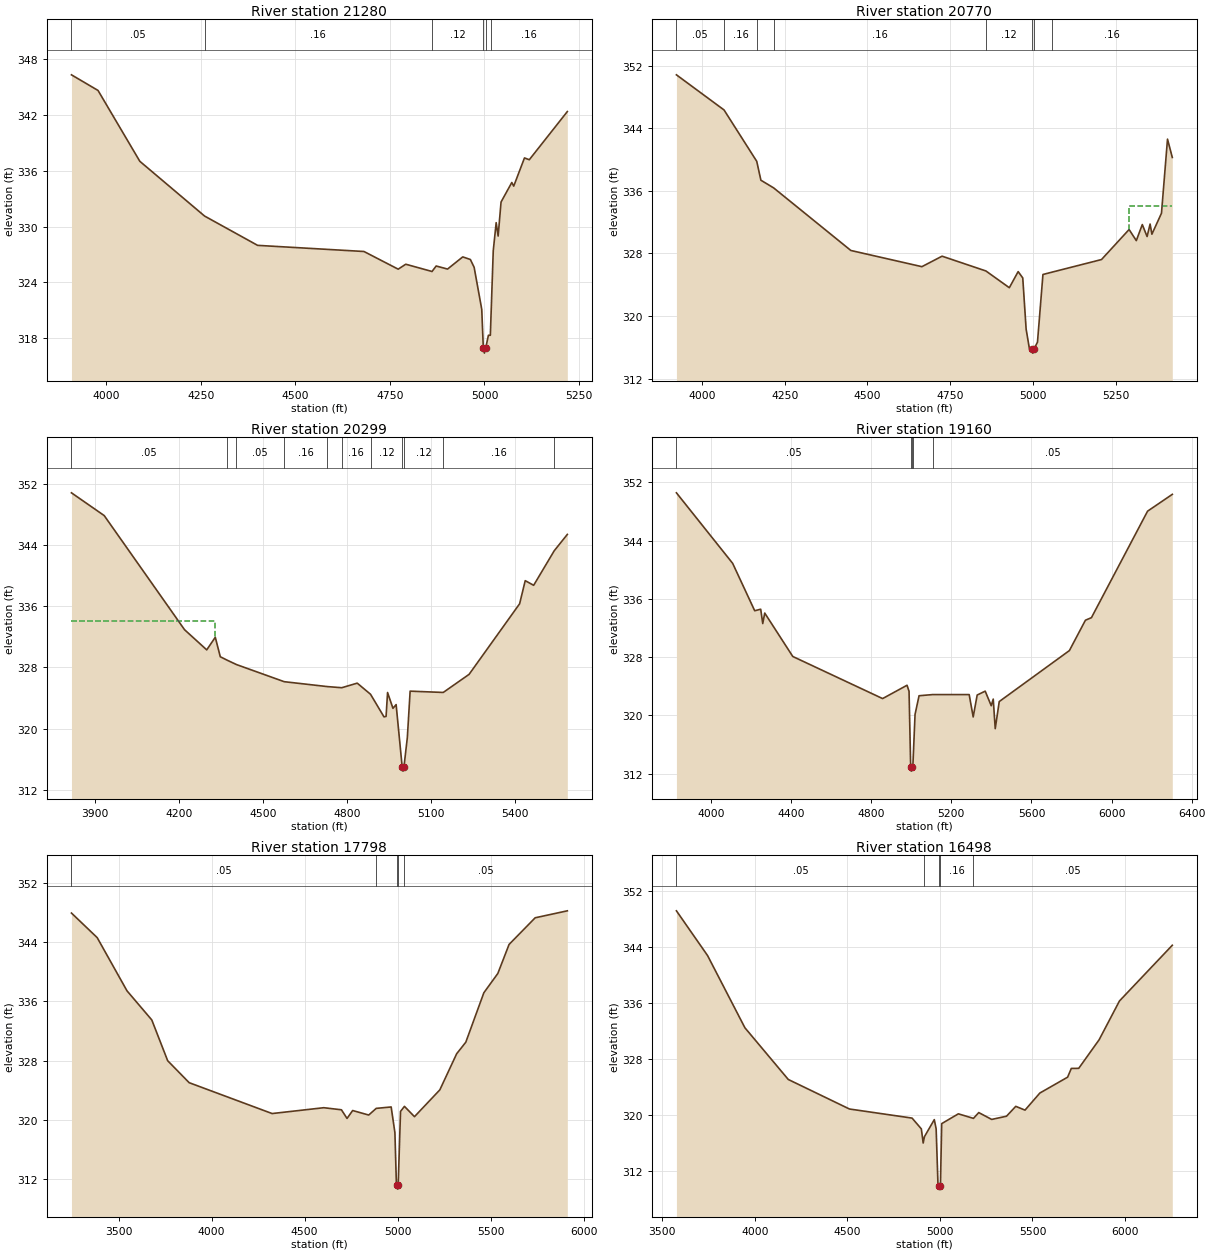
Type RM Length L Ch R = 1 ,21280   ,510,510,510
BEGIN DESCRIPTION:
SLOAN CREEK 34.0
END DESCRIPTION:
XS GIS Cut Line= 3
      3546999.61     10666210.15      3546899.61     10665110.19
       3546949.6     10664910.24
#Sta/Elev= 30
  3908.4  346.33  3978.6  344.65  4089.1  337.03  4260.3  331.14  4400.4  327.99
  4681.5  327.33  4771.9  325.43    4792  325.96  4861.4  325.18  4872.3  325.77
  4902.4  325.44  4942.6  326.75  4962.7  326.47  4972.7  325.63  4992.8  321.11
    4997   316.9  4999.8   316.4    5003   316.9  5010.4  318.32  5015.5  318.32
  5016.9  319.97  5023.2  327.41  5030.9  330.43  5036.1  328.99  5043.8  332.65
  5072.2  334.75  5077.3  334.36  5105.7  337.39  5118.5   337.2    5219  342.38
#Mann= 6 ,-1 , 0
  3908.4     .05       0  4260.3     .16       0  4861.4     .12       0
    4997     .07       0    5003     .12       0  5016.9     .16       0
Bank Sta=4997,5003
XS Rating Curve= 0 ,0
Exp/Cntr=0.3,0.1

Type RM Length L Ch R = 1 ,20770   ,471,471,471
BEGIN DESCRIPTION:
SLOAN CREEK 33.0
END DESCRIPTION:
XS GIS Cut Line= 3
      3547049.62     10666310.15      3547249.61     10665210.19
      3547399.62     10664860.17
#Sta/Elev= 30
  3922.5  350.83  4066.4  346.34  4165.3  339.77  4177.8  337.36  4216.3  336.38
  4449.7  328.38  4664.4  326.31  4725.4  327.65    4858  325.76  4928.7  323.62
  4955.4  325.68  4969.3  324.87  4979.5  318.32  4989.7  315.76    4997  315.76
  4999.8  315.26    5003  315.76  5013.8  316.66  5030.3  325.31  5056.8   325.6
  5207.3  327.22  5290.7  331.06  5312.5  329.64  5330.6  331.69  5345.1  330.16
  5354.2  331.76  5359.6  330.46  5388.6  333.14  5406.8  342.61  5421.3  340.27
#Mann= 8 ,-1 , 0
  3922.5     .05       0  4066.4     .16       0  4165.3     .05       0
  4216.3     .16       0    4858     .12       0    4997     .07       0
    5003     .12       0  5056.8     .16       0
#XS Ineff= 2 , 0
                         5291.14          334.07
Permanent Ineff=
       F       F
Bank Sta=4997,5003
XS Rating Curve= 0 ,0
Exp/Cntr=0.3,0.1

Type RM Length L Ch R = 1 ,20299   ,1139,1139,1139
BEGIN DESCRIPTION:
SLOAN CREEK 32.0
END DESCRIPTION:
XS GIS Cut Line= 3
      3547249.62     10666410.17      3547649.61     10665310.19
      3547599.61     10664710.22
#Sta/Elev= 30
  3814.7  350.89  3931.7  347.91    4219  332.95  4298.2  330.31  4328.8  331.96
  4346.7  329.41  4369.5  328.99  4404.1  328.39  4575.2  326.14  4728.9   325.5
  4780.9  325.35  4836.2  325.95  4883.8  324.49  4931.9  321.53  4939.3  321.59
  4944.6  324.72  4963.9  322.65  4975.2  323.14    4997  314.92  4999.8  314.42
    5003  314.92  5015.3  318.82  5025.3   324.9  5143.6  324.73    5236   327.1
  5416.6  336.35  5436.7  339.38  5466.8  338.77  5540.4   343.3  5587.2  345.44
#Mann= 11 ,-1 , 0
  3814.7     .05       0  4369.5     .16       0  4404.1     .05       0
  4575.2     .16       0  4728.9     .05       0  4780.9     .16       0
  4883.8     .12       0    4997     .07       0    5003     .12       0
  5143.6     .16       0  5540.4     .05       0
#XS Ineff= 2 , 0
         4329.55  334.11
Permanent Ineff=
       F       F
Bank Sta=4997,5003
XS Rating Curve= 0 ,0
Exp/Cntr=0.3,0.1

Type RM Length L Ch R = 1 ,19160   ,1362,1362,1362
BEGIN DESCRIPTION:
SLOAN CREEK 30.0
END DESCRIPTION:
XS GIS Cut Line= 2
      3548301.17     10666810.76      3548405.34     10664336.75
#Sta/Elev= 30
  3827.2  350.57    4108  340.89  4218.1  334.38  4248.1  334.59  4258.2  332.62
  4268.2  334.06  4408.3   328.1  4856.8  322.32  4978.8  324.15  4988.8  323.32
    4997  312.86  4999.8  312.36    5003  312.86  5008.5  313.45  5018.8  320.15
  5038.8  322.71  5107.3  322.87  5289.1  322.87  5309.1   319.8  5329.1  322.81
  5369.1  323.34  5399.2  321.34  5409.2  322.25  5419.2  318.19  5439.2  321.91
  5789.5  328.91  5869.6  333.08  5899.6  333.43  6179.9  348.05  6303.4  350.36
#Mann= 5 ,-1 , 0
  3827.2     .05       0    4997    .035       0    5003     .05       0
  5008.5     .16       0  5107.3     .05       0
#XS Ineff= 2 ,-1
 5282.95  5339.2  322.58 5366.48 5473.86  321.64
Permanent Ineff=
       F       F
Bank Sta=4997,5003
XS Rating Curve= 0 ,0
Exp/Cntr=0.3,0.1

Type RM Length L Ch R = 1 ,17798   ,1300,1300,1300
BEGIN DESCRIPTION:
SLOAN CREEK 29.0
END DESCRIPTION:
XS GIS Cut Line= 3
      3548552.89     10666949.65       3549091.1     10665517.33
      3549212.63     10664388.86
#Sta/Elev= 30
  3247.1  347.95  3385.4  344.63  3545.6  337.44  3678.8  333.51  3764.2     328
  3879.8  325.03  4325.5  320.86  4603.2  321.65    4698  321.37  4728.2   320.2
  4758.4  321.27  4844.7  320.66  4885.1  321.56  4965.4  321.75  4985.5  318.28
  4993.7  311.15    4997  311.15  4999.8  310.65    5003  311.15  5015.7  321.15
  5036.7  321.83  5090.7  320.44  5226.9  324.06  5317.4  328.94  5366.5   330.5
  5463.5  337.18  5538.7  339.79  5599.1  343.71  5739.4  347.31  5912.2  348.25
#Mann= 5 ,-1 , 0
  3247.1     .05       0  4885.1     .16       0    4997     .07       0
    5003     .16       0  5036.7     .05       0
Bank Sta=4997,5003
XS Rating Curve= 0 ,0
Exp/Cntr=0.3,0.1

Type RM Length L Ch R = 1 ,16498   ,821,821,821
BEGIN DESCRIPTION:
SLOAN CREEK 28.0
END DESCRIPTION:
XS GIS Cut Line= 3
      3549336.77     10667220.43      3549621.48     10665998.24
       3549656.2     10664574.87
#Sta/Elev= 30
  3576.8  349.13    3745  342.74  3946.7  332.42    4181  325.03  4511.4  320.81
  4849.8  319.51  4899.8  317.97  4909.8  315.95  4916.5  316.85  4969.8  319.29
  4979.8  317.97  4989.8  309.97    4997  309.86  4999.8  309.36    5003  309.86
  5009.8  318.72  5099.8  320.12  5181.3  319.47  5209.9   320.3  5279.9  319.32
  5359.9  319.78  5409.9  321.19  5459.9  320.65    5540  323.09    5690  325.36
    5710  326.61    5750  326.62  5860.1   330.7  5970.1  336.25  6255.5  344.21
#Mann= 5 ,-1 , 0
  3576.8     .05       0  4916.5     .16       0    4997     .07       0
    5003     .16       0  5181.3     .05       0
Bank Sta=4997,5003
XS Rating Curve= 0 ,0
Exp/Cntr=0.3,0.1

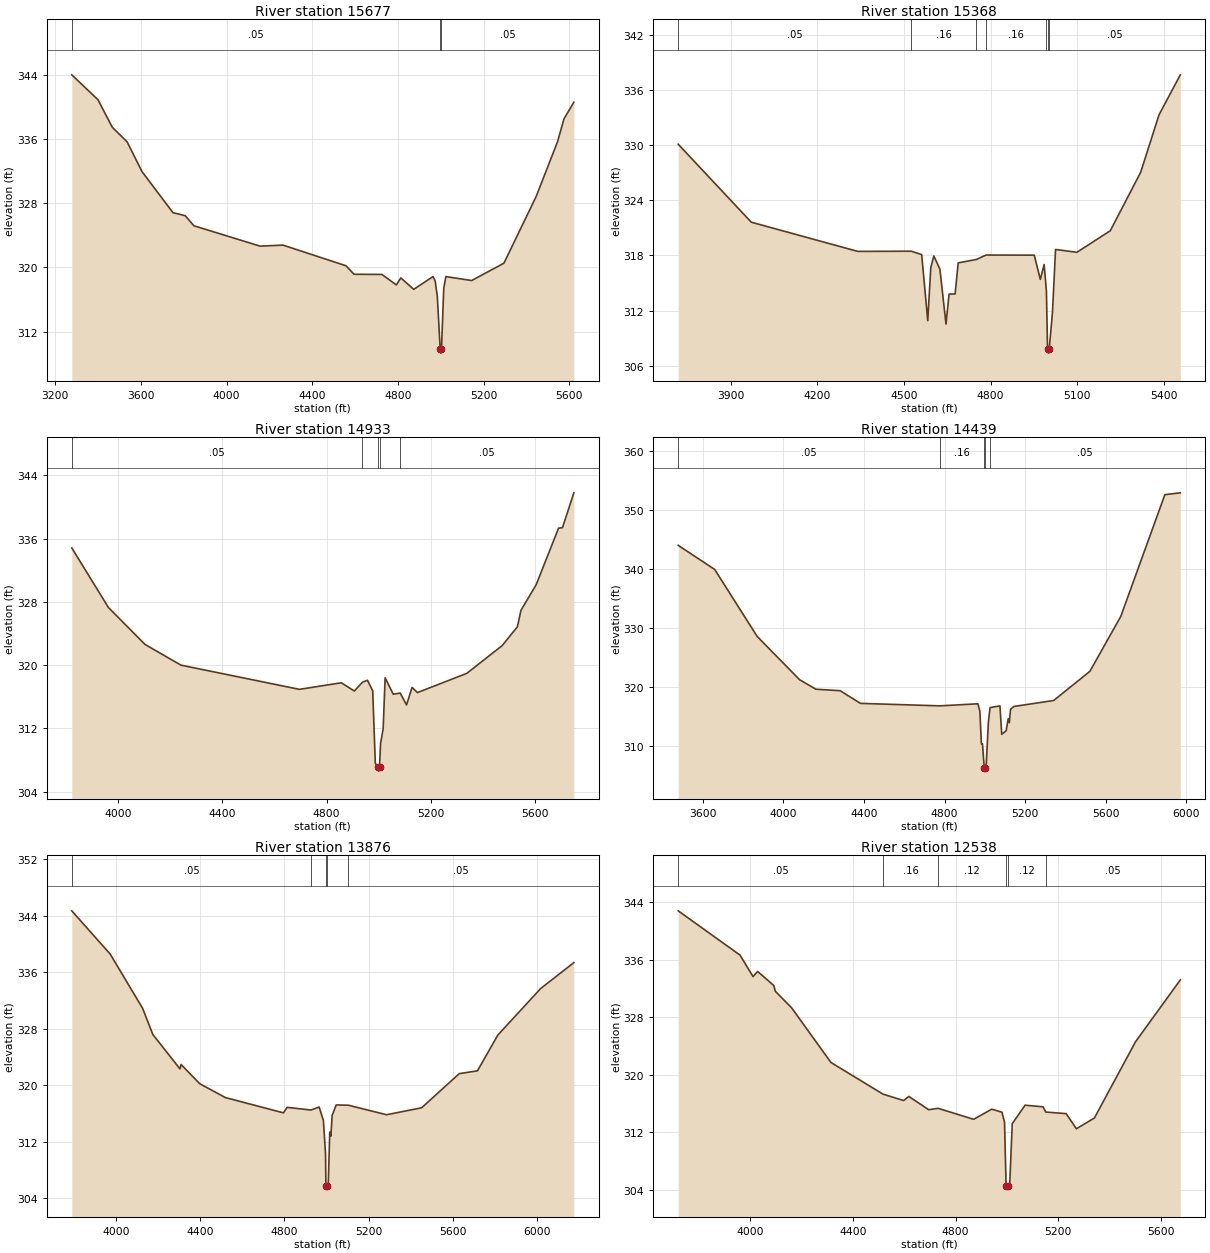
Type RM Length L Ch R = 1 ,15677   ,309,309,309
BEGIN DESCRIPTION:
SLOAN CREEK 27.0
END DESCRIPTION:
XS GIS Cut Line= 3
      3549558.97     10667171.87      3550183.98     10665782.96
      3550128.48     10664964.39
#Sta/Elev= 30
  3277.3  344.04  3399.8  340.93  3466.3   337.5  3535.8  335.67  3605.2  331.96
  3749.6  326.84  3806.9  326.46  3847.7   325.2  4156.4  322.66  4263.2  322.79
  4557.4  320.21    4595  319.15    4725  319.13  4792.4  317.82  4813.2   318.7
  4873.3  317.27  4963.5  318.86  4973.5  318.32  4983.5  316.42    4997  309.81
  4999.8  309.31    5003  309.81  5013.6  317.42  5023.6  318.86  5143.9  318.37
  5294.3  320.53  5444.6  328.83  5544.8   335.7  5574.9  338.55  5620.8  340.62
#Mann= 3 ,-1 , 0
  3277.3     .05       0    4997     .03       0    5003     .05       0
Bank Sta=4997,5003
XS Rating Curve= 0 ,0
Exp/Cntr=0.3,0.1

Type RM Length L Ch R = 1 ,15368   ,435,435,435
BEGIN DESCRIPTION:
SLOAN CREEK 26.0
END DESCRIPTION:
XS GIS Cut Line= 3
      3550799.61      10666660.2      3550399.61     10665460.19
       3550249.6     10665010.15
#Sta/Elev= 30
  3717.7  330.11  3970.7  321.62  4339.6  318.44  4524.9  318.46    4561  318.09
  4582.1   310.9  4592.6  316.68  4603.1  317.94  4624.2  316.51  4645.3  310.53
  4655.9  313.79  4676.9   313.8  4687.5  317.19  4750.9  317.56  4783.8  318.04
    4951  318.03  4972.1  315.39  4985.3  317.01  4992.2  314.45  4993.2  314.08
    4997  307.86  4999.8  307.36    5003  307.86  5014.2  311.82  5024.8  318.65
  5098.6  318.34  5214.5  320.69  5319.9  327.07  5383.2  333.31    5457  337.67
#Mann= 7 ,-1 , 0
  3717.7     .05       0  4524.9     .16       0  4750.9     .05       0
  4783.8     .16       0  4992.2     .05       0    4997     .03       0
    5003     .05       0
Bank Sta=4997,5003
XS Rating Curve= 0 ,0
Exp/Cntr=0.3,0.1

Type RM Length L Ch R = 1 ,14933   ,494,494,494
BEGIN DESCRIPTION:
SLOAN CREEK 25.0
END DESCRIPTION:
XS GIS Cut Line= 3
      3550849.61     10666710.17      3550749.61     10665510.19
      3550349.58     10664910.15
#Sta/Elev= 30
  3822.9  334.83  3963.4  327.29  4103.9  322.61  4241.8  319.99  4695.9  316.93
  4856.5  317.76  4906.6  316.72  4937.4  317.83  4956.8  318.08  4976.9  316.75
  4986.9  307.58    4997  307.08  4999.8  306.58    5003  307.08    5007  310.06
    5017  311.95  5024.5  318.39  5055.6  316.32  5082.5  316.46  5106.7  314.96
  5127.7  317.18  5148.7  316.52    5338  318.96  5473.2  322.46  5531.8  324.85
  5545.3  326.92  5603.9  330.18  5689.6  337.33  5704.6  337.39  5748.2   341.8
#Mann= 5 ,-1 , 0
  3822.9     .05       0  4937.4     .16       0    4997     .07       0
    5003     .16       0  5082.5     .05       0
Bank Sta=4997,5003
XS Rating Curve= 0 ,0
Exp/Cntr=0.3,0.1

Type RM Length L Ch R = 1 ,14439   ,563,563,563
BEGIN DESCRIPTION:
SLOAN CREEK 24.0
END DESCRIPTION:
XS GIS Cut Line= 3
      3550899.61     10666960.19      3551049.61     10665460.19
       3550649.6     10664560.16
#Sta/Elev= 30
  3477.7  343.96  3658.6  339.88  3869.6  328.51  4080.7  321.16  4161.1  319.56
  4281.7  319.31  4382.2  317.16  4776.8  316.74  4965.1  317.09  4975.1  315.84
  4982.7  310.31  4987.9  310.31    4997  306.17  4999.8  305.67    5003  306.17
  5007.1  307.03  5017.3  314.01  5025.8  316.45  5074.8  316.73  5083.7  311.92
  5105.6  312.53  5115.8  314.57  5121.3  313.89  5127.4  316.16  5144.5  316.64
  5341.5  317.65  5521.4   322.6  5674.6  331.91  5893.5  352.56  5970.1  352.87
#Mann= 5 ,-1 , 0
  3477.7     .05       0  4776.8     .16       0    4997     .07       0
    5003     .16       0  5025.8     .05       0
#XS Ineff= 1 ,-1
  5062.5  5139.2  315.92
Permanent Ineff=
       F
Bank Sta=4997,5003
XS Rating Curve= 0 ,0
Exp/Cntr=0.3,0.1

Type RM Length L Ch R = 1 ,13876   ,1338,1338,1338
BEGIN DESCRIPTION:
SLOAN CREEK 23.0
END DESCRIPTION:
XS GIS Cut Line= 3
       3551049.6     10666910.23      3551249.61     10665710.19
      3551649.62     10664610.15
#Sta/Elev= 30
  3788.7   344.7  3971.2  338.58  4125.8  330.87    4174  327.18  4303.2   322.3
  4308.3  322.93    4397   320.2  4518.7  318.24  4794.9  316.07  4812.7  316.85
  4926.2  316.47  4964.7   316.9    4985     315  4995.2  310.23    4997  305.76
  4999.8  305.26    5003  305.76    5008  305.76  5015.3  313.35  5020.6  312.76
  5026.6   315.7  5045.9  317.19    5104  317.15  5285.3   315.8  5452.2  316.79
  5631.1  321.63  5717.5  322.02  5814.6   327.1  6018.1  333.69  6175.8  337.36
#Mann= 5 ,-1 , 0
  3788.7     .05       0  4926.2     .16       0    4997     .07       0
    5003     .16       0    5104     .05       0
Bank Sta=4997,5003
XS Rating Curve= 0 ,0
Exp/Cntr=0.3,0.1

Type RM Length L Ch R = 1 ,12538   ,296,296,296
BEGIN DESCRIPTION:
SLOAN CREEK 21.0
END DESCRIPTION:
XS GIS Cut Line= 3
      3551757.65     10667048.23      3551929.53     10665918.01
      3551929.53     10665105.53
#Sta/Elev= 30
  3719.9  342.79  3960.7  336.63  4011.3  333.65  4029.3  334.37  4092.2  332.41
    4098  331.62  4161.6  329.31  4314.7  321.72  4517.5  317.32  4597.9  316.43
  4618.2     317  4695.7  315.15  4731.8  315.35  4870.9  313.82  4940.9  315.23
  4980.9  314.81  4990.9  313.43    4997  304.62  4999.8  304.12    5003  304.62
  5010.9  304.62  5020.9  313.21  5070.9  315.78  5140.9  315.56  5151.4  314.83
  5230.9  314.61  5270.9  312.51  5340.9     314  5500.9  324.58  5675.6  333.19
#Mann= 6 ,-1 , 0
  3719.9     .05       0  4517.5     .16       0  4731.8     .12       0
    4997     .07       0    5003     .12       0  5151.4     .05       0
Bank Sta=4997,5003
XS Rating Curve= 0 ,0
Exp/Cntr=0.3,0.1

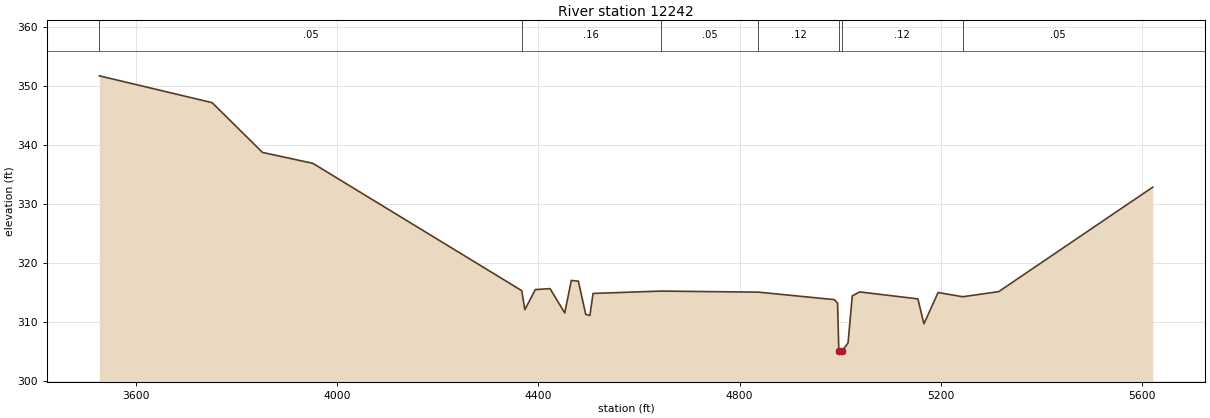
Type RM Length L Ch R = 1 ,12242   ,396,396,396
BEGIN DESCRIPTION:
SLOAN CREEK 20.0
END DESCRIPTION:
XS GIS Cut Line= 3
      3552960.77     10666891.96      3552044.11      10665662.8
      3551992.03     10665105.55
#Sta/Elev= 30
  3527.7  351.68  3751.8  347.13  3851.9  338.69    3952  336.84    4367  315.25
  4373.2  312.03    4394  315.43  4423.2   315.6  4452.4  311.48  4465.5  316.99
  4479.5  316.86  4494.1  311.23  4502.4  311.05  4508.7  314.78  4642.9  315.18
  4837.3     315  4988.2  313.73  4994.5  313.11    4997  304.99  4999.8  304.49
    5003  304.99  5015.3  306.38  5023.7  314.36  5038.3  315.04    5154  313.86
  5166.1  309.63  5194.2  314.94  5243.2  314.22  5314.7  315.09  5620.7   332.8
#Mann= 7 ,-1 , 0
  3527.7     .05       0    4367     .16       0  4642.9     .05       0
  4837.3     .12       0    4997     .07       0    5003     .12       0
  5243.2     .05       0
Bank Sta=4997,5003
XS Rating Curve= 0 ,0
Exp/Cntr=0.3,0.1