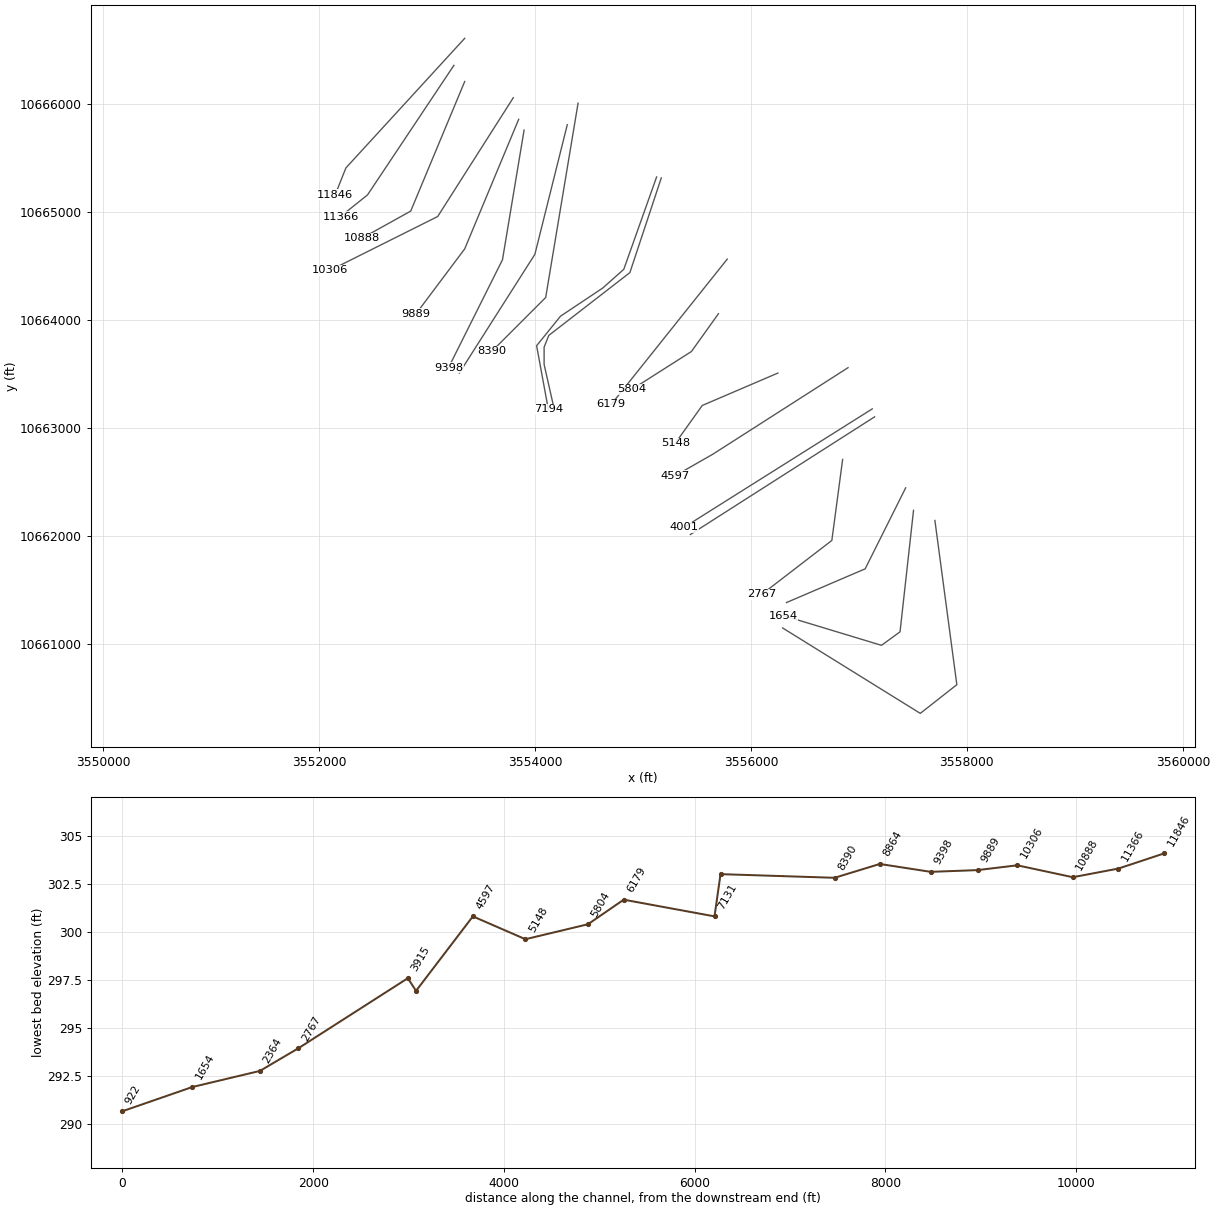
HEC-RAS study SLOAN CREEK.prj: SLOAN CREEK Base Level Engineering

--- SLOAN CREEK.g01 (geometry) --- (continued)

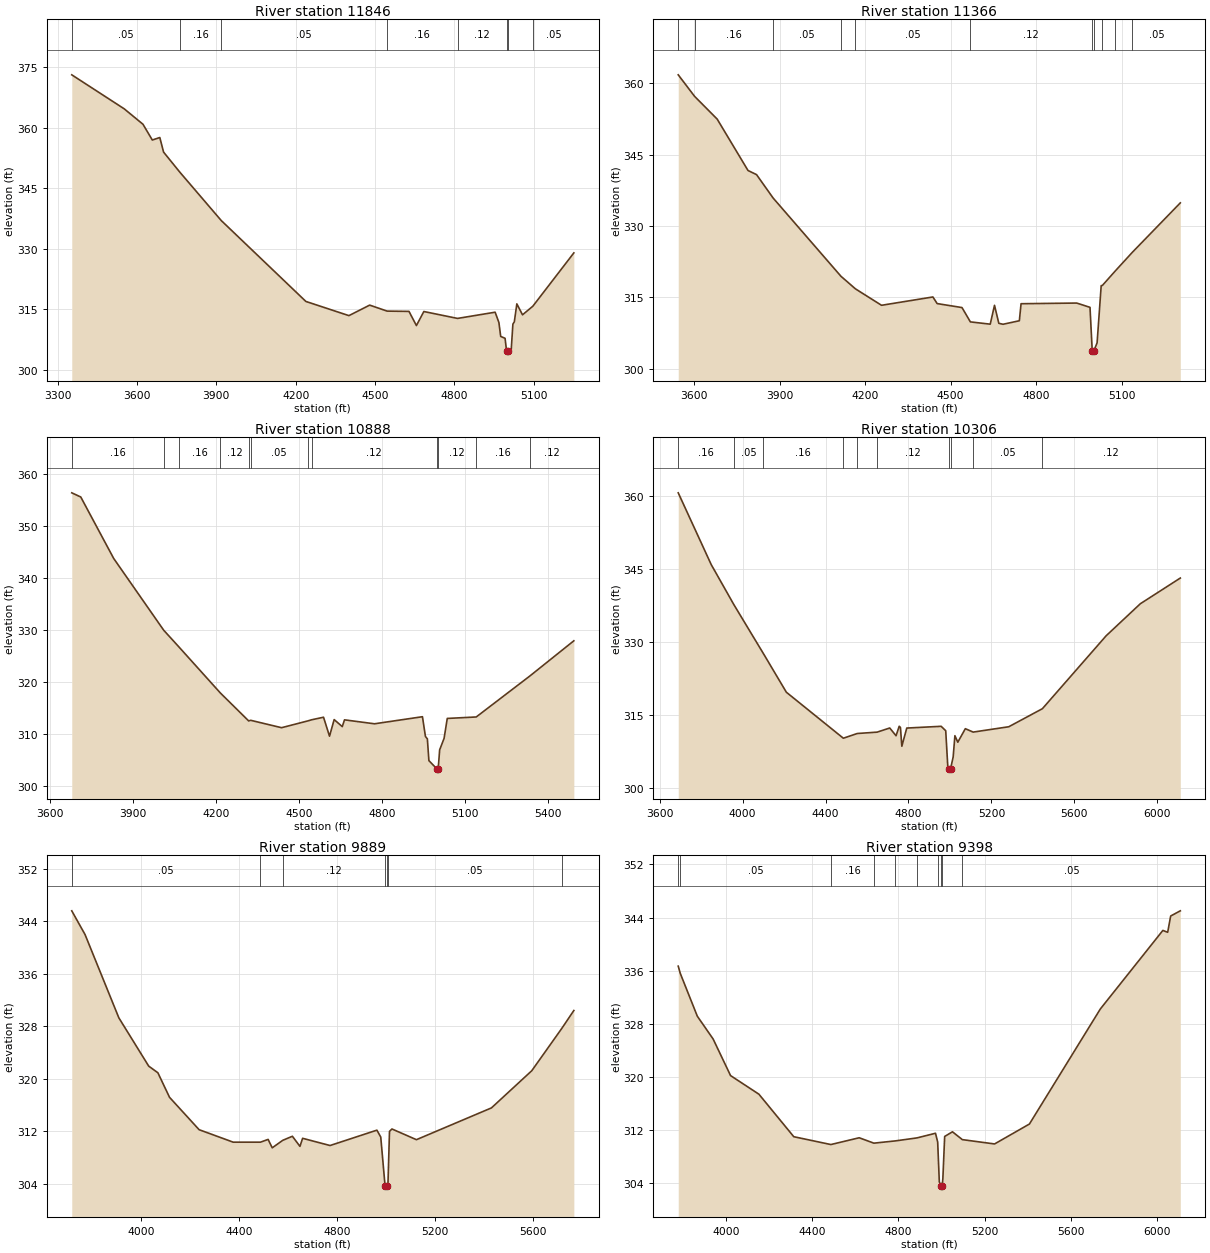
Type RM Length L Ch R = 1 ,11846   ,480,480,480
BEGIN DESCRIPTION:
SLOAN CREEK 19.0
END DESCRIPTION:
XS GIS Cut Line= 3
      3553349.62      10666610.2      3552249.61     10665410.19
      3552149.59     10665160.15
#Sta/Elev= 30
  3353.9  373.11  3552.2  364.67  3623.1  360.84  3658.2  356.94  3686.6  357.56
  3700.8  353.94  3762.6  348.94  3918.7  336.97  4238.5   316.9  4401.2  313.38
  4479.6  315.99  4545.6   314.5  4628.2  314.43  4656.2  310.92  4684.3   314.4
  4811.6  312.69  4953.7  314.23  4967.9  311.68  4974.7  308.22  4991.2  307.76
    4997  304.58  4999.8  304.08    5003  304.58  5014.1  304.58  5020.8  311.27
  5026.2  311.84  5035.7   316.3  5057.2  313.58  5096.2  315.72  5251.1  328.94
#Mann= 8 ,-1 , 0
  3353.9     .05       0  3762.6     .16       0  3918.7     .05       0
  4545.6     .16       0  4811.6     .12       0    4997     .07       0
    5003     .12       0  5096.2     .05       0
Bank Sta=4997,5003
XS Rating Curve= 0 ,0
Exp/Cntr=0.3,0.1

Type RM Length L Ch R = 1 ,11366   ,478,478,478
BEGIN DESCRIPTION:
SLOAN CREEK 18.0
END DESCRIPTION:
XS GIS Cut Line= 3
      3553249.62      10666360.2      3552449.61     10665160.19
      3552199.61     10664960.19
#Sta/Elev= 30
  3543.8  361.82  3601.1   357.3  3680.5  352.51  3788.7   341.7  3818.7  340.83
  3876.9  335.91  4114.9  319.46  4165.8  316.81  4257.4  313.35  4437.7   315.1
  4452.7  313.71  4539.9  312.87  4569.3  309.86    4639  309.38    4654  313.35
  4669.1  309.56  4684.1  309.36  4741.2   310.1  4747.2  313.68  4942.5  313.82
  4989.2  312.92    4997  303.79  4999.8  303.29    5003  303.79  5014.1  305.46
  5028.5  317.49  5032.4  317.51  5077.9  320.57  5138.1  324.51  5306.2  334.89
#Mann= 11 ,-1 , 0
  3543.8     .05       0  3601.1     .16       0  3876.9     .05       0
  4114.9     .16       0  4165.8     .05       0  4569.3     .12       0
    4997     .07       0    5003     .12       0  5032.4     .16       0
  5077.9     .12       0  5138.1     .05       0
Bank Sta=4997,5003
XS Rating Curve= 0 ,0
Exp/Cntr=0.3,0.1

Type RM Length L Ch R = 1 ,10888   ,582,582,582
BEGIN DESCRIPTION:
SLOAN CREEK 17.0
END DESCRIPTION:
XS GIS Cut Line= 3
       3553349.6     10666210.16      3552849.61     10665010.19
      3552399.65     10664760.21
#Sta/Elev= 30
  3678.5  356.29    3711  355.49  3830.1  343.68  4010.7  329.91    4066  326.68
  4215.4  317.86    4318  312.48  4325.2   312.6  4436.8  311.18    4532  312.49
  4545.4   312.7  4588.5  313.19  4610.1  309.55  4626.9  312.74  4656.2  311.39
  4664.3  312.69  4772.6  311.93    4946  313.29  4956.8   309.5  4963.8  309.03
  4969.3  304.86    4997  303.34  4999.8  302.84    5003  303.34  5008.2  306.93
  5024.2  309.13  5035.7  312.96  5140.4  313.24  5335.2  321.15  5493.2  327.87
#Mann= 12 ,-1 , 0
  3678.5     .16       0  4010.7     .05       0    4066     .16       0
  4215.4     .12       0    4318     .16       0  4325.2     .05       0
    4532     .16       0  4545.4     .12       0    4997     .07       0
    5003     .12       0  5140.4     .16       0  5335.2     .12       0
Bank Sta=4997,5003
XS Rating Curve= 0 ,0
Exp/Cntr=0.3,0.1

Type RM Length L Ch R = 1 ,10306   ,417,417,417
BEGIN DESCRIPTION:
SLOAN CREEK 16.0
END DESCRIPTION:
XS GIS Cut Line= 3
      3553799.62      10666060.2      3553099.61     10664960.19
       3552099.6     10664460.18
#Sta/Elev= 30
  3689.3  360.71  3848.5  345.94  3957.4  337.73  4099.6  327.68  4210.9  319.69
  4485.7  310.23  4552.9   311.2  4648.6  311.48  4709.5  312.33    4740  310.74
  4755.2  312.69  4761.2  312.44  4767.9  308.58  4791.7  312.32  4957.6  312.68
  4979.6  311.77  4990.2  303.96    4997  303.96  4999.8  303.46    5003  303.96
  5015.5  306.37  5023.9  310.75  5037.9  309.41  5074.2  312.19    5112  311.49
  5283.8  312.59  5445.9   316.3  5753.4   331.3  5918.3  337.89  6111.2  343.18
#Mann= 10 ,-1 , 0
  3689.3     .16       0  3957.4     .05       0  4099.6     .16       0
  4485.7     .12       0  4552.9     .16       0  4648.6     .12       0
    4997     .07       0    5003     .12       0    5112     .05       0
  5445.9     .12       0
Bank Sta=4997,5003
XS Rating Curve= 0 ,0
Exp/Cntr=0.3,0.1

Type RM Length L Ch R = 1 ,9889    ,491,491,491
BEGIN DESCRIPTION:
SLOAN CREEK 15.0
END DESCRIPTION:
XS GIS Cut Line= 3
      3553849.62     10665860.21      3553349.61     10664660.19
      3552899.62     10664060.21
#Sta/Elev= 30
  3717.8  345.59    3772  341.98  3910.1  329.29    4032  321.94  4069.4  320.93
    4117  317.19  4237.8  312.26    4377  310.36  4488.2  310.36  4519.5  310.78
  4536.3   309.5  4579.2  310.64  4618.6  311.26  4649.5  309.72  4660.3  310.95
  4772.4  309.85  4963.7  312.19  4979.4  311.14    4997  303.71  4999.8  303.21
    5003  303.71  5007.4  303.78  5008.6  303.71  5015.1     312  5025.1  312.37
  5125.1  310.74  5431.4  315.58    5596  321.24  5718.9   327.7  5767.8  330.41
#Mann= 7 ,-1 , 0
  3717.8     .05       0  4488.2     .16       0  4579.2     .12       0
    4997     .07       0    5003     .12       0  5007.4     .05       0
  5718.9     .16       0
Bank Sta=4997,5003
XS Rating Curve= 0 ,0
Exp/Cntr=0.3,0.1

Type RM Length L Ch R = 1 ,9398    ,534,534,534
BEGIN DESCRIPTION:
SLOAN CREEK 14.0
END DESCRIPTION:
XS GIS Cut Line= 3
      3553899.61     10665760.17      3553699.61     10664560.19
      3553199.59     10663560.16
#Sta/Elev= 30
  3775.8  336.68  3785.1  335.61  3864.5  329.15    3938  325.72  4019.1  320.21
  4150.9  317.41  4313.1  311.01  4485.5  309.83  4617.2  310.85  4685.6  310.04
  4785.7  310.38  4885.8  310.83  4972.1  311.53  4982.2   310.2  4985.8  307.37
  4989.8  304.23    4997  303.62  4999.8  303.12    5003  303.62  5006.3  304.69
  5014.7  311.05    5051  311.75  5096.9  310.57  5246.7  309.92  5408.8  312.92
  5738.6  330.24  6029.3  342.06  6051.7  341.78  6065.6  344.23  6110.4  345.01
#Mann= 10 ,-1 , 0
  3775.8     .07       0  3785.1     .05       0  4485.5     .16       0
  4685.6     .12       0  4785.7     .16       0  4885.8     .12       0
  4985.8     .16       0    4997     .07       0    5003     .16       0
  5096.9     .05       0
Bank Sta=4997,5003
XS Rating Curve= 0 ,0
Exp/Cntr=0.3,0.1

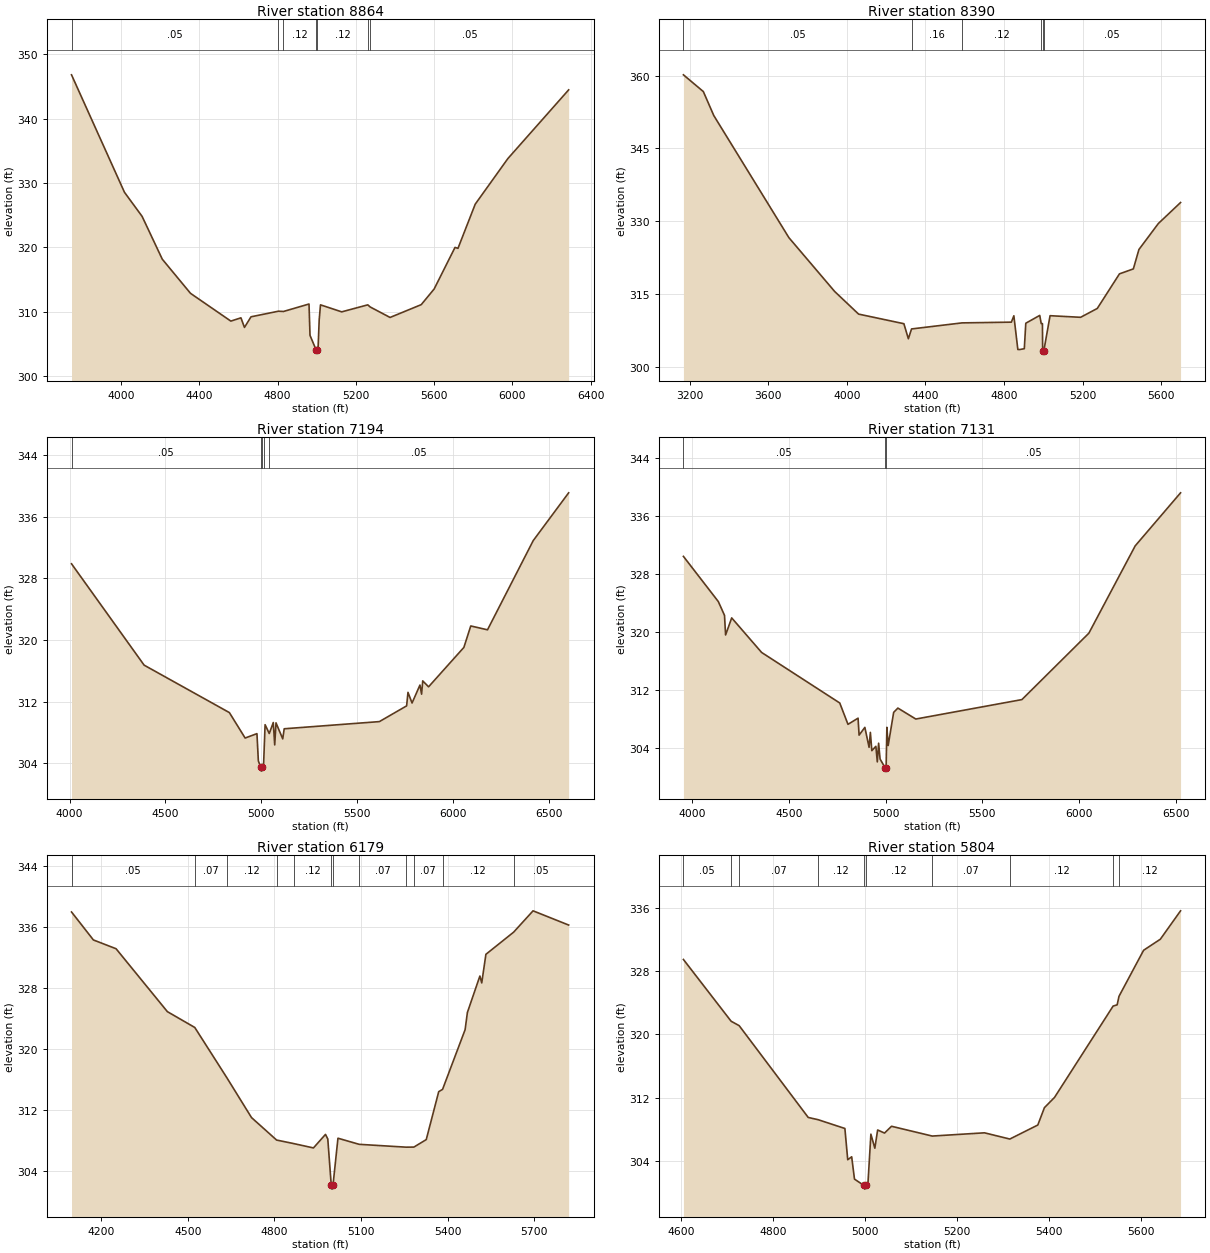
Type RM Length L Ch R = 1 ,8864    ,474,474,474
BEGIN DESCRIPTION:
SLOAN CREEK 13.0
END DESCRIPTION:
XS GIS Cut Line= 3
      3554299.62     10665810.22      3553999.61     10664610.19
      3553299.61      10663510.2
#Sta/Elev= 30
  3746.8  346.82  4017.4  328.55  4107.6   324.8  4210.7  318.14    4355  312.83
  4561.1  308.51  4612.7  309.02  4630.7  307.53  4664.2  309.18  4804.1  310.05
  4830.2  310.01  4960.6  311.17  4965.7  306.29    4997  304.03  4999.8  303.53
    5003  304.03  5006.6  304.03  5012.6  308.68  5019.3  311.04  5127.7  309.95
  5260.9  311.04  5273.3  310.71  5374.9  309.08  5534.1  311.07  5600.1   313.5
  5706.8  319.97    5722  319.83  5810.1   326.7  5976.9  333.79  6287.6  344.48
#Mann= 7 ,-1 , 0
  3746.8     .05       0  4804.1     .16       0  4830.2     .12       0
    4997     .07       0    5003     .12       0  5260.9     .16       0
  5273.3     .05       0
Bank Sta=4997,5003
XS Rating Curve= 0 ,0
Exp/Cntr=0.3,0.1

Type RM Length L Ch R = 1 ,8390    ,1196,1196,1196
BEGIN DESCRIPTION:
SLOAN CREEK 12.0
END DESCRIPTION:
XS GIS Cut Line= 3
      3554399.61      10666010.2      3554099.61     10664210.19
      3553599.64     10663710.22
#Sta/Elev= 30
  3167.4  360.14  3268.8  356.69    3322  351.75  3704.7  326.59  3937.9   315.5
  4059.5  310.85  4290.2  308.87    4313  305.77  4329.2  307.79  4586.4  309.04
  4837.6  309.19  4850.3   310.5  4870.6  303.56  4880.7  303.55  4903.5  303.72
  4911.1  308.97  4982.1  310.58  4989.7  308.89  4995.8  308.89    4997  303.31
  4999.8  302.81    5003  303.31  5034.7  310.52  5190.2  310.19  5275.1  312.01
  5388.2  319.14  5458.9  320.16  5487.2  324.15  5586.2  329.51  5699.3  333.83
#Mann= 6 ,-1 , 0
  3167.4     .05       0  4329.2     .16       0  4586.4     .12       0
  4989.7     .05       0    4997     .03       0    5003     .05       0
Bank Sta=4997,5003
XS Rating Curve= 0 ,0
Exp/Cntr=0.3,0.1

Type RM Length L Ch R = 1 ,7194    ,63,63,63
BEGIN DESCRIPTION:
SLOAN CREEK 11.0
END DESCRIPTION:
XS GIS Cut Line= 6
      3555126.74     10665326.18       3554822.9     10664471.11
      3554627.59     10664297.49      3554236.96     10664037.08
      3554015.61     10663763.64      3554123.92     10663174.28
#Sta/Elev= 30
  4010.3  329.88  4388.9  316.74  4833.4  310.59  4915.6  307.29  4977.2  307.86
  4984.6  304.32    4997   303.5  4999.8     303    5003   303.5  5011.5  303.65
  5019.7  309.02  5041.4  307.88  5062.4   309.3  5069.9   306.4  5076.6  309.26
  5111.7  307.18  5119.3  308.49  5615.7  309.42  5757.7  311.46  5764.8  313.21
    5786  311.83  5827.2  314.16  5835.8  312.98  5841.7   314.7  5872.2  313.93
  6056.3  319.04  6092.2  321.82  6179.5  321.32    6418  332.89  6602.6  339.08
#Mann= 5 ,-1 , 0
  4010.3     .05       0    4997     .04       0    5003     .05       0
  5011.5     .12       0  5041.4     .05       0
Bank Sta=4997,5003
XS Rating Curve= 0 ,0
Exp/Cntr=0.3,0.1

Type RM Length L Ch R = 1 ,7131    ,952,952,952
BEGIN DESCRIPTION:
SLOAN CREEK 10.0
END DESCRIPTION:
XS GIS Cut Line= 6
      3555170.12     10665317.44      3554879.33     10664440.72
      3554128.46     10663859.13      3554085.06     10663750.62
      3554085.06     10663590.03       3554176.2     10663186.38
#Sta/Elev= 30
  3955.4   330.4  4135.8  324.17  4167.7  322.27  4173.3  319.57  4204.9  321.92
  4359.4  317.16  4763.4  310.19  4805.9  307.25    4858   308.1  4863.3  305.76
  4893.1  306.83  4914.9  304.08  4921.6  306.14  4929.1  303.62    4950  304.22
  4957.5  302.07  4964.2  304.65  4971.8  302.47    4997   301.3  4999.8   300.8
    5003   301.3  5006.9  306.84  5013.6  304.33    5042   308.9  5063.8  309.49
  5156.4  307.98  5704.8  310.66  6050.8  319.81  6290.4  331.85  6524.8  339.16
#Mann= 3 ,-1 , 0
  3955.4     .05       0    4997     .04       0    5003     .05       0
Bank Sta=4997,5003
XS Rating Curve= 0 ,0
Exp/Cntr=0.3,0.1

Type RM Length L Ch R = 1 ,6179    ,375,375,375
BEGIN DESCRIPTION:
SLOAN CREEK 8.0
END DESCRIPTION:
XS GIS Cut Line= 2
      3555781.02     10664565.52      3554706.75     10663219.96
#Sta/Elev= 30
  4097.4  337.93  4173.2  334.27  4251.7  333.12  4429.4  324.89  4524.3  322.82
  4635.5  316.24  4720.8  311.03  4807.7  308.09  4866.8  307.63  4935.3  307.06
    4977  308.83    4985  308.23    4997  302.17  4999.8  301.67    5003  302.17
  5020.2  308.33  5093.9  307.53  5256.3  307.16  5283.2  307.17    5326  308.15
  5369.2  314.42  5382.5  314.72  5460.6  322.53  5468.5  324.78  5511.8  329.55
  5518.2  328.65  5532.6  332.39  5628.7  335.29  5695.9  338.08  5819.2  336.22
#Mann= 12 ,-1 , 0
  4097.4     .05       0  4524.3     .07       0  4635.5     .12       0
  4807.7     .07       0  4866.8     .12       0    4997     .07       0
    5003     .12       0  5093.9     .07       0  5256.3     .12       0
  5283.2     .07       0  5382.5     .12       0  5628.7     .05       0
Bank Sta=4997,5003
XS Rating Curve= 0 ,0
Exp/Cntr=0.3,0.1

Type RM Length L Ch R = 1 ,5804    ,656,656,656
BEGIN DESCRIPTION:
SLOAN CREEK 7.0
END DESCRIPTION:
XS GIS Cut Line= 3
      3555699.59     10664060.16      3555449.61     10663710.19
      3554899.61     10663360.19
#Sta/Elev= 30
    4605  329.51  4708.8  321.68  4726.3  321.12  4876.6  309.48  4898.4  309.19
  4956.4  308.08  4962.6  304.12  4971.2  304.49  4977.3  301.66    4997  300.89
  4999.8  300.39    5003  300.89  5006.8   301.3    5013  307.36  5021.6  305.58
  5027.7  307.89  5042.7   307.5  5057.9  308.36  5146.5  307.12  5260.3  307.53
  5315.4  306.74  5376.3  308.52  5390.7  310.72  5412.7  312.02  5540.2   323.6
    5549  323.76    5553  324.84  5606.6  330.68    5643  332.08    5687  335.68
#Mann= 10 ,-1 , 0
    4605     .05       0  4708.8     .12       0  4726.3     .07       0
  4898.4     .12       0    4997     .07       0    5003     .12       0
  5146.5     .07       0  5315.4     .12       0  5540.2     .07       0
    5553     .12       0
Bank Sta=4997,5003
XS Rating Curve= 0 ,0
Exp/Cntr=0.3,0.1

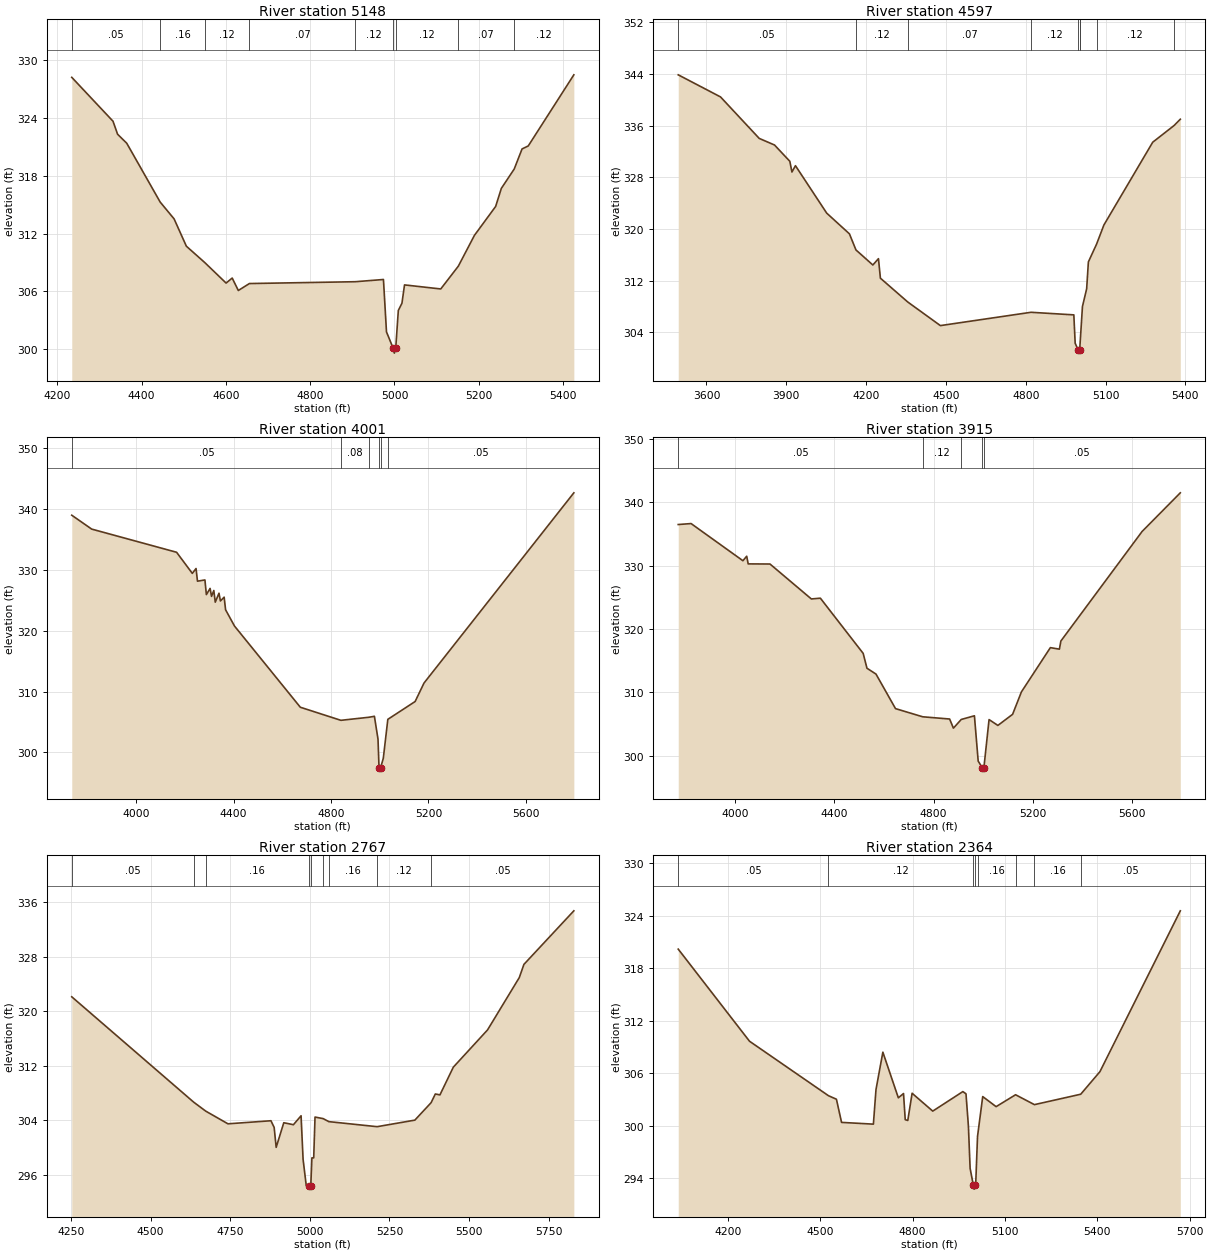
Type RM Length L Ch R = 1 ,5148    ,551,551,551
BEGIN DESCRIPTION:
SLOAN CREEK 6.0
END DESCRIPTION:
XS GIS Cut Line= 3
      3556249.58     10663510.18      3555549.61     10663210.19
      3555299.59     10662860.16
#Sta/Elev= 30
  4234.1  328.19    4332  323.64  4342.9  322.29  4364.6  321.36    4444  315.26
    4477  313.52  4506.1  310.69  4549.9  308.99  4600.4  306.87  4614.9  307.39
  4629.4   306.1  4655.7  306.82    4907  307.01  4973.9  307.24  4981.1  301.81
    4997  300.11  4999.8  299.61    5003  300.11  5009.2  304.03  5017.8  304.78
  5023.9  306.68  5109.9  306.26  5151.6  308.62  5189.8  311.81  5240.2  314.81
  5253.7  316.68  5284.3  318.69  5302.9  320.77  5317.6  321.08  5425.8  328.45
#Mann= 9 ,-1 , 0
  4234.1     .05       0    4444     .16       0  4549.9     .12       0
  4655.7     .07       0    4907     .12       0    4997     .07       0
    5003     .12       0  5151.6     .07       0  5284.3     .12       0
Bank Sta=4997,5003
XS Rating Curve= 0 ,0
Exp/Cntr=0.3,0.1

Type RM Length L Ch R = 1 ,4597    ,596,596,596
BEGIN DESCRIPTION:
SLOAN CREEK 5.0
END DESCRIPTION:
XS GIS Cut Line= 3
      3556899.62     10663560.19      3555649.61     10662760.19
      3555299.61     10662560.19
#Sta/Elev= 30
    3494  343.87    3653  340.45  3798.4  334.03  3855.9  333.01  3913.4  330.49
  3921.4  328.83  3934.6  329.81    4052  322.47  4137.5  319.26    4162  316.77
  4225.5  314.44  4246.6  315.42  4253.9   312.4  4356.8  308.71  4479.4  305.06
    4820  307.12    4981  306.72    4986  302.33    4997   301.3  4999.8   300.8
    5003   301.3  5003.3  301.52  5013.4  308.02  5029.2  310.76  5035.7  314.92
  5066.5  317.67    5094  320.63  5277.5  333.44  5357.7  336.02  5381.2     337
#Mann= 9 ,-1 , 0
    3494     .05       0    4162     .12       0  4356.8     .07       0
    4820     .12       0    4997     .07       0    5003     .12       0
  5003.3     .07       0  5066.5     .12       0  5357.7     .16       0
Bank Sta=4997,5003
XS Rating Curve= 0 ,0
Exp/Cntr=0.3,0.1

Type RM Length L Ch R = 1 ,4001    ,86,86,86
BEGIN DESCRIPTION:
SLOAN CREEK 4.0
END DESCRIPTION:
XS GIS Cut Line= 2
      3557123.91     10663178.61       3555379.1     10662080.51
#Sta/Elev= 30
  3735.3  338.98    3817   336.7  4165.7  332.89  4230.3  329.42  4245.6  330.22
  4251.5  328.14  4282.1  328.34    4288  325.93  4303.3  326.95  4309.2  325.64
  4318.6  326.61  4324.5  324.69  4339.8  326.16  4345.7  324.89    4361  325.51
  4366.9  323.44  4403.4  320.77  4673.8  307.42  4840.4  305.27  4954.5  305.77
    4978  305.93  4992.8  302.17    4997  297.42  4999.8  296.92    5003  297.42
  5014.5  299.02  5033.1  305.43  5145.2  308.36  5181.7   311.4  5796.9  342.66
#Mann= 6 ,-1 , 0
  3735.3     .05       0  4840.4     .08       0  4954.5     .07       0
    4997     .07       0    5003     .07       0  5033.1     .05       0
Bank Sta=4997,5003
XS Rating Curve= 0 ,0
Exp/Cntr=0.3,0.1

Type RM Length L Ch R = 1 ,3915    ,1148,1148,1148
BEGIN DESCRIPTION:
SLOAN CREEK 3.0
END DESCRIPTION:
XS GIS Cut Line= 2
       3557145.6     10663104.82      3555439.82     10662015.37
#Sta/Elev= 30
  3770.9  336.48  3822.7  336.63  4031.7  330.77  4046.9  331.48  4052.9  330.27
  4140.8  330.25  4307.5  324.74  4343.9  324.86  4516.5  316.15  4531.7  313.81
  4568.1  312.89  4646.8  307.44  4756.5  306.15    4865   305.8  4880.2  304.36
  4911.8  305.73  4964.9  306.31  4980.1  299.16    4997  298.08  4999.8  297.58
    5003  298.08  5023.9  305.71  5059.5  304.79  5118.8  306.54  5154.4  310.08
  5271.1  317.06  5307.5  316.82  5313.4   318.1  5640.8  335.38  5794.9  341.48
#Mann= 5 ,-1 , 0
  3770.9     .05       0  4756.5     .12       0  4911.8     .05       0
    4997     .04       0    5003     .05       0
Bank Sta=4997,5003
XS Rating Curve= 0 ,0
Exp/Cntr=0.3,0.1

Type RM Length L Ch R = 1 ,2767    ,403,403,403
BEGIN DESCRIPTION:
SLOAN CREEK 2.0
END DESCRIPTION:
XS GIS Cut Line= 3
      3556849.61     10662710.17      3556749.61     10661960.19
       3556099.6     10661460.18
#Sta/Elev= 30
  4252.4  322.11  4635.1  306.68  4673.1  305.36  4742.9   303.5  4877.9  303.95
    4888  302.97  4894.3  300.05  4918.2  303.66  4948.5  303.37  4972.5  304.68
  4978.8  298.31  4988.8  294.43    4997  294.43  4999.8  293.93    5003  294.43
  5006.5  298.51  5012.2  298.51  5016.3  304.49  5041.9  304.26  5059.7  303.82
  5211.4  303.08  5329.8  304.04  5380.9   306.6  5394.1  307.87  5408.6  307.74
  5450.6   311.8  5558.1  317.26  5657.8  324.93  5672.3  326.86  5829.1  334.71
#Mann= 9 ,-1 , 0
  4252.4     .05       0  4635.1     .12       0  4673.1     .16       0
    4997     .07       0    5003     .16       0  5041.9     .12       0
  5059.7     .16       0  5211.4     .12       0  5380.9     .05       0
Bank Sta=4997,5003
XS Rating Curve= 0 ,0
Exp/Cntr=0.3,0.1

Type RM Length L Ch R = 1 ,2364    ,710,710,710
BEGIN DESCRIPTION:
Mapping XS b55e6ac9
END DESCRIPTION:
XS GIS Cut Line= 3
      3557433.26     10662447.32      3557058.26     10661697.32
      3556329.49     10661384.99
#Sta/Elev= 30
  4038.4  320.19    4270  309.66  4526.6  303.43  4552.4  303.03  4569.1  300.38
  4672.5  300.18    4681  304.14  4703.3  308.41  4753.6  303.19  4770.4  303.68
    4776  300.69  4784.3   300.6  4798.3  303.71  4865.4  301.67  4963.2   303.9
  4973.4  303.65  4981.3  299.94  4986.8  295.13    4997  293.25  4999.8  292.75
    5003  293.25  5004.9  293.25  5010.9  298.78  5027.8  303.33  5071.3  302.18
  5134.5  303.54  5195.8  302.41  5346.2   303.6  5408.6  306.18  5669.8  324.57
#Mann= 8 ,-1 , 0
  4038.4     .05       0  4526.6     .12       0    4997     .07       0
    5003     .12       0  5010.9     .16       0  5134.5     .12       0
  5195.8     .16       0  5346.2     .05       0
Bank Sta=4997,5003
XS Rating Curve= 0 ,0
Exp/Cntr=0.3,0.1

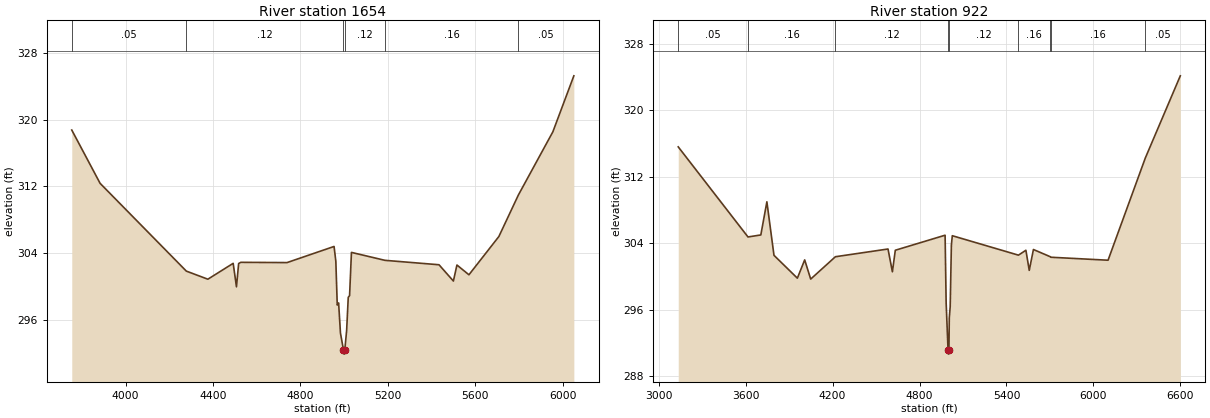
Type RM Length L Ch R = 1 ,1654    ,732,732,732
BEGIN DESCRIPTION:
Mapping XS 0e6e30d3
END DESCRIPTION:
XS GIS Cut Line= 4
      3557506.17     10662238.96      3557381.18     10661113.99
       3557209.3     10660988.99       3556297.8     10661265.04
#Sta/Elev= 30
    3754  318.74  3883.6  312.36    4278  301.85  4376.6  300.88  4492.4  302.78
  4507.4  299.97  4517.4  302.76  4527.5   302.9  4738.8  302.87  4953.9   304.8
    4962  303.03  4968.5  297.79  4974.7  298.04  4983.2  294.42    4997  292.41
  4999.8  291.91    5003  292.41  5011.5  294.77  5018.8  298.71  5024.9  298.92
  5033.4  304.09  5186.6  303.14    5434  302.61  5499.8  300.66    5516  302.58
  5570.9  301.41  5707.8  305.99  5797.1  310.96  5954.9  318.53  6050.8  325.23
#Mann= 6 ,-1 , 0
    3754     .05       0    4278     .12       0    4997     .07       0
    5003     .12       0  5186.6     .16       0  5797.1     .05       0
Bank Sta=4997,5003
XS Rating Curve= 0 ,0
Exp/Cntr=0.3,0.1

Type RM Length L Ch R = 1 ,922     ,0,0,0
BEGIN DESCRIPTION:
SLOAN CREEK 1.0
END DESCRIPTION:
XS GIS Cut Line= 4
       3557704.1      10662145.2      3557907.22      10660624.4
      3557568.68     10660358.78      3556293.64     10661149.82
#Sta/Elev= 30
  3134.8  315.59  3616.2  304.75  3704.8  304.99  3746.6  308.98  3795.6  302.54
    3957  299.79  4007.5  301.99    4049  299.68  4219.5  302.37  4582.6   303.3
  4612.8  300.56    4633  303.15  4976.6  304.96  4983.8  296.82    4997  291.15
  4999.8  290.65    5003  291.15  5005.5  295.01  5011.8  296.38  5019.9  303.76
  5026.3   304.9  5482.8  302.56  5534.2  303.15  5557.3  300.73  5586.2  303.24
  5702.6  302.37  5705.7  302.31  6101.2  301.95  6358.4  314.25  6599.9  324.14
#Mann= 9 ,-1 , 0
  3134.8     .05       0  3616.2     .16       0  4219.5     .12       0
    4997     .07       0    5003     .12       0  5482.8     .16       0
  5702.6     .12       0  5705.7     .16       0  6358.4     .05       0
Bank Sta=4997,5003
XS Rating Curve= 0 ,0
Exp/Cntr=0.3,0.1

Chan Stop Cuts=-1
Use User Specified Reach Order=0
Composite Channel Slope=5