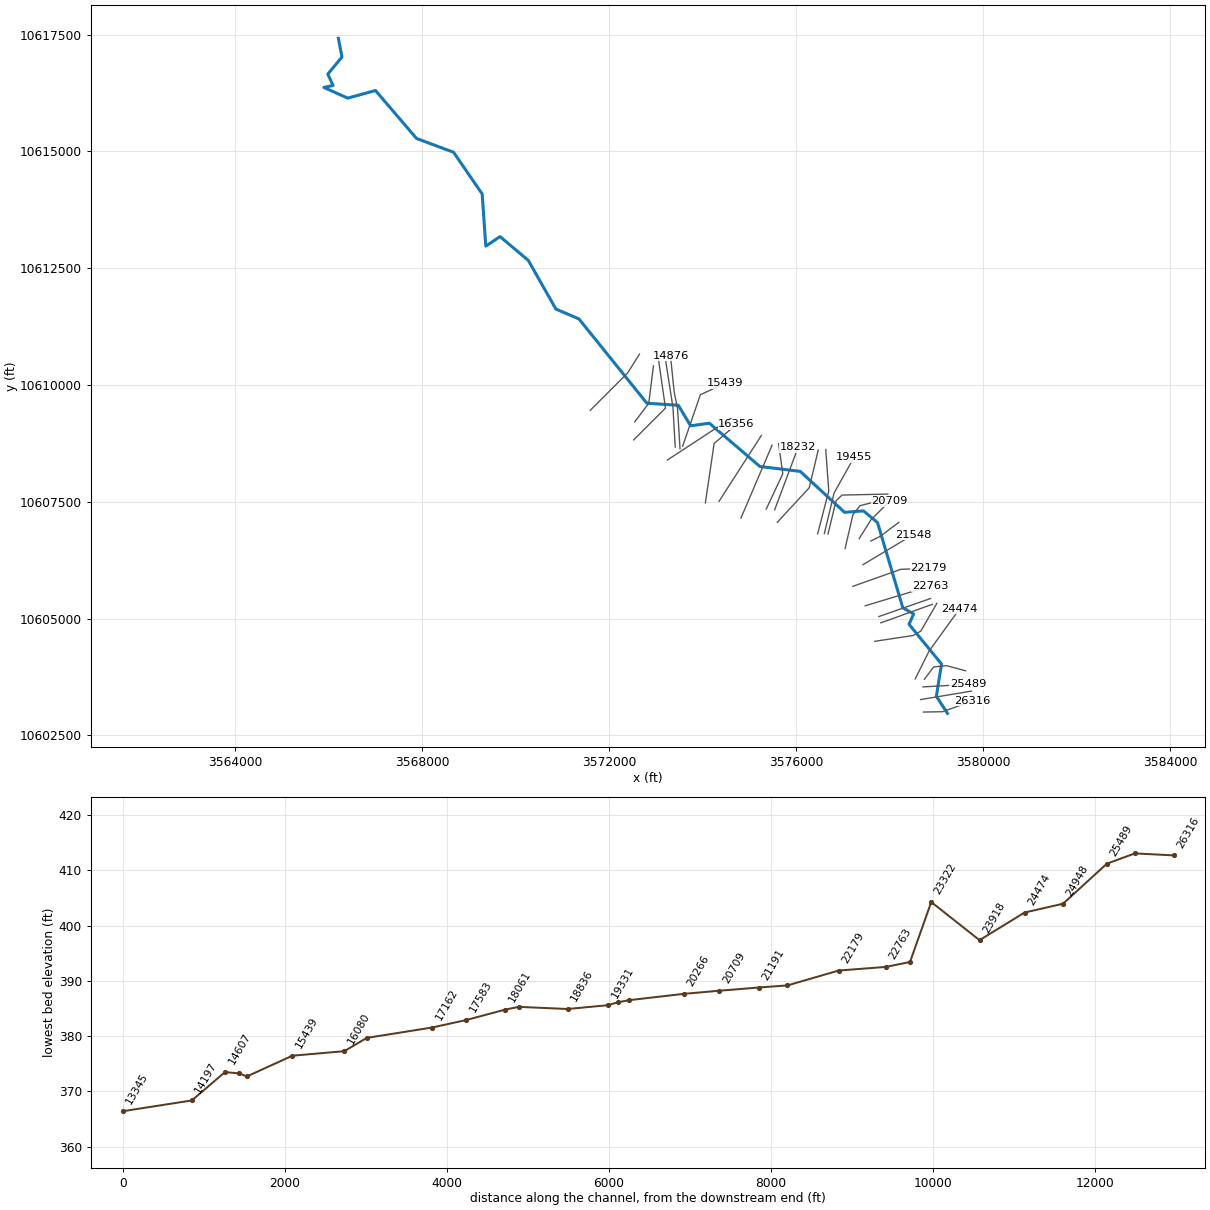
--- SNEED CREEK.prj (project) ---

Proj Title=SNEED CREEK Base Level Engineering
Current Plan=p01
Default Exp/Contr=0.3,0.1
English Units
Geom File=g01
Flow File=f01
Plan File=p01
Y Axis Title=Elevation
X Axis Title(PF)=Main Channel Distance
X Axis Title(XS)=Station
BEGIN DESCRIPTION:
SNEED CREEK
END DESCRIPTION:
DSS Export Rating Curves= 0
DSS Export Rating Curve Sorted= 0
DSS Export Volume Flow Curves= 0
DXF OffsetX= 0
DXF OffsetY= 0
DXF ScaleX= 1
DXF ScaleY= 10

--- SNEED CREEK.p01 (plan) ---

Plan Title=Multiple Run
Short Identifier=Multiple
Geom File=g01
Flow File=f01
Subcritical Flow
K Sum by GR= 0
Std Step Tol= 0.01
Critical Tol= 0.01
Num of Std Step Trials= 20
Max Error Tol= 0.3
Flow Tol Ratio= 0.001
Split Flow NTrial= 30
Split Flow Tol= 0.02
Split Flow Ratio= 0.02
Log Output Level= 0
Friction Slope Method= 1
Unsteady Friction Slope Method= 2
Unsteady Bridges Friction Slope Method= 1
Parabolic Critical Depth
Global Vel Dist=  1 , 1 , 1
Global Log Level= 0
CheckData=True
Encroach Param= -1, 0, 0, 0
BEGIN DESCRIPTION:
Multiple Run
END DESCRIPTION:

--- SNEED CREEK.f01 (steady flow) ---

Flow Title=Multiple
Program Version=4.10
Number of Profiles= 7
Profile Names=10-year,25-year,50-year,1pct_min,100-year,1pct_plu,500-year
River Rch & RM=SNEED CREEK,Reach-1         ,26316
    1923    2699    3356    3044    4117    5568    6173
River Rch & RM=SNEED CREEK,Reach-1         ,23322
    2521    3577    4477    4083    5522    7467    8373
River Rch & RM=SNEED CREEK,Reach-1         ,19455
    3270    4693    5918    5432    7346    9935   11289
River Rch & RM=SNEED CREEK,Reach-1         ,18061
    3270    4693    5918    5432    7346    9935   11289
River Rch & RM=SNEED CREEK,Reach-1         ,16080
    4215    6095    7726    7120    9629   13022   14916
River Rch & RM=SNEED CREEK,Reach-1         ,14876
    4215    6095    7726    7120    9629   13022   14916
River Rch & RM=SNEED CREEK,Reach-1         ,10969
    4438    6425    8150    7515   10164   13745   15762
River Rch & RM=SNEED CREEK,Reach-1         ,9700
    4438    6425    8150    7515   10164   13745   15762
River Rch & RM=SNEED CREEK,Reach-1         ,7420
    6362    9314   11902   11041   14932   20194   23443
River Rch & RM=SNEED CREEK,Reach-1         ,6961
    6362    9314   11902   11041   14932   20194   23443
Boundary for River Rch & Prof#=SNEED CREEK,Reach-1         , 1
Up Type= 0
Dn Type= 3
Dn Slope=0.00149
Boundary for River Rch & Prof#=SNEED CREEK,Reach-1         , 2
Up Type= 0
Dn Type= 3
Dn Slope=0.00149
Boundary for River Rch & Prof#=SNEED CREEK,Reach-1         , 3
Up Type= 0
Dn Type= 3
Dn Slope=0.00149
Boundary for River Rch & Prof#=SNEED CREEK,Reach-1         , 4
Up Type= 0
Dn Type= 3
Dn Slope=0.00149
Boundary for River Rch & Prof#=SNEED CREEK,Reach-1         , 5
Up Type= 0
Dn Type= 3
Dn Slope=0.00149
Boundary for River Rch & Prof#=SNEED CREEK,Reach-1         , 6
Up Type= 0
Dn Type= 3
Dn Slope=0.00149
Boundary for River Rch & Prof#=SNEED CREEK,Reach-1         , 7
Up Type= 0
Dn Type= 3
Dn Slope=0.00149
DSS Import GetInterval= 0
DSS Import GetPeak= 0
DSS Import FillOption= 0

--- SNEED CREEK.g01 (geometry) ---

Geom Title=Existing Conditions
Program Version=4.10

River Reach=SNEED CREEK     ,Reach-1
Reach XY= 30
      3579240.25       10602971.       3579001.5       10603336.
      3579112.25       10604028.       3578416.5       10604879.
       3578516.5       10605098.        3578284.       10605232.
      3577744.25       10607053.       3577442.5       10607306.
        3577037.       10607275.        3576090.       10608151.
      3575227.25       10608256.        3574146.       10609182.
        3573746.       10609127.      3573481.75       10609566.
      3572809.25       10609610.        3571356.       10611415.
        3570863.       10611626.        3570273.       10612667.
        3569668.       10613177.      3569363.25       10612972.
       3569286.5       10614089.      3568674.75       10614982.
        3567883.       10615277.      3567003.75       10616304.
      3566410.25       10616141.       3565899.5       10616370.
      3566097.25       10616411.       3565983.5       10616655.
      3566286.75       10617022.      3566210.25       10617421.

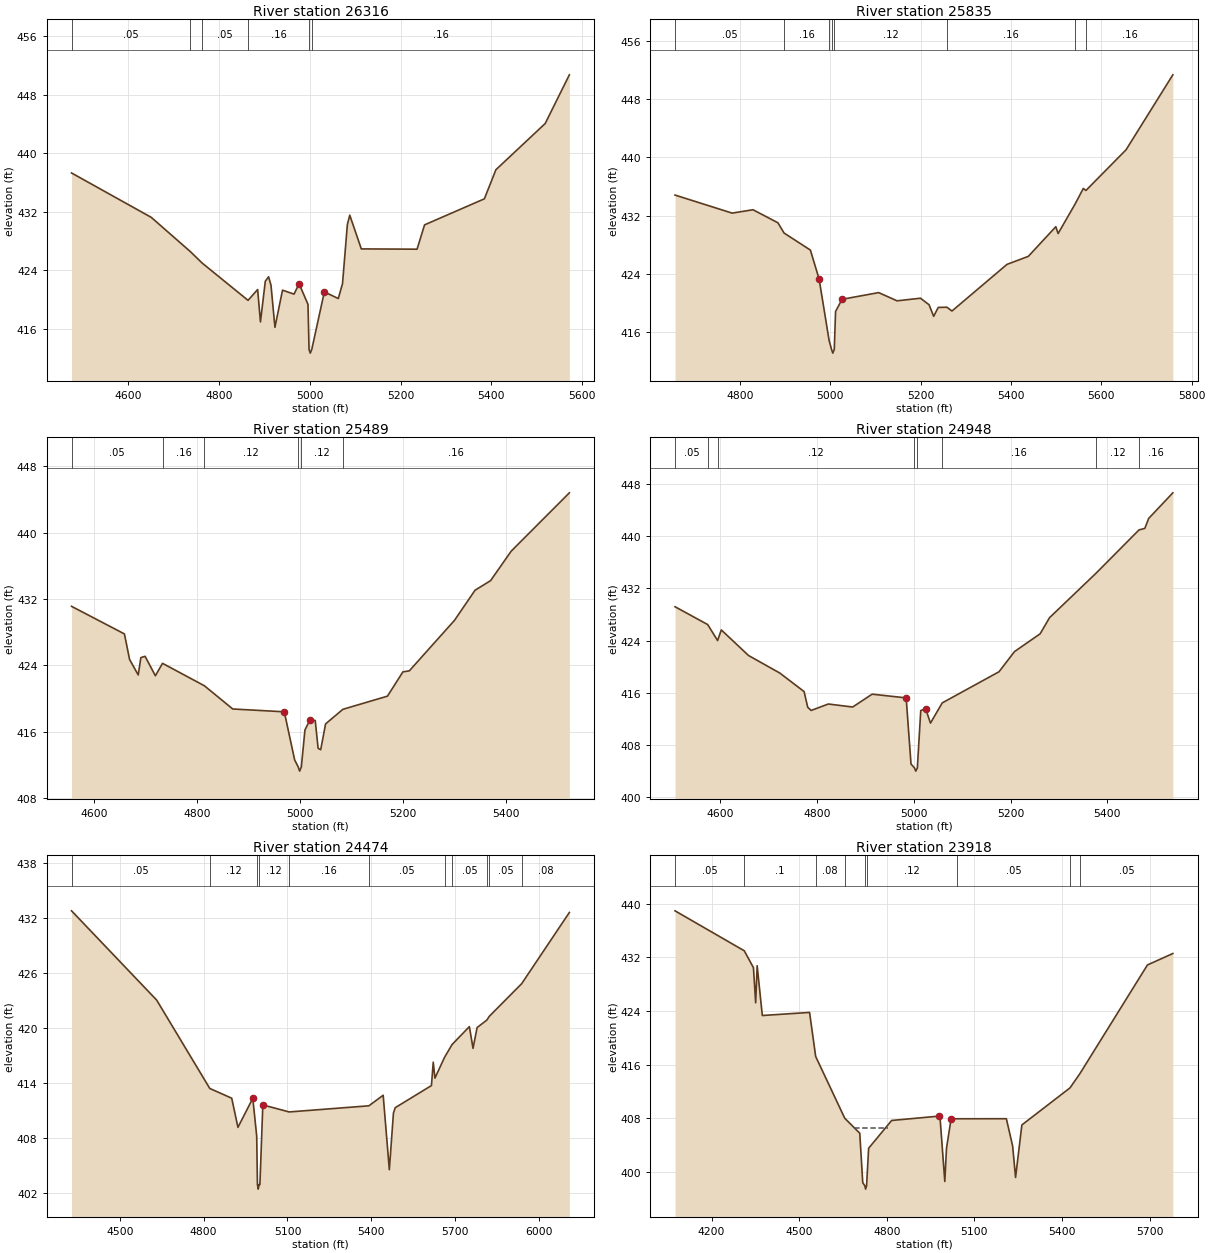
Type RM Length L Ch R = 1 ,26316   ,481,481,481
BEGIN DESCRIPTION:
SNEED CREEK 50.0
END DESCRIPTION:
XS GIS Cut Line= 3
        3578724.     10602999.45      3579133.77     10603006.39
      3579779.62     10603239.04
#Sta/Elev= 30
  4475.5   437.3  4651.1  431.24  4736.8  426.59  4763.3     425  4864.2  419.92
  4885.3   421.4  4891.5  416.98  4902.2  422.53  4909.4  423.14  4914.7     422
  4923.4  416.24  4940.1  421.31  4965.5  420.77  4976.6  422.19  4996.2  419.37
  4998.5  413.22  5001.2  412.72  5004.5  413.22  5032.2  421.07  5062.9  420.17
  5072.2  422.18  5082.9  430.26  5088.2  431.54  5113.6  426.94  5236.4   426.9
  5252.9  430.22  5384.6  433.77    5410  437.74  5518.6  444.05  5571.8  450.69
#Mann= 6 ,-1 , 0
  4475.5     .05       0  4736.8     .16       0  4763.3     .05       0
  4864.2     .16       0  4998.5     .07       0  5004.5     .16       0
Bank Sta=4976.6,5032.2
XS Rating Curve= 0 ,0
Exp/Cntr=0.3,0.1

Type RM Length L Ch R = 1 ,25835   ,346,346,346
BEGIN DESCRIPTION:
Mapping XS c5393229
END DESCRIPTION:
XS GIS Cut Line= 2
      3578664.98      10603266.8      3579751.78     10603447.36
#Sta/Elev= 30
  4656.7  434.81    4783  432.33  4829.3  432.79  4884.4     431    4898  429.59
  4956.2  427.25  4975.6  423.26  4997.6  414.85  5003.1  413.58  5005.8  413.08
  5009.1  413.58    5012   418.8  5026.3  420.48  5107.4   421.4    5148  420.27
  5199.9  420.63  5218.9  419.73  5229.1  418.14  5239.2  419.36  5258.4  419.39
  5269.6  418.87  5391.3  425.28  5438.5  426.38  5499.4  430.46  5504.5  429.52
  5541.3  433.49  5560.3  435.72    5566  435.44  5654.8  441.03  5758.4  451.34
#Mann= 8 ,-1 , 0
  4656.7     .05       0    4898     .16       0  4997.6     .12       0
  5003.1     .07       0  5009.1     .12       0  5258.4     .16       0
  5541.3     .05       0    5566     .16       0
Bank Sta=4975.6,5026.3
XS Rating Curve= 0 ,0
Exp/Cntr=0.3,0.1

Type RM Length L Ch R = 1 ,25489   ,541,541,541
BEGIN DESCRIPTION:
SNEED CREEK 49.0
END DESCRIPTION:
XS GIS Cut Line= 2
      3578717.07     10603537.64      3579682.37      10603593.2
#Sta/Elev= 30
  4556.9  431.11  4659.6  427.78  4669.6   424.7  4686.4  422.83  4691.5  424.92
  4699.7  425.08  4719.7  422.73  4733.6  424.23    4815  421.52    4870  418.72
  4970.1  418.38  4990.2  412.58  4997.2  411.72  4999.9  411.22  5003.2  411.72
  5010.2  416.18  5020.2  417.43  5030.2  417.33  5035.8  413.98  5040.8   413.8
  5050.3  416.92  5083.9  418.68  5170.5  420.27  5200.5   423.2  5212.9  423.32
  5300.7  429.42  5340.7  433.06  5370.8  434.21  5410.8  437.77  5523.8  444.81
#Mann= 6 ,-1 , 0
  4556.9     .05       0  4733.6     .16       0    4815     .12       0
  4997.2     .07       0  5003.2     .12       0  5083.9     .16       0
Bank Sta=4970.1,5020.2
XS Rating Curve= 0 ,0
Exp/Cntr=0.3,0.1

Type RM Length L Ch R = 1 ,24948   ,474,474,474
BEGIN DESCRIPTION:
SNEED CREEK 48.0
END DESCRIPTION:
XS GIS Cut Line= 4
      3578746.13     10603700.37      3578944.08     10603966.03
      3579220.12     10603992.07      3579625.51     10603882.93
#Sta/Elev= 30
  4506.8   429.2  4574.3  426.46  4594.7  424.01  4602.4  425.64  4658.7  421.71
  4723.3  419.02  4773.4  416.18  4780.9  413.77    4788  413.28  4823.4  414.27
  4873.8  413.81    4914  415.78  4984.3  415.21  4994.3  405.06  5001.4  404.47
  5004.1  403.97  5007.4  404.47  5014.4  413.26  5024.5  413.55  5034.5  411.34
  5058.8  414.44  5176.1  419.22    5208  422.31  5261.1  425.05  5280.5  427.52
  5376.5  434.34  5465.3  440.99  5477.3  441.22  5485.3  442.75  5535.2  446.68
#Mann= 8 ,-1 , 0
  4506.8     .05       0  4574.3     .16       0  4594.7     .12       0
  5001.4     .07       0  5007.4     .12       0  5058.8     .16       0
  5376.5     .12       0  5465.3     .16       0
Bank Sta=4984.3,5024.5
XS Rating Curve= 0 ,0
Exp/Cntr=0.3,0.1

Type RM Length L Ch R = 1 ,24474   ,556,556,556
BEGIN DESCRIPTION:
SNEED CREEK 47.0
END DESCRIPTION:
XS GIS Cut Line= 3
      3578549.62      10603710.2      3578849.61     10604310.19
      3579499.62      10605210.2
#Sta/Elev= 30
  4327.6  432.74  4632.2     423  4822.2  413.36  4900.6   412.3  4922.9  409.12
    4976  412.29    4990  408.17  4992.6  402.88  4995.4  402.38  4998.6  402.88
  5001.5  402.88  5011.9  411.57  5106.1   410.8  5391.3  411.47  5442.5  412.62
  5464.5   404.5  5479.2  410.67  5485.4  411.26  5615.2  413.68  5621.6  416.23
  5627.7  414.49  5661.9  416.75  5688.9  418.15  5750.9  420.11  5763.9  417.74
  5778.6  420.01  5813.4  420.82  5822.1  421.23  5937.9  424.79  6108.6  432.56
#Mann= 11 ,-1 , 0
  4327.6     .05       0  4822.2     .12       0  4992.6     .07       0
  4998.6     .12       0  5106.1     .16       0  5391.3     .05       0
  5661.9     .16       0  5688.9     .05       0  5813.4     .08       0
  5822.1     .05       0  5937.9     .08       0
Bank Sta=4976,5011.9
XS Rating Curve= 0 ,0
Exp/Cntr=0.3,0.1

Type RM Length L Ch R = 1 ,23918   ,596,596,596
BEGIN DESCRIPTION:
SNEED CREEK 46.0
END DESCRIPTION:
XS GIS Cut Line= 4
      3577684.14     10604513.34      3578507.04     10604638.34
       3578668.5     10604732.09      3579012.03     10605325.47
#Sta/Elev= 30
  4075.1  438.96  4312.2  432.99  4343.6  430.47  4351.2  425.22  4356.3  430.76
    4374  423.32  4535.8  423.78  4556.7   417.2  4656.2  407.98  4707.7  405.73
  4717.9  398.35    4725  397.88  4727.7  397.38    4731  397.88  4738.1  403.49
  4816.9  407.64  4977.4  408.28  4983.2  407.71  4998.9  398.52  5004.7  403.48
  5020.5   407.9  5040.6  407.89  5209.7   407.9  5231.2  403.82  5241.2  399.12
  5262.8  406.97  5427.7  412.51  5461.9  414.66  5692.8  430.87  5779.8  432.58
#Mann= 9 ,-1 , 0
  4075.1     .05       0  4312.2      .1       0  4556.7     .08       0
  4656.2     .12       0    4725     .07       0    4731     .12       0
  5040.6     .05       0  5427.7     .08       0  5461.9     .05       0
#XS Ineff= 2 ,-1
 4689.32 4805.91  406.58 5208.86 5267.16  407.08
Permanent Ineff=
       F       F
Bank Sta=4977.4,5020.5
XS Rating Curve= 0 ,0
Exp/Cntr=0.3,0.1

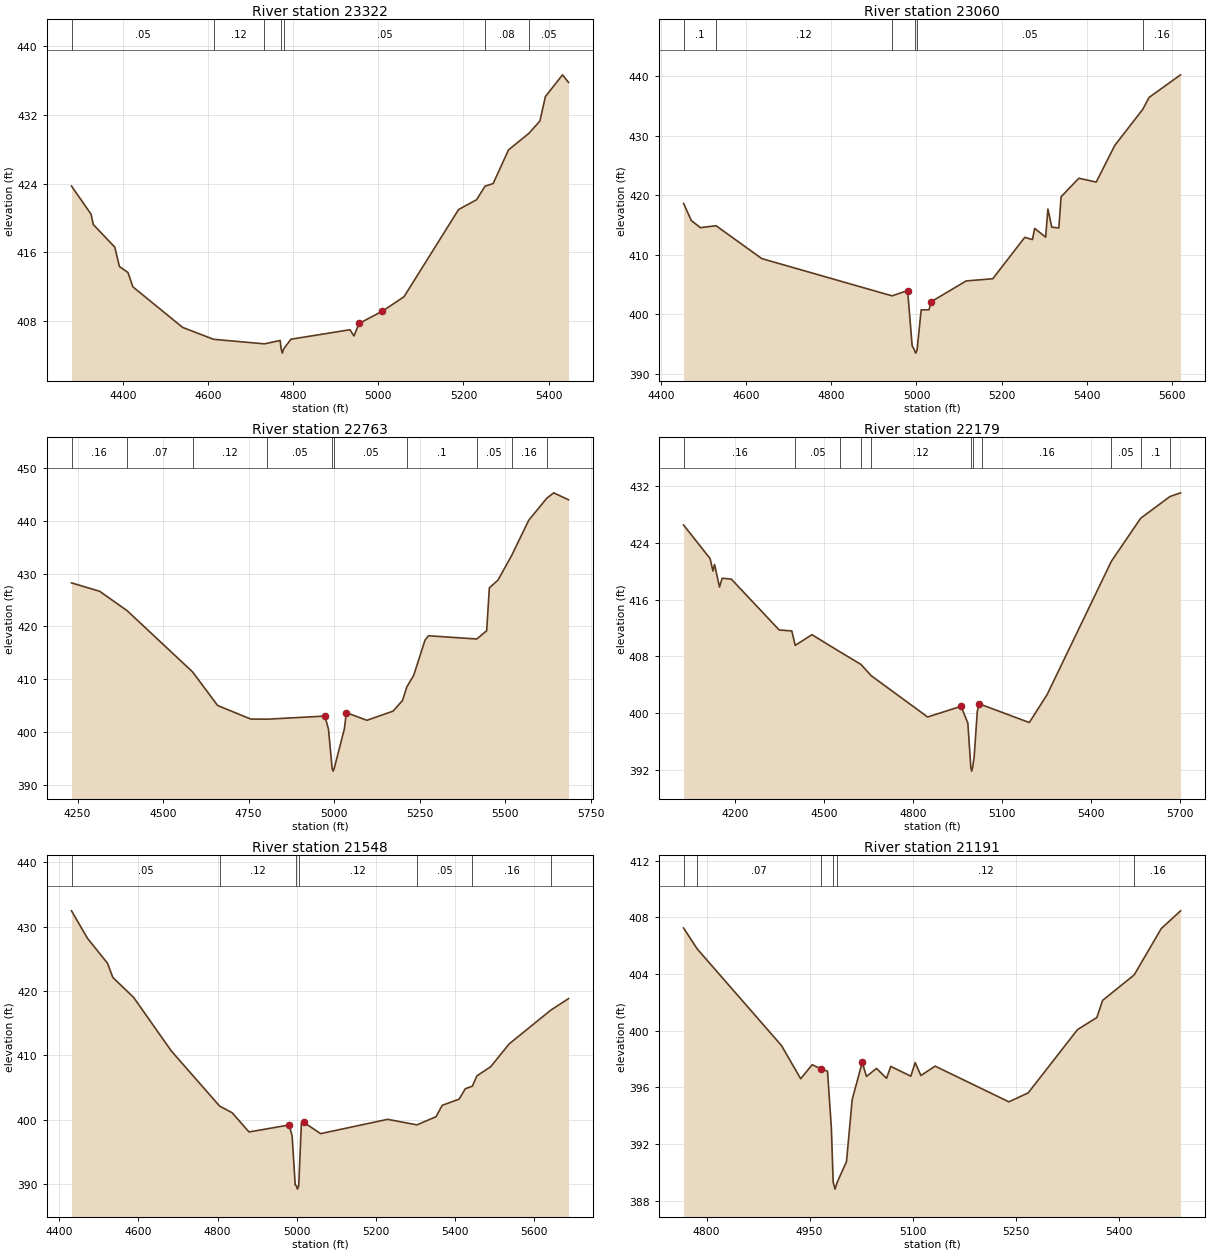
Type RM Length L Ch R = 1 ,23322   ,262,262,262
BEGIN DESCRIPTION:
SNEED CREEK 45.0
END DESCRIPTION:
XS GIS Cut Line= 2
      3577813.89     10604908.75      3578912.87     10605304.59
#Sta/Elev= 30
  4278.8  423.72  4324.7  420.45    4330  419.24  4380.5  416.61  4391.4  414.36
  4411.5  413.66  4423.1  411.99    4540  407.27  4612.6  405.89  4732.2  405.36
  4769.2  405.75  4771.5  404.78  4774.3  404.28  4777.5  404.78  4794.6   405.9
  4933.2     407  4942.8  406.28  4954.5  407.73  5009.5  409.16  5060.3  410.84
  5188.4  420.98  5230.9  422.13  5250.6   423.7  5269.8  424.01  5305.8  427.92
  5354.2  429.87  5379.7  431.29  5392.6  434.13  5432.8  436.66  5446.9  435.78
#Mann= 7 ,-1 , 0
  4278.8     .05       0  4612.6     .12       0  4732.2     .05       0
  4771.5    .035       0  4777.5     .05       0  5250.6     .08       0
  5354.2     .05       0
Bank Sta=4954.5,5009.5
XS Rating Curve= 0 ,0
Exp/Cntr=0.3,0.1

Type RM Length L Ch R = 1 ,23060   ,297,297,297
BEGIN DESCRIPTION:
SNEED CREEK 44.0
END DESCRIPTION:
XS GIS Cut Line= 2
      3577772.24     10605044.17      3578875.46     10605429.26
#Sta/Elev= 30
  4452.5  418.63  4470.9  415.73  4492.1  414.55    4529  414.87  4636.4  409.34
  4942.5  403.07  4979.3  403.96  4989.9  394.68  4995.5  393.93  4998.2  393.43
  5001.5  393.93  5011.1   400.7  5029.5  400.73  5034.8  402.09    5117  405.58
  5179.5  405.95  5254.7  412.92  5272.7  412.54    5278  414.42  5303.8  412.96
  5309.1  417.68  5318.2  414.63  5334.8   414.5  5340.1  419.74  5381.8  422.87
  5422.7  422.22  5466.5  428.41  5532.1  434.46    5547  436.47    5621  440.27
#Mann= 6 ,-1 , 0
  4452.5      .1       0    4529     .12       0  4942.5     .05       0
  4995.5    .035       0  5001.5     .05       0  5532.1     .16       0
Bank Sta=4979.3,5034.8
XS Rating Curve= 0 ,0
Exp/Cntr=0.3,0.1

Type RM Length L Ch R = 1 ,22763   ,584,584,584
BEGIN DESCRIPTION:
SNEED CREEK 43.0
END DESCRIPTION:
XS GIS Cut Line= 2
      3577480.97     10605273.75      3578870.92     10605695.42
#Sta/Elev= 30
  4232.4  428.24  4314.6  426.65  4395.2  422.96  4586.2  411.36  4659.4  404.99
  4756.4  402.41  4803.8  402.39  4972.9  402.98  4983.4  400.49  4994.1  393.04
  4996.9  392.54  5000.1  393.04    5030   400.6  5035.6  403.63  5095.8  402.18
  5172.1  403.92  5199.7  405.93  5212.4  408.51  5232.6  410.73  5265.5  417.38
    5276  418.21  5416.7   417.6  5445.7  419.16  5453.6   427.3  5478.6  428.75
  5518.9  433.46  5568.6  440.11    5621  444.27  5641.7  445.32  5684.9     444
#Mann= 10 ,-1 , 0
  4232.4     .16       0  4395.2     .07       0  4586.2     .12       0
  4803.8     .05       0  4994.1    .035       0  5000.1     .05       0
  5212.4      .1       0  5416.7     .05       0  5518.9     .16       0
    5621     .12       0
Bank Sta=4972.9,5035.6
XS Rating Curve= 0 ,0
Exp/Cntr=0.3,0.1

Type RM Length L Ch R = 1 ,22179   ,631,631,631
BEGIN DESCRIPTION:
SNEED CREEK 42.0
END DESCRIPTION:
XS GIS Cut Line= 3
      3577215.33     10605690.41      3578241.41     10606055.01
      3578829.91     10606075.84
#Sta/Elev= 30
  4025.8  426.48  4115.2  421.77  4125.1  420.01  4130.4  420.92  4147.1  417.76
    4156  418.99  4186.8  418.88  4348.7  411.72  4391.2  411.59  4402.7  409.56
  4459.2  411.06  4555.2  408.61  4624.4  406.89  4658.8  405.31  4849.6  399.49
  4962.4  400.99  4985.5  398.64  4995.6  392.38  4998.4  391.88  5001.6  392.38
  5006.7  393.83  5017.3  400.25  5024.1  401.38    5034  401.18    5193  398.71
    5253  402.63  5470.2  421.39    5569  427.43  5667.8  430.48  5703.6     431
#Mann= 11 ,-1 , 0
  4025.8     .16       0  4402.7     .05       0  4555.2     .16       0
  4624.4     .05       0  4658.8     .12       0  4995.6     .07       0
  5001.6     .12       0    5034     .16       0  5470.2     .05       0
    5569      .1       0  5667.8     .16       0
Bank Sta=4962.4,5024.1
XS Rating Curve= 0 ,0
Exp/Cntr=0.3,0.1

Type RM Length L Ch R = 1 ,21548   ,357,357,357
BEGIN DESCRIPTION:
SNEED CREEK 41.0
END DESCRIPTION:
XS GIS Cut Line= 2
      3577431.77     10606153.48      3578508.18     10606799.33
#Sta/Elev= 30
  4431.1  432.46  4471.3   428.2  4521.9  424.32  4535.5   422.1    4588     419
  4683.2  410.67  4805.1  402.11  4836.7  401.07  4879.5  398.08  4980.6  399.16
  4988.3  397.47  4996.1  389.85    4999  389.69  5001.7  389.19    5005  389.69
  5011.7  399.46  5017.5  399.58  5060.3  397.82  5229.4  400.04  5303.6  399.18
  5351.8  400.45  5367.4  402.22  5410.1  403.18  5425.7   404.8  5443.6   405.2
  5454.8  406.79  5489.8  408.22  5536.5  411.77  5641.7  417.02  5686.4  418.81
#Mann= 7 ,-1 , 0
  4431.1     .05       0  4805.1     .12       0    4999     .07       0
    5005     .12       0  5303.6     .05       0  5443.6     .16       0
  5641.7     .08       0
Bank Sta=4980.6,5017.5
XS Rating Curve= 0 ,0
Exp/Cntr=0.3,0.1

Type RM Length L Ch R = 1 ,21191   ,482,482,482
BEGIN DESCRIPTION:
SNEED CREEK 40.0
END DESCRIPTION:
XS GIS Cut Line= 3
      3577599.61     10606660.19      3577799.61     10606760.19
       3578199.6     10607060.18
#Sta/Elev= 30
  4766.5  407.24  4786.4  405.76  4909.1  398.94    4937   396.6  4953.8  397.59
  4966.4   397.3  4976.1  397.13  4981.7  393.12  4984.3  389.31  4987.1  388.81
  4990.3  389.31  5003.7  390.75    5012  395.13  5026.6  397.75  5032.8  396.76
  5047.4  397.33    5062  396.63  5068.2  397.47  5097.4  396.78  5103.7  397.74
    5112  396.83  5132.8  397.49  5240.1  394.97  5268.2   395.6  5340.1  400.07
  5368.2  400.92  5376.6  402.13  5422.6  403.93    5462   407.2  5490.1  408.45
#Mann= 6 ,-1 , 0
  4766.5     .05       0  4786.4     .07       0  4966.4     .12       0
  4984.3     .07       0  4990.3     .12       0  5422.6     .16       0
Bank Sta=4966.4,5026.6
XS Rating Curve= 0 ,0
Exp/Cntr=0.3,0.1

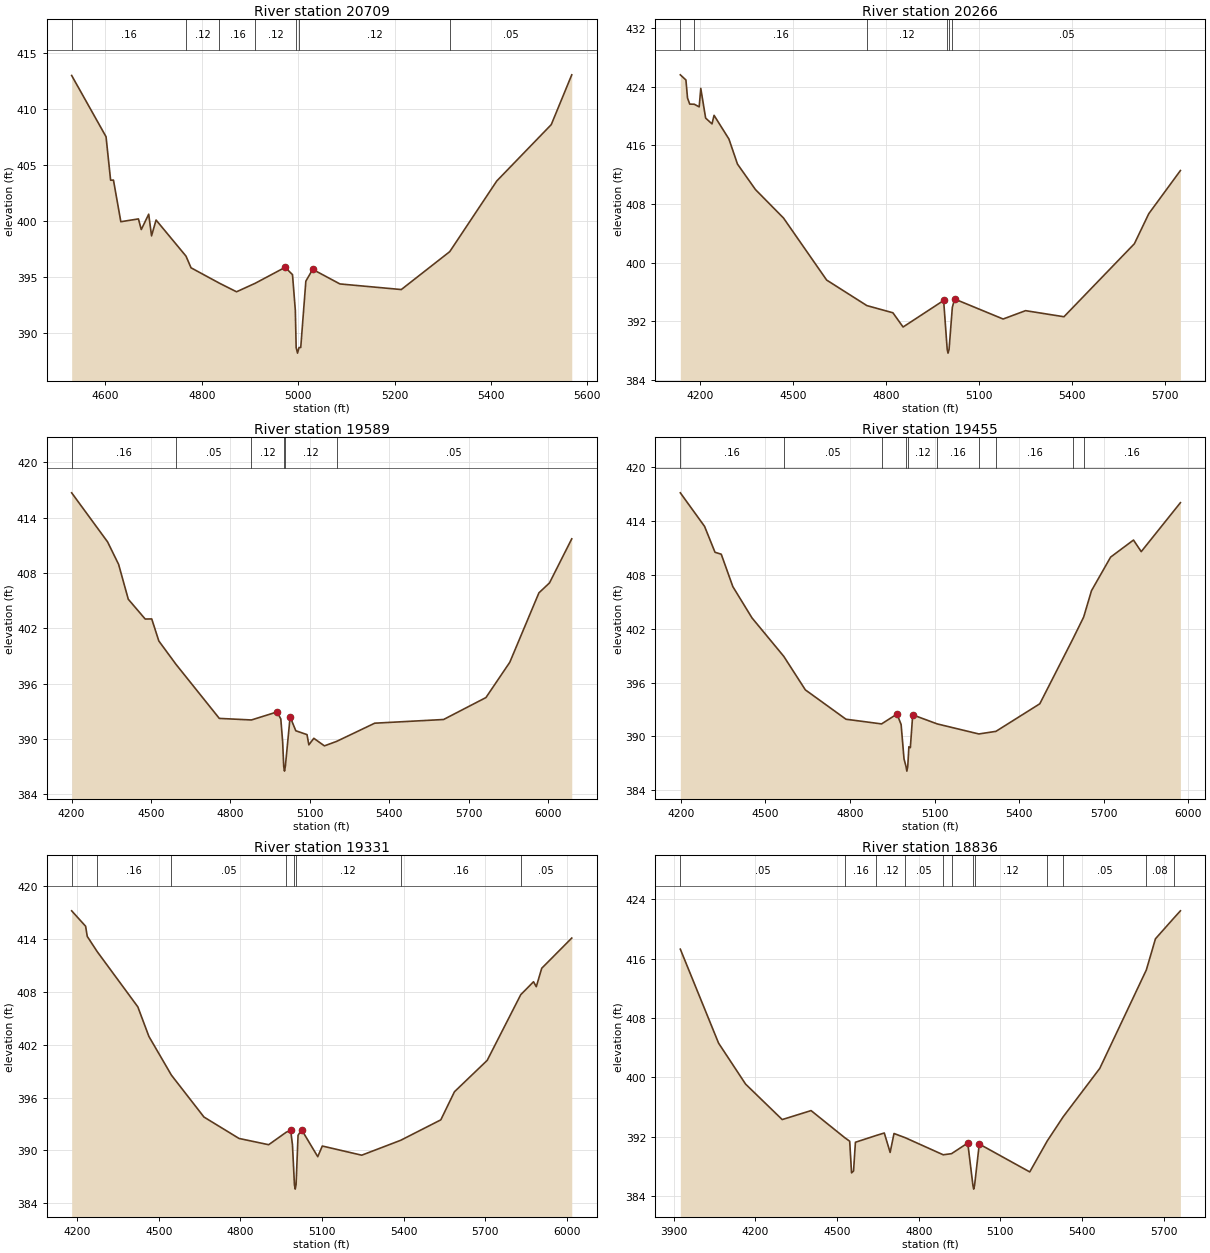
Type RM Length L Ch R = 1 ,20709   ,443,443,443
BEGIN DESCRIPTION:
SNEED CREEK 39.0
END DESCRIPTION:
XS GIS Cut Line= 3
      3577349.62     10606710.21      3577599.61     10607110.19
      3577999.63     10607510.21
#Sta/Elev= 30
  4530.2  412.99  4601.5  407.53    4611  403.65  4616.9  403.66  4632.2  399.95
  4668.7   400.2  4674.6  399.25    4690  400.62  4695.9  398.69  4705.3   400.1
  4767.4  396.88  4777.8  395.84  4836.6  394.47  4872.2   393.7  4911.4  394.47
    4973  395.88  4988.3  395.23  4994.2  392.04  4995.9  388.73  4998.7  388.23
  5001.9  388.73  5005.4  388.73    5016  394.65  5030.2   395.7  5086.7   394.4
    5214   393.9  5314.5  397.28    5412  403.58  5525.1  408.61  5567.6  413.05
#Mann= 7 ,-1 , 0
  4530.2     .16       0  4767.4     .12       0  4836.6     .16       0
  4911.4     .12       0  4995.9     .07       0  5001.9     .12       0
  5314.5     .05       0
Bank Sta=4973,5030.2
XS Rating Curve= 0 ,0
Exp/Cntr=0.3,0.1

Type RM Length L Ch R = 1 ,20266   ,677,677,677
BEGIN DESCRIPTION:
SNEED CREEK 38.0
END DESCRIPTION:
XS GIS Cut Line= 4
      3577049.85     10606500.68      3577216.53     10607222.94
      3577369.31     10607417.39      3577973.46     10607570.16
#Sta/Elev= 30
  4137.7   425.6  4155.7   424.9  4160.9  422.43    4168  421.61  4182.8  421.59
  4198.5  421.23  4203.6  423.75  4219.3   419.7  4239.8  418.91  4246.4  420.08
  4294.3  416.85  4321.9  413.43  4379.8  409.96  4470.4  406.07  4609.3  397.62
  4738.9  394.14  4822.8  393.16  4855.6  391.22  4986.3  394.84  4997.8  388.16
  5000.5  387.66  5003.8  388.16  5014.3  393.88  5021.6  395.04  5178.1  392.31
  5250.3  393.45  5374.1  392.62    5601  402.57  5647.5  406.67  5749.4  412.55
#Mann= 6 ,-1 , 0
  4137.7     .05       0  4182.8     .16       0  4738.9     .12       0
  4997.8     .07       0  5003.8     .12       0  5014.3     .05       0
Bank Sta=4986.3,5021.6
XS Rating Curve= 0 ,0
Exp/Cntr=0.3,0.1

Type RM Length L Ch R = 1 ,19589   ,134,134,134
BEGIN DESCRIPTION:
Mapping XS 8adac4fb
END DESCRIPTION:
XS GIS Cut Line= 4
      3576683.22     10606810.39      3576856.84     10607522.24
      3576982.71     10607643.77      3577963.59     10607665.47
#Sta/Elev= 30
  4200.4   416.7    4336  411.38  4377.7  408.94  4414.2  405.16  4478.1  403.01
  4502.8  403.02  4529.6  400.63  4594.3   398.1    4758  392.23  4879.3  392.06
  4976.1  392.93  4990.3  392.17  4997.2  389.73  5001.4  387.01  5004.2  386.51
  5007.4  387.01  5025.5   392.4  5046.9  390.89  5089.3  390.47  5096.3  389.36
    5115  390.07    5155  389.25  5201.4  389.74    5345  391.71  5605.1  392.11
  5765.1  394.49  5855.2  398.32  5965.2  405.85  6005.2  406.93  6089.2  411.71
#Mann= 6 ,-1 , 0
  4200.4     .16       0  4594.3     .05       0  4879.3     .12       0
  5001.4     .07       0  5007.4     .12       0  5201.4     .05       0
Bank Sta=4976.1,5025.5
XS Rating Curve= 0 ,0
Exp/Cntr=0.3,0.1

Type RM Length L Ch R = 1 ,19455   ,124,124,124
BEGIN DESCRIPTION:
SNEED CREEK 37.0
END DESCRIPTION:
XS GIS Cut Line= 3
       3576605.1     10606819.12      3576813.44     10607687.17
      3577243.06     10608455.28
#Sta/Elev= 30
  4198.7  417.13  4284.7  413.39  4321.6  410.51  4343.8  410.29  4384.9  406.68
  4452.7   403.2  4565.3  398.92    4642  395.18    4786  391.91  4912.1  391.39
  4966.9  392.49  4981.4  391.32  4991.7  387.49  4998.9  386.63  5001.7  386.13
  5004.9  386.63  5008.9  388.84  5014.1  388.74  5022.5   392.4  5109.3  391.39
  5256.9  390.27  5317.5  390.56    5473  393.63  5590.2  400.85  5628.5  403.29
  5656.3  406.23  5724.1  409.97  5805.2  411.87  5832.6  410.58  5971.5  416.03
#Mann= 10 ,-1 , 0
  4198.7     .16       0  4565.3     .05       0  4912.1     .12       0
  4998.9     .07       0  5004.9     .12       0  5109.3     .16       0
  5256.9     .12       0  5317.5     .16       0  5590.2     .12       0
  5628.5     .16       0
Bank Sta=4966.9,5022.5
XS Rating Curve= 0 ,0
Exp/Cntr=0.3,0.1

Type RM Length L Ch R = 1 ,19331   ,495,495,495
BEGIN DESCRIPTION:
SNEED CREEK 36.0
END DESCRIPTION:
XS GIS Cut Line= 3
      3576461.87     10606814.76      3576700.59     10607730.57
      3576635.49     10608620.28
#Sta/Elev= 30
  4179.8  417.19  4231.1  415.44  4237.1  414.29    4273  412.59  4423.1  406.29
  4463.7  402.94  4546.6  398.54  4666.2  393.79  4795.1  391.36    4904  390.65
  4968.8  392.07  4984.9  392.27  4991.5  390.66  4998.8  386.11  5001.6  385.61
  5004.8  386.11  5012.1  391.72  5025.4  392.34  5084.5  389.29  5101.2   390.5
  5246.2  389.46  5389.3  391.15  5536.9  393.47  5587.1  396.66  5707.4  400.22
  5830.9  407.68  5877.8  409.14  5887.9  408.58  5907.9  410.67  6018.3   414.1
#Mann= 8 ,-1 , 0
  4179.8     .05       0    4273     .16       0  4546.6     .05       0
  4968.8     .12       0  4998.8     .07       0  5004.8     .12       0
  5389.3     .16       0  5830.9     .05       0
Bank Sta=4984.9,5025.4
XS Rating Curve= 0 ,0
Exp/Cntr=0.3,0.1

Type RM Length L Ch R = 1 ,18836   ,604,604,604
BEGIN DESCRIPTION:
SNEED CREEK 35.0
END DESCRIPTION:
XS GIS Cut Line= 3
      3575599.93     10607061.38      3576282.24     10607800.98
      3576474.94     10608608.24
#Sta/Elev= 30
  3924.7  417.28  4065.1  404.61  4164.4  399.08  4298.8   394.3  4404.8  395.51
  4528.7  391.85  4546.6  391.38  4553.4  387.11  4560.7  387.36  4567.6  391.24
  4643.5  392.15  4673.6  392.49  4695.1  389.87  4709.3  392.42  4750.1  391.86
    4890  389.55  4920.4   389.7 4980.11  391.14  4999.1  385.42  5001.9  384.92
  5005.1  385.42  5022.4     391  5207.7  387.24  5271.8  391.41  5330.4  394.67
  5464.8   401.2  5635.7  414.47  5669.3  418.68  5737.5   421.5  5760.9  422.45
#Mann= 12 ,-1 , 0
  3924.7     .05       0  4528.7     .16       0  4643.5     .12       0
  4750.1     .05       0    4890     .16       0  4920.4     .12       0
  4999.1     .07       0  5005.1     .12       0  5271.8     .16       0
  5330.4     .05       0  5635.7     .08       0  5737.5      .1       0
#XS Ineff= 1 ,-1
 4490.06 4740.06  391.83
Permanent Ineff=
       F
Bank Sta=4980.11,5022.4
XS Rating Curve= 0 ,0
Exp/Cntr=0.3,0.1

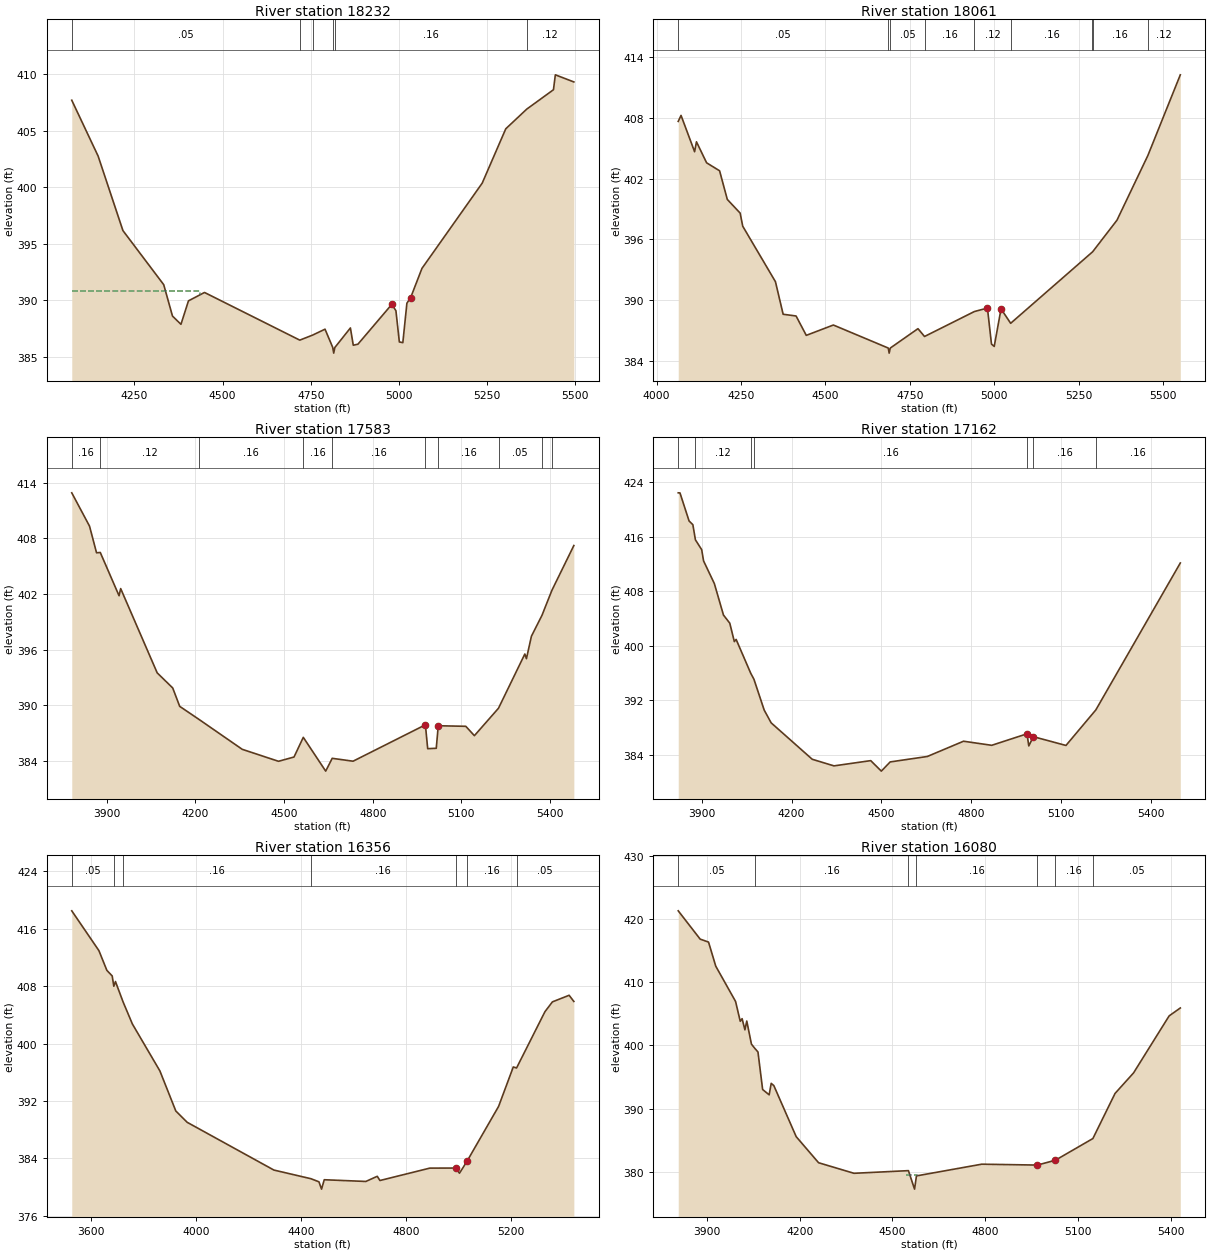
Type RM Length L Ch R = 1 ,18232   ,171,171,171
BEGIN DESCRIPTION:
SNEED CREEK 34.0
END DESCRIPTION:
XS GIS Cut Line= 2
      3575543.32     10607330.22      3576043.32     10608663.55
#Sta/Elev= 30
  4072.3   407.7    4147  402.76  4217.4  396.16  4333.1  391.37    4358  388.59
    4382  387.86  4403.3  389.94  4448.8  390.68    4719  386.46  4755.7  386.91
  4790.6  387.43  4812.5  385.81  4815.2  385.31  4818.5  385.81  4862.6  387.54
  4870.7  386.01  4883.9   386.1  4980.1  389.63  4991.7  389.06  5001.4   386.3
  5011.3  386.24  5022.8  389.73  5033.5  390.23  5065.5  392.81  5236.4  400.36
  5303.2  405.17  5362.6  406.91  5438.5  408.63  5443.8  409.95  5496.3  409.32
#Mann= 6 ,-1 , 0
  4072.3     .05       0    4719     .12       0  4755.7     .16       0
  4812.5     .07       0  4818.5     .16       0  5362.6     .12       0
#XS Ineff= 2 , 0
         4435.45  390.85
Permanent Ineff=
       F       F
Bank Sta=4980.1,5033.5
XS Rating Curve= 0 ,0
Exp/Cntr=0.3,0.1

Type RM Length L Ch R = 1 ,18061   ,478,478,478
BEGIN DESCRIPTION:
SNEED CREEK 33.0
END DESCRIPTION:
XS GIS Cut Line= 3
      3575362.76     10607344.11      3575716.92     10608101.04
      3575626.77     10608745.98
#Sta/Elev= 30
  4064.3  407.64  4072.6  408.23  4112.8  404.65  4118.3  405.63  4148.3  403.56
  4186.8  402.77  4209.6  399.95  4247.7   398.6  4255.3  397.31  4352.2  391.84
    4375  388.63  4413.3  388.46  4443.5  386.55  4523.7  387.57  4686.3   385.3
    4689   384.8  4692.3   385.3  4774.3  387.21  4793.7  386.44  4941.4   388.9
    4980  389.24    4992  385.69  5000.1  385.46  5020.3  389.16  5048.8  387.74
  5290.2  394.75  5291.8   394.8  5363.6   397.9  5455.3  404.29  5551.2  412.23
#Mann= 9 ,-1 , 0
  4064.3     .05       0  4686.3     .07       0  4692.3     .05       0
  4793.7     .16       0  4941.4     .12       0  5048.8     .16       0
  5290.2     .05       0  5291.8     .16       0  5455.3     .12       0
Bank Sta=4980,5020.3
XS Rating Curve= 0 ,0
Exp/Cntr=0.3,0.1

Type RM Length L Ch R = 1 ,17583   ,421,421,421
BEGIN DESCRIPTION:
SNEED CREEK 32.0
END DESCRIPTION:
XS GIS Cut Line= 2
       3574821.1     10607149.67      3575487.77     10608712.19
#Sta/Elev= 30
  3781.7  412.91  3841.8  409.32  3865.5  406.45  3878.2  406.48  3941.7  401.82
  3947.2  402.59  4070.7  393.51  4123.3  391.88  4146.9   389.9    4211  388.52
  4358.5  385.27  4481.1  383.98  4533.7  384.44  4565.1  386.56  4640.9  382.92
  4662.9   384.3  4733.5  383.99  4978.2  387.91    4986  385.34    5015  385.38
  5021.7  387.81  5114.9  387.75    5144  386.74  5225.6   389.7  5314.7  395.54
  5320.1  395.04    5337  397.46  5372.7  399.71  5406.2   402.4  5480.5  407.23
#Mann= 10 ,-1 , 0
  3781.7     .16       0  3878.2     .12       0    4211     .16       0
  4565.1     .16       0  4662.9     .16       0  4978.2     .16       0
  5021.7     .16       0  5225.6     .05       0  5372.7     .16       0
  5406.2     .12       0
Bank Sta=4978.2,5021.7
XS Rating Curve= 0 ,0
Exp/Cntr=0.3,0.1

Type RM Length L Ch R = 1 ,17162   ,806,806,806
BEGIN DESCRIPTION:
SNEED CREEK 31.0
END DESCRIPTION:
XS GIS Cut Line= 2
      3574352.34     10607509.02      3575258.56     10608920.44
#Sta/Elev= 30
  3821.4  422.43  3827.2  422.42  3857.6   418.3  3870.3  417.75  3878.8  415.53
  3899.8  414.08    3906  412.44  3942.1   409.1  3972.5  404.49  3993.6  403.29
  4008.8  400.59  4014.8  400.91  4063.5  395.95  4074.3  395.06  4108.6  390.53
  4131.8  388.66  4269.1  383.31  4341.8  382.34  4464.5  383.11  4499.9  381.57
  4529.4  382.92  4653.6  383.72  4774.5  385.96  4868.6  385.36  4986.6  387.05
  4992.5  385.27  5007.7  386.63  5116.7  385.34  5216.4  390.55  5498.7  412.13
#Mann= 7 ,-1 , 0
  3821.4     .16       0  3878.8     .12       0  4063.5     .16       0
  4074.3     .16       0  4986.6     .16       0  5007.7     .16       0
  5216.4     .16       0
Bank Sta=4986.6,5007.7
XS Rating Curve= 0 ,0
Exp/Cntr=0.3,0.1

Type RM Length L Ch R = 1 ,16356   ,276,276,276
BEGIN DESCRIPTION:
SNEED CREEK 30.0
END DESCRIPTION:
XS GIS Cut Line= 3
      3574060.67     10607477.76      3574248.17      10608748.6
      3574725.98      10609158.9
#Sta/Elev= 30
  3526.7  418.51  3630.2  412.96  3660.6   410.2  3680.8  409.43  3687.1  407.99
  3693.3  408.65  3722.4   405.8  3757.9  402.72  3862.7  396.18  3923.4  390.59
  3966.8  389.01  4297.4  382.35  4438.9  381.14  4469.2  380.71  4479.1  379.69
  4489.4     381    4648  380.76  4691.6  381.48  4701.7  380.89  4891.9  382.62
  4990.7  382.63    5005  381.91  5033.5  383.56  5154.2  391.23  5210.2  396.73
  5222.7  396.59  5330.9  404.44  5359.4  405.81  5423.1  406.73  5441.1  405.87
#Mann= 7 ,-1 , 0
  3526.7     .05       0  3687.1     .16       0  3722.4     .16       0
  4438.9     .16       0  4990.7     .16       0  5033.5     .16       0
  5222.7     .05       0
Bank Sta=4990.7,5033.5
XS Rating Curve= 0 ,0
Exp/Cntr=0.3,0.1

Type RM Length L Ch R = 1 ,16080   ,641,641,641
BEGIN DESCRIPTION:
SNEED CREEK 29.0
END DESCRIPTION:
XS GIS Cut Line= 2
      3573248.17     10608394.44      3574606.08      10609284.1
#Sta/Elev= 30
  3807.4  421.26  3878.3  416.79  3905.4  416.32  3928.7  412.52  3992.8  406.94
  4007.9  403.81  4013.9  404.22    4023  402.46    4029  403.85  4044.1   400.2
  4054.5  399.56  4065.2  398.96  4080.3  393.03  4101.4  392.19    4108     394
  4116.5  393.65  4188.8  385.58  4261.2  381.46  4375.7  379.79  4551.7  380.21
  4571.5  377.29  4577.7  379.38  4788.8  381.23  4968.8  381.09    5027  381.86
  5148.1  385.28  5219.8  392.41  5279.6  395.65  5394.7  404.66  5430.8  405.91
#Mann= 7 ,-1 , 0
  3807.4     .05       0  4054.5     .16       0  4551.7     .16       0
  4577.7     .16       0  4968.8     .16       0    5027     .16       0
  5148.1     .05       0
#XS Ineff= 1 ,-1
  4542.5 4579.32  379.54
Permanent Ineff=
       F
Bank Sta=4968.8,5027
XS Rating Curve= 0 ,0
Exp/Cntr=0.3,0.1

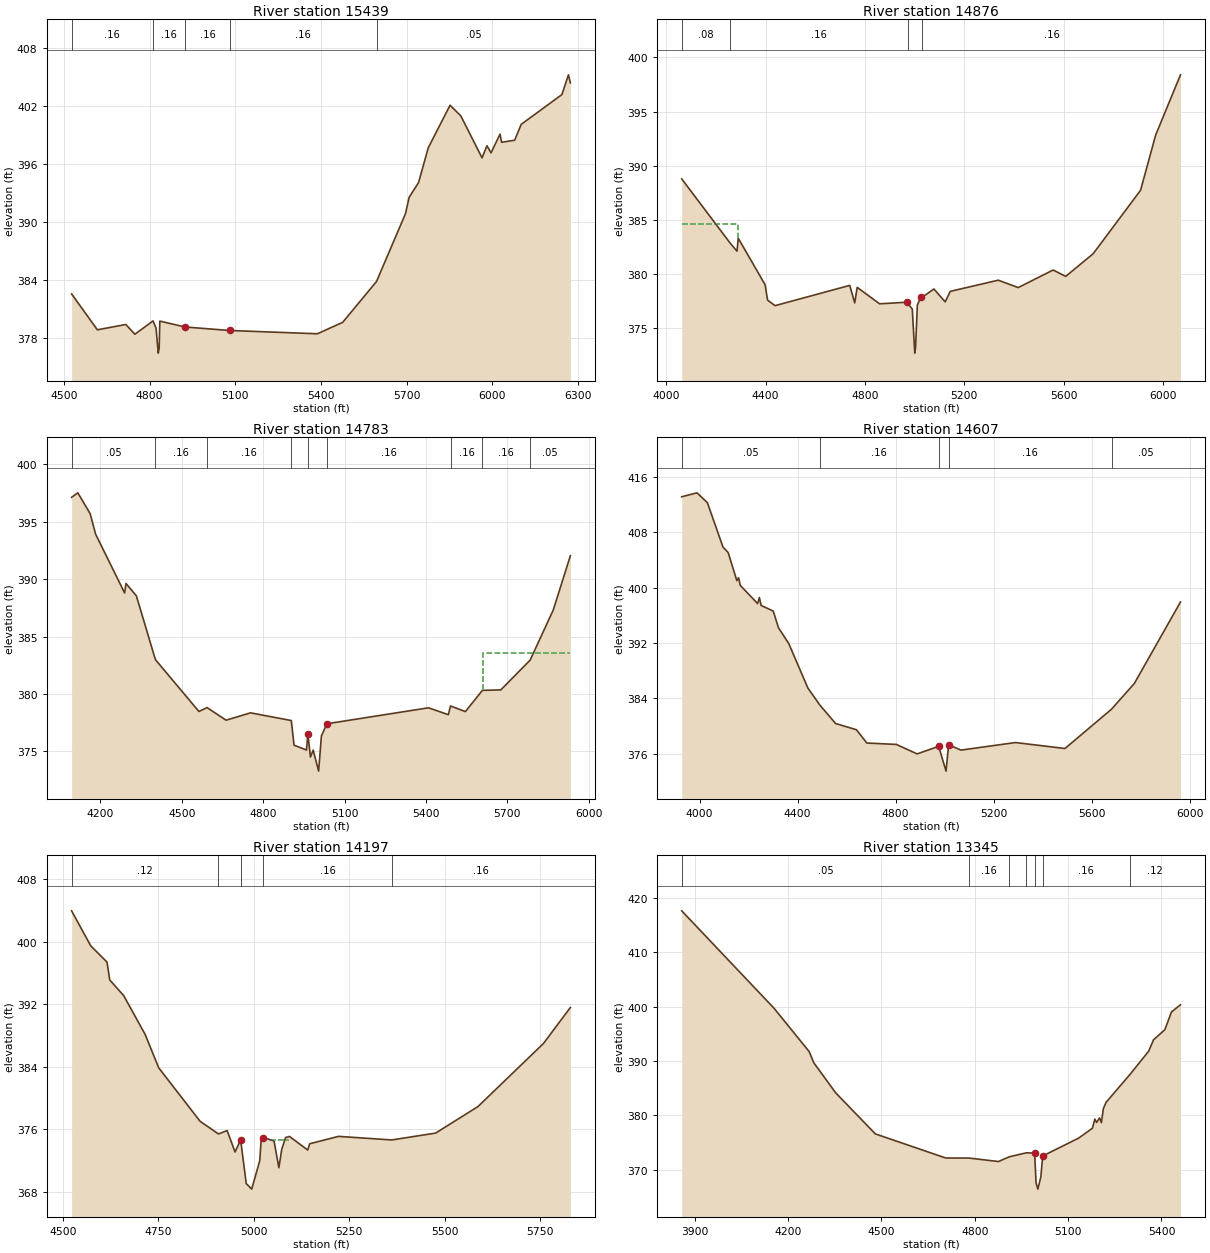
Type RM Length L Ch R = 1 ,15439   ,563,563,563
BEGIN DESCRIPTION:
SNEED CREEK 24.0
END DESCRIPTION:
XS GIS Cut Line= 3
        3573575.     10608690.61      3573953.47     10609791.28
      3574481.21     10610037.79
#Sta/Elev= 30
    4527  382.59  4617.2  378.88  4716.9  379.43  4748.6  378.42  4812.1   379.8
  4822.6  379.06  4830.4  376.47  4833.6  376.97  4835.9  379.78  4924.3  379.17
  5080.5  378.81  5387.6  378.47  5476.1  379.65  5594.6  383.87  5696.2  390.89
  5708.7  392.56  5741.9   394.1  5775.8  397.69  5852.2  402.09    5890  400.98
  5964.1  396.65  5981.4   397.9  5995.7  397.17  6027.1   399.1  6032.6  398.26
  6078.3  398.47  6101.2  400.11  6243.8  403.19  6266.7  405.23  6273.4   404.4
#Mann= 5 ,-1 , 0
    4527     .16       0  4812.1     .16       0  4924.3     .16       0
  5080.5     .16       0  5594.6     .05       0
Bank Sta=4924.3,5080.5
XS Rating Curve= 0 ,0
Exp/Cntr=0.3,0.1

Type RM Length L Ch R = 1 ,14876   ,93,93,93
BEGIN DESCRIPTION:
SNEED CREEK 28.0
END DESCRIPTION:
XS GIS Cut Line= 4
      3573518.34     10608635.14      3573466.26     10609485.84
      3573392.47     10609859.11      3573313.77     10610629.92
#Sta/Elev= 30
  4062.4  388.79  4257.8  382.85    4285  382.12    4290  383.31  4398.1  379.02
  4408.1   377.6  4438.2  377.09  4738.7  378.96  4758.8  377.35  4768.8  378.78
  4858.9  377.26  4969.9  377.41    4975  377.21  4990.5  376.78  5000.4  372.71
  5003.7  373.21  5010.9  377.15  5026.2  377.93  5031.3  377.88  5077.5  378.63
    5123  377.44  5143.4  378.41  5336.5  379.44  5416.9  378.76  5557.6  380.38
  5607.9  379.79  5718.5  381.88  5909.4  387.74  5969.8  392.81    6070  398.39
#Mann= 4 ,-1 , 0
  4062.4     .08       0  4257.8     .16       0    4975     .16       0
  5031.3     .16       0
#XS Ineff= 2 , 0
         4289.77  384.64
Permanent Ineff=
       F       F
Bank Sta=4969.9,5026.2
XS Rating Curve= 0 ,0
Exp/Cntr=0.3,0.1

Type RM Length L Ch R = 1 ,14783   ,176,176,176
BEGIN DESCRIPTION:
SNEED CREEK 27.0
END DESCRIPTION:
XS GIS Cut Line= 3
      3573415.91     10608671.89       3573367.3     10609519.12
       3573214.8     10610496.48
#Sta/Elev= 30
  4094.2  397.14  4117.2  397.53  4162.6  395.71  4182.6  393.93  4289.6   388.8
  4294.6  389.63  4332.9  388.55    4403  382.99  4563.3  378.47  4593.3  378.81
  4663.4  377.71  4753.6  378.35  4903.8  377.68  4913.8  375.53  4959.7  375.11
  4964.7  376.52  4974.3   374.5  4984.4   375.1  5004.4  373.27  5014.7  376.34
    5035   377.4  5409.4  378.79  5482.3  378.19  5490.4  378.95  5545.1  378.46
  5607.9  380.31  5675.7  380.35  5783.9  382.95  5869.2  387.33    5932  392.05
#Mann= 9 ,-1 , 0
  4094.2     .05       0    4403     .16       0  4593.3     .16       0
  4903.8     .16       0  4964.7     .16       0    5035     .16       0
  5490.4     .16       0  5607.9     .16       0  5783.9     .05       0
#XS Ineff= 2 , 0
                         5609.09          383.55
Permanent Ineff=
       F       F
Bank Sta=4964.7,5035
XS Rating Curve= 0 ,0
Exp/Cntr=0.3,0.1

Type RM Length L Ch R = 1 ,14607   ,410,410,410
BEGIN DESCRIPTION:
SNEED CREEK 26.0
END DESCRIPTION:
XS GIS Cut Line= 3
      3572527.05     10608824.71      3573207.58     10609505.23
      3573054.97     10610566.51
#Sta/Elev= 30
  3927.3  413.15  3989.6  413.72    4032   412.3  4095.6  405.89  4116.8  405.09
  4152.2  401.03  4159.3  401.45  4166.3  400.34    4237  397.71  4244.1  398.59
  4251.2  397.45  4300.7  396.63  4321.9  394.23  4364.3  391.91  4442.1   385.5
  4491.6  383.01  4555.2  380.38  4640.1  379.48  4682.5  377.56  4802.7  377.36
  4887.6  375.99  4975.5  377.08  5005.6   373.5    5016  377.31  5066.5  376.54
  5288.7  377.63  5490.8  376.77  5680.6  382.45  5773.7  386.17  5961.9  397.94
#Mann= 5 ,-1 , 0
  3927.3     .05       0  4491.6     .16       0  4975.5     .16       0
    5016     .16       0  5680.6     .05       0
Bank Sta=4975.5,5016
XS Rating Curve= 0 ,0
Exp/Cntr=0.3,0.1

Type RM Length L Ch R = 1 ,14197   ,852,852,852
BEGIN DESCRIPTION:
SNEED CREEK 25.0
END DESCRIPTION:
XS GIS Cut Line= 3
       3572549.6     10609210.18      3572849.61     10609610.19
       3572949.6     10610410.15
#Sta/Elev= 30
  4522.8  403.97  4572.8   399.5  4615.5  397.41  4622.8  395.12  4659.3  393.12
  4715.5  388.15  4750.9  383.89  4859.3  377.05  4907.3  375.43  4930.1  375.86
  4950.9  373.12  4965.5  374.68  4980.1  369.09  4994.4  368.37  5015.5     372
  5019.7  374.97  5025.3  374.97    5053  374.53  5065.6  371.11  5073.2  373.48
  5083.3  374.97  5093.4  375.11  5141.2  373.37  5146.3  374.17  5221.9  375.12
    5361  374.66  5476.3  375.54  5587.2  378.94  5758.5     387    5829   391.6
#Mann= 5 ,-1 , 0
  4522.8     .12       0  4907.3     .16       0  4965.5     .16       0
  5025.3     .16       0    5361     .16       0
#XS Ineff= 1 ,-1
 5042.73 5092.73374.7091
Permanent Ineff=
       F
Bank Sta=4965.5,5025.3
XS Rating Curve= 0 ,0
Exp/Cntr=0.3,0.1

Type RM Length L Ch R = 1 ,13345   ,457,457,457
BEGIN DESCRIPTION:
SNEED CREEK 23.0
END DESCRIPTION:
XS GIS Cut Line= 3
      3571599.61     10609460.19      3572399.61     10610260.19
      3572649.62     10610660.21
#Sta/Elev= 30
    3858  417.65    4155   399.7  4268.1  391.71  4282.3   389.7    4353  384.14
  4480.3  376.59  4706.5  372.15  4781.3  372.14  4876.2   371.5  4910.3  372.36
    4966  373.11  4992.3  373.04    4997  367.57  5002.7  366.42  5012.4  368.69
  5018.3  372.52  5133.8  375.81  5178.1  377.63  5185.7  379.31  5191.6  378.69
    5201  379.54  5206.9  378.65  5213.4  381.27  5222.3  382.42  5297.9  387.47
  5359.1  391.83  5374.4   393.9    5411  395.78  5432.2  399.04  5461.1  400.35
#Mann= 7 ,-1 , 0
    3858     .05       0  4781.3     .16       0  4910.3     .16       0
    4966     .16       0  4992.3     .16       0  5018.3     .16       0
  5297.9     .12       0
Bank Sta=4992.3,5018.3
XS Rating Curve= 0 ,0
Exp/Cntr=0.3,0.1