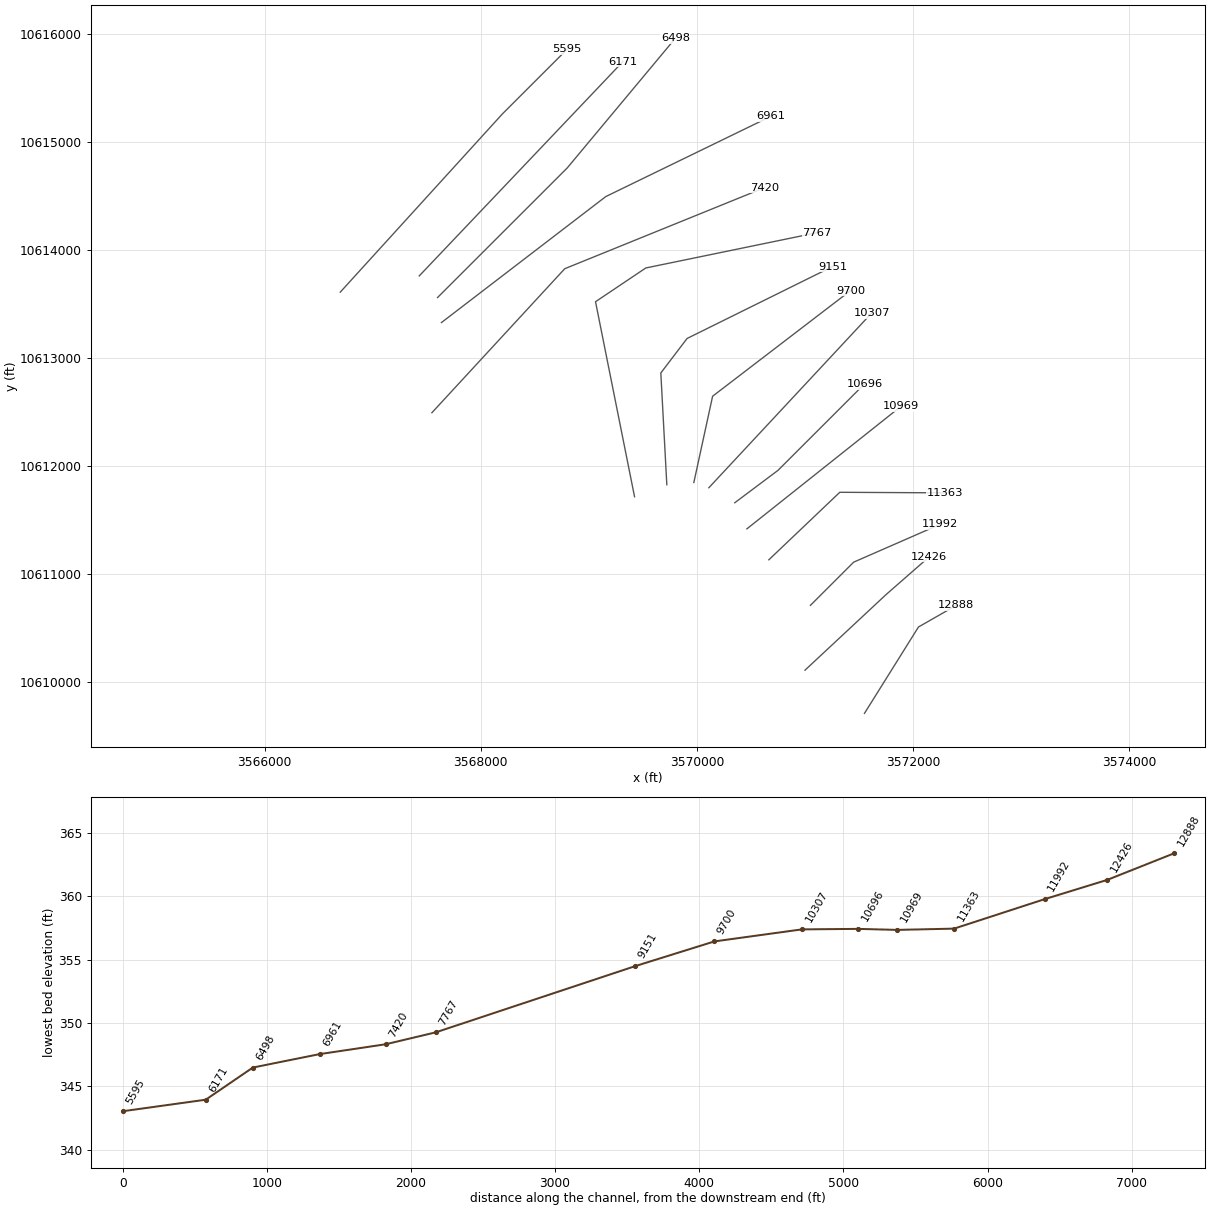
HEC-RAS study SNEED CREEK.prj: SNEED CREEK Base Level Engineering

--- SNEED CREEK.g01 (geometry) --- (continued)

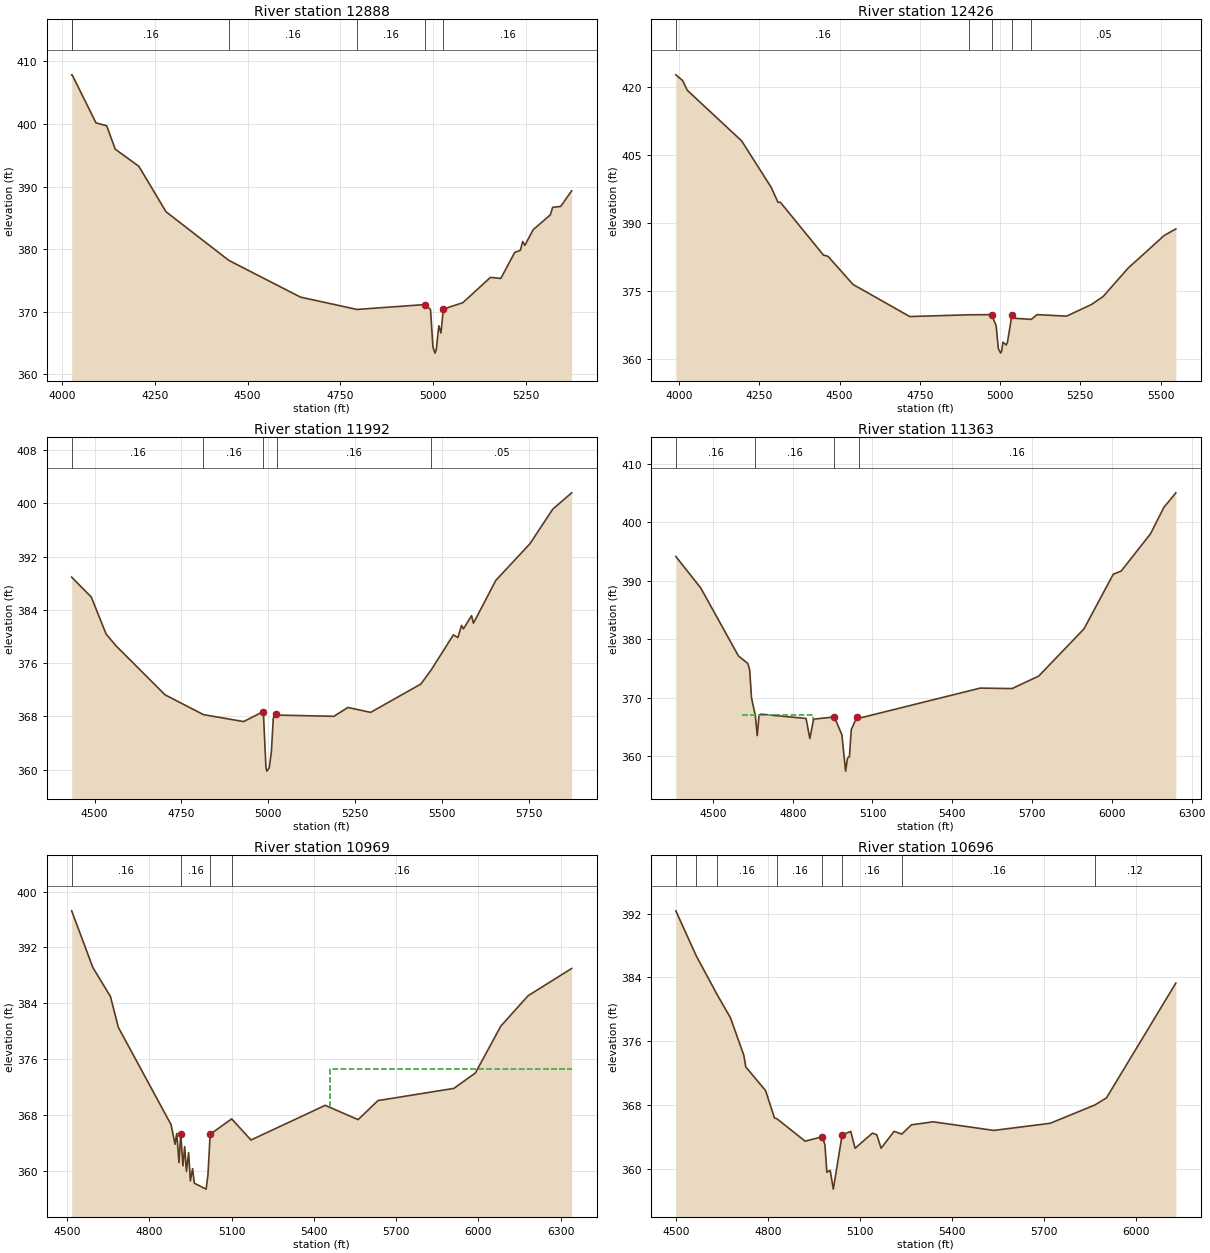
Type RM Length L Ch R = 1 ,12888   ,462,462,462
BEGIN DESCRIPTION:
SNEED CREEK 22.0
END DESCRIPTION:
XS GIS Cut Line= 3
      3571549.61     10609710.19      3572049.61     10610510.19
       3572399.6     10610710.18
#Sta/Elev= 30
  4026.1  407.86  4027.5  407.86  4091.6  400.18  4120.4  399.72  4143.4  395.98
  4207.1  393.24  4280.2  385.98  4449.3  378.21  4642.3  372.34  4794.4  370.37
  4977.4  371.15  4992.5  370.36    4999  364.38  5004.5  363.39  5007.8  363.89
  5014.9  367.77  5020.6  366.61  5027.1  370.43  5079.6  371.45  5153.8  375.49
  5181.9  375.33  5219.3  379.48  5234.4  379.81  5240.9  381.22  5246.6  380.61
    5269  383.12    5315  385.47  5321.5  386.69  5343.1  386.83  5372.6  389.33
#Mann= 6 ,-1 , 0
  4026.1     .05       0  4027.5     .16       0  4449.3     .16       0
  4794.4     .16       0  4977.4     .16       0  5027.1     .16       0
Bank Sta=4977.4,5027.1
XS Rating Curve= 0 ,0
Exp/Cntr=0.3,0.1

Type RM Length L Ch R = 1 ,12426   ,434,434,434
BEGIN DESCRIPTION:
SNEED CREEK 21.0
END DESCRIPTION:
XS GIS Cut Line= 3
      3570999.64     10610110.21      3571749.61     10610810.19
      3572149.62      10611160.2
#Sta/Elev= 30
  3990.2  422.62  4011.4  421.36  4025.6  419.24  4195.3  408.05  4287.4  397.81
  4308.4  394.54  4315.8  394.54  4450.1   382.9  4464.3  382.63    4542  376.44
  4718.8  369.36  4903.9  369.75  4973.8  369.78    4988  367.34  4994.8  362.29
  5001.9   361.3  5005.2   361.8    5009  363.72  5019.4  363.09  5023.2  363.73
  5037.4  369.81  5044.1  368.99  5097.3  368.73  5115.3  369.78  5207.3  369.45
  5285.2  372.03  5321.2  373.78    5399  380.03    5512  387.26  5547.6  388.66
#Mann= 5 ,-1 , 0
  3990.2     .16       0  4903.9     .16       0  4973.8     .16       0
  5037.4     .16       0  5097.3     .05       0
Bank Sta=4973.8,5037.4
XS Rating Curve= 0 ,0
Exp/Cntr=0.3,0.1

Type RM Length L Ch R = 1 ,11992   ,629,629,629
BEGIN DESCRIPTION:
SNEED CREEK 20.0
END DESCRIPTION:
XS GIS Cut Line= 3
      3571049.58     10610710.16      3571449.61     10611110.19
      3572249.57     10611460.17
#Sta/Elev= 30
  4434.2   388.9  4490.8  385.91  4533.2  380.37  4561.5  378.61  4702.9  371.24
  4813.5  368.26  4929.2  367.22  4985.8  368.73  4993.4  360.28  4996.1  359.78
  5002.7  360.28  5008.9  362.63  5014.4  367.72  5021.8  368.31  5025.9  368.19
    5189  368.01  5229.1  369.34  5294.6   368.6  5439.3  372.86  5469.3  375.01
  5532.8  380.24  5545.7  379.83  5556.2  381.66  5561.7  381.14  5585.1  383.12
  5590.5  381.99  5654.8  388.41  5753.1  393.92  5818.6   399.1  5873.1  401.56
#Mann= 5 ,-1 , 0
  4434.2     .16       0  4813.5     .16       0  4985.8     .16       0
  5025.9     .16       0  5469.3     .05       0
Bank Sta=4985.8,5021.8
XS Rating Curve= 0 ,0
Exp/Cntr=0.3,0.1

Type RM Length L Ch R = 1 ,11363   ,394,394,394
BEGIN DESCRIPTION:
SNEED CREEK 19.0
END DESCRIPTION:
XS GIS Cut Line= 3
      3570665.06     10611132.15      3571321.31     10611757.14
      3572294.95     10611751.93
#Sta/Elev= 30
  4360.6  394.13  4454.3  388.75  4595.9  377.14  4631.1  375.86  4638.3  374.72
  4645.2  369.95  4659.6  366.94  4666.6  363.52  4673.6  367.04  4680.8  367.18
  4850.3  366.45  4864.5  363.02  4878.6  366.33  4956.6  366.71    4985  363.66
  4998.9  357.45    5006  359.66  5013.3  359.92  5020.2  364.55  5041.6   366.7
  5048.5  366.48  5505.1  371.64  5625.1  371.56  5725.2   373.7  5895.2  381.76
  6005.2  391.09  6035.2  391.65  6145.2     398  6195.2  402.49  6240.5  405.01
#Mann= 4 ,-1 , 0
  4360.6     .16       0  4659.6     .16       0  4956.6     .16       0
  5048.5     .16       0
#XS Ineff= 1 ,-1
 4607.95 4877.84366.9757
Permanent Ineff=
       F
Bank Sta=4956.6,5041.6
XS Rating Curve= 0 ,0
Exp/Cntr=0.3,0.1

Type RM Length L Ch R = 1 ,10969   ,273,273,273
BEGIN DESCRIPTION:
SNEED CREEK 18.0
END DESCRIPTION:
XS GIS Cut Line= 2
      3570461.97     10611418.63      3571889.01     10612554.01
#Sta/Elev= 30
  4516.8  397.24  4594.2  389.11  4658.3  384.96  4687.1  380.53  4879.3   366.6
  4893.8  363.78  4900.1  365.33  4908.2  361.15  4914.6  365.28  4915.6  364.71
  4922.6  360.68    4929  363.44  4935.5  359.89  4943.4  362.59  4949.8  358.53
  4957.8  360.29  4964.2   358.2  5007.2  357.35  5013.9  359.41  5021.9  365.21
  5100.4  367.42  5170.8  364.39  5441.6  369.36  5561.7  367.31  5633.8  370.04
  5910.9  371.79  5989.3     374  6082.3  380.73  6181.6  385.07  6340.4  388.98
#Mann= 4 ,-1 , 0
  4516.8     .16       0  4915.6     .16       0  5021.9     .16       0
  5100.4     .16       0
#XS Ineff= 2 , 0
                         5457.95          374.59
Permanent Ineff=
       F       F
Bank Sta=4914.6,5021.9
XS Rating Curve= 0 ,0
Exp/Cntr=0.3,0.1

Type RM Length L Ch R = 1 ,10696   ,389,389,389
BEGIN DESCRIPTION:
SNEED CREEK 17.0
END DESCRIPTION:
XS GIS Cut Line= 3
      3570349.57     10611660.16      3570749.61     10611960.19
      3571549.59     10612760.17
#Sta/Elev= 30
  4498.7  392.36  4565.3  386.71  4634.1   381.8  4676.9  378.94  4720.6  374.22
  4726.9  372.77  4791.5   369.8  4820.6  366.37    4829  366.25  4920.6  363.45
  4976.9  364.01  4985.2  362.98  4991.5  359.55  5002.3  359.78  5012.6  357.43
  5041.2  364.23  5069.5  364.67  5083.6  362.56  5140.2  364.46  5154.3  364.26
  5168.5  362.56  5210.9  364.69  5235.8  364.33  5267.5   365.5  5338.2  365.88
  5536.2   364.8    5720  365.69  5865.8  367.99  5903.8  368.88  6130.1  383.29
#Mann= 8 ,-1 , 0
  4498.7     .05       0  4565.3     .16       0  4634.1     .16       0
    4829     .16       0  4976.9     .16       0  5041.2     .16       0
  5235.8     .16       0  5865.8     .12       0
Bank Sta=4976.9,5041.2
XS Rating Curve= 0 ,0
Exp/Cntr=0.3,0.1

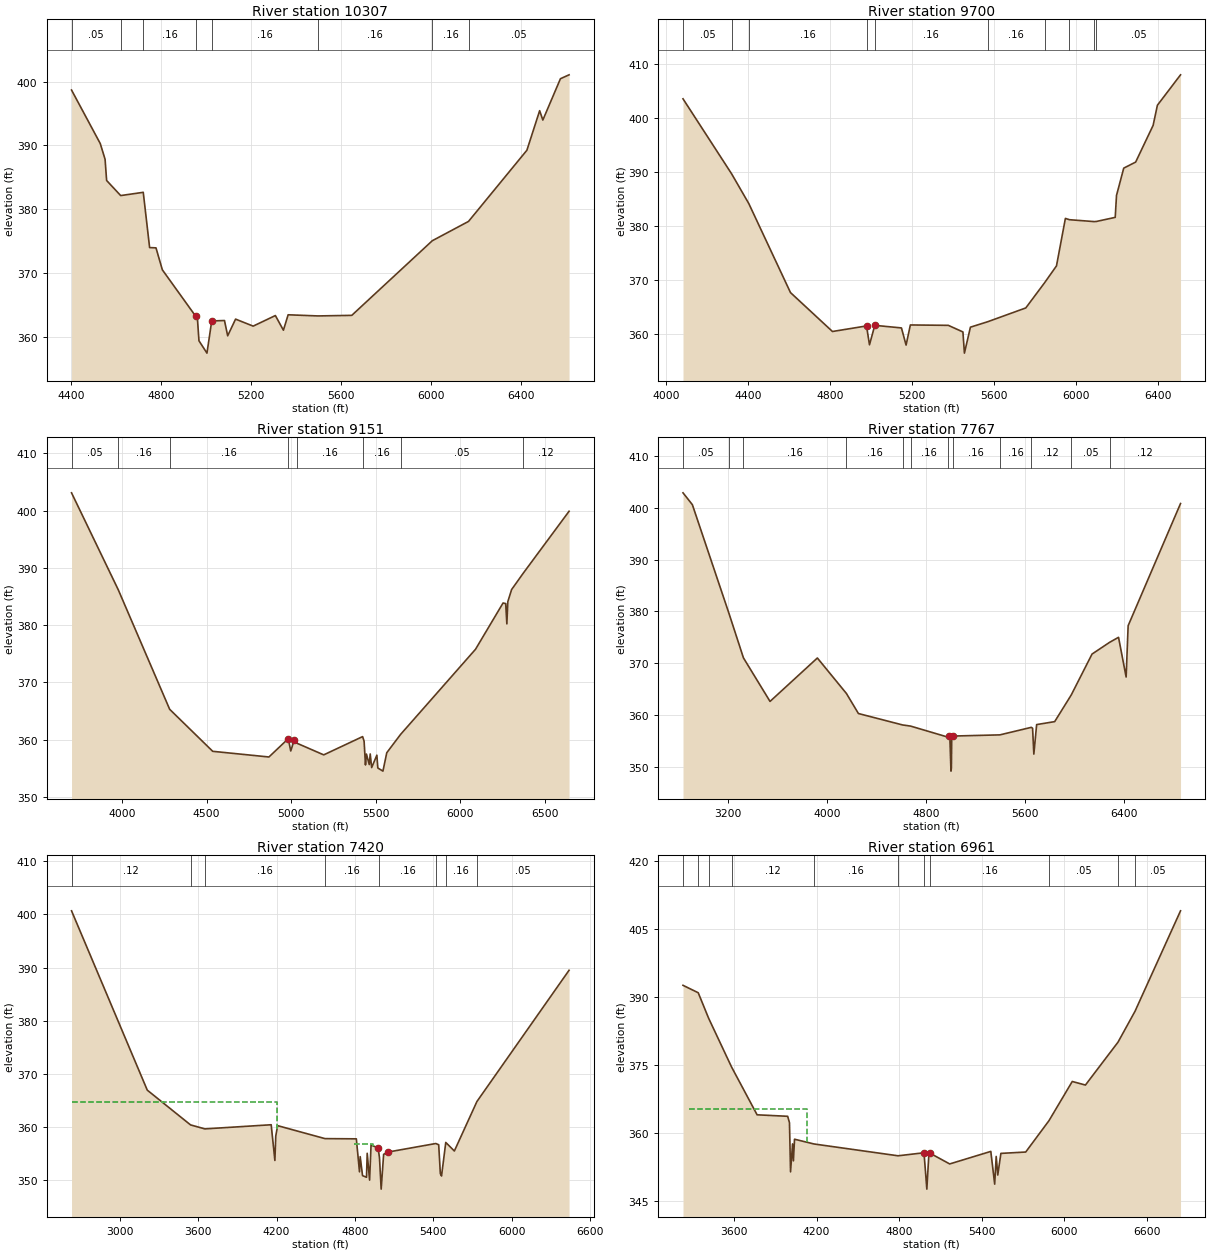
Type RM Length L Ch R = 1 ,10307   ,607,607,607
BEGIN DESCRIPTION:
SNEED CREEK 15.0
END DESCRIPTION:
XS GIS Cut Line= 2
      3570109.96     10611799.33       3571616.9     10613417.38
#Sta/Elev= 30
    4401   398.7  4528.6   390.3  4550.1  387.82  4556.9   384.5  4619.4  382.13
  4719.7  382.64    4748  373.96  4776.3  373.92  4804.6  370.47  4953.2  363.16
  4960.5  362.81  4967.3  359.33  5002.8  357.39    5024  362.44  5080.7  362.51
  5094.9  360.11    5130  362.73  5208.2  361.63  5306.9  363.29  5342.6  360.99
  5363.6  363.41  5495.7  363.23  5646.4  363.32  6004.3  375.04  6165.2  378.07
  6424.7  389.25  6481.4  395.46  6495.6  393.99  6573.8  400.48  6612.1  401.09
#Mann= 8 ,-1 , 0
    4401     .05       0  4619.4     .16       0  4719.7     .16       0
  4953.2     .16       0    5024     .16       0  5495.7     .16       0
  6004.3     .16       0  6165.2     .05       0
#XS Ineff= 1 ,-1
 5278.41 5377.27  362.47
Permanent Ineff=
       F
Bank Sta=4953.2,5024
XS Rating Curve= 0 ,0
Exp/Cntr=0.3,0.1

Type RM Length L Ch R = 1 ,9700    ,549,549,549
BEGIN DESCRIPTION:
SNEED CREEK 14.0
END DESCRIPTION:
XS GIS Cut Line= 3
      3569971.08     10611847.96      3570144.69     10612646.55
      3571422.11     10613625.44
#Sta/Elev= 30
  4083.7  403.48  4320.9   389.6  4404.8  384.09  4607.9  367.64  4812.6  360.44
  4978.7  361.47  4993.2  357.98  5019.1  361.58  5149.1   361.1  5171.7  357.93
  5192.6  361.65  5377.5  361.58  5448.9  360.36  5456.2  356.44  5485.5  361.24
  5570.7  362.26  5755.6   364.8  5847.5  369.47  5905.2  372.57  5948.7  381.36
  5968.5  381.12  6089.5  380.77  6100.3   380.8  6191.7  381.55    6198  385.61
  6233.3  390.66  6291.4  391.78  6376.6  398.57  6397.4  402.29  6510.3  407.92
#Mann= 10 ,-1 , 0
  4083.7     .05       0  4320.9     .16       0  4404.8     .16       0
  4978.7     .16       0  5019.1     .16       0  5570.7     .16       0
  5847.5     .12       0  5968.5      .1       0  6089.5     .15       0
  6100.3     .05       0
#XS Ineff= 1 ,-1
 5433.52 5520.45  359.84
Permanent Ineff=
       F
Bank Sta=4978.7,5019.1
XS Rating Curve= 0 ,0
Exp/Cntr=0.3,0.1

Type RM Length L Ch R = 1 ,9151    ,1384,1384,1384
BEGIN DESCRIPTION:
SNEED CREEK 13.0
END DESCRIPTION:
XS GIS Cut Line= 4
      3569721.07      10611827.1      3569665.52     10612861.83
      3569908.57     10613181.27       3571255.2     10613847.64
#Sta/Elev= 30
  3702.3   403.1  3978.7  386.15  4282.2  365.29  4536.6  357.95  4868.8  356.96
  4983.1  360.16  4997.7  358.01  5018.5  359.92    5033  359.38  5192.6  357.33
  5422.4  360.52  5431.2   359.7  5439.3  355.57  5444.9  357.47  5461.7  355.64
  5467.3  357.49  5475.8  355.11  5506.6  357.28  5512.2  355.04  5542.5  354.49
  5565.1   357.7  5646.7   360.9  6089.5  375.77  6252.4  383.86    6268  383.75
  6274.8  380.21  6280.4  384.08  6302.8   386.2  6372.1  389.08  6642.4  399.88
#Mann= 8 ,-1 , 0
  3702.3     .05       0  3978.7     .16       0  4282.2     .16       0
  4983.1     .16       0    5033     .16       0  5422.4     .16       0
  5646.7     .05       0  6372.1     .12       0
#XS Ineff= 1 ,-1
 5409.09 5623.86  358.64
Permanent Ineff=
       F
Bank Sta=4983.1,5018.5
XS Rating Curve= 0 ,0
Exp/Cntr=0.3,0.1

Type RM Length L Ch R = 1 ,7767    ,347,347,347
BEGIN DESCRIPTION:
SNEED CREEK 12.0
END DESCRIPTION:
XS GIS Cut Line= 4
      3569422.46     10611716.02      3569061.35     10613521.55
      3569526.63     10613834.05      3571109.97     10614160.44
#Sta/Elev= 30
  2838.5  402.84  2914.1  400.56  3209.9  379.61  3326.7  371.06  3541.4  362.68
  3923.7  371.04  4158.3  364.21  4255.2  360.35  4612.2  358.15  4676.5  357.93
  4979.1   355.8    4988  355.93  4994.1   355.6  5002.7  349.26  5005.9  349.76
  5009.1  355.82  5015.1  356.01    5398  356.24  5651.7  357.69  5661.9  357.52
  5672.1  352.54  5694.7  358.22  5840.4  358.79  5973.9  363.91  6142.2   371.8
  6284.2  374.06  6356.2  375.02  6417.5  367.38  6433.7  377.26  6856.9  400.78
#Mann= 12 ,-1 , 0
  2838.5     .05       0  3209.9     .16       0  3326.7     .16       0
  4158.3     .16       0  4612.2     .16       0  4676.5     .16       0
  4979.1     .16       0  5015.1     .16       0    5398     .16       0
  5651.7     .12       0  5973.9     .05       0  6284.2     .12       0
#XS Ineff= 2 ,-1
  2838.5 3644.89  364.71  5639.2 5715.91  357.26
Permanent Ineff=
       F       F
Bank Sta=4988,5015.1
XS Rating Curve= 0 ,0
Exp/Cntr=0.3,0.1

Type RM Length L Ch R = 1 ,7420    ,459,459,459
BEGIN DESCRIPTION:
SNEED CREEK 11.0
END DESCRIPTION:
XS GIS Cut Line= 3
      3567547.48     10612493.79      3568776.63     10613827.11
      3570623.85      10614577.1
#Sta/Elev= 30
  2631.2  400.67  3210.7  366.94  3541.9   360.4  3651.7  359.65  4158.9  360.43
  4187.2  353.71    4194  358.32  4208.2  360.26  4570.6  357.82  4810.5  357.78
  4834.6  351.57    4840  354.43    4858  350.86  4888.2  350.55  4893.6  355.06
  4911.9  350.02  4923.1  356.62  4976.7  356.07  4987.5  354.27  5000.5  348.32
  5019.4  354.87  5054.3   355.3  5418.4   356.9  5440.8  356.67  5453.3  351.22
  5462.4  350.79  5494.8   357.1  5560.5  355.49  5733.2   364.8  6438.3  389.49
#Mann= 8 ,-1 , 0
  2631.2     .12       0  3541.9     .16       0  3651.7     .16       0
  4570.6     .16       0  4987.5     .16       0  5418.4     .16       0
  5494.8     .16       0  5733.2     .05       0
#XS Ineff= 3 ,-1
  2631.2  4201.7  364.62 4795.45  4937.5  356.73 5411.93 5511.36  356.38
Permanent Ineff=
       F       F       F
Bank Sta=4976.7,5054.3
XS Rating Curve= 0 ,0
Exp/Cntr=0.3,0.1

Type RM Length L Ch R = 1 ,6961    ,463,463,463
BEGIN DESCRIPTION:
SNEED CREEK 9.0
END DESCRIPTION:
XS GIS Cut Line= 3
      3567635.77     10613328.59       3569156.6     10614495.26
       3570684.4     10615238.33
#Sta/Elev= 30
  3229.2  392.54  3339.9   390.9  3415.4  385.27  3581.8  374.52  3767.7  363.95
  3989.9  363.62  4002.9   362.2  4010.7  351.35  4025.2  357.53  4031.5  353.78
  4039.7  358.56  4181.1  357.51  4792.2   354.9  4980.6  355.57  5001.2  347.54
  5015.9  355.27  5023.7  355.48  5167.3   353.1  5466.1  355.87  5494.2  348.64
  5505.2  354.76  5516.7  350.65  5539.3  355.43  5719.7  355.73  5888.7  362.65
    6058  371.31  6153.7  370.52  6390.7     380  6514.1  386.81  6844.9  408.99
#Mann= 11 ,-1 , 0
  3229.2     .12       0  3339.9     .08       0  3415.4     .05       0
  3581.8     .12       0  4181.1     .16       0  4792.2     .16       0
  4980.6     .16       0  5023.7     .16       0  5888.7     .05       0
  6390.7     .07       0  6514.1     .05       0
#XS Ineff= 2 ,-1
 3270.11 4127.27365.2272 5422.73 5554.55  354.46
Permanent Ineff=
       F       F
Bank Sta=4980.6,5023.7
XS Rating Curve= 0 ,0
Exp/Cntr=0.3,0.1

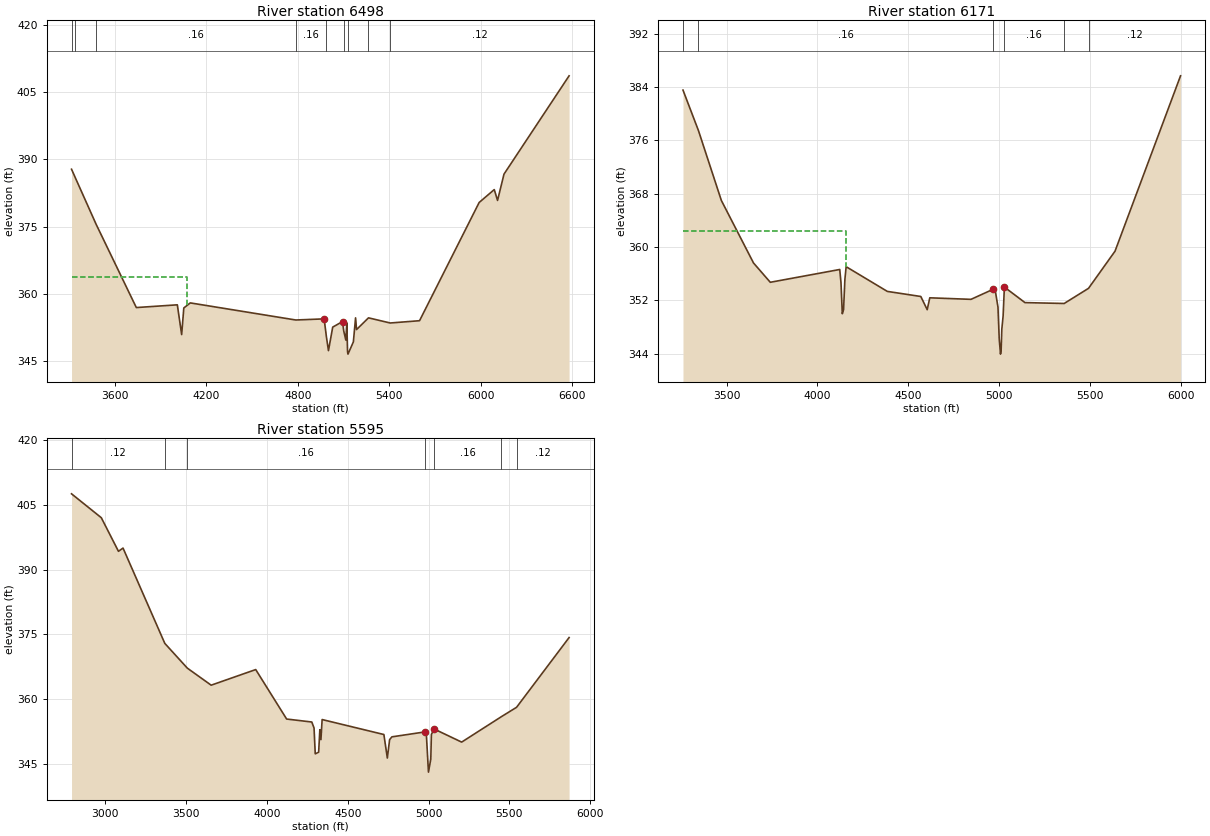
Type RM Length L Ch R = 1 ,6498    ,327,327,327
BEGIN DESCRIPTION:
SNEED CREEK 8.0
END DESCRIPTION:
XS GIS Cut Line= 3
      3567599.58     10613560.16      3568799.61     10614760.19
      3569799.58     10615960.16
#Sta/Elev= 30
  3318.6  387.81    3344  385.86  3478.6  375.58  3742.9  356.89  4011.6   357.5
  4039.9  350.85    4054   356.8  4096.5  357.93  4787.3  354.11  4973.3  354.36
  4987.8  350.42  5001.5  347.26  5029.4  352.52  5093.8  353.76  5101.3   351.7
  5115.3  349.62  5121.8  353.46  5126.6  346.98  5129.3  346.48  5164.7  349.22
  5179.1  354.59  5185.6  351.97  5263.7  354.59  5406.2  353.44  5598.2  353.95
  5988.7  380.38  6087.6  383.26  6109.1  380.84  6151.4  386.72  6577.7  408.69
#Mann= 9 ,-1 , 0
  3318.6     .12       0    3344      .1       0  3478.6     .16       0
  4787.3     .16       0  4987.8     .16       0  5101.3     .16       0
  5126.6     .16       0  5263.7     .16       0  5406.2     .12       0
#XS Ineff= 2 ,-1
  3318.6    4075  363.83 5088.64 5218.18  352.88
Permanent Ineff=
       F       F
Bank Sta=4973.3,5093.8
XS Rating Curve= 0 ,0
Exp/Cntr=0.3,0.1

Type RM Length L Ch R = 1 ,6171    ,576,576,576
BEGIN DESCRIPTION:
SNEED CREEK 7.0
END DESCRIPTION:
XS GIS Cut Line= 2
      3567430.66     10613760.86      3569314.39     10615744.42
#Sta/Elev= 30
  3260.8  383.56    3346  377.47  3471.7     367  3648.5  357.62  3740.7  354.72
  4122.6  356.64  4129.5  354.66  4136.7     350  4143.6   350.6  4150.9  355.14
  4157.8  357.06  4384.3  353.35  4568.3  352.59  4603.5  350.61  4617.7  352.39
  4844.2  352.16  4964.3  353.65  4978.5  353.34  4992.6  350.99  4999.5   346.2
  5006.5  343.94  5009.8  344.44  5013.7  347.68  5020.9  349.69  5027.8     354
  5141.1  351.67  5356.6  351.54  5490.3  353.81  5636.2  359.39  5996.3   385.7
#Mann= 6 ,-1 , 0
  3260.8     .16       0    3346     .16       0  4964.3     .12       0
  5027.8     .16       0  5356.6     .16       0  5490.3     .12       0
#XS Ineff= 2 , 0
         4159.09   362.4
Permanent Ineff=
       F       F
Bank Sta=4964.3,5027.8
XS Rating Curve= 0 ,0
Exp/Cntr=0.3,0.1

Type RM Length L Ch R = 1 ,5595    ,384,384,384
BEGIN DESCRIPTION:
SNEED CREEK 6.0
END DESCRIPTION:
XS GIS Cut Line= 3
      3566699.59     10613610.17      3568199.61     10615260.19
      3568799.64     10615860.22
#Sta/Elev= 30
    2791  407.56  2975.2  402.02  3081.3  394.23  3109.6  394.98  3368.1  372.88
  3507.5  367.14  3654.9  363.19  3930.6  366.81  4121.9  355.34  4277.6  354.65
  4291.5  353.26  4298.9  347.27  4319.9  347.65  4327.3  352.86  4334.1  350.57
  4341.5  355.22  4723.6  351.75  4744.9   346.3  4759.1  350.57  4773.3  351.21
  4978.7  352.36  4985.5   352.4  4999.4  343.03  5013.8  346.05  5017.6  351.79
  5035.1  353.02  5204.8  349.99  5450.3  355.88  5544.5  358.06  5869.5  374.23
#Mann= 7 ,-1 , 0
    2791     .12       0  3368.1     .16       0  3507.5     .16       0
  4978.7     .12       0  5035.1     .16       0  5450.3     .16       0
  5544.5     .12       0
#XS Ineff= 2 ,-1
 4271.88 4349.43  354.19 4691.48 4773.01  350.69
Permanent Ineff=
       F       F
Bank Sta=4978.7,5035.1
XS Rating Curve= 0 ,0
Exp/Cntr=0.3,0.1