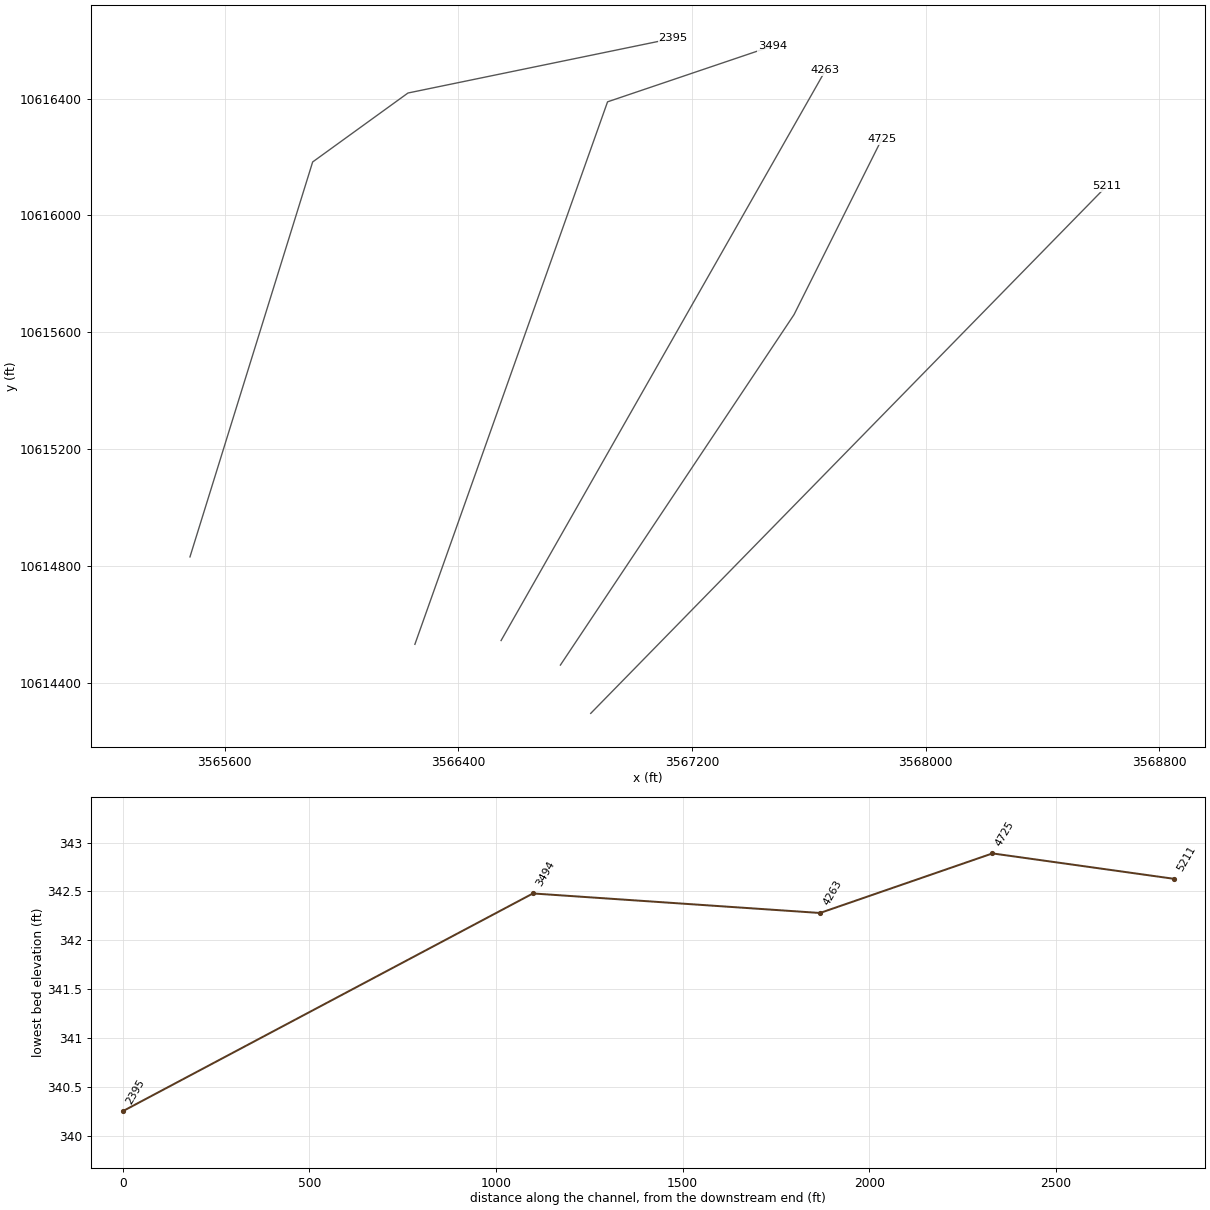
HEC-RAS study SNEED CREEK.prj: SNEED CREEK Base Level Engineering

--- SNEED CREEK.g01 (geometry) --- (continued)

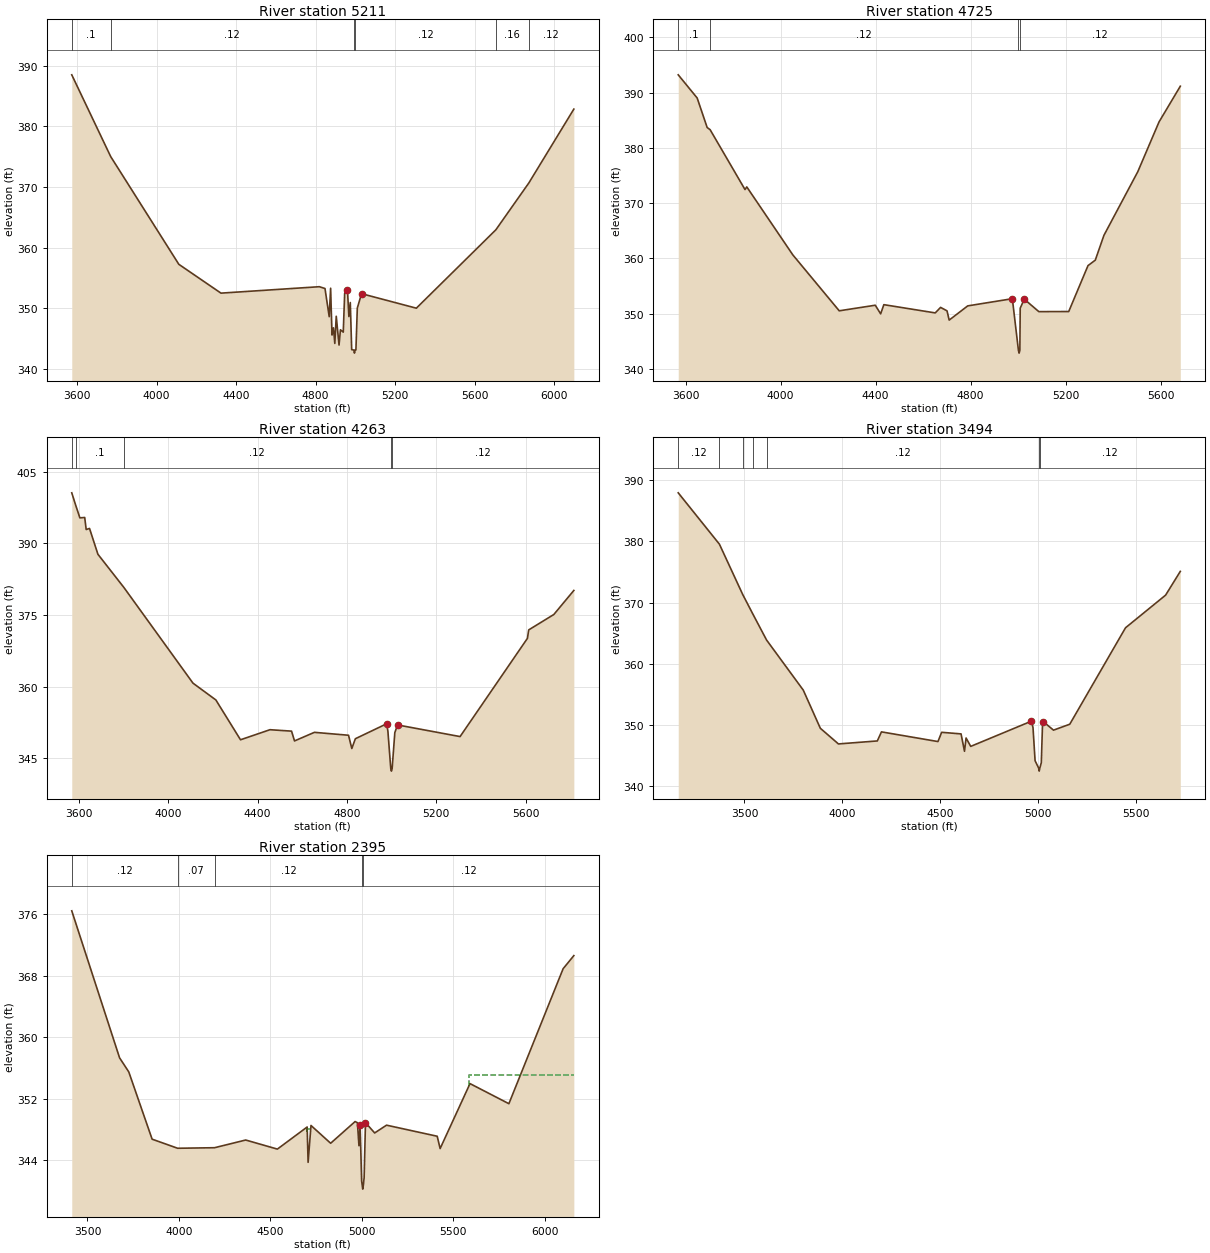
Type RM Length L Ch R = 1 ,5211    ,486,486,486
BEGIN DESCRIPTION:
SNEED CREEK 5.0
END DESCRIPTION:
XS GIS Cut Line= 2
      3566853.43     10614294.74      3568619.95     10616100.32
#Sta/Elev= 30
  3573.4  388.51  3769.1  375.04  4112.1  357.27  4324.1  352.52  4819.1  353.58
  4847.4  353.28  4868.6  348.64  4875.7  353.33  4882.7  345.61  4889.9   346.8
  4896.8  344.23    4904  348.71  4918.1  343.96  4925.1  346.48  4939.3  346.09
  4946.4  352.48  4960.6  352.96  4967.6  348.66  4974.7  350.97  4981.7  343.21
  4992.9  343.13  4995.6  342.63  4998.9  343.13    5003  343.16    5010  350.05
  5031.3  352.43    5307  350.04    5707  362.96  5873.1  370.69  6099.4  382.86
#Mann= 6 ,-1 , 0
  3573.4      .1       0  3769.1     .12       0  4992.9     .07       0
  4998.9     .12       0    5707     .16       0  5873.1     .12       0
#XS Ineff= 1 ,-1
 4827.84 4957.39  352.33
Permanent Ineff=
       F
Bank Sta=4960.6,5031.3
XS Rating Curve= 0 ,0
Exp/Cntr=0.3,0.1

Type RM Length L Ch R = 1 ,4725    ,462,462,462
BEGIN DESCRIPTION:
SNEED CREEK 4.0
END DESCRIPTION:
XS GIS Cut Line= 3
      3566749.59     10614460.15      3567549.61     10615660.19
      3567849.62      10616260.2
#Sta/Elev= 30
  3569.2   393.2  3648.9  389.01  3690.9  383.68  3703.4  383.28  3850.2  372.46
  3857.7  372.94  4051.5  360.65  4246.8  350.54  4398.5  351.55  4421.1  349.99
  4434.6  351.65  4650.9  350.16  4673.4  351.16  4700.5  350.53  4709.5  348.86
  4787.6  351.43  4975.4  352.73    5001  343.39  5003.7  342.89    5007  343.39
  5008.5  351.01  5025.4  352.65  5086.9  350.39  5212.7  350.41  5293.8  358.71
  5324.5   359.7  5360.8  364.18  5503.4  375.69  5592.8  384.69  5682.3  391.14
#Mann= 4 ,-1 , 0
  3569.2      .1       0  3703.4     .12       0    5001     .07       0
    5007     .12       0
Bank Sta=4975.4,5025.4
XS Rating Curve= 0 ,0
Exp/Cntr=0.3,0.1

Type RM Length L Ch R = 1 ,4263    ,769,769,769
BEGIN DESCRIPTION:
SNEED CREEK 3.0
END DESCRIPTION:
XS GIS Cut Line= 2
      3566546.42     10614544.13      3567656.96     10616496.25
#Sta/Elev= 30
  3569.1  400.61  3586.2  398.08  3605.4  395.36    3627  395.44  3633.6  392.92
  3648.6  393.14  3686.1  387.73  3802.3  380.77  4111.3  360.72  4213.6   357.2
  4323.9  348.85  4455.7  350.96  4552.3  350.66  4565.5  348.61  4654.6  350.41
  4807.1   349.8  4821.8  347.02  4837.7  349.07  4977.5   352.2  4983.3  350.63
  4996.1  342.78  4998.9  342.28  5002.1  342.78  5014.2  350.35  5026.5  351.96
  5306.1  349.52  5607.4  370.11  5613.1  371.88  5725.5  375.11    5815  380.15
#Mann= 5 ,-1 , 0
  3569.1     .12       0  3586.2      .1       0  3802.3     .12       0
  4996.1     .07       0  5002.1     .12       0
Bank Sta=4977.5,5026.5
XS Rating Curve= 0 ,0
Exp/Cntr=0.3,0.1

Type RM Length L Ch R = 1 ,3494    ,1099,1099,1099
BEGIN DESCRIPTION:
SNEED CREEK 2.0
END DESCRIPTION:
XS GIS Cut Line= 3
       3566251.3     10614531.17      3566911.02     10616388.78
      3567474.91     10616579.64
#Sta/Elev= 30
  3161.6  387.93  3372.2  379.54  3491.5  371.31  3542.5  368.17  3613.2  363.89
  3800.8  355.71    3888  349.48  3980.6  346.92  4179.3  347.41  4200.5  348.89
  4489.3  347.31  4508.3  348.82  4607.4  348.56    4625  345.72    4633  347.89
  4656.8  346.52  4967.1  350.64  4975.2  349.59  4985.8  344.18    5004  342.98
  5006.8  342.48    5010  342.98  5017.6  343.86  5023.5  349.82  5028.8  350.54
  5079.9  349.17  5163.1  350.14  5448.1  365.89    5653  371.22  5728.2   375.1
#Mann= 7 ,-1 , 0
  3161.6     .12       0  3372.2      .1       0  3491.5     .12       0
  3542.5     .07       0  3613.2     .12       0    5004     .07       0
    5010     .12       0
Bank Sta=4967.1,5028.8
XS Rating Curve= 0 ,0
Exp/Cntr=0.3,0.1

Type RM Length L Ch R = 1 ,2395    ,0,0,0
BEGIN DESCRIPTION:
SNEED CREEK 16.0
END DESCRIPTION:
XS GIS Cut Line= 4
      3565481.11      10614830.5      3565901.24     10616182.89
      3566227.63       10616419.      3567135.95     10616606.22
#Sta/Elev= 30
    3414  376.41  3675.5  357.31  3725.9  355.48  3853.5  346.74  3993.1  345.56
    4195  345.63  4365.5  346.63  4538.7  345.45  4701.5  348.32  4706.8  343.73
  4722.6  348.52  4830.1  346.21  4963.9  349.03  4976.5  348.88    4985  345.89
  4991.2  348.58  4999.7  341.28  5002.9  340.75  5005.6  340.25  5008.9  340.75
  5013.3  341.75  5020.6  348.89  5070.9  347.55  5135.8  348.56    5413  347.12
    5429  345.52  5592.4  353.96  5805.1  351.35  6101.8  368.89  6160.4  370.59
#Mann= 5 ,-1 , 0
    3414     .12       0  3993.1     .07       0    4195     .12       0
  5002.9     .07       0  5008.9     .12       0
#XS Ineff= 2 ,-1
 4702.27 4726.14  348.01 5587.22  6160.4  355.12
Permanent Ineff=
       F       F
Bank Sta=4991.2,5020.6
XS Rating Curve= 0 ,0
Exp/Cntr=0.3,0.1

Chan Stop Cuts=-1
Use User Specified Reach Order=0
Composite Channel Slope=5