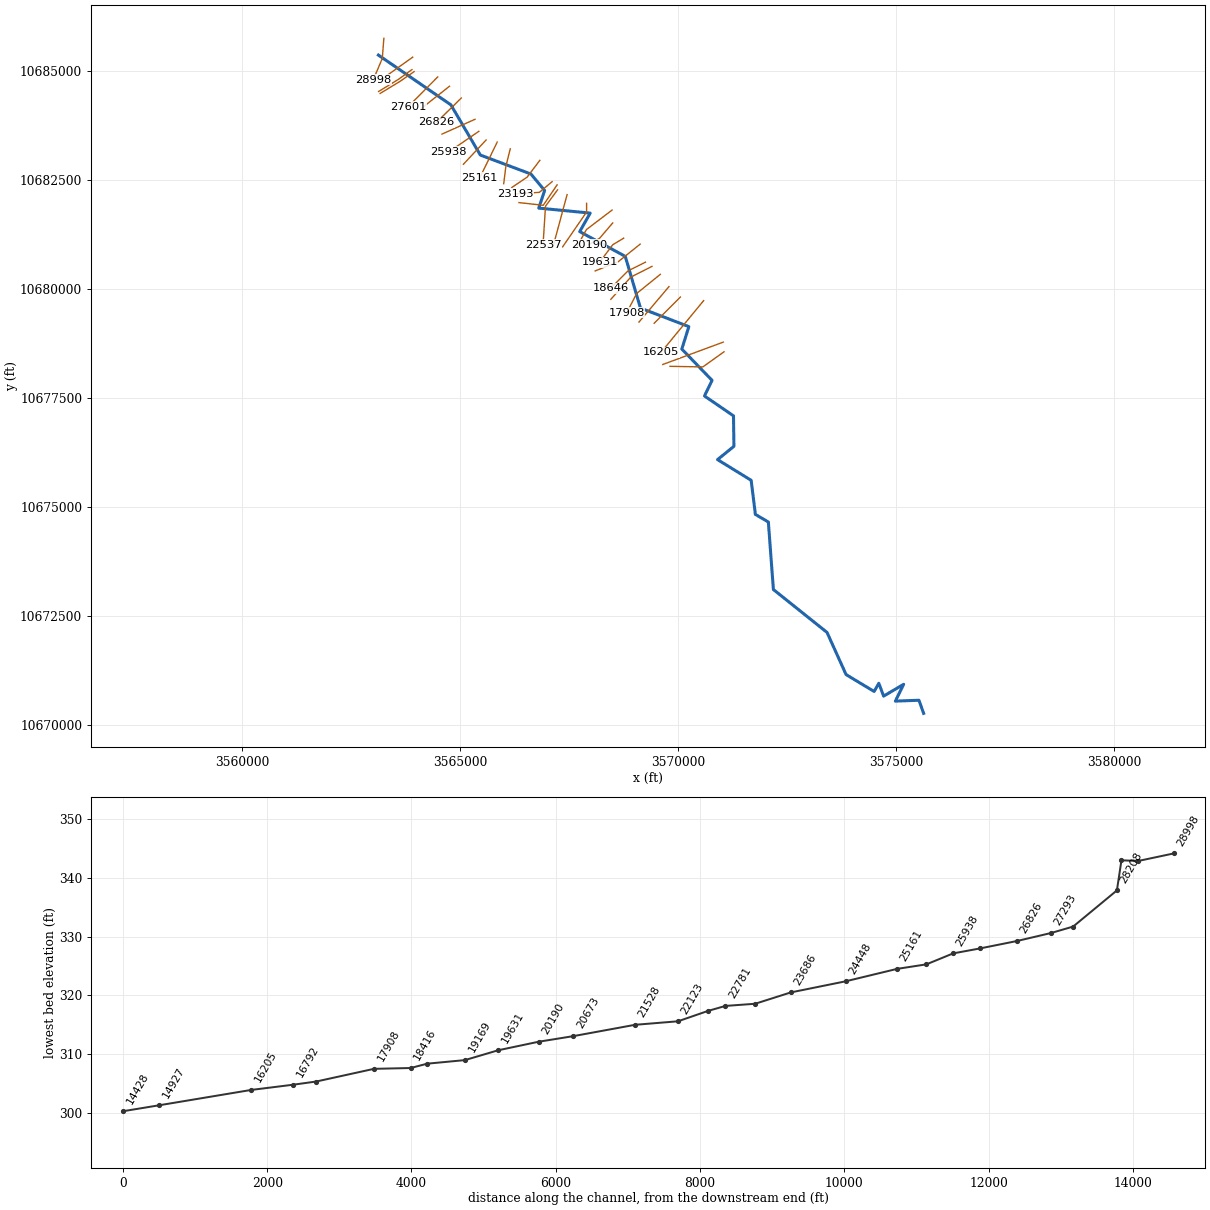
--- SPRING BRANCH.prj (project) ---

Proj Title=SPRING BRANCH Base Level Engineering
Current Plan=p01
Default Exp/Contr=0.3,0.1
English Units
Geom File=g01
Flow File=f01
Plan File=p01
BEGIN DESCRIPTION:
SPRING BRANCH
END DESCRIPTION:

--- SPRING BRANCH.p01 (plan) ---

Plan Title=Multiple Run
Short Identifier=Multiple
Geom File=g01
Flow File=f01
Subcritical Flow
K Sum by GR= 0
Std Step Tol= 0.01
Critical Tol= 0.01
Num of Std Step Trials= 20
Max Error Tol= 0.3
Flow Tol Ratio= 0.001
Split Flow NTrial= 30
Split Flow Tol= 0.02
Split Flow Ratio= 0.02
Log Output Level= 0
Friction Slope Method= 1
Unsteady Friction Slope Method= 2
Unsteady Bridges Friction Slope Method= 1
Parabolic Critical Depth
Global Vel Dist=  1 , 1 , 1
Global Log Level= 0
CheckData=True
Encroach Param= -1, 0, 0, 0
BEGIN DESCRIPTION:
Multiple Run
END DESCRIPTION:

--- SPRING BRANCH.f01 (steady flow) ---

Flow Title=Multiple
Number of Profiles=7
Profile Names=10-year,25-year,50-year,1pct_min,100-year,1pct_plu,500-year
River Rch & RM= SPRING BRANCH,Reach-1,28998
    1482    2051    2524    2266    3065    4144    4504
River Rch & RM= SPRING BRANCH,Reach-1,27601
    1837    2555    3154    2835    3834    5185    5653
River Rch & RM= SPRING BRANCH,Reach-1,22537
    3234    4616    5796    5291    7155    9676   10882
River Rch & RM= SPRING BRANCH,Reach-1,14428
    3684    5283    6653    6089    8235   11137   12591
River Rch & RM= SPRING BRANCH,Reach-1,7808
    3767    5378    6752    6157    8326   11260   12639
Boundary for River Rch & Prof#=SPRING BRANCH,Reach-1,1
Up Type=0
Dn Type=3
Dn Slope=0.005
Boundary for River Rch & Prof#=SPRING BRANCH,Reach-1,2
Up Type=0
Dn Type=3
Dn Slope=0.005
Boundary for River Rch & Prof#=SPRING BRANCH,Reach-1,3
Up Type=0
Dn Type=3
Dn Slope=0.005
Boundary for River Rch & Prof#=SPRING BRANCH,Reach-1,4
Up Type=0
Dn Type=3
Dn Slope=0.005
Boundary for River Rch & Prof#=SPRING BRANCH,Reach-1,5
Up Type=0
Dn Type=3
Dn Slope=0.005
Boundary for River Rch & Prof#=SPRING BRANCH,Reach-1,6
Up Type=0
Dn Type=3
Dn Slope=0.005
Boundary for River Rch & Prof#=SPRING BRANCH,Reach-1,7
Up Type=0
Dn Type=3
Dn Slope=0.005

--- SPRING BRANCH.g01 (geometry) ---

Geom Title=Existing Conditions

River Reach=SPRING BRANCH,Reach-1
Reach XY= 30
      3563127.50     10685360.00      3564788.75     10684219.00
      3565463.50     10683068.00      3566624.00     10682632.00
      3566937.75     10682254.00      3566804.00     10681850.00
      3567982.75     10681736.00      3567742.75     10681311.00
      3568786.75     10680743.00      3569134.50     10679557.00
      3570244.25     10679132.00      3570083.50     10678617.00
      3570776.50     10677899.00      3570602.25     10677541.00
      3571267.75     10677085.00      3571277.50     10676386.00
      3570901.75     10676081.00      3571672.25     10675607.00
      3571769.25     10674825.00      3572067.00     10674649.00
      3572182.50     10673101.00      3573412.00     10672117.00
      3573848.50     10671150.00      3574491.25     10670763.00
      3574599.25     10670951.00      3574709.50     10670656.00
      3575168.50     10670927.00      3574978.75     10670541.00
      3575519.50     10670561.00      3575627.25     10670260.00

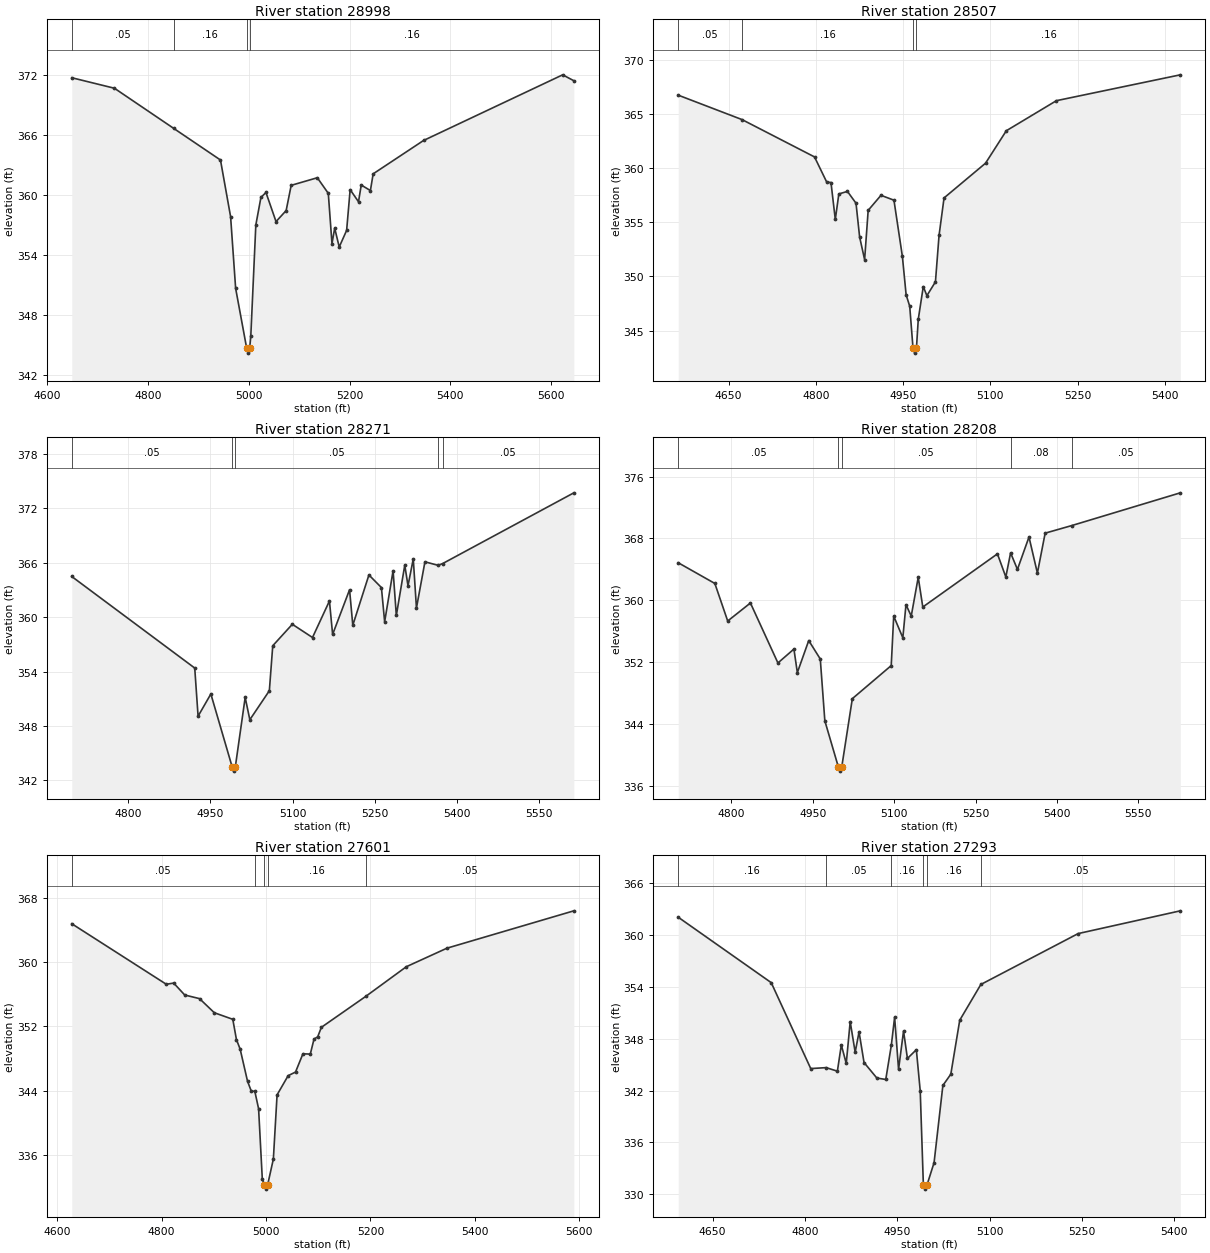
Type RM Length L Ch R = 1,28998,491,491,491
BEGIN DESCRIPTION:
SPRING BRANCH 52.0
END DESCRIPTION:
XS GIS Cut Line= 3
      3563252.07     10685744.59      3563215.61     10685281.07
      3563007.28     10684791.50
#Sta/Elev= 30
  4648.2  371.70  4732.9  370.65  4850.9  366.63  4943.5  363.48  4963.6  357.82
  4973.6  350.66  4995.5  344.69  4998.3  344.19  5001.5  344.69  5003.7  345.88
  5013.7  356.99  5023.8  359.74  5033.8  360.24  5053.8  357.33  5073.9  358.43
  5083.9  360.95  5135.8  361.71  5157.6  360.15  5164.9  355.13  5170.3  356.67
  5179.3  354.79  5194.0  356.45  5201.0  360.52  5217.6  359.31  5223.0  360.98
  5241.2  360.43  5246.7  362.10  5346.7  365.43  5623.0  371.99  5645.2  371.40
#Mann=4,-1,0
  4648.2    0.05       0  4850.9    0.16       0  4995.5    0.07       0
  5001.5    0.16       0
Bank Sta=4995.5,5001.5
Exp/Cntr=0.3,0.1

Type RM Length L Ch R = 1,28507,236,236,236
BEGIN DESCRIPTION:
SPRING BRANCH 51.0
END DESCRIPTION:
XS GIS Cut Line= 2
      3563913.51     10685312.31      3563210.37     10684812.30
#Sta/Elev= 30
  4563.5  366.76  4673.2  364.50  4797.7  361.05  4818.6  358.73  4826.0  358.68
  4833.4  355.27  4839.5  357.63  4854.3  357.86  4869.0  356.77  4875.2  353.65
  4883.8  351.55  4889.9  356.11  4911.9  357.50  4934.2  357.05  4948.7  351.85
  4955.1  348.31  4961.3  347.24  4966.9  343.41  4969.6  342.91  4972.9  343.41
  4976.0  346.04  4984.6  349.06  4990.8  348.22  5005.5  349.50  5011.7  353.79
  5020.3  357.26  5091.6  360.47  5127.3  363.47  5213.4  366.25  5426.3  368.64
#Mann=4,-1,0
  4563.5    0.05       0  4673.2    0.16       0  4966.9    0.07       0
  4972.9    0.16       0
Bank Sta=4966.9,4972.9
Exp/Cntr=0.3,0.1

Type RM Length L Ch R = 1,28271,63,63,63
BEGIN DESCRIPTION:
SPRING BRANCH 50.0
END DESCRIPTION:
XS GIS Cut Line= 3
      3563895.73     10685027.03      3563585.80     10684803.04
      3563130.72     10684524.79
#Sta/Elev= 30
  4697.2  364.48  4921.5  354.38  4927.6  349.07  4950.9  351.52  4989.6  343.51
  4992.4  343.01  4995.6  343.51  5013.5  351.14  5022.0  348.68  5057.6  351.88
  5063.8  356.84  5099.5  359.21  5136.3  357.75  5167.2  361.78  5173.0  358.09
  5203.9  363.02  5209.8  359.10  5239.2  364.65  5262.0  363.26  5267.9  359.48
  5283.3  365.12  5289.2  360.18  5304.6  365.73  5310.5  363.46  5320.1  366.42
  5325.9  361.00  5341.4  366.10  5365.5  365.71  5373.8  365.91  5613.0  373.71
#Mann=5,-1,0
  4697.2    0.05       0  4989.6    0.04       0  4995.6    0.05       0
  5365.5    0.08       0  5373.8    0.05       0
Bank Sta=4989.6,4995.6
Exp/Cntr=0.3,0.1

Type RM Length L Ch R = 1,28208,607,607,607
BEGIN DESCRIPTION:
Mapping XS 2afbbbbb
END DESCRIPTION:
XS GIS Cut Line= 3
      3563945.16     10684980.11      3563617.05     10684753.56
      3563166.56     10684480.14
#Sta/Elev= 30
  4701.9  364.85  4769.4  362.17  4793.1  357.31  4835.0  359.64  4885.7  351.88
  4915.2  353.68  4921.5  350.63  4942.5  354.78  4963.8  352.39  4972.2  344.39
  4997.3  338.38  5000.0  337.88  5003.3  338.38  5022.9  347.26  5094.6  351.54
  5099.2  357.94  5116.0  355.14  5121.8  359.42  5131.5  357.95  5144.4  362.97
  5152.8  359.12  5290.4  366.00  5305.9  363.01  5314.7  366.13  5327.3  363.99
  5348.6  368.18  5364.1  363.51  5378.4  368.68  5427.8  369.67  5627.6  373.90
#Mann=5,-1,0
  4701.9    0.05       0  4997.3    0.04       0  5003.3    0.05       0
  5314.7    0.08       0  5427.8    0.05       0
Bank Sta=4997.3,5003.3
Exp/Cntr=0.3,0.1

Type RM Length L Ch R = 1,27601,308,308,308
BEGIN DESCRIPTION:
SPRING BRANCH 49.0
END DESCRIPTION:
XS GIS Cut Line= 2
      3564486.47     10684859.23      3563809.34     10684176.88
#Sta/Elev= 30
  4628.1  364.81  4809.1  357.26  4823.2  357.41  4844.4  355.92  4872.7  355.47
  4901.0  353.71  4936.4  352.89  4943.4  350.36  4950.5  349.17  4964.6  345.17
  4971.7  343.95  4978.6  343.90  4985.8  341.74  4992.9  332.98  4997.0  332.21
  4999.7  331.71  5003.0  332.21  5014.1  335.47  5021.2  343.47  5042.4  345.86
  5056.5  346.31  5070.7  348.59  5084.8  348.55  5091.9  350.42  5099.0  350.71
  5106.0  351.89  5191.0  355.75  5268.7  359.45  5346.4  361.76  5589.4  366.42
#Mann=5,-1,0
  4628.1    0.05       0  4978.6    0.16       0  4997.0    0.07       0
  5003.0    0.16       0  5191.0    0.05       0
Bank Sta=4997,5003
Exp/Cntr=0.3,0.1

Type RM Length L Ch R = 1,27293,467,467,467
BEGIN DESCRIPTION:
SPRING BRANCH 48.0
END DESCRIPTION:
XS GIS Cut Line= 2
      3564757.25     10684645.63      3564116.68     10684140.47
#Sta/Elev= 30
  4594.1  362.03  4745.2  354.47  4809.4  344.54  4834.4  344.65  4852.7  344.24
  4859.1  347.27  4867.1  345.13  4873.5  349.97  4881.6  346.43  4887.9  348.77
  4896.0  345.24  4916.8  343.45  4931.3  343.28  4940.3  347.21  4945.7  350.48
  4952.1  344.45  4960.2  348.88  4966.5  345.71  4981.0  346.72  4987.3  341.96
  4992.4  331.11  4995.2  330.61  4998.4  331.11  5009.8  333.67  5024.1  342.59
  5037.0  343.89  5051.5  350.13  5085.8  354.26  5243.9  360.14  5409.9  362.77
#Mann=6,-1,0
  4594.1    0.16       0  4834.4    0.05       0  4940.3    0.16       0
  4992.4    0.07       0  4998.4    0.16       0  5085.8    0.05       0
Bank Sta=4992.4,4998.4
Exp/Cntr=0.3,0.1

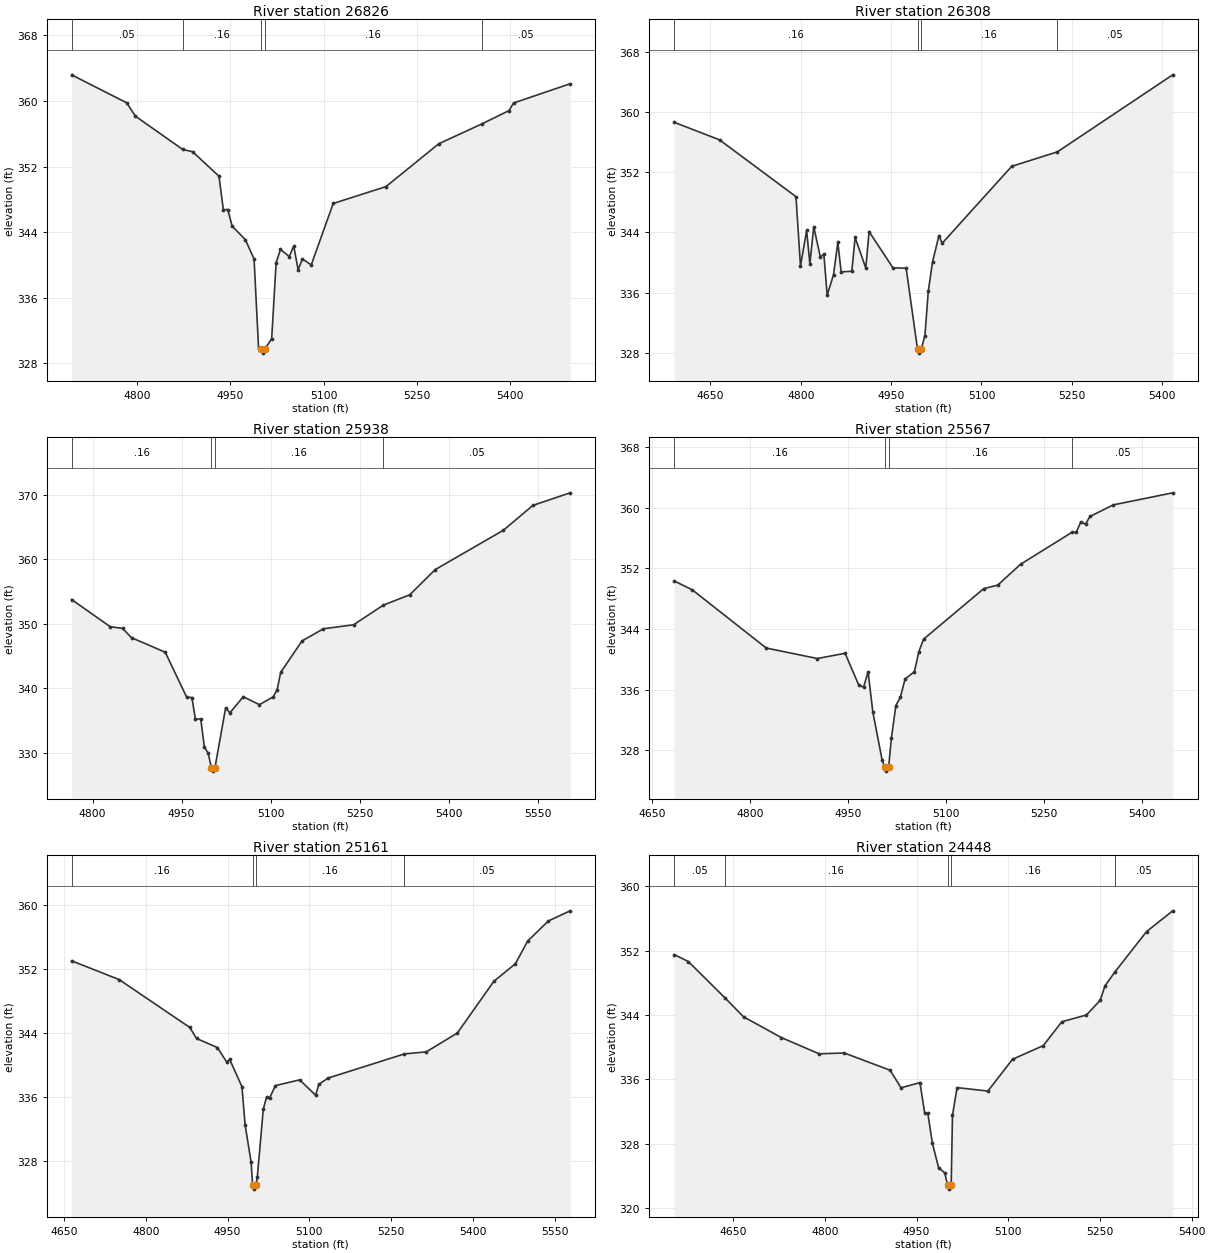
Type RM Length L Ch R = 1,26826,518,518,518
BEGIN DESCRIPTION:
SPRING BRANCH 47.0
END DESCRIPTION:
XS GIS Cut Line= 2
      3565028.52     10684376.62      3564456.17     10683814.67
#Sta/Elev= 30
  4694.4  363.20  4783.0  359.79  4797.2  358.15  4873.2  354.10  4889.1  353.82
  4931.5  350.84  4938.6  346.75  4945.6  346.77  4952.7  344.75  4973.9  343.10
  4988.0  340.75  4995.2  329.88  4999.2  329.76  5001.9  329.26  5005.2  329.76
  5016.3  331.01  5023.5  340.30  5030.5  341.90  5044.6  341.04  5051.8  342.32
  5058.8  339.45  5065.9  340.74  5080.0  340.02  5115.3  347.51  5200.2  349.57
  5285.1  354.79  5354.4  357.21  5398.2  358.84  5405.4  359.76  5496.5  362.11
#Mann=5,-1,0
  4694.4    0.05       0  4873.2    0.16       0  4999.2    0.07       0
  5005.2    0.16       0  5354.4    0.05       0
Bank Sta=4999.2,5005.2
Exp/Cntr=0.3,0.1

Type RM Length L Ch R = 1,26308,370,370,370
BEGIN DESCRIPTION:
SPRING BRANCH 46.0
END DESCRIPTION:
XS GIS Cut Line= 2
      3565341.00     10683887.02      3564585.81     10683548.49
#Sta/Elev= 30
  4589.9  358.62  4665.2  356.29  4792.1  348.75  4799.6  339.55  4809.8  344.26
  4815.2  339.83  4821.6  344.77  4832.5  340.75  4838.4  341.09  4843.9  335.67
  4854.4  338.38  4861.6  342.68  4867.1  338.76  4884.8  338.85  4890.3  343.33
  4908.0  339.27  4913.5  344.11  4953.1  339.30  4975.0  339.26  4993.9  328.48
  4996.7  327.98  4999.9  328.48  5006.2  330.30  5011.7  336.17  5018.8  340.08
  5029.4  343.57  5034.8  342.56  5150.3  352.78  5226.0  354.69  5417.5  364.92
#Mann=4,-1,0
  4589.9    0.16       0  4993.9    0.07       0  4999.9    0.16       0
  5226.0    0.05       0
Bank Sta=4993.9,4999.9
Exp/Cntr=0.3,0.1

Type RM Length L Ch R = 1,25938,371,371,371
BEGIN DESCRIPTION:
SPRING BRANCH 45.0
END DESCRIPTION:
XS GIS Cut Line= 2
      3565429.55     10683610.98      3564736.87     10683137.04
#Sta/Elev= 30
  4764.8  353.75  4829.8  349.54  4850.7  349.27  4865.7  347.83  4922.5  345.58
  4958.6  338.60  4967.3  338.55  4973.3  335.16  4982.2  335.26  4988.2  330.94
  4994.9  329.88  5000.1  327.64  5002.9  327.14  5006.1  327.64  5024.1  336.94
  5031.3  336.18  5053.9  338.68  5081.0  337.45  5104.0  338.64  5110.8  339.74
  5116.8  342.44  5152.7  347.33  5188.8  349.22  5239.4  349.83  5289.6  352.88
  5334.2  354.49  5376.9  358.39  5491.7  364.49  5541.4  368.35  5604.1  370.30
#Mann=4,-1,0
  4764.8    0.16       0  5000.1    0.07       0  5006.1    0.16       0
  5289.6    0.05       0
Bank Sta=5000.1,5006.1
Exp/Cntr=0.3,0.1

Type RM Length L Ch R = 1,25567,406,406,406
BEGIN DESCRIPTION:
SPRING BRANCH 44.0
END DESCRIPTION:
XS GIS Cut Line= 2
      3565596.21     10683413.06      3565075.36     10682855.75
#Sta/Elev= 30
  4683.8  350.35  4711.8  349.16  4824.7  341.50  4902.9  340.12  4945.3  340.81
  4966.4  336.59  4973.7  336.34  4980.5  338.37  4987.8  333.06  5002.0  326.72
  5005.9  325.77  5008.6  325.27  5011.9  325.77  5016.2  329.63  5023.0  333.92
  5029.9  335.03  5037.2  337.42  5051.4  338.39  5058.2  341.03  5065.5  342.68
  5157.4  349.33  5178.9  349.80  5214.0  352.56  5292.6  356.77  5299.0  356.76
  5305.9  358.12  5313.2  357.84  5320.0  358.85  5355.7  360.38  5446.6  361.97
#Mann=4,-1,0
  4683.8    0.16       0  5005.9    0.07       0  5011.9    0.16       0
  5292.6    0.05       0
Bank Sta=5005.9,5011.9
Exp/Cntr=0.3,0.1

Type RM Length L Ch R = 1,25161,713,713,713
BEGIN DESCRIPTION:
SPRING BRANCH 43.0
END DESCRIPTION:
XS GIS Cut Line= 2
      3565851.45     10683366.23      3565450.86     10682544.25
#Sta/Elev= 30
  4664.0  353.04  4751.1  350.70  4880.8  344.71  4893.2  343.33  4931.4  342.20
  4948.4  340.40  4954.0  340.71  4976.5  337.30  4982.2  332.56  4993.3  327.86
  4996.0  325.00  4998.8  324.50  5002.0  325.00  5004.6  325.98  5015.6  334.50
  5021.6  335.99  5027.1  335.88  5037.8  337.44  5082.3  338.16  5111.7  336.23
  5117.3  337.58  5134.3  338.38  5274.3  341.40  5314.6  341.66  5371.6  344.02
  5438.4  350.47  5477.9  352.67  5500.4  355.50  5538.4  358.02  5578.4  359.29
#Mann=4,-1,0
  4664.0    0.16       0  4996.0    0.07       0  5002.0    0.16       0
  5274.3    0.05       0
Bank Sta=4996,5002
Exp/Cntr=0.3,0.1

Type RM Length L Ch R = 1,24448,762,762,762
BEGIN DESCRIPTION:
SPRING BRANCH 42.0
END DESCRIPTION:
XS GIS Cut Line= 3
      3566149.61     10683210.20      3566049.61     10682810.19
      3565999.61     10682410.22
#Sta/Elev= 30
  4553.6  351.52  4576.8  350.65  4636.8  346.13  4667.0  343.79  4728.8  341.21
  4790.7  339.19  4831.9  339.29  4906.7  337.15  4924.7  334.97  4955.6  335.61
  4963.3  331.84  4968.4  331.84  4976.0  328.05  4986.1  325.05  4996.2  324.40
  5000.7  322.88  5003.5  322.38  5006.7  322.88  5008.8  331.54  5016.3  334.99
  5066.7  334.56  5107.0  338.51  5157.4  340.21  5187.6  343.17  5227.9  344.01
  5250.6  345.85  5258.2  347.63  5274.7  349.38  5326.2  354.37  5369.0  356.95
#Mann=5,-1,0
  4553.6    0.05       0  4636.8    0.16       0  5000.7    0.07       0
  5006.7    0.16       0  5274.7    0.05       0
Bank Sta=5000.7,5006.7
Exp/Cntr=0.3,0.1

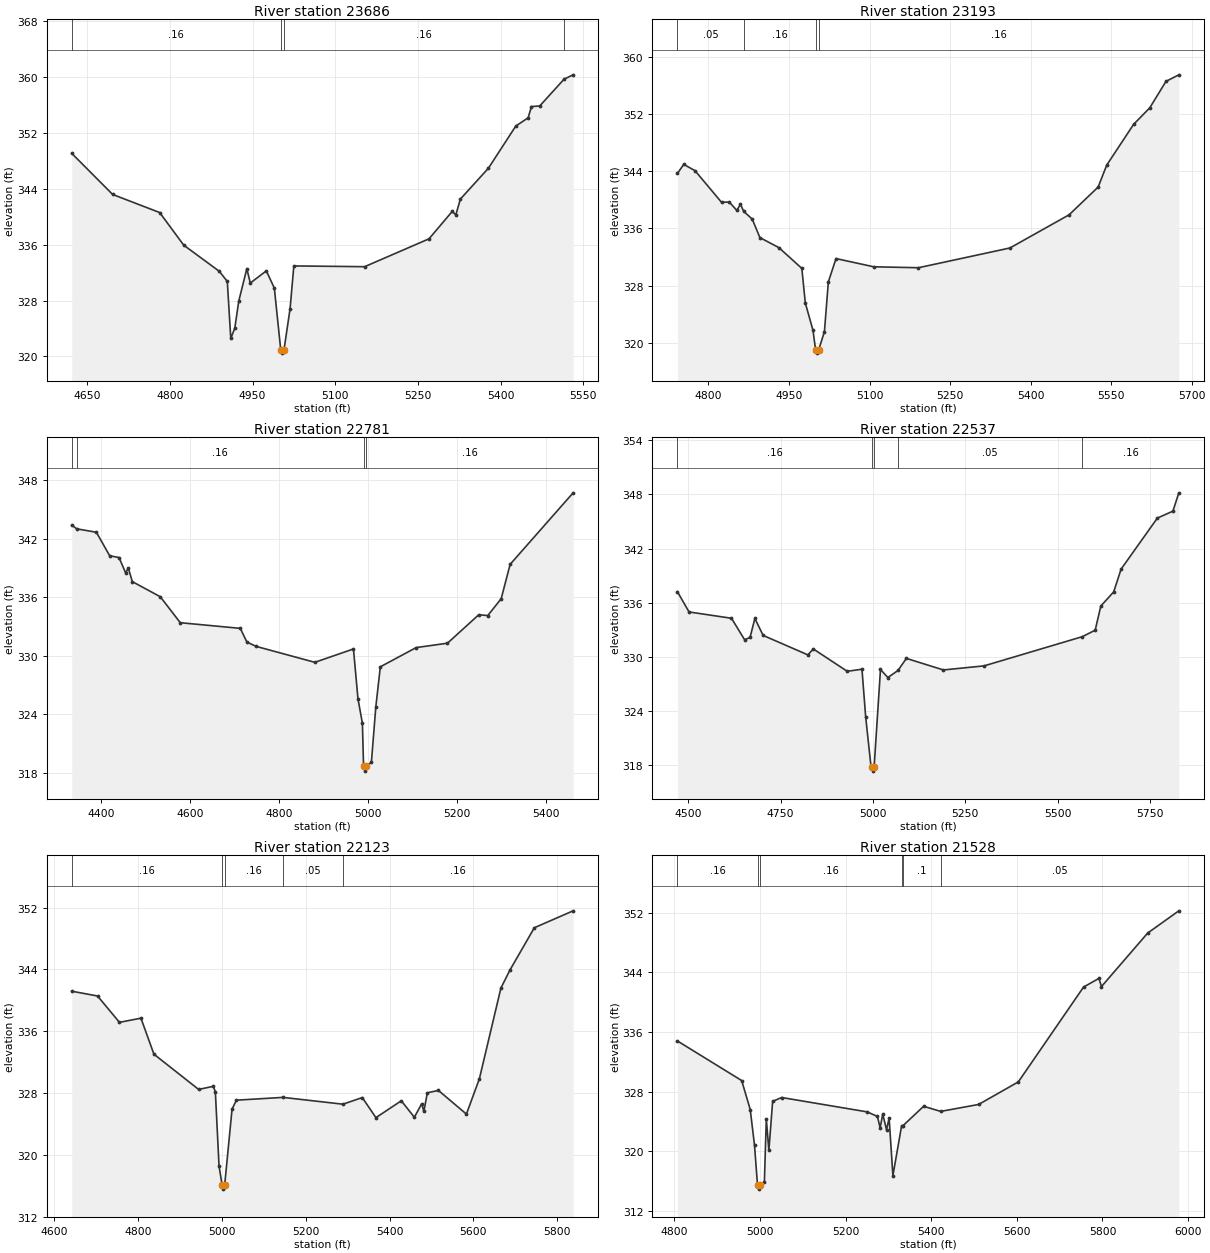
Type RM Length L Ch R = 1,23686,493,493,493
BEGIN DESCRIPTION:
Mapping XS 736bc8a9
END DESCRIPTION:
XS GIS Cut Line= 3
      3566828.08     10682946.04      3566536.43     10682560.64
      3566183.43     10682321.85
#Sta/Elev= 30
  4622.1  349.07  4696.3  343.19  4781.6  340.60  4825.3  335.93  4889.8  332.19
  4904.3  330.74  4910.6  322.58  4917.9  324.06  4925.1  327.93  4939.7  332.57
  4946.0  330.51  4975.1  332.25  4989.6  329.79  5001.2  320.98  5003.9  320.48
  5007.2  320.98  5018.2  326.86  5025.0  332.96  5153.4  332.85  5270.2  336.84
  5312.2  340.75  5318.9  340.27  5327.1  342.53  5378.0  346.95  5427.6  352.98
  5450.0  354.16  5456.0  355.77  5471.0  355.85  5515.2  359.69  5531.6  360.31
#Mann=4,-1,0
  4622.1    0.16       0  5001.2    0.07       0  5007.2    0.16       0
  5515.2    0.05       0
Bank Sta=5001.2,5007.2
Exp/Cntr=0.3,0.1

Type RM Length L Ch R = 1,23193,412,412,412
BEGIN DESCRIPTION:
SPRING BRANCH 41.0
END DESCRIPTION:
XS GIS Cut Line= 3
      3567109.32     10682456.46      3566817.68     10682211.68
      3566265.63     10682175.22
#Sta/Elev= 30
  4742.2  343.68  4754.0  344.94  4774.9  344.06  4824.3  339.64  4838.6  339.68
  4852.9  338.50  4859.5  339.37  4865.6  338.37  4881.5  337.29  4895.8  334.70
  4931.0  333.31  4973.9  330.40  4980.4  325.56  4994.7  321.74  4999.5  319.05
  5002.3  318.55  5005.5  319.05  5016.0  321.55  5023.3  328.51  5037.6  331.77
  5107.9  330.62  5191.2  330.49  5361.5  333.25  5471.8  337.89  5525.9  341.77
  5541.9  344.84  5592.0  350.54  5622.1  352.85  5652.2  356.54  5676.2  357.46
#Mann=4,-1,0
  4742.2    0.05       0  4865.6    0.16       0  4999.5    0.07       0
  5005.5    0.16       0
Bank Sta=4999.5,5005.5
Exp/Cntr=0.3,0.1

Type RM Length L Ch R = 1,22781,244,244,244
BEGIN DESCRIPTION:
SPRING BRANCH 40.0
END DESCRIPTION:
XS GIS Cut Line= 3
      3567223.94     10682383.57      3566906.22     10681914.80
      3566348.90     10681977.31
#Sta/Elev= 30
  4333.6  343.40  4344.9  343.01  4389.0  342.66  4418.9  340.25  4439.9  340.07
  4454.8  338.49  4460.8  338.99  4469.8  337.60  4532.7  336.05  4577.6  333.39
  4712.5  332.81  4727.4  331.40  4748.4  330.96  4880.1  329.33  4966.9  330.70
  4977.0  325.61  4987.0  323.08  4989.6  318.68  4992.3  318.18  4995.6  318.68
  5007.2  319.08  5017.2  324.78  5027.3  328.87  5107.8  330.84  5178.2  331.29
  5248.7  334.21  5268.8  334.12  5299.0  335.85  5319.1  339.37  5460.7  346.70
#Mann=4,-1,0
  4333.6    0.05       0  4344.9    0.16       0  4989.6    0.07       0
  4995.6    0.16       0
Bank Sta=4989.6,4995.6
Exp/Cntr=0.3,0.1

Type RM Length L Ch R = 1,22537,414,414,414
BEGIN DESCRIPTION:
SPRING BRANCH 39.0
END DESCRIPTION:
XS GIS Cut Line= 3
      3567234.34     10682268.96      3566958.30     10681893.97
      3566901.07     10681004.24
#Sta/Elev= 30
  4470.8  337.21  4502.2  334.97  4617.1  334.27  4652.6  331.89  4667.3  332.14
  4680.4  334.25  4702.7  332.37  4823.9  330.21  4838.5  330.87  4930.4  328.39
  4970.3  328.62  4980.3  323.34  4994.6  317.88  4997.3  317.82  5000.1  317.32
  5003.3  317.82  5020.4  328.59  5040.4  327.70  5067.8  328.48  5090.5  329.82
  5190.7  328.54  5300.7  328.99  5566.8  332.23  5601.6  332.95  5616.8  335.62
  5651.7  337.20  5671.7  339.72  5769.9  345.38  5812.0  346.15  5828.0  348.18
#Mann=5,-1,0
  4470.8    0.16       0  4997.3    0.07       0  5003.3    0.16       0
  5067.8    0.05       0  5566.8    0.16       0
Bank Sta=4997.3,5003.3
Exp/Cntr=0.3,0.1

Type RM Length L Ch R = 1,22123,595,595,595
BEGIN DESCRIPTION:
SPRING BRANCH 38.0
END DESCRIPTION:
XS GIS Cut Line= 2
      3567453.10     10682159.63      3567140.85     10681004.28
#Sta/Elev= 30
  4641.3  341.17  4702.9  340.55  4755.2  337.14  4806.5  337.68  4837.5  333.02
  4944.2  328.46  4978.9  328.86  4984.1  328.19  4992.9  318.56  5000.3  316.06
  5003.0  315.56  5006.3  316.06  5024.0  325.92  5034.4  327.07  5145.5  327.43
  5288.7  326.55  5334.8  327.41  5367.4  324.81  5428.0  326.99  5459.1  324.86
  5476.7  326.61  5481.8  325.61  5490.1  328.02  5516.5  328.33  5583.4  325.27
  5614.4  329.85  5665.7  341.57  5687.0  343.88  5745.5  349.38  5838.1  351.57
#Mann=5,-1,0
  4641.3    0.16       0  5000.3    0.07       0  5006.3    0.16       0
  5145.5    0.05       0  5288.7    0.16       0
Bank Sta=5000.3,5006.3
Exp/Cntr=0.3,0.1

Type RM Length L Ch R = 1,21528,855,855,855
BEGIN DESCRIPTION:
SPRING BRANCH 37.0
END DESCRIPTION:
XS GIS Cut Line= 3
      3567899.61     10681960.20      3567899.61     10681760.19
      3567349.63     10680960.22
#Sta/Elev= 30
  4807.5  334.80  4957.5  329.50  4977.5  325.61  4987.5  320.81  4994.5  315.46
  4997.3  314.96  5000.5  315.46  5010.5  315.90  5015.0  324.35  5021.0  320.14
  5029.8  326.71  5050.8  327.23  5251.0  325.30  5274.5  324.69  5280.8  323.17
  5286.9  325.01  5295.7  322.91  5301.8  324.48  5310.6  316.76  5331.0  323.46
  5334.4  323.47  5382.3  326.05  5422.3  325.37  5510.8  326.30  5603.5  329.32
  5755.8  342.02  5791.6  343.18  5797.7  342.09  5905.5  349.25  5978.3  352.23
#Mann=6,-1,0
  4807.5    0.16       0  4994.5    0.07       0  5000.5    0.16       0
  5331.0    0.12       0  5334.4     0.1       0  5422.3    0.05       0
Bank Sta=4994.5,5000.5
Exp/Cntr=0.3,0.1

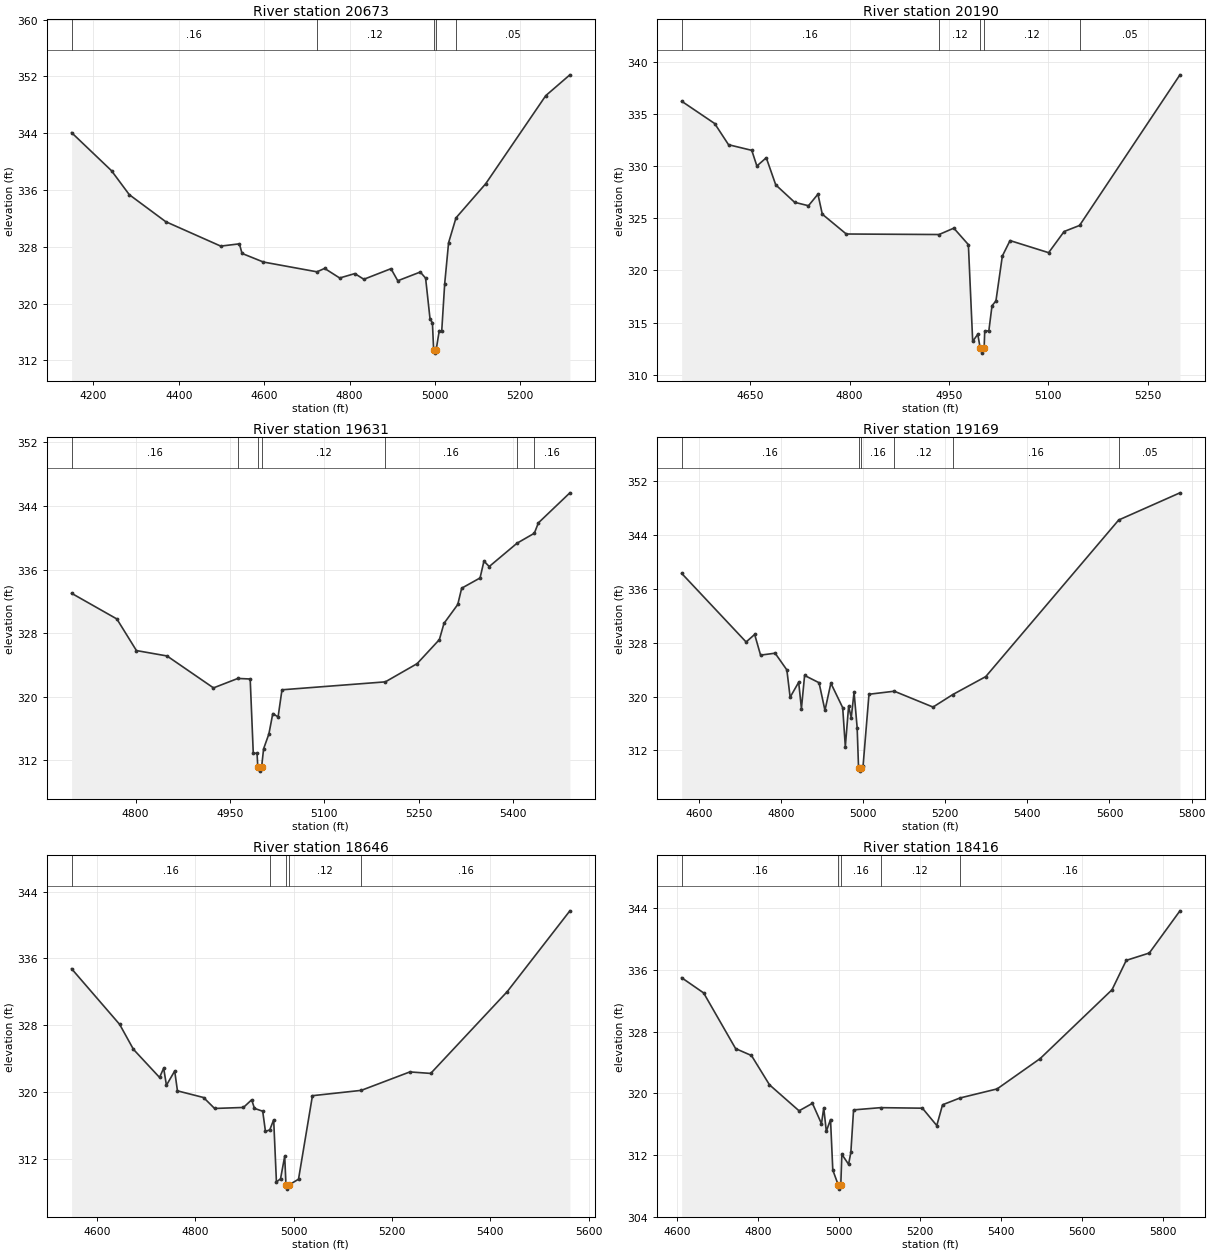
Type RM Length L Ch R = 1,20673,483,483,483
BEGIN DESCRIPTION:
SPRING BRANCH 36.0
END DESCRIPTION:
XS GIS Cut Line= 3
      3568484.34     10681805.42      3567895.80     10681357.51
      3567688.23     10680983.89
#Sta/Elev= 30
  4149.0  344.08  4242.5  338.72  4284.2  335.34  4369.5  331.54  4498.3  328.10
  4542.0  328.42  4548.2  327.07  4598.1  325.86  4723.7  324.48  4741.6  324.96
  4776.9  323.61  4812.3  324.23  4833.5  323.43  4897.0  324.92  4912.9  323.22
  4965.6  324.45  4978.1  323.59  4988.4  317.89  4994.1  317.28  4996.9  313.53
  4999.7  313.03  5002.9  313.53  5010.1  316.20  5015.8  316.08  5022.8  322.79
  5031.9  328.57  5049.3  332.08  5118.8  336.88  5259.5  349.29  5316.0  352.22
#Mann=5,-1,0
  4149.0    0.16       0  4723.7    0.12       0  4996.9    0.07       0
  5002.9    0.12       0  5049.3    0.05       0
Bank Sta=4996.9,5002.9
Exp/Cntr=0.3,0.1

Type RM Length L Ch R = 1,20190,559,559,559
BEGIN DESCRIPTION:
SPRING BRANCH 35.0
END DESCRIPTION:
XS GIS Cut Line= 3
      3568499.59     10681510.17      3568199.61     10681160.19
      3567949.61     10681010.19
#Sta/Elev= 30
  4546.3  336.22  4596.2  334.08  4617.1  332.05  4652.2  331.51  4659.9  330.01
  4674.1  330.80  4688.4  328.20  4716.9  326.53  4737.8  326.20  4752.1  327.31
  4758.7  325.39  4794.9  323.49  4935.0  323.44  4957.3  324.05  4979.3  322.47
  4985.8  313.20  4993.5  313.88  4997.1  312.57  4999.9  312.07  5003.1  312.57
  5004.0  314.20  5010.2  314.20  5015.0  316.62  5020.9  317.07  5030.6  321.38
  5042.2  322.86  5100.5  321.70  5123.9  323.73  5147.2  324.31  5298.8  338.75
#Mann=5,-1,0
  4546.3    0.16       0  4935.0    0.12       0  4997.1    0.07       0
  5003.1    0.12       0  5147.2    0.05       0
Bank Sta=4997.1,5003.1
Exp/Cntr=0.3,0.1

Type RM Length L Ch R = 1,19631,462,462,462
BEGIN DESCRIPTION:
SPRING BRANCH 34.0
END DESCRIPTION:
XS GIS Cut Line= 3
      3568749.57     10681160.17      3568499.61     10681010.19
      3568199.61     10680610.19
#Sta/Elev= 30
  4698.4  333.01  4770.3  329.78  4801.4  325.80  4850.0  325.12  4923.8  321.10
  4962.5  322.29  4982.1  322.22  4987.0  312.87  4993.0  312.87  4994.2  311.12
  4996.9  310.62  5000.2  311.12  5003.4  313.43  5011.8  315.30  5018.0  317.87
  5026.4  317.44  5032.6  320.86  5196.8  321.86  5247.2  324.15  5282.6  327.18
  5289.9  329.22  5311.8  331.60  5318.0  333.65  5347.2  334.94  5353.4  337.06
  5361.8  336.38  5406.0  339.32  5433.4  340.57  5439.9  341.88  5489.9  345.66
#Mann=7,-1,0
  4698.4    0.16       0  4962.5    0.12       0  4994.2    0.07       0
  5000.2    0.12       0  5196.8    0.16       0  5406.0    0.05       0
  5433.4    0.16       0
Bank Sta=4994.2,5000.2
Exp/Cntr=0.3,0.1

Type RM Length L Ch R = 1,19169,523,523,523
BEGIN DESCRIPTION:
SPRING BRANCH 33.0
END DESCRIPTION:
XS GIS Cut Line= 3
      3569127.15     10681023.32      3568627.14     10680622.27
      3568095.93     10680408.74
#Sta/Elev= 30
  4558.1  338.27  4715.1  328.09  4735.9  329.21  4750.3  326.14  4785.7  326.43
  4814.3  323.95  4822.3  319.90  4843.1  322.12  4849.8  318.22  4857.5  323.13
  4892.7  322.05  4907.1  317.95  4921.5  321.98  4950.3  318.35  4956.7  312.57
  4964.7  318.58  4971.1  316.88  4978.0  320.65  4985.5  315.38  4988.9  309.44
  4991.7  308.94  4994.9  309.44  4999.9  309.69  5014.3  320.34  5075.9  320.79
  5170.3  318.44  5218.5  320.30  5298.7  322.96  5622.4  346.18  5771.6  350.21
#Mann=6,-1,0
  4558.1    0.16       0  4988.9    0.07       0  4994.9    0.16       0
  5075.9    0.12       0  5218.5    0.16       0  5622.4    0.05       0
Bank Sta=4988.9,4994.9
Exp/Cntr=0.3,0.1

Type RM Length L Ch R = 1,18646,230,230,230
BEGIN DESCRIPTION:
SPRING BRANCH 32.0
END DESCRIPTION:
XS GIS Cut Line= 3
      3569249.58     10680610.17      3568849.61     10680410.19
      3568449.58     10680010.16
#Sta/Elev= 30
  4548.7  334.75  4646.5  328.07  4674.4  325.09  4727.5  321.72  4735.9  322.83
  4741.5  320.78  4758.3  322.49  4763.9  320.11  4817.0  319.31  4839.4  318.00
  4898.0  318.12  4914.8  319.04  4920.4  318.01  4937.2  317.67  4942.8  315.24
  4951.6  315.44  4959.5  316.64  4965.1  309.18  4973.5  309.58  4981.9  312.27
  4984.5  308.83  4987.2  308.33  4990.5  308.83  5010.0  309.52  5038.3  319.53
  5137.6  320.17  5236.3  322.38  5278.7  322.20  5434.3  332.01  5561.6  341.69
#Mann=5,-1,0
  4548.7    0.16       0  4951.6    0.12       0  4984.5    0.07       0
  4990.5    0.12       0  5137.6    0.16       0
Bank Sta=4984.5,4990.5
Exp/Cntr=0.3,0.1

Type RM Length L Ch R = 1,18416,508,508,508
BEGIN DESCRIPTION:
SPRING BRANCH 31.0
END DESCRIPTION:
XS GIS Cut Line= 3
      3569397.97     10680512.89      3568913.60     10680268.10
      3568455.27     10679757.70
#Sta/Elev= 30
  4612.1  334.99  4666.3  333.02  4745.2  325.80  4784.2  324.91  4828.7  321.11
  4901.6  317.74  4934.6  318.71  4956.9  316.07  4962.5  318.13  4968.8  315.09
  4979.2  316.61  4984.8  310.06  4998.5  308.09  5001.2  307.59  5004.5  308.09
  5007.1  312.10  5023.7  310.81  5029.3  312.34  5036.0  317.86  5102.8  318.15
  5205.8  318.08  5241.2  315.83  5255.4  318.52  5298.2  319.40  5390.0  320.58
  5496.1  324.51  5673.3  333.43  5708.4  337.24  5765.2  338.19  5840.8  343.66
#Mann=5,-1,0
  4612.1    0.16       0  4998.5    0.07       0  5004.5    0.16       0
  5102.8    0.12       0  5298.2    0.16       0
Bank Sta=4998.5,5004.5
Exp/Cntr=0.3,0.1

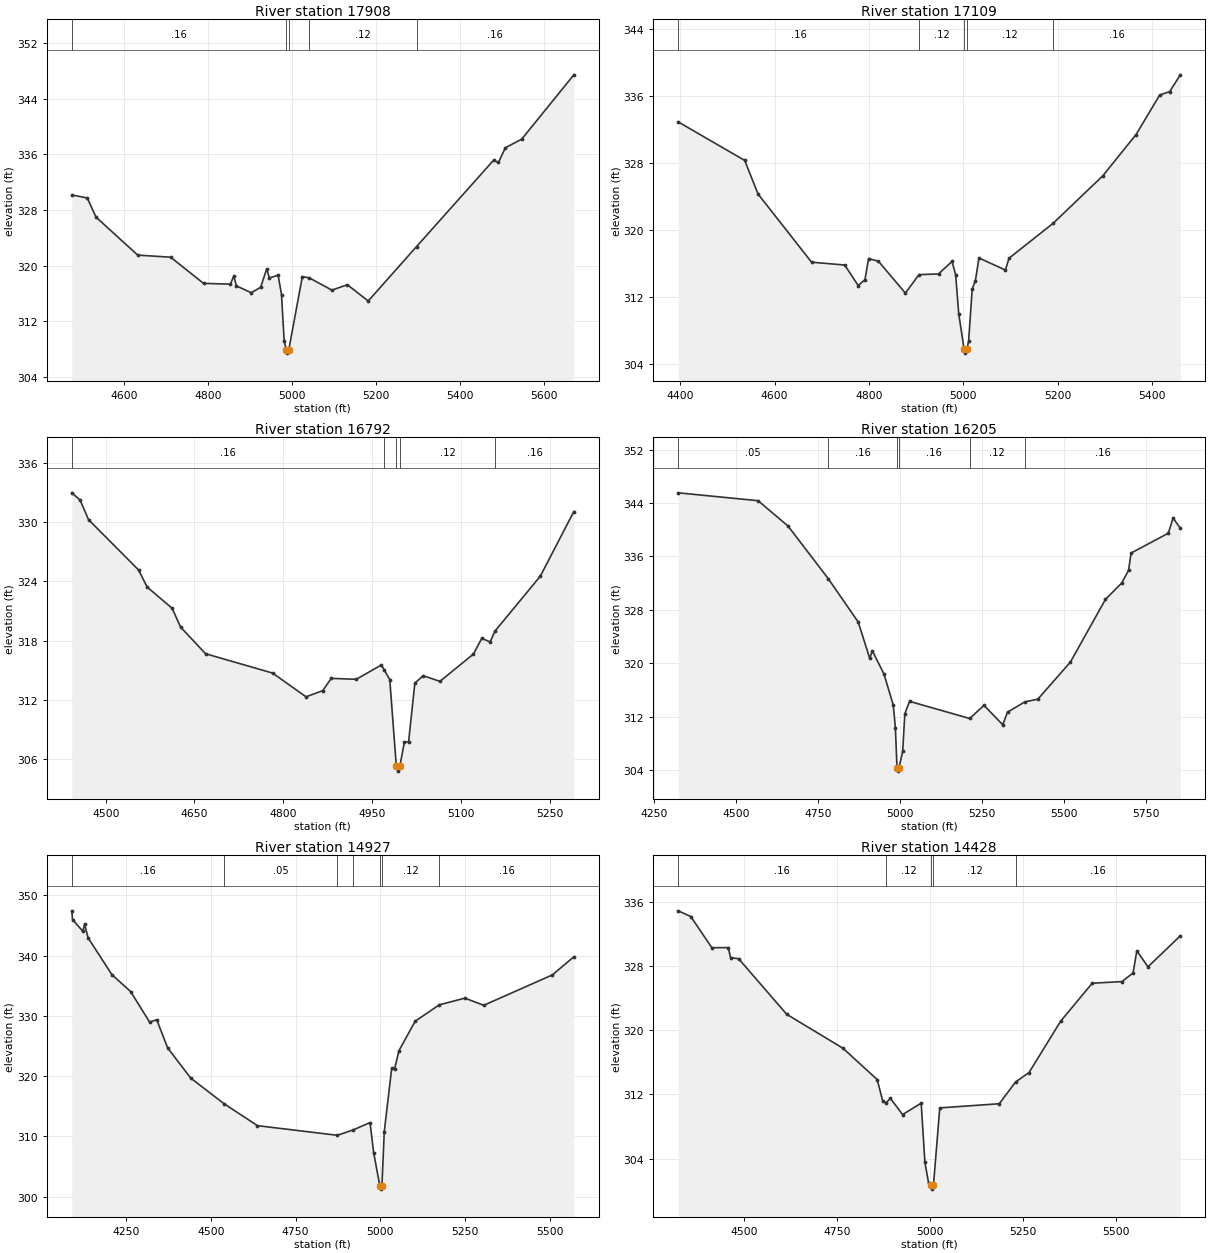
Type RM Length L Ch R = 1,17908,799,799,799
BEGIN DESCRIPTION:
SPRING BRANCH 30.0
END DESCRIPTION:
XS GIS Cut Line= 3
      3569590.65     10680330.58      3569049.01     10679893.10
      3568819.82     10679450.35
#Sta/Elev= 30
  4476.1  330.18  4513.0  329.74  4533.9  326.98  4633.0  321.53  4711.4  321.23
  4789.7  317.47  4853.7  317.36  4861.6  318.53  4868.1  317.10  4903.3  316.13
  4925.6  316.91  4940.0  319.55  4946.4  318.25  4967.2  318.65  4975.2  315.87
  4981.6  309.15  4986.6  307.95  4989.3  307.45  4992.6  307.95  5024.8  318.44
  5041.0  318.27  5095.2  316.50  5131.9  317.28  5181.6  314.94  5296.6  322.76
  5479.7  335.15  5491.5  334.84  5508.0  336.96  5546.7  338.18  5670.9  347.43
#Mann=5,-1,0
  4476.1    0.16       0  4986.6    0.07       0  4992.6    0.16       0
  5041.0    0.12       0  5296.6    0.16       0
Bank Sta=4986.6,4992.6
Exp/Cntr=0.3,0.1

Type RM Length L Ch R = 1,17109,317,317,317
BEGIN DESCRIPTION:
SPRING BRANCH 29.0
END DESCRIPTION:
XS GIS Cut Line= 2
      3569788.56     10680049.32      3569101.09     10679236.84
#Sta/Elev= 30
  4395.7  332.87  4536.6  328.28  4564.9  324.27  4678.3  316.14  4748.6  315.80
  4777.2  313.35  4791.5  314.05  4799.2  316.57  4820.1  316.25  4877.2  312.45
  4905.9  314.65  4947.5  314.74  4976.1  316.23  4983.8  314.63  4990.3  309.97
  5001.6  305.79  5004.4  305.29  5007.6  305.79  5011.2  306.70  5018.9  312.96
  5025.5  313.90  5033.2  316.64  5089.2  315.20  5096.9  316.61  5190.7  320.79
  5295.8  326.45  5366.1  331.36  5416.3  336.08  5437.5  336.49  5460.0  338.49
#Mann=5,-1,0
  4395.7    0.16       0  4905.9    0.12       0  5001.6    0.07       0
  5007.6    0.12       0  5190.7    0.16       0
Bank Sta=5001.6,5007.6
Exp/Cntr=0.3,0.1

Type RM Length L Ch R = 1,16792,587,587,587
BEGIN DESCRIPTION:
SPRING BRANCH 28.0
END DESCRIPTION:
XS GIS Cut Line= 3
      3570049.58     10679810.16      3569649.61     10679410.19
      3569449.60     10679210.18
#Sta/Elev= 30
  4442.6  332.99  4456.7  332.25  4470.9  330.27  4555.7  325.15  4569.8  323.44
  4612.3  321.27  4626.4  319.37  4668.8  316.66  4782.0  314.70  4838.5  312.29
  4866.8  312.92  4881.0  314.16  4923.4  314.07  4965.8  315.52  4970.5  315.03
  4980.0  314.04  4991.1  305.25  4993.9  304.75  4997.1  305.25  5004.7  307.71
  5011.8  307.71  5022.4  313.68  5036.5  314.43  5064.8  313.86  5121.4  316.63
  5135.5  318.22  5149.7  317.86  5157.8  318.96  5234.5  324.54  5291.1  331.09
#Mann=5,-1,0
  4442.6    0.16       0  4970.5    0.12       0  4991.1    0.07       0
  4997.1    0.12       0  5157.8    0.16       0
Bank Sta=4991.1,4997.1
Exp/Cntr=0.3,0.1

Type RM Length L Ch R = 1,16205,1278,1278,1278
BEGIN DESCRIPTION:
SPRING BRANCH 26.0
END DESCRIPTION:
XS GIS Cut Line= 2
      3570583.33     10679728.04      3569611.08     10678547.45
#Sta/Elev= 30
  4324.3  345.52  4567.6  344.34  4658.7  340.55  4781.0  332.69  4872.5  326.18
  4907.6  320.74  4915.5  321.87  4950.7  318.43  4979.3  313.76  4985.8  310.34
  4990.7  304.35  4993.4  303.85  4996.7  304.35  5008.0  306.79  5014.5  312.43
  5028.8  314.30  5212.1  311.73  5255.6  313.70  5312.9  310.79  5327.3  312.68
  5380.1  314.22  5419.8  314.63  5518.8  320.17  5625.7  329.57  5675.2  332.01
  5696.0  333.91  5703.9  336.51  5817.2  339.47  5831.6  341.74  5853.7  340.23
#Mann=6,-1,0
  4324.3    0.05       0  4781.0    0.16       0  4990.7    0.07       0
  4996.7    0.16       0  5212.1    0.12       0  5380.1    0.16       0
Bank Sta=4990.7,4996.7
Exp/Cntr=0.3,0.1

Type RM Length L Ch R = 1,14927,499,499,499
BEGIN DESCRIPTION:
SPRING BRANCH 24.0
END DESCRIPTION:
XS GIS Cut Line= 2
      3571034.71     10678776.65      3569645.83     10678262.76
#Sta/Elev= 30
  4089.7  347.45  4091.9  346.00  4122.3  344.06  4127.6  345.19  4137.8  342.97
  4208.1  336.85  4263.6  334.03  4319.1  328.98  4340.4  329.35  4372.4  324.70
  4440.7  319.66  4538.5  315.43  4637.5  311.77  4873.3  310.17  4919.2  311.05
  4969.5  312.29  4980.1  307.30  4998.5  301.73  5001.2  301.23  5004.5  301.73
  5011.4  310.78  5033.4  321.31  5041.8  321.16  5054.8  324.23  5102.6  329.12
  5173.8  331.84  5249.3  332.95  5304.8  331.76  5507.0  336.80  5570.6  339.81
#Mann=7,-1,0
  4089.7    0.16       0  4538.5    0.05       0  4873.3    0.16       0
  4919.2    0.12       0  4998.5    0.07       0  5004.5    0.12       0
  5173.8    0.16       0
Bank Sta=4998.5,5004.5
Exp/Cntr=0.3,0.1

Type RM Length L Ch R = 1,14428,459,459,459
BEGIN DESCRIPTION:
SPRING BRANCH 23.0
END DESCRIPTION:
XS GIS Cut Line= 3
      3571051.96     10678554.98      3570565.83     10678207.75
      3569812.64     10678220.73
#Sta/Elev= 30
  4321.8  334.86  4355.6  334.15  4412.2  330.27  4456.4  330.28  4462.5  329.05
  4484.4  328.89  4613.7  321.98  4764.9  317.76  4857.0  313.86  4871.8  311.21
  4880.2  310.94  4892.7  311.51  4925.4  309.50  4975.4  310.92  4985.4  303.55
  4995.4  300.97  5002.4  300.72  5005.2  300.22  5008.4  300.72  5025.4  310.33
  5185.5  310.85  5229.2  313.55  5265.5  314.73  5350.7  321.13  5435.5  325.85
  5515.5  326.05  5545.5  327.14  5555.5  329.88  5585.5  327.89  5672.5  331.75
#Mann=5,-1,0
  4321.8    0.16       0  4880.2    0.12       0  5002.4    0.07       0
  5008.4    0.12       0  5229.2    0.16       0
Bank Sta=5002.4,5008.4
Exp/Cntr=0.3,0.1