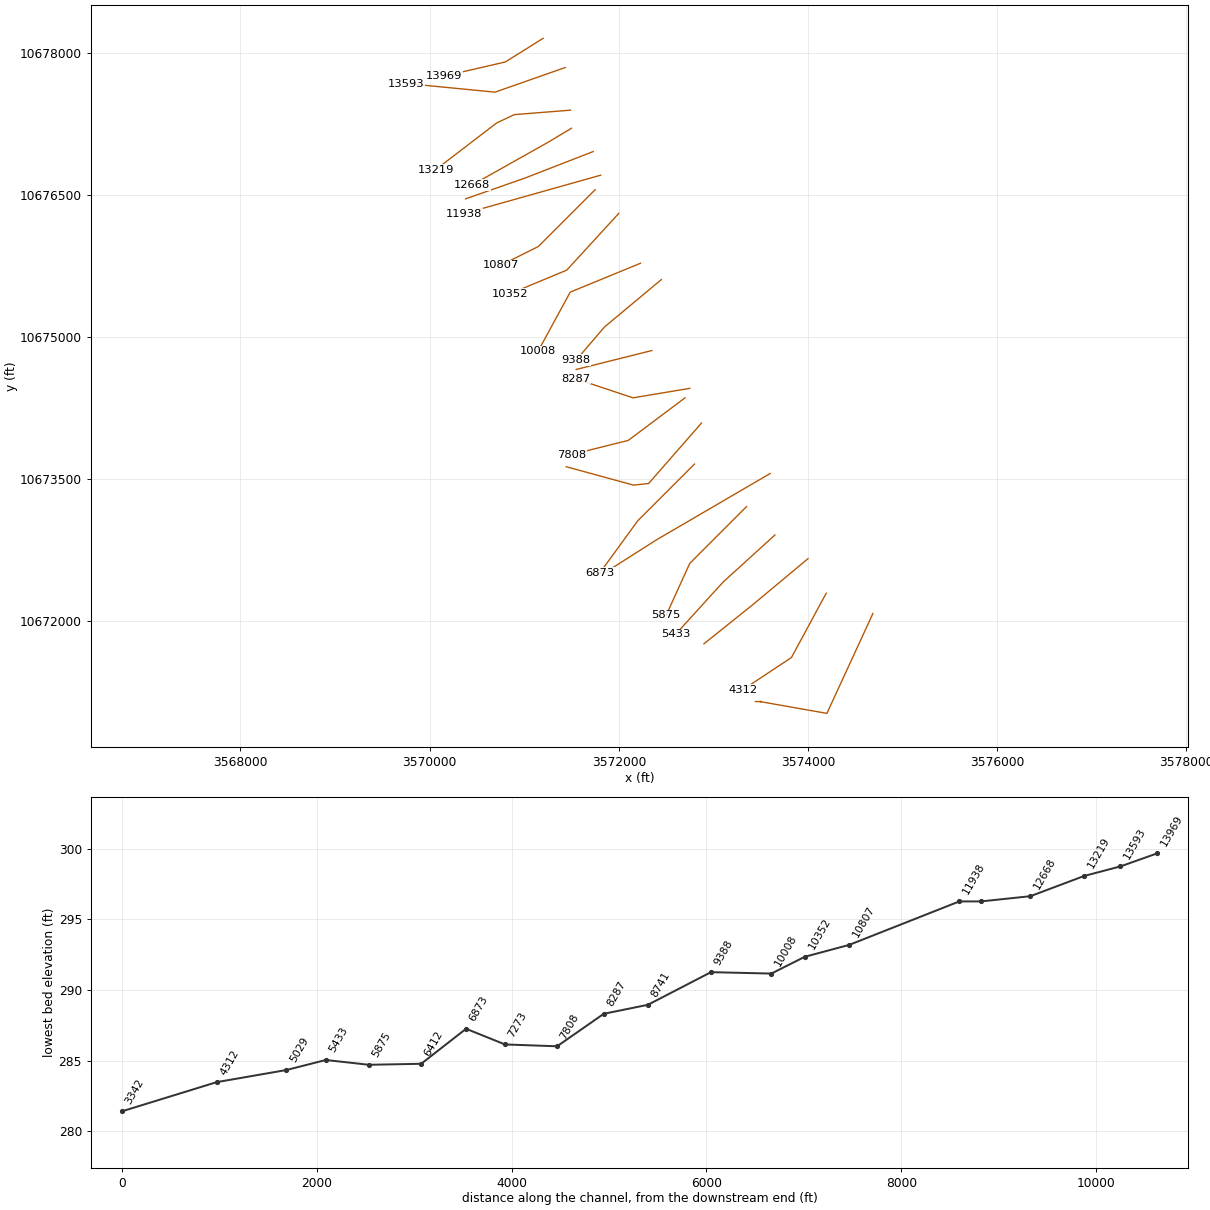
HEC-RAS study SPRING BRANCH.prj: SPRING BRANCH Base Level Engineering

--- SPRING BRANCH.g01 (geometry) --- (continued)

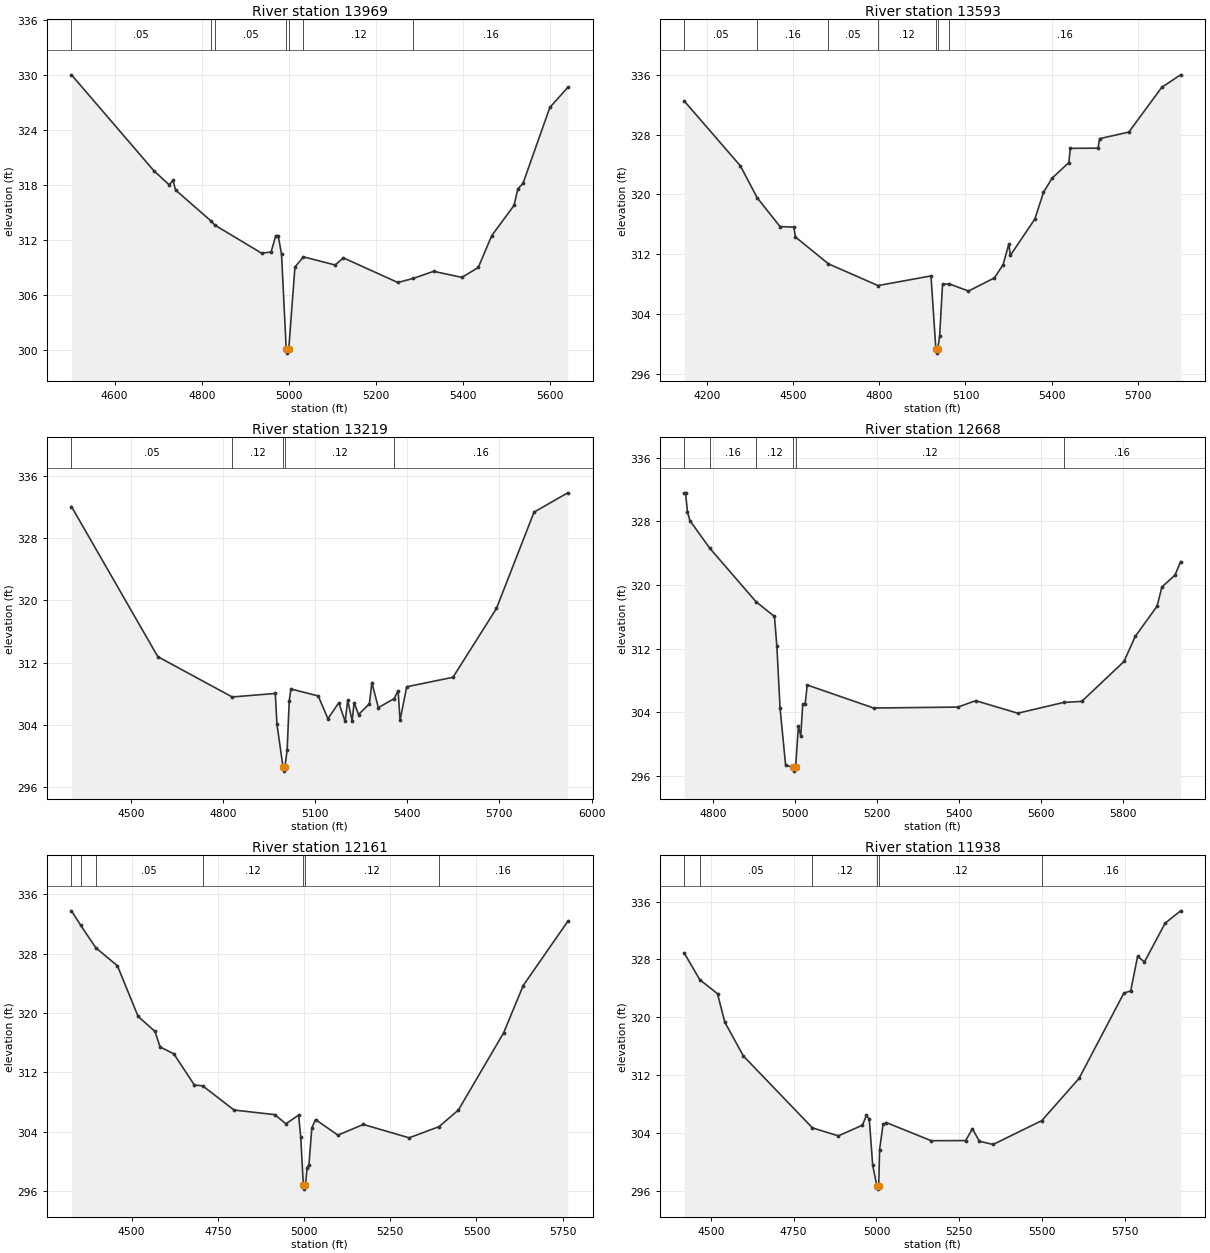
Type RM Length L Ch R = 1,13969,376,376,376
BEGIN DESCRIPTION:
SPRING BRANCH 22.0
END DESCRIPTION:
XS GIS Cut Line= 3
      3571199.62     10678160.20      3570799.61     10677910.19
      3570149.60     10677760.19
#Sta/Elev= 30
  4501.1  330.05  4689.8  319.60  4725.2  318.04  4734.0  318.53  4739.9  317.48
  4820.5  314.13  4830.2  313.64  4937.4  310.58  4959.2  310.71  4969.9  312.49
  4975.4  312.49  4983.1  310.50  4993.8  300.17  4996.5  299.67  4999.8  300.17
  5013.9  309.07  5033.4  310.18  5106.2  309.29  5125.0  310.07  5249.9  307.38
  5285.7  307.83  5332.0  308.60  5397.0  307.94  5434.6  309.02  5465.4  312.49
  5516.7  315.80  5525.3  317.59  5537.3  318.21  5598.8  326.49  5639.9  328.67
#Mann=7,-1,0
  4501.1    0.05       0  4820.5    0.16       0  4830.2    0.05       0
  4993.8   0.035       0  4999.8    0.05       0  5033.4    0.12       0
  5285.7    0.16       0
Bank Sta=4993.8,4999.8
Exp/Cntr=0.3,0.1

Type RM Length L Ch R = 1,13593,374,374,374
BEGIN DESCRIPTION:
SPRING BRANCH 21.0
END DESCRIPTION:
XS GIS Cut Line= 3
      3571433.88     10677851.84      3570691.70     10677591.43
      3569754.36     10677682.56
#Sta/Elev= 30
  4121.0  332.51  4316.3  323.83  4374.7  319.56  4454.1  315.71  4502.6  315.62
  4507.9  314.31  4622.9  310.71  4795.5  307.80  4980.0  309.09  4997.1  299.25
  4999.8  298.75  5003.1  299.25  5010.1  300.99  5020.2  307.99  5043.6  308.02
  5110.6  307.07  5201.0  308.83  5231.1  310.60  5251.2  313.38  5256.4  311.85
  5341.7  316.71  5371.8  320.29  5402.0  322.20  5460.2  324.28  5465.2  326.18
  5562.1  326.21  5567.1  327.48  5669.0  328.36  5783.7  334.36  5849.3  336.03
#Mann=7,-1,0
  4121.0    0.05       0  4374.7    0.16       0  4622.9    0.05       0
  4795.5    0.12       0  4997.1    0.07       0  5003.1    0.12       0
  5043.6    0.16       0
Bank Sta=4997.1,5003.1
Exp/Cntr=0.3,0.1

Type RM Length L Ch R = 1,13219,551,551,551
BEGIN DESCRIPTION:
SPRING BRANCH 20.0
END DESCRIPTION:
XS GIS Cut Line= 4
      3571489.60     10677400.92      3570895.80     10677354.04
      3570708.30     10677265.50      3570063.56     10676771.55
#Sta/Elev= 30
  4307.2  332.07  4588.1  312.78  4830.3  307.60  4970.5  308.05  4976.0  304.11
  4995.8  298.57  4998.5  298.07  5001.8  298.57  5009.2  300.84  5016.0  307.12
  5021.5  308.63  5110.2  307.73  5141.8  304.81  5177.2  306.85  5198.0  304.45
  5206.2  307.20  5220.7  304.52  5227.0  306.86  5241.5  305.34  5276.9  306.73
  5284.9  309.45  5305.9  306.23  5357.1  307.38  5370.3  308.40  5376.6  304.60
  5398.3  308.91  5548.9  310.13  5690.3  318.97  5812.7  331.35  5922.4  333.83
#Mann=5,-1,0
  4307.2    0.05       0  4830.3    0.12       0  4995.8    0.07       0
  5001.8    0.12       0  5357.1    0.16       0
Bank Sta=4995.8,5001.8
Exp/Cntr=0.3,0.1

Type RM Length L Ch R = 1,12668,507,507,507
BEGIN DESCRIPTION:
SPRING BRANCH 19.0
END DESCRIPTION:
XS GIS Cut Line= 3
      3571499.58     10677210.17      3571249.61     10677060.19
      3570449.60     10676610.18
#Sta/Elev= 30
  4730.1  331.57  4733.0  331.57  4737.8  329.19  4743.7  328.08  4791.8  324.64
  4904.6  317.91  4949.7  316.05  4955.5  312.39  4963.3  304.61  4976.9  297.37
  4995.3  297.14  4998.0  296.64  5001.3  297.14  5008.0  302.26  5013.8  301.07
  5018.7  305.06  5024.5  305.06  5029.6  307.45  5191.5  304.56  5396.7  304.68
  5440.1  305.48  5542.7  303.91  5654.4  305.26  5698.5  305.39  5801.5  310.40
  5828.9  313.54  5882.1  317.34  5893.9  319.75  5925.8  321.24  5939.5  322.94
#Mann=6,-1,0
  4730.1    0.05       0  4791.8    0.16       0  4904.6    0.12       0
  4995.3    0.07       0  5001.3    0.12       0  5654.4    0.16       0
Bank Sta=4995.3,5001.3
Exp/Cntr=0.3,0.1

Type RM Length L Ch R = 1,12161,223,223,223
BEGIN DESCRIPTION:
SPRING BRANCH 18.0
END DESCRIPTION:
XS GIS Cut Line= 3
      3571729.10     10676963.40      3571005.18     10676682.17
      3570380.18     10676463.42
#Sta/Elev= 30
  4325.9  333.75  4352.9  331.78  4396.4  328.78  4459.2  326.34  4519.0  319.54
  4568.1  317.50  4582.8  315.42  4622.6  314.49  4682.4  310.28  4706.0  310.19
  4797.4  306.92  4915.4  306.30  4947.6  305.07  4984.4  306.24  4990.5  303.32
  4998.2  296.77  5001.0  296.27  5004.2  296.77  5009.0  299.15  5014.3  299.55
  5022.7  304.50  5033.4  305.64  5098.4  303.54  5172.0  304.98  5304.9  303.18
  5391.2  304.68  5447.5  306.91  5578.8  317.32  5635.6  323.69  5764.7  332.33
#Mann=7,-1,0
  4325.9    0.05       0  4352.9    0.16       0  4396.4    0.05       0
  4706.0    0.12       0  4998.2    0.07       0  5004.2    0.12       0
  5391.2    0.16       0
Bank Sta=4998.2,5004.2
Exp/Cntr=0.3,0.1

Type RM Length L Ch R = 1,11938,1131,1131,1131
BEGIN DESCRIPTION:
SPRING BRANCH 17.0
END DESCRIPTION:
XS GIS Cut Line= 2
      3571807.25     10676713.41      3570364.56     10676307.17
#Sta/Elev= 30
  4419.8  328.87  4466.5  325.20  4520.0  323.27  4542.0  319.34  4598.4  314.65
  4806.8  304.73  4884.9  303.63  4957.6  305.10  4969.9  306.48  4978.4  305.92
  4988.7  299.57  5000.9  296.77  5003.7  296.27  5006.9  296.77  5009.5  301.73
  5019.9  305.20  5030.3  305.46  5165.4  302.96  5269.2  302.98  5290.0  304.60
  5310.8  302.89  5352.4  302.44  5499.5  305.74  5612.1  311.58  5747.1  323.34
  5767.9  323.66  5788.7  328.42  5809.5  327.66  5871.8  333.01  5918.6  334.72
#Mann=6,-1,0
  4419.8    0.16       0  4466.5    0.05       0  4806.8    0.12       0
  5000.9    0.07       0  5006.9    0.12       0  5499.5    0.16       0
Bank Sta=5000.9,5006.9
Exp/Cntr=0.3,0.1

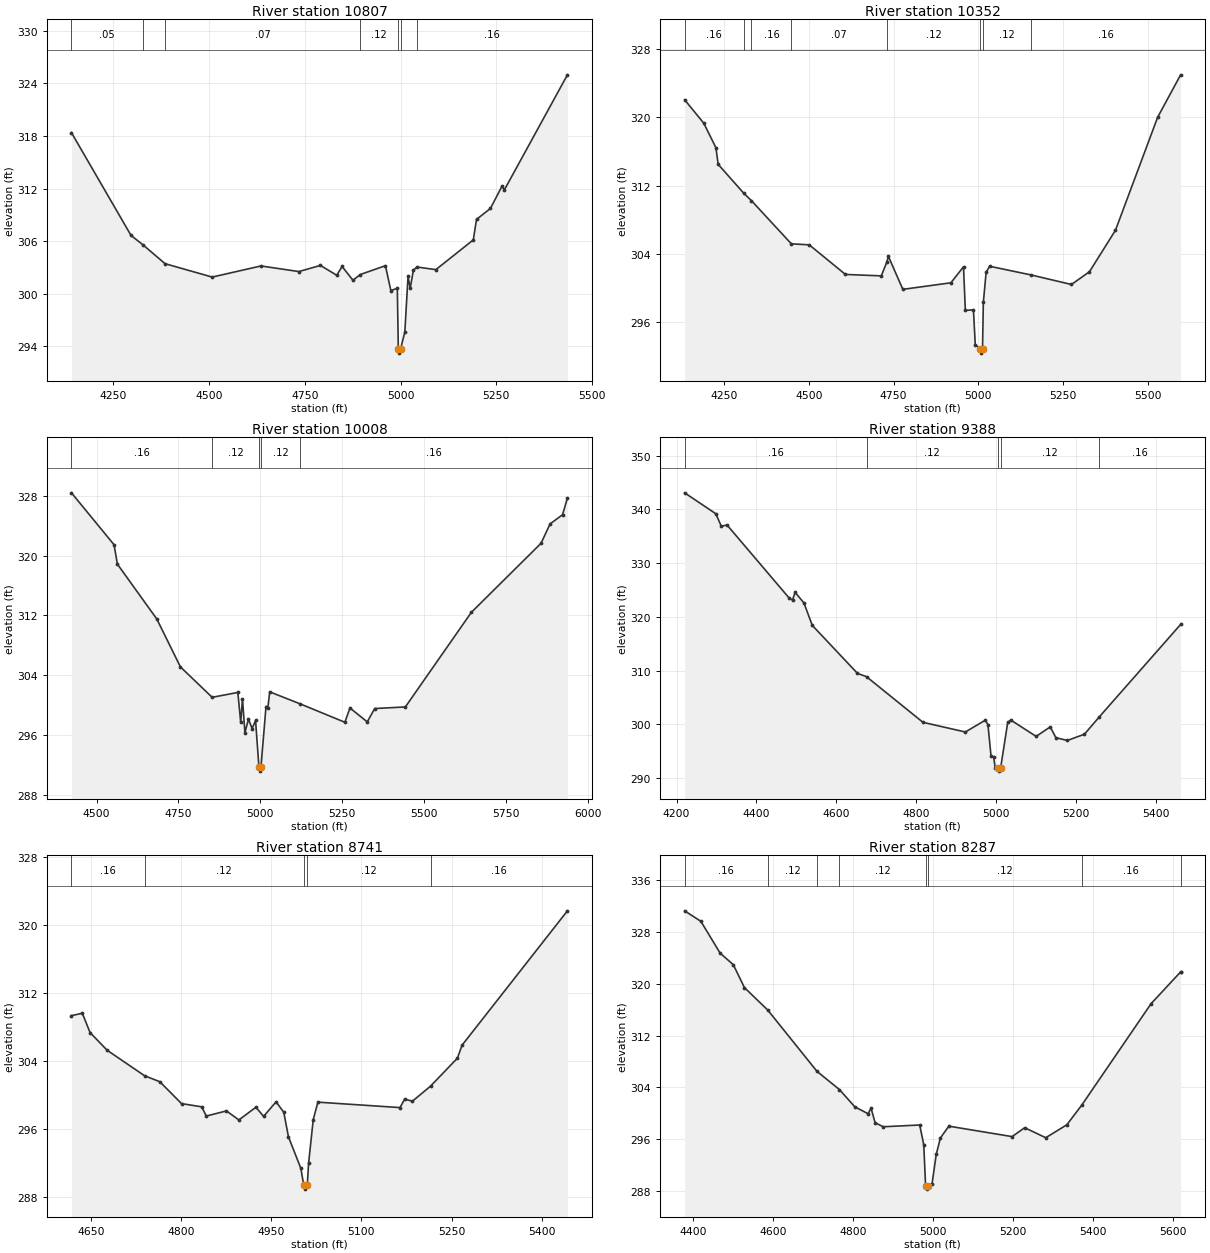
Type RM Length L Ch R = 1,10807,455,455,455
BEGIN DESCRIPTION:
SPRING BRANCH 16.0
END DESCRIPTION:
XS GIS Cut Line= 3
      3571749.61     10676560.19      3571149.61     10675960.19
      3570749.65     10675760.21
#Sta/Elev= 30
  4140.3  318.38  4295.9  306.64  4327.0  305.57  4384.8  303.41  4508.0  301.88
  4635.3  303.15  4734.3  302.51  4790.8  303.21  4833.3  302.09  4847.4  303.09
  4875.7  301.51  4894.7  302.17  4960.5  303.18  4974.7  300.34  4991.6  300.60
  4994.2  293.69  4997.0  293.19  5000.2  293.69  5011.2  295.59  5019.6  301.96
  5025.2  300.60  5033.6  302.66  5042.8  303.03  5092.3  302.73  5190.1  306.13
  5198.5  308.47  5234.8  309.72  5265.5  312.30  5271.1  311.83  5436.0  324.99
#Mann=7,-1,0
  4140.3    0.05       0  4327.0    0.16       0  4384.8    0.07       0
  4894.7    0.12       0  4994.2    0.07       0  5000.2    0.12       0
  5042.8    0.16       0
Bank Sta=4994.2,5000.2
Exp/Cntr=0.3,0.1

Type RM Length L Ch R = 1,10352,344,344,344
BEGIN DESCRIPTION:
SPRING BRANCH 15.0
END DESCRIPTION:
XS GIS Cut Line= 3
      3571999.60     10676310.18      3571449.61     10675710.19
      3570849.63     10675460.20
#Sta/Elev= 30
  4133.5  322.06  4189.9  319.32  4225.7  316.45  4232.5  314.49  4308.0  311.10
  4330.7  310.23  4448.4  305.17  4501.3  305.05  4608.0  301.58  4714.0  301.41
  4730.0  303.01  4735.0  303.69  4777.5  299.83  4919.4  300.60  4956.6  302.48
  4962.0  297.36  4985.9  297.43  4991.3  293.34  5006.7  292.85  5009.5  292.35
  5012.7  292.85  5015.1  298.29  5023.3  301.81  5033.5  302.54  5156.0  301.52
  5275.1  300.40  5328.2  301.89  5405.1  306.76  5529.7  320.02  5597.4  324.99
#Mann=8,-1,0
  4133.5    0.16       0  4308.0    0.05       0  4330.7    0.16       0
  4448.4    0.07       0  4730.0    0.12       0  5006.7    0.07       0
  5012.7    0.12       0  5156.0    0.16       0
Bank Sta=5006.7,5012.7
Exp/Cntr=0.3,0.1

Type RM Length L Ch R = 1,10008,620,620,620
BEGIN DESCRIPTION:
SPRING BRANCH 14.0
END DESCRIPTION:
XS GIS Cut Line= 3
      3572229.17     10675782.88      3571486.08     10675477.30
      3571146.56     10674853.71
#Sta/Elev= 30
  4423.6  328.41  4553.6  321.46  4563.7  318.87  4684.2  311.51  4756.1  305.11
  4852.9  301.04  4931.3  301.69  4940.1  297.69  4945.5  300.85  4952.9  296.31
  4963.8  298.12  4974.8  296.86  4985.4  297.94  4995.8  291.66  4998.5  291.16
  5001.8  291.66  5017.3  299.81  5022.8  299.58  5028.6  301.77  5121.7  300.16
  5257.9  297.70  5273.5  299.61  5326.3  297.75  5349.0  299.54  5442.5  299.75
  5643.9  312.41  5856.6  321.66  5884.2  324.25  5922.2  325.48  5937.1  327.71
#Mann=5,-1,0
  4423.6    0.16       0  4852.9    0.12       0  4995.8    0.07       0
  5001.8    0.12       0  5121.7    0.16       0
Bank Sta=4995.8,5001.8
Exp/Cntr=0.3,0.1

Type RM Length L Ch R = 1,9388,647,647,647
BEGIN DESCRIPTION:
SPRING BRANCH 13.0
END DESCRIPTION:
XS GIS Cut Line= 3
      3572449.59     10675610.18      3571849.61     10675110.19
      3571549.60     10674760.18
#Sta/Elev= 30
  4220.3  343.10  4298.4  339.20  4312.1  336.87  4326.4  337.11  4482.6  323.45
  4490.4  323.13  4496.9  324.56  4519.0  322.59  4539.9  318.41  4653.1  309.47
  4675.7  308.85  4817.1  300.35  4923.2  298.55  4973.3  300.75  4979.8  299.91
  4987.6  294.03  4994.1  293.89  4998.1  291.80  5005.4  291.76  5008.2  291.26
  5011.4  291.76  5029.3  300.32  5037.0  300.77  5100.6  297.73  5135.8  299.50
  5150.0  297.49  5178.6  296.97  5221.4  298.13  5258.7  301.37  5462.3  318.58
#Mann=5,-1,0
  4220.3    0.16       0  4675.7    0.12       0  5005.4    0.07       0
  5011.4    0.12       0  5258.7    0.16       0
Bank Sta=5005.4,5011.4
Exp/Cntr=0.3,0.1

Type RM Length L Ch R = 1,8741,454,454,454
BEGIN DESCRIPTION:
SPRING BRANCH 12.0
END DESCRIPTION:
XS GIS Cut Line= 3
      3572349.61     10674860.19      3571949.61     10674760.19
      3571549.63     10674660.19
#Sta/Elev= 30
  4618.0  309.33  4636.0  309.62  4648.9  307.35  4677.3  305.27  4739.6  302.27
  4764.9  301.57  4801.0  299.00  4834.5  298.62  4842.2  297.54  4875.7  298.14
  4896.3  297.08  4924.7  298.57  4937.5  297.50  4958.2  299.21  4971.0  297.98
  4978.8  295.09  4999.4  291.39  5004.1  289.45  5006.9  288.95  5010.1  289.45
  5012.3  292.02  5020.0  297.12  5027.7  299.17  5164.3  298.53  5172.0  299.53
  5184.9  299.28  5215.0  301.05  5259.7  304.34  5267.4  305.86  5442.6  321.65
#Mann=5,-1,0
  4618.0    0.16       0  4739.6    0.12       0  5004.1    0.07       0
  5010.1    0.12       0  5215.0    0.16       0
Bank Sta=5004.1,5010.1
Exp/Cntr=0.3,0.1

Type RM Length L Ch R = 1,8287,479,479,479
BEGIN DESCRIPTION:
SPRING BRANCH 11.0
END DESCRIPTION:
XS GIS Cut Line= 3
      3572749.63     10674460.19      3572149.61     10674360.19
      3571549.56     10674560.20
#Sta/Elev= 30
  4379.1  331.23  4419.7  329.61  4467.8  324.71  4500.8  322.92  4528.7  319.39
  4587.1  315.92  4710.2  306.47  4766.2  303.67  4804.9  301.00  4837.9  299.94
  4845.5  300.78  4855.6  298.55  4875.9  297.93  4967.1  298.20  4977.3  295.16
  4981.9  288.81  4984.6  288.31  4987.9  288.81  4997.9  289.08  5008.5  293.66
  5019.0  296.21  5040.1  298.02  5198.2  296.41  5229.8  297.78  5282.5  296.24
  5335.2  298.23  5372.3  301.24  5546.1  316.92  5619.8  321.80  5619.9  321.80
#Mann=8,-1,0
  4379.1    0.16       0  4587.1    0.12       0  4710.2    0.16       0
  4766.2    0.12       0  4981.9    0.07       0  4987.9    0.12       0
  5372.3    0.16       0  5619.8    0.07       0
Bank Sta=4981.9,4987.9
Exp/Cntr=0.3,0.1

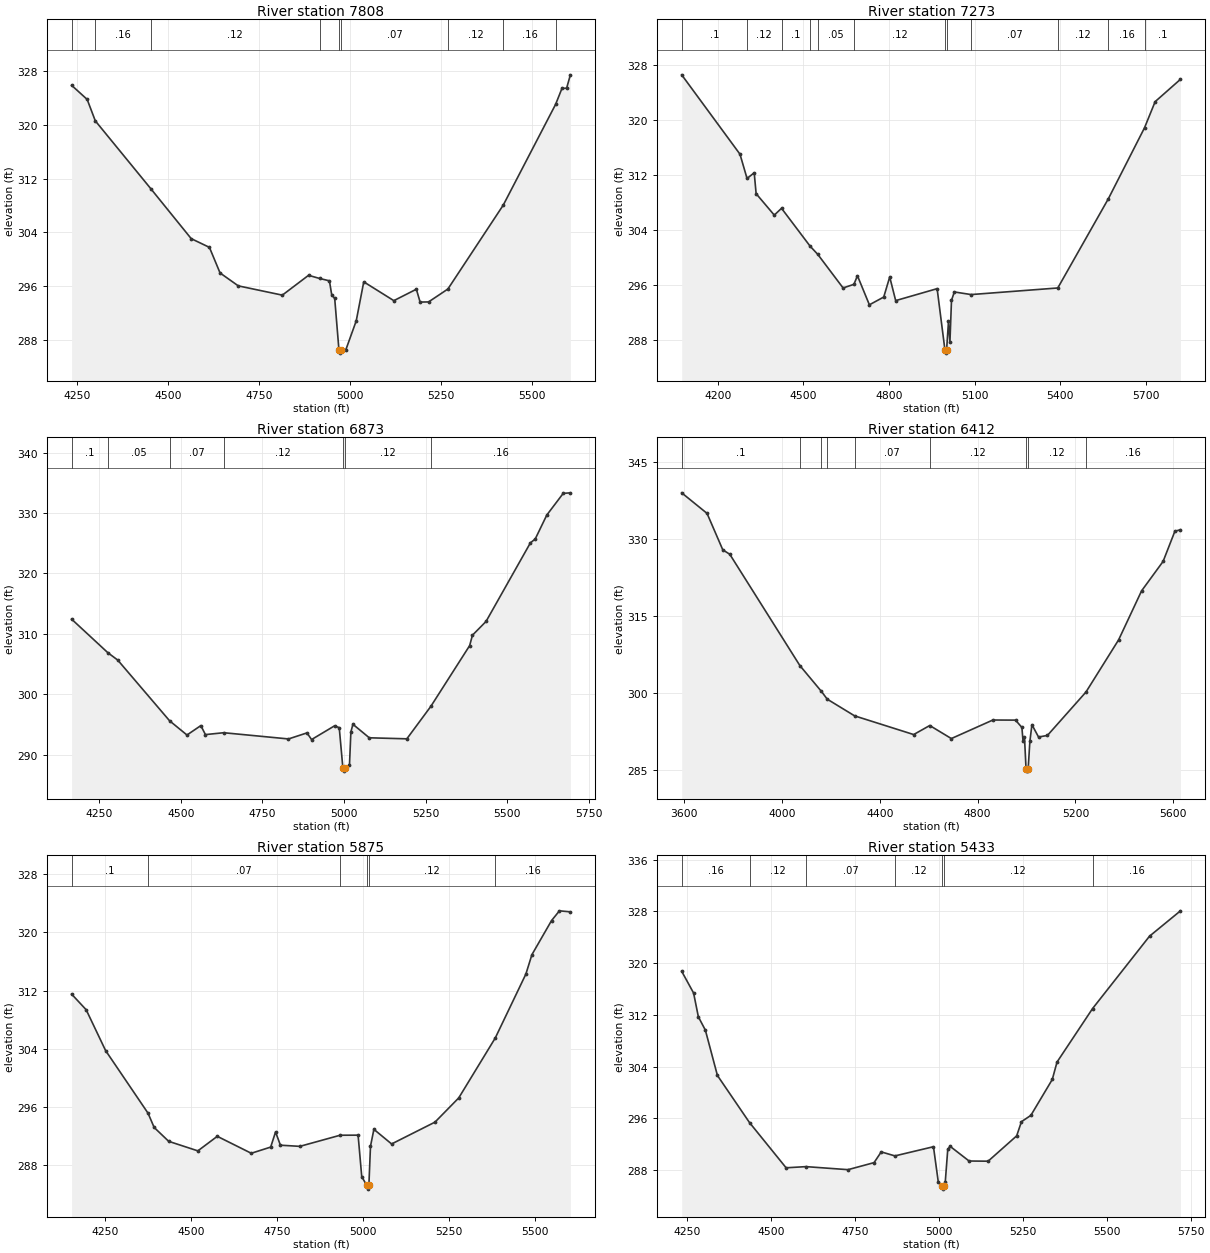
Type RM Length L Ch R = 1,7808,535,535,535
BEGIN DESCRIPTION:
SPRING BRANCH 10.0
END DESCRIPTION:
XS GIS Cut Line= 3
      3572699.58     10674360.17      3572099.61     10673910.19
      3571499.64     10673760.20
#Sta/Elev= 30
  4236.2  325.87  4278.9  323.77  4301.2  320.58  4453.5  310.48  4564.3  303.05
  4614.3  301.75  4643.5  297.94  4693.5  296.02  4814.3  294.64  4886.2  297.59
  4916.8  297.12  4943.5  296.77  4949.7  294.72  4958.0  294.15  4969.6  286.51
  4972.4  286.01  4975.6  286.51  4988.7  286.53  5017.1  290.82  5037.7  296.62
  5120.2  293.82  5182.0  295.52  5192.3  293.61  5215.5  293.63  5268.5  295.55
  5420.4  308.04  5564.0  323.03  5581.4  325.40  5594.3  325.45  5604.6  327.43
#Mann=9,-1,0
  4236.2     0.1       0  4301.2    0.16       0  4453.5    0.12       0
  4916.8    0.07       0  4969.6    0.07       0  4975.6    0.07       0
  5268.5    0.12       0  5420.4    0.16       0  5564.0     0.1       0
Bank Sta=4969.6,4975.6
Exp/Cntr=0.3,0.1

Type RM Length L Ch R = 1,7273,400,400,400
BEGIN DESCRIPTION:
SPRING BRANCH 9.0
END DESCRIPTION:
XS GIS Cut Line= 4
      3572874.09     10674093.85      3572315.03     10673454.92
      3572155.31     10673437.56      3571444.02     10673631.87
#Sta/Elev= 30
  4073.6  326.63  4277.8  315.08  4302.5  311.55  4327.6  312.38  4334.3  309.34
  4397.9  306.22  4423.3  307.21  4523.4  301.70  4550.2  300.51  4638.9  295.62
  4676.8  296.15  4689.2  297.40  4731.0  293.17  4781.3  294.30  4802.2  297.22
  4823.1  293.78  4968.3  295.52  4995.5  286.64  4998.2  286.14  5001.5  286.64
  5008.1  290.75  5013.1  287.71  5018.6  293.82  5028.6  295.04  5087.3  294.66
  5390.9  295.62  5568.0  308.60  5694.6  318.92  5731.9  322.73  5820.6  325.98
#Mann=12,-1,0
  4073.6     0.1       0  4302.5    0.12       0  4423.3     0.1       0
  4523.4    0.12       0  4550.2    0.05       0  4676.8    0.12       0
  4995.5    0.07       0  5001.5    0.12       0  5087.3    0.07       0
  5390.9    0.12       0  5568.0    0.16       0  5694.6     0.1       0
Bank Sta=4995.5,5001.5
Exp/Cntr=0.3,0.1

Type RM Length L Ch R = 1,6873,461,461,461
BEGIN DESCRIPTION:
SPRING BRANCH 8.0
END DESCRIPTION:
XS GIS Cut Line= 3
      3572799.61     10673660.19      3572199.61     10673060.19
      3571799.61     10672510.19
#Sta/Elev= 30
  4165.0  312.42  4275.9  306.87  4306.4  305.64  4465.4  295.58  4518.6  293.23
  4561.0  294.79  4575.1  293.30  4631.2  293.61  4829.7  292.58  4886.3  293.58
  4900.4  292.48  4971.1  294.76  4985.2  294.44  4996.4  287.75  4999.1  287.25
  5002.4  287.75  5016.6  288.28  5020.9  293.74  5027.1  295.01  5077.3  292.77
  5192.4  292.60  5266.1  297.99  5384.9  308.04  5393.4  309.76  5435.1  312.04
  5571.1  325.06  5585.8  325.69  5621.3  329.66  5671.6  333.25  5693.6  333.34
#Mann=7,-1,0
  4165.0     0.1       0  4275.9    0.05       0  4465.4    0.07       0
  4631.2    0.12       0  4996.4    0.07       0  5002.4    0.12       0
  5266.1    0.16       0
Bank Sta=4996.4,5002.4
Exp/Cntr=0.3,0.1

Type RM Length L Ch R = 1,6412,537,537,537
BEGIN DESCRIPTION:
SPRING BRANCH 7.0
END DESCRIPTION:
XS GIS Cut Line= 3
      3573599.58     10673560.17      3572399.61     10672860.19
      3571849.63     10672510.20
#Sta/Elev= 30
  3588.9  338.95  3692.6  334.95  3757.1  327.85  3785.7  326.99  4072.5  305.32
  4160.7  300.29  4184.5  298.78  4296.5  295.53  4538.2  291.89  4604.0  293.65
  4692.4  291.11  4862.3  294.72  4955.0  294.70  4981.1  293.27  4985.7  290.63
  4991.7  291.32  4998.0  285.27  5000.7  284.77  5004.0  285.27  5006.9  285.35
  5013.7  290.54  5022.1  293.81  5049.2  291.41  5085.6  291.72  5243.3  300.17
  5376.9  310.33  5470.9  319.87  5558.9  325.60  5607.2  331.48  5630.0  331.76
#Mann=9,-1,0
  3588.9     0.1       0  4072.5    0.12       0  4160.7     0.1       0
  4184.5    0.12       0  4296.5    0.07       0  4604.0    0.12       0
  4998.0    0.07       0  5004.0    0.12       0  5243.3    0.16       0
Bank Sta=4998,5004
Exp/Cntr=0.3,0.1

Type RM Length L Ch R = 1,5875,442,442,442
BEGIN DESCRIPTION:
SPRING BRANCH 6.0
END DESCRIPTION:
XS GIS Cut Line= 3
      3573349.61     10673210.19      3572749.61     10672610.19
      3572499.60     10672060.17
#Sta/Elev= 30
  4151.4  311.51  4193.8  309.36  4250.4  303.75  4374.0  295.14  4391.8  293.18
  4434.2  291.27  4519.1  289.96  4575.7  291.96  4674.7  289.63  4731.2  290.48
  4745.4  292.56  4759.5  290.74  4816.1  290.58  4933.6  292.11  4985.8  292.12
  4996.4  286.42  5011.2  285.20  5014.0  284.70  5017.2  285.20  5021.9  290.60
  5031.8  292.92  5083.4  290.91  5209.7  293.91  5278.9  297.24  5385.2  305.47
  5474.5  314.27  5492.0  316.93  5549.2  321.62  5572.2  322.96  5604.1  322.82
#Mann=6,-1,0
  4151.4     0.1       0  4374.0    0.07       0  4933.6    0.12       0
  5011.2    0.07       0  5017.2    0.12       0  5385.2    0.16       0
Bank Sta=5011.2,5017.2
Exp/Cntr=0.3,0.1

Type RM Length L Ch R = 1,5433,404,404,404
BEGIN DESCRIPTION:
SPRING BRANCH 5.0
END DESCRIPTION:
XS GIS Cut Line= 3
      3573649.63     10672910.21      3573099.61     10672410.19
      3572599.63     10671860.21
#Sta/Elev= 30
  4233.3  318.74  4268.8  315.37  4283.0  311.69  4303.9  309.63  4339.8  302.62
  4435.5  295.33  4544.5  288.34  4603.8  288.52  4729.0  288.05  4806.7  289.14
  4828.0  290.80  4868.8  290.18  4983.7  291.60  4997.9  286.21  5009.1  285.54
  5011.9  285.04  5015.1  285.54  5018.9  286.16  5026.3  291.19  5033.1  291.67
  5089.8  289.39  5146.6  289.36  5231.7  293.28  5245.9  295.47  5274.0  296.45
  5337.8  302.00  5352.0  304.70  5458.0  312.98  5627.7  324.17  5719.9  328.09
#Mann=7,-1,0
  4233.3    0.16       0  4435.5    0.12       0  4603.8    0.07       0
  4868.8    0.12       0  5009.1    0.07       0  5015.1    0.12       0
  5458.0    0.16       0
Bank Sta=5009.1,5015.1
Exp/Cntr=0.3,0.1

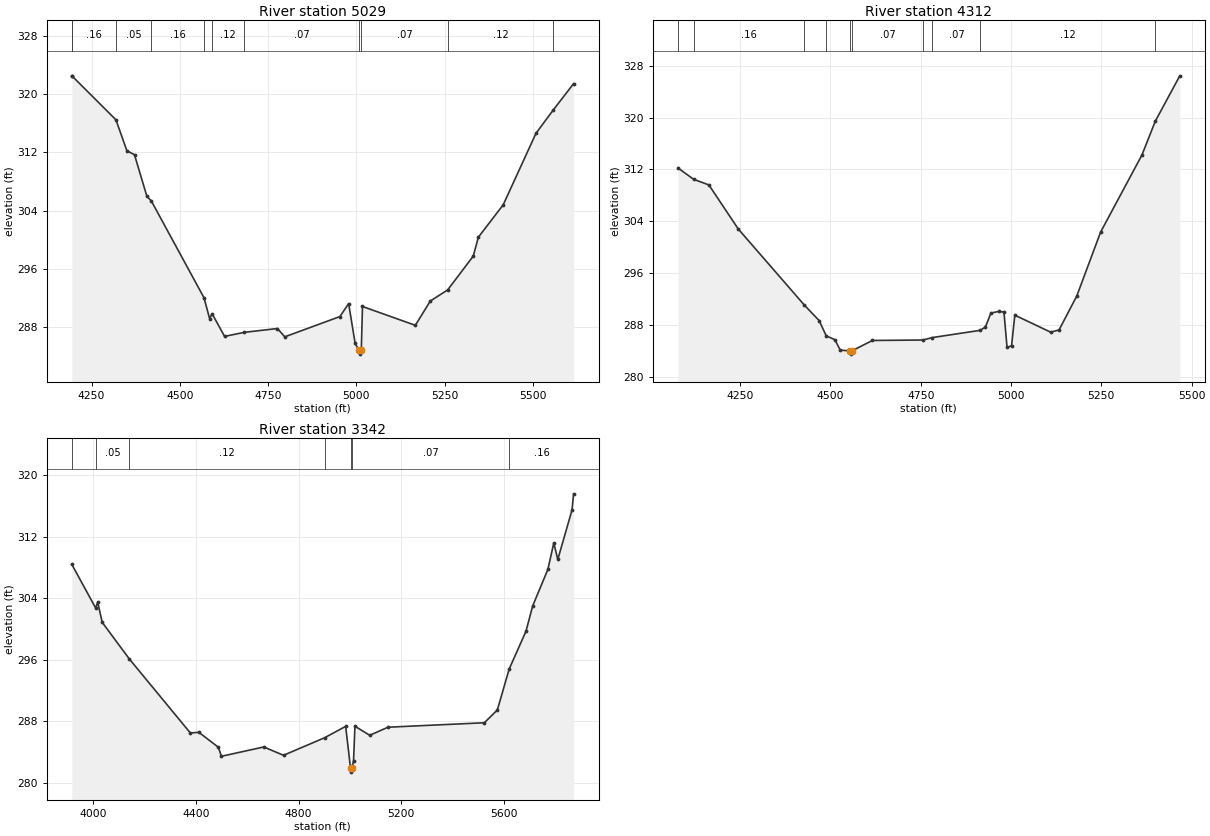
Type RM Length L Ch R = 1,5029,717,717,717
BEGIN DESCRIPTION:
SPRING BRANCH 4.0
END DESCRIPTION:
XS GIS Cut Line= 3
      3573999.60     10672660.18      3573399.61     10672160.19
      3572899.63     10671760.20
#Sta/Elev= 30
  4193.9  322.48  4194.3  322.48  4319.0  316.45  4350.1  312.21  4371.6  311.66
  4406.7  305.96  4419.1  305.34  4568.4  292.06  4584.4  289.19  4591.4  289.87
  4626.7  286.76  4683.0  287.32  4776.4  287.84  4797.2  286.70  4953.4  289.48
  4978.1  291.26  4996.5  285.80  5007.9  284.83  5010.7  284.33  5013.9  284.83
  5017.3  290.86  5167.0  288.28  5209.4  291.61  5258.5  293.13  5331.1  297.77
  5345.5  300.36  5415.9  304.80  5508.8  314.61  5557.4  317.78  5615.2  321.41
#Mann=11,-1,0
  4193.9     0.1       0  4194.3    0.16       0  4319.0    0.05       0
  4419.1    0.16       0  4568.4    0.07       0  4591.4    0.12       0
  4683.0    0.07       0  5007.9    0.07       0  5013.9    0.07       0
  5258.5    0.12       0  5557.4    0.16       0
Bank Sta=5007.9,5013.9
Exp/Cntr=0.3,0.1

Type RM Length L Ch R = 1,4312,970,970,970
BEGIN DESCRIPTION:
SPRING BRANCH 3.0
END DESCRIPTION:
XS GIS Cut Line= 3
      3574192.44     10672295.52      3573824.40     10671615.00
      3573310.85     10671274.95
#Sta/Elev= 30
  4077.6  312.23  4121.1  310.47  4163.2  309.61  4244.9  302.78  4428.0  291.02
  4468.5  288.66  4488.2  286.29  4512.2  285.70  4527.0  284.09  4553.0  283.97
  4555.8  283.47  4559.0  283.97  4616.0  285.58  4755.7  285.65  4782.2  286.03
  4915.0  287.15  4929.2  287.68  4944.2  289.82  4965.3  290.06  4980.3  289.98
  4988.9  284.50  5001.4  284.77  5010.4  289.49  5109.7  286.86  5132.9  287.21
  5181.9  292.44  5248.1  302.34  5362.4  314.23  5399.4  319.45  5467.2  326.46
#Mann=10,-1,0
  4077.6    0.05       0  4121.1    0.16       0  4428.0    0.12       0
  4488.2    0.07       0  4553.0    0.07       0  4559.0    0.07       0
  4755.7    0.12       0  4782.2    0.07       0  4915.0    0.12       0
  5399.4    0.16       0
Bank Sta=4553,4559
Exp/Cntr=0.3,0.1

Type RM Length L Ch R = 1,3342,1035,1035,1035
BEGIN DESCRIPTION:
Mapping XS d43eb96b
END DESCRIPTION:
XS GIS Cut Line= 5
      3574685.50     10672080.24      3574199.40     10671024.72
      3573491.07     10671149.72      3573504.96     10671149.72
      3573443.50     10671149.72
#Sta/Elev= 30
  3915.3  308.44  4008.3  302.76  4016.5  303.50  4034.0  300.89  4140.4  296.10
  4377.8  286.50  4410.8  286.59  4486.8  284.65  4498.9  283.47  4664.0  284.68
  4741.1  283.60  4901.1  285.88  4983.3  287.36  5002.3  281.91  5005.0  281.41
  5008.3  281.91  5014.0  282.92  5019.5  287.38  5077.1  286.20  5148.2  287.25
  5524.0  287.83  5574.7  289.49  5621.0  294.83  5686.4  299.73  5712.4  303.01
  5771.7  307.77  5794.9  311.21  5810.4  309.06  5865.9  315.50  5872.0  317.60
#Mann=7,-1,0
  3915.3    0.07       0  4008.3    0.05       0  4140.4    0.12       0
  4901.1    0.07       0  5002.3    0.07       0  5008.3    0.07       0
  5621.0    0.16       0
Bank Sta=5002.3,5008.3
Exp/Cntr=0.3,0.1