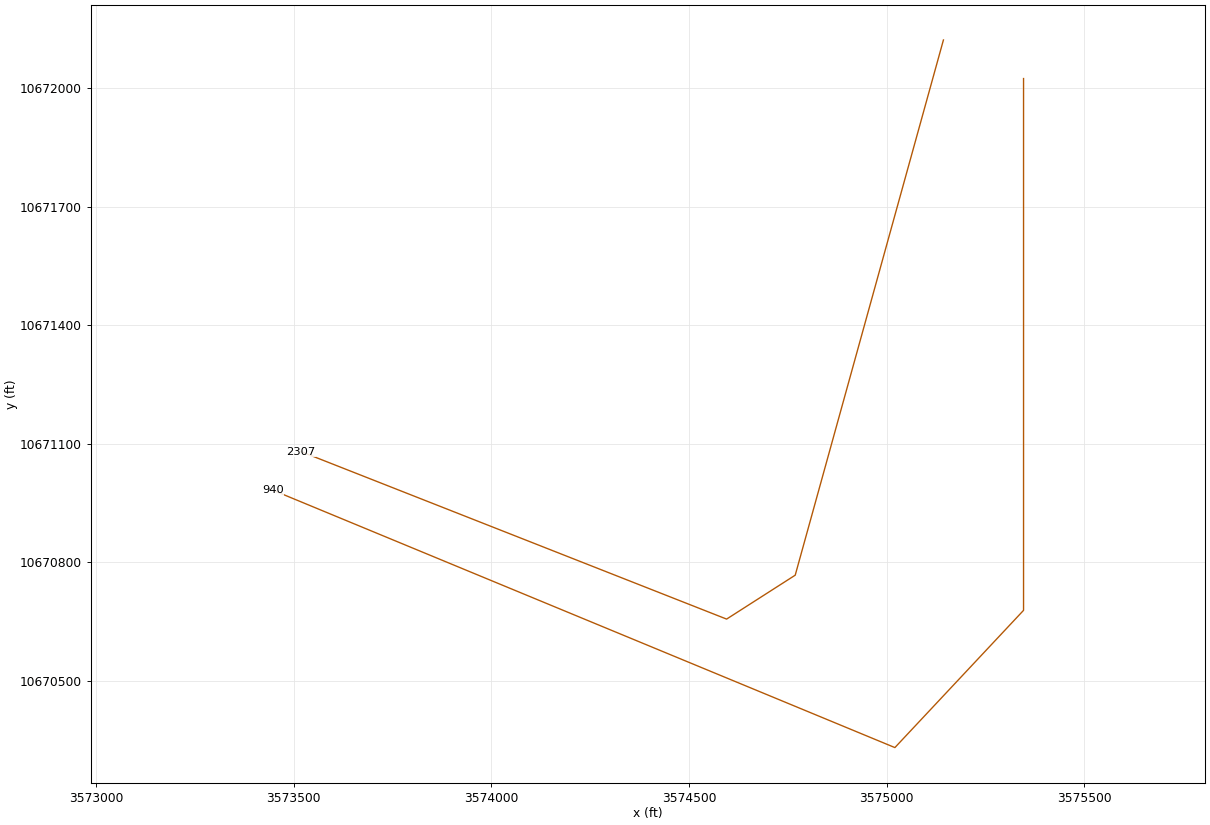
HEC-RAS study SPRING BRANCH.prj: SPRING BRANCH Base Level Engineering

--- SPRING BRANCH.g01 (geometry) --- (continued)

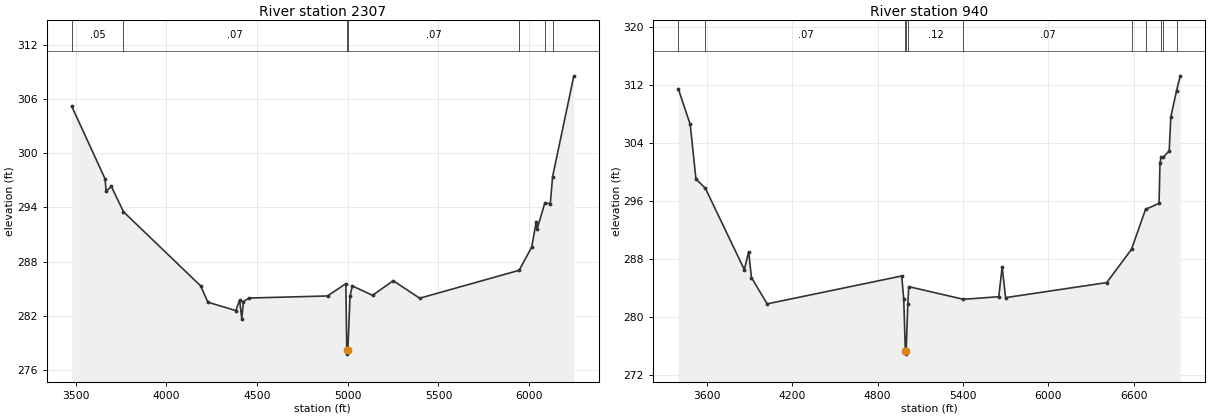
Type RM Length L Ch R = 1,2307,1367,1367,1367
BEGIN DESCRIPTION:
SPRING BRANCH 2.0
END DESCRIPTION:
XS GIS Cut Line= 4
      3575143.84     10672121.92      3574768.85     10670767.78
      3574595.24     10670656.67      3573518.82     10671080.29
#Sta/Elev= 30
  3478.2  305.19  3662.1  297.15  3667.3  295.79  3696.4  296.33  3763.3  293.52
  4189.0  285.31  4228.5  283.51  4382.7  282.58  4403.5  283.75  4415.6  281.65
  4424.2  283.58  4455.4  283.97  4888.2  284.20  4989.3  285.56  4994.3  278.26
  4997.1  277.76  5000.3  278.26  5012.5  284.20  5024.9  285.31  5136.5  284.27
  5250.3  285.89  5396.4  283.95  5944.7  287.04  6014.1  289.62  6038.5  292.39
  6043.8  291.62  6086.0  294.47  6116.4  294.42  6129.2  297.42  6246.2  308.57
#Mann=7,-1,0
  3478.2    0.05       0  3763.3    0.07       0  4994.3    0.07       0
  5000.3    0.07       0  5944.7    0.05       0  6086.0    0.07       0
  6129.2    0.16       0
Bank Sta=4994.3,5000.3
Exp/Cntr=0.3,0.1

Type RM Length L Ch R = 1,940,0,0,0
BEGIN DESCRIPTION:
SPRING BRANCH 1.0
END DESCRIPTION:
XS GIS Cut Line= 4
      3575346.54     10672024.32      3575346.54     10670678.80
      3575021.02     10670331.58      3573447.66     10670982.62
#Sta/Elev= 30
  3401.3  311.55  3485.4  306.61  3525.4  299.08  3591.8  297.79  3865.4  286.55
  3895.4  289.03  3915.4  285.46  4025.4  281.83  4970.0  285.68  4984.2  282.50
  4995.4  275.39  4998.1  274.89  5001.4  275.39  5012.8  281.84  5019.4  284.21
  5403.2  282.46  5651.2  282.82  5675.1  286.94  5699.0  282.69  6409.2  284.77
  6582.9  289.37  6681.5  294.88  6776.3  295.71  6782.7  301.24  6790.4  302.12
  6805.3  302.06  6847.6  302.98  6858.8  307.62  6899.2  311.28  6925.5  313.32
#Mann=11,-1,0
  3401.3    0.05       0  3591.8    0.07       0  4995.4    0.07       0
  5001.4    0.07       0  5012.8    0.12       0  5403.2    0.07       0
  6582.9    0.05       0  6681.5    0.07       0  6790.4    0.05       0
  6805.3    0.16       0  6899.2    0.05       0
Bank Sta=4995.4,5001.4
Exp/Cntr=0.3,0.1

Chan Stop Cuts=-1