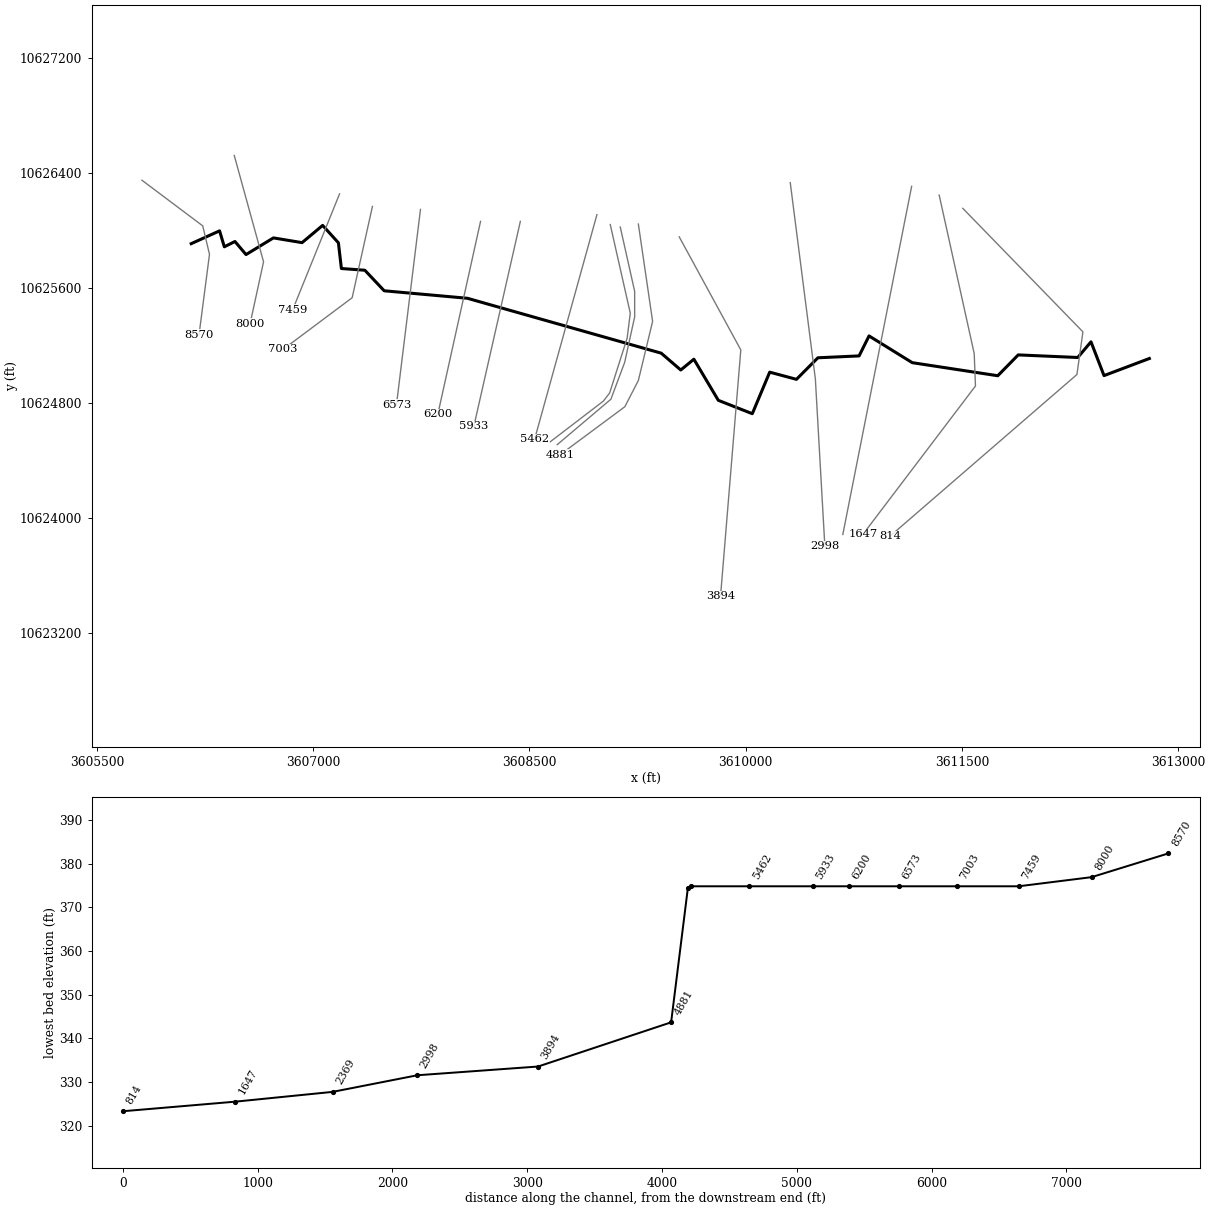
--- TANBARK BRANCH 1.prj (project) ---

Proj Title=TANBARK BRANCH 1 Base Level Engineering
Current Plan=p01
Default Exp/Contr=0.3,0.1
English Units
Geom File=g01
Flow File=f01
Plan File=p01
Y Axis Title=Elevation
X Axis Title(PF)=Main Channel Distance
X Axis Title(XS)=Station
BEGIN DESCRIPTION:
TANBARK BRANCH 1
END DESCRIPTION:
DSS Export Rating Curves= 0
DSS Export Rating Curve Sorted= 0
DSS Export Volume Flow Curves= 0
DXF OffsetX= 0
DXF OffsetY= 0
DXF ScaleX= 1
DXF ScaleY= 10

--- TANBARK BRANCH 1.p01 (plan) ---

Plan Title=Multiple Run
Short Identifier=Multiple
Geom File=g01
Flow File=f01
Subcritical Flow
K Sum by GR= 0
Std Step Tol= 0.01
Critical Tol= 0.01
Num of Std Step Trials= 20
Max Error Tol= 0.3
Flow Tol Ratio= 0.001
Split Flow NTrial= 30
Split Flow Tol= 0.02
Split Flow Ratio= 0.02
Log Output Level= 0
Friction Slope Method= 1
Unsteady Friction Slope Method= 2
Unsteady Bridges Friction Slope Method= 1
Parabolic Critical Depth
Global Vel Dist=  1 , 1 , 1
Global Log Level= 0
CheckData=True
Encroach Param= -1, 0, 0, 0
BEGIN DESCRIPTION:
Multiple Run
END DESCRIPTION:

--- TANBARK BRANCH 1.f01 (steady flow) ---

Flow Title=Multiple
Number of Profiles=7
Profile Names=10-year,25-year,50-year,1pct_min,100-year,1pct_plu,500-year
River Rch & RM= TANBARK BRANCH 1,Reach-1,8570
    1405    1930    2363    2112    2857    3864    4159
River Rch & RM= TANBARK BRANCH 1,Reach-1,5933
    2423    3433    4293    3911    5289    7153    8006
Boundary for River Rch & Prof#=TANBARK BRANCH 1,Reach-1,1
Up Type=0
Dn Type=3
Dn Slope=0.005
Boundary for River Rch & Prof#=TANBARK BRANCH 1,Reach-1,2
Up Type=0
Dn Type=3
Dn Slope=0.005
Boundary for River Rch & Prof#=TANBARK BRANCH 1,Reach-1,3
Up Type=0
Dn Type=3
Dn Slope=0.005
Boundary for River Rch & Prof#=TANBARK BRANCH 1,Reach-1,4
Up Type=0
Dn Type=3
Dn Slope=0.005
Boundary for River Rch & Prof#=TANBARK BRANCH 1,Reach-1,5
Up Type=0
Dn Type=3
Dn Slope=0.005
Boundary for River Rch & Prof#=TANBARK BRANCH 1,Reach-1,6
Up Type=0
Dn Type=3
Dn Slope=0.005
Boundary for River Rch & Prof#=TANBARK BRANCH 1,Reach-1,7
Up Type=0
Dn Type=3
Dn Slope=0.005

--- TANBARK BRANCH 1.g01 (geometry) ---

Geom Title=Existing Conditions
Program Version=4.10

River Reach=TANBARK BRANCH 1,Reach-1
Reach XY= 30
      3606153.94     10625909.87      3606350.75       10625999.
      3606383.75       10625888.       3606457.5       10625925.
      3606534.25       10625834.      3606724.25       10625950.
        3606923.       10625917.      3607065.75       10626037.
        3607175.       10625916.      3607195.75       10625737.
       3607358.5       10625725.      3607492.75       10625582.
       3608069.5       10625530.      3609414.25       10625148.
      3609549.75       10625031.      3609640.75       10625106.
      3609810.25       10624820.        3610046.       10624727.
      3610166.75       10625016.      3610352.25       10624966.
        3610501.       10625116.      3610786.75       10625129.
      3610855.75       10625268.       3611155.5       10625082.
      3611748.75       10624991.       3611890.5       10625136.
       3612303.5       10625118.      3612395.25       10625227.
      3612485.75       10624992.      3612800.25       10625111.

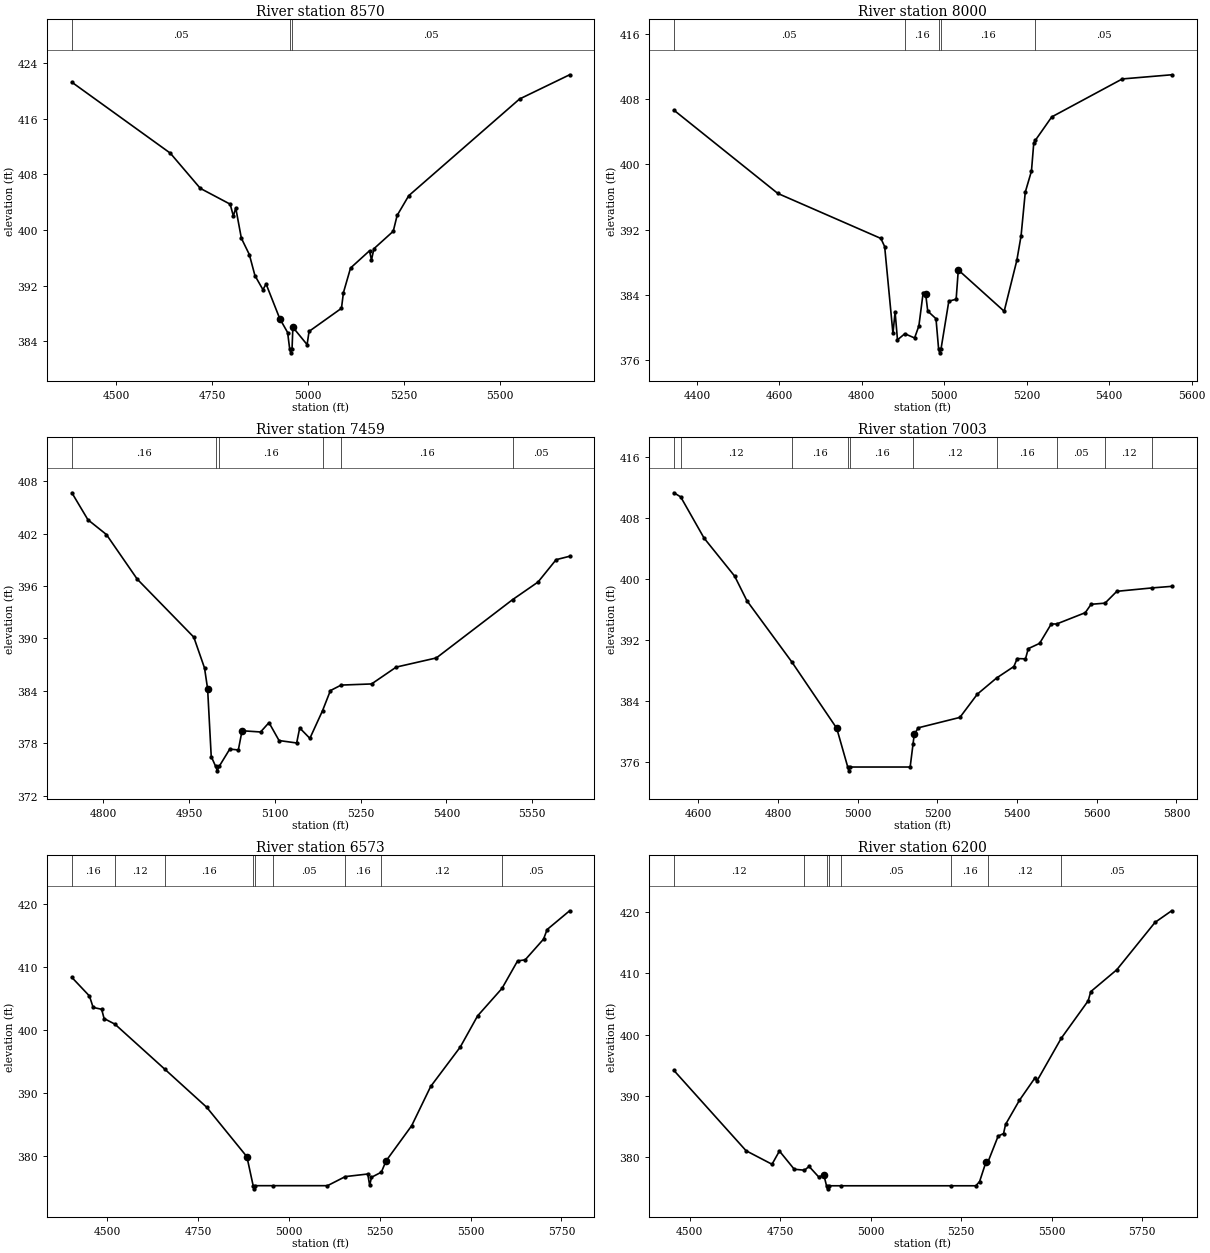
Type RM Length L Ch R = 1 ,8570    ,570,570,570
BEGIN DESCRIPTION:
TANBARK BRANCH 1 15.0
END DESCRIPTION:
XS GIS Cut Line= 4
      3605812.08     10626351.34      3606233.94     10626033.65
      3606280.81     10625835.73      3606208.03     10625274.23
#Sta/Elev= 30
  4384.3  421.24  4640.9  411.05  4719.2  405.99    4797  403.72  4805.3  402.02
  4811.6  403.17  4826.2  398.83    4847  396.48  4861.6  393.46  4882.4  391.44
  4890.7  392.25  4926.2  387.29  4946.8  385.28  4952.3  382.86  4955.1  382.36
  4958.3  382.86  4960.5  386.04  4997.6  383.54  5002.7  385.44  5087.2  388.76
  5092.3  391.01  5110.9  394.55  5160.4  397.03  5165.4  395.69  5171.8  397.32
  5222.2  399.83  5232.3   402.1  5262.6  404.94  5551.5  418.83    5682  422.31
#Mann= 3 ,-1 , 0
  4384.3     .05       0  4952.3     .03       0  4958.3     .05       0
Bank Sta=4926.2,4960.5
XS Rating Curve= 0 ,0
Exp/Cntr=0.3,0.1

Type RM Length L Ch R = 1 ,8000    ,541,541,541
BEGIN DESCRIPTION:
TANBARK BRANCH 1 14.0
END DESCRIPTION:
XS GIS Cut Line= 3
      3606452.68     10626523.26      3606655.81     10625783.65
      3606562.47     10625353.25
#Sta/Elev= 30
    4344  406.64  4596.1  396.44  4846.1  390.93  4855.3  389.93  4875.4   379.3
  4880.6  381.93  4886.4  378.51  4904.2  379.26  4927.9  378.74  4938.3  380.22
  4948.7  384.29  4954.6  384.18  4959.8  382.03  4979.8   381.1  4986.1  377.42
  4988.8  376.92  4992.1  377.42  5010.9  383.24  5028.7  383.49  5033.9  387.07
  5145.2  382.01  5175.9  388.24  5186.2  391.25  5196.4   396.6  5211.4  399.18
  5216.9  402.57  5220.9  402.95  5260.6  405.81  5431.7  410.46  5551.4  410.97
#Mann= 5 ,-1 , 0
    4344     .05       0  4904.2     .16       0  4986.1     .07       0
  4992.1     .16       0  5220.9     .05       0
Bank Sta=4954.6,5033.9
XS Rating Curve= 0 ,0
Exp/Cntr=0.3,0.1

Type RM Length L Ch R = 1 ,7459    ,456,456,456
BEGIN DESCRIPTION:
TANBARK BRANCH 1 13.0
END DESCRIPTION:
XS GIS Cut Line= 2
        3607183.     10626256.23       3606857.5     10625448.99
#Sta/Elev= 30
    4745  406.67  4773.1  403.58  4805.4  401.89  4859.3  396.78  4958.2  390.14
    4977   386.6  4982.4  384.21  4988.7  376.47  4996.5  375.33  4999.3  374.83
  5002.5  375.33  5021.1  377.32  5036.1  377.22  5042.6  379.42    5075  379.28
  5089.7  380.35  5107.3   378.3  5138.1  378.02  5143.4  379.74  5161.2  378.55
  5183.3  381.71  5197.1  384.02  5215.9  384.65  5269.1  384.78  5312.2  386.71
  5382.4  387.76  5515.6  394.43  5560.2  396.45  5591.8  399.01  5615.4   399.4
#Mann= 6 ,-1 , 0
    4745     .16       0  4996.5     .07       0  5002.5     .16       0
  5183.3     .12       0  5215.9     .16       0  5515.6     .05       0
Bank Sta=4982.4,5042.6
XS Rating Curve= 0 ,0
Exp/Cntr=0.3,0.1

Type RM Length L Ch R = 1 ,7003    ,430,430,430
BEGIN DESCRIPTION:
TANBARK BRANCH 1 12.0
END DESCRIPTION:
XS GIS Cut Line= 3
      3607411.03      10626169.1       3607270.4     10625533.65
      3606791.86     10625174.74
#Sta/Elev= 30
  4538.9  411.26    4556  410.72  4614.7  405.32  4691.4  400.34  4722.1  397.12
  4835.1  389.08  4947.5  380.41  4975.2  375.33  4977.9  374.83  4981.2  375.33
  5131.8  375.33    5139  378.34  5142.1  379.63  5152.3  380.47  5256.6  381.83
  5300.4  384.88  5348.6  386.99  5392.1   388.5  5400.4  389.54  5421.2   389.5
  5428.2  390.84  5456.6  391.53  5485.8  394.07  5499.3  394.07  5571.2  395.55
  5585.8  396.65  5620.8   396.8  5650.4  398.35  5739.6   398.8  5787.9     399
#Mann= 10 ,-1 , 0
  4538.9     .16       0    4556     .12       0  4835.1     .16       0
  4975.2     .07       0  4981.2     .16       0    5139     .12       0
  5348.6     .16       0  5499.3     .05       0  5620.8     .12       0
  5739.6     .05       0
Bank Sta=4947.5,5142.1
XS Rating Curve= 0 ,0
Exp/Cntr=0.3,0.1

Type RM Length L Ch R = 1 ,6573    ,373,373,373
BEGIN DESCRIPTION:
TANBARK BRANCH 1 11.0
END DESCRIPTION:
XS GIS Cut Line= 2
      3607744.35     10626148.21      3607577.69     10624788.89
#Sta/Elev= 30
    4403  408.34  4451.4  405.39  4461.5  403.58  4484.9  403.29  4491.7  401.82
  4521.5  400.93  4658.9  393.78  4773.8  387.77  4884.6  379.92  4901.8  375.33
  4904.5  374.83  4907.8  375.33  4956.7  375.33  5106.3  375.33  5155.3  376.77
  5217.1  377.18  5222.4  375.38  5227.4  376.66  5254.5  377.47  5267.4  379.25
    5338  384.84  5390.2  391.05  5471.6   397.3  5519.3  402.24  5586.5   406.6
  5629.3  410.95  5650.3  411.13  5700.7   414.4  5710.7  415.93  5772.5   418.9
#Mann= 9 ,-1 , 0
    4403     .16       0  4521.5     .12       0  4658.9     .16       0
  4901.8    .033       0  4907.8     .16       0  4956.7     .05       0
  5155.3     .16       0  5254.5     .12       0  5586.5     .05       0
Bank Sta=4884.6,5267.4
XS Rating Curve= 0 ,0
Exp/Cntr=0.3,0.1

Type RM Length L Ch R = 1 ,6200    ,267,267,267
BEGIN DESCRIPTION:
TANBARK BRANCH 1 10.0
END DESCRIPTION:
XS GIS Cut Line= 2
      3608161.02     10626064.89      3607864.37     10624722.17
#Sta/Elev= 30
  4456.1  394.16  4655.5  381.05  4727.2  378.84  4747.7     381  4788.6  378.03
  4816.9  377.87  4829.6  378.49  4855.9  376.79  4870.6  377.05  4877.8  375.33
  4880.5  374.83  4883.8  375.33  4918.2  375.33  5222.1  375.33  5290.4  375.33
  5300.7  376.02  5318.1  379.18  5323.4  379.16  5351.9  383.43  5366.9  383.86
  5372.4  385.34  5410.6  389.27  5454.2  392.98  5459.3  392.45  5526.1  399.39
  5600.6  405.51  5607.9  407.02  5679.6  410.58  5785.4  418.32  5831.2  420.21
#Mann= 8 ,-1 , 0
  4456.1     .12       0  4816.9     .16       0  4877.8    .033       0
  4883.8     .16       0  4918.2     .05       0  5222.1     .16       0
  5323.4     .12       0  5526.1     .05       0
Bank Sta=4870.6,5318.1
XS Rating Curve= 0 ,0
Exp/Cntr=0.3,0.1

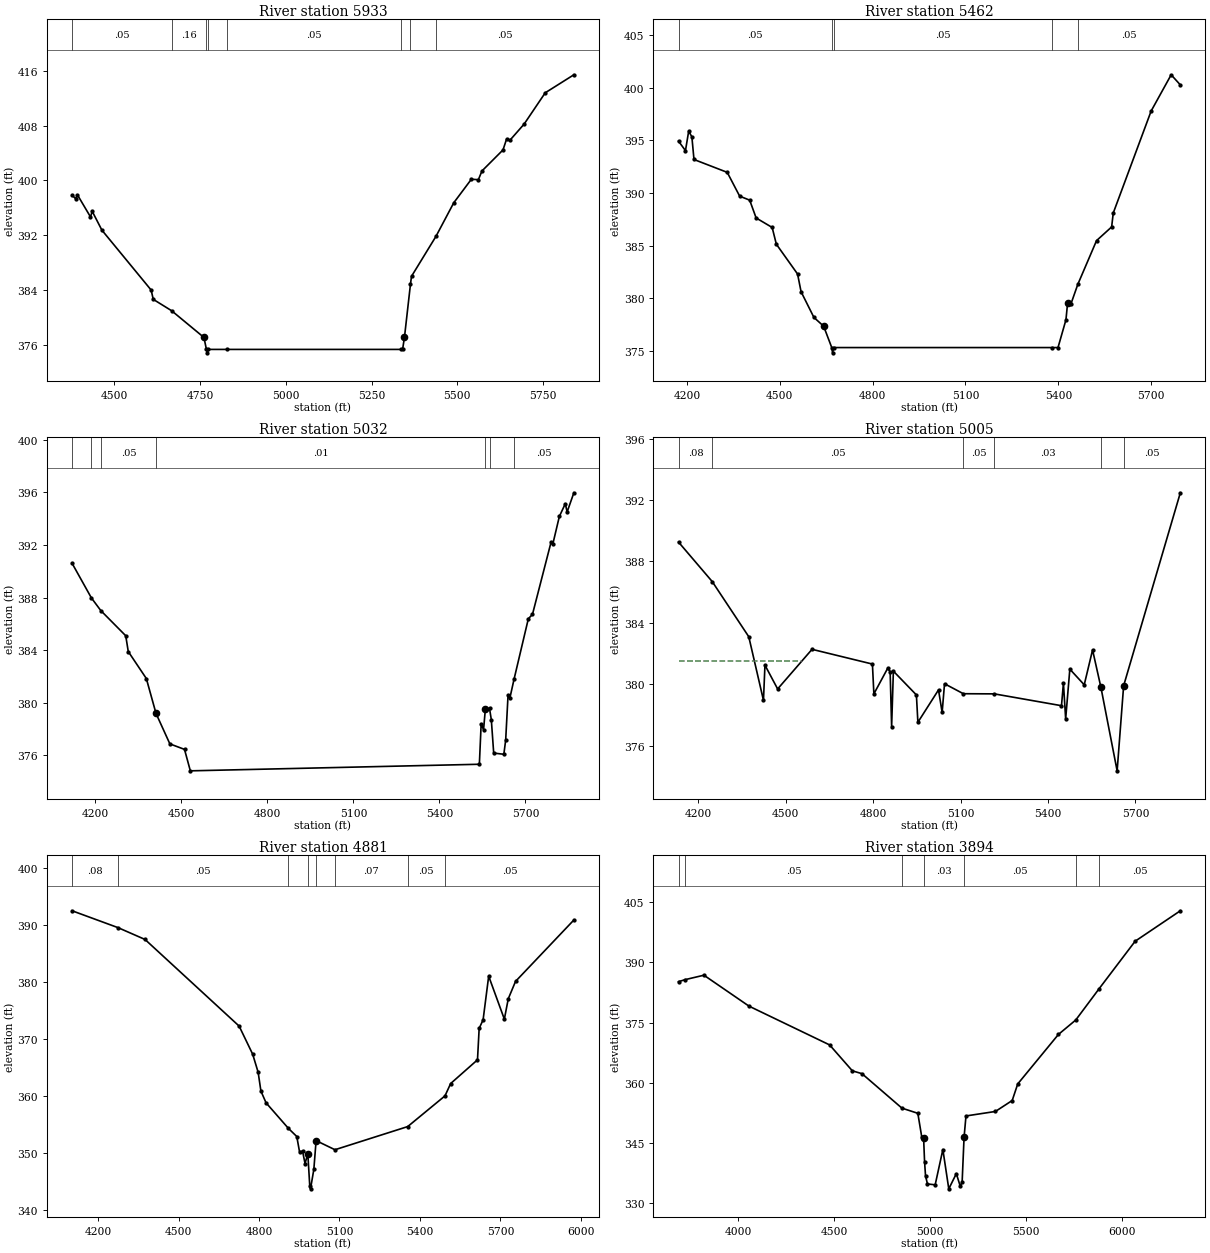
Type RM Length L Ch R = 1 ,5933    ,471,471,471
BEGIN DESCRIPTION:
TANBARK BRANCH 1 9.0
END DESCRIPTION:
XS GIS Cut Line= 2
      3608437.07     10626064.92      3608114.39     10624638.87
#Sta/Elev= 30
  4377.5  397.86  4388.1  397.33  4393.2   397.9  4431.2  394.68  4436.3  395.49
  4464.4  392.75  4607.9     384  4614.1  382.64  4667.6  380.98  4761.7  377.08
    4769  375.33  4771.7  374.83    4775  375.33  4829.1  375.33  5336.3  375.33
  5340.6  375.33  5346.1  377.14  5363.6   384.9  5366.6  386.01  5437.8  391.84
  5489.7  396.75  5540.9  400.18  5561.4  400.12  5571.8  401.39  5633.2  404.47
  5643.4  406.03    5653  405.86  5694.7  408.24  5756.2  412.81  5839.6  415.44
#Mann= 8 ,-1 , 0
  4377.5     .05       0  4667.6     .16       0    4769    .033       0
    4775     .16       0  4829.1     .05       0  5336.3     .16       0
  5363.6     .12       0  5437.8     .05       0
Bank Sta=4761.7,5346.1
XS Rating Curve= 0 ,0
Exp/Cntr=0.3,0.1

Type RM Length L Ch R = 1 ,5462    ,430,430,430
BEGIN DESCRIPTION:
TANBARK BRANCH 1 8.0
END DESCRIPTION:
XS GIS Cut Line= 2
      3608968.31     10626111.77      3608536.02     10624549.27
#Sta/Elev= 30
    4173  394.92  4195.4  394.02  4205.8  395.87  4216.1  395.33  4222.9  393.18
  4330.3  391.96  4370.5   389.7  4402.9  389.32  4423.7  387.63  4475.5  386.73
    4489  385.14  4557.6  382.31  4568.9  380.63  4610.4  378.19  4641.8  377.36
    4668  375.33  4670.7  374.83    4674  375.33  5378.3  375.33    5399  375.33
  5424.7  377.97  5430.1   379.6  5440.5  379.45    5463  381.33  5523.5  385.48
  5572.3  386.78  5577.5   388.1  5699.9  397.78  5764.6  401.22  5794.2  400.26
#Mann= 5 ,-1 , 0
    4173     .05       0    4668    .033       0    4674     .05       0
  5378.3     .16       0    5463     .05       0
Bank Sta=4641.8,5430.1
XS Rating Curve= 0 ,0
Exp/Cntr=0.3,0.1

Type RM Length L Ch R = 1 ,5032    ,27,27,27
BEGIN DESCRIPTION:
Mapping XS ea7e3b40
END DESCRIPTION:
XS GIS Cut Line= 6
      3609060.72     10626042.83      3609199.61     10625426.52
      3609177.91     10625252.91      3609056.38     10624870.97
      3609012.98     10624814.54      3608639.72     10624528.09
#Sta/Elev= 30
  4118.7  390.61  4186.3  387.97  4219.1  387.01  4305.9   385.1  4314.7   383.9
  4377.7  381.85  4411.4   379.2  4459.8  376.88  4510.9  376.46  4531.2  374.83
  5539.3  375.33  5545.6  378.41  5553.9  377.95  5560.2  379.51  5574.7  379.58
    5581  378.72  5589.3  376.18  5624.7  376.09  5631.1  377.17  5639.3  380.56
  5645.5  380.34  5660.1  381.78  5710.1  386.39  5724.6  386.73  5789.2   392.2
  5795.4  392.06  5818.3  394.17  5839.1  395.14  5845.4  394.51  5868.9  395.97
#Mann= 7 ,-1 , 0
  4118.7     .05       0  4186.3     .08       0  4219.1     .05       0
  4411.4     .01       0  5560.2     .03       0  5574.7     .07       0
  5660.1     .05       0
Bank Sta=4411.4,5560.2
XS Rating Curve= 0 ,0
Exp/Cntr=0.3,0.1

Type RM Length L Ch R = 1 ,5005    ,124,124,124
BEGIN DESCRIPTION:
Mapping XS 390dd2f1
END DESCRIPTION:
XS GIS Cut Line= 6
      3609130.17     10626025.44      3609229.99     10625578.43
      3609229.99     10625400.48      3609160.55     10625083.64
      3609065.06     10624827.56       3608693.2     10624511.91
#Sta/Elev= 30
  4132.5  389.26  4248.1  386.69  4373.5   383.1  4423.9  378.96    4429  381.25
  4472.5   379.7  4590.5  382.28  4797.7  381.32  4802.7  379.38  4849.9  381.04
  4858.5  380.83  4863.6  377.25  4869.6  380.86  4948.6  379.31  4953.7  377.53
  5024.5  379.64  5036.9  378.17  5045.1  380.04  5109.7  379.39  5215.9  379.38
  5446.4  378.61    5453  380.08  5460.7  377.75    5475  380.99  5524.4  379.97
    5553  382.24  5581.6  379.81  5637.3  374.37  5659.6  379.91  5854.1  392.47
#Mann= 6 ,-1 , 0
  4132.5     .08       0  4248.1     .05       0  5109.7     .05       0
  5215.9     .03       0  5581.6     .01       0  5659.6     .05       0
#XS Ineff= 2 , 0
         4554.55  381.51
Permanent Ineff=
       F       F
Bank Sta=5581.6,5659.6
XS Rating Curve= 0 ,0
Exp/Cntr=0.3,0.1

Type RM Length L Ch R = 1 ,4881    ,987,987,987
BEGIN DESCRIPTION:
TANBARK BRANCH 1 7.0
END DESCRIPTION:
XS GIS Cut Line= 5
       3609255.6     10626046.33      3609354.56     10625369.23
       3609255.6     10624957.77      3609161.85     10624775.48
      3608714.26     10624442.39
#Sta/Elev= 30
  4103.2  392.45  4274.6  389.49  4375.1  387.42  4725.9  372.22  4776.4  367.29
  4796.8  364.12  4807.1  360.82  4826.3  358.76  4909.9  354.26  4940.8  352.85
  4951.1  350.16  4962.4  350.26  4971.6  348.11  4981.9  349.84  4989.2  344.17
    4992  343.67  5004.4  347.09  5012.8  352.13  5083.1  350.53  5354.2  354.59
  5493.3  359.98  5514.3  362.14  5614.4   366.3  5620.6  371.82  5635.3  373.32
  5656.1  380.98  5714.5  373.44  5729.1  377.01  5756.2  380.06  5973.6  390.83
#Mann= 8 ,-1 , 0
  4103.2     .08       0  4274.6     .05       0  4909.9     .05       0
  4981.9     .03       0  5012.8     .05       0  5083.1     .07       0
  5354.2     .05       0  5493.3     .05       0
Bank Sta=4981.9,5012.8
XS Rating Curve= 0 ,0
Exp/Cntr=0.3,0.1

Type RM Length L Ch R = 1 ,3894    ,896,896,896
BEGIN DESCRIPTION:
TANBARK BRANCH 1 6.0
END DESCRIPTION:
XS GIS Cut Line= 3
      3609539.19     10625957.19      3609966.26     10625170.76
      3609825.63     10623457.23
#Sta/Elev= 30
  3689.1   385.2  3723.3   385.7  3821.4  386.81  4056.1   379.1  4476.2  369.43
  4594.6  362.97  4644.8  362.26  4852.9  353.67  4935.8  352.38  4955.8  346.59
  4965.9  346.18  4970.9  340.29  4975.9  336.78  4985.9  334.77  5026.1  334.55
  5066.2  343.35    5097  333.55  5136.4  337.34  5156.5  334.23  5166.5  335.15
  5176.6  346.36  5186.6  351.72  5339.9  352.84  5427.4  355.57  5456.2   359.7
  5668.2  372.04  5758.5  375.64  5879.9  383.42  6067.9  395.28  6303.3  402.87
#Mann= 7 ,-1 , 0
  3689.1     .08       0  3723.3     .05       0  4852.9     .05       0
  4965.9     .03       0  5176.6     .05       0  5758.5     .05       0
  5879.9     .05       0
Bank Sta=4965.9,5176.6
XS Rating Curve= 0 ,0
Exp/Cntr=0.3,0.1

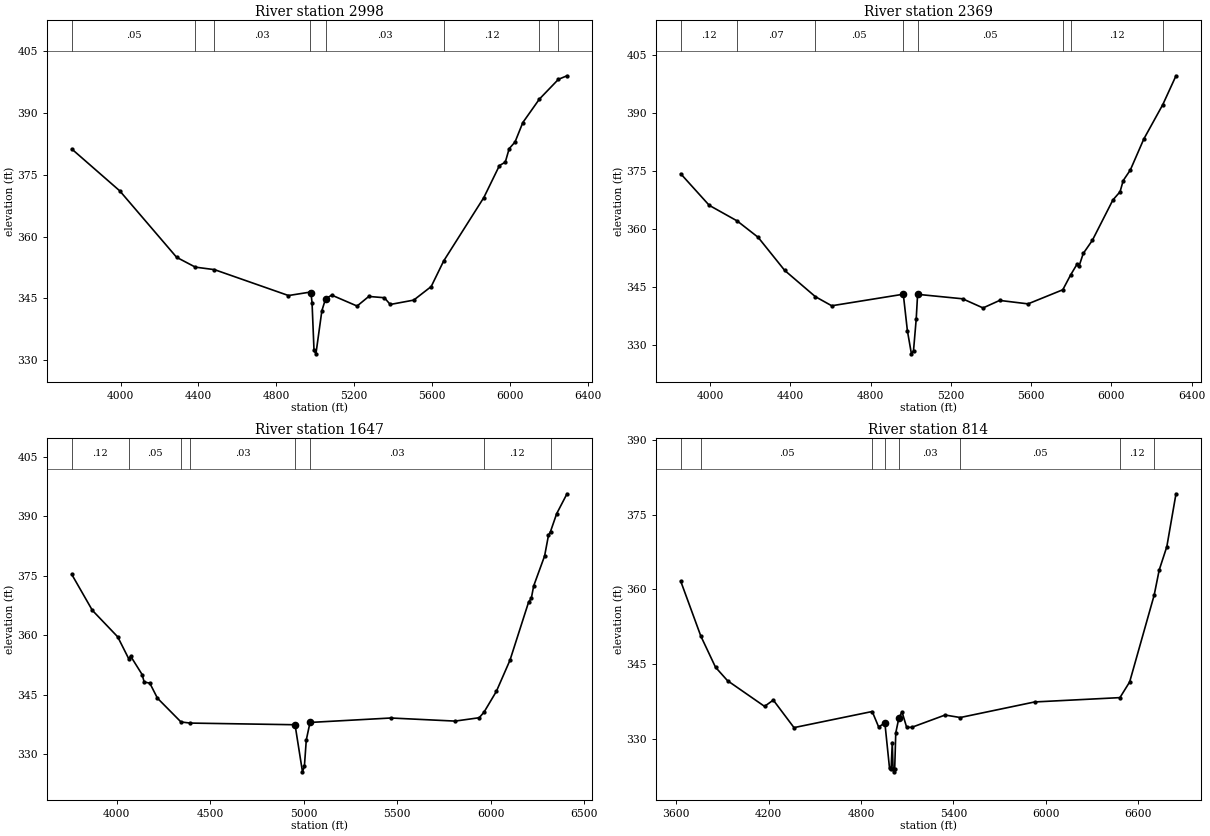
Type RM Length L Ch R = 1 ,2998    ,629,629,629
BEGIN DESCRIPTION:
TANBARK BRANCH 1 5.0
END DESCRIPTION:
XS GIS Cut Line= 3
      3610309.25     10626334.55      3610483.44     10624968.82
      3610549.33     10623803.67
#Sta/Elev= 30
  3749.5  381.31  3995.8  371.15  4288.2     355  4384.4  352.61  4482.7     352
  4862.8  345.71    4973  346.54  4978.1  346.43  4983.8  343.94  4993.9  332.37
  5003.7  331.55  5034.2  342.01  5052.9  344.87  5084.6  345.82  5215.1  343.16
  5275.2  345.49  5355.3  345.18  5385.3  343.54  5505.9   344.6  5595.7  347.89
    5660  354.12  5866.1  369.51  5946.2  377.28  5976.3  378.11  5996.3  381.39
  6026.4  383.01  6066.4  387.73  6151.3  393.42  6249.3  398.23  6293.3  399.09
#Mann= 8 ,-1 , 0
  3749.5     .05       0  4384.4      .1       0  4482.7     .03       0
    4973     .01       0  5052.9     .03       0    5660     .12       0
  6151.3      .1       0  6249.3     .05       0
Bank Sta=4978.1,5052.9
XS Rating Curve= 0 ,0
Exp/Cntr=0.3,0.1

Type RM Length L Ch R = 1 ,2369    ,722,722,722
BEGIN DESCRIPTION:
TANBARK BRANCH 1 3.0
END DESCRIPTION:
XS GIS Cut Line= 2
      3611151.27     10626308.53      3610673.83     10623886.64
#Sta/Elev= 30
  3853.2  374.22  3995.2  366.08  4134.4  362.05  4238.8  357.83  4371.3  349.28
  4524.2   342.5  4605.8  340.15  4962.5  343.13  4982.9  333.71    5003  327.74
  5013.5   328.6  5026.9  336.73  5033.8   343.1  5258.1  341.95    5360  339.59
  5442.7  341.53  5584.2  340.64  5757.5  344.28  5796.1  348.07  5828.8  350.91
    5839  350.45  5859.4  353.65  5904.7  357.03  6007.3  367.47  6042.9  369.58
  6058.7  372.48  6093.9  375.18  6161.3   383.2  6255.9  392.08  6321.7  399.52
#Mann= 8 ,-1 , 0
  3853.2     .12       0  4134.4     .07       0  4524.2     .05       0
  4962.5     .03       0  5033.8     .05       0  5757.5     .05       0
  5796.1     .12       0  6255.9      .1       0
Bank Sta=4962.5,5033.8
XS Rating Curve= 0 ,0
Exp/Cntr=0.3,0.1

Type RM Length L Ch R = 1 ,1647    ,833,833,833
BEGIN DESCRIPTION:
TANBARK BRANCH 1 2.0
END DESCRIPTION:
XS GIS Cut Line= 4
      3611342.23     10626247.77      3611585.29     10625145.33
      3611593.97     10624919.63      3610813.65     10623887.87
#Sta/Elev= 30
  3760.2  375.31  3870.4  366.24    4006  359.55  4064.7  354.05  4075.2  354.67
  4136.6  350.04  4147.4  348.16  4177.6  347.87  4218.5  344.08  4344.3  338.08
  4393.6   337.8  4954.3  337.38  4994.1   325.5  5004.3  326.88  5014.4  333.54
  5034.4  337.96  5466.8  339.08  5810.2   338.3  5939.2  339.15  5964.9  340.56
  6030.8  345.79  6103.6  353.65  6203.4  368.34  6217.6  369.25  6230.5  372.41
  6288.8  379.95  6309.6  385.17  6320.4  386.12  6353.3  390.62  6408.6  395.64
#Mann= 8 ,-1 , 0
  3760.2     .12       0  4064.7     .05       0  4344.3     .05       0
  4393.6     .03       0  4954.3     .01       0  5034.4     .03       0
  5964.9     .12       0  6320.4      .1       0
Bank Sta=4954.3,5034.4
XS Rating Curve= 0 ,0
Exp/Cntr=0.3,0.1

Type RM Length L Ch R = 1 ,814     ,0,0,0
BEGIN DESCRIPTION:
TANBARK BRANCH 1 1.0
END DESCRIPTION:
XS GIS Cut Line= 4
      3611506.03     10626155.69      3612339.37     10625296.31
       3612297.7     10624999.44      3611001.27     10623874.82
#Sta/Elev= 30
  3630.6  361.63  3761.1  350.59  3856.3  344.34    3934  341.64  4174.5  336.47
  4231.1  337.74  4365.4   332.2  4872.8  335.44  4914.6  332.33    4955  333.15
  4985.3  323.99  4995.4  323.84  5003.1   329.2  5008.2  323.83  5015.4  323.31
  5018.6  323.81  5025.7  331.14  5045.9  334.15  5066.1  335.36  5096.4  332.26
  5129.5  332.26  5345.5  334.73  5444.2  334.23  5926.7  337.36    6480  338.23
    6543  341.38    6702  358.82  6734.8  363.89  6784.2  368.58  6843.7  379.21
#Mann= 8 ,-1 , 0
  3630.6     .12       0  3761.1     .05       0  4872.8     .03       0
    4955     .01       0  5045.9     .03       0  5444.2     .05       0
    6480     .12       0    6702      .1       0
Bank Sta=4955,5045.9
XS Rating Curve= 0 ,0
Exp/Cntr=0.3,0.1

Chan Stop Cuts=-1
Use User Specified Reach Order=0
Composite Channel Slope=5