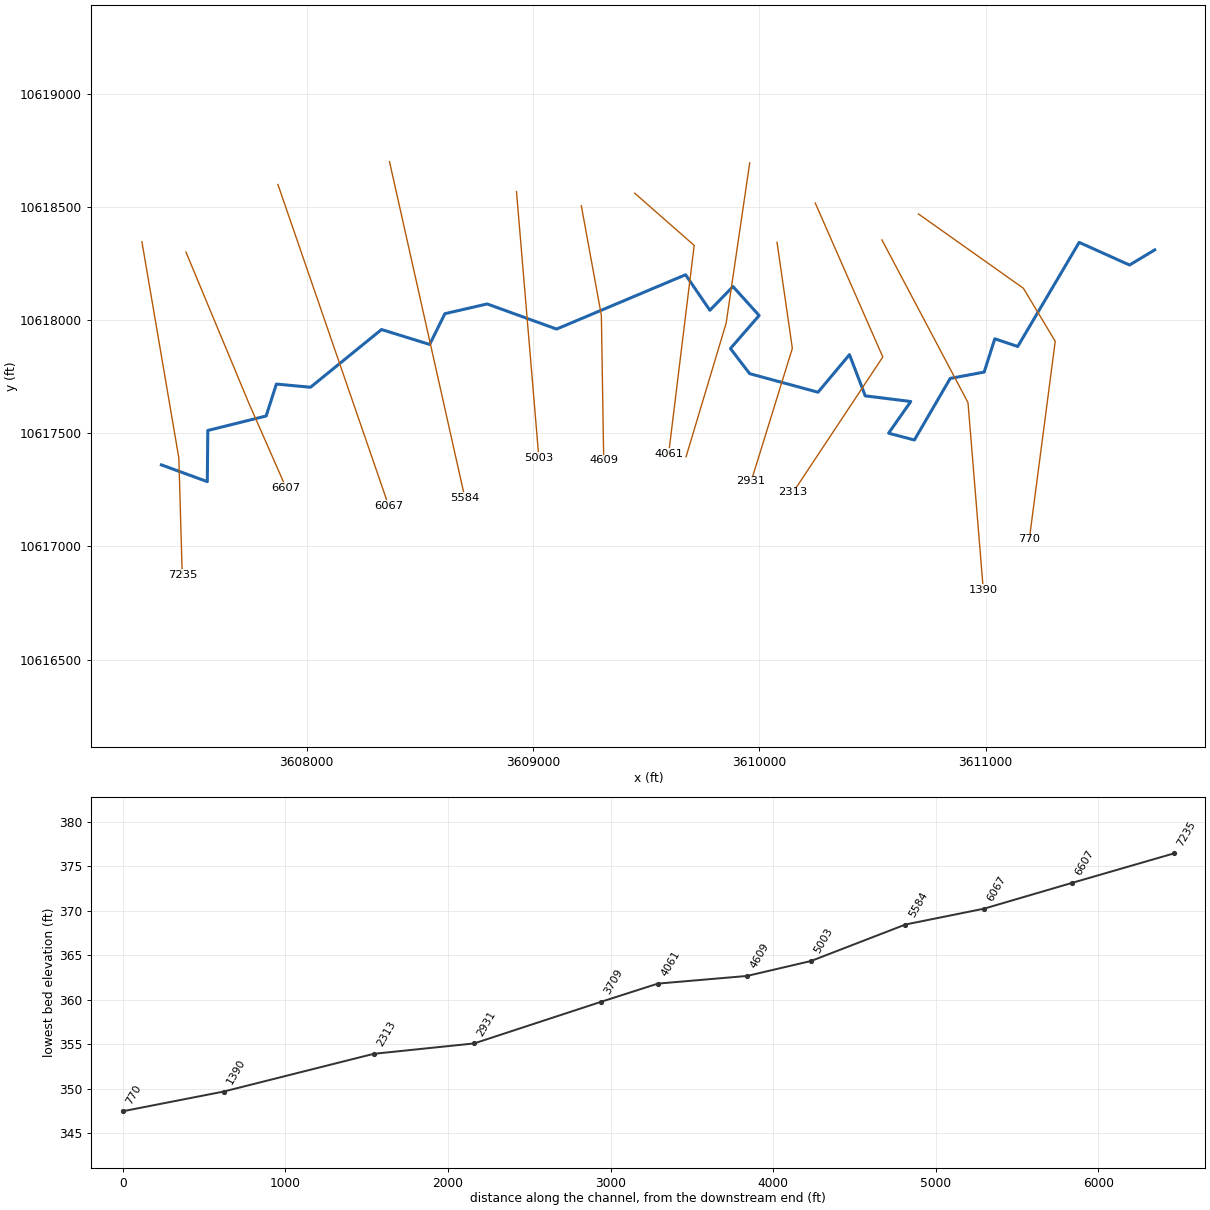
--- TANBARK BRANCH 2.prj (project) ---

Proj Title=TANBARK BRANCH 2 Base Level Engineering
Current Plan=p01
Default Exp/Contr=0.3,0.1
English Units
Geom File=g01
Flow File=f01
Plan File=p01
Y Axis Title=Elevation
X Axis Title(PF)=Main Channel Distance
X Axis Title(XS)=Station
BEGIN DESCRIPTION:
TANBARK BRANCH 2
END DESCRIPTION:
DSS Export Rating Curves= 0
DSS Export Rating Curve Sorted= 0
DSS Export Volume Flow Curves= 0
DXF OffsetX= 0
DXF OffsetY= 0
DXF ScaleX= 1
DXF ScaleY= 10

--- TANBARK BRANCH 2.p01 (plan) ---

Plan Title=Multiple Run
Short Identifier=Multiple
Geom File=g01
Flow File=f01
Subcritical Flow
K Sum by GR= 0
Std Step Tol= 0.01
Critical Tol= 0.01
Num of Std Step Trials= 20
Max Error Tol= 0.3
Flow Tol Ratio= 0.001
Split Flow NTrial= 30
Split Flow Tol= 0.02
Split Flow Ratio= 0.02
Log Output Level= 0
Friction Slope Method= 1
Unsteady Friction Slope Method= 2
Unsteady Bridges Friction Slope Method= 1
Parabolic Critical Depth
Global Vel Dist=  1 , 1 , 1
Global Log Level= 0
CheckData=True
Encroach Param= -1, 0, 0, 0
BEGIN DESCRIPTION:
Multiple Run
END DESCRIPTION:

--- TANBARK BRANCH 2.f01 (steady flow) ---

Flow Title=Multiple
Number of Profiles=7
Profile Names=10-year,25-year,50-year,1pct_min,100-year,1pct_plu,500-year
River Rch & RM= TANBARK BRANCH 2,Reach-1,7235
    1546    2138    2630    2362    3194    4320    4693
River Rch & RM= TANBARK BRANCH 2,Reach-1,6607
    2279    3211    4000    3631    4910    6641    7376
Boundary for River Rch & Prof#=TANBARK BRANCH 2,Reach-1,1
Up Type=0
Dn Type=3
Dn Slope=0.005
Boundary for River Rch & Prof#=TANBARK BRANCH 2,Reach-1,2
Up Type=0
Dn Type=3
Dn Slope=0.005
Boundary for River Rch & Prof#=TANBARK BRANCH 2,Reach-1,3
Up Type=0
Dn Type=3
Dn Slope=0.005
Boundary for River Rch & Prof#=TANBARK BRANCH 2,Reach-1,4
Up Type=0
Dn Type=3
Dn Slope=0.005
Boundary for River Rch & Prof#=TANBARK BRANCH 2,Reach-1,5
Up Type=0
Dn Type=3
Dn Slope=0.005
Boundary for River Rch & Prof#=TANBARK BRANCH 2,Reach-1,6
Up Type=0
Dn Type=3
Dn Slope=0.005
Boundary for River Rch & Prof#=TANBARK BRANCH 2,Reach-1,7
Up Type=0
Dn Type=3
Dn Slope=0.005

--- TANBARK BRANCH 2.g01 (geometry) ---

Geom Title=Existing Conditions
Program Version=4.10

River Reach=TANBARK BRANCH 2,Reach-1
Reach XY= 30
       3607358.5       10617360.      3607561.25       10617286.
       3607563.5       10617512.      3607821.25       10617576.
       3607866.5       10617717.      3608017.25       10617703.
        3608331.       10617958.      3608543.75       10617892.
        3608611.       10618028.      3608797.75       10618071.
       3609104.5       10617960.      3609674.25       10618200.
      3609781.75       10618043.      3609883.75       10618148.
      3609999.25       10618020.       3609872.5       10617874.
       3609957.5       10617763.       3610259.5       10617681.
       3610398.5       10617847.        3610468.       10617665.
      3610669.25       10617640.      3610571.25       10617500.
      3610685.25       10617470.       3610843.5       10617742.
       3610993.5       10617770.       3611040.5       10617917.
      3611141.75       10617883.      3611413.25       10618343.
      3611635.75       10618243.      3611747.25       10618310.

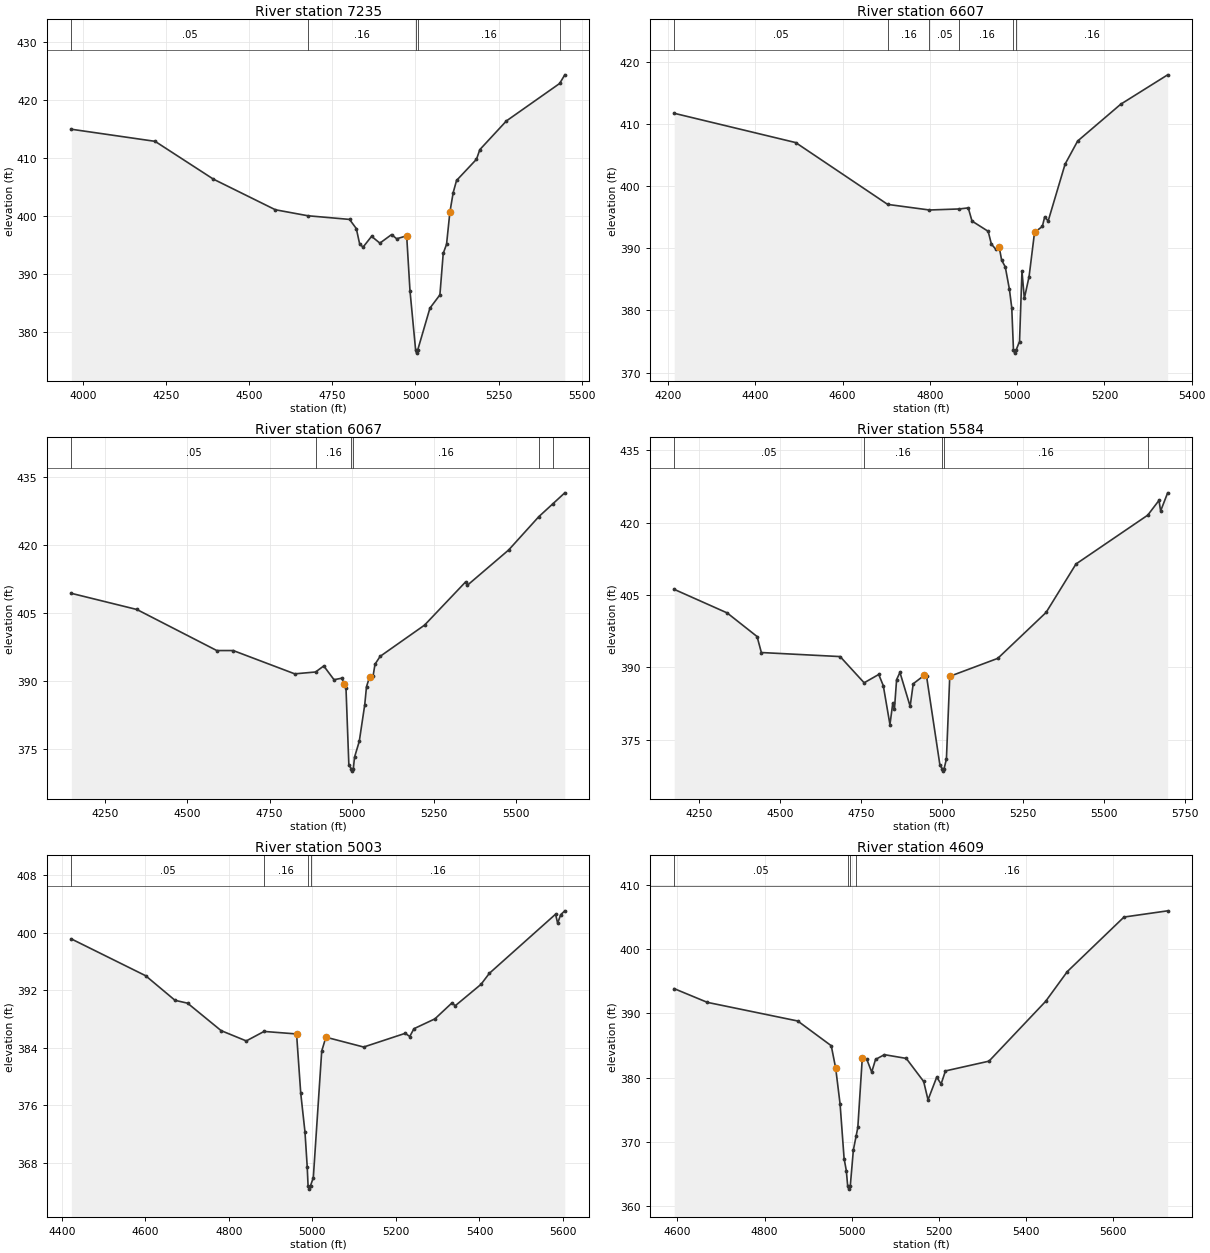
Type RM Length L Ch R = 1 ,7235    ,628,628,628
BEGIN DESCRIPTION:
TANBARK BRANCH 2 12.0
END DESCRIPTION:
XS GIS Cut Line= 3
       3607272.5     10618345.44      3607435.52     10617390.64
      3607450.61     10616874.58
#Sta/Elev= 30
  3964.5  414.95  4216.5  412.87  4391.9  406.37  4578.5   401.1  4676.2  400.07
  4801.7  399.44    4822  397.87  4832.1  395.22  4842.3  394.67    4868  396.53
    4893  395.36  4928.1  396.83  4943.6  396.11  4973.6  396.62  4983.6  387.15
  5000.6  376.94  5003.3  376.44  5006.6  376.94  5043.6  384.18  5073.6  386.46
  5083.6   393.6  5093.6  395.16  5103.6  400.67  5113.6  404.06  5123.7  406.14
  5183.7  409.79  5193.7  411.44  5273.7  416.38  5433.9  422.82  5449.4  424.31
#Mann= 5 ,-1 , 0
  3964.5     .05       0  4676.2     .16       0  5000.6     .07       0
  5006.6     .16       0  5433.9     .05       0
Bank Sta=4973.6,5103.6
XS Rating Curve= 0 ,0
Exp/Cntr=0.3,0.1

Type RM Length L Ch R = 1 ,6607    ,540,540,540
BEGIN DESCRIPTION:
TANBARK BRANCH 2 11.0
END DESCRIPTION:
XS GIS Cut Line= 3
      3607466.94      10618300.3      3607743.38     10617636.06
      3607908.97     10617259.42
#Sta/Elev= 30
  4214.1  411.71  4492.4     407  4703.3  397.05    4799  396.15  4867.7  396.32
    4888  396.49  4896.6  394.37  4933.6  392.72    4941  390.66  4950.9  389.85
  4958.9   390.2  4964.4   388.1  4972.8     387  4982.3   383.4  4987.7  380.41
  4991.6  373.62  4994.4  373.12  4997.6  373.62  5005.5  374.98  5011.1  386.31
  5016.5  381.91  5027.4  385.44  5039.9  392.54  5057.8  393.51  5063.2  395.06
  5071.1  394.37  5109.9  403.53  5138.7  407.25  5237.6  413.18    5345   417.9
#Mann= 6 ,-1 , 0
  4214.1     .05       0  4703.3     .16       0    4799     .05       0
  4867.7     .16       0  4991.6     .07       0  4997.6     .16       0
Bank Sta=4958.9,5039.9
XS Rating Curve= 0 ,0
Exp/Cntr=0.3,0.1

Type RM Length L Ch R = 1 ,6067    ,483,483,483
BEGIN DESCRIPTION:
TANBARK BRANCH 2 10.0
END DESCRIPTION:
XS GIS Cut Line= 2
      3607873.22     10618598.84      3608362.78     10617178.76
#Sta/Elev= 30
  4146.6  409.38  4346.1  405.82  4589.4  396.78  4639.4  396.78  4826.7  391.65
  4890.1  392.06    4915  393.39  4946.2  390.36  4970.2   390.7  4977.4  389.32
  4982.7  388.44  4991.4  371.57    4999  370.73  5001.7  370.23    5005  370.73
  5008.6  373.28  5023.1  376.79  5039.8  384.88  5045.1  388.83  5054.8  391.03
  5065.4  391.28    5071  393.77  5086.6   395.5  5221.8  402.38  5346.6  411.88
  5351.9  411.14  5477.9  418.93  5569.6  426.26  5612.6  429.11  5648.7  431.51
#Mann= 6 ,-1 , 0
  4146.6     .05       0  4890.1     .16       0    4999     .07       0
    5005     .16       0  5569.6     .05       0  5612.6     .16       0
Bank Sta=4977.4,5054.8
XS Rating Curve= 0 ,0
Exp/Cntr=0.3,0.1

Type RM Length L Ch R = 1 ,5584    ,581,581,581
BEGIN DESCRIPTION:
TANBARK BRANCH 2 9.0
END DESCRIPTION:
XS GIS Cut Line= 2
      3608366.26     10618699.57      3608699.41     10617214.28
#Sta/Elev= 30
  4174.4  406.17  4337.7  401.28    4430  396.38  4443.2  393.06  4686.2  392.22
  4760.3  386.78  4805.3  388.51  4819.4  386.17  4839.9   378.1  4848.6  382.55
  4853.8  381.36  4860.4  387.43  4870.7  388.94  4902.2  381.89  4911.7  386.58
  4945.6  388.33  4952.7  388.18    4994  369.72  5000.9  368.95  5003.6  368.45
  5006.9  368.95  5014.1  370.97  5024.4  388.12  5172.5  391.85  5321.6  401.38
  5413.8  411.43  5635.2  421.57  5669.8  424.63  5674.9  422.44  5696.6   426.2
#Mann= 5 ,-1 , 0
  4174.4     .05       0  4760.3     .16       0  5000.9     .07       0
  5006.9     .16       0  5635.2     .05       0
Bank Sta=4945.6,5024.4
XS Rating Curve= 0 ,0
Exp/Cntr=0.3,0.1

Type RM Length L Ch R = 1 ,5003    ,394,394,394
BEGIN DESCRIPTION:
TANBARK BRANCH 2 8.0
END DESCRIPTION:
XS GIS Cut Line= 2
      3608927.27     10618567.48      3609026.23     10617390.34
#Sta/Elev= 30
    4423  399.16  4600.9  394.04  4671.2  390.62  4701.3  390.22  4781.6   386.4
  4841.8  384.97  4884.4  386.29  4962.2  385.94  4972.2  377.68  4982.3  372.32
  4987.7  367.45  4989.7  364.85  4992.5  364.35  4995.7  364.85  5002.3  365.95
  5022.4  383.56  5032.4  385.49  5122.8  384.12  5222.5  386.03  5233.1  385.58
  5243.2  386.67  5293.4  388.04  5333.5  390.22  5342.4  389.88  5403.7  392.84
  5423.8  394.38  5582.2   402.6  5587.2  401.35  5594.4  402.52  5604.3  403.07
#Mann= 4 ,-1 , 0
    4423     .05       0  4884.4     .16       0  4989.7     .07       0
  4995.7     .16       0
Bank Sta=4962.2,5032.4
XS Rating Curve= 0 ,0
Exp/Cntr=0.3,0.1

Type RM Length L Ch R = 1 ,4609    ,548,548,548
BEGIN DESCRIPTION:
TANBARK BRANCH 2 7.0
END DESCRIPTION:
XS GIS Cut Line= 3
      3609213.73     10618504.91      3609302.27     10618020.56
      3609312.69     10617379.92
#Sta/Elev= 30
  4592.6  393.86  4668.6  391.73  4876.2  388.83  4953.2  384.98  4963.4  381.48
  4973.5  375.89  4982.7  367.42  4987.8  365.55  4990.9  363.17  4993.6  362.67
  4996.9  363.17    5004  368.77  5010.1  370.86  5014.2  372.26  5024.4  383.01
  5034.5  382.92  5046.1  380.88  5054.9  382.85  5075.2  383.59  5125.4  383.01
  5165.4  379.42  5175.4  376.56  5195.4   380.1  5205.4  379.02  5215.4  381.06
  5315.4  382.58  5445.4  391.88  5495.4  396.53  5625.4     405  5725.7  405.97
#Mann= 4 ,-1 , 0
  4592.6     .05       0  4990.9     .03       0  4996.9     .05       0
  5010.1     .16       0
Bank Sta=4963.4,5024.4
XS Rating Curve= 0 ,0
Exp/Cntr=0.3,0.1

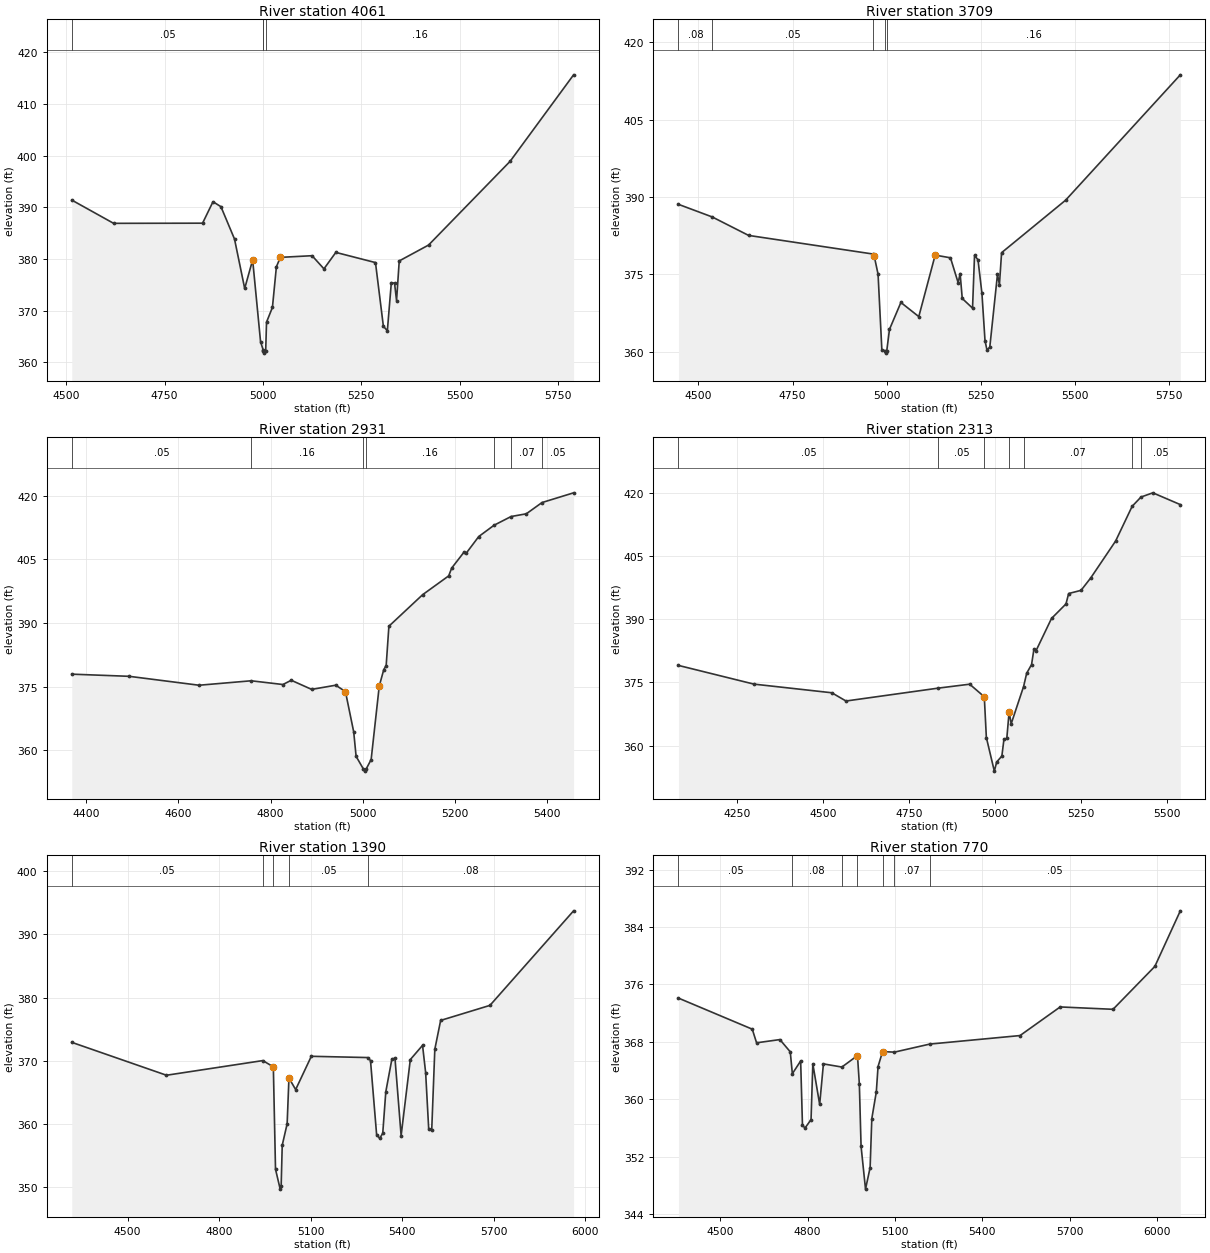
Type RM Length L Ch R = 1 ,4061    ,352,352,352
BEGIN DESCRIPTION:
TANBARK BRANCH 2 6.0
END DESCRIPTION:
XS GIS Cut Line= 3
      3609449.61     10618560.19      3609712.35     10618329.76
      3609599.61     10617410.21
#Sta/Elev= 30
    4514  391.41  4620.4  386.91  4846.6  386.94  4873.1  391.09  4893.3  390.13
  4927.8  383.87  4953.7  374.31  4973.9  379.84    4994  364.05    5001  362.33
  5001.1  362.31  5003.8  361.81  5007.1  362.31  5009.2   367.8  5024.2  370.65
  5034.3  378.52  5044.4  380.33    5125  380.65  5155.2  378.11  5185.4  381.29
  5286.2  379.32  5306.3     367  5316.4  366.14  5326.5  375.44  5334.7  375.34
  5339.8  371.97  5346.6  379.64  5421.2  382.71  5628.7  398.92  5789.9  415.63
#Mann= 4 ,-1 , 0
    4514     .05       0    5001     .16       0  5001.1     .03       0
  5007.1     .16       0
Bank Sta=4973.9,5044.4
XS Rating Curve= 0 ,0
Exp/Cntr=0.3,0.1

Type RM Length L Ch R = 1 ,3709    ,778,778,778
BEGIN DESCRIPTION:
TANBARK BRANCH 2 5.0
END DESCRIPTION:
XS GIS Cut Line= 3
      3609957.71      10618694.3      3609853.54     10617985.94
      3609676.47     10617395.71
#Sta/Elev= 30
  4447.3  388.59  4536.8  386.15  4633.4  382.57  4962.8  378.97  4966.9  378.56
  4977.1  375.05  4987.2  360.33  4994.3  360.25    4997  359.75  5000.3  360.25
  5007.4  364.36  5037.7  369.57  5085.2  366.83  5128.7  378.75  5169.3  378.23
  5189.7   373.4  5194.9  375.18  5200.6  370.34  5227.9  368.47  5233.2  378.71
  5242.4  377.83  5252.8  371.37    5261  362.17  5266.2  360.36  5273.7   360.9
  5294.1  375.02  5299.3  373.02    5305  379.22    5475   389.4  5779.5   413.7
#Mann= 5 ,-1 , 0
  4447.3     .08       0  4536.8     .05       0  4962.8     .16       0
  4994.3     .07       0  5000.3     .16       0
Bank Sta=4966.9,5128.7
XS Rating Curve= 0 ,0
Exp/Cntr=0.3,0.1

Type RM Length L Ch R = 1 ,2931    ,618,618,618
BEGIN DESCRIPTION:
TANBARK BRANCH 2 4.0
END DESCRIPTION:
XS GIS Cut Line= 3
      3610078.32     10618343.43      3610146.02     10617874.73
      3609964.17     10617287.62
#Sta/Elev= 30
  4368.9  377.93  4493.4  377.42    4645  375.32  4757.9  376.37  4826.8  375.49
  4844.9  376.49  4889.1  374.34  4941.4  375.33  4962.4  373.81  4980.3  364.33
  4985.5  358.57  5001.3  355.59    5004  355.09  5007.3  355.59  5018.1  357.81
  5035.7  375.13  5045.5  379.01  5050.7  379.96  5056.6  389.22  5129.9  396.66
  5186.3  401.08  5192.7  402.91  5218.9  406.59  5224.2  406.41  5251.5  410.35
  5284.7  413.01  5321.6  415.06  5354.6   415.7  5388.6  418.35  5457.1  420.64
#Mann= 7 ,-1 , 0
  4368.9     .05       0  4757.9     .16       0  5001.3     .07       0
  5007.3     .16       0  5284.7     .05       0  5321.6     .07       0
  5388.6     .05       0
Bank Sta=4962.4,5035.7
XS Rating Curve= 0 ,0
Exp/Cntr=0.3,0.1

Type RM Length L Ch R = 1 ,2313    ,923,923,923
BEGIN DESCRIPTION:
TANBARK BRANCH 2 3.0
END DESCRIPTION:
XS GIS Cut Line= 3
      3610247.05     10618517.29      3610545.68     10617836.71
      3610149.85     10617239.49
#Sta/Elev= 30
  4079.6  379.05  4298.9  374.61  4525.6  372.55  4566.8  370.59  4835.6  373.66
  4926.6  374.59  4969.1   371.6  4975.1  361.91  4998.3  353.92  5005.2   356.1
  5020.2   357.5  5026.2  361.44  5034.6  361.73  5041.3  368.02  5047.3  365.17
  5083.4  374.03  5092.4   377.2  5106.6  379.26  5113.5  382.94  5119.5  382.53
  5164.6  390.22  5206.7  393.67  5214.5  396.15  5250.5   396.9  5278.9  399.88
  5351.1  408.63  5399.2  416.89  5424.9  419.09  5459.4  420.09  5539.3  417.29
#Mann= 7 ,-1 , 0
  4079.6     .05       0  4835.6     .05       0  4969.1     .03       0
  5041.3     .05       0  5083.4     .07       0  5399.2     .16       0
  5424.9     .05       0
Bank Sta=4969.1,5041.3
XS Rating Curve= 0 ,0
Exp/Cntr=0.3,0.1

Type RM Length L Ch R = 1 ,1390    ,620,620,620
BEGIN DESCRIPTION:
TANBARK BRANCH 2 2.0
END DESCRIPTION:
XS GIS Cut Line= 3
      3610541.84     10618353.92      3610922.06     10617635.15
      3610989.77     10616807.06
#Sta/Elev= 30
  4317.2  372.92  4627.5  367.71  4943.1  370.03  4977.6  369.04  4984.7  352.83
    5000  349.68  5003.2  350.18  5006.7  356.63  5022.8  360.02  5028.7  367.27
  5050.7  365.44    5102  370.71  5286.9  370.51  5295.9  370.03  5315.9  358.32
    5326  357.71    5336  358.52    5346  365.09  5366.1   370.3  5376.1  370.38
  5396.2  358.15  5426.3  370.19  5466.4  372.44  5476.5  368.14  5486.5  359.25
  5496.5   359.1  5506.6  371.83  5525.7  376.39  5687.2  378.77  5961.2  393.74
#Mann= 5 ,-1 , 0
  4317.2     .05       0  4943.1     .05       0  4977.6     .03       0
  5028.7     .05       0  5286.9     .08       0
Bank Sta=4977.6,5028.7
XS Rating Curve= 0 ,0
Exp/Cntr=0.3,0.1

Type RM Length L Ch R = 1 ,770     ,0,0,0
BEGIN DESCRIPTION:
TANBARK BRANCH 2 1.0
END DESCRIPTION:
XS GIS Cut Line= 4
      3610703.31     10618468.48      3611166.85     10618140.35
      3611307.48     10617905.98       3611192.9     10617031.01
#Sta/Elev= 30
  4356.4   374.1  4609.8  369.77  4624.6  367.87  4704.7  368.32  4740.3  366.61
  4747.5  363.56    4776  365.34  4782.2  356.41  4790.8  355.98  4811.7  357.16
  4817.8  364.94  4841.3  359.28  4854.2  364.93  4917.6  364.49  4971.2  366.09
  4977.6  362.12  4983.5  353.45  4998.8  347.47  5014.6  350.48  5020.4   357.3
  5035.9  361.03  5041.8  364.55  5057.3  366.64  5098.2  366.57  5219.2  367.69
  5529.5  368.88  5667.4  372.87    5849  372.54  5992.6  378.52  6080.1  386.27
#Mann= 7 ,-1 , 0
  4356.4     .05       0  4747.5     .08       0  4917.6     .05       0
  4971.2     .03       0  5057.3     .05       0  5098.2     .07       0
  5219.2     .05       0
Bank Sta=4971.2,5057.3
XS Rating Curve= 0 ,0
Exp/Cntr=0.3,0.1

Chan Stop Cuts=-1
Use User Specified Reach Order=0
Composite Channel Slope=5