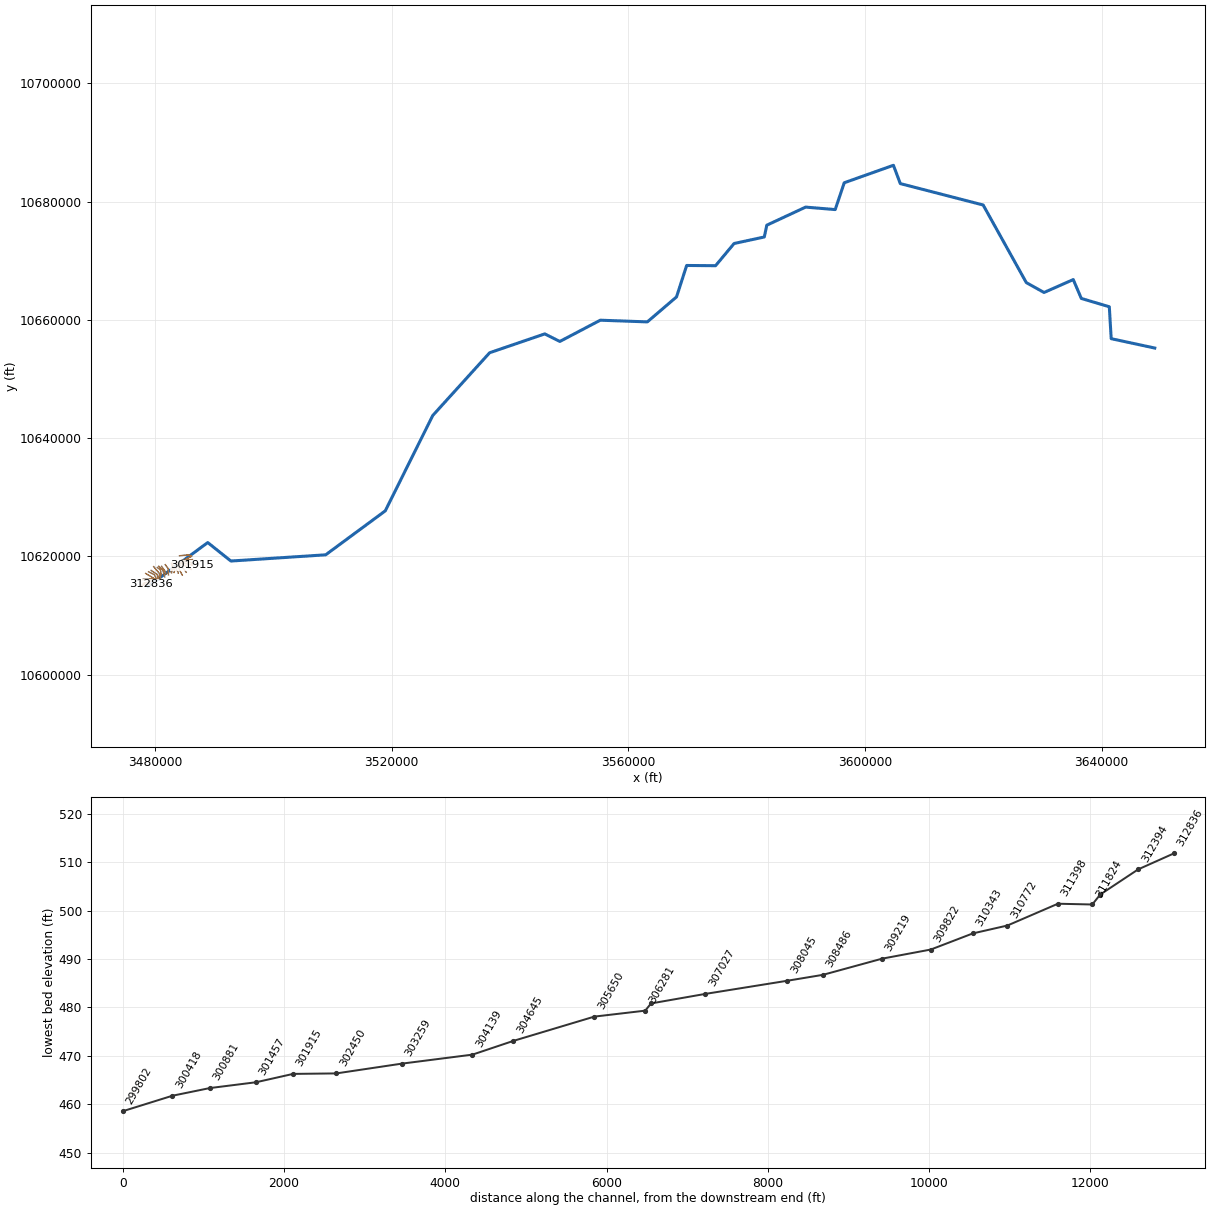
--- TEHUACANA CREEK.prj (project) ---

Proj Title=TEHUACANA CREEK Base Level Engineering
Current Plan=p01
Default Exp/Contr=0.3,0.1
English Units
Geom File=g01
Flow File=f01
Plan File=p01
Y Axis Title=Elevation
X Axis Title(PF)=Main Channel Distance
X Axis Title(XS)=Station
BEGIN DESCRIPTION:
TEHUACANA CREEK
END DESCRIPTION:
DSS Export Rating Curves= 0
DSS Export Rating Curve Sorted= 0
DSS Export Volume Flow Curves= 0
DXF OffsetX= 0
DXF OffsetY= 0
DXF ScaleX= 1
DXF ScaleY= 10

--- TEHUACANA CREEK.p01 (plan) ---

Plan Title=Multiple Run
Short Identifier=Multiple
Geom File=g01
Flow File=f01
Subcritical Flow
K Sum by GR= 0
Std Step Tol= 0.01
Critical Tol= 0.01
Num of Std Step Trials= 20
Max Error Tol= 0.3
Flow Tol Ratio= 0.001
Split Flow NTrial= 30
Split Flow Tol= 0.02
Split Flow Ratio= 0.02
Log Output Level= 0
Friction Slope Method= 1
Unsteady Friction Slope Method= 2
Unsteady Bridges Friction Slope Method= 1
Parabolic Critical Depth
Global Vel Dist=  1 , 1 , 1
Global Log Level= 0
CheckData=True
Encroach Param= -1, 0, 0, 0
BEGIN DESCRIPTION:
Multiple Run
END DESCRIPTION:

--- TEHUACANA CREEK.f01 (steady flow) ---

Flow Title=Multiple
Program Version=4.10
Number of Profiles= 7
Profile Names=10-year,25-year,50-year,1pct_min,100-year,1pct_plu,500-year
River Rch & RM=TEHUACANA CREEK,Reach-1         ,312836
    2636    3812    4831    4460    6032    8158    9389
River Rch & RM=TEHUACANA CREEK,Reach-1         ,309219
    3101    4500    5714    5282    7143    9660   11145
River Rch & RM=TEHUACANA CREEK,Reach-1         ,302450
    3511    5109    6498    6012    8130   10995   12712
River Rch & RM=TEHUACANA CREEK,Reach-1         ,297733
    3785    5527    7046    6533    8836   11949   13874
River Rch & RM=TEHUACANA CREEK,Reach-1         ,294459
    5284    7785    9986    9302   12580   17013   19941
River Rch & RM=TEHUACANA CREEK,Reach-1         ,285270
    5527    8161   10482    9778   13223   17883   21016
River Rch & RM=TEHUACANA CREEK,Reach-1         ,284581
    5527    8161   10482    9778   13223   17883   21016
River Rch & RM=TEHUACANA CREEK,Reach-1         ,283044
    7126   10585   13652   12777   17279   23368   27639
River Rch & RM=TEHUACANA CREEK,Reach-1         ,282697
    7126   10585   13652   12777   17279   23368   27639
River Rch & RM=TEHUACANA CREEK,Reach-1         ,279197
    7359   10948   14135   13242   17909   24220   28706
River Rch & RM=TEHUACANA CREEK,Reach-1         ,276167
    7760   11561   14941   14009   18945   25621   30416
River Rch & RM=TEHUACANA CREEK,Reach-1         ,275482
    7760   11561   14941   14009   18945   25621   30416
River Rch & RM=TEHUACANA CREEK,Reach-1         ,273421
    7841   11657   15043   14081   19043   25753   30469
River Rch & RM=TEHUACANA CREEK,Reach-1         ,269456
    8137   12104   15625   14630   19785   26757   31670
River Rch & RM=TEHUACANA CREEK,Reach-1         ,264881
    8287   12301   15856   14820   20043   27105   31973
River Rch & RM=TEHUACANA CREEK,Reach-1         ,262772
    8287   12301   15856   14820   20043   27105   31973
River Rch & RM=TEHUACANA CREEK,Reach-1         ,257892
   18496   28058   36725   34804   47069   63655   77127
River Rch & RM=TEHUACANA CREEK,Reach-1         ,253464
   18496   28058   36725   34804   47069   63655   77127
River Rch & RM=TEHUACANA CREEK,Reach-1         ,250752
   18496   28058   36725   34804   47069   63655   77127
River Rch & RM=TEHUACANA CREEK,Reach-1         ,246037
   18736   28405   37164   35204   47610   64386   77937
River Rch & RM=TEHUACANA CREEK,Reach-1         ,243927
   18736   28405   37164   35204   47610   64386   77937
River Rch & RM=TEHUACANA CREEK,Reach-1         ,240569
   19614   29741   38920   36870   49862   67433   81629
River Rch & RM=TEHUACANA CREEK,Reach-1         ,237539
   19815   30046   39319   37248   50374   68125   82466
River Rch & RM=TEHUACANA CREEK,Reach-1         ,236850
   19815   30046   39319   37248   50374   68125   82466
River Rch & RM=TEHUACANA CREEK,Reach-1         ,228645
   19815   30046   39319   37248   50374   68125   82466
River Rch & RM=TEHUACANA CREEK,Reach-1         ,224068
   20634   31121   40577   38287   51779   70026   84078
River Rch & RM=TEHUACANA CREEK,Reach-1         ,215676
   20634   31121   40577   38287   51779   70026   84078
River Rch & RM=TEHUACANA CREEK,Reach-1         ,214529
   24482   37004   48329   45665   61757   83519  100534
River Rch & RM=TEHUACANA CREEK,Reach-1         ,206546
   29170   44073   57559   54371   73530   99441  119578
River Rch & RM=TEHUACANA CREEK,Reach-1         ,204446
   29170   44073   57559   54371   73530   99441  119578
River Rch & RM=TEHUACANA CREEK,Reach-1         ,196031
   29170   44073   57559   54371   73530   99441  119578
River Rch & RM=TEHUACANA CREEK,Reach-1         ,189255
   29170   44073   57559   54371   73530   99441  119578
River Rch & RM=TEHUACANA CREEK,Reach-1         ,187775
   29170   44073   57559   54371   73530   99441  119578
River Rch & RM=TEHUACANA CREEK,Reach-1         ,181711
   29170   44073   57559   54371   73530   99441  119578
River Rch & RM=TEHUACANA CREEK,Reach-1         ,179885
   29170   44073   57559   54371   73530   99441  119578
River Rch & RM=TEHUACANA CREEK,Reach-1         ,174696
   29170   44073   57559   54371   73530   99441  119578
River Rch & RM=TEHUACANA CREEK,Reach-1         ,173560
   29170   44073   57559   54371   73530   99441  119578
River Rch & RM=TEHUACANA CREEK,Reach-1         ,167385
   29170   44073   57559   54371   73530   99441  119578
River Rch & RM=TEHUACANA CREEK,Reach-1         ,162940
   30180   45352   59013   55528   75095  101557  121150
River Rch & RM=TEHUACANA CREEK,Reach-1         ,158624
   40101   60287   78515   73923   99973  135201  161362
River Rch & RM=TEHUACANA CREEK,Reach-1         ,157152
   40101   60287   78515   73923   99973  135201  161362
River Rch & RM=TEHUACANA CREEK,Reach-1         ,150374
   40101   60287   78515   73923   99973  135201  161362
River Rch & RM=TEHUACANA CREEK,Reach-1         ,148895
   41334   61942   80500   75623  102272  138311  164313
River Rch & RM=TEHUACANA CREEK,Reach-1         ,142109
   41334   61942   80500   75623  102272  138311  164313
River Rch & RM=TEHUACANA CREEK,Reach-1         ,128694
   41334   61942   80500   75623  102272  138311  164313
River Rch & RM=TEHUACANA CREEK,Reach-1         ,127287
   41334   61942   80500   75623  102272  138311  164313
River Rch & RM=TEHUACANA CREEK,Reach-1         ,121800
   41334   61942   80500   75623  102272  138311  164313
River Rch & RM=TEHUACANA CREEK,Reach-1         ,116306
   41529   62155   80709   75752  102446  138546  164313
River Rch & RM=TEHUACANA CREEK,Reach-1         ,109998
   41574   62166   80709   75752  102446  138546  164313
River Rch & RM=TEHUACANA CREEK,Reach-1         ,108339
   41746   62405   80967   75929  102686  138870  164391
River Rch & RM=TEHUACANA CREEK,Reach-1         ,106890
   41746   62405   80967   75929  102686  138870  164391
River Rch & RM=TEHUACANA CREEK,Reach-1         ,98904
   41746   62405   80967   75929  102686  138870  164391
River Rch & RM=TEHUACANA CREEK,Reach-1         ,97429
   41746   62405   80967   75929  102686  138870  164391
River Rch & RM=TEHUACANA CREEK,Reach-1         ,91239
   41746   62405   80967   75929  102686  138870  164391
River Rch & RM=TEHUACANA CREEK,Reach-1         ,88818
   45771   68128   88154   82432  111480  150764  177385
River Rch & RM=TEHUACANA CREEK,Reach-1         ,85492
   45771   68128   88154   82432  111480  150764  177385
River Rch & RM=TEHUACANA CREEK,Reach-1         ,81722
   45771   68128   88154   82432  111480  150764  177385
River Rch & RM=TEHUACANA CREEK,Reach-1         ,73065
   45771   68128   88154   82432  111480  150764  177385
River Rch & RM=TEHUACANA CREEK,Reach-1         ,68139
   47738   71102   92052   86123  116472  157515  185512
River Rch & RM=TEHUACANA CREEK,Reach-1         ,63596
   47738   71102   92052   86123  116472  157515  185512
River Rch & RM=TEHUACANA CREEK,Reach-1         ,57358
   47746   71102   92052   86123  116472  157515  185512
River Rch & RM=TEHUACANA CREEK,Reach-1         ,40819
   47996   71321   92193   86123  116472  157515  185512
River Rch & RM=TEHUACANA CREEK,Reach-1         ,36188
   48399   71896   92916   86772  117350  158702  186205
River Rch & RM=TEHUACANA CREEK,Reach-1         ,35229
   48399   71896   92916   86772  117350  158702  186205
River Rch & RM=TEHUACANA CREEK,Reach-1         ,25674
   48399   71896   92916   86772  117350  158702  186205
River Rch & RM=TEHUACANA CREEK,Reach-1         ,9995
   51193   75832   97833   91201  123338  166801  194973
Boundary for River Rch & Prof#=TEHUACANA CREEK,Reach-1         , 1
Up Type= 0
Dn Type= 3
Dn Slope=0.00059
Boundary for River Rch & Prof#=TEHUACANA CREEK,Reach-1         , 2
Up Type= 0
Dn Type= 3
Dn Slope=0.00059
Boundary for River Rch & Prof#=TEHUACANA CREEK,Reach-1         , 3
Up Type= 0
Dn Type= 3
Dn Slope=0.00059
Boundary for River Rch & Prof#=TEHUACANA CREEK,Reach-1         , 4
Up Type= 0
Dn Type= 3
Dn Slope=0.00059
Boundary for River Rch & Prof#=TEHUACANA CREEK,Reach-1         , 5
Up Type= 0
Dn Type= 3
Dn Slope=0.00059
Boundary for River Rch & Prof#=TEHUACANA CREEK,Reach-1         , 6
Up Type= 0
Dn Type= 3
Dn Slope=0.00059
Boundary for River Rch & Prof#=TEHUACANA CREEK,Reach-1         , 7
Up Type= 0
Dn Type= 3
Dn Slope=0.00059
DSS Import GetInterval= 0
DSS Import GetPeak= 0
DSS Import FillOption= 0

--- TEHUACANA CREEK.g01 (geometry) ---

Geom Title=Existing Conditions
Program Version=4.10

River Reach=TEHUACANA CREEK ,Reach-1
Reach XY= 30
       3478846.5       10614909.      3488942.75       10622325.
      3492855.25       10619202.      3508868.25       10620254.
        3518939.       10627690.        3526963.       10643819.
      3536573.25       10654433.       3545889.5       10657621.
        3548434.       10656342.        3555269.       10659937.
      3563218.25       10659653.        3568152.       10663873.
      3569866.75       10669195.        3574752.       10669155.
       3577879.5       10672910.      3582986.25       10674013.
       3583406.5       10676005.      3589971.25       10679067.
      3594967.25       10678650.       3596493.5       10683182.
      3604805.25       10686139.       3605966.5       10683044.
       3619967.5       10679423.        3627257.       10666295.
        3630252.       10664624.       3635191.5       10666806.
      3636553.75       10663618.      3641284.75       10662209.
        3641602.       10656813.       3648965.3     10655226.66

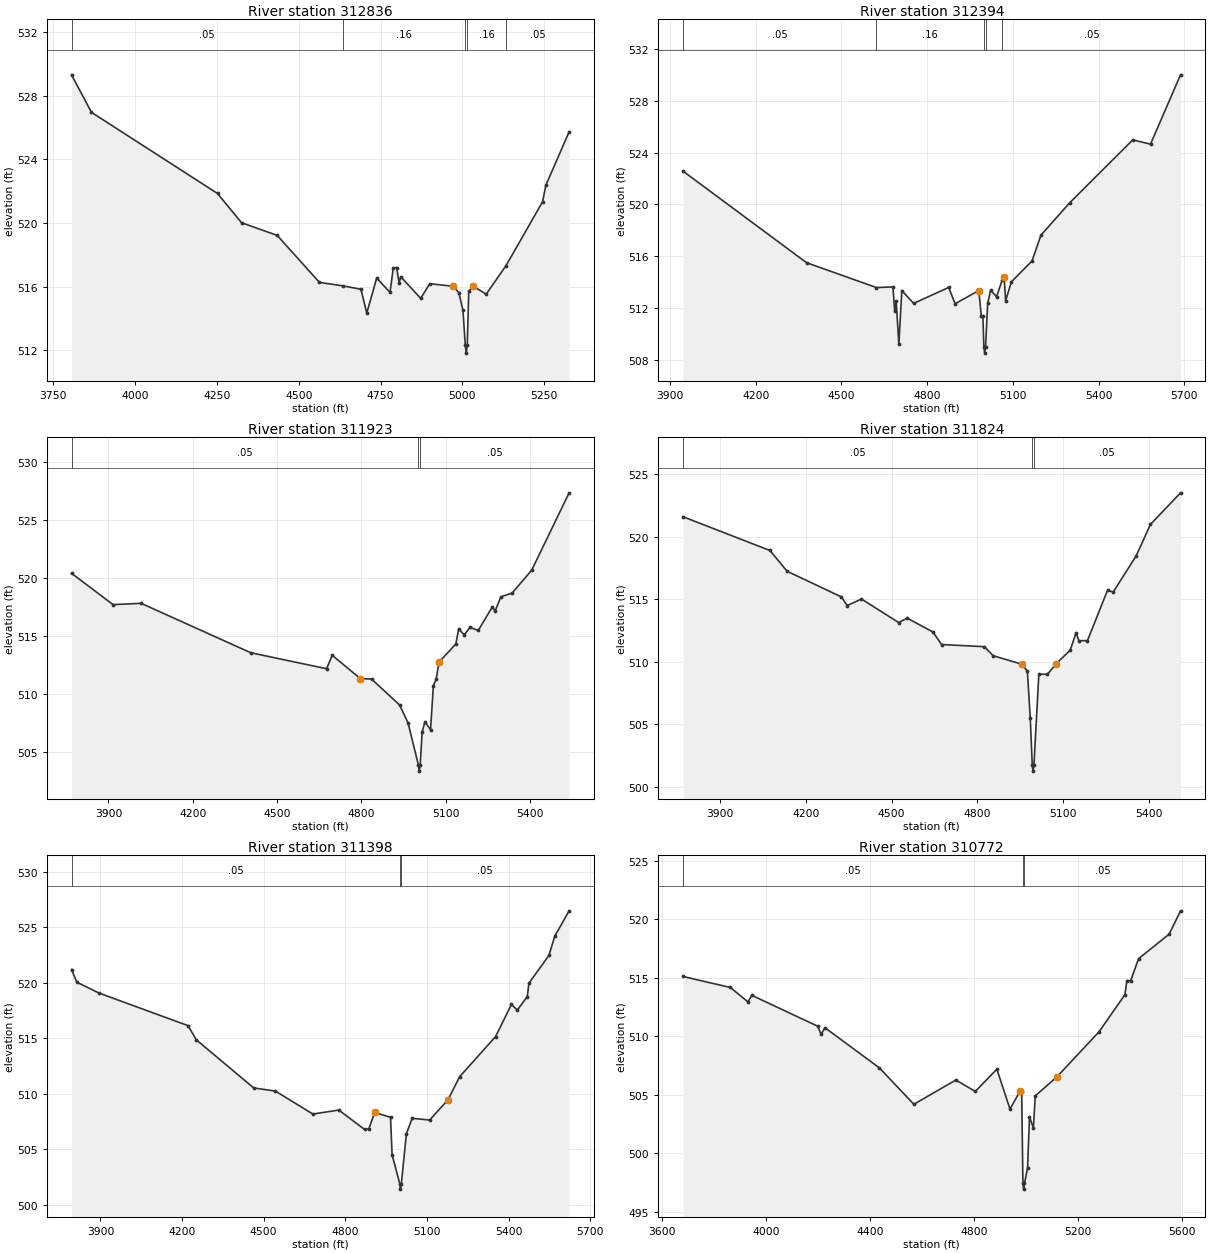
Type RM Length L Ch R = 1 ,312836  ,442,442,442
BEGIN DESCRIPTION:
TEHUACANA CREEK 259.0
END DESCRIPTION:
XS GIS Cut Line= 3
      3477799.59     10615110.19      3478999.61     10615310.19
       3479299.6     10615260.19
#Sta/Elev= 30
  3805.6  529.33  3866.4  526.97  4251.7  521.86  4325.2  520.02  4434.2  519.22
  4563.4  516.26    4634  516.05  4690.2  515.83  4707.9  514.33  4738.3  516.54
  4778.9  515.63    4789  517.18  4799.1   517.2  4806.7  516.22  4811.8  516.62
  4872.6  515.26  4900.5  516.18  4971.5  516.02  4989.2  515.62  5001.9  514.51
    5009  512.31  5011.8  511.81    5015  512.31  5019.6  515.69  5032.3  516.03
  5072.9  515.52  5133.6  517.32  5245.2  521.34  5255.3  522.38  5326.3  525.74
#Mann= 5 ,-1 , 0
  3805.6     .05       0    4634     .16       0    5009     .07       0
    5015     .16       0  5133.6     .05       0
Bank Sta=4971.5,5032.3
XS Rating Curve= 0 ,0
Exp/Cntr=0.3,0.1

Type RM Length L Ch R = 1 ,312394  ,471,471,471
BEGIN DESCRIPTION:
TEHUACANA CREEK 258.0
END DESCRIPTION:
XS GIS Cut Line= 2
      3478060.49      10615421.4      3479741.02     10615876.26
#Sta/Elev= 30
  3945.4  522.57  4377.7   515.5  4622.5  513.58    4680  513.63  4686.2  511.77
  4691.4  512.55  4700.8   509.2  4711.1  513.35  4752.6  512.36  4875.1  513.59
  4897.6  512.33  4980.5  513.35  4989.5  511.35  4994.7  511.41  4998.2  509.02
  5000.9  508.52  5004.2  509.02  5011.5  512.36  5021.9  513.37  5042.6  512.88
    5063   514.2  5069.2  514.42  5074.4  512.56  5094.4  514.02  5166.9  515.64
    5198  517.63    5298  520.11  5519.2  524.98  5581.3  524.65  5686.4     530
#Mann= 5 ,-1 , 0
  3945.4     .05       0  4622.5     .16       0  4998.2     .07       0
  5004.2     .16       0    5063     .05       0
Bank Sta=4980.5,5069.2
XS Rating Curve= 0 ,0
Exp/Cntr=0.3,0.1

Type RM Length L Ch R = 1 ,311923  ,99,99,99
BEGIN DESCRIPTION:
TEHUACANA CREEK 257.0
END DESCRIPTION:
XS GIS Cut Line= 2
      3478011.88     10616042.93      3479782.72     10616056.81
#Sta/Elev= 30
  3768.8  520.38  3916.5  517.68  4016.5  517.79  4406.6  513.53  4676.6  512.15
  4696.6  513.31  4796.6   511.3  4836.6  511.26  4936.6  509.02  4966.6  507.47
  5003.6  503.82  5006.3  503.32  5009.6  503.82  5016.6  506.68  5026.6  507.58
  5046.6  506.89  5056.6  510.69  5066.6  511.26  5076.6  512.72  5136.6  514.29
  5146.6  515.58  5166.6  515.08  5186.6  515.71  5216.6  515.46  5266.6  517.49
  5276.6  517.13  5296.6  518.35    5337  518.68  5406.6  520.65  5539.7  527.32
#Mann= 3 ,-1 , 0
  3768.8     .05       0  5003.6     .03       0  5009.6     .05       0
Bank Sta=4796.6,5076.6
XS Rating Curve= 0 ,0
Exp/Cntr=0.3,0.1

Type RM Length L Ch R = 1 ,311824  ,426,426,426
BEGIN DESCRIPTION:
TEHUACANA CREEK 256.0
END DESCRIPTION:
XS GIS Cut Line= 2
      3478025.73     10616147.09      3479764.93     10616150.56
#Sta/Elev= 30
  3770.6   521.6  4074.5   518.9  4134.5  517.24  4324.5  515.19  4344.5   514.5
  4394.5  515.02  4524.5  513.14  4554.5  513.49  4644.5  512.38  4674.5  511.38
  4824.5  511.21  4854.5  510.49  4954.5  509.81  4974.5  509.25  4984.5  505.49
  4991.5  501.76  4994.2  501.26  4997.5  501.76  5014.5  509.01  5044.5     509
  5074.5  509.83  5124.5  510.94  5144.5  512.32  5154.5  511.68  5184.5   511.7
  5254.5  515.71  5274.5  515.58  5354.5  518.46  5404.5  520.98  5509.8  523.51
#Mann= 3 ,-1 , 0
  3770.6     .05       0  4991.5     .04       0  4997.5     .05       0
Bank Sta=4954.5,5074.5
XS Rating Curve= 0 ,0
Exp/Cntr=0.3,0.1

Type RM Length L Ch R = 1 ,311398  ,626,626,626
BEGIN DESCRIPTION:
TEHUACANA CREEK 255.0
END DESCRIPTION:
XS GIS Cut Line= 2
      3478452.81     10617101.97      3480018.84     10616157.49
#Sta/Elev= 30
  3793.8  521.19  3813.4  520.05  3895.2  519.07  4222.1  516.14  4251.8  514.88
  4463.4  510.53    4543  510.25  4680.8  508.18    4776  508.54  4871.1  506.79
  4886.6  506.84    4908  508.33  4966.2  507.88    4972  504.52  5000.1  501.92
  5002.8  501.42  5006.1  501.92  5024.4  506.39  5045.8   507.8  5109.9  507.64
  5177.8  509.48  5220.5  511.55  5352.5  515.16  5410.8  518.06  5432.1  517.54
    5469  518.76  5474.8  519.96  5548.6  522.47    5570   524.2  5622.6  526.48
#Mann= 3 ,-1 , 0
  3793.8     .05       0  5000.1    .035       0  5006.1     .05       0
Bank Sta=4908,5177.8
XS Rating Curve= 0 ,0
Exp/Cntr=0.3,0.1

Type RM Length L Ch R = 1 ,310772  ,429,429,429
BEGIN DESCRIPTION:
TEHUACANA CREEK 254.0
END DESCRIPTION:
XS GIS Cut Line= 3
      3478937.78     10617386.68      3479937.79     10616865.84
       3480284.8     10616157.94
#Sta/Elev= 30
  3679.8  515.09  3862.3  514.15  3929.9  512.92  3944.8  513.48  4198.7  510.84
  4211.8  510.14  4226.5  510.71  4436.2  507.28  4568.8  504.17  4730.4  506.24
  4805.5  505.27  4888.5  507.17    4939  503.76  4978.5  505.33    4984  505.21
  4988.8  497.42  4991.6  496.92  4994.8  497.42  5006.5  498.69  5014.1  503.09
    5029  502.15  5036.4  504.89    5119   506.5  5282.1  510.37  5381.6  513.54
    5389  514.74  5403.9  514.73    5434  516.61    5552  518.71  5595.7   520.7
#Mann= 3 ,-1 , 0
  3679.8     .05       0  4988.8    .035       0  4994.8     .05       0
Bank Sta=4978.5,5119
XS Rating Curve= 0 ,0
Exp/Cntr=0.3,0.1

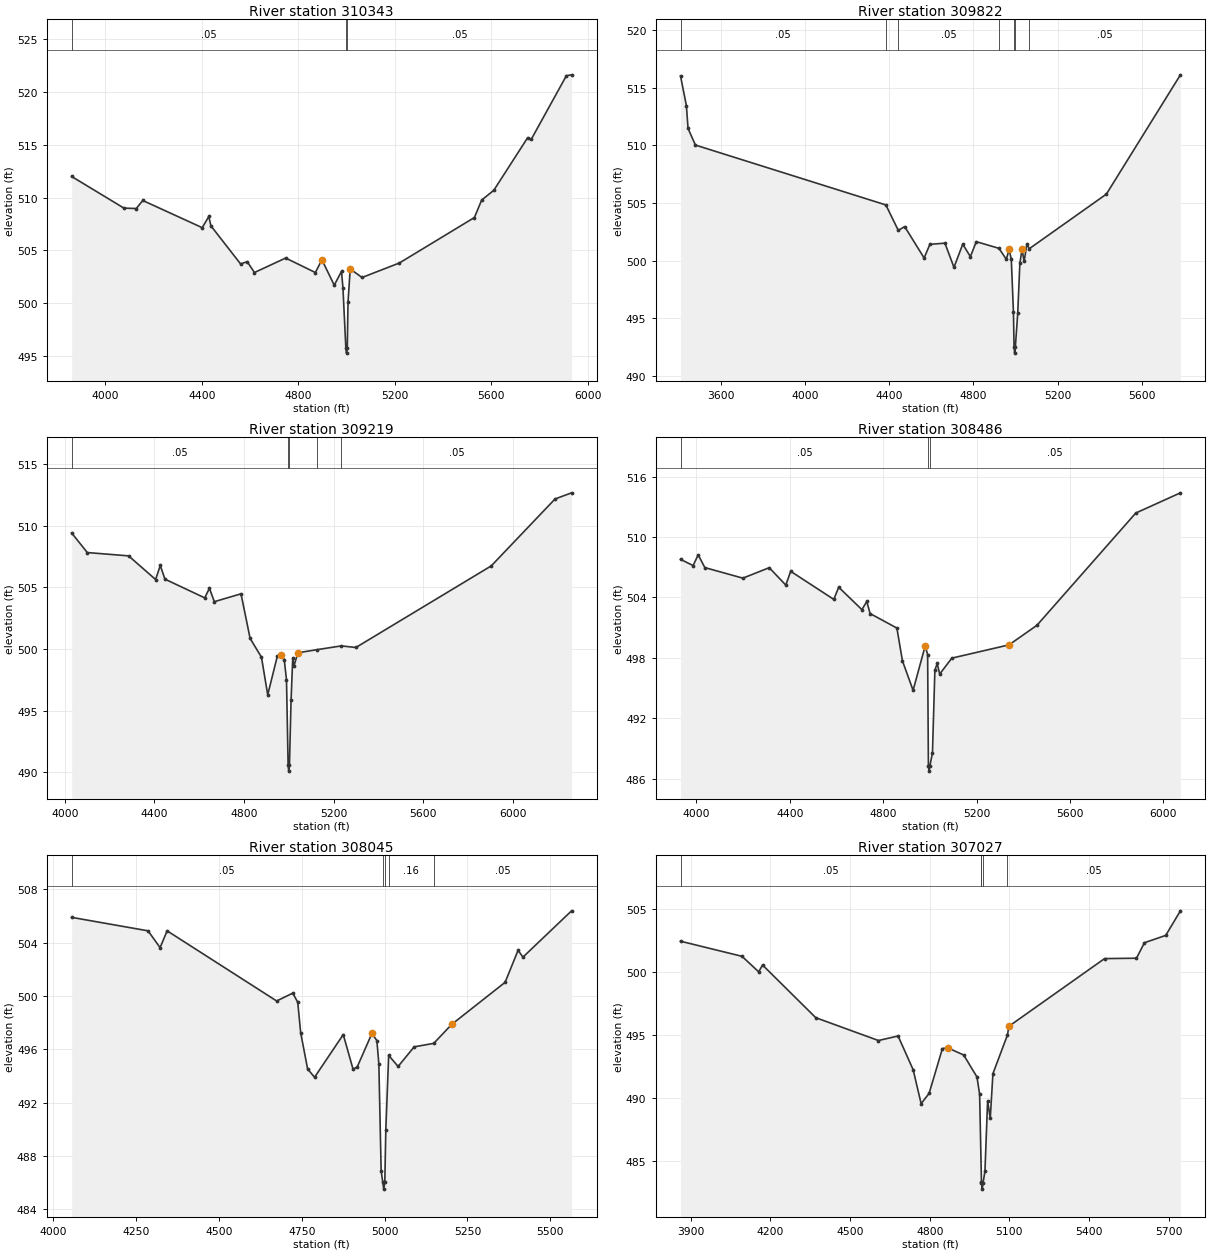
Type RM Length L Ch R = 1 ,310343  ,521,521,521
BEGIN DESCRIPTION:
TEHUACANA CREEK 253.0
END DESCRIPTION:
XS GIS Cut Line= 3
      3479375.29     10617615.85       3480423.9      10616921.4
      3480500.29      10616108.9
#Sta/Elev= 30
  3859.8  511.99  4076.6     509  4127.8  508.96  4154.8  509.72  4401.5  507.15
  4428.7  508.21  4437.6  507.32  4560.6  503.72    4588  503.94  4618.1  502.91
  4747.5  504.28  4870.8  502.91  4897.9  504.12  4949.1  501.71  4979.2  503.02
  4985.2  501.46  4997.2  495.79    5000  495.29  5003.2  495.79  5006.2  500.09
  5015.3  503.25  5064.4  502.44  5219.2  503.81  5530.5  508.11  5560.7  509.76
  5610.9  510.68  5751.5  515.66  5766.3   515.5  5912.2  521.52  5933.6   521.6
#Mann= 3 ,-1 , 0
  3859.8     .05       0  4997.2    .035       0  5003.2     .05       0
Bank Sta=4897.9,5015.3
XS Rating Curve= 0 ,0
Exp/Cntr=0.3,0.1

Type RM Length L Ch R = 1 ,309822  ,603,603,603
BEGIN DESCRIPTION:
TEHUACANA CREEK 252.0
END DESCRIPTION:
XS GIS Cut Line= 3
      3479799.62     10618260.18      3480799.61     10617060.19
       3480649.6     10616260.16
#Sta/Elev= 30
  3407.6  516.03  3435.6  513.45  3443.4  511.47  3478.5  510.03  4383.6  504.83
  4442.7  502.62    4473  502.95  4565.5  500.22  4592.8  501.41  4664.4  501.51
  4707.3  499.41    4749  501.42  4785.4  500.34  4813.4  501.64  4921.4  501.06
    4956  500.11  4969.6  500.97  4979.8   500.1    4990  495.52  4992.9  492.46
  4995.7  491.96  4998.9  492.46  5010.3  495.41  5020.5  499.76  5030.7  500.97
  5040.9  499.92  5053.6  501.43  5065.5  501.03  5431.7  505.77  5783.6  516.13
#Mann= 7 ,-1 , 0
  3407.6     .05       0  4383.6     .16       0  4442.7     .05       0
  4921.4     .16       0  4992.9     .07       0  4998.9     .16       0
  5065.5     .05       0
Bank Sta=4969.6,5030.7
XS Rating Curve= 0 ,0
Exp/Cntr=0.3,0.1

Type RM Length L Ch R = 1 ,309219  ,733,733,733
BEGIN DESCRIPTION:
TEHUACANA CREEK 251.0
END DESCRIPTION:
XS GIS Cut Line= 4
      3480423.93     10618122.76      3480951.68      10617671.4
      3481062.79     10617060.29      3480896.12     10616157.51
#Sta/Elev= 30
    4030  509.42  4099.9  507.83  4284.4  507.56  4405.1  505.64    4426  506.78
  4446.8  505.67  4624.7  504.15  4645.5  504.93  4667.5  503.84  4786.6  504.48
  4827.3  500.86  4878.1  499.33    4906  496.28  4949.3  499.44  4964.5  499.52
  4979.8  499.14  4989.9  497.51  4997.1  490.58  4999.8  490.08  5003.1  490.58
  5010.3  495.83  5017.8  499.27  5022.9   498.6  5040.7  499.69    5125  499.94
  5234.8  500.25  5299.9  500.12    5905  506.75  6189.7  512.18  6263.6  512.68
#Mann= 5 ,-1 , 0
    4030     .05       0  4997.1    .035       0  5003.1     .05       0
    5125     .16       0  5234.8     .05       0
Bank Sta=4964.5,5040.7
XS Rating Curve= 0 ,0
Exp/Cntr=0.3,0.1

Type RM Length L Ch R = 1 ,308486  ,441,441,441
BEGIN DESCRIPTION:
TEHUACANA CREEK 250.0
END DESCRIPTION:
XS GIS Cut Line= 3
      3480659.99     10618317.25      3481347.51     10617699.18
      3481666.96     10616525.57
#Sta/Elev= 30
  3932.3  507.79  3986.3  507.17    4008  508.24  4036.4  506.97  4199.3  505.92
  4312.2  506.96  4383.2  505.23  4404.1   506.6  4588.7  503.81  4609.7  505.02
  4709.1  502.79    4730   503.6  4744.2   502.4  4858.9  500.96  4882.7   497.7
  4928.3  494.77  4980.1  499.19  4990.5  498.33  4993.9  487.24  4996.6  486.74
  4999.9  487.24  5011.2  488.54  5021.6  496.77  5031.4  497.44  5042.3  496.39
  5094.1  497.97  5339.2  499.29  5458.5  501.23  5881.8  512.39  6073.1   514.4
#Mann= 3 ,-1 , 0
  3932.3     .05       0  4993.9    .035       0  4999.9     .05       0
Bank Sta=4980.1,5339.2
XS Rating Curve= 0 ,0
Exp/Cntr=0.3,0.1

Type RM Length L Ch R = 1 ,308045  ,1018,1018,1018
BEGIN DESCRIPTION:
TEHUACANA CREEK 249.0
END DESCRIPTION:
XS GIS Cut Line= 3
      3481149.61     10618310.18      3481699.61     10617510.19
       3481899.6     10617010.22
#Sta/Elev= 30
    4055   505.9  4285.6  504.89    4322  503.63  4343.2  504.89  4673.9  499.63
  4722.7  500.22  4737.6  499.53  4746.4  497.25  4767.4  494.53  4788.4  493.91
    4875  497.11  4904.5  494.52  4916.9  494.67  4961.6   497.2  4976.5  496.66
  4982.5   494.9  4989.4  486.89  4994.4  486.02  4997.2  485.52  5000.4  486.02
  5003.5  489.99  5012.1  495.55  5040.6  494.72  5089.1  496.19  5148.2  496.45
  5202.2  497.87  5363.7  501.03  5402.8  503.43  5417.6  502.92  5564.3  506.39
#Mann= 5 ,-1 , 0
    4055     .05       0  4994.4    .035       0  5000.4     .05       0
  5012.1     .16       0  5148.2     .05       0
Bank Sta=4961.6,5202.2
XS Rating Curve= 0 ,0
Exp/Cntr=0.3,0.1

Type RM Length L Ch R = 1 ,307027  ,674,674,674
BEGIN DESCRIPTION:
TEHUACANA CREEK 248.0
END DESCRIPTION:
XS GIS Cut Line= 3
      3481763.32     10618586.75      3482249.42     10617927.04
      3482304.96     10616864.86
#Sta/Elev= 30
  3861.1  502.47  4092.8  501.27  4155.5  500.04  4170.2  500.58  4370.7   496.4
  4606.7  494.59  4680.6  494.95  4737.5  492.27  4767.5  489.58  4797.6   490.4
  4847.6  493.95  4867.7  494.01  4927.8  493.44  4977.8   491.7  4987.8  490.33
  4994.7   483.4  4994.8   483.3  4997.6   482.8  5000.8   483.3  5007.9  484.23
  5017.9   489.8  5027.9  488.42  5037.9  491.96  5092.7  495.03    5098  495.72
  5458.5  501.09  5578.6  501.12  5608.7  502.35  5688.8  502.93  5744.2  504.88
#Mann= 5 ,-1 , 0
  3861.1     .05       0  4994.7     .16       0  4994.8     .07       0
  5000.8     .16       0  5092.7     .05       0
Bank Sta=4867.7,5098
XS Rating Curve= 0 ,0
Exp/Cntr=0.3,0.1

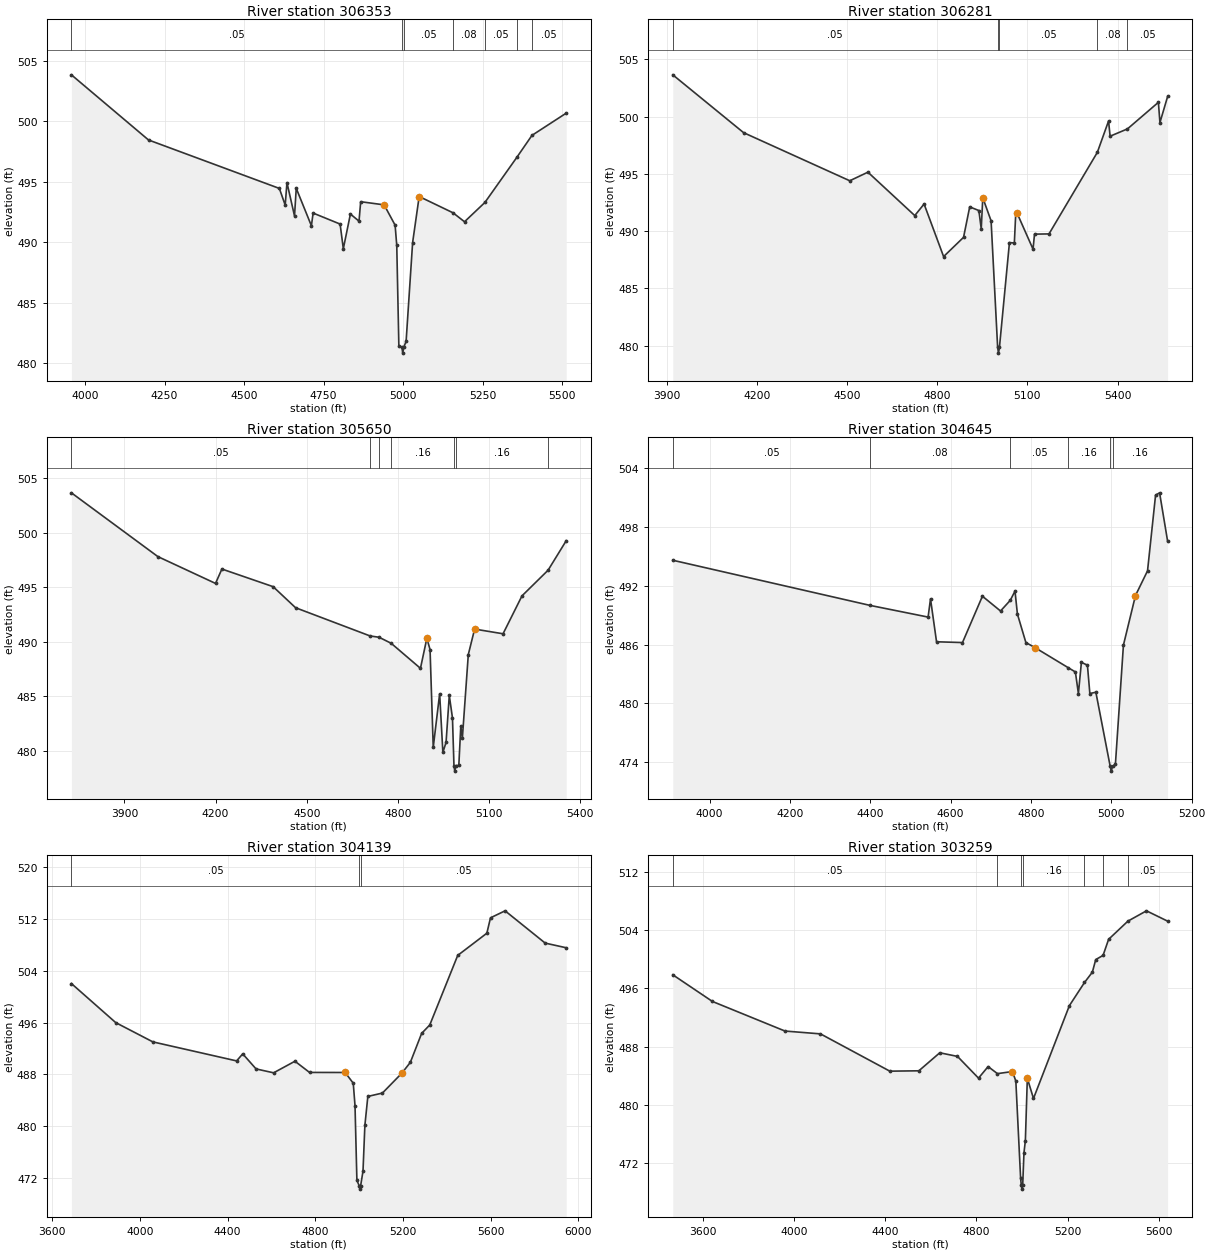
Type RM Length L Ch R = 1 ,306353  ,72,72,72
BEGIN DESCRIPTION:
TEHUACANA CREEK 247.0
END DESCRIPTION:
XS GIS Cut Line= 6
      3482783.63     10618773.47      3482993.39     10618180.44
      3482923.66     10618013.09      3482861.16     10617799.55
      3482835.12     10617690.17      3482767.52     10617284.57
#Sta/Elev= 30
  3956.9  503.86  4199.4  498.47    4611  494.46  4629.4  493.08  4634.9  494.94
  4658.7  492.18  4664.1  494.47  4711.8  491.37  4717.2  492.42  4802.1  491.51
  4812.2  489.47  4834.5  492.34  4861.6  491.75  4866.8  493.36  4940.6   493.1
  4975.1  491.42  4980.3  489.74  4986.9  481.44  4996.4  481.33  4999.1  480.83
  5002.4  481.33  5009.7   481.8  5030.2  489.98  5050.8  493.79  5157.5  492.44
  5193.4   491.7  5257.6   493.3  5357.7  497.02  5405.6  498.85  5513.4  500.69
#Mann= 7 ,-1 , 0
  3956.9     .05       0  4996.4    .035       0  5002.4     .05       0
  5157.5     .08       0  5257.6     .05       0  5357.7     .08       0
  5405.6     .05       0
Bank Sta=4940.6,5050.8
XS Rating Curve= 0 ,0
Exp/Cntr=0.3,0.1

Type RM Length L Ch R = 1 ,306281  ,631,631,631
BEGIN DESCRIPTION:
TEHUACANA CREEK 246.0
END DESCRIPTION:
XS GIS Cut Line= 6
      3482842.24     10618792.97      3483054.75     10618178.92
      3483006.99     10618070.38      3482975.74     10617981.84
      3482944.49     10617872.47       3482829.9     10617210.99
#Sta/Elev= 30
  3919.4  503.64  4155.1  498.59  4508.6  494.39    4569  495.14    4725  491.35
    4756  492.36    4821  487.77  4887.4  489.45  4907.9  492.11  4938.4  491.79
  4946.3  490.19  4951.4  492.91  4979.1  490.89  5000.9  479.84  5003.7  479.34
  5006.9  479.84  5040.2  488.99  5056.5  488.96  5061.3   491.6    5065   491.6
  5118.7  488.42  5123.7  489.73  5171.9  489.75  5332.8  496.87  5370.2  499.61
  5375.3  498.28  5433.2  498.92  5536.1  501.24  5541.2  499.47  5566.8  501.75
#Mann= 5 ,-1 , 0
  3919.4     .05       0  5000.9     .04       0  5006.9     .05       0
  5332.8     .08       0  5433.2     .05       0
Bank Sta=4951.4,5065
XS Rating Curve= 0 ,0
Exp/Cntr=0.3,0.1

Type RM Length L Ch R = 1 ,305650  ,1005,1005,1005
BEGIN DESCRIPTION:
TEHUACANA CREEK 245.0
END DESCRIPTION:
XS GIS Cut Line= 3
       3482949.6     10618810.21      3483349.61     10617610.19
      3483249.62     10617260.23
#Sta/Elev= 30
  3725.5  503.64  4010.1  497.79  4199.9  495.33  4220.9  496.65  4389.6  495.03
  4463.4   493.1  4708.7  490.51  4738.3  490.39    4778  489.84  4874.5  487.54
  4895.6   490.3  4906.1  489.26  4916.6  480.29  4937.7  485.21  4948.3  479.83
  4958.8  480.75  4969.4  485.05  4979.9  482.99  4984.8  478.61  4987.5  478.11
  4990.8  478.61  5000.8  478.63  5007.3  482.24  5012.5  481.15    5032   488.8
  5052.8  491.14  5146.4  490.71  5208.8  494.19  5294.6  496.54  5354.4  499.25
#Mann= 7 ,-1 , 0
  3725.5     .05       0  4708.7     .08       0  4738.3     .05       0
    4778     .16       0  4984.8     .07       0  4990.8     .16       0
  5294.6     .05       0
Bank Sta=4895.6,5052.8
XS Rating Curve= 0 ,0
Exp/Cntr=0.3,0.1

Type RM Length L Ch R = 1 ,304645  ,506,506,506
BEGIN DESCRIPTION:
TEHUACANA CREEK 244.0
END DESCRIPTION:
XS GIS Cut Line= 3
       3483349.6      10618210.2      3483949.61     10617310.19
      3483949.61     10617160.17
#Sta/Elev= 30
  3908.3  494.61  4399.6     490  4543.8  488.81  4549.8  490.67  4564.8  486.29
  4629.4  486.21    4679  490.94  4724.1  489.43  4748.3  490.52  4760.1  491.46
  4766.1  489.12  4787.2  486.21  4809.7   485.7  4893.2  483.63  4910.4  483.21
  4917.9  481.01  4925.4  484.19  4940.4   483.9  4946.4  481.01  4961.4  481.14
    4997  473.59  4999.7  473.09    5003  473.59    5010  473.77    5030  485.95
    5060  491.01    5090  493.53    5110  501.25    5120  501.49    5140  496.55
#Mann= 6 ,-1 , 0
  3908.3     .05       0  4399.6     .08       0  4748.3     .05       0
  4893.2     .16       0    4997     .07       0    5003     .16       0
Bank Sta=4809.7,5060
XS Rating Curve= 0 ,0
Exp/Cntr=0.3,0.1

Type RM Length L Ch R = 1 ,304139  ,880,880,880
BEGIN DESCRIPTION:
TEHUACANA CREEK 243.0
END DESCRIPTION:
XS GIS Cut Line= 2
      3483596.64     10618829.83      3484630.77     10616824.02
#Sta/Elev= 30
  3688.1  502.04  3890.2     496  4059.6  493.02  4441.5  490.08  4469.4  491.17
  4530.3  488.84  4610.3  488.24  4707.6  490.03  4774.1   488.3  4936.5  488.29
  4973.5  486.63  4981.5  483.16  4990.1   471.6    5001  470.76  5003.8  470.26
    5007  470.76  5017.9  473.03  5026.5  480.12    5040  484.59  5106.5  485.11
  5195.3  488.19  5233.9  489.86  5285.3  494.33  5322.5  495.64  5449.9  506.39
  5582.8  509.82  5599.4   512.2  5665.9  513.28  5848.8  508.29  5944.8  507.57
#Mann= 3 ,-1 , 0
  3688.1     .05       0    5001    .035       0    5007     .05       0
Bank Sta=4936.5,5195.3
XS Rating Curve= 0 ,0
Exp/Cntr=0.3,0.1

Type RM Length L Ch R = 1 ,303259  ,809,809,809
BEGIN DESCRIPTION:
TEHUACANA CREEK 241.0
END DESCRIPTION:
XS GIS Cut Line= 3
       3483825.8     10618892.33      3484888.31     10617885.37
      3485298.01     10617309.01
#Sta/Elev= 30
  3467.6  497.88  3641.5  494.21  3959.8  490.14  4115.6  489.75  4419.8  484.62
  4547.2  484.67    4639  487.15  4716.7  486.65  4808.9  483.66    4851  485.25
    4892  484.28  4957.9  484.57  4972.7  483.25  4993.6  469.91  4996.7  468.89
  4999.5  468.39  5002.7  468.89  5008.3  473.38  5014.5  475.07  5023.1  483.64
  5050.1  480.86  5207.7  493.64  5273.9  496.82  5308.4  498.24  5323.2  499.97
  5355.4  500.55  5379.7  502.76  5464.3  505.26  5545.8  506.68  5638.6  505.26
#Mann= 7 ,-1 , 0
  3467.6     .05       0    4892     .16       0  4996.7     .07       0
  5002.7     .16       0  5273.9     .05       0  5355.4     .16       0
  5464.3     .05       0
Bank Sta=4957.9,5023.1
XS Rating Curve= 0 ,0
Exp/Cntr=0.3,0.1

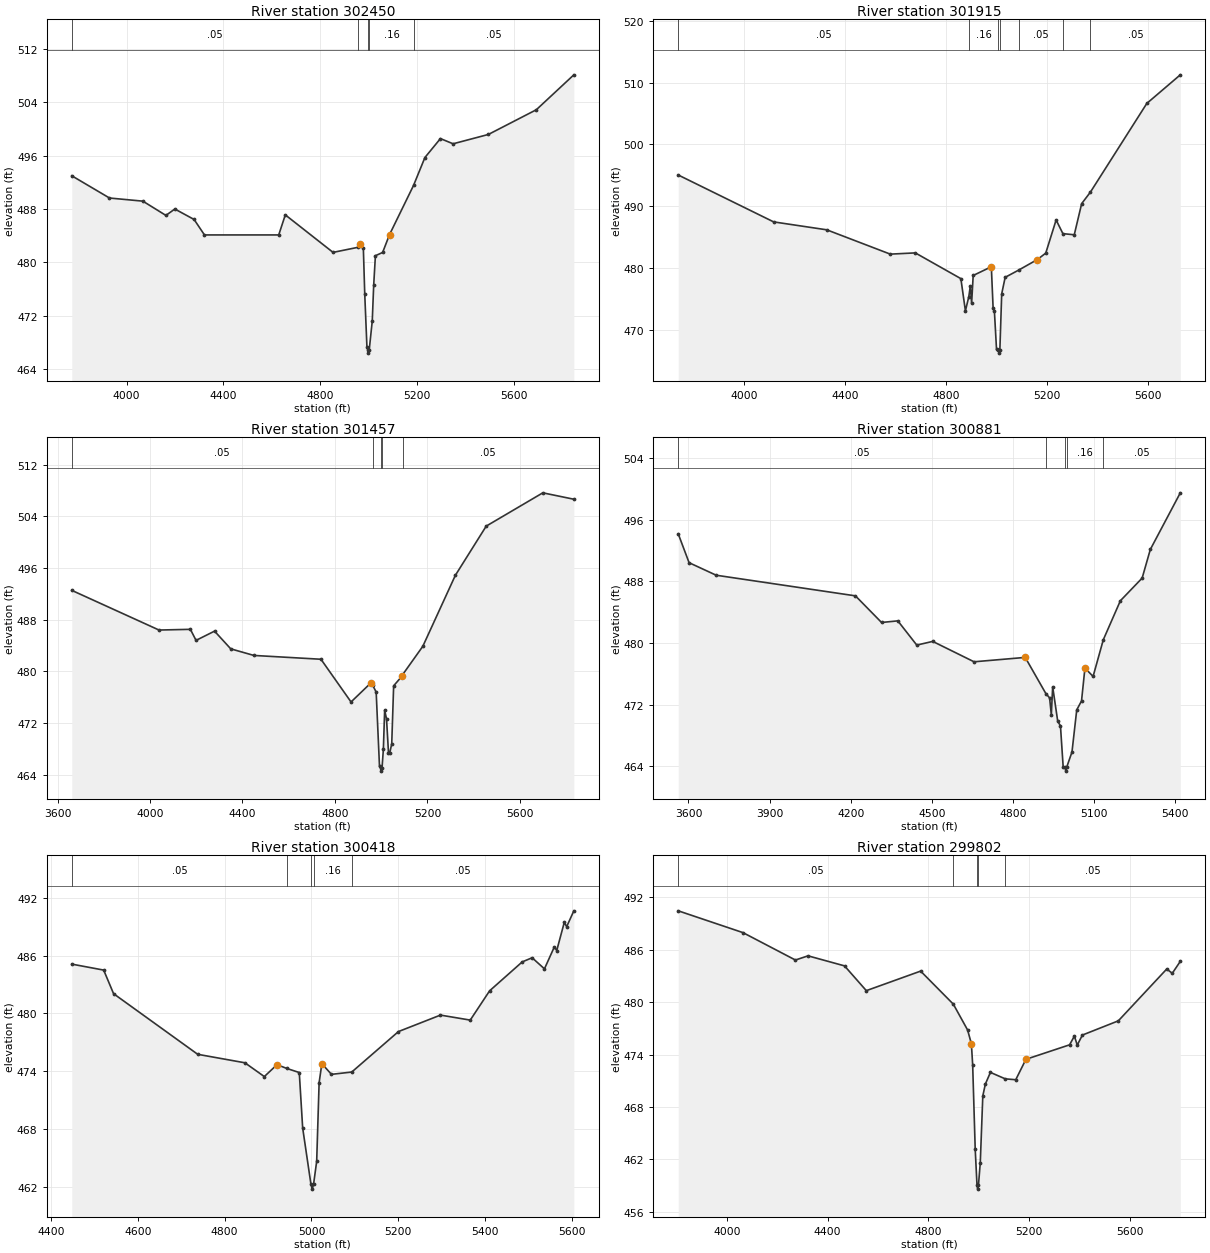
Type RM Length L Ch R = 1 ,302450  ,535,535,535
BEGIN DESCRIPTION:
TEHUACANA CREEK 239.0
END DESCRIPTION:
XS GIS Cut Line= 2
      3484374.42      10618857.6      3486152.23     10617788.13
#Sta/Elev= 30
  3773.5     493  3929.4  489.66  4067.3  489.19  4162.5  487.05  4199.4  488.01
    4279  486.44  4321.8  484.12  4628.7  484.12  4655.9  487.13  4853.2   481.5
  4954.6  482.25  4962.8  482.82  4978.3  482.21  4984.2  475.21  4993.2   467.3
  4996.7  466.88  4999.5  466.38  5002.7  466.88  5015.2   471.2  5021.1  476.56
  5028.2     481    5058  481.49  5086.6  484.17  5185.8  491.55  5232.8  495.74
  5296.9  498.58  5349.3   497.8    5495   499.2  5693.2  502.91  5848.2  508.15
#Mann= 5 ,-1 , 0
  3773.5     .05       0  4954.6     .16       0  4996.7     .07       0
  5002.7     .16       0  5185.8     .05       0
Bank Sta=4962.8,5086.6
XS Rating Curve= 0 ,0
Exp/Cntr=0.3,0.1

Type RM Length L Ch R = 1 ,301915  ,458,458,458
BEGIN DESCRIPTION:
TEHUACANA CREEK 238.0
END DESCRIPTION:
XS GIS Cut Line= 2
      3484381.35     10618968.71      3486318.86     10618517.32
#Sta/Elev= 30
  3738.8  495.07  4116.9  487.49  4327.3  486.21    4579  482.28  4678.2  482.48
  4858.7  478.32  4876.7  473.11  4890.3  475.43  4896.2  477.16  4901.3  474.32
  4907.5  478.83  4979.4  480.24  4986.5  473.53  4991.6  473.02    5000  466.88
  5007.2  466.78    5010  466.28  5013.2  466.78  5020.5  475.86  5034.2  478.53
  5088.6  479.72  5161.9  481.41    5195  482.44  5236.1   487.8    5263  485.59
    5308  485.41  5337.3  490.44  5372.1  492.31  5595.5  506.64  5728.2  511.26
#Mann= 7 ,-1 , 0
  3738.8     .05       0  4890.3     .16       0  5007.2     .07       0
  5013.2     .16       0  5088.6     .05       0    5263     .16       0
  5372.1     .05       0
Bank Sta=4979.4,5161.9
XS Rating Curve= 0 ,0
Exp/Cntr=0.3,0.1

Type RM Length L Ch R = 1 ,301457  ,576,576,576
BEGIN DESCRIPTION:
TEHUACANA CREEK 237.0
END DESCRIPTION:
XS GIS Cut Line= 3
      3484492.45     10619135.37      3485728.59     10619086.76
      3486561.91     10618663.16
#Sta/Elev= 30
  3661.7  492.53  4039.1  486.39  4174.8   486.5  4199.3  484.79  4279.3  486.22
  4349.4  483.48  4449.5  482.46  4739.7  481.87  4869.8  475.26    4956  478.22
  4962.9  477.89  4978.5  476.79  4992.9  465.28  4997.9  465.06  5000.6  464.56
  5003.9  465.06  5009.6  467.92  5015.2  473.98  5023.3  472.64  5031.8  467.42
  5037.4  467.41  5045.8  468.78  5054.1  477.76  5090.6  479.27  5092.4  479.46
  5180.4  483.88  5321.1  494.86  5454.6  502.47  5699.4  507.62  5833.6  506.63
#Mann= 5 ,-1 , 0
  3661.7     .05       0  4962.9     .16       0  4997.9     .07       0
  5003.9     .16       0  5092.4     .05       0
Bank Sta=4956,5090.6
XS Rating Curve= 0 ,0
Exp/Cntr=0.3,0.1

Type RM Length L Ch R = 1 ,300881  ,463,463,463
BEGIN DESCRIPTION:
TEHUACANA CREEK 236.0
END DESCRIPTION:
XS GIS Cut Line= 3
      3484499.57     10619310.19      3485949.61     10619410.19
      3486349.61     10619460.19
#Sta/Elev= 30
  3562.1  494.19  3602.2  490.44  3702.5  488.81  4217.4  486.13  4313.9  482.67
  4374.1  482.88  4444.2  479.73  4503.1  480.21    4656  477.56  4845.2  478.13
  4921.7  473.42  4935.4  472.87  4941.7  470.65  4946.7  474.32  4965.5  469.81
  4975.5  469.24  4985.5  463.92  4992.5  463.85  4995.3  463.35  4998.5  463.85
  5018.1  465.84  5035.7  471.31  5053.4  472.47    5066  476.74  5096.2  475.66
    5134  480.43    5197  485.49  5277.6  488.44  5307.8  492.16  5418.7  499.52
#Mann= 5 ,-1 , 0
  3562.1     .05       0  4921.7     .16       0  4992.5     .07       0
  4998.5     .16       0    5134     .05       0
Bank Sta=4845.2,5066
XS Rating Curve= 0 ,0
Exp/Cntr=0.3,0.1

Type RM Length L Ch R = 1 ,300418  ,616,616,616
BEGIN DESCRIPTION:
TEHUACANA CREEK 235.0
END DESCRIPTION:
XS GIS Cut Line= 2
      3485157.91      10619494.1      3486205.32      10619984.2
#Sta/Elev= 30
  4447.9  485.12  4521.4   484.5  4544.2  482.05    4738  475.76  4846.7  474.88
  4891.4  473.45  4920.7  474.69  4943.3  474.29  4971.9  473.87  4979.7  468.12
  4998.8  462.27  5001.6  461.77  5004.8  462.27    5012  464.66  5017.6  472.81
  5023.9  474.79    5046  473.68  5092.8  473.92  5200.3  478.12  5297.1  479.83
  5365.7  479.31  5410.3  482.35  5485.4  485.35  5508.2  485.78  5536.6  484.63
  5559.4  486.91  5564.9  486.53  5582.2  489.44  5587.8  489.01  5604.3  490.65
#Mann= 5 ,-1 , 0
  4447.9     .05       0  4943.3     .16       0  4998.8     .07       0
  5004.8     .16       0  5092.8     .05       0
Bank Sta=4920.7,5023.9
XS Rating Curve= 0 ,0
Exp/Cntr=0.3,0.1

Type RM Length L Ch R = 1 ,299802  ,608,608,608
BEGIN DESCRIPTION:
TEHUACANA CREEK 233.0
END DESCRIPTION:
XS GIS Cut Line= 3
      3484167.02      10620099.9      3485526.39     10620235.31
      3486140.93     10620115.53
#Sta/Elev= 30
  3807.2  490.47  4064.2  487.97  4272.1  484.83  4322.3  485.31    4467  484.16
  4553.5  481.32    4769  483.56  4898.8  479.77  4955.4  476.81  4970.4  475.23
  4975.5  472.81  4985.6  463.13  4992.6  459.07  4995.4  458.57  4998.6  459.07
  5005.7   461.6  5015.7  469.25  5025.8  470.61  5045.9  471.95  5104.8  471.21
  5146.4  471.11  5186.8  473.45    5360  475.11  5379.1  476.11  5390.5  475.08
  5410.9  476.23  5553.5  477.86  5745.5   483.8  5767.5  483.31  5799.4  484.68
#Mann= 5 ,-1 , 0
  3807.2     .05       0  4898.8     .16       0  4992.6     .07       0
  4998.6     .16       0  5104.8     .05       0
Bank Sta=4970.4,5186.8
XS Rating Curve= 0 ,0
Exp/Cntr=0.3,0.1