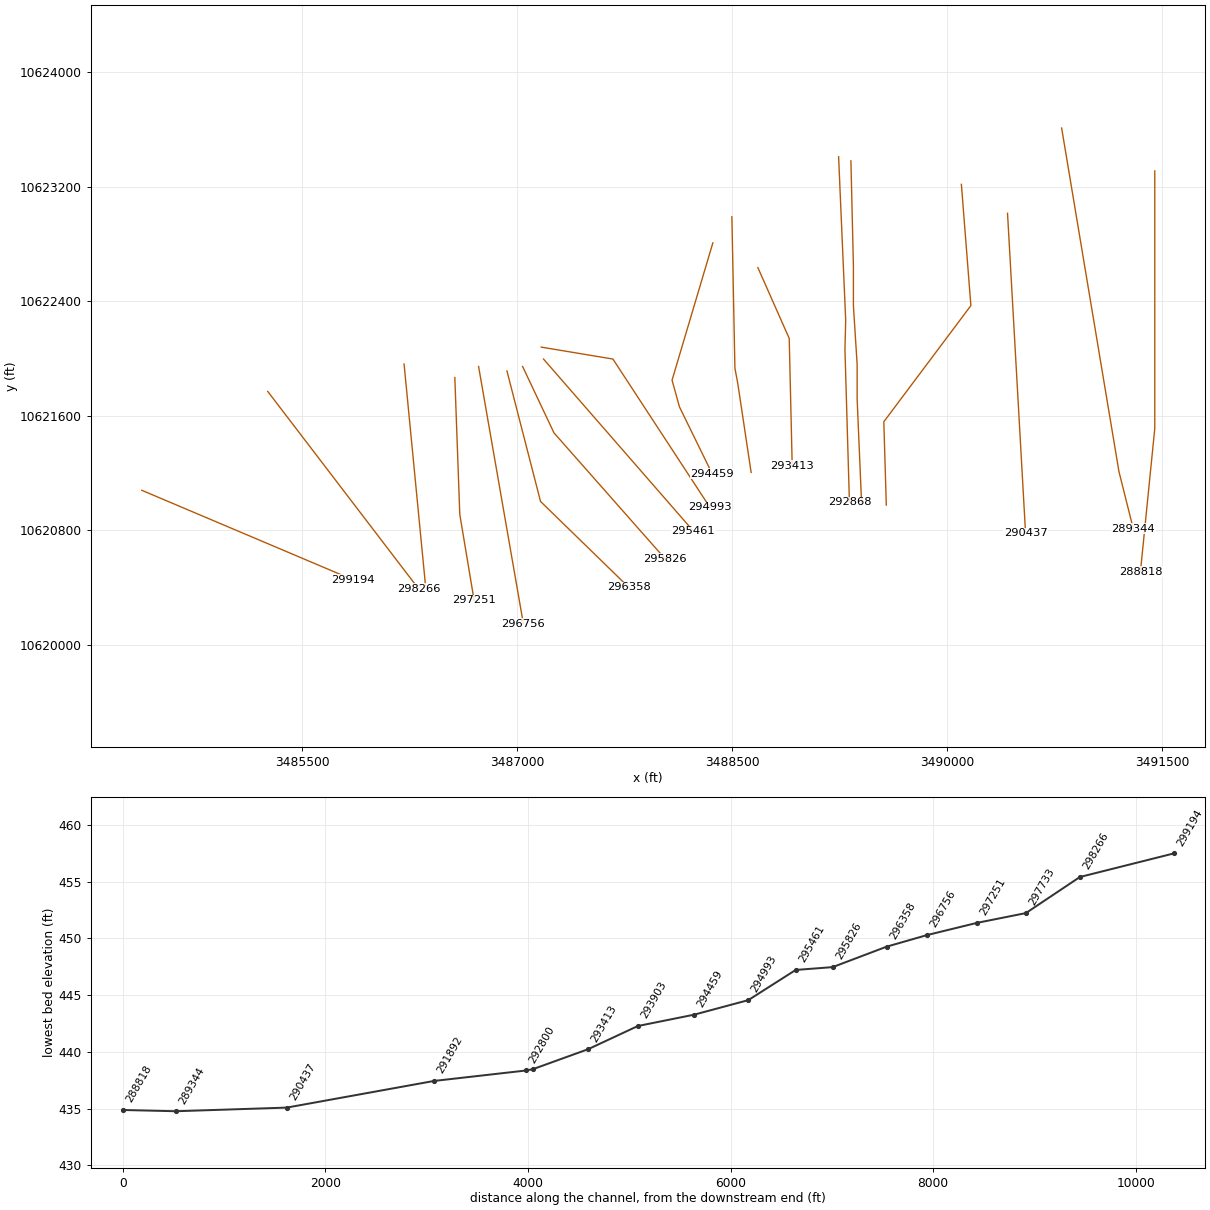
HEC-RAS study TEHUACANA CREEK.prj: TEHUACANA CREEK Base Level Engineering

--- TEHUACANA CREEK.g01 (geometry) --- (continued)

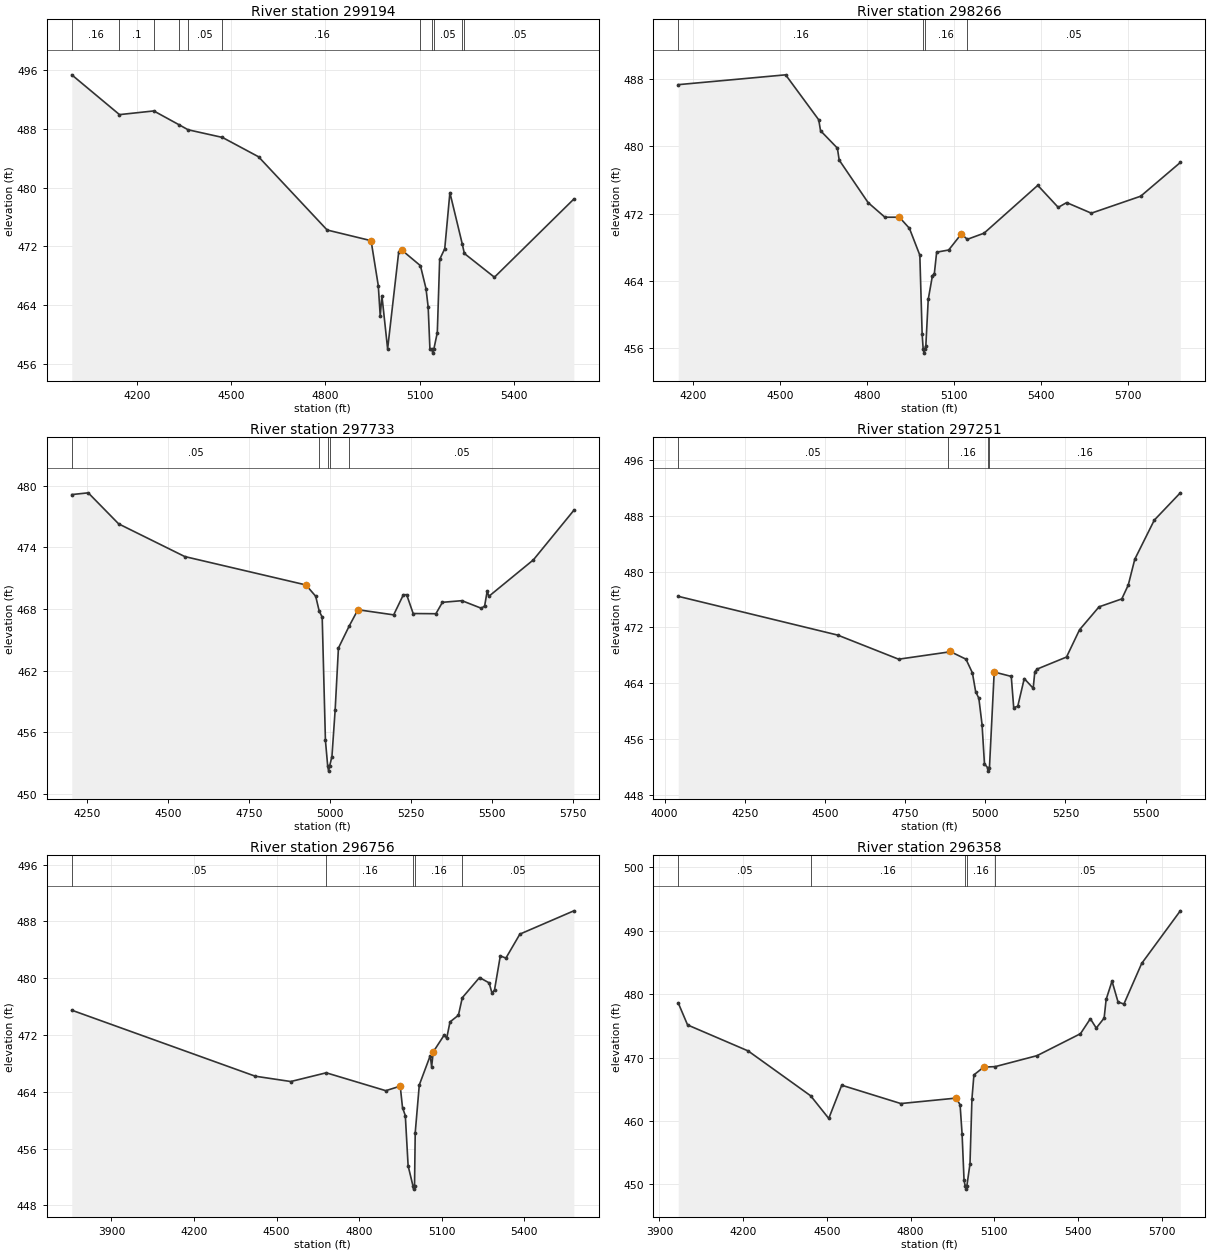
Type RM Length L Ch R = 1 ,299194  ,928,928,928
BEGIN DESCRIPTION:
TEHUACANA CREEK 232.0
END DESCRIPTION:
XS GIS Cut Line= 2
      3484380.54     10621079.07      3485853.22     10620454.61
#Sta/Elev= 30
  3992.1  495.32  4144.1  489.91  4253.4  490.41  4332.6  488.56  4362.7  487.85
    4472  486.81  4587.1  484.18  4805.7  474.22  4945.7  472.77  4968.7  466.64
  4974.8  462.55  4980.2  465.29  4998.4  458.06  5033.8  471.27  5044.7  471.45
  5102.9  469.37  5120.7  466.25  5127.6  463.73  5133.1   458.1  5139.4  457.98
  5142.2  457.48  5145.4  457.98  5156.7  460.27  5164.2  470.22  5180.4  471.68
  5196.8   479.3  5236.1  472.34  5242.9  471.03  5338.7   467.8  5591.7  478.43
#Mann= 11 ,-1 , 0
  3992.1     .16       0  4144.1      .1       0  4253.4     .05       0
  4332.6      .1       0  4362.7     .05       0    4472     .16       0
  5102.9     .05       0  5139.4     .07       0  5145.4     .05       0
  5236.1     .16       0  5242.9     .05       0
Bank Sta=4945.7,5044.7
XS Rating Curve= 0 ,0
Exp/Cntr=0.3,0.1

Type RM Length L Ch R = 1 ,298266  ,533,533,533
BEGIN DESCRIPTION:
TEHUACANA CREEK 230.0
END DESCRIPTION:
XS GIS Cut Line= 2
      3485259.43     10621769.82      3486311.46     10620391.42
#Sta/Elev= 30
  4148.3  487.34  4519.2  488.51  4633.5  483.16  4639.8  481.86  4697.9  479.79
  4704.2  478.37    4804  473.31  4862.1  471.57    4912  471.57  4946.7  470.25
  4982.7  467.05  4990.7  457.67  4994.2   455.9    4997   455.4  5000.2   455.9
  5003.5   456.3  5011.7  461.79  5026.3  464.63  5032.6  464.79  5040.8  467.41
  5082.4  467.67    5126  469.58  5146.7  468.94  5204.5  469.67    5390  475.36
  5460.7  472.74  5489.7  473.31    5575  472.05  5745.5  474.07  5882.3  478.08
#Mann= 4 ,-1 , 0
  4148.3     .16       0  4994.2     .07       0  5000.2     .16       0
  5146.7     .05       0
Bank Sta=4912,5126
XS Rating Curve= 0 ,0
Exp/Cntr=0.3,0.1

Type RM Length L Ch R = 1 ,297733  ,482,482,482
BEGIN DESCRIPTION:
TEHUACANA CREEK 229.0
END DESCRIPTION:
XS GIS Cut Line= 2
      3486210.79     10621960.85       3486360.1     10620415.65
#Sta/Elev= 30
  4201.5  479.12  4252.4  479.29  4346.5  476.27    4551  473.09  4925.5  470.33
  4955.7  469.23  4966.6  467.78  4975.8   467.2  4985.8  455.21  4992.8  452.72
  4995.6  452.22  4998.8  452.72  5005.9  453.63  5015.9  458.18    5026  464.19
  5059.7  466.36  5086.3  467.92  5196.8  467.42  5226.9  469.38    5237  469.38
  5257.1  467.55  5327.4  467.53  5347.5  468.64  5407.8   468.8    5468  468.06
  5478.1  468.29    5486  469.74    5491  469.22  5628.8  472.77  5753.9  477.59
#Mann= 5 ,-1 , 0
  4201.5     .05       0  4966.6     .16       0  4992.8     .07       0
  4998.8     .16       0  5059.7     .05       0
Bank Sta=4925.5,5086.3
XS Rating Curve= 0 ,0
Exp/Cntr=0.3,0.1

Type RM Length L Ch R = 1 ,297251  ,495,495,495
BEGIN DESCRIPTION:
TEHUACANA CREEK 228.0
END DESCRIPTION:
XS GIS Cut Line= 3
      3486564.96     10621867.04      3486599.61     10620910.19
      3486699.62     10620310.14
#Sta/Elev= 30
  4042.5  476.44  4539.7  470.88  4729.8  467.42  4883.9  468.44  4889.9  468.54
  4939.9  467.42  4959.9  465.46    4970  462.78    4980  461.81    4990  458.05
  4997.5  452.41  5007.1  451.86  5009.9  451.36  5013.1  451.86  5027.9  465.58
  5081.1  464.95  5088.7  460.47  5101.4  460.67  5121.6  464.64  5149.5  463.25
  5154.6  465.63  5162.2  466.01  5253.4  467.73    5294  471.64  5354.8  474.93
  5425.8  476.07    5446  478.06  5466.3  481.76  5527.1  487.37  5608.3  491.29
#Mann= 4 ,-1 , 0
  4042.5     .05       0  4883.9     .16       0  5007.1     .07       0
  5013.1     .16       0
Bank Sta=4889.9,5027.9
XS Rating Curve= 0 ,0
Exp/Cntr=0.3,0.1

Type RM Length L Ch R = 1 ,296756  ,398,398,398
BEGIN DESCRIPTION:
TEHUACANA CREEK 227.0
END DESCRIPTION:
XS GIS Cut Line= 2
      3486730.76      10621943.9      3487043.25     10620147.07
#Sta/Elev= 30
    3756  475.49  4422.5  466.19  4551.5  465.44  4680.3  466.67  4896.6  464.15
  4949.1  464.79  4957.5  461.75  4967.6  460.64  4977.8  453.57  4995.1  450.78
  4997.8  450.28  5001.1  450.78  5003.6  458.23  5018.4  464.96  5058.2  469.09
  5063.2  467.51  5069.1  469.62  5109.7  472.04  5117.8  471.52    5130  473.84
  5160.5  474.78  5174.6  477.25  5237.1  480.09  5272.1  479.34  5282.3  477.91
  5291.6  478.34  5312.7  483.14    5333  482.83  5383.8  486.21  5579.8  489.49
#Mann= 5 ,-1 , 0
    3756     .05       0  4680.3     .16       0  4995.1     .07       0
  5001.1     .16       0  5174.6     .05       0
Bank Sta=4949.1,5069.1
XS Rating Curve= 0 ,0
Exp/Cntr=0.3,0.1

Type RM Length L Ch R = 1 ,296358  ,532,532,532
BEGIN DESCRIPTION:
TEHUACANA CREEK 226.0
END DESCRIPTION:
XS GIS Cut Line= 3
      3486928.69     10621912.62      3487163.05      10621001.2
      3487777.61     10620402.27
#Sta/Elev= 30
  3967.2  478.61  4000.7  475.14  4217.5  471.05  4441.8  463.97  4506.6   460.4
  4553.1  465.64  4764.8  462.75  4963.1  463.61  4977.2  462.56  4984.4  457.94
  4991.4  450.66  4995.5  449.76  4998.3  449.26  5001.5  449.76  5012.7  453.25
  5019.7  463.49  5026.8  467.27  5062.1   468.5    5103  468.57    5253   470.3
  5408.6  473.76    5444  476.12  5465.2  474.65  5493.4  476.22  5500.6  479.16
  5521.7  482.05  5543.1  478.78  5564.2  478.43  5627.9  484.83  5766.4  493.13
#Mann= 5 ,-1 , 0
  3967.2     .05       0  4441.8     .16       0  4995.5     .07       0
  5001.5     .16       0    5103     .05       0
Bank Sta=4963.1,5062.1
XS Rating Curve= 0 ,0
Exp/Cntr=0.3,0.1

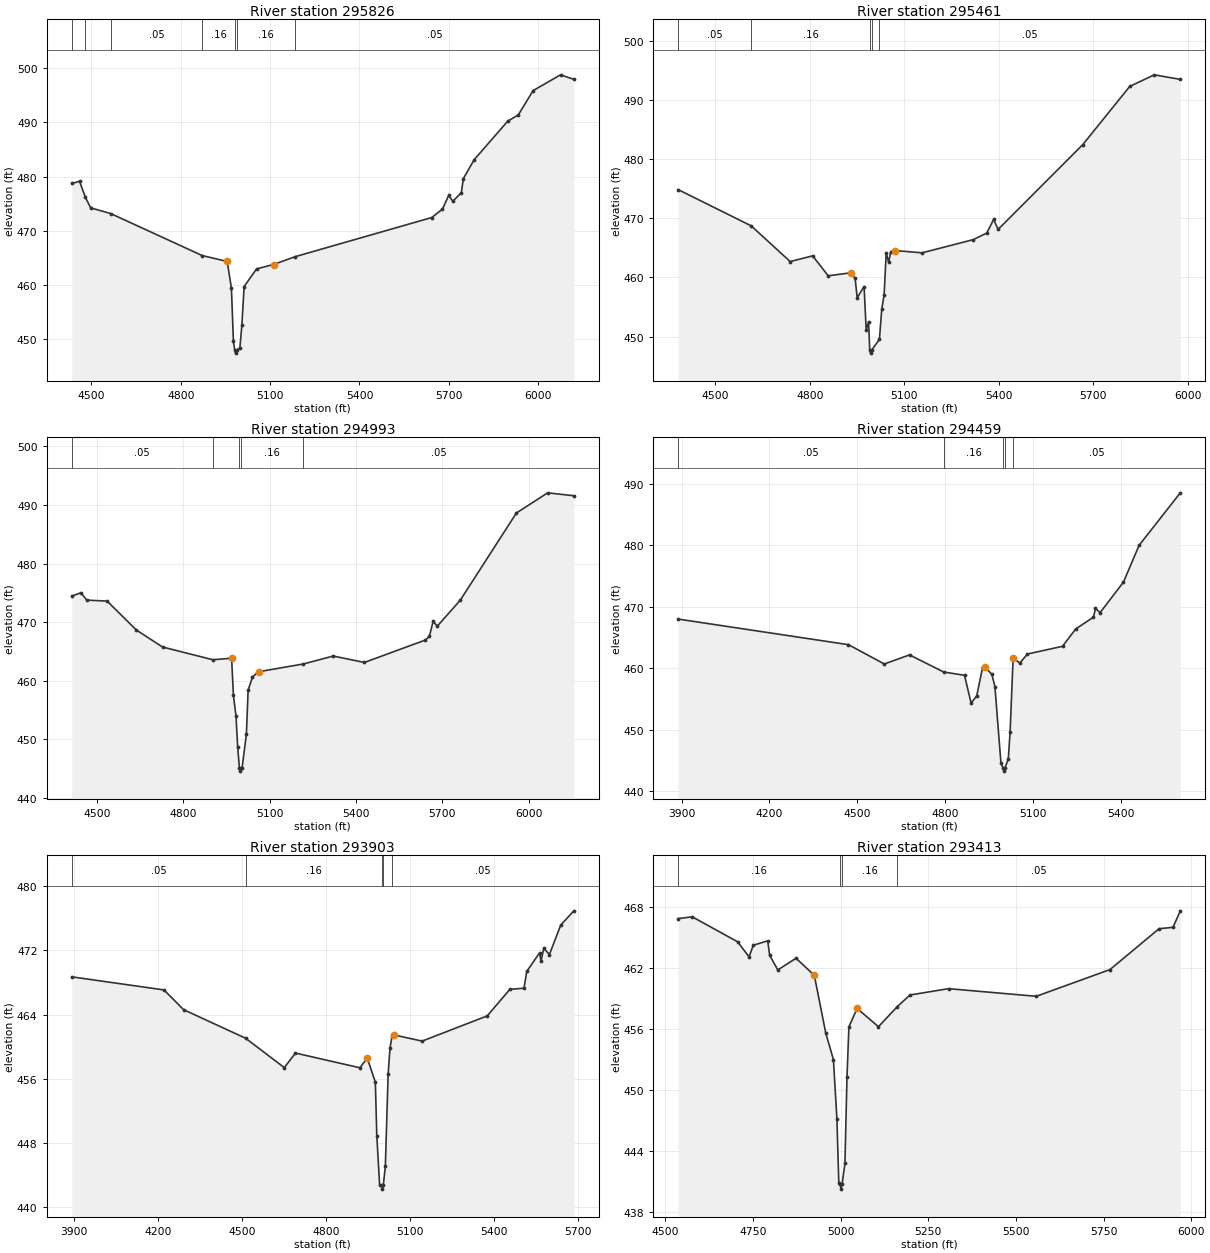
Type RM Length L Ch R = 1 ,295826  ,365,365,365
BEGIN DESCRIPTION:
TEHUACANA CREEK 225.0
END DESCRIPTION:
XS GIS Cut Line= 3
      3487038.05     10621943.91       3487256.8     10621480.36
      3488032.83     10620600.17
#Sta/Elev= 30
  4433.8  478.74    4460  479.13  4479.4   476.2  4497.4  474.24  4564.2   473.2
  4871.8  465.45  4955.7  464.36  4969.9  459.45  4976.6  449.68  4981.2  447.96
  4983.9  447.46  4987.2  447.96  4998.4  448.45  5005.1  452.71  5012.6  459.74
  5054.4  462.99  5111.3   463.8  5184.3  465.25  5642.6  472.46  5678.6  474.01
  5699.5  476.53  5713.7  475.46  5742.1  477.05  5748.8  479.63  5784.8   483.1
  5897.7  490.22  5933.1  491.37  5983.1  495.86  6075.1  498.77  6119.8  497.94
#Mann= 7 ,-1 , 0
  4433.8     .05       0  4479.4     .16       0  4564.2     .05       0
  4871.8     .16       0  4981.2     .07       0  4987.2     .16       0
  5184.3     .05       0
Bank Sta=4955.7,5111.3
XS Rating Curve= 0 ,0
Exp/Cntr=0.3,0.1

Type RM Length L Ch R = 1 ,295461  ,468,468,468
BEGIN DESCRIPTION:
TEHUACANA CREEK 224.0
END DESCRIPTION:
XS GIS Cut Line= 2
      3487183.86     10621996.02      3488229.74     10620794.04
#Sta/Elev= 30
  4382.5  474.82  4614.2   468.7  4737.8  462.67    4809  463.64  4858.4  460.27
  4929.6  460.77  4943.8  459.84  4950.4  456.57  4972.3  458.46  4978.9  451.14
  4986.6   452.5  4990.2  447.71  4992.9  447.21  4996.2  447.71    5021  449.55
  5028.3  454.62  5035.9  457.07  5042.5  464.14  5050.2  462.56  5056.8  464.34
    5071  464.53  5156.5  464.15  5318.8  466.38  5361.6  467.48  5383.4  469.79
  5397.7  468.11  5666.4  482.43  5815.4  492.26  5893.3  494.21  5975.8  493.44
#Mann= 5 ,-1 , 0
  4382.5     .05       0  4614.2     .16       0  4990.2     .07       0
  4996.2     .16       0    5021     .05       0
Bank Sta=4929.6,5071
XS Rating Curve= 0 ,0
Exp/Cntr=0.3,0.1

Type RM Length L Ch R = 1 ,294993  ,534,534,534
BEGIN DESCRIPTION:
TEHUACANA CREEK 223.0
END DESCRIPTION:
XS GIS Cut Line= 3
      3487168.27     10622079.32      3487668.26     10621995.99
      3488344.96     10620960.13
#Sta/Elev= 30
  4412.5  474.44  4444.3  475.01  4464.6  473.75  4535.5  473.58  4636.9  468.64
  4728.1  465.74  4902.4  463.57  4967.8  463.83  4974.1  457.48    4983  453.99
  4988.9  448.66    4995  445.05  4997.7  444.55    5001  445.05  5004.1  445.06
  5019.2  450.87  5025.1  458.35  5040.3  460.63  5061.3  461.52  5217.1  462.85
  5320.7   464.2  5429.3  463.11  5640.6  466.93  5654.9  467.56  5667.6   470.1
  5682.7  469.32  5762.5  473.76  5957.2  488.63  6065.8  492.07  6156.7  491.57
#Mann= 5 ,-1 , 0
  4412.5     .05       0  4902.4     .16       0    4995     .07       0
    5001     .16       0  5217.1     .05       0
Bank Sta=4967.8,5061.3
XS Rating Curve= 0 ,0
Exp/Cntr=0.3,0.1

Type RM Length L Ch R = 1 ,294459  ,556,556,556
BEGIN DESCRIPTION:
TEHUACANA CREEK 222.0
END DESCRIPTION:
XS GIS Cut Line= 4
      3488365.62     10622807.72      3488080.86     10621848.49
      3488132.95     10621660.99      3488361.38     10621193.74
#Sta/Elev= 30
  3888.7  467.99  4470.3  463.83  4592.6  460.69  4678.9  462.17  4795.5  459.39
  4866.7  458.85  4889.3  454.34  4908.4  455.49  4929.1  460.26  4937.5  460.15
  4960.2     459  4970.6  457.02  4991.3  444.53  4998.7  443.77  5001.5  443.27
  5004.7  443.77  5016.3  445.24  5022.5  449.64  5032.8  461.65  5033.4  461.63
  5055.8  460.84  5081.7  462.31  5201.6  463.57  5246.6  466.38  5307.4  468.31
  5314.2  469.76  5329.7  469.02  5409.8  474.01  5463.3  479.99    5604  488.52
#Mann= 5 ,-1 , 0
  3888.7     .05       0  4795.5     .16       0  4998.7     .07       0
  5004.7     .16       0  5033.4     .05       0
Bank Sta=4937.5,5032.8
XS Rating Curve= 0 ,0
Exp/Cntr=0.3,0.1

Type RM Length L Ch R = 1 ,293903  ,490,490,490
BEGIN DESCRIPTION:
TEHUACANA CREEK 221.0
END DESCRIPTION:
XS GIS Cut Line= 4
      3488498.42     10622989.97      3488519.55     10621932.26
       3488539.2     10621827.65      3488632.76     10621203.89
#Sta/Elev= 30
  3891.7   468.7  4221.5  467.07  4291.6  464.61  4513.1  461.06  4651.6   457.4
  4691.6  459.21  4921.7  457.38  4948.2  458.59  4977.1  455.58  4982.3  448.92
  4992.4  442.79  4999.6  442.77  5002.4  442.27  5005.6  442.77  5012.8  445.09
  5022.9  456.65  5029.6  459.87  5037.3  461.37  5043.3  461.47  5144.5   460.7
  5377.1  463.84    5458  467.14  5508.5  467.29  5518.6  469.39  5564.3  471.69
  5569.3  470.65  5579.3  472.25  5599.5  471.48    5640  475.15  5686.8  476.92
#Mann= 5 ,-1 , 0
  3891.7     .05       0  4513.1     .16       0  4999.6     .07       0
  5005.6     .16       0  5037.3     .05       0
Bank Sta=4948.2,5043.3
XS Rating Curve= 0 ,0
Exp/Cntr=0.3,0.1

Type RM Length L Ch R = 1 ,293413  ,545,545,545
BEGIN DESCRIPTION:
TEHUACANA CREEK 220.0
END DESCRIPTION:
XS GIS Cut Line= 3
      3488679.82     10622634.96      3488898.57     10622140.15
      3488919.41      10621249.5
#Sta/Elev= 30
    4537  466.82    4577  466.99  4706.2  464.54    4739  463.06  4751.1   464.2
  4792.2  464.63  4797.7  463.21    4821  461.77    4873  462.92  4925.1  461.24
  4957.7  455.57  4979.6  452.96  4989.5  447.14    4995  440.81  4998.4  440.73
  5001.2  440.23  5004.4  440.73  5012.4  442.76  5018.3  451.28  5023.8  456.18
  5047.1  457.99    5108  456.19  5161.9  458.17    5198  459.31    5308  459.93
  5558.1  459.18  5768.5  461.81  5908.2  465.82  5948.2  465.96  5968.9  467.58
#Mann= 4 ,-1 , 0
    4537     .16       0  4998.4     .07       0  5004.4     .16       0
  5161.9     .05       0
Bank Sta=4925.1,5047.1
XS Rating Curve= 0 ,0
Exp/Cntr=0.3,0.1

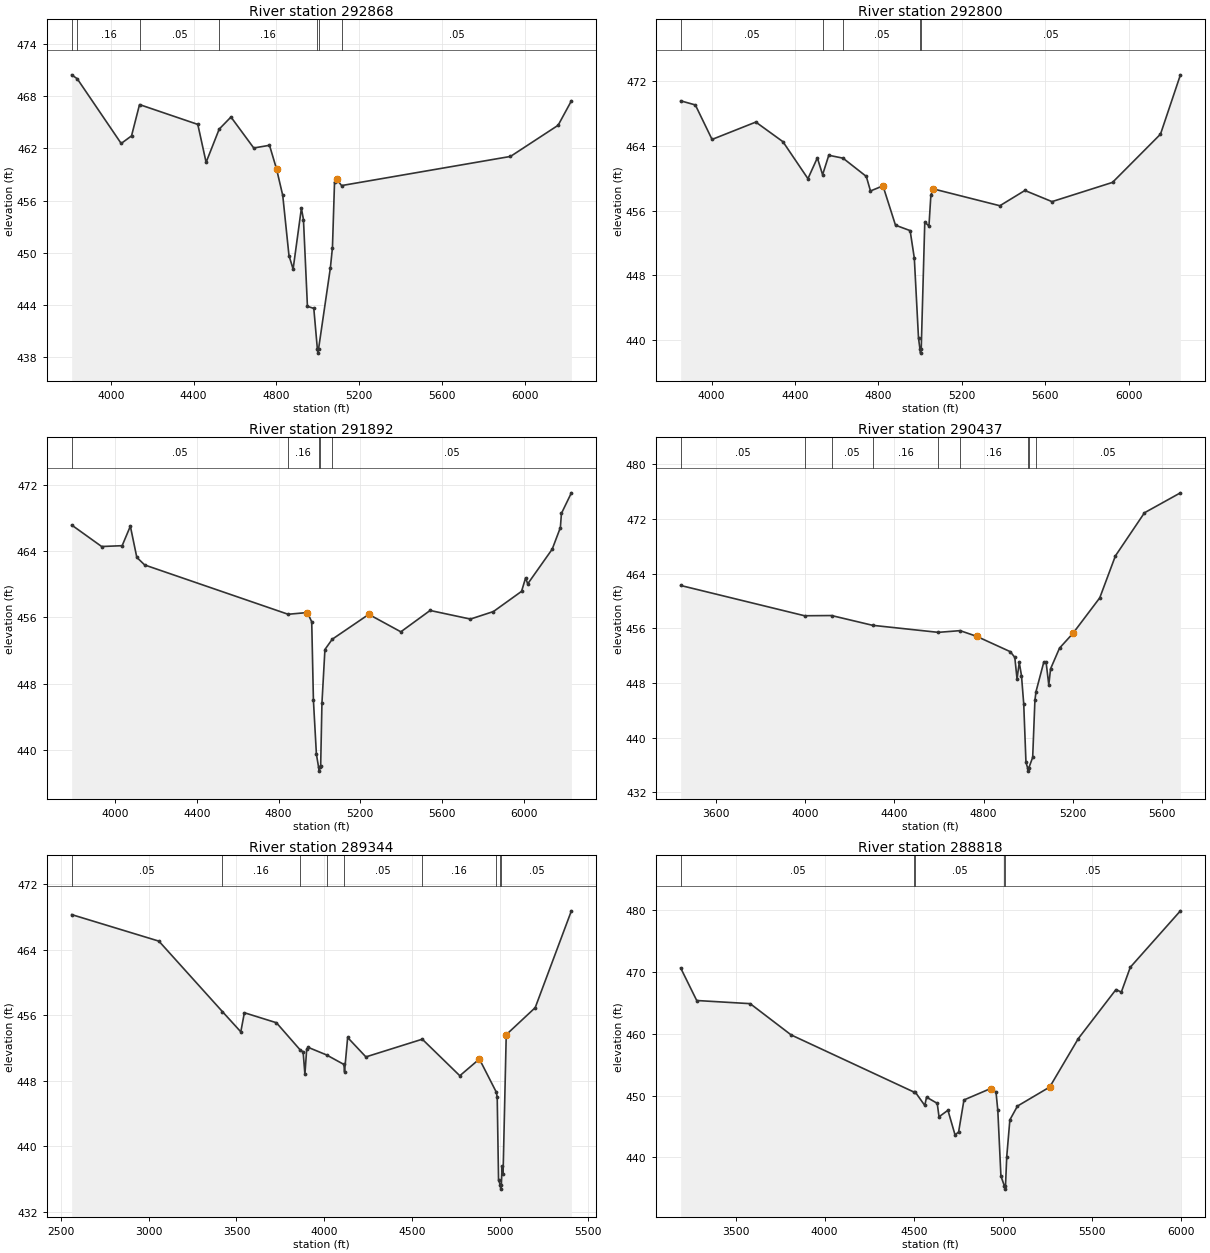
Type RM Length L Ch R = 1 ,292868  ,68,68,68
BEGIN DESCRIPTION:
TEHUACANA CREEK 219.0
END DESCRIPTION:
XS GIS Cut Line= 4
      3489243.21     10623409.26      3489292.67     10622266.89
      3489287.46     10622063.76      3489318.71     10620996.05
#Sta/Elev= 30
  3810.5  470.46  3837.4  470.01  4049.8  462.57  4099.8  463.44  4138.5  467.04
  4420.1  464.76  4460.2   460.4  4523.4  464.22  4580.3  465.61  4690.4  462.05
  4766.5  462.36  4800.5  459.64  4830.5   456.6  4860.6  449.69  4880.6  448.13
  4920.6  455.12  4930.6  453.83  4949.8  443.85  4980.6  443.61  4997.7  438.97
  5000.4  438.47  5003.7  438.97  5060.7  448.28  5070.7   450.6  5080.7  458.09
  5090.7  458.47  5114.8  457.73    5931  461.08  6161.1  464.66  6225.3  467.47
#Mann= 7 ,-1 , 0
  3810.5     .05       0  3837.4     .16       0  4138.5     .05       0
  4523.4     .16       0  4997.7     .07       0  5003.7     .16       0
  5114.8     .05       0
Bank Sta=4800.5,5090.7
XS Rating Curve= 0 ,0
Exp/Cntr=0.3,0.1

Type RM Length L Ch R = 1 ,292800  ,908,908,908
BEGIN DESCRIPTION:
TEHUACANA CREEK 218.0
END DESCRIPTION:
XS GIS Cut Line= 6
      3489329.15     10623380.62      3489346.49     10622645.36
      3489346.49     10622369.32      3489372.53     10621957.86
      3489372.53     10621718.28      3489403.75     10620984.57
#Sta/Elev= 30
  3851.3  469.59  3921.7  469.08  4001.8  464.81  4211.8  466.96  4341.9  464.53
  4461.9  459.95    4507  462.53  4532.2  460.44  4561.9  462.85  4630.2  462.49
  4741.9  460.23  4761.9  458.43  4821.9  459.06    4882  454.19  4952.2  453.52
  4972.3  450.11  4992.4   440.2  4999.4  438.85  5002.1  438.35  5005.4  438.85
  5022.5  454.57  5042.5  454.09  5051.8  457.93  5062.6  458.69  5382.8   456.6
  5502.8  458.49  5632.9  457.11  5923.2  459.49  6153.4  465.46  6249.1  472.81
#Mann= 5 ,-1 , 0
  3851.3     .05       0  4532.2     .08       0  4630.2     .05       0
  4999.4     .04       0  5005.4     .05       0
Bank Sta=4821.9,5062.6
XS Rating Curve= 0 ,0
Exp/Cntr=0.3,0.1

Type RM Length L Ch R = 1 ,291892  ,1455,1455,1455
BEGIN DESCRIPTION:
TEHUACANA CREEK 217.0
END DESCRIPTION:
XS GIS Cut Line= 4
      3490099.98     10623216.54      3490166.34     10622369.53
      3489558.71      10621557.9      3489576.07     10620976.35
#Sta/Elev= 30
  3787.5  467.18  3934.3  464.58  4034.6  464.68  4074.7  467.04  4106.3  463.27
  4144.9  462.35  4846.7  456.39  4941.3   456.6  4962.2  455.47  4970.5  445.99
  4985.1  439.48  4995.6  437.93  4998.3  437.43  5001.6  437.93  5005.9  438.01
  5012.2  445.65  5026.8  452.13  5062.4  453.37  5241.4  456.38  5398.3  454.27
  5541.5  456.85  5738.7  455.81  5851.3  456.72  5988.9  459.16  6008.9   460.8
  6018.9  460.06  6138.9  464.26  6178.9  466.87    6184  468.58  6232.8  471.07
#Mann= 5 ,-1 , 0
  3787.5     .05       0  4846.7     .16       0  4995.6     .07       0
  5001.6     .16       0  5062.4     .05       0
Bank Sta=4941.3,5241.4
XS Rating Curve= 0 ,0
Exp/Cntr=0.3,0.1

Type RM Length L Ch R = 1 ,290437  ,1093,1093,1093
BEGIN DESCRIPTION:
TEHUACANA CREEK 216.0
END DESCRIPTION:
XS GIS Cut Line= 2
      3490422.06     10623014.59      3490547.93     10620779.33
#Sta/Elev= 30
  3443.2  462.25  3998.1  457.82  4119.1  457.85    4303  456.42    4597  455.39
    4695  455.64  4769.7   454.8  4919.9  452.56    4940  451.73    4950  448.58
    4960  450.98    4970  449.04    4980  444.92    4990  436.38  4997.1  435.58
  4999.8  435.08  5003.1  435.58  5020.1  437.09  5030.1  445.43  5035.1  446.73
  5070.2  451.07  5080.2  451.02  5092.3   447.7  5100.2  450.05  5140.3  453.08
  5200.4  455.24  5320.6  460.44  5390.7  466.58  5520.9  472.89    5682  475.81
#Mann= 9 ,-1 , 0
  3443.2     .05       0  3998.1     .16       0  4119.1     .05       0
    4303     .16       0    4597     .05       0    4695     .16       0
  4997.1     .07       0  5003.1     .16       0  5035.1     .05       0
Bank Sta=4769.7,5200.4
XS Rating Curve= 0 ,0
Exp/Cntr=0.3,0.1

Type RM Length L Ch R = 1 ,289344  ,526,526,526
BEGIN DESCRIPTION:
TEHUACANA CREEK 215.0
END DESCRIPTION:
XS GIS Cut Line= 3
       3490799.6     10623610.21      3491199.61     10621210.19
       3491299.6     10620810.23
#Sta/Elev= 30
  2561.5  468.27  3058.3  465.03  3420.2  456.42  3524.6  453.96  3544.9  456.29
  3727.4  455.07  3861.5  451.78  3879.5  451.51  3889.6  448.76  3899.7  451.84
  3909.9  452.05  4012.8  451.14  4111.6  449.98  4115.2  449.08  4132.9  453.27
  4236.8   450.9  4557.9  453.06  4771.6   448.6  4883.1  450.64  4979.3   446.6
  4984.5  445.98  4992.1  435.89  5001.9  435.26  5004.7  434.76  5007.9  435.26
  5012.7  437.55  5017.8  436.56  5035.9  453.61  5200.8  456.91  5406.9  468.73
#Mann= 9 ,-1 , 0
  2561.5     .05       0  3420.2     .16       0  3861.5     .05       0
  4012.8     .16       0  4111.6     .05       0  4557.9     .16       0
  4979.3     .05       0  5001.9    .035       0  5007.9     .05       0
Bank Sta=4883.1,5035.9
XS Rating Curve= 0 ,0
Exp/Cntr=0.3,0.1

Type RM Length L Ch R = 1 ,288818  ,535,535,535
BEGIN DESCRIPTION:
TEHUACANA CREEK 214.0
END DESCRIPTION:
XS GIS Cut Line= 3
      3491449.61     10623310.16      3491449.61     10621510.19
      3491349.61     10620510.15
#Sta/Elev= 30
  3191.8  470.65  3281.8  465.39  3581.8  464.88  3811.8  459.82  4503.8  450.54
    4508  450.59  4561.8  448.41  4571.8  449.75  4631.8  448.75  4641.8  446.57
  4691.8  447.63  4731.8  443.64  4751.8  444.12  4781.8   449.3  4931.8  451.15
  4961.8  450.55  4971.8   447.6  4989.3  436.98  5008.9  435.37  5011.6  434.87
  5014.9  435.37  5021.9  440.12  5039.5  446.08  5082.2  448.31  5263.1  451.39
  5423.9  459.24    5635  467.16  5665.1  466.75  5715.4  470.77  5996.8   479.9
#Mann= 5 ,-1 , 0
  3191.8     .05       0  4503.8     .16       0    4508     .05       0
  5008.9    .035       0  5014.9     .05       0
Bank Sta=4931.8,5263.1
XS Rating Curve= 0 ,0
Exp/Cntr=0.3,0.1