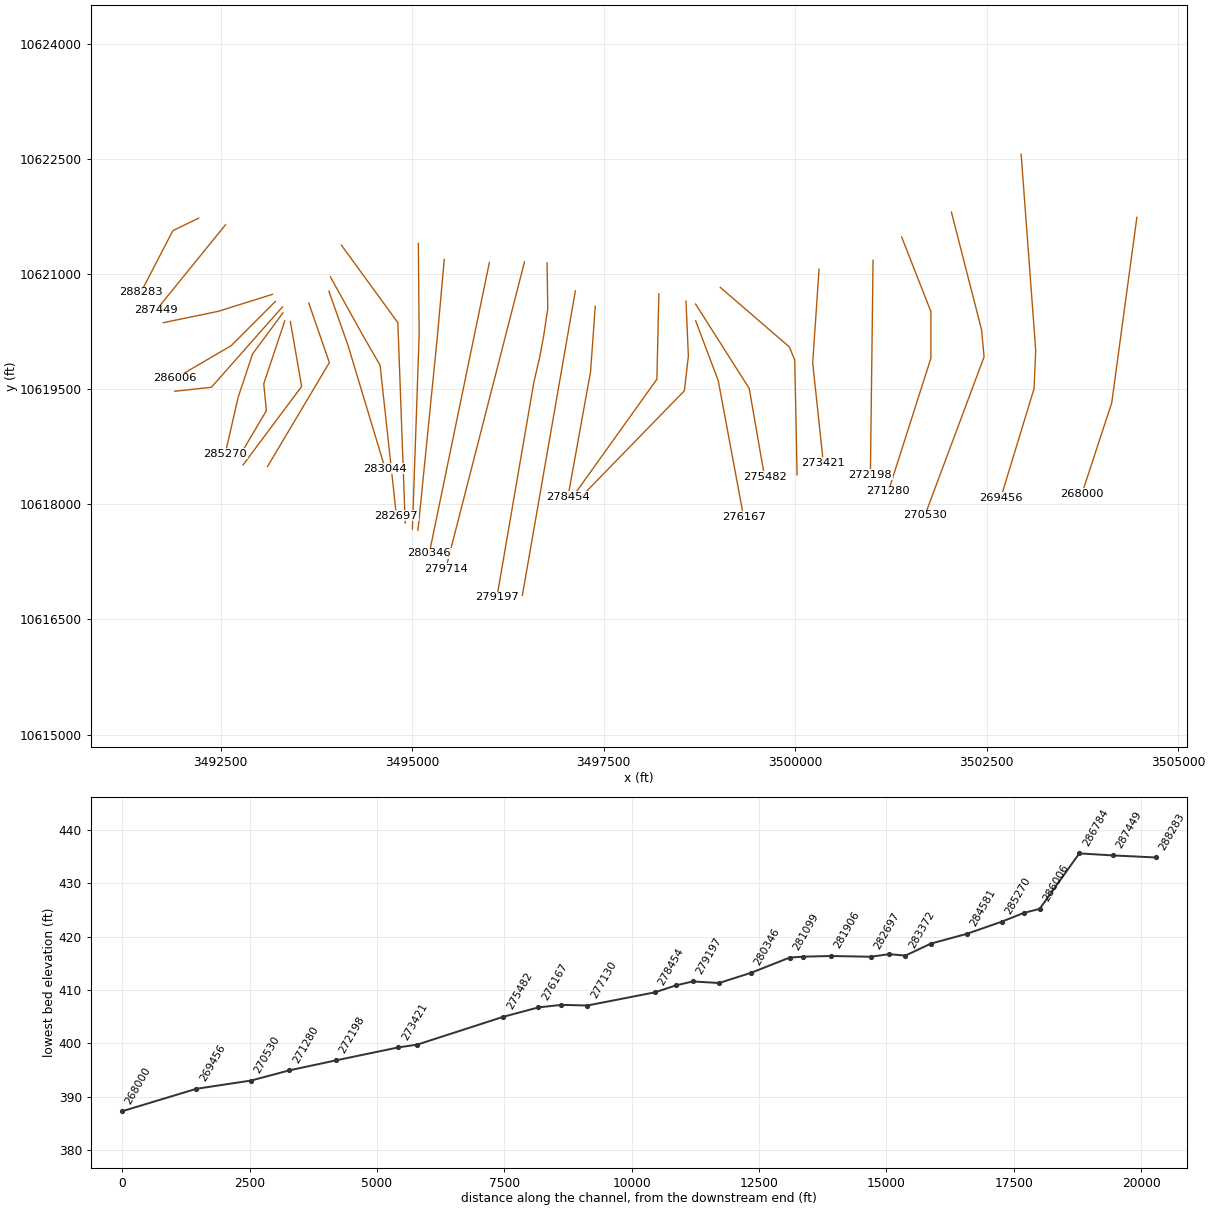
HEC-RAS study TEHUACANA CREEK.prj: TEHUACANA CREEK Base Level Engineering

--- TEHUACANA CREEK.g01 (geometry) --- (continued)

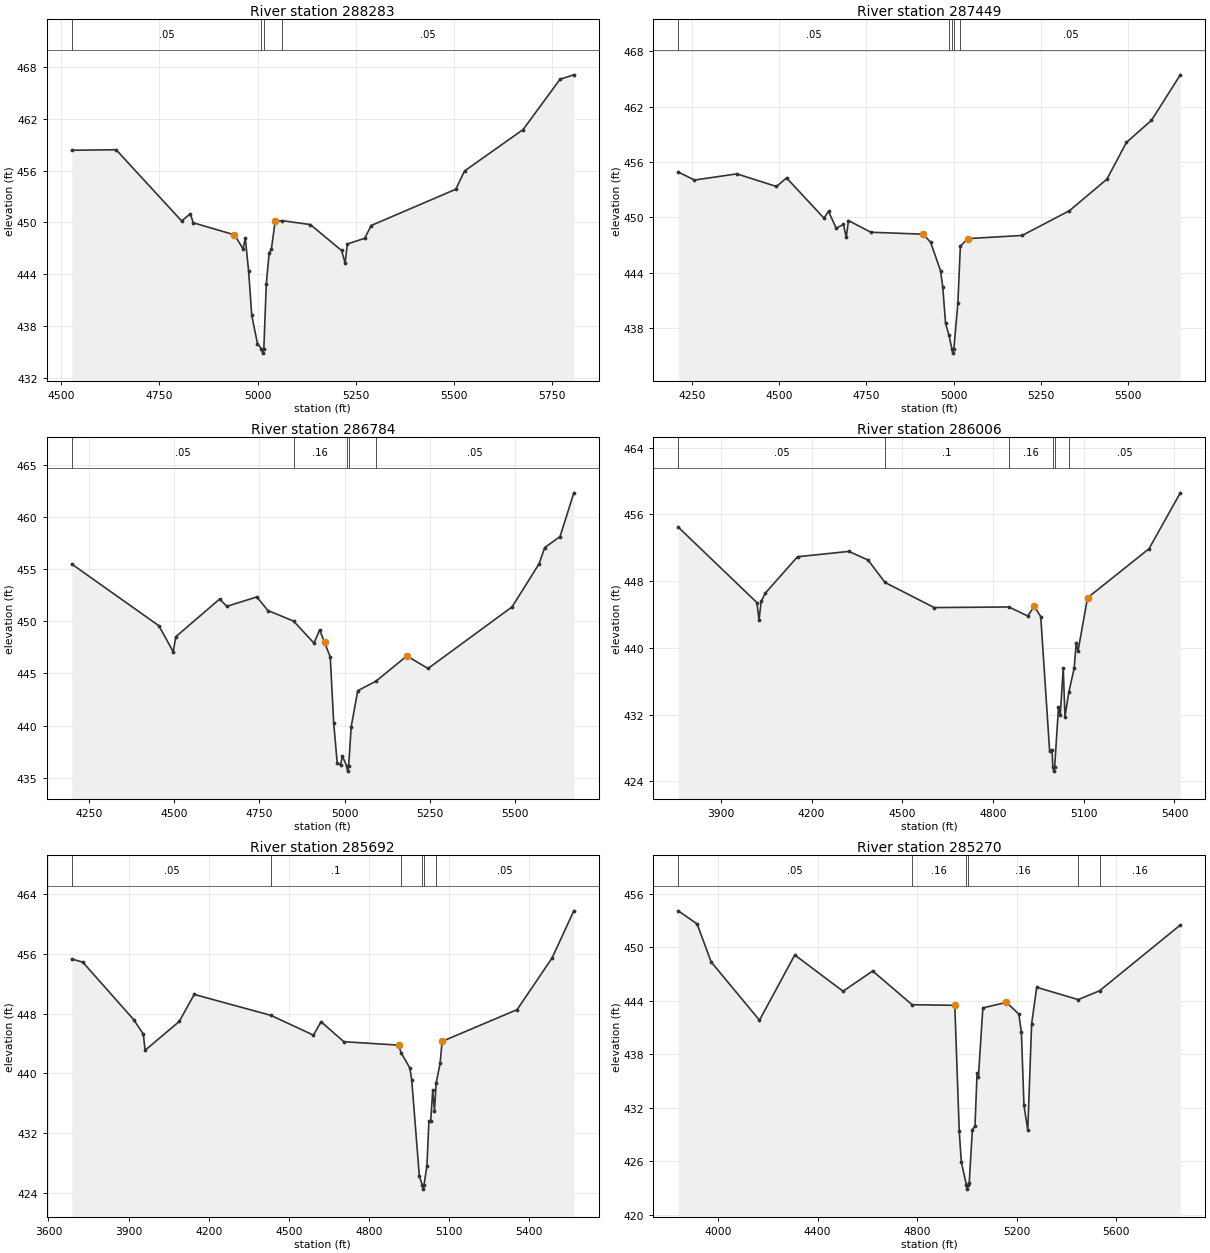
Type RM Length L Ch R = 1 ,288283  ,834,834,834
BEGIN DESCRIPTION:
TEHUACANA CREEK 213.0
END DESCRIPTION:
XS GIS Cut Line= 3
       3492211.2     10621730.76      3491874.42     10621567.58
      3491457.75     10620765.48
#Sta/Elev= 30
  4527.1  458.36    4640  458.42  4806.7  450.18  4828.9  451.01  4836.2  449.97
  4941.1  448.57  4963.2  446.96  4968.8  448.18  4977.3  444.38  4985.3  439.24
  4999.8  435.98    5010  435.38  5012.8  434.88    5016  435.38  5022.3  442.88
  5029.5  446.44  5035.2  446.91  5044.9  450.13  5062.7  450.21  5134.5  449.76
  5213.9  446.76  5222.9  445.31  5228.6  447.51  5272.8  448.17  5289.3  449.65
  5504.8  453.85  5526.9  455.96  5675.9  460.75  5770.2  466.58  5805.2  467.09
#Mann= 4 ,-1 , 0
  4527.1     .05       0    5010     .04       0    5016     .05       0
  5062.7     .05       0
Bank Sta=4941.1,5044.9
XS Rating Curve= 0 ,0
Exp/Cntr=0.3,0.1

Type RM Length L Ch R = 1 ,287449  ,665,665,665
BEGIN DESCRIPTION:
Mapping XS 4401b077
END DESCRIPTION:
XS GIS Cut Line= 2
      3492561.59     10621644.12      3491654.56     10620528.78
#Sta/Elev= 30
  4211.1   454.9  4257.6  454.03    4379   454.7  4492.4  453.33  4521.2  454.26
  4628.2  449.91  4641.5  450.63  4663.4   448.8  4684.2  449.22  4692.1   447.8
  4698.6  449.64  4762.5  448.37  4912.2  448.16  4933.5   447.3  4962.2   444.2
  4968.6   442.4  4976.6  438.48  4986.1  437.23  4994.4  435.76  4997.1  435.26
  5000.4  435.76  5011.8  440.68  5018.9  446.87  5040.5  447.68  5195.8  448.02
  5331.4  450.71  5438.4  454.12  5494.4  458.11  5566.2  460.51  5648.7  465.44
#Mann= 5 ,-1 , 0
  4211.1     .05       0  4986.1     .16       0  4994.4     .07       0
  5000.4     .16       0  5018.9     .05       0
Bank Sta=4912.2,5040.5
XS Rating Curve= 0 ,0
Exp/Cntr=0.3,0.1

Type RM Length L Ch R = 1 ,286784  ,778,778,778
BEGIN DESCRIPTION:
Mapping XS 74282d72
END DESCRIPTION:
XS GIS Cut Line= 3
      3493173.57     10620737.01      3492466.11     10620515.66
      3491749.93     10620368.08
#Sta/Elev= 30
  4199.7  455.47  4455.3  449.56  4497.2  447.07  4504.8  448.51  4633.4  452.12
  4654.4  451.42  4742.5  452.32    4775  451.02  4850.1  450.01  4910.1   447.9
  4926.8  449.17    4941  447.97  4957.8  446.57    4968  440.21  4978.2  436.41
  4988.1  436.24  4993.2  437.08  5005.9  436.14  5008.6  435.64  5011.9  436.14
  5019.1  439.87  5038.4  443.34  5092.6  444.27  5182.4  446.67  5244.7  445.47
  5491.1  451.37  5570.4   455.5  5586.6  457.04  5631.7   458.1  5672.2  462.29
#Mann= 5 ,-1 , 0
  4199.7     .05       0  4850.1     .16       0  5005.9     .07       0
  5011.9     .16       0  5092.6     .05       0
Bank Sta=4941,5182.4
XS Rating Curve= 0 ,0
Exp/Cntr=0.3,0.1

Type RM Length L Ch R = 1 ,286006  ,314,314,314
BEGIN DESCRIPTION:
Mapping XS e07ac4fa
END DESCRIPTION:
XS GIS Cut Line= 3
      3493212.65       10620645.      3492635.38     10620067.74
      3491906.25     10619642.41
#Sta/Elev= 30
  3758.9  454.48    4019  445.44  4026.1  443.36  4033.2  445.59  4047.3  446.59
  4153.4  450.93  4323.1  451.57  4386.7  450.54  4442.7  447.85  4605.5  444.84
  4852.9  444.91  4914.8  443.83  4936.3  444.99  4957.8  443.76  4987.2  427.65
    4995  427.83  4997.8  425.74  5000.6  425.24  5003.8  425.74  5016.5   432.9
  5022.3  431.95  5032.2  437.56    5038  431.78  5050.6  434.68  5068.2  437.54
  5075.2   440.6    5081   439.6  5112.5  446.01  5315.9  451.89  5419.4  458.59
#Mann= 6 ,-1 , 0
  3758.9     .05       0  4442.7      .1       0  4852.9     .16       0
  4997.8     .07       0  5003.8     .16       0  5050.6     .05       0
Bank Sta=4936.3,5112.5
XS Rating Curve= 0 ,0
Exp/Cntr=0.3,0.1

Type RM Length L Ch R = 1 ,285692  ,422,422,422
BEGIN DESCRIPTION:
Mapping XS a0f187d4
END DESCRIPTION:
XS GIS Cut Line= 3
      3493304.66     10620572.95      3492377.57     10619526.07
      3491898.37     10619473.99
#Sta/Elev= 30
  3687.4  455.32  3728.6   454.9  3919.3  447.19  3955.3  445.25    3962  443.08
  4089.9  446.94    4146  450.57  4433.2  447.76  4592.6  445.11    4621  446.91
  4706.3  444.23  4911.3  443.77  4920.6  442.78  4953.9  440.68  4960.6  439.11
  4989.1  426.22  5000.3  424.96    5003  424.46  5006.3  424.96  5017.5  427.56
    5025  433.55  5031.7  433.63  5039.3   437.7  5045.9     435  5052.2   438.7
  5066.9  441.32  5074.4  444.27  5355.3  448.53  5486.1  455.45  5567.8  461.78
#Mann= 6 ,-1 , 0
  3687.4     .05       0  4433.2      .1       0  4920.6     .16       0
  5000.3     .07       0  5006.3     .16       0  5052.2     .05       0
Bank Sta=4911.3,5074.4
XS Rating Curve= 0 ,0
Exp/Cntr=0.3,0.1

Type RM Length L Ch R = 1 ,285270  ,689,689,689
BEGIN DESCRIPTION:
TEHUACANA CREEK 212.0
END DESCRIPTION:
XS GIS Cut Line= 4
      3493310.75     10620494.85       3492914.9      10619960.1
       3492727.4      10619397.6      3492557.25     10618657.97
#Sta/Elev= 30
  3840.4  454.08  3916.3  452.61  3972.6  448.35  4166.8  441.81  4308.6  449.13
  4502.6  445.06  4621.6  447.33    4780  443.55  4951.5  443.48  4969.4  429.37
  4977.8  425.88  4998.1  423.36  5000.8  422.86  5004.1  423.36  5009.5  423.56
  5022.1  429.52  5032.7  429.96  5041.1  435.91  5046.4  435.46  5064.3  443.19
  5159.2  443.81  5208.9  442.49  5219.1  440.45  5229.4  432.26  5244.8  429.48
  5260.2   441.4  5280.7   445.5  5447.3  444.12  5533.1  445.11  5857.6  452.49
#Mann= 6 ,-1 , 0
  3840.4     .05       0    4780     .16       0  4998.1     .07       0
  5004.1     .16       0  5447.3     .05       0  5533.1     .16       0
Bank Sta=4951.5,5159.2
XS Rating Curve= 0 ,0
Exp/Cntr=0.3,0.1

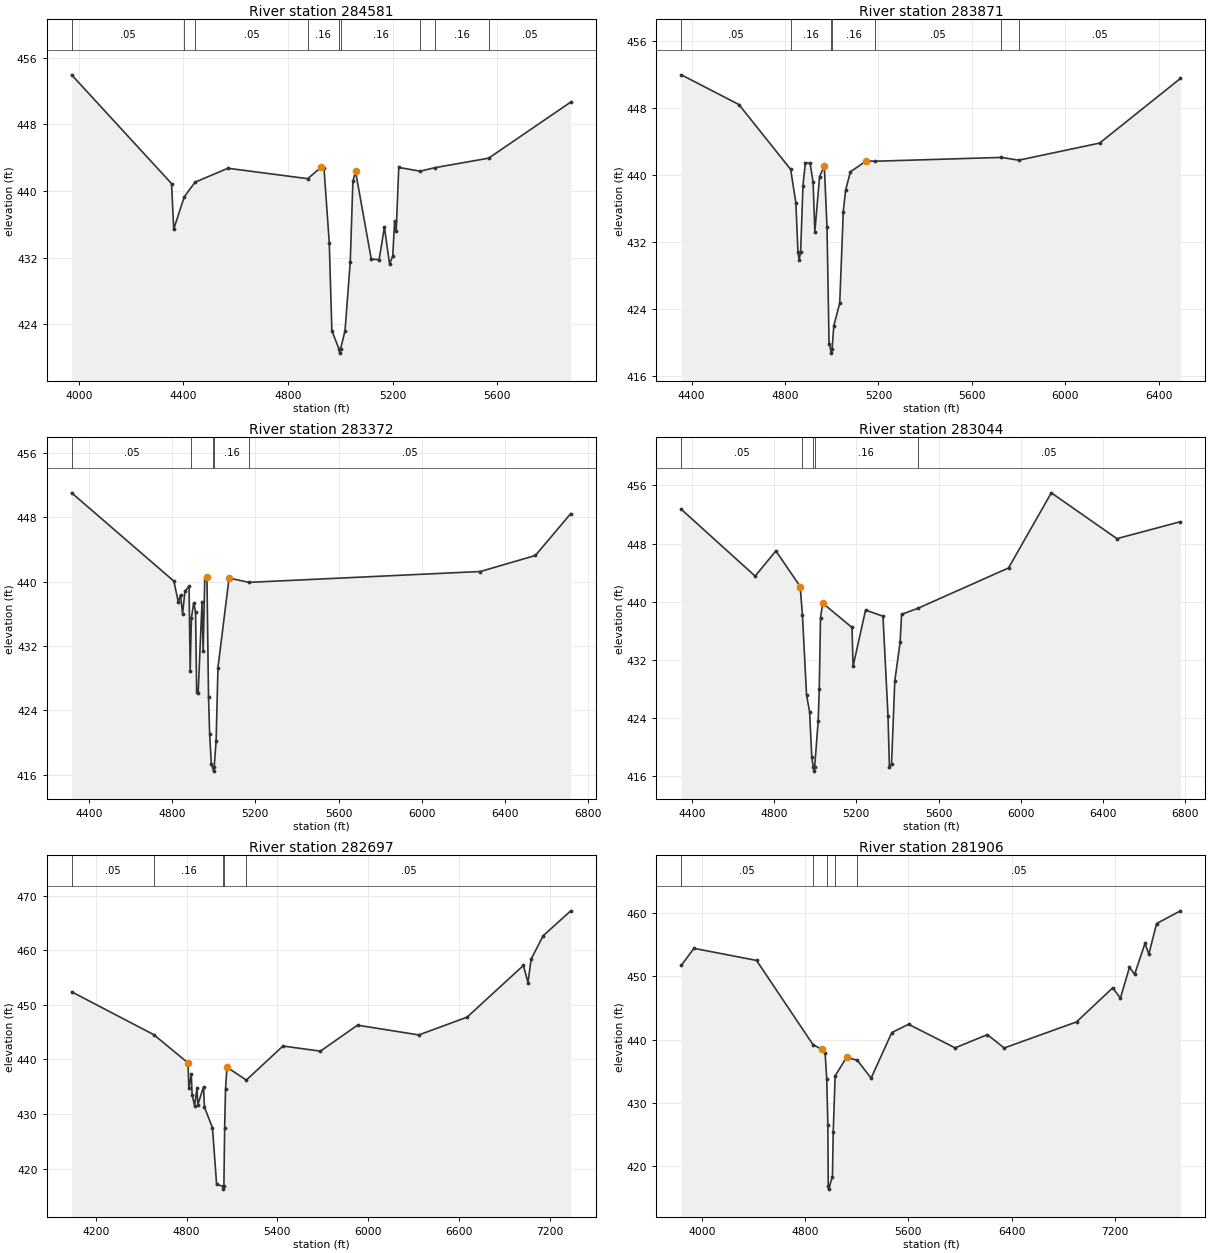
Type RM Length L Ch R = 1 ,284581  ,710,710,710
BEGIN DESCRIPTION:
TEHUACANA CREEK 211.0
END DESCRIPTION:
XS GIS Cut Line= 4
      3493335.05      10620390.7      3493060.73     10619571.21
      3493095.45     10619220.52      3492741.86     10618624.27
#Sta/Elev= 30
    3972  453.95  4354.4   440.9  4362.7  435.44  4403.1  439.32  4444.4  441.07
  4570.1  442.74  4875.2  441.49  4927.7  442.89  4937.7  442.73  4957.8  433.82
  4967.8  423.25    4995  421.06  4997.7  420.56    5001  421.06  5018.1  423.24
  5038.2  431.55  5048.2  441.16  5058.3  442.38  5118.6  431.83  5148.7  431.78
  5168.8  435.69  5188.6  431.23  5200.6   432.2  5208.1  436.44  5213.9  435.24
  5223.7  442.84  5305.8  442.39  5361.9  442.81  5567.6  443.95  5881.8  450.68
#Mann= 9 ,-1 , 0
    3972     .05       0  4403.1     .16       0  4444.4     .05       0
  4875.2     .16       0    4995     .07       0    5001     .16       0
  5305.8     .05       0  5361.9     .16       0  5567.6     .05       0
Bank Sta=4927.7,5058.3
XS Rating Curve= 0 ,0
Exp/Cntr=0.3,0.1

Type RM Length L Ch R = 1 ,283871  ,499,499,499
BEGIN DESCRIPTION:
TEHUACANA CREEK 210.0
END DESCRIPTION:
XS GIS Cut Line= 3
      3493408.13     10620383.16       3493555.7     10619536.84
      3492790.54     10618513.69
#Sta/Elev= 30
  4356.1  451.94  4602.7  448.39    4824  440.65  4846.4  436.67  4855.5  430.73
  4860.6  429.87  4866.7  430.74  4876.8  438.71    4887  441.46  4907.3  441.38
  4920.1  439.16  4927.6  433.19  4947.9  439.79  4968.2  441.06  4979.7  433.76
  4988.5  419.78  4995.6  419.21  4998.4  418.71  5001.6  419.21  5008.8  421.98
  5034.2  424.68  5049.4  435.62  5059.5   438.2  5079.8  440.36  5148.2  441.67
  5183.8  441.62  5725.5  442.08  5800.7  441.75  6146.7  443.79  6492.8  451.51
#Mann= 7 ,-1 , 0
  4356.1     .05       0    4824     .16       0  4995.6     .07       0
  5001.6     .16       0  5183.8     .05       0  5725.5     .16       0
  5800.7     .05       0
Bank Sta=4968.2,5148.2
XS Rating Curve= 0 ,0
Exp/Cntr=0.3,0.1

Type RM Length L Ch R = 1 ,283372  ,328,328,328
BEGIN DESCRIPTION:
TEHUACANA CREEK 209.0
END DESCRIPTION:
XS GIS Cut Line= 3
      3493648.59     10620624.48      3493917.68      10619847.6
       3493110.9     10618494.29
#Sta/Elev= 30
  4317.3  451.03  4808.6  440.06  4829.8  437.46  4840.4  438.36  4850.4  435.99
  4861.6  438.83  4881.5  439.41  4886.8  428.95  4892.8   435.5  4903.9  437.38
  4912.7  436.24    4918  426.25  4925.1  426.12  4943.8  437.51  4949.1  431.35
  4956.8  440.27  4967.4  440.52    4975  425.62  4980.3  421.13  4988.6   417.3
  4996.1  416.97  4998.9  416.47  5002.1  416.97  5011.4  420.24  5020.3  429.33
  5073.7  440.45  5168.7  439.91  6280.7  441.26  6545.1  443.25    6715  448.45
#Mann= 5 ,-1 , 0
  4317.3     .05       0  4892.8     .16       0  4996.1     .07       0
  5002.1     .16       0  5168.7     .05       0
Bank Sta=4967.4,5073.7
XS Rating Curve= 0 ,0
Exp/Cntr=0.3,0.1

Type RM Length L Ch R = 1 ,283044  ,347,347,347
BEGIN DESCRIPTION:
TEHUACANA CREEK 208.0
END DESCRIPTION:
XS GIS Cut Line= 3
      3493911.42     10620778.87      3494161.43      10620070.5
      3494646.51     10618464.14
#Sta/Elev= 30
  4348.2  452.72  4707.4  443.54  4808.3  447.01  4926.7  442.11  4937.7  438.13
  4957.6   427.2  4972.5  424.89  4983.1  418.63  4990.9  417.23  4993.6  416.73
  4996.9  417.23  5014.2  423.61  5019.5  427.99  5025.5  437.81  5036.1  439.83
  5178.8  436.48    5184  431.14  5244.8  438.87  5329.5  438.03  5354.1  424.31
  5360.9  417.24  5371.3  417.75  5387.1  429.14  5413.1  434.45    5420  438.28
    5499  439.11  5940.6  444.66  6148.9  454.99  6468.2  448.69  6777.4  451.02
#Mann= 5 ,-1 , 0
  4348.2     .05       0  4937.7     .16       0  4990.9     .07       0
  4996.9     .16       0    5499     .05       0
Bank Sta=4926.7,5036.1
XS Rating Curve= 0 ,0
Exp/Cntr=0.3,0.1

Type RM Length L Ch R = 1 ,282697  ,791,791,791
BEGIN DESCRIPTION:
TEHUACANA CREEK 207.0
END DESCRIPTION:
XS GIS Cut Line= 4
      3493930.51     10620966.36      3494362.62     10620188.57
      3494579.83     10619812.72      3494793.37     10617849.16
#Sta/Elev= 30
  4040.2  452.39  4583.2  444.54  4809.3  439.37    4815  434.72    4831   437.3
  4836.7  433.53  4852.7  431.53  4868.7   434.7  4874.5   431.7  4912.2     435
  4917.9  431.28  4971.2  427.48  4998.5  417.14  5040.6  416.75  5043.3  416.25
  5046.6  416.75  5051.6  427.44  5057.4  434.52  5066.7  438.59  5194.8  436.22
    5437  442.46  5684.6  441.52  5929.9  446.28  6335.2  444.49  6654.2  447.75
  7026.3  457.22  7056.5  454.09  7077.4  458.38  7157.1  462.66  7339.2  467.22
#Mann= 5 ,-1 , 0
  4040.2     .05       0  4583.2     .16       0  5040.6     .07       0
  5046.6     .16       0  5194.8     .05       0
Bank Sta=4809.3,5066.7
XS Rating Curve= 0 ,0
Exp/Cntr=0.3,0.1

Type RM Length L Ch R = 1 ,281906  ,552,552,552
BEGIN DESCRIPTION:
TEHUACANA CREEK 206.0
END DESCRIPTION:
XS GIS Cut Line= 3
      3494073.92     10621379.73      3494811.77     10620368.43
      3494907.95     10617755.46
#Sta/Elev= 30
  3841.1  451.76  3938.7  454.45  4423.8  452.54  4861.6  439.21  4932.1  438.48
  4954.6  437.95  4967.6  433.85  4976.1  426.59  4979.3  416.89    4982  416.39
  5011.6  418.35  5017.8  425.42  5032.5  434.29  5121.2  437.22  5204.3  436.75
  5311.4  433.94  5471.5  441.14  5601.5  442.45  5961.8  438.72    6212  440.81
  6342.1   438.7  6902.4  442.82  7182.6   448.2  7242.7  446.59  7312.7  451.45
  7352.7  450.35  7432.8  455.22  7462.8  453.53  7522.8  458.37  7707.7  460.38
#Mann= 5 ,-1 , 0
  3841.1     .05       0  4861.6     .16       0  4967.6     .07       0
  5032.5     .16       0  5204.3     .05       0
Bank Sta=4932.1,5121.2
XS Rating Curve= 0 ,0
Exp/Cntr=0.3,0.1

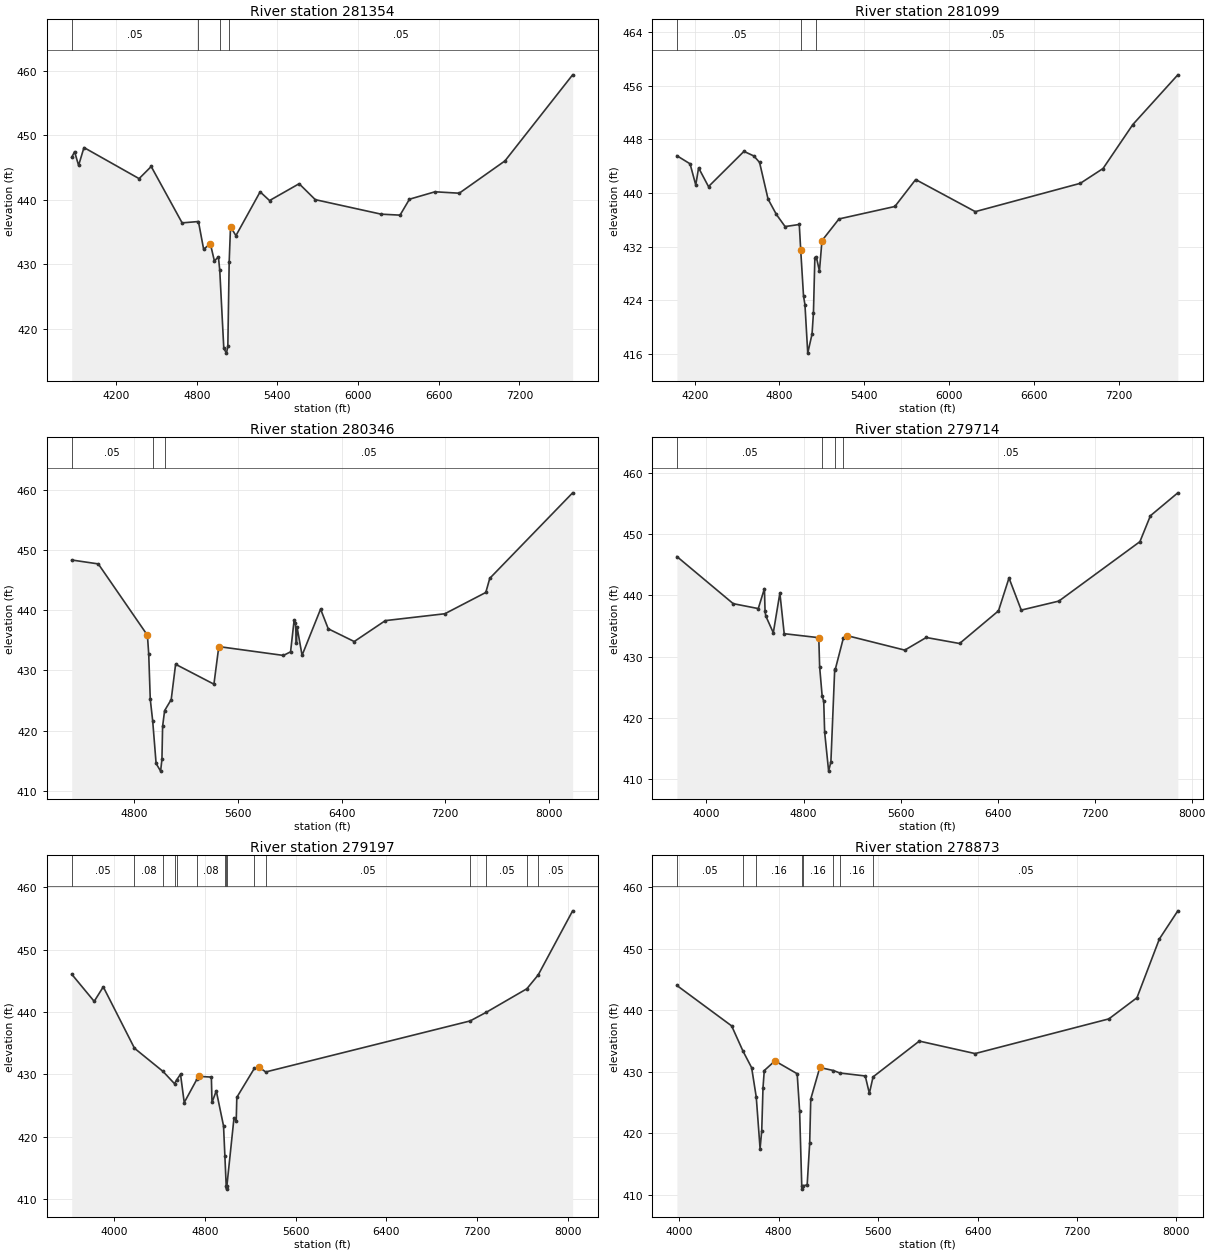
Type RM Length L Ch R = 1 ,281354  ,255,255,255
BEGIN DESCRIPTION:
TEHUACANA CREEK 205.0
END DESCRIPTION:
XS GIS Cut Line= 3
      3495079.29     10621401.37      3495090.25     10620213.76
       3495001.7     10617677.26
#Sta/Elev= 30
    3870   446.6  3891.2  447.49  3921.2  445.36  3961.2  448.13  4371.2  443.31
  4461.2  445.19  4691.2  436.45  4812.6  436.66  4851.2  432.37  4901.2  433.21
  4931.2  430.55  4961.2  431.18  4971.2  429.07  5001.2  416.98    5021  416.26
  5031.2  417.32  5041.2  430.37  5051.2  435.85  5091.3  434.47  5271.4  441.26
  5341.4  439.91  5561.5  442.52  5681.6  440.05  6171.9   437.8    6312  437.65
    6382  440.12  6572.2  441.27  6752.3  441.05  7092.5  446.06  7595.7   459.4
#Mann= 4 ,-1 , 0
    3870     .05       0  4812.6     .16       0  4971.2     .07       0
  5041.2     .05       0
Bank Sta=4901.2,5051.2
XS Rating Curve= 0 ,0
Exp/Cntr=0.3,0.1

Type RM Length L Ch R = 1 ,281099  ,753,753,753
BEGIN DESCRIPTION:
TEHUACANA CREEK 204.0
END DESCRIPTION:
XS GIS Cut Line= 3
      3495417.83     10621193.03      3495327.71     10620187.91
      3495074.79     10617663.39
#Sta/Elev= 30
  4073.7  445.57  4166.9  444.36  4207.1   441.2  4227.2  443.76  4297.4  440.96
  4548.4  446.22  4618.7  445.53  4658.9  444.57  4719.1  439.09    4778   436.8
  4839.6  434.99    4940   435.3    4950  431.56  4970.1  424.61  4980.2  423.33
    5000  416.09  5030.4  418.94  5040.4  422.13  5050.4  430.37  5060.5  430.46
  5082.8  428.35  5100.7  432.89  5221.3  436.13  5616.9  437.99    5764  442.01
  6186.1  437.22  6929.8  441.45  7090.6  443.66  7301.6  450.23    7620  457.65
#Mann= 3 ,-1 , 0
  4073.7     .05       0    4950     .07       0  5060.5     .05       0
Bank Sta=4950,5100.7
XS Rating Curve= 0 ,0
Exp/Cntr=0.3,0.1

Type RM Length L Ch R = 1 ,280346  ,632,632,632
BEGIN DESCRIPTION:
TEHUACANA CREEK 203.0
END DESCRIPTION:
XS GIS Cut Line= 2
      3496006.91     10621152.96      3495222.59     10617363.27
#Sta/Elev= 30
  4315.4  448.36  4520.7  447.71  4900.3  435.85  4910.5  432.65  4922.3  425.21
  4941.2  421.56  4967.4  414.52  5002.2  413.25  5012.5  415.23  5017.6   420.7
  5033.1  423.31  5084.1  425.15    5118  431.02  5414.1  427.71  5451.8  433.96
    5951  432.49  6006.3  433.09  6033.8  438.37    6044   437.9  6051.4  434.57
  6056.5   437.2  6095.1  432.51  6238.1  440.19  6297.3  436.92  6498.1   434.8
  6738.5  438.28    7198  439.42  7514.6  442.96  7545.2  445.31  8185.4  459.53
#Mann= 3 ,-1 , 0
  4315.4     .05       0  4941.2     .07       0  5033.1     .05       0
Bank Sta=4900.3,5451.8
XS Rating Curve= 0 ,0
Exp/Cntr=0.3,0.1

Type RM Length L Ch R = 1 ,279714  ,517,517,517
BEGIN DESCRIPTION:
TEHUACANA CREEK 202.0
END DESCRIPTION:
XS GIS Cut Line= 2
      3496465.26     10621159.98      3495437.46     10617159.91
#Sta/Elev= 30
  3756.1  446.34  4220.5  438.65    4427  437.85  4477.7  441.11  4482.9  437.38
  4488.9  436.64  4550.9   433.9  4605.1  440.38  4640.7  433.75  4925.9   433.1
  4932.9  428.34  4953.6  423.58  4966.6  422.69  4974.2  417.68  5007.1  411.32
  5025.8  412.85  5056.8  427.78  5062.7  427.99  5128.7  433.05    5160  433.43
    5635  431.07  5811.9  433.13  6086.7  432.15  6407.5  437.48  6494.1  442.84
  6595.2   437.6    6905  439.07  7573.5  448.77  7660.1     453  7886.1  456.74
#Mann= 4 ,-1 , 0
  3756.1     .05       0  4953.6     .07       0  5062.7     .16       0
  5128.7     .05       0
Bank Sta=4925.9,5160
XS Rating Curve= 0 ,0
Exp/Cntr=0.3,0.1

Type RM Length L Ch R = 1 ,279197  ,324,324,324
BEGIN DESCRIPTION:
TEHUACANA CREEK 201.0
END DESCRIPTION:
XS GIS Cut Line= 6
      3496760.39     10621148.61      3496769.07     10620549.67
      3496716.99     10620202.45       3496664.9     10619924.67
      3496586.78     10619586.13       3496104.4     10616786.45
#Sta/Elev= 30
  3622.9  446.08  3821.3  441.72  3901.4  444.05    4177   434.2  4428.5  430.49
  4530.1  428.52  4549.3  429.12  4583.1  430.04    4616  425.49    4729  429.27
  4745.9  429.69  4855.4  429.58  4861.1  425.51  4898.8  427.37  4962.9  421.75
  4974.6     417  4986.4  412.11  4989.2  411.61  4992.4  412.11  5055.2  423.03
    5075   422.6  5080.1  426.33  5235.1  430.98  5274.9  431.19  5335.3   430.4
  7138.9  438.58    7282  439.97  7639.9  443.74  7740.1  445.96    8044  456.24
#Mann= 15 ,-1 , 0
  3622.9     .05       0    4177     .08       0  4428.5     .05       0
  4530.1     .08       0  4549.3     .05       0    4729     .08       0
  4974.6     .05       0  4986.4    .035       0  4992.4     .05       0
  5235.1     .08       0  5335.3     .05       0  7138.9     .08       0
    7282     .05       0  7639.9      .1       0  7740.1     .05       0
Bank Sta=4745.9,5274.9
XS Rating Curve= 0 ,0
Exp/Cntr=0.3,0.1

Type RM Length L Ch R = 1 ,278873  ,419,419,419
BEGIN DESCRIPTION:
TEHUACANA CREEK 200.0
END DESCRIPTION:
XS GIS Cut Line= 3
      3497129.31     10620782.31      3496937.87      10619679.5
      3496437.68     10616813.93
#Sta/Elev= 30
  3982.7     444  4422.9  437.43  4513.7  433.35  4583.7  430.63  4620.8  425.86
  4651.5  417.48  4664.9  420.38    4675  427.34  4685.2  430.17  4770.8  431.74
  4949.9  429.65  4969.4  423.61  4986.7  411.39  4989.4  410.89  4992.7  411.39
  5030.3  411.59  5050.6  418.44  5059.1  425.54  5131.8  430.67  5241.9  430.17
  5293.2  429.77  5497.2  429.29  5530.4  426.46  5560.1  429.14  5931.9  434.96
  6380.4  432.93  7456.4  438.57  7682.3  442.01  7862.4  451.56  8010.9  456.14
#Mann= 8 ,-1 , 0
  3982.7     .05       0  4513.7     .12       0  4620.8     .16       0
  4986.7     .07       0  4992.7     .16       0  5241.9     .05       0
  5293.2     .16       0  5560.1     .05       0
Bank Sta=4770.8,5131.8
XS Rating Curve= 0 ,0
Exp/Cntr=0.3,0.1

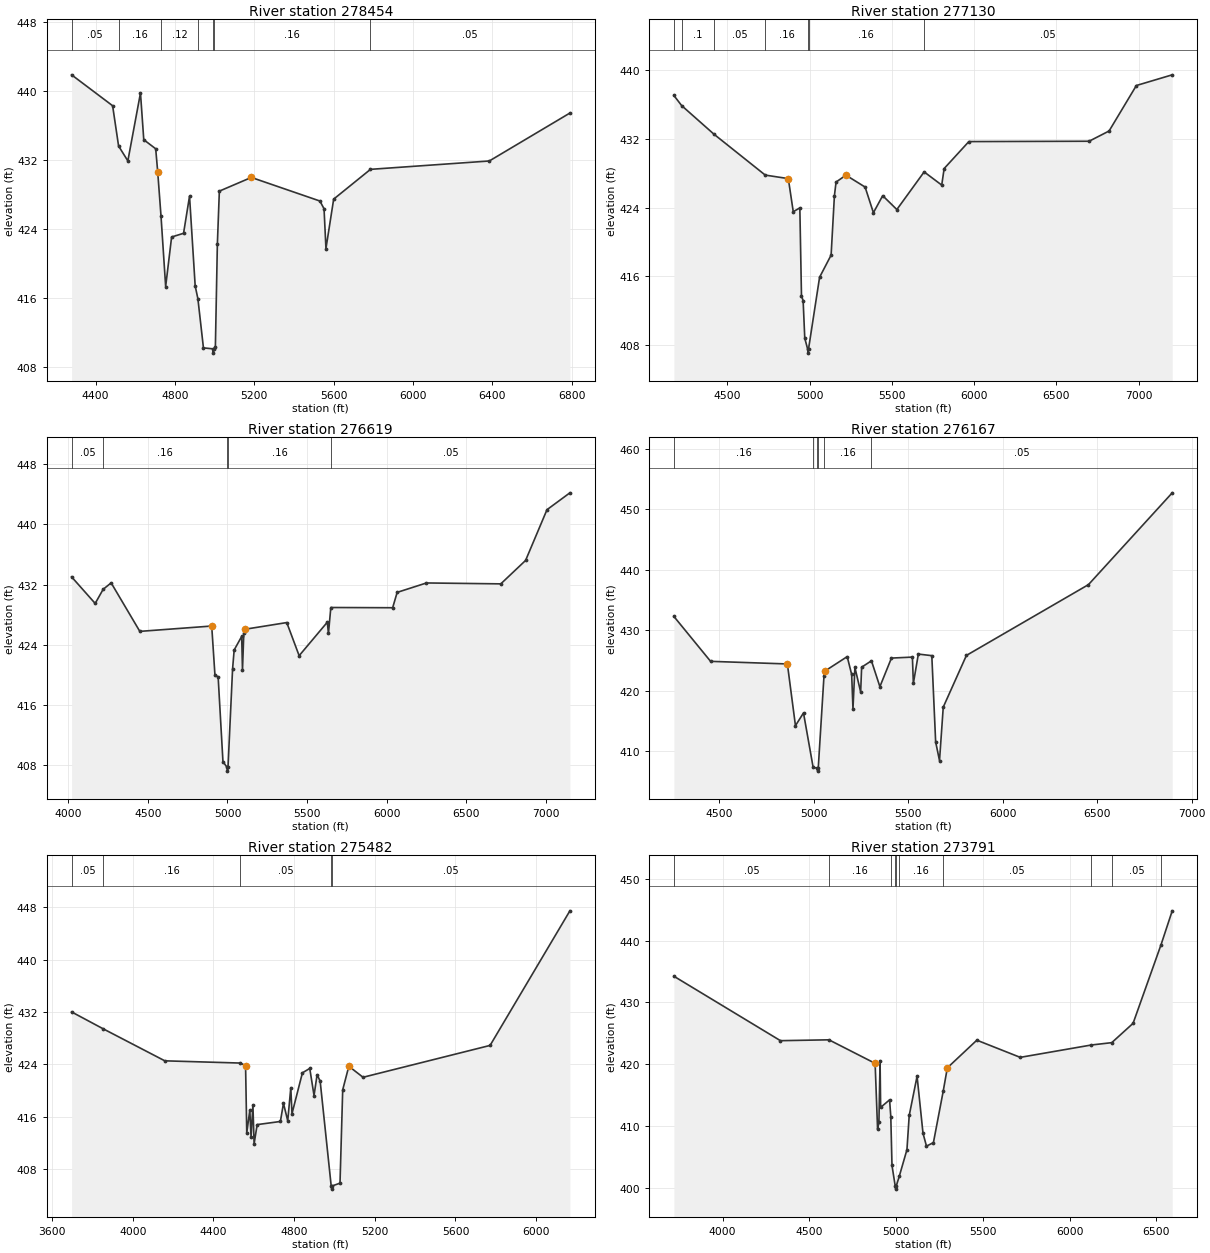
Type RM Length L Ch R = 1 ,278454  ,1324,1324,1324
BEGIN DESCRIPTION:
TEHUACANA CREEK 199.0
END DESCRIPTION:
XS GIS Cut Line= 3
      3497389.23     10620583.04      3497328.46     10619732.33
      3497033.32     10618100.38
#Sta/Elev= 30
  4279.1   441.9  4485.9  438.31    4516  433.63  4562.7   431.9  4626.3  439.79
  4642.9  434.36    4703  433.31  4713.1  430.64  4729.9  425.45  4753.2  417.31
  4783.2  423.06  4843.4  423.49  4873.5   427.8    4902  417.37  4915.6   415.9
  4943.6  410.18  4990.8  410.07  4993.5  409.57  4996.8  410.07  5003.8  410.33
  5013.8  422.22  5023.8  428.39    5185  429.98  5530.5  427.24  5551.4  426.34
    5561  421.72  5599.9  427.46  5785.5  430.92  6384.1  431.89  6790.4  437.46
#Mann= 7 ,-1 , 0
  4279.1     .05       0    4516     .16       0  4729.9     .12       0
  4915.6     .16       0  4990.8     .07       0  4996.8     .16       0
  5785.5     .05       0
Bank Sta=4713.1,5185
XS Rating Curve= 0 ,0
Exp/Cntr=0.3,0.1

Type RM Length L Ch R = 1 ,277130  ,511,511,511
BEGIN DESCRIPTION:
TEHUACANA CREEK 197.0
END DESCRIPTION:
XS GIS Cut Line= 3
      3498219.91     10620745.08      3498193.87     10619630.54
      3497079.38     10618075.89
#Sta/Elev= 30
  4175.7  437.01  4222.6  435.84  4418.9  432.52  4730.6  427.77  4870.8  427.36
  4900.8  423.52  4940.8  423.96  4950.8  413.73  4960.8   413.2  4970.8  408.83
  4987.8   407.6  4990.6   407.1  4993.8   407.6  5060.8  415.91  5130.8  418.48
  5150.9  425.37  5160.9  426.96  5220.9  427.76  5337.4  426.38  5387.8   423.4
  5444.3  425.38  5530.2  423.77  5696.1  428.14  5802.9  426.61  5817.6  428.53
  5967.7  431.66  6698.2   431.7  6819.8  432.89  6985.6  438.17  7203.4  439.41
#Mann= 7 ,-1 , 0
  4175.7     .05       0  4222.6      .1       0  4418.9     .05       0
  4730.6     .16       0  4987.8     .07       0  4993.8     .16       0
  5696.1     .05       0
Bank Sta=4870.8,5220.9
XS Rating Curve= 0 ,0
Exp/Cntr=0.3,0.1

Type RM Length L Ch R = 1 ,276619  ,452,452,452
BEGIN DESCRIPTION:
TEHUACANA CREEK 196.0
END DESCRIPTION:
XS GIS Cut Line= 4
      3498574.12     10620648.16      3498605.01     10619931.61
      3498552.92     10619480.22      3497187.05      10618079.4
#Sta/Elev= 30
  4021.5  433.02  4169.6  429.49  4219.8  431.37  4269.9  432.22  4449.9  425.78
  4901.2  426.49  4921.5  419.96  4941.5  419.74  4971.7  408.49  4997.4  407.72
  5000.1  407.22  5003.4  407.72  5032.1  420.78  5042.1  423.31  5089.3  425.11
  5094.3   420.6  5102.5  425.51  5112.6  426.07  5372.3  426.95    5450  422.55
  5626.8     427  5633.9   425.5  5648.9  428.95    6037  428.92  6065.3  430.96
  6249.2  432.21  6715.8  432.09  6871.4   435.2  7005.8  441.94  7149.6  444.18
#Mann= 5 ,-1 , 0
  4021.5     .05       0  4219.8     .16       0  4997.4     .07       0
  5003.4     .16       0  5648.9     .05       0
Bank Sta=4901.2,5112.6
XS Rating Curve= 0 ,0
Exp/Cntr=0.3,0.1

Type RM Length L Ch R = 1 ,276167  ,685,685,685
BEGIN DESCRIPTION:
TEHUACANA CREEK 195.0
END DESCRIPTION:
XS GIS Cut Line= 3
      3498700.48     10620391.71      3498995.63     10619610.43
      3499325.92     10617839.85
#Sta/Elev= 30
  4260.9  432.28  4454.9  424.87  4861.2  424.44  4903.9  414.25  4946.5  416.35
  4997.5  407.36  5018.5  407.24  5021.3  406.74  5024.5  407.24  5054.8  422.43
  5061.9  423.31  5177.7  425.65  5201.3   422.7  5208.2  417.03  5218.4  423.87
  5248.9   419.8    5254   423.9  5305.9  424.96  5350.6  420.69  5411.7  425.41
  5522.6  425.57  5527.7  421.23  5554.1  426.07  5625.3  425.81  5645.6  411.56
    5666  408.48  5685.8  417.31  5808.4  425.85  6454.1  437.54  6897.2   452.7
#Mann= 6 ,-1 , 0
  4260.9     .16       0  4997.5     .05       0  5018.5    .035       0
  5024.5     .05       0  5054.8     .16       0  5305.9     .05       0
Bank Sta=4861.2,5061.9
XS Rating Curve= 0 ,0
Exp/Cntr=0.3,0.1

Type RM Length L Ch R = 1 ,275482  ,1691,1691,1691
BEGIN DESCRIPTION:
TEHUACANA CREEK 194.0
END DESCRIPTION:
XS GIS Cut Line= 3
       3498699.6     10620610.21      3499399.61     10619510.19
       3499599.6     10618360.21
#Sta/Elev= 30
  3696.4  432.02  3853.3  429.44  4158.7  424.56  4533.7  424.22  4559.2  423.82
  4565.1  413.57  4580.3  417.04  4586.3  412.93  4595.6  417.83  4601.5   411.9
  4616.7  414.83  4731.9  415.31  4747.1  418.08  4768.3  415.41  4783.5  420.47
  4789.4   416.5  4841.1  422.73  4877.5   423.4  4898.7  419.27  4913.9  422.44
  4929.1  421.46  4983.7  405.49  4986.5  404.99  4989.7  405.49  5027.5   405.9
  5040.9  420.14  5071.3  423.73  5141.7  422.05  5771.7  426.91  6167.5  447.44
#Mann= 5 ,-1 , 0
  3696.4     .05       0  3853.3     .16       0  4533.7     .05       0
  4983.7    .035       0  4989.7     .05       0
Bank Sta=4559.2,5071.3
XS Rating Curve= 0 ,0
Exp/Cntr=0.3,0.1

Type RM Length L Ch R = 1 ,273791  ,370,370,370
BEGIN DESCRIPTION:
TEHUACANA CREEK 193.0
END DESCRIPTION:
XS GIS Cut Line= 4
      3499021.88     10620827.78      3499924.69     10620050.85
      3499994.13     10619877.24       3500024.5     10618384.72
#Sta/Elev= 30
  3719.8  434.22  4333.6  423.79  4612.9  423.93    4879  420.12  4893.2  409.46
  4900.9  410.57  4907.5  420.55  4910.8  412.99  4962.3  414.21  4969.3  411.51
  4976.2  403.59  4994.8  400.26  4997.5  399.76  5000.8  400.26  5019.3  401.95
  5062.4  406.15  5075.4  411.68  5120.7  418.03  5154.9   408.8  5174.9  406.72
  5214.9  407.29  5271.2   415.6    5295  419.39    5465  423.87    5715  421.09
  6124.4  423.09  6242.3  423.47  6365.2   426.6  6526.2  439.32  6590.7  444.81
#Mann= 10 ,-1 , 0
  3719.8     .05       0  4612.9     .16       0  4969.3     .05       0
  4994.8    .035       0  5000.8     .05       0  5019.3     .16       0
  5271.2     .05       0  6124.4     .16       0  6242.3     .05       0
  6526.2     .16       0
Bank Sta=4879,5295
XS Rating Curve= 0 ,0
Exp/Cntr=0.3,0.1

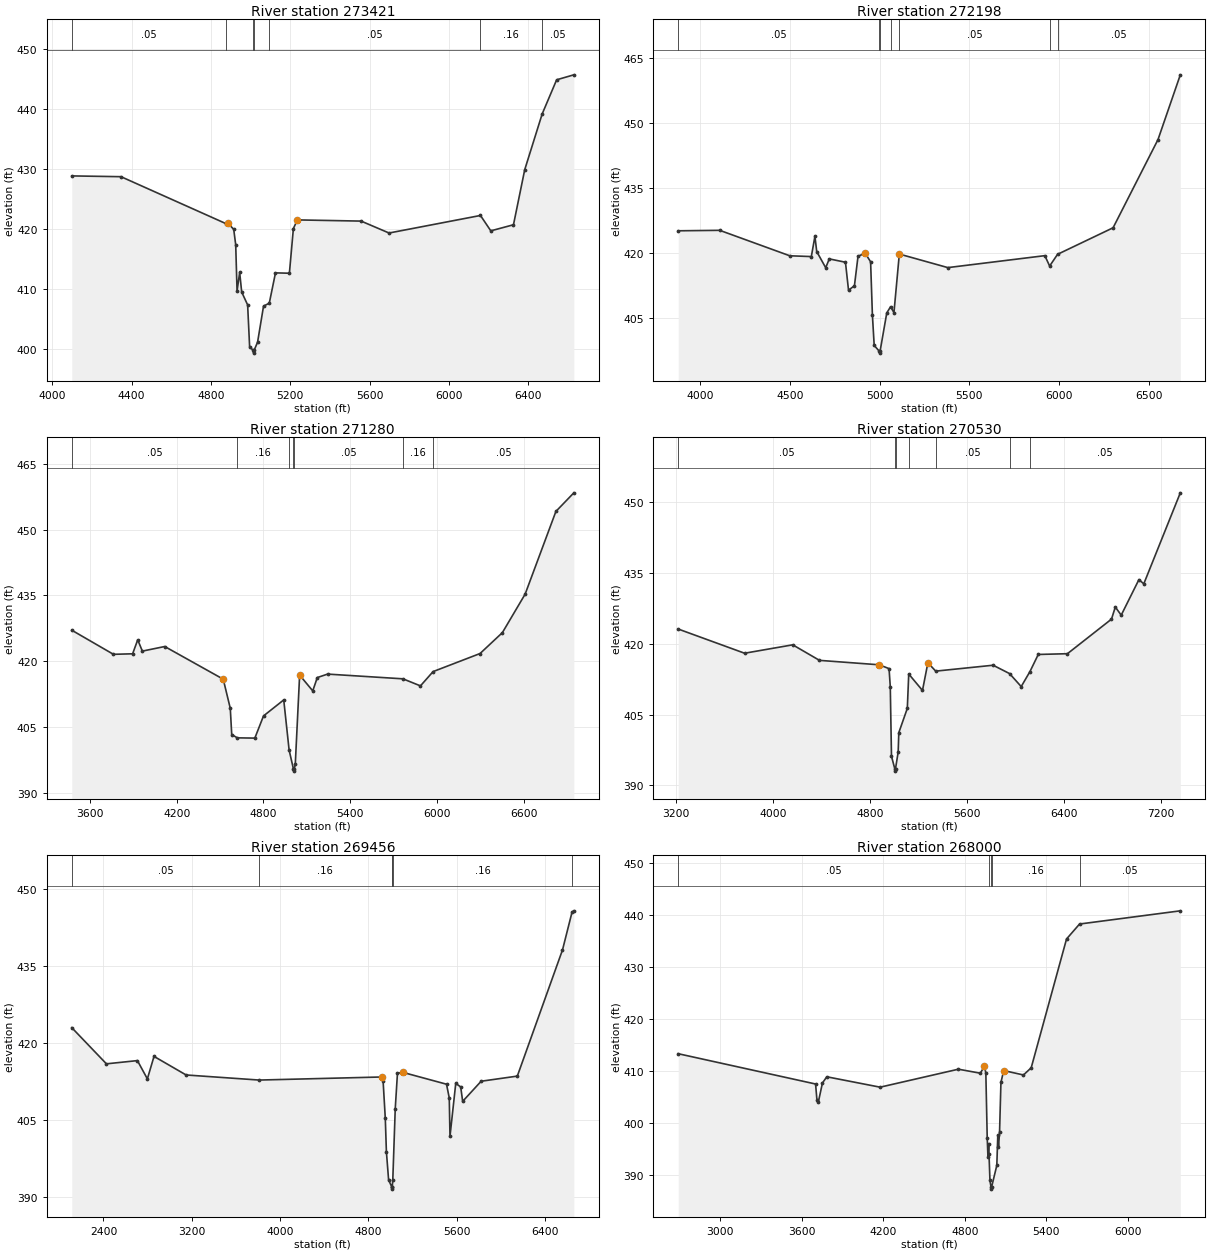
Type RM Length L Ch R = 1 ,273421  ,1223,1223,1223
BEGIN DESCRIPTION:
TEHUACANA CREEK 192.0
END DESCRIPTION:
XS GIS Cut Line= 3
      3500311.34     10621064.68      3500228.27     10619844.81
      3500367.02     10618543.98
#Sta/Elev= 30
  4098.9  428.85  4347.1  428.72  4876.6  420.87  4885.2  420.98  4915.3  419.92
  4925.3  417.35  4932.1  409.63  4945.3  412.72  4955.4  409.45  4985.4   407.3
  4995.5  400.28  5012.5  399.74  5015.3  399.24  5018.5  399.74  5035.6  401.08
  5065.6   407.1  5094.5  407.58  5125.8  412.65  5195.9  412.59    5216  420.05
    5236   421.5  5557.5   421.3  5698.3  419.31  6159.1  422.24  6211.2  419.67
  6325.5  420.69  6382.2  429.89  6470.1   439.2  6543.1  444.91  6629.8  445.74
#Mann= 7 ,-1 , 0
  4098.9     .05       0  4876.6     .16       0  5012.5     .07       0
  5018.5     .16       0  5094.5     .05       0  6159.1     .16       0
  6470.1     .05       0
Bank Sta=4885.2,5236
XS Rating Curve= 0 ,0
Exp/Cntr=0.3,0.1

Type RM Length L Ch R = 1 ,272198  ,918,918,918
BEGIN DESCRIPTION:
TEHUACANA CREEK 190.0
END DESCRIPTION:
XS GIS Cut Line= 2
      3501016.41     10621181.11      3500981.69     10618386.03
#Sta/Elev= 30
  3878.8  425.06  4109.7  425.17  4499.8  419.29  4619.8  419.11  4639.8  423.79
  4649.8  420.27  4699.8  416.53  4719.8  418.57  4809.8   417.8  4826.9  411.34
  4859.8  412.38  4879.8  419.19  4919.8  419.88  4949.8   417.9  4959.8  405.63
  4969.8  398.59  4996.8  397.31  4999.6  396.81  5002.8  397.31  5039.8  406.09
    5061  407.53  5079.8  406.16  5109.7  419.69  5379.8  416.56  5919.9  419.32
  5946.6  416.92  5990.7  419.63  6299.9  425.76  6549.9  446.13  6674.1  461.08
#Mann= 7 ,-1 , 0
  3878.8     .05       0  4996.8    .035       0  5002.8     .05       0
    5061     .16       0  5109.7     .05       0  5946.6     .16       0
  5990.7     .05       0
Bank Sta=4919.8,5109.7
XS Rating Curve= 0 ,0
Exp/Cntr=0.3,0.1

Type RM Length L Ch R = 1 ,271280  ,750,750,750
BEGIN DESCRIPTION:
TEHUACANA CREEK 189.0
END DESCRIPTION:
XS GIS Cut Line= 4
      3501389.67     10621484.97      3501771.62     10620512.73
      3501771.62     10619905.09      3501216.08     10618169.02
#Sta/Elev= 30
  3473.1  427.07  3761.5  421.57  3894.4  421.69  3929.5  424.88  3961.7   422.3
  4116.6  423.35  4521.4   415.9  4570.2  409.25  4580.2  403.28  4618.8  402.52
  4740.2  402.46  4800.2  407.52  4940.2  411.17  4977.4  399.74  5007.2  395.43
    5010  394.93  5013.2  395.43  5020.2  396.55  5050.2  416.83    5141  413.23
  5172.5  416.27  5243.7  417.06  5765.4  415.98  5886.4  414.37  5973.9  417.63
  6298.9  421.75  6453.4  426.51  6610.9  435.29  6823.9  454.16  6948.1   458.4
#Mann= 7 ,-1 , 0
  3473.1     .05       0  4618.8     .16       0  4977.4     .05       0
  5007.2    .035       0  5013.2     .05       0  5765.4     .16       0
  5973.9     .05       0
Bank Sta=4521.4,5050.2
XS Rating Curve= 0 ,0
Exp/Cntr=0.3,0.1

Type RM Length L Ch R = 1 ,270530  ,1074,1074,1074
BEGIN DESCRIPTION:
TEHUACANA CREEK 188.0
END DESCRIPTION:
XS GIS Cut Line= 4
      3502039.42     10621808.91      3502433.22      10620274.6
      3502466.06     10619922.45      3501694.06     10617857.99
#Sta/Elev= 30
  3219.1   423.1  3766.5  417.98  4163.8  419.76  4384.4  416.47  4877.9  415.53
  4958.2  414.72  4968.3  410.91  4978.3  396.17  5005.4  393.52  5008.2  393.02
  5011.4  393.52  5033.5  397.07  5038.6  401.16  5108.9  406.31  5120.6  413.58
    5234   410.1  5278.6  415.97  5343.1  414.19  5816.7  415.44  5952.4  413.67
  6048.4  410.92  6120.6   414.1  6189.1  417.72  6429.7  417.88  6793.2   425.2
  6824.7  427.76  6873.4  426.04  7019.5  433.57  7059.6  432.67  7360.9  451.94
#Mann= 7 ,-1 , 0
  3219.1     .05       0  5005.4    .035       0  5011.4     .05       0
  5120.6     .16       0  5343.1     .05       0  5952.4     .16       0
  6120.6     .05       0
Bank Sta=4877.9,5278.6
XS Rating Curve= 0 ,0
Exp/Cntr=0.3,0.1

Type RM Length L Ch R = 1 ,269456  ,1456,1456,1456
BEGIN DESCRIPTION:
TEHUACANA CREEK 187.0
END DESCRIPTION:
XS GIS Cut Line= 4
      3502949.91     10622563.23      3503140.25     10620007.34
      3503118.54     10619508.21      3502684.58     10618086.96
#Sta/Elev= 30
  2113.1  422.93    2427  415.88  2707.8  416.51    2798  412.95  2858.2  417.33
    3149  413.71  3810.8  412.72  4923.5  413.32  4933.5  412.59  4953.5  405.27
  4963.5  398.77  4983.5  393.27  5010.5  391.97  5013.3  391.47  5016.5  391.97
  5021.3  393.18  5043.6  407.12  5063.6  414.01  5113.6  414.21  5508.2  411.91
    5533  409.23  5539.6  401.76  5591.8  412.07  5636.6  411.38  5654.6  408.57
  5821.9  412.49  6149.6  413.49  6558.9  438.07  6645.5  445.45  6661.7  445.69
#Mann= 6 ,-1 , 0
  2113.1     .05       0  3810.8     .16       0  5010.5     .07       0
  5016.5     .16       0  5021.3     .16       0  6645.5     .05       0
Bank Sta=4923.5,5113.6
XS Rating Curve= 0 ,0
Exp/Cntr=0.3,0.1

Type RM Length L Ch R = 1 ,268000  ,870,870,870
BEGIN DESCRIPTION:
Mapping XS f656ac5f
END DESCRIPTION:
XS GIS Cut Line= 3
      3504461.22     10621740.67      3504132.73     10619323.49
      3503742.28     10618134.77
#Sta/Elev= 30
  2693.6  413.32  3703.2  407.49  3713.4  404.32  3723.5  404.03  3753.7  407.69
  3785.7  408.88  4177.6  406.88  4752.8  410.34  4914.3  409.57  4944.6  410.92
  4954.7   409.6  4964.8  397.17  4970.2  393.48  4975.2  396.02    4978  393.98
  4984.9  388.94    4992  387.76  4994.8  387.26    4998  387.76  5035.4  391.84
  5042.6  397.61  5047.7  395.28  5055.6  398.26  5065.7  407.79  5085.9  410.08
  5231.2  409.23  5288.1  410.61  5547.9   435.4  5643.6  438.28  6384.2  440.82
#Mann= 5 ,-1 , 0
  2693.6     .05       0    4978     .16       0    4992     .07       0
    4998     .16       0  5643.6     .05       0
Bank Sta=4944.6,5085.9
XS Rating Curve= 0 ,0
Exp/Cntr=0.3,0.1