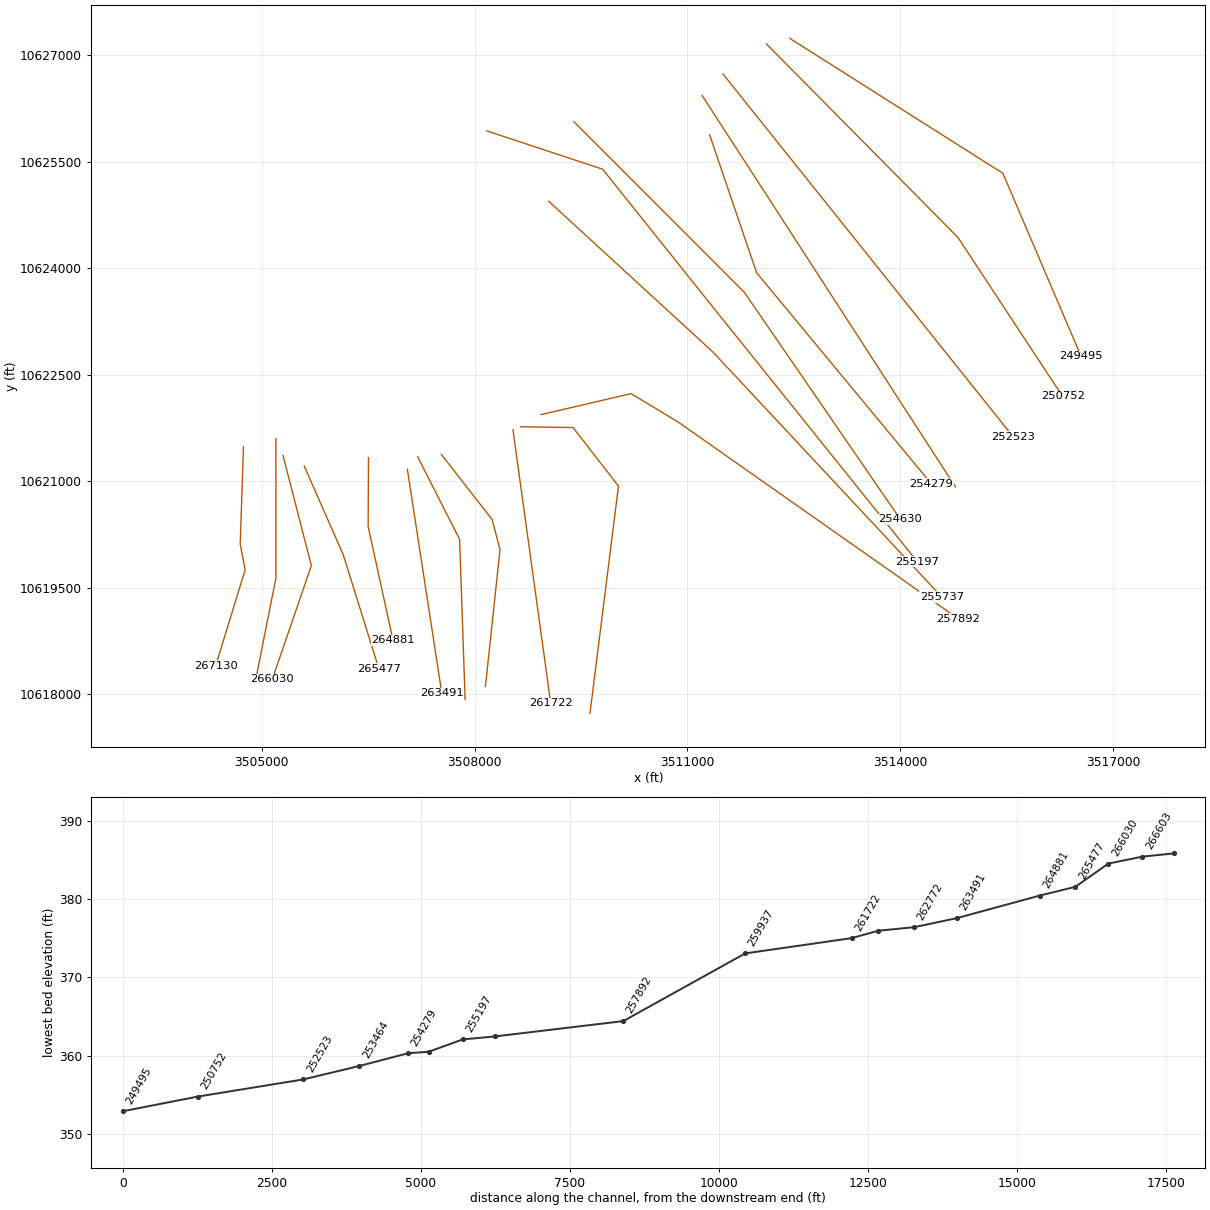
HEC-RAS study TEHUACANA CREEK.prj: TEHUACANA CREEK Base Level Engineering

--- TEHUACANA CREEK.g01 (geometry) --- (continued)

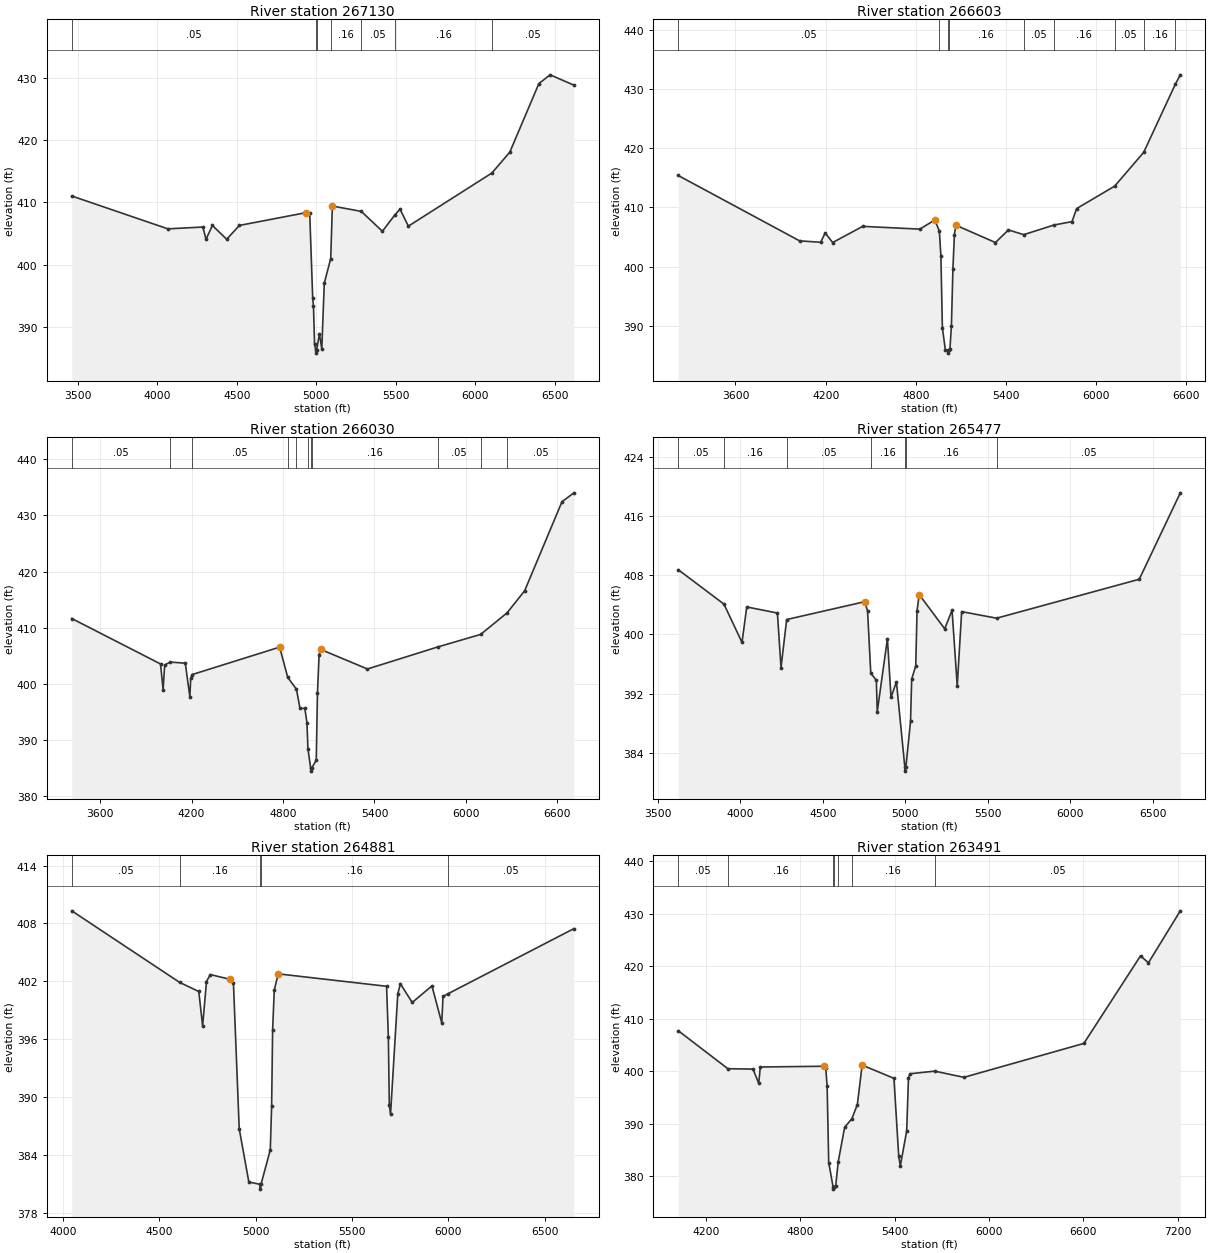
Type RM Length L Ch R = 1 ,267130  ,527,527,527
BEGIN DESCRIPTION:
TEHUACANA CREEK 186.0
END DESCRIPTION:
XS GIS Cut Line= 4
      3504743.33     10621484.57      3504696.97     10620113.42
      3504766.41     10619748.84      3504349.83     10618394.95
#Sta/Elev= 30
    3462  411.02  4066.7  405.75  4286.9  406.04  4306.9  404.08  4346.9  406.29
  4436.9  404.08    4517   406.3    4939  408.36  4959.4  408.24  4978.2  394.64
  4983.2   393.3  4989.9  387.28  4997.1  386.31  4999.9  385.81  5003.1  386.31
  5020.5  388.93  5035.4  386.48    5051  397.02  5091.6  400.99  5101.9  409.41
    5284  408.55  5416.7  405.36  5496.9  408.04    5528   408.9  5580.2  406.18
    6106  414.71  6218.5  418.05  6401.5  429.05  6472.1  430.46  6621.6  428.81
#Mann= 7 ,-1 , 0
    3462     .05       0  4997.1    .035       0  5003.1     .05       0
  5091.6     .16       0    5284     .05       0  5496.9     .16       0
    6106     .05       0
Bank Sta=4939,5101.9
XS Rating Curve= 0 ,0
Exp/Cntr=0.3,0.1

Type RM Length L Ch R = 1 ,266603  ,573,573,573
BEGIN DESCRIPTION:
TEHUACANA CREEK 185.0
END DESCRIPTION:
XS GIS Cut Line= 3
      3505200.44     10621597.78      3505200.44     10619635.99
      3504931.68     10618283.53
#Sta/Elev= 30
    3219   415.4  4026.6  404.36  4166.6  404.12  4196.6  405.69  4246.6  404.08
  4446.6  406.81  4826.6  406.34  4926.6   407.9  4956.3     406  4966.6  401.88
  4976.6  389.68  4996.6  385.91  5013.6   385.9  5016.3   385.4  5019.6   385.9
  5026.6  386.02  5036.6  389.98  5046.6  399.58  5056.6  405.43  5066.6     407
  5329.4  404.08    5416   406.2  5518.1  405.41  5719.7  407.04  5839.2  407.61
  5869.8  409.81  6122.8   413.6  6316.3  419.32  6525.9  430.78  6559.7   432.4
#Mann= 9 ,-1 , 0
    3219     .05       0  4956.3     .16       0  5013.6     .07       0
  5019.6     .16       0  5518.1     .05       0  5719.7     .16       0
  6122.8     .05       0  6316.3     .16       0  6525.9     .05       0
Bank Sta=4926.6,5066.6
XS Rating Curve= 0 ,0
Exp/Cntr=0.3,0.1

Type RM Length L Ch R = 1 ,266030  ,553,553,553
BEGIN DESCRIPTION:
TEHUACANA CREEK 184.0
END DESCRIPTION:
XS GIS Cut Line= 3
      3505299.62     10621360.15      3505699.61     10619810.19
      3505149.62     10618210.22
#Sta/Elev= 30
  3414.8  411.66  3996.7  403.58  4013.8  399.02  4024.1   403.4  4060.8  403.91
  4159.3  403.71  4189.3  397.71  4194.8  401.02  4205.6   401.7    4778  406.57
    4831  401.19  4888.4  399.08  4911.3  395.67  4943.2  395.67  4957.1  393.14
  4963.5  388.52  4981.6  385.01  4984.3  384.51  4987.6  385.01  5018.2  386.47
  5025.9  398.34  5036.7  405.18  5047.3  406.16  5353.9  402.68  5813.4  406.59
    6096  408.83  6268.9  412.65  6384.7  416.59  6629.3  432.42  6707.4  434.02
#Mann= 11 ,-1 , 0
  3414.8     .05       0  4060.8     .16       0  4205.6     .05       0
    4831     .16       0  4888.4     .05       0  4963.5     .16       0
  4981.6     .07       0  4987.6     .16       0  5813.4     .05       0
    6096     .16       0  6268.9     .05       0
Bank Sta=4778,5047.3
XS Rating Curve= 0 ,0
Exp/Cntr=0.3,0.1

Type RM Length L Ch R = 1 ,265477  ,596,596,596
BEGIN DESCRIPTION:
TEHUACANA CREEK 183.0
END DESCRIPTION:
XS GIS Cut Line= 3
      3505599.61     10621210.18      3506149.61     10619960.19
       3506649.6     10618360.23
#Sta/Elev= 30
  3623.9  408.74  3901.1  404.09  4010.2  398.92    4039  403.71  4224.8  402.89
  4246.6  395.52  4280.8  402.01  4754.1  404.42    4771  403.17  4790.4  394.78
  4824.2   393.8  4829.6  389.56  4891.2  399.42  4913.1   391.5  4945.8   393.6
    4997  382.04  4999.8  381.54    5003  382.04  5031.4   388.3  5038.3  393.98
  5062.9  395.75  5070.7  403.18  5083.8  405.38  5238.4  400.76  5282.9  403.28
  5314.3  393.05    5341  403.08  5552.8  402.19    6417  407.45  6665.8  419.12
#Mann= 7 ,-1 , 0
  3623.9     .05       0  3901.1     .16       0  4280.8     .05       0
  4790.4     .16       0    4997     .07       0    5003     .16       0
  5552.8     .05       0
Bank Sta=4754.1,5083.8
XS Rating Curve= 0 ,0
Exp/Cntr=0.3,0.1

Type RM Length L Ch R = 1 ,264881  ,1390,1390,1390
BEGIN DESCRIPTION:
TEHUACANA CREEK 182.0
END DESCRIPTION:
XS GIS Cut Line= 3
      3506504.71     10621329.75      3506499.61     10620360.19
      3506849.61      10618760.2
#Sta/Elev= 30
  4044.9  409.31  4604.5  401.89  4704.5  400.94  4724.5  397.37  4744.5  401.97
  4764.5   402.7  4864.5  402.21  4884.5   401.8  4914.5   386.7  4964.5  381.17
  5021.7  380.93  5024.5  380.43  5027.7  380.93  5075.9  384.51  5082.8  389.04
    5088  396.93  5096.4  401.05  5116.8  402.77  5679.8  401.48    5689  396.24
  5694.1  389.14  5700.3  388.19    5738  400.69  5751.5  401.74  5812.9   399.8
  5915.3  401.52  5966.5  397.67  5972.7  400.42  5997.4  400.69  6652.3  407.46
#Mann= 5 ,-1 , 0
  4044.9     .05       0  4604.5     .16       0  5021.7     .07       0
  5027.7     .16       0  5997.4     .05       0
Bank Sta=4864.5,5116.8
XS Rating Curve= 0 ,0
Exp/Cntr=0.3,0.1

Type RM Length L Ch R = 1 ,263491  ,719,719,719
BEGIN DESCRIPTION:
TEHUACANA CREEK 181.0
END DESCRIPTION:
XS GIS Cut Line= 2
      3507052.46     10621166.15       3507538.1     10618009.99
#Sta/Elev= 30
  4022.8  407.72  4338.6  400.48  4498.3  400.41  4534.7   397.7  4544.8  400.81
  4949.5  400.95  4961.1  400.61  4969.8  397.13  4979.9  382.62  5007.2  378.05
    5010  377.55  5013.2  378.05  5024.3  378.13  5040.3  382.76  5081.1   389.3
  5127.6  390.99    5162  393.66  5192.4  401.17  5394.7  398.65  5425.1  383.84
  5435.2  381.97  5475.7   388.6  5487.2  398.71  5495.9  399.52  5654.2  400.02
  5839.9  398.84  6602.6   405.3    6963  421.97  7013.5  420.66  7216.1  430.55
#Mann= 7 ,-1 , 0
  4022.8     .05       0  4338.6     .16       0  5007.2     .07       0
  5013.2     .16       0  5040.3     .05       0  5127.6     .16       0
  5654.2     .05       0
Bank Sta=4949.5,5192.4
XS Rating Curve= 0 ,0
Exp/Cntr=0.3,0.1

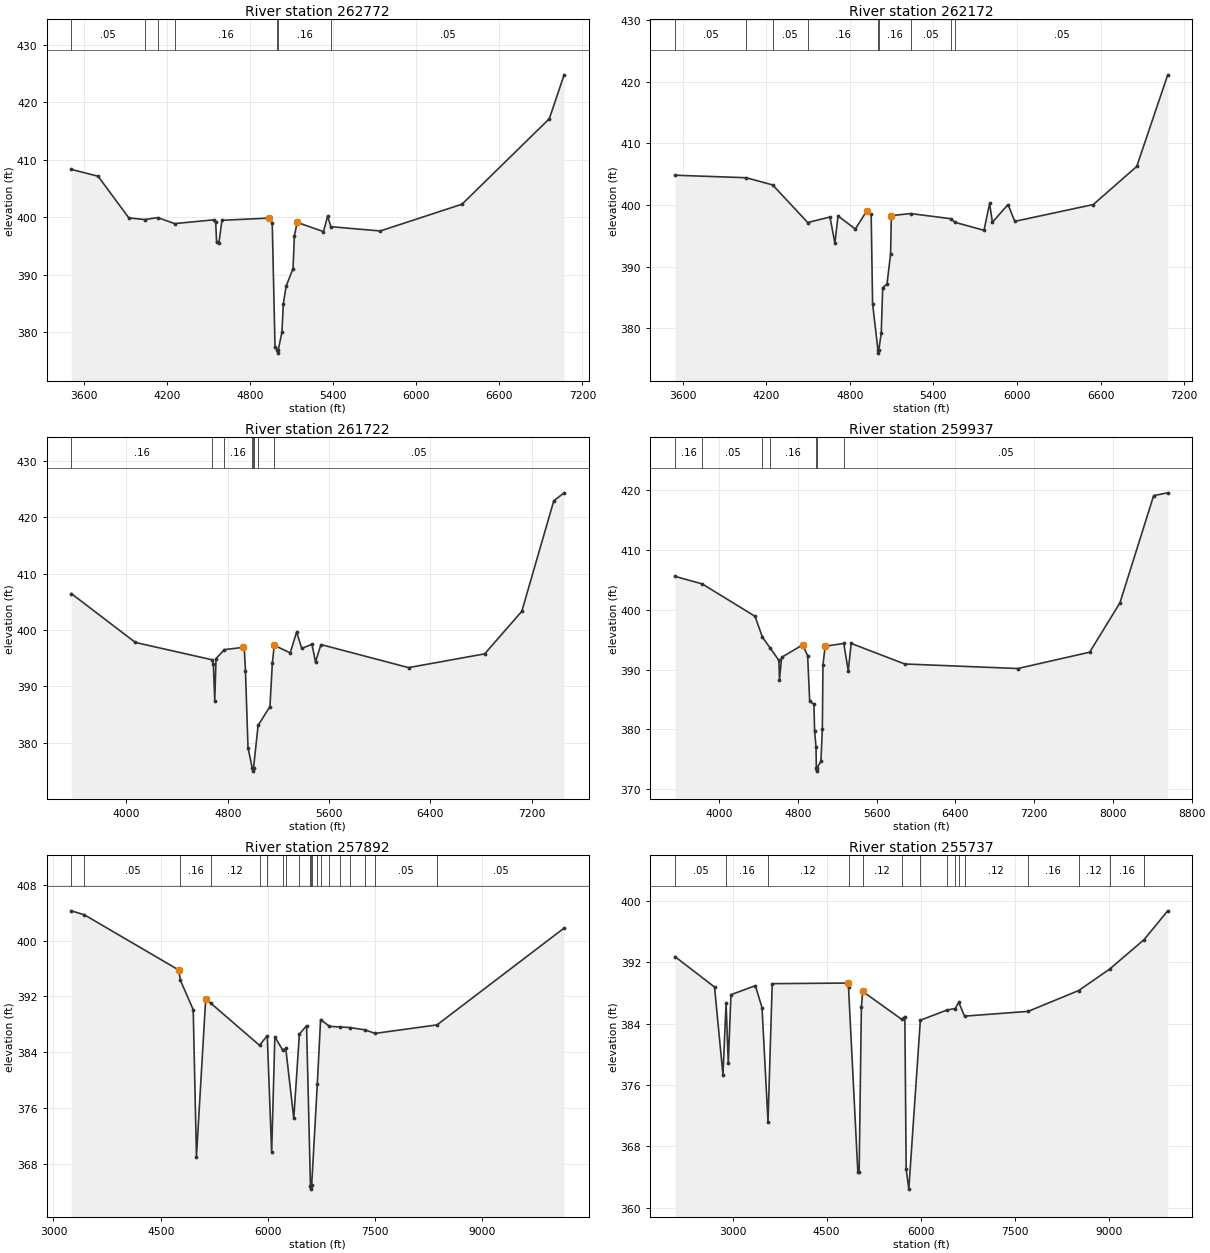
Type RM Length L Ch R = 1 ,262772  ,600,600,600
BEGIN DESCRIPTION:
TEHUACANA CREEK 180.0
END DESCRIPTION:
XS GIS Cut Line= 3
      3507198.28     10621339.81      3507788.56     10620180.07
      3507866.15     10617923.32
#Sta/Elev= 30
  3508.5  408.32  3701.6  407.13  3924.1  399.89  4038.5   399.6  4133.5  399.94
  4254.3   398.9  4541.3  399.56  4551.6  399.14  4557.9  395.63    4574  395.44
  4596.5  399.47  4939.8  399.86  4959.8  398.97  4979.8  377.51  4996.8  376.89
  4999.6  376.39  5002.8  376.89  5029.8  380.03  5039.8  384.91  5059.8  387.99
  5109.9  391.09  5119.9  396.78  5139.9  399.11    5330  397.51    5360  400.21
    5383  398.36  5740.2  397.62  6330.6  402.27    6961  417.12  7067.9  424.75
#Mann= 7 ,-1 , 0
  3508.5     .05       0  4038.5     .16       0  4133.5     .05       0
  4254.3     .16       0  4996.8     .07       0  5002.8     .16       0
    5383     .05       0
Bank Sta=4939.8,5139.9
XS Rating Curve= 0 ,0
Exp/Cntr=0.3,0.1

Type RM Length L Ch R = 1 ,262172  ,450,450,450
BEGIN DESCRIPTION:
TEHUACANA CREEK 179.0
END DESCRIPTION:
XS GIS Cut Line= 4
      3507531.62     10621374.51       3508246.9     10620457.85
      3508358.01     10620034.24      3508152.68     10618109.01
#Sta/Elev= 30
  3545.6  404.83  4057.9  404.42    4247  403.25  4498.5  397.15  4658.4  398.04
  4693.7   393.8  4716.2  398.22  4840.3  396.09    4923  399.06    4954  398.51
  4964.3  383.97  5002.7  376.44  5005.5  375.94  5008.7  376.44  5026.4  379.22
  5036.7  386.57  5067.7  387.16  5093.5  392.06  5098.7  398.27  5237.5   398.6
  5524.7  397.77  5555.6  397.18  5763.8  395.88    5804  400.25  5824.1  397.19
  5936.2  400.07    5985  397.34  6548.2  400.07    6860  406.25  7082.4  421.13
#Mann= 9 ,-1 , 0
  3545.6     .05       0  4057.9     .16       0    4247     .05       0
  4498.5     .16       0  5002.7     .07       0  5008.7     .16       0
  5237.5     .05       0  5524.7     .16       0  5555.6     .05       0
Bank Sta=4923,5098.7
XS Rating Curve= 0 ,0
Exp/Cntr=0.3,0.1

Type RM Length L Ch R = 1 ,261722  ,1785,1785,1785
BEGIN DESCRIPTION:
TEHUACANA CREEK 178.0
END DESCRIPTION:
XS GIS Cut Line= 2
      3508540.79     10621721.36      3509072.48     10617869.38
#Sta/Elev= 30
  3565.8  406.48  4071.7  397.81  4674.7  394.75  4686.6  394.02  4697.6  387.48
  4707.7  394.95  4773.1  396.54  4919.7  396.93  4929.8  397.09  4939.9  392.82
  4960.1  379.14  4993.6  375.52  4997.4  375.49  5000.2  374.99  5003.4  375.49
  5039.7   383.1  5133.1  386.44  5151.9  394.09    5167   397.3  5293.2  395.97
  5343.7  399.66    5384  396.76  5464.8  397.48  5492.6  394.35  5535.5  397.44
  6226.8  393.35  6827.6  395.79  7120.4  403.33  7372.7  422.93  7454.3  424.35
#Mann= 8 ,-1 , 0
  3565.8     .16       0  4674.7     .12       0  4773.1     .16       0
  4993.6     .05       0  4997.4     .03       0  5003.4     .05       0
  5039.7     .16       0    5167     .05       0
Bank Sta=4919.7,5167
XS Rating Curve= 0 ,0
Exp/Cntr=0.3,0.1

Type RM Length L Ch R = 1 ,259937  ,2045,2045,2045
BEGIN DESCRIPTION:
TEHUACANA CREEK 177.0
END DESCRIPTION:
XS GIS Cut Line= 4
      3508649.27     10621764.74      3509387.15     10621753.88
      3510027.34     10620929.23      3509625.87     10617728.26
#Sta/Elev= 30
  3548.8  405.58  3826.5  404.31  4362.6  398.91  4437.6  395.43  4516.4  393.61
  4605.2  391.54  4611.5  388.32  4633.3  392.05  4847.8  394.15  4897.5  392.31
  4918.4  384.69  4961.8  384.24  4968.1  379.78  4982.6  377.07  4985.9  373.54
  4988.7  373.04  4991.9  373.54  5032.4  374.68  5046.9  380.01  5053.2  390.83
  5075.8  393.91  5264.7  394.37  5310.3  389.79  5339.9  394.37  5884.1  390.94
    7033  390.18  7763.5  392.91  8071.1  401.15  8413.8  419.07  8556.8  419.53
#Mann= 7 ,-1 , 0
  3548.8     .16       0  3826.5     .05       0  4437.6      .1       0
  4516.4     .16       0  4985.9     .07       0  4991.9     .16       0
  5264.7     .05       0
Bank Sta=4847.8,5075.8
XS Rating Curve= 0 ,0
Exp/Cntr=0.3,0.1

Type RM Length L Ch R = 1 ,257892  ,2155,2155,2155
BEGIN DESCRIPTION:
TEHUACANA CREEK 176.0
END DESCRIPTION:
XS GIS Cut Line= 4
      3508937.75     10621936.14      3510205.08     10622231.27
      3510868.42     10621831.46      3514810.84     10619064.08
#Sta/Elev= 30
  3249.2  404.27  3432.4   403.7  4752.2  395.79  4774.3  394.33  4954.1  390.12
  4999.4  369.06  5128.8  391.67  5197.6  391.06  5881.6     385  5989.8  386.39
  6051.4  369.68  6095.9  386.23  6204.8  384.32  6248.6  384.56  6360.8  374.55
    6439  386.61  6539.5  387.81    6594   364.9  6596.8   364.4    6600   364.9
  6611.4     365  6689.5  379.42  6735.7  388.69  6860.1  387.72  7012.7  387.63
    7142  387.55  7357.4  387.22  7497.4  386.71  8364.5  387.93 10141.7   401.8
#Mann= 20 ,-1 , 0
  3249.2     .16       0  3432.4     .05       0  4774.3     .16       0
  5197.6     .12       0  5881.6     .12       0  5989.8     .16       0
  6204.8     .05       0  6248.6     .16       0    6439     .05       0
    6594     .07       0    6600     .05       0  6611.4     .16       0
  6689.5     .05       0  6735.7     .16       0  6860.1     .16       0
  7012.7     .16       0    7142     .16       0  7357.4     .16       0
  7497.4     .05       0  8364.5     .05       0
Bank Sta=4752.2,5128.8
XS Rating Curve= 0 ,0
Exp/Cntr=0.3,0.1

Type RM Length L Ch R = 1 ,255737  ,540,540,540
BEGIN DESCRIPTION:
TEHUACANA CREEK 175.0
END DESCRIPTION:
XS GIS Cut Line= 3
      3509045.51      10624939.1      3511354.54     10622821.04
      3514584.65     10619366.72
#Sta/Elev= 30
  2079.9  392.74  2711.7  388.77  2846.2  377.36  2896.2  386.67  2931.2  378.86
  2973.8  387.77  3362.9  388.95  3469.5  386.09  3564.9   371.2  3632.3  389.21
  4842.1  389.29  4849.5  388.73  4998.1  364.67  5019.1   364.7  5054.8  386.15
  5075.8   388.2  5698.5  384.56  5748.3  384.93  5769.3  365.04  5811.5  362.44
  5995.5  384.45  6422.4  385.78  6551.9  385.97  6608.3  386.78  6700.3  384.98
  7715.2   385.6  8520.2  388.31  9014.7   391.1  9565.4  394.95  9942.5   398.7
#Mann= 15 ,-1 , 0
  2079.9     .05       0  2896.2     .16       0  3564.9     .12       0
  4849.5     .16       0  5075.8     .12       0  5698.5     .12       0
  5995.5      .1       0  6422.4     .16       0  6551.9     .12       0
  6608.3     .16       0  6700.3     .12       0  7715.2     .16       0
  8520.2     .12       0  9014.7     .16       0  9565.4     .05       0
#XS Ineff= 2 ,-1
 3204.55 3709.09  387.13 5631.82 6018.18  384.13
Permanent Ineff=
       F       F
Bank Sta=4842.1,5075.8
XS Rating Curve= 0 ,0
Exp/Cntr=0.3,0.1

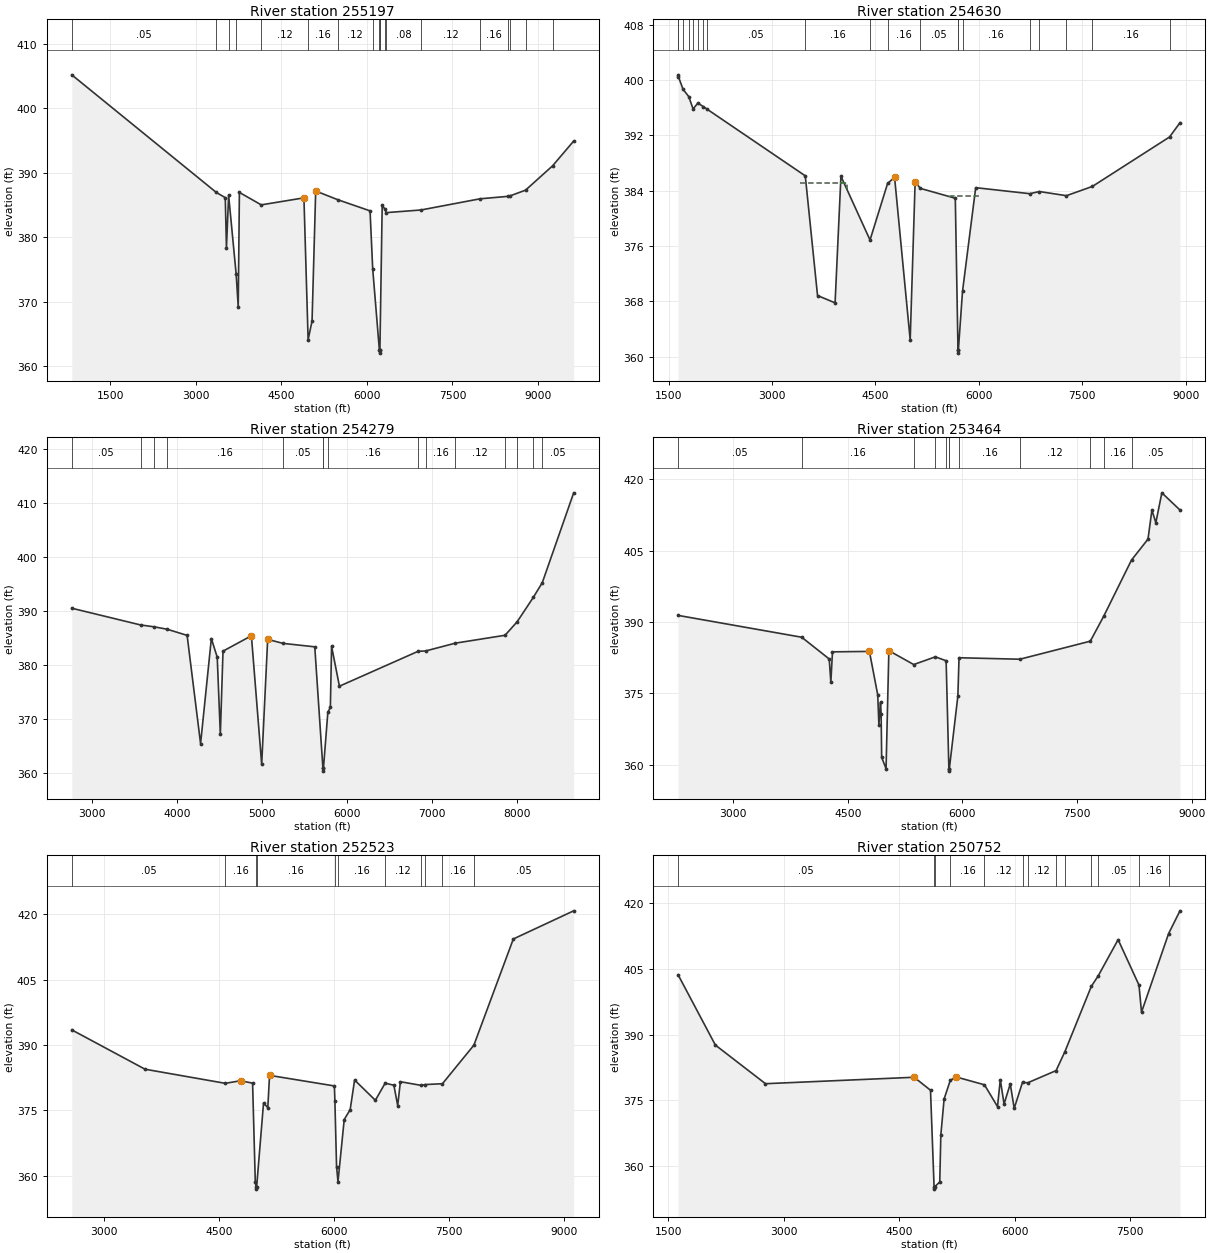
Type RM Length L Ch R = 1 ,255197  ,567,567,567
BEGIN DESCRIPTION:
TEHUACANA CREEK 174.0
END DESCRIPTION:
XS GIS Cut Line= 4
      3508171.87      10625931.4      3509803.86     10625392.37
      3511349.61     10623460.19       3514237.4     10619865.88
#Sta/Elev= 30
   822.8  405.18    3358  386.96  3515.2  386.15    3536  378.38  3574.3  386.51
  3706.1  374.33  3742.5  369.26  3763.3  386.96  4146.6  385.03  4895.1  386.12
  4968.7  364.14  5037.5  367.03  5101.5  387.18  5485.7  385.84    6055   384.1
  6101.3  375.14  6217.9  362.59  6221.7  362.56  6224.5  362.06  6227.7  362.56
  6267.9  384.94  6316.9  384.36  6339.8  383.83  6949.5  384.24  7983.1  385.97
  8470.6  386.35  8506.3  386.41    8782  387.31  9255.5  391.07  9626.6  394.92
#Mann= 19 ,-1 , 0
   822.8     .05       0    3358     .16       0  3574.3     .12       0
  3706.1     .16       0  4146.6     .12       0  4968.7     .16       0
  5485.7     .12       0  6101.3     .16       0  6217.9     .05       0
  6221.7     .07       0  6227.7     .05       0  6316.9     .16       0
  6339.8     .08       0  6949.5     .12       0  7983.1     .16       0
  8470.6     .12       0  8506.3     .16       0    8782     .05       0
  9255.5     .16       0
#XS Ineff= 2 ,-1
 3454.55 3823.86  385.72 5971.59 6306.82  383.84
Permanent Ineff=
       F       F
Bank Sta=4895.1,5101.5
XS Rating Curve= 0 ,0
Exp/Cntr=0.3,0.1

Type RM Length L Ch R = 1 ,254630  ,351,351,351
BEGIN DESCRIPTION:
TEHUACANA CREEK 173.0
END DESCRIPTION:
XS GIS Cut Line= 3
      3509399.64     10626060.16      3511799.61     10623660.19
      3513999.63     10620460.16
#Sta/Elev= 30
  1638.5  400.74  1643.8  400.46    1711  398.65    1793   397.6  1856.7   395.8
  1926.4  396.66  2002.4  396.15  2059.8  395.77  3483.1  386.13  3660.8  368.82
  3915.3  367.76  4000.2  386.07  4421.9  376.85    4677  385.04    4778  385.91
  5004.3   362.4  5075.9  385.24  5153.7  384.31  5658.4  382.89  5697.3  360.99
    5700  360.49  5703.3  360.99  5762.9  369.42    5954  384.42  6737.6  383.55
  6877.8  383.86  7269.7  383.26    7646   384.6  8764.5  391.75  8915.9  393.81
#Mann= 20 ,-1 , 0
  1638.5     .16       0  1643.8     .05       0    1711     .16       0
    1793     .05       0  1856.7     .16       0  1926.4     .05       0
  2002.4     .16       0  2059.8     .05       0  3483.1     .16       0
  4421.9     .05       0    4677     .16       0  5153.7     .05       0
  5697.3     .07       0  5703.3     .05       0  5762.9     .16       0
  6737.6     .05       0  6877.8     .16       0  7269.7     .12       0
    7646     .16       0  8764.5     .05       0
#XS Ineff= 2 ,-1
    3400 4086.36  385.03 5577.27    6000  383.22
Permanent Ineff=
       F       F
Bank Sta=4778,5075.9
XS Rating Curve= 0 ,0
Exp/Cntr=0.3,0.1

Type RM Length L Ch R = 1 ,254279  ,815,815,815
BEGIN DESCRIPTION:
TEHUACANA CREEK 172.0
END DESCRIPTION:
XS GIS Cut Line= 3
      3511311.87     10625876.19      3511973.75     10623933.96
      3514435.73     10620962.23
#Sta/Elev= 30
  2759.5  390.46  3570.4  387.36  3731.7  387.01  3885.1  386.56  4118.1  385.43
  4276.6  365.38  4403.4  384.83  4472.6   381.4  4509.2   367.1  4540.7  382.51
  4875.1  385.36  4996.2  361.53  5066.6  384.69  5247.4  383.95  5621.4  383.31
  5717.4  360.79  5720.1  360.29  5723.4  360.79  5775.4  371.19    5805   372.1
  5819.3   383.4  5911.8  376.02  6838.3  382.48  6925.5  382.54  7277.3  383.99
  7862.2  385.45  8004.8  387.95  8194.8  392.46    8301   395.2  8670.5  411.83
#Mann= 15 ,-1 , 0
  2759.5     .05       0  3570.4     .16       0  3731.7     .05       0
  3885.1     .16       0  5247.4     .05       0  5717.4     .07       0
  5723.4     .05       0  5775.4     .16       0  6838.3     .12       0
  6925.5     .16       0  7277.3     .12       0  7862.2     .16       0
  8004.8     .05       0  8194.8     .16       0    8301     .05       0
Bank Sta=4875.1,5066.6
XS Rating Curve= 0 ,0
Exp/Cntr=0.3,0.1

Type RM Length L Ch R = 1 ,253464  ,941,941,941
BEGIN DESCRIPTION:
TEHUACANA CREEK 171.0
END DESCRIPTION:
XS GIS Cut Line= 2
      3511206.23     10626430.01      3514775.35     10620919.02
#Sta/Elev= 30
  2280.9   391.4  3898.5  386.81  4258.4  382.24  4279.7  377.35  4300.8  383.74
  4784.2  383.83    4893  374.69  4908.1  368.39  4929.3   373.1  4937.5   370.7
  4944.4  361.58  5001.8  359.19 5038.64  383.99    5364  381.07  5646.3  382.69
  5787.7  381.87  5823.7  359.17  5826.5  358.67  5829.7  359.17  5941.5  374.49
  5956.5   382.5  6751.9  382.19  7673.6  385.98  7847.7  391.18  8212.6  403.03
  8428.3  407.43  8479.7  413.53  8531.1  410.88  8609.6  417.16  8846.7  413.55
#Mann= 12 ,-1 , 0
  2280.9     .05       0  3898.5     .16       0    5364     .05       0
  5646.3     .16       0  5787.7     .05       0  5823.7     .07       0
  5829.7     .05       0  5956.5     .16       0  6751.9     .12       0
  7673.6     .05       0  7847.7     .16       0  8212.6     .05       0
Bank Sta=4784.2,5038.64
XS Rating Curve= 0 ,0
Exp/Cntr=0.3,0.1

Type RM Length L Ch R = 1 ,252523  ,1771,1771,1771
BEGIN DESCRIPTION:
TEHUACANA CREEK 168.0
END DESCRIPTION:
XS GIS Cut Line= 2
      3511499.19     10626733.83      3515589.08     10621624.18
#Sta/Elev= 30
  2576.7   393.5  3532.6  384.47  4579.2  381.23  4777.9  381.83  4934.8  381.27
    4970  358.49  4981.4  357.45  4984.1  356.95  4987.4  357.45  5077.2  376.67
  5133.3  375.68  5155.7  383.06  6001.3  380.63  6007.8  377.24  6029.6  362.13
  6048.1  358.65  6129.4  372.91  6207.3  375.21  6264.9  381.99  6535.5  377.34
  6663.4  381.27  6777.2  380.79  6826.8  376.14    6862   381.6  7136.4  380.75
  7185.2  380.95    7410  381.14  7820.3  389.99  8334.6  414.36  9121.6  420.82
#Mann= 11 ,-1 , 0
  2576.7     .05       0  4579.2     .16       0  4981.4     .07       0
  4987.4     .16       0  6007.8     .05       0  6048.1     .16       0
  6663.4     .12       0  7136.4     .16       0  7185.2     .12       0
    7410     .16       0  7820.3     .05       0
Bank Sta=4777.9,5155.7
XS Rating Curve= 0 ,0
Exp/Cntr=0.3,0.1

Type RM Length L Ch R = 1 ,250752  ,1257,1257,1257
BEGIN DESCRIPTION:
TEHUACANA CREEK 167.0
END DESCRIPTION:
XS GIS Cut Line= 3
      3512111.22     10627156.95      3514810.84     10624431.29
      3516285.58     10622193.17
#Sta/Elev= 30
  1627.4  403.65  2111.9  387.61  2762.5   378.8  4692.8  380.27    4905  377.31
  4951.5  355.26  4954.2  354.76  4957.5  355.26  5025.2   356.4  5039.3  367.15
  5081.8  375.32    5162  379.56  5237.3  380.34  5605.8  378.55    5775  373.58
  5811.1  379.72  5860.2  374.17  5940.6  378.77  5991.8  373.18  6099.9  379.14
  6165.4  378.99  6535.5  381.79    6650  386.11  6993.4  401.01  7081.2  403.35
  7340.9  411.65  7611.8  401.29  7644.6  395.11  7996.4  413.03    8144  418.22
#Mann= 13 ,-1 , 0
  1627.4     .05       0  4951.5     .03       0  4957.5     .05       0
    5162     .16       0  5605.8     .12       0  6099.9     .16       0
  6165.4     .12       0  6535.5     .16       0    6650     .05       0
  6993.4     .16       0  7081.2     .05       0  7611.8     .16       0
  7996.4     .05       0
Bank Sta=4692.8,5237.3
XS Rating Curve= 0 ,0
Exp/Cntr=0.3,0.1

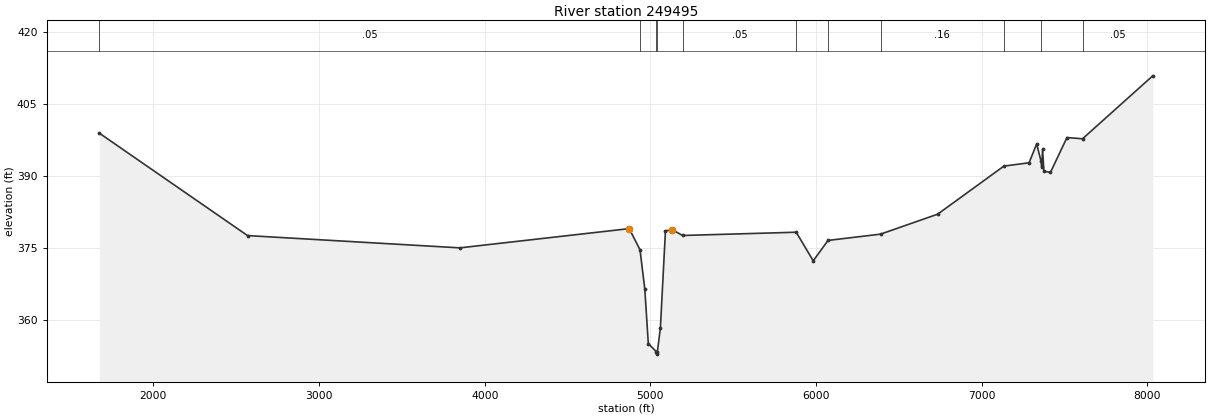
Type RM Length L Ch R = 1 ,249495  ,853,853,853
BEGIN DESCRIPTION:
TEHUACANA CREEK 166.0
END DESCRIPTION:
XS GIS Cut Line= 3
      3512441.04     10627235.12      3515444.52     10625334.07
      3516546.95     10622755.94
#Sta/Elev= 30
  1673.7  398.95  2568.3   377.6  3849.6  375.04  4872.1  379.05  4937.3  374.63
  4966.2  366.45  4987.4  355.08  5036.1  353.39  5038.8  352.89  5042.1  353.39
  5060.3  358.34  5090.8  378.59  5133.2   378.8  5194.2  377.62  5880.1   378.3
  5982.9  372.34  6072.2  376.59  6389.1   377.9  6733.9  382.06    7134  392.09
  7285.6  392.77  7331.5  396.69  7358.3  393.07  7361.8   391.9  7367.3  395.58
    7375  391.05  7414.5  390.75  7514.3  398.03  7608.4  397.78  8032.2   410.9
#Mann= 11 ,-1 , 0
  1673.7     .05       0  4937.3     .16       0  5036.1     .07       0
  5042.1     .16       0  5194.2     .05       0  5880.1     .16       0
  6072.2     .05       0  6389.1     .16       0    7134     .05       0
  7358.3     .16       0  7608.4     .05       0
Bank Sta=4872.1,5133.2
XS Rating Curve= 0 ,0
Exp/Cntr=0.3,0.1