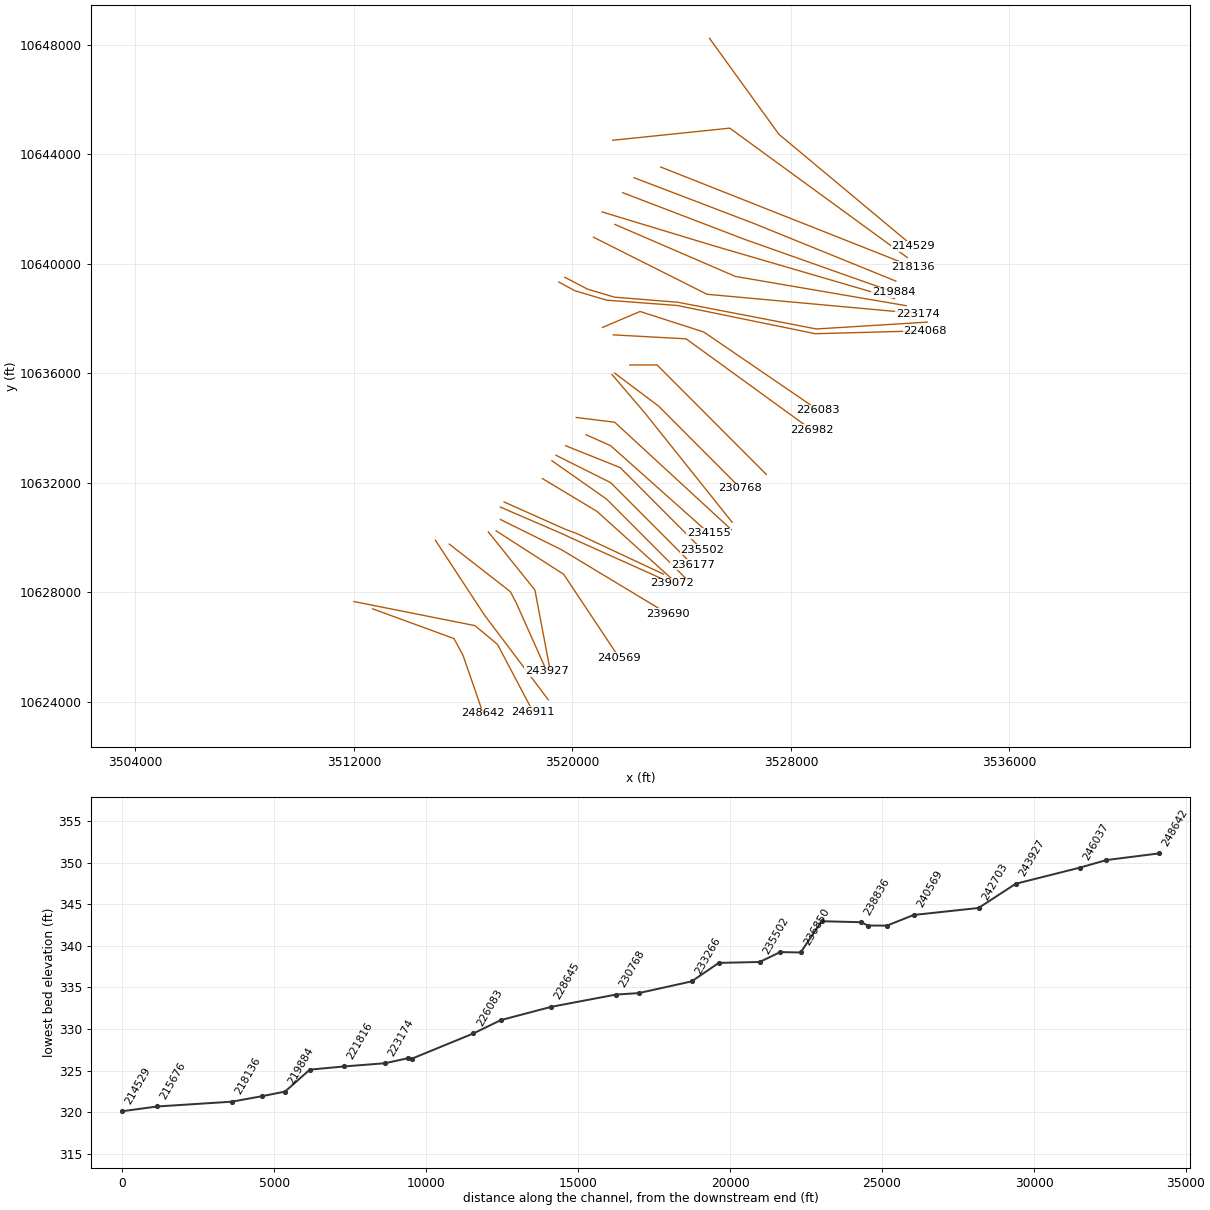
HEC-RAS study TEHUACANA CREEK.prj: TEHUACANA CREEK Base Level Engineering

--- TEHUACANA CREEK.g01 (geometry) --- (continued)

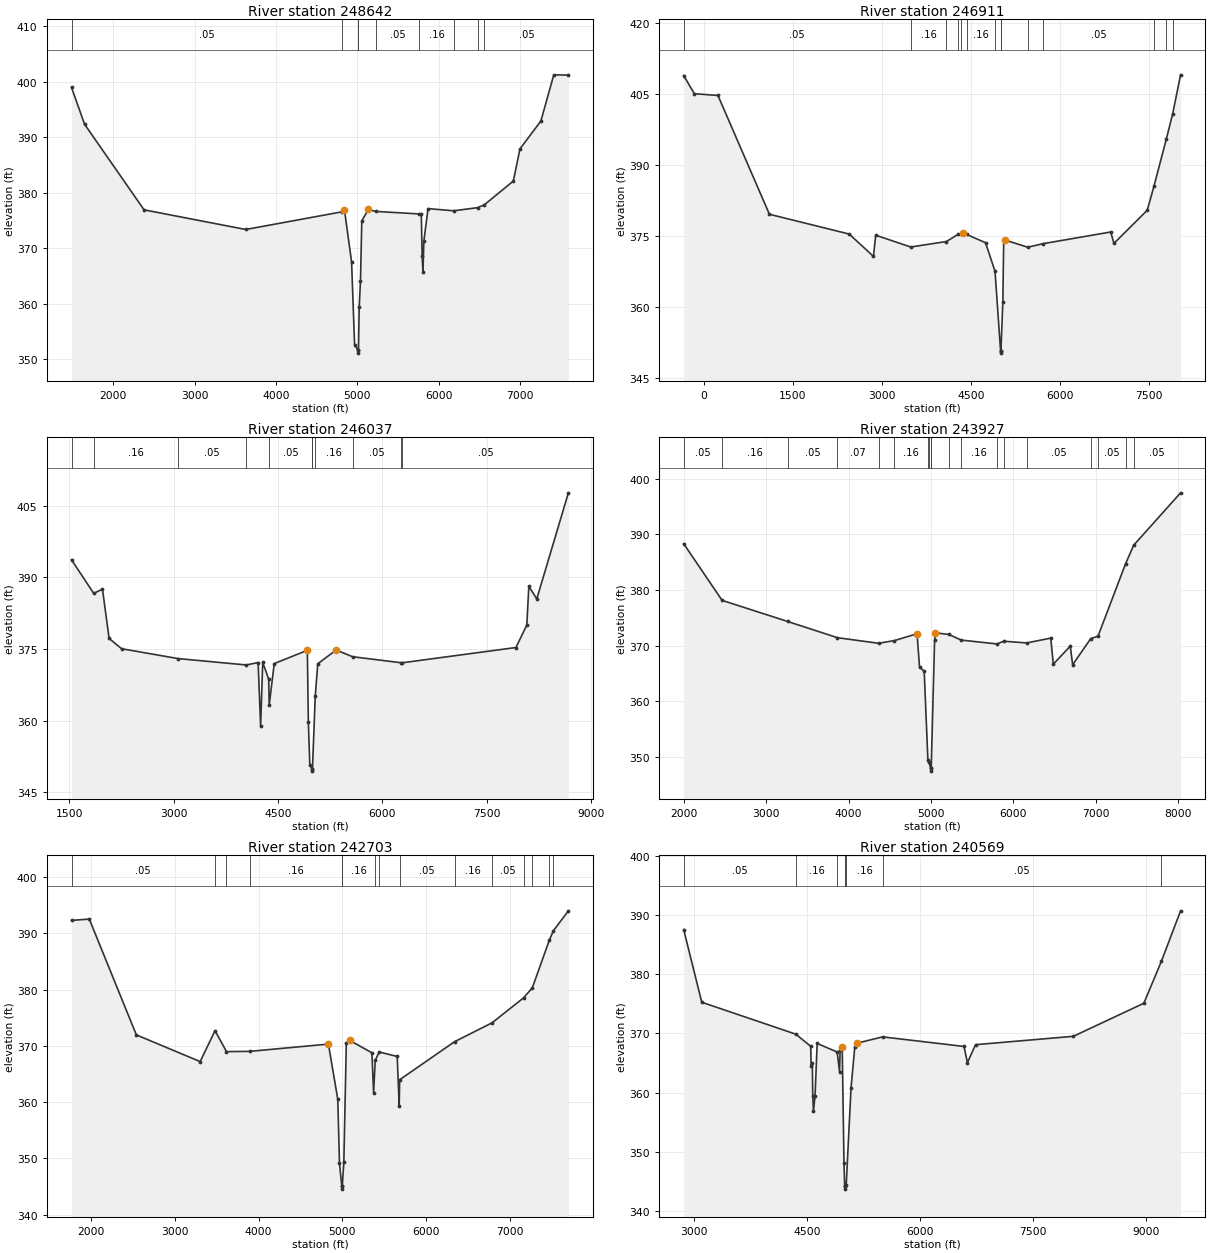
Type RM Length L Ch R = 1 ,248642  ,1731,1731,1731
BEGIN DESCRIPTION:
TEHUACANA CREEK 165.0
END DESCRIPTION:
XS GIS Cut Line= 4
      3512684.08     10627400.05      3515661.54     10626314.97
       3515991.4     10625707.33      3516729.24      10623580.6
#Sta/Elev= 30
  1484.5  398.96  1644.7  392.34    2377  376.91  3627.5  373.37  4810.4  376.55
    4841  376.96  4929.4  367.53  4966.2  352.64  5008.1   351.6  5010.9   351.1
  5014.1   351.6  5023.1   359.4  5038.7  364.09  5054.9  374.93  5136.6  376.98
  5224.7  376.63  5761.9  376.17  5786.8  376.14    5797  368.64  5807.3  365.75
  5818.2  371.26  5869.6  377.13  6184.8  376.74  6479.6   377.3  6563.4  377.83
    6919   382.1  7000.3  387.89  7257.7  392.91  7416.5  401.23    7596  401.18
#Mann= 9 ,-1 , 0
  1484.5     .05       0  4810.4     .16       0  5008.1     .07       0
  5014.1     .16       0  5224.7     .05       0  5761.9     .16       0
  6184.8     .05       0  6479.6     .16       0  6563.4     .05       0
Bank Sta=4841,5136.6
XS Rating Curve= 0 ,0
Exp/Cntr=0.3,0.1

Type RM Length L Ch R = 1 ,246911  ,874,874,874
BEGIN DESCRIPTION:
TEHUACANA CREEK 164.0
END DESCRIPTION:
XS GIS Cut Line= 4
      3512003.59     10627665.46      3516430.71     10626786.54
      3517255.36     10626102.95      3518557.46     10623639.81
#Sta/Elev= 30
  -341.3  408.87  -161.8  405.03   235.8  404.67  1102.7   379.6  2448.1  375.42
  2855.9   370.7  2893.5  375.18  3484.1  372.69  4085.3  373.85  4278.9  375.34
  4323.4  375.44  4367.2  375.75  4425.5  375.33  4743.6   373.6  4903.7  367.55
  4997.2   350.8    5000   350.3  5003.2   350.8  5035.4  361.15  5049.7  373.97
    5064  374.19  5454.4  372.65  5720.1  373.41  6852.7  375.86  6907.2  373.46
  7468.1  380.44  7582.9   385.6  7788.5  395.41  7897.2  400.83  8029.5  409.02
#Mann= 14 ,-1 , 0
  -341.3     .05       0  3484.1     .16       0  4085.3     .05       0
  4278.9     .16       0  4323.4     .05       0  4425.5     .16       0
  4903.7     .05       0  4997.2     .03       0  5003.2     .05       0
  5454.4     .16       0  5720.1     .05       0  7582.9     .16       0
  7788.5     .05       0  7897.2     .16       0
Bank Sta=4367.2,5064
XS Rating Curve= 0 ,0
Exp/Cntr=0.3,0.1

Type RM Length L Ch R = 1 ,246037  ,2110,2110,2110
BEGIN DESCRIPTION:
TEHUACANA CREEK 163.0
END DESCRIPTION:
XS GIS Cut Line= 3
      3514985.02     10629902.34       3516781.9     10627167.95
       3519115.8     10624079.22
#Sta/Elev= 30
    1532   393.7  1851.1  386.66  1977.3  387.54  2072.3  377.22  2252.5  375.05
    3067  372.98    4044  371.65  4214.9  372.15  4250.8  358.78  4280.8  372.21
  4367.1  368.65  4374.2  363.25  4446.5  371.94  4922.4  374.72  4936.9  359.69
  4957.8  350.75  4990.2  349.89  4992.9  349.39  4996.2  349.89  5035.8  365.05
  5072.2  371.89  5336.5  374.79    5572  373.38  6272.9  372.11  6288.3  372.11
  7921.3  375.31  8077.5  380.01  8106.6  388.12    8221   385.5  8675.3  407.74
#Mann= 11 ,-1 , 0
    1532     .05       0  1851.1     .16       0    3067     .05       0
    4044     .16       0  4367.1     .05       0  4990.2     .03       0
  4996.2     .05       0  5035.8     .16       0    5572     .05       0
  6272.9     .16       0  6288.3     .05       0
Bank Sta=4922.4,5336.5
XS Rating Curve= 0 ,0
Exp/Cntr=0.3,0.1

Type RM Length L Ch R = 1 ,243927  ,1224,1224,1224
BEGIN DESCRIPTION:
TEHUACANA CREEK 161.0
END DESCRIPTION:
XS GIS Cut Line= 4
      3515490.99     10629764.87      3517726.21     10628028.77
      3517932.37     10627638.15      3519060.82     10625120.83
#Sta/Elev= 30
  1998.3  388.31  2464.2  378.13  3259.6  374.34    3865  371.42  4363.6  370.42
  4554.7   370.9  4830.6  372.13  4860.9  366.11  4917.4  365.43  4962.3  349.41
  4976.2  349.03  4996.4  347.95  4999.1  347.45  5002.4  347.95  5043.4  370.93
  5053.1   372.3  5213.9  372.01  5367.8  370.99  5801.8   370.3  5883.3  370.79
    6161  370.48  6453.1  371.35  6484.4  366.67  6690.4  369.91    6719  366.57
  6939.2  371.27    7026  371.67  7361.6  384.71  7460.1  388.04  8028.9  397.45
#Mann= 19 ,-1 , 0
  1998.3     .05       0  2464.2     .16       0  3259.6     .05       0
    3865     .07       0  4363.6     .05       0  4554.7     .16       0
  4962.3     .05       0  4976.2     .16       0  4996.4     .07       0
  5002.4     .16       0  5213.9     .12       0  5367.8     .16       0
  5801.8     .05       0  5883.3     .16       0    6161     .05       0
  6939.2     .16       0    7026     .05       0  7361.6     .16       0
  7460.1     .05       0
Bank Sta=4830.6,5053.1
XS Rating Curve= 0 ,0
Exp/Cntr=0.3,0.1

Type RM Length L Ch R = 1 ,242703  ,2134,2134,2134
BEGIN DESCRIPTION:
TEHUACANA CREEK 159.0
END DESCRIPTION:
XS GIS Cut Line= 3
      3516921.08     10630209.77      3518626.81     10628087.37
      3519225.78     10624936.28
#Sta/Elev= 30
  1767.6  392.33  1979.8  392.56  2541.4  371.97  3302.9  367.22  3480.7  372.72
  3617.3  368.99  3893.7  369.04  4833.7  370.33  4945.7  360.52    4966  349.15
  4993.6  345.04  4996.3  344.54  4999.6  345.04  5018.1  349.42  5047.5   370.5
  5088.2  370.98  5352.8  368.79  5373.2  361.66  5392.7  367.43    5440  368.93
    5655  368.13  5678.6  359.34    5684  363.99  6338.7  370.75  6787.6  374.12
  7162.7  378.55  7267.7  380.34  7472.1  388.88  7519.2  390.49    7698  394.03
#Mann= 15 ,-1 , 0
  1767.6     .05       0  3480.7     .16       0  3617.3     .05       0
  3893.7     .16       0  4993.6     .07       0  4999.6     .16       0
  5392.7     .05       0    5440     .16       0    5684     .05       0
  6338.7     .16       0  6787.6     .05       0  7162.7     .16       0
  7267.7     .05       0  7472.1     .16       0  7519.2     .05       0
Bank Sta=4833.7,5088.2
XS Rating Curve= 0 ,0
Exp/Cntr=0.3,0.1

Type RM Length L Ch R = 1 ,240569  ,879,879,879
BEGIN DESCRIPTION:
Mapping XS 01223791
END DESCRIPTION:
XS GIS Cut Line= 3
      3517207.54     10630248.83       3519681.5     10628660.28
      3521712.17     10625614.28
#Sta/Elev= 30
  2859.4  387.56  3099.5  375.28  4350.1  369.88  4546.9  367.83  4552.8  364.54
    4568  364.97    4574   359.5  4583.2  356.86  4604.4  359.42  4632.6  368.32
  4898.1  366.87  4929.7  363.56  4937.3  367.14  4965.3  367.75  4988.9  348.09
    4998   344.2  5000.7   343.7    5004   344.2  5018.7  344.44  5082.7  360.84
  5131.7  367.64  5167.4  368.38  5501.3  369.43  6583.5  367.81  6628.6  365.07
  6736.8  368.11  8034.8  369.52  8972.2  375.11  9205.4  382.19  9460.3  390.73
#Mann= 8 ,-1 , 0
  2859.4     .05       0  4350.1     .16       0  4898.1     .05       0
    4998     .03       0    5004     .05       0  5018.7     .16       0
  5501.3     .05       0  9205.4     .16       0
Bank Sta=4965.3,5167.4
XS Rating Curve= 0 ,0
Exp/Cntr=0.3,0.1

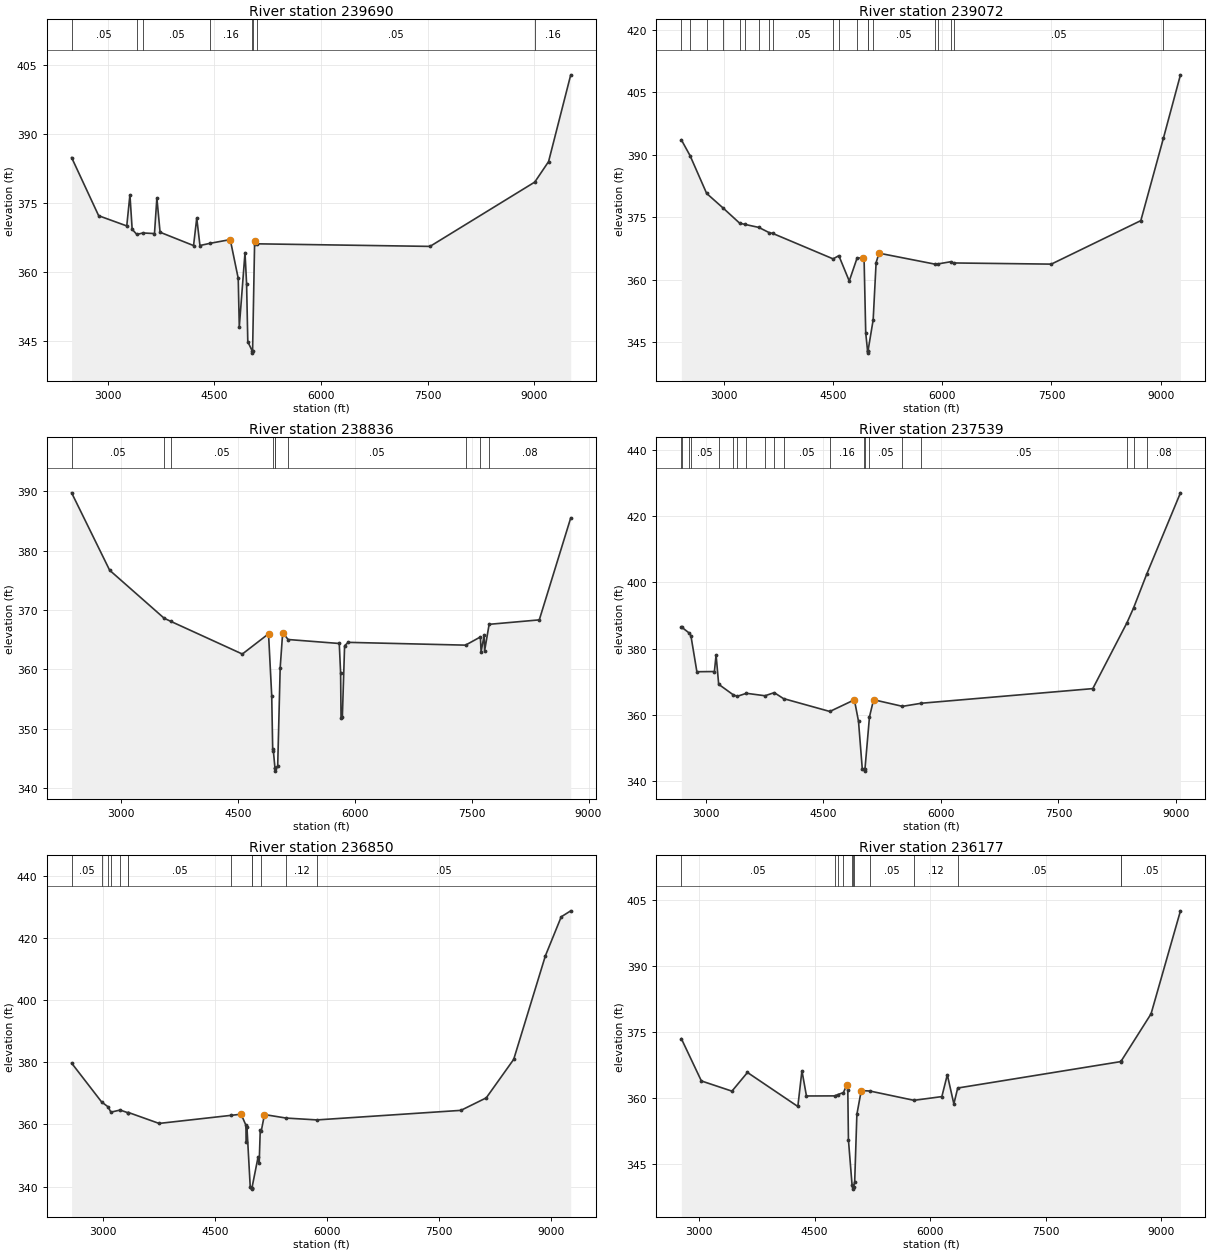
Type RM Length L Ch R = 1 ,239690  ,618,618,618
BEGIN DESCRIPTION:
TEHUACANA CREEK 158.0
END DESCRIPTION:
XS GIS Cut Line= 3
      3517363.67     10630663.85      3519599.61     10629560.19
      3523482.57     10627224.71
#Sta/Elev= 30
  2489.3  384.95  2869.9   372.3  3265.4  370.08    3310  376.86  3341.3  369.35
  3406.9  368.23    3492  368.55  3655.6  368.42  3689.2  376.17  3734.1  368.71
  4205.5  365.81  4250.4   371.8  4295.3  365.82    4441  366.31  4721.8  367.11
  4834.1  358.68    4849  348.11  4929.5  364.28  4951.9   357.5  4968.8   344.9
  5030.3  342.92  5033.1  342.42  5036.3  342.92  5064.4   366.2  5076.1  366.87
  5100.6  366.19  7533.3  365.63  9007.9  379.62    9202  384.07    9514  402.94
#Mann= 8 ,-1 , 0
  2489.3     .05       0  3406.9     .15       0    3492     .05       0
    4441     .16       0  5030.3     .07       0  5036.3     .16       0
  5100.6     .05       0  9007.9     .16       0
Bank Sta=4721.8,5076.1
XS Rating Curve= 0 ,0
Exp/Cntr=0.3,0.1

Type RM Length L Ch R = 1 ,239072  ,236,236,236
BEGIN DESCRIPTION:
TEHUACANA CREEK 157.0
END DESCRIPTION:
XS GIS Cut Line= 4
      3517357.43     10631118.91      3519625.25     10630142.33
      3519950.77     10629990.42      3523629.17     10628341.11
#Sta/Elev= 30
  2412.9  393.63  2533.5   389.8  2760.6  380.76  2987.7  377.24  3214.8  373.61
  3293.4   373.3  3477.9   372.6  3622.2  371.33    3669  371.16  4498.9  365.05
  4577.3  365.82  4720.6  359.74  4827.6  365.22  4908.9  365.32    4924  365.39
  4946.9  347.31  4972.3  342.93    4975  342.43  4978.3  342.93  5049.3  350.43
  5089.6  364.15  5129.6  366.42  5897.2  363.79  5933.8  363.82  6117.5  364.37
  6154.6  364.07  7497.4  363.79  8727.7  374.23  9039.1  394.07  9272.5  409.22
#Mann= 20 ,-1 , 0
  2412.9     .05       0  2533.5     .05       0  2760.6     .05       0
  2987.7     .05       0  3214.8     .05       0  3293.4     .08       0
  3477.9     .05       0  3622.2     .08       0    3669     .05       0
  4498.9     .08       0  4577.3     .05       0  4827.6     .05       0
  4972.3     .07       0  4978.3     .08       0  5049.3     .05       0
  5897.2     .16       0  5933.8     .05       0  6117.5     .16       0
  6154.6     .05       0  9039.1     .05       0
Bank Sta=4908.9,5129.6
XS Rating Curve= 0 ,0
Exp/Cntr=0.3,0.1

Type RM Length L Ch R = 1 ,238836  ,1297,1297,1297
BEGIN DESCRIPTION:
TEHUACANA CREEK 156.0
END DESCRIPTION:
XS GIS Cut Line= 4
      3517498.56     10631303.34      3519744.61     10630305.09
      3520178.64     10630142.33      3523335.37     10628667.02
#Sta/Elev= 30
  2366.1  389.75  2854.1   376.7  3553.4  368.61  3637.3  368.09  4557.1  362.57
  4893.4  365.98  4934.2  355.54  4946.8  346.48  4956.1  346.15  4975.9  343.33
  4978.6  342.83  4981.9  343.33  5010.9  343.72  5042.9  360.27  5074.8  366.17
  5144.8  365.02  5801.1  364.35  5818.4  359.41    5824  351.85  5840.5  351.88
  5869.7  363.97  5915.4  364.54  7421.3  364.07  7612.6  365.45  7621.1  362.94
  7661.3  365.76  7666.8  363.13  7724.7  367.58  8368.3  368.33    8772  385.53
#Mann= 10 ,-1 , 0
  2366.1     .05       0  3553.4     .08       0  3637.3     .05       0
  4956.1     .16       0  4975.9     .07       0  4981.9     .16       0
  5144.8     .05       0  7421.3     .08       0  7612.6     .05       0
  7724.7     .08       0
Bank Sta=4893.4,5074.8
XS Rating Curve= 0 ,0
Exp/Cntr=0.3,0.1

Type RM Length L Ch R = 1 ,237539  ,689,689,689
BEGIN DESCRIPTION:
TEHUACANA CREEK 155.0
END DESCRIPTION:
XS GIS Cut Line= 3
      3518899.57     10632160.21      3520899.61     10630960.19
       3523899.6     10628260.19
#Sta/Elev= 30
  2688.3   386.5  2691.9  386.48  2782.7  384.79  2810.1  383.92  2886.6  372.99
  3110.1  373.05  3131.5  378.06  3164.6   369.2  3349.5  366.03    3401  365.56
  3519.2  366.47  3755.6  365.73  3873.8  366.67  3991.9  364.87  4582.9  360.98
  4896.3   364.5  4948.8  358.02  4997.4  343.49  5024.8  343.45  5027.6  342.95
  5030.8  343.45  5088.7  359.35  5141.4  364.53    5510  362.53  5751.6  363.47
  7938.3  367.89    8374  387.79  8458.9  392.29  8625.2  402.43  9056.8  427.06
#Mann= 20 ,-1 , 0
  2688.3      .1       0  2691.9     .15       0  2782.7      .1       0
  2810.1     .05       0  3164.6     .05       0  3349.5     .08       0
    3401     .15       0  3519.2     .08       0  3755.6     .15       0
  3873.8      .1       0  3991.9     .05       0  4582.9     .16       0
  5024.8     .07       0  5030.8     .16       0  5088.7     .05       0
    5510     .12       0  5751.6     .05       0    8374     .16       0
  8458.9     .08       0  8625.2     .08       0
Bank Sta=4896.3,5141.4
XS Rating Curve= 0 ,0
Exp/Cntr=0.3,0.1

Type RM Length L Ch R = 1 ,236850  ,673,673,673
BEGIN DESCRIPTION:
TEHUACANA CREEK 154.0
END DESCRIPTION:
XS GIS Cut Line= 3
      3519249.63     10632810.17      3521249.61     10631410.19
      3524249.59     10628410.21
#Sta/Elev= 30
    2583   379.7  2984.4  367.22  3070.9  365.65  3108.6  363.93  3232.8  364.61
  3333.9  363.77  3344.6  363.82  3754.4  360.31  4723.4  362.92    4853  363.27
  4915.7   359.8  4924.5  354.22  4930.6  359.22    4975  339.83  4992.9  339.69
  4995.7  339.19  4998.9  339.69  5080.9  349.62    5095  347.69  5109.1  358.19
  5122.6  357.88  5165.7  363.16  5456.6  362.03  5868.9  361.44  7796.1  364.51
  8135.6  368.53  8503.2  380.91  8927.5   414.2  9139.6  426.73  9266.9  428.65
#Mann= 13 ,-1 , 0
    2583     .05       0  2984.4     .08       0  3070.9     .05       0
  3108.6     .08       0  3232.8     .05       0  3333.9     .08       0
  3344.6     .05       0  4723.4     .16       0  4992.9     .07       0
  4998.9     .16       0  5122.6     .05       0  5456.6     .12       0
  5868.9     .05       0
Bank Sta=4853,5165.7
XS Rating Curve= 0 ,0
Exp/Cntr=0.3,0.1

Type RM Length L Ch R = 1 ,236177  ,675,675,675
BEGIN DESCRIPTION:
TEHUACANA CREEK 153.0
END DESCRIPTION:
XS GIS Cut Line= 3
      3519399.59      10633010.2      3521399.61     10632010.19
      3524399.59     10629010.21
#Sta/Elev= 30
  2771.1  373.48  3031.1  363.85    3428  361.53  3629.2  365.78  4283.3  358.04
  4336.4  366.17  4395.1  360.43  4761.3  360.45  4801.9  360.74  4874.1   361.2
  4917.7  362.87  4931.7  361.89  4940.1  350.45    4987  340.21  5001.4  339.74
  5004.1  339.24  5007.4  339.74  5021.3  340.95  5049.6  356.24  5106.2  361.66
  5217.7  361.56  5790.7  359.44  6152.7  360.29  6223.4  365.26  6308.3  358.63
  6358.6  362.24  8474.5  368.25  8477.6   368.3    8868  379.11  9249.8  402.55
#Mann= 12 ,-1 , 0
  2771.1     .05       0  4761.3     .16       0  4801.9     .05       0
  4874.1     .12       0    4987     .16       0  5001.4     .07       0
  5007.4     .16       0  5217.7     .05       0  5790.7     .12       0
  6358.6     .05       0  8474.5      .1       0  8477.6     .05       0
Bank Sta=4917.7,5106.2
XS Rating Curve= 0 ,0
Exp/Cntr=0.3,0.1

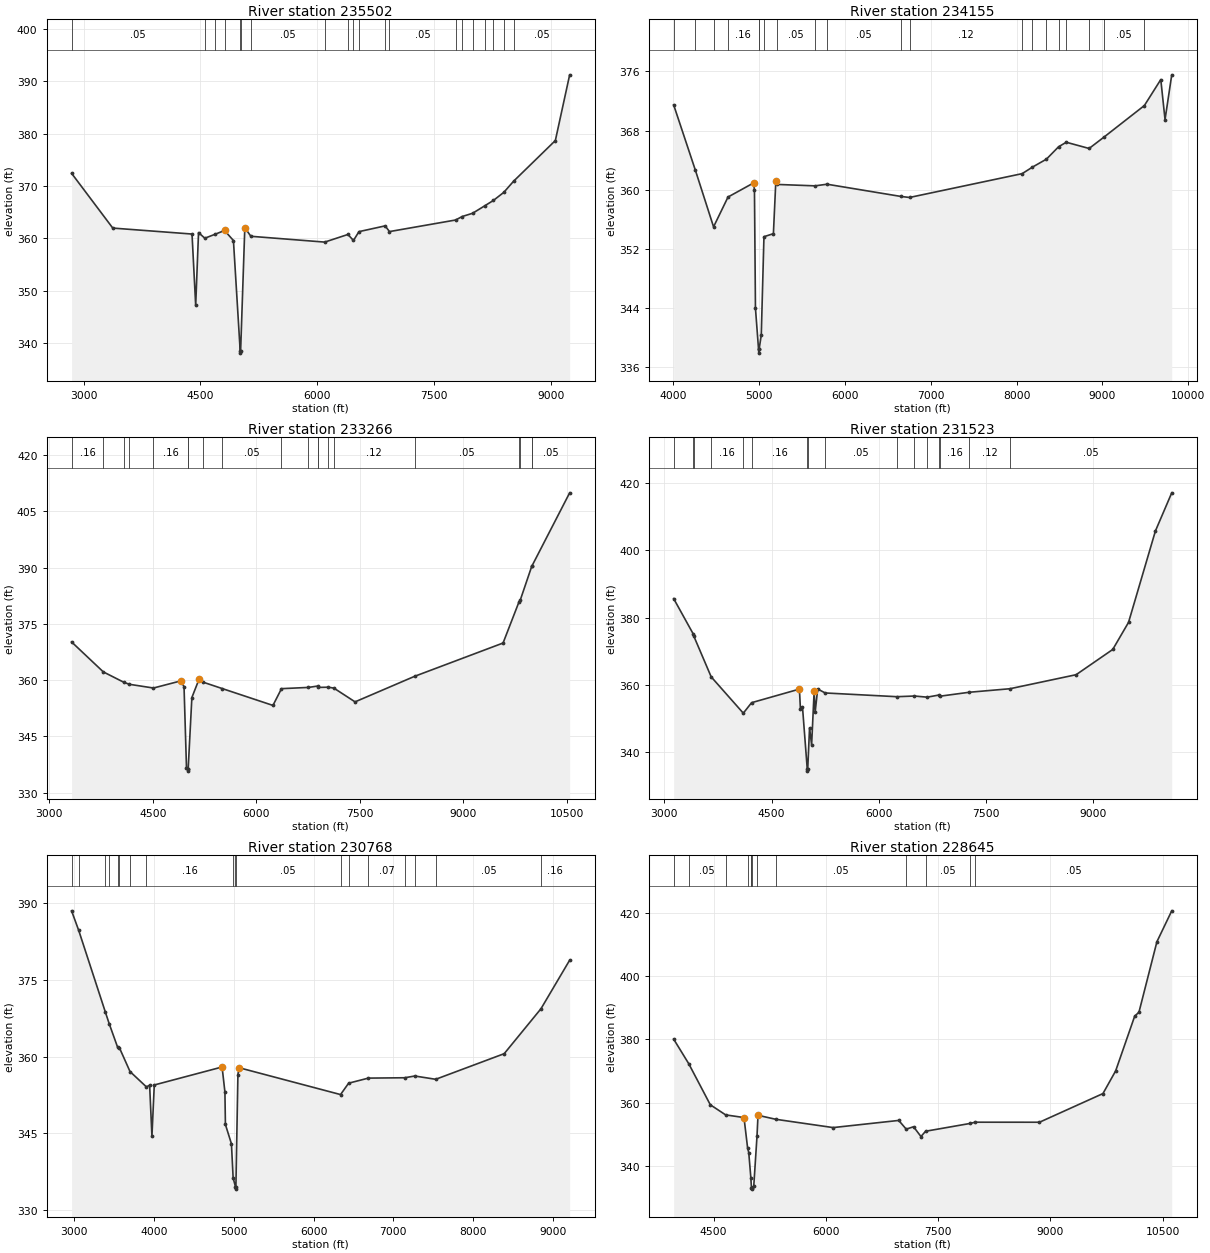
Type RM Length L Ch R = 1 ,235502  ,1347,1347,1347
BEGIN DESCRIPTION:
TEHUACANA CREEK 152.0
END DESCRIPTION:
XS GIS Cut Line= 3
      3519749.58      10633360.2      3521749.61     10632560.19
      3524749.58     10629560.21
#Sta/Elev= 30
  2846.5  372.42  3375.6  361.95  4393.4  360.81  4440.5  347.16  4476.9  361.09
    4558  360.01  4682.6  360.73  4817.5  361.52  4822.2   361.3  4925.2  359.57
  5011.7  338.55  5014.5  338.05  5017.7  338.55  5071.3  362.02  5149.2  360.38
  6097.4  359.27  6395.7  360.73  6466.7  359.58  6537.3  361.27  6873.3  362.37
  6929.3  361.28  7777.8  363.49  7863.2  364.16  7996.6  364.78  8156.4  366.24
  8263.5  367.23  8396.9  368.77    8524  370.92  9059.4  378.68  9243.2  391.24
#Mann= 20 ,-1 , 0
  2846.5     .05       0    4558     .16       0  4682.6     .16       0
  4822.2     .16       0  5011.7     .07       0  5017.7     .16       0
  5149.2     .05       0  6097.4     .12       0  6395.7     .16       0
  6466.7     .12       0  6537.3     .16       0  6873.3     .12       0
  6929.3     .05       0  7777.8     .12       0  7863.2     .16       0
  7996.6     .12       0  8156.4     .05       0  8263.5      .1       0
  8396.9      .1       0    8524     .05       0
Bank Sta=4817.5,5071.3
XS Rating Curve= 0 ,0
Exp/Cntr=0.3,0.1

Type RM Length L Ch R = 1 ,234155  ,889,889,889
BEGIN DESCRIPTION:
TEHUACANA CREEK 151.0
END DESCRIPTION:
XS GIS Cut Line= 3
      3520499.58      10633760.2      3521399.61     10633360.19
      3524999.65     10630160.16
#Sta/Elev= 30
  4006.6  371.48  4259.7  362.65  4471.4     355  4639.8  359.03  4936.8  360.93
  4947.7     360  4959.4     344  4995.6  338.44  4998.4  337.94  5001.6  338.44
  5027.1  340.37  5058.4  353.67  5168.4  354.08  5196.8  361.22  5214.9  360.73
  5653.2  360.54  5793.3  360.76  6652.9  359.11  6753.9  358.97  8066.1  362.19
  8185.6  363.07  8348.8  364.15  8490.1  365.82  8579.7  366.43  8845.7  365.59
    9015  367.09  9489.4  371.39  9680.6   374.9    9730  369.49  9808.2  375.54
#Mann= 20 ,-1 , 0
  4006.6     .05       0  4259.7     .16       0  4471.4     .12       0
  4639.8     .16       0  4995.6     .03       0  5001.6     .05       0
  5058.4     .16       0  5214.9     .05       0  5653.2     .16       0
  5793.3     .05       0  6652.9     .16       0  6753.9     .12       0
  8066.1     .12       0  8185.6     .05       0  8348.8     .12       0
  8490.1      .1       0  8579.7     .12       0  8845.7     .12       0
    9015     .05       0  9489.4     .12       0
Bank Sta=4936.8,5196.8
XS Rating Curve= 0 ,0
Exp/Cntr=0.3,0.1

Type RM Length L Ch R = 1 ,233266  ,1743,1743,1743
BEGIN DESCRIPTION:
TEHUACANA CREEK 149.0
END DESCRIPTION:
XS GIS Cut Line= 3
      3520140.84     10634391.47      3521547.09     10634217.85
      3525817.43      10630294.7
#Sta/Elev= 30
  3322.3  370.17  3782.2  362.18  4082.7  359.38  4161.2  358.87  4508.6  357.88
  4909.1   359.8  4951.6   358.2  4987.1  336.66  5005.3  336.22  5008.1  335.72
  5011.3  336.22  5065.1  355.34  5171.1  360.32  5219.8  359.49  5502.5  357.75
  6239.6  353.24  6363.5  357.71  6753.4  358.04  6885.3   358.4  6892.8  358.04
  7040.5   358.1  7122.1  357.86    7429  354.19  8290.5  360.99  9573.4  369.88
  9803.7  380.83  9820.6  381.23  9990.1  390.41  9990.5  390.38 10538.1  409.93
#Mann= 20 ,-1 , 0
  3322.3     .16       0  3782.2     .05       0  4082.7     .16       0
  4161.2     .05       0  4508.6     .16       0  5005.3     .07       0
  5011.3     .16       0  5219.8     .12       0  5502.5     .05       0
  6363.5     .16       0  6753.4     .05       0  6885.3     .16       0
  6892.8     .12       0  7040.5     .16       0  7122.1     .12       0
  8290.5     .05       0  9803.7     .08       0  9820.6     .05       0
  9990.1     .08       0  9990.5     .05       0
Bank Sta=4909.1,5171.1
XS Rating Curve= 0 ,0
Exp/Cntr=0.3,0.1

Type RM Length L Ch R = 1 ,231523  ,755,755,755
BEGIN DESCRIPTION:
TEHUACANA CREEK 148.0
END DESCRIPTION:
XS GIS Cut Line= 3
      3521449.61     10635960.19      3522649.61     10634560.19
       3525849.6      10630560.2
#Sta/Elev= 30
    3131  385.63  3407.4  375.01    3412  374.51  3655.9  362.35  4105.1  351.55
  4221.1  354.67  4889.9  358.71  4904.1  352.72  4932.7  353.47  4999.9  334.81
  5002.7  334.31  5005.9  334.81  5031.7   347.2  5060.6  342.12  5095.8  358.05
  5110.2  351.88  5145.4  358.74  5250.2  357.56  6252.6  356.45  6499.3  356.65
  6675.9  356.31  6835.4  356.92  6860.5  356.61  7265.4  357.77  7834.9  358.82
    8760  362.99  9272.2   370.5  9493.1  378.56  9869.3  405.76 10097.4  417.09
#Mann= 16 ,-1 , 0
    3131     .05       0  3407.4     .16       0    3412     .05       0
  3655.9     .16       0  4105.1     .05       0  4221.1     .16       0
  4999.9     .07       0  5005.9     .16       0  5250.2     .05       0
  6252.6     .16       0  6499.3     .05       0  6675.9     .16       0
  6835.4     .12       0  6860.5     .16       0  7265.4     .12       0
  7834.9     .05       0
Bank Sta=4889.9,5095.8
XS Rating Curve= 0 ,0
Exp/Cntr=0.3,0.1

Type RM Length L Ch R = 1 ,230768  ,2123,2123,2123
BEGIN DESCRIPTION:
TEHUACANA CREEK 147.0
END DESCRIPTION:
XS GIS Cut Line= 3
      3521549.59     10636010.21      3523149.61     10634810.19
      3526149.63     10631810.17
#Sta/Elev= 30
  2966.7  388.43  3056.4   384.6  3388.8  368.74  3438.8  366.38  3544.1   361.8
  3566.2  361.71  3699.3  357.07  3905.2  354.07  3944.9  354.41    3974  344.48
  4003.2  354.45  4853.2  357.96  4888.6  353.09  4894.9  346.74  4970.3  342.98
  4991.7   336.3  5020.3  334.63    5023  334.13  5026.3  334.63  5051.6  356.49
  5065.7  357.82  6337.7  352.58  6439.3   354.8  6686.5  355.79  7140.7  355.86
  7268.7   356.2  7530.3  355.56  8389.1  360.56  8850.4  369.34  9209.4   378.8
#Mann= 18 ,-1 , 0
  2966.7     .05       0  3056.4     .16       0  3388.8     .05       0
  3438.8     .16       0  3544.1     .05       0  3566.2     .16       0
  3699.3     .05       0  3905.2     .16       0  4991.7     .05       0
  5020.3     .03       0  5026.3     .05       0  6337.7     .12       0
  6439.3     .05       0  6686.5     .07       0  7140.7     .16       0
  7268.7     .12       0  7530.3     .05       0  8850.4     .16       0
Bank Sta=4853.2,5065.7
XS Rating Curve= 0 ,0
Exp/Cntr=0.3,0.1

Type RM Length L Ch R = 1 ,228645  ,1663,1663,1663
BEGIN DESCRIPTION:
TEHUACANA CREEK 145.0
END DESCRIPTION:
XS GIS Cut Line= 3
      3522099.59     10636310.19      3523099.61     10636310.19
      3527099.63     10632310.17
#Sta/Elev= 30
  3965.5  380.07  4165.8  372.35  4455.5  359.31  4660.5  356.12  4905.5  355.28
  4953.5  345.75  4969.1  344.21  4997.2  336.26  5004.9  333.16  5007.7  332.66
  5010.9  333.16  5036.2  333.64  5079.2   349.3  5092.8  355.99  5330.3  354.73
  6096.9  352.11  6973.7  354.37  7073.6  351.62  7171.7  352.37  7270.7  349.28
  7332.4  350.95  7925.8  353.41  7994.5  353.81  8854.6   353.8  9703.1  362.86
  9872.8  370.03 10127.4  387.34   10184  388.56 10424.4  410.86 10622.4  420.61
#Mann= 13 ,-1 , 0
  3965.5     .16       0  4165.8     .05       0  4660.5     .12       0
  4953.5     .16       0  4997.2     .12       0  5004.9     .07       0
  5010.9     .12       0  5079.2     .16       0  5330.3     .05       0
  7073.6     .12       0  7332.4     .05       0  7925.8     .08       0
  7994.5     .05       0
Bank Sta=4905.5,5092.8
XS Rating Curve= 0 ,0
Exp/Cntr=0.3,0.1

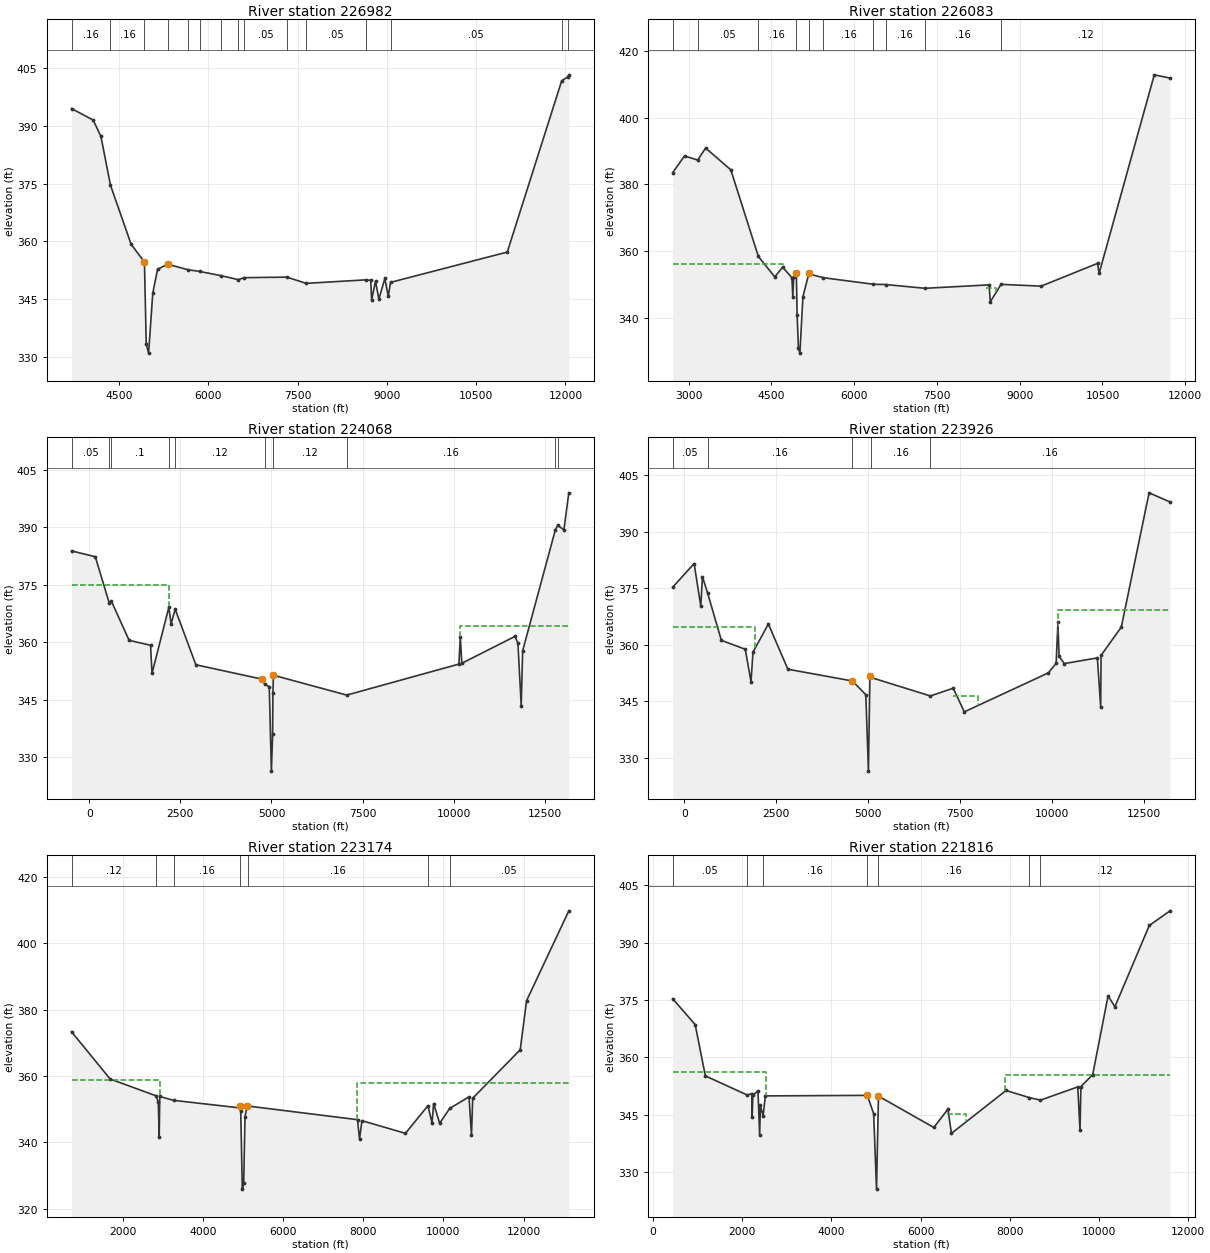
Type RM Length L Ch R = 1 ,226982  ,899,899,899
BEGIN DESCRIPTION:
TEHUACANA CREEK 144.0
END DESCRIPTION:
XS GIS Cut Line= 3
      3521496.65     10637409.91       3524163.3     10637264.08
      3528766.03     10633931.79
#Sta/Elev= 30
  3703.6  394.46  4067.1  391.47  4197.3  387.23  4357.5  374.61  4704.4  359.28
  4928.4  354.66  4958.4  333.42  4998.2  331.06  5067.8  346.57  5148.7   352.8
    5319  354.11  5657.7  352.68  5854.4  352.24  6210.3  351.16  6503.9  350.11
  6604.4  350.62  7320.3  350.76  7644.8  349.15    8645  350.05  8729.7  349.92
  8744.4  344.85  8809.4  349.72  8865.8  345.07  8966.4  350.41    9024   345.8
  9061.7   349.4 11022.7  357.26   11937  401.66 12041.5  402.68 12056.6   403.2
#Mann= 15 ,-1 , 0
  3703.6     .16       0  4357.5     .16       0  4928.4     .16       0
    5319     .12       0  5657.7     .16       0  5854.4     .16       0
  6210.3     .12       0  6503.9     .16       0  6604.4     .05       0
  7320.3     .16       0  7644.8     .05       0    8645     .16       0
  9061.7     .05       0   11937     .16       0 12041.5     .05       0
Bank Sta=4928.4,5319
XS Rating Curve= 0 ,0
Exp/Cntr=0.3,0.1

Type RM Length L Ch R = 1 ,226083  ,2015,2015,2015
BEGIN DESCRIPTION:
TEHUACANA CREEK 143.0
END DESCRIPTION:
XS GIS Cut Line= 4
      3521100.84     10637680.76       3522475.8     10638264.08
      3524809.14     10637514.08      3528995.58     10634660.63
#Sta/Elev= 30
  2713.4  383.52  2926.7   388.5    3166  387.28  3308.9  390.87  3765.7  384.34
  4264.8   358.4  4562.8  352.29  4704.7  355.21  4872.7  352.04    4889  346.22
  4904.2  352.18  4953.2  353.45  4967.3  340.88  4990.6  331.01  5017.2  329.46
  5072.3  346.35  5183.2  353.56  5188.4  353.15  5442.4  352.04  6350.5  350.08
  6569.1     350    7287  348.87  8446.4   349.9  8467.3  344.82  8661.8  350.05
  9388.9  349.52 10410.1  356.33 10439.1  353.33 11438.7  412.79 11724.3  411.81
#Mann= 10 ,-1 , 0
  2713.4     .16       0    3166     .05       0  4264.8     .16       0
  4953.2     .16       0  5188.4     .16       0  5442.4     .16       0
  6350.5     .16       0  6569.1     .16       0    7287     .16       0
  8661.8     .12       0
#XS Ineff= 2 ,-1
  2713.4 4704.45  356.07 8386.36  8562.5  349.04
Permanent Ineff=
       F       F
Bank Sta=4953.2,5183.2
XS Rating Curve= 0 ,0
Exp/Cntr=0.3,0.1

Type RM Length L Ch R = 1 ,224068  ,142,142,142
BEGIN DESCRIPTION:
TEHUACANA CREEK 142.0
END DESCRIPTION:
XS GIS Cut Line= 6
      3519504.43     10639339.61      3520079.54     10639024.93
      3521251.41     10638677.71      3523844.73     10638482.39
       3528890.3     10637451.58      3532904.88     10637560.08
#Sta/Elev= 30
  -487.8  383.82   164.7   382.3   545.5  370.29   606.3  370.71  1092.3  360.52
  1681.2  359.23  1721.6  351.92  2182.3  369.11  2245.6  364.83  2357.1  368.64
  2924.7  354.15  4739.5  350.41  4816.1  349.11  4938.9  348.43  4997.5  326.44
  5031.4  336.16    5040  346.71    5052  351.43  7064.8  346.25 10143.5  354.33
 10182.2  361.38 10223.5  354.54 11684.2  361.55 11764.3  359.74 11854.4  343.52
 11894.4  357.83 12790.8   389.3 12855.4  390.45 13025.6  389.34   13161  398.95
#Mann= 10 ,-1 , 0
  -487.8     .05       0   545.5     .08       0   606.3      .1       0
  2182.3     .16       0  2357.1     .12       0  4816.1     .16       0
    5052     .12       0  7064.8     .16       0 12790.8     .16       0
 12855.4     .05       0
#XS Ineff= 2 , 0
         2190.91  374.8710181.82          364.26
Permanent Ineff=
       F       F
Bank Sta=4739.5,5052
XS Rating Curve= 0 ,0
Exp/Cntr=0.3,0.1

Type RM Length L Ch R = 1 ,223926  ,752,752,752
BEGIN DESCRIPTION:
TEHUACANA CREEK 141.0
END DESCRIPTION:
XS GIS Cut Line= 6
      3519721.43     10639513.23      3520556.97     10639079.18
      3521544.38     10638786.21      3523855.58     10638601.75
       3528933.7     10637625.19      3532991.89     10637874.76
#Sta/Elev= 30
  -319.6  375.29   262.4  381.54   442.9  370.27   488.8  378.06     627  373.78
  1003.7  361.17    1654   358.8  1810.1  350.19  1862.7  358.02  2282.1   365.5
  2813.6  353.51  4570.7  350.39  4933.9  346.75  5004.6  326.48  5045.5  351.64
  5065.8  351.34  6691.7  346.42  7312.2  348.48    7613   342.2  9900.7  352.54
 10111.2  355.06 10161.3  365.95 10191.4  356.94 10332.5  355.01 11233.9  356.51
 11324.1  343.48 11334.1  357.18 11885.4   364.7 12640.8   400.3 13210.9  397.88
#Mann= 5 ,-1 , 0
  -319.6     .05       0     627     .16       0  4570.7     .16       0
  5065.8     .16       0  6691.7     .16       0
#XS Ineff= 3 ,-1
  -319.6 1927.27  364.61 7318.18 7972.73  346.4710172.73 13210.9  369.34
Permanent Ineff=
       F       F       F
Bank Sta=4570.7,5045.5
XS Rating Curve= 0 ,0
Exp/Cntr=0.3,0.1

Type RM Length L Ch R = 1 ,223174  ,1358,1358,1358
BEGIN DESCRIPTION:
TEHUACANA CREEK 140.0
END DESCRIPTION:
XS GIS Cut Line= 3
      3520773.32     10640976.27      3524927.01     10638892.91
      3532646.49     10638189.96
#Sta/Elev= 30
   728.2  373.31  1690.7  359.07  2836.5     354  2891.5  352.09  2913.8  341.57
    2928   353.8  3271.3  352.64  4924.4  350.36  4930.5   350.9  4946.7  349.34
  4985.6  325.88    5020  327.58  5052.8   347.7  5109.5  350.98  5125.5  350.92
  7857.9  346.81  7908.1  340.93  7968.4  346.51  9052.8  342.69  9615.2  351.04
  9715.6  345.81  9755.7  351.65  9906.4  345.72 10155.4   350.2 10638.6  353.69
 10699.6  342.12 10729.7  353.27 11914.6  367.88 12073.3  382.68 13126.5  409.75
#Mann= 7 ,-1 , 0
   728.2     .12       0  2836.5     .16       0  3271.3     .16       0
  4924.4     .16       0  5125.5     .16       0  9615.2     .16       0
 10155.4     .05       0
#XS Ineff= 2 , 0
          2928.9  358.67 7843.18           357.8
Permanent Ineff=
       F       F
Bank Sta=4930.5,5109.5
XS Rating Curve= 0 ,0
Exp/Cntr=0.3,0.1

Type RM Length L Ch R = 1 ,221816  ,1116,1116,1116
BEGIN DESCRIPTION:
TEHUACANA CREEK 139.0
END DESCRIPTION:
XS GIS Cut Line= 3
      3521554.59     10641445.01      3525968.68     10639543.95
      3532218.68     10638476.25
#Sta/Elev= 30
   444.5  375.32   947.5  368.57  1175.6  355.14  2115.7  350.12  2216.5  350.51
  2224.7  344.26    2240  350.04  2355.4  351.25  2392.1  339.74  2409.8  347.39
  2469.5  344.62  2520.6   349.9  4805.2  350.04  4948.1  345.24  5011.8  325.49
  5055.6  349.85  6296.4  341.63  6612.5  346.42  6692.1  340.09    7915  351.32
  8433.4  349.47  8686.7  348.79  9523.2  352.26  9573.2  340.95  9593.5  352.34
  9857.3  355.46 10202.2  376.09 10354.9  373.25 11126.4  394.53 11591.1  398.36
#Mann= 7 ,-1 , 0
   444.5     .05       0  2115.7     .16       0  2469.5     .16       0
  4805.2     .16       0  5055.6     .16       0  8433.4     .16       0
  8686.7     .12       0
#XS Ineff= 3 ,-1
   444.5 2529.55  356.25 6593.18 7022.73  345.23 7902.27 11591.1  355.34
Permanent Ineff=
       F       F       F
Bank Sta=4805.2,5055.6
XS Rating Curve= 0 ,0
Exp/Cntr=0.3,0.1

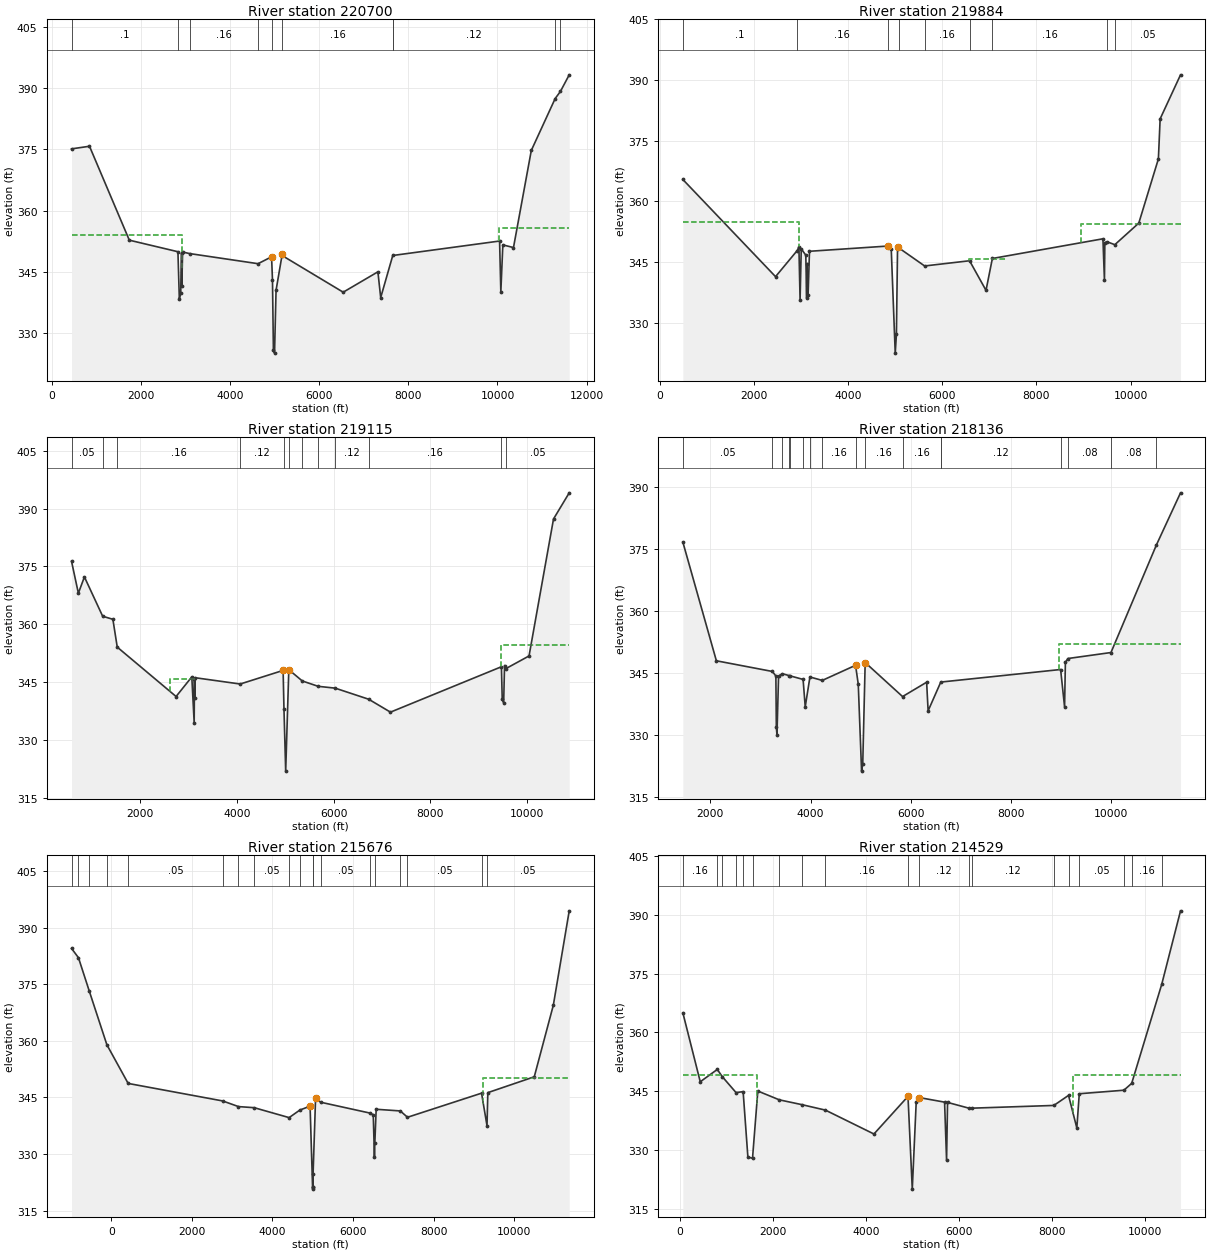
Type RM Length L Ch R = 1 ,220700  ,816,816,816
BEGIN DESCRIPTION:
TEHUACANA CREEK 138.0
END DESCRIPTION:
XS GIS Cut Line= 3
       3521085.9     10641900.72      3525174.41     10640663.75
      3531788.97     10638736.67
#Sta/Elev= 30
   448.1  375.13   850.6  375.77  1743.6  352.77  2833.9  349.94  2865.4  338.38
  2896.7  339.86  2915.7  349.61  2920.9  341.45  2938.5  349.87  3095.2  349.49
    4631  347.01  4933.8   348.7  4954.2  343.04    4975  325.91  5000.5  325.11
  5034.3  340.48  5172.9  349.36  5178.7  348.96  6540.2  340.03  7318.6  345.02
  7381.1  338.71  7651.9  349.02 10047.5  352.56 10075.4  340.14 10120.4  351.62
   10359  350.96 10758.7  374.74 11293.9  387.45 11412.2   389.2 11609.2  393.26
#Mann= 10 ,-1 , 0
   448.1      .1       0  2833.9     .16       0  3095.2     .16       0
    4631     .16       0  4933.8     .16       0  5178.7     .16       0
  7651.9     .16       0  7651.9     .12       0 11293.9      .1       0
 11412.2     .05       0
#XS Ineff= 2 , 0
         2918.18  353.9410036.36          355.64
Permanent Ineff=
       F       F
Bank Sta=4933.8,5172.9
XS Rating Curve= 0 ,0
Exp/Cntr=0.3,0.1

Type RM Length L Ch R = 1 ,219884  ,769,769,769
BEGIN DESCRIPTION:
TEHUACANA CREEK 137.0
END DESCRIPTION:
XS GIS Cut Line= 3
      3521841.09     10642603.84      3526307.22     10640898.12
      3531762.91     10638971.05
#Sta/Elev= 30
   491.8   365.4  2459.8  341.38  2920.1  347.84    2956   348.7  2980.8   335.6
  3005.5  348.25  3102.1   346.7  3120.4  336.08  3125.8  344.45  3150.5  336.77
  3180.5  347.65    4837  348.94  4916.5  348.15  5001.1  322.47  5026.1  327.08
  5050.3  348.59  5080.8  348.46  5625.1  344.02  6579.3  345.31  6928.5  337.99
  7063.4  345.87  9411.2  350.74  9443.1  340.46  9451.6  349.81  9504.3  349.98
  9663.4  349.28 10172.5  354.62 10588.5  370.49 10625.7   380.4 11058.6  391.28
#Mann= 9 ,-1 , 0
   491.8      .1       0  2920.1     .16       0    4837     .16       0
  5080.8     .16       0  5625.1     .16       0  6579.3     .16       0
  7063.4     .16       0  9504.3     .16       0  9663.4     .05       0
#XS Ineff= 3 ,-1
   491.8 2952.27  354.94 6565.91    7350  345.63 8945.45 11058.6  354.34
Permanent Ineff=
       F       F       F
Bank Sta=4837,5050.3
XS Rating Curve= 0 ,0
Exp/Cntr=0.3,0.1

Type RM Length L Ch R = 1 ,219115  ,979,979,979
BEGIN DESCRIPTION:
TEHUACANA CREEK 136.0
END DESCRIPTION:
XS GIS Cut Line= 3
      3522257.71     10643150.74      3526632.74     10641484.06
      3531840.42     10639374.95
#Sta/Elev= 30
   575.1  376.32   716.2  368.07   841.4  372.29  1219.2  362.09  1430.6   361.3
  1520.9  354.08  2738.7  341.27  3063.9  346.36  3113.3  334.46  3118.7   345.7
  3124.1  341.01  3134.7  346.14  4065.7  344.51  4953.9  348.04  4971.3   338.1
  5007.1  321.91  5071.6  348.23  5350.6   345.3  5679.8  343.91    6031  343.44
  6725.2  340.56  7175.6  337.21    9472  348.99  9488.8  340.58  9518.3  339.65
  9536.7  349.31  9563.5   348.5 10043.7  351.79 10550.3  387.33 10875.4  394.11
#Mann= 12 ,-1 , 0
   575.1     .05       0  1219.2     .05       0  1520.9     .16       0
  4065.7     .12       0  4971.3     .16       0  5071.6     .16       0
  5350.6     .16       0  5679.8     .16       0    6031     .12       0
  6725.2     .16       0    9472     .16       0  9563.5     .05       0
#XS Ineff= 2 ,-1
 2618.18 3177.27  345.83 9470.45 10875.4  354.64
Permanent Ineff=
       F       F
Bank Sta=4953.9,5071.6
XS Rating Curve= 0 ,0
Exp/Cntr=0.3,0.1

Type RM Length L Ch R = 1 ,218136  ,2460,2460,2460
BEGIN DESCRIPTION:
TEHUACANA CREEK 133.0
END DESCRIPTION:
XS GIS Cut Line= 2
       3523234.3     10643541.35      3532465.32     10639895.82
#Sta/Elev= 30
  1453.2   376.7  2121.7  347.97  3237.8  345.39  3308.2  344.29  3317.4  331.94
  3329.7  330.05  3361.9  344.27  3436.9  344.84  3577.9  344.37  3598.4   344.3
    3851  343.46  3893.6  336.82  3987.4  344.05  4233.4  343.22  4897.2  346.88
  4951.3  342.29  5017.4  321.26  5040.5  322.98  5089.2  347.55  5834.8  339.31
  6314.6  342.78  6344.3  335.86  6596.9  342.82  8986.6  345.86  9065.6  336.82
  9081.8   347.6  9132.4  348.52  9990.8  349.97 10898.4  376.05   11378  388.63
#Mann= 17 ,-1 , 0
  1453.2     .05       0  3237.8     .16       0  3436.9     .08       0
  3577.9     .16       0  3598.4     .08       0    3851     .16       0
  3987.4     .08       0  4233.4     .16       0  4897.2     .12       0
  5089.2     .16       0  5834.8     .16       0  6596.9     .16       0
  6596.9     .12       0  8986.6     .16       0  9132.4     .08       0
  9990.8     .08       0 10898.4     .05       0
#XS Ineff= 2 , 0
                         8952.27          351.98
Permanent Ineff=
       F       F
Bank Sta=4897.2,5089.2
XS Rating Curve= 0 ,0
Exp/Cntr=0.3,0.1

Type RM Length L Ch R = 1 ,215676  ,1147,1147,1147
BEGIN DESCRIPTION:
TEHUACANA CREEK 131.0
END DESCRIPTION:
XS GIS Cut Line= 3
      3521477.14     10644519.47      3525761.01     10644962.18
      3532262.57     10640232.49
#Sta/Elev= 30
    -984  384.49  -812.9  382.04  -545.1  373.21  -107.1  358.94   420.4   348.7
  2764.6  344.06  3157.7  342.56  3547.1  342.27  4413.7  339.64  4679.5  341.64
  4933.6  342.68  4995.5  321.18  4998.3  320.68  5001.5  321.18  5008.1  324.73
  5069.6  344.71  5199.3  343.71  6416.2  340.85  6500.8   340.4  6530.2  329.29
  6539.5  332.78  6573.2  341.85    7172  341.41  7350.3  339.73  9187.7  346.12
  9322.8   337.5  9343.3  346.26 10495.3  350.46 10968.2  369.43 11362.6  394.46
#Mann= 20 ,-1 , 0
    -984     .05       0  -812.9     .16       0  -545.1     .05       0
  -107.1     .16       0   420.4     .05       0  2764.6     .16       0
  3157.7     .05       0  3547.1     .05       0  4413.7     .16       0
  4679.5     .05       0  4995.5     .07       0  5001.5     .16       0
  5008.1     .12       0  5199.3     .05       0  6416.2     .16       0
  6539.5     .05       0    7172     .16       0  7350.3     .05       0
  9187.7     .16       0  9322.8     .05       0
#XS Ineff= 2 , 0
                         9231.82          350.04
Permanent Ineff=
       F       F
Bank Sta=4933.6,5069.6
XS Rating Curve= 0 ,0
Exp/Cntr=0.3,0.1

Type RM Length L Ch R = 1 ,214529  ,1008,1008,1008
BEGIN DESCRIPTION:
TEHUACANA CREEK 130.0
END DESCRIPTION:
XS GIS Cut Line= 3
      3525018.79     10648243.47      3527557.88     10644740.82
       3532465.7     10640653.14
#Sta/Elev= 30
    58.3  365.01   432.9  347.45     800  350.59   904.2  348.79  1204.2  344.68
  1355.8  344.94    1458  328.32  1557.8  327.95    1672  345.09  2133.9  342.85
  2618.1  341.63  3127.2  340.23  4171.7  334.15  4904.8  343.73    4997  320.11
  5081.9  342.34  5145.6  343.43  5692.4  342.26  5735.3  327.44  5756.2  342.19
  6211.7  340.74  6290.4  340.73  8043.9  341.42  8360.7  343.98  8539.4  335.68
  8591.8   344.4  9552.6   345.3    9720  347.04 10367.1  372.28 10771.6  390.98
#Mann= 19 ,-1 , 0
    58.3     .16       0     800     .12       0   904.2     .05       0
  1204.2     .16       0  1355.8     .12       0  1557.8     .16       0
  2133.9     .12       0  2618.1     .16       0  3127.2     .16       0
  4904.8     .16       0  5145.6     .12       0  6211.7     .16       0
  6290.4     .12       0  8043.9     .16       0  8360.7     .12       0
  8591.8     .05       0  9552.6     .16       0    9720     .16       0
 10367.1     .05       0
#XS Ineff= 2 , 0
            1650  349.24 8461.36          349.24
Permanent Ineff=
       F       F
Bank Sta=4904.8,5145.6
XS Rating Curve= 0 ,0
Exp/Cntr=0.3,0.1