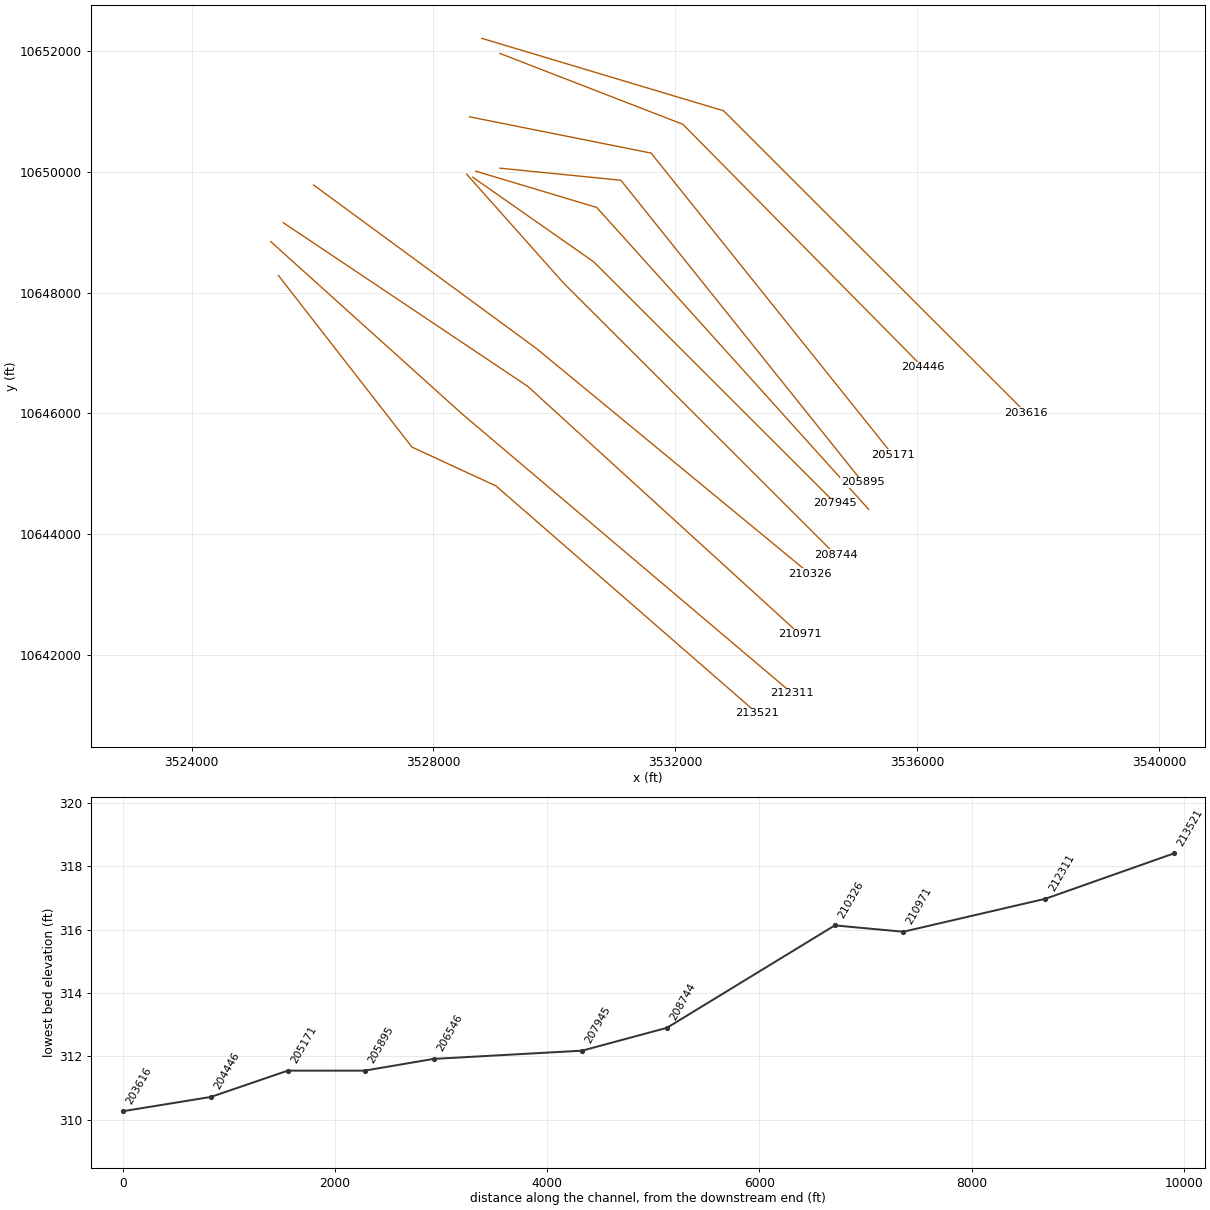
HEC-RAS study TEHUACANA CREEK.prj: TEHUACANA CREEK Base Level Engineering

--- TEHUACANA CREEK.g01 (geometry) --- (continued)

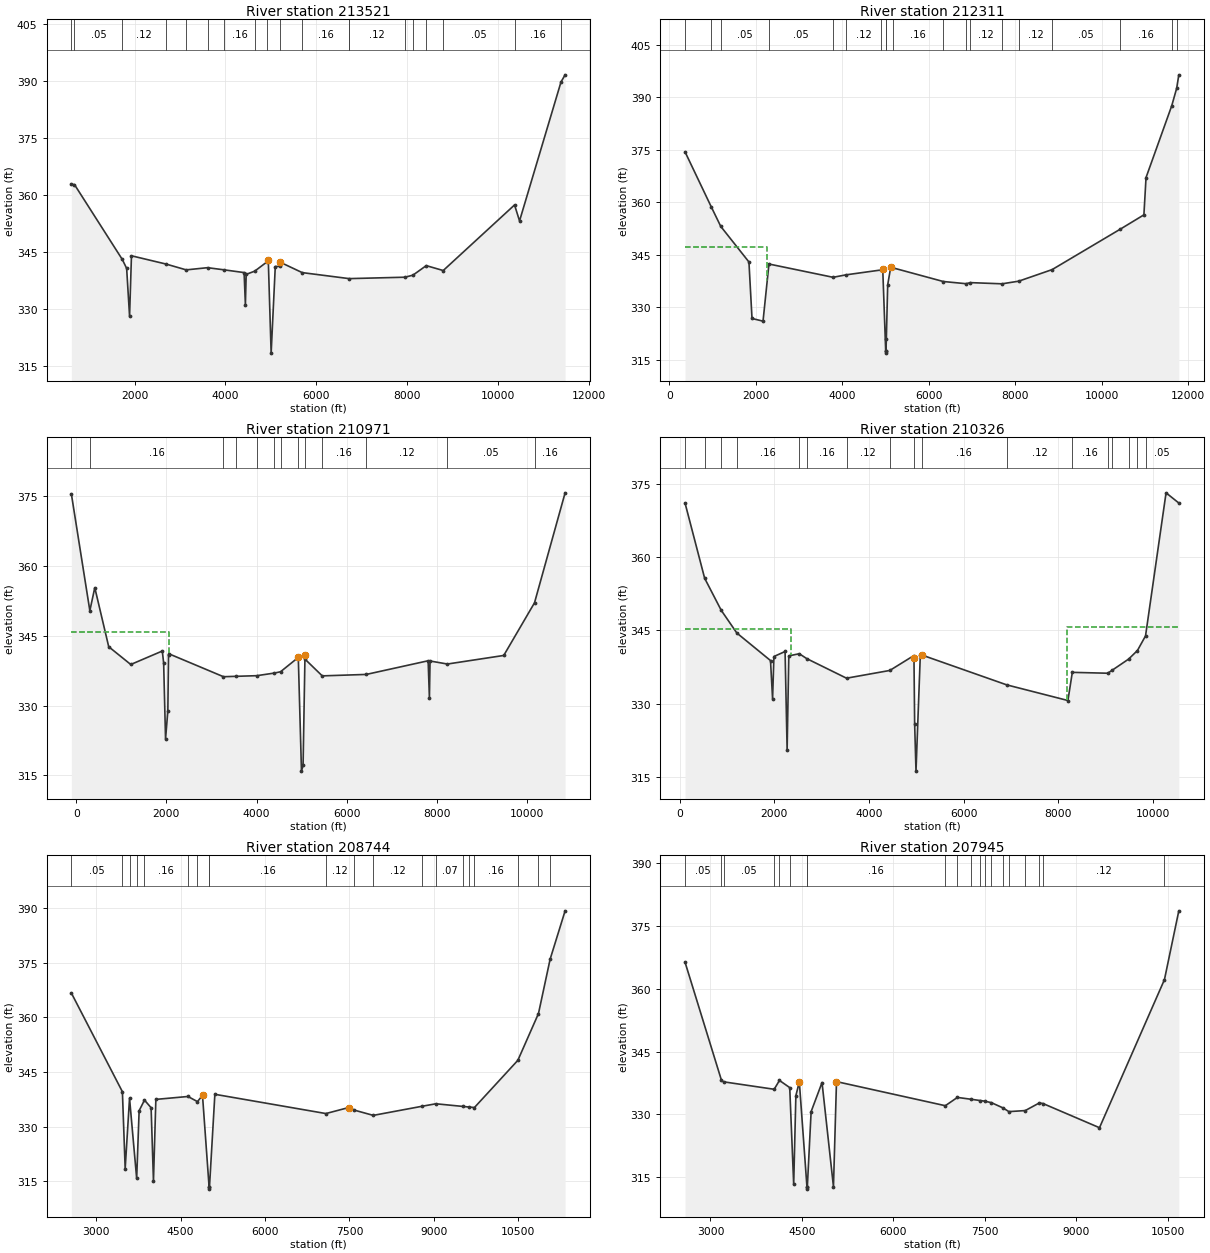
Type RM Length L Ch R = 1 ,213521  ,1210,1210,1210
BEGIN DESCRIPTION:
TEHUACANA CREEK 129.0
END DESCRIPTION:
XS GIS Cut Line= 4
      3525435.48      10648282.5      3527644.51     10645440.83
       3529033.4     10644798.47      3533355.49     10641031.83
#Sta/Elev= 30
   610.4  362.84   679.2  362.78  1731.3  343.06    1827  340.71  1891.2  328.12
  1932.8  344.03  2695.3  341.85  3137.2  340.32  3605.9   340.9  3972.6  340.33
  4410.9  339.61  4439.3  331.14  4456.8  339.14  4644.9  339.99  4920.4  342.48
  4942.9  342.89  5005.9   318.4  5096.7   341.2  5195.1  341.26  5200.6  342.36
  5689.6   339.6    6721  338.02  7949.9  338.39  8125.1  338.93  8418.3  341.44
  8791.5  340.15 10360.8  357.42 10470.4  353.21   11383  389.81   11473  391.68
#Mann= 19 ,-1 , 0
   610.4     .16       0   679.2     .05       0  1731.3     .12       0
  2695.3     .16       0  3137.2     .12       0  3605.9     .12       0
  3972.6     .16       0  4644.9     .12       0  4920.4     .16       0
  5195.1     .12       0  5689.6     .16       0    6721     .16       0
    6721     .12       0  7949.9     .05       0  8125.1     .16       0
  8418.3     .12       0  8791.5     .05       0 10360.8     .16       0
   11383     .05       0
Bank Sta=4942.9,5200.6
XS Rating Curve= 0 ,0
Exp/Cntr=0.3,0.1

Type RM Length L Ch R = 1 ,212311  ,1340,1340,1340
BEGIN DESCRIPTION:
TEHUACANA CREEK 128.0
END DESCRIPTION:
XS GIS Cut Line= 3
      3525307.71     10648844.33      3528474.37     10645990.17
       3533932.7     10641365.17
#Sta/Elev= 30
   364.6   374.4     969  358.75  1189.7  353.14  1841.7  342.98  1912.7  326.86
  2167.5  326.09  2304.4   342.4  3787.5  338.61  4086.2  339.31  4902.7  340.71
    4936   340.9  5004.4  317.47  5007.1  316.97  5010.4  317.47  5019.1  321.09
  5050.2  336.45  5120.5  341.51    5164  341.33  6334.6  337.41  6863.9  336.78
  6962.8  337.09  7693.5  336.75  8078.9   337.5  8853.1  340.81 10428.9  352.35
 10974.7  356.43 11024.1  367.08 11618.3  387.56 11732.9  392.58   11782  396.39
#Mann= 20 ,-1 , 0
   364.6     .16       0     969     .05       0  1189.7     .05       0
  2304.4     .05       0  3787.5     .16       0  4086.2     .12       0
  4902.7     .16       0  5004.4     .07       0  5010.4     .12       0
  5019.1     .16       0    5164     .16       0  6334.6     .16       0
  6863.9     .16       0  6962.8     .12       0  7693.5     .16       0
  8078.9     .12       0  8853.1     .05       0 10428.9     .16       0
 11618.3     .05       0 11732.9     .16       0
#XS Ineff= 2 , 0
         2263.64  347.31
Permanent Ineff=
       F       F
Bank Sta=4936,5120.5
XS Rating Curve= 0 ,0
Exp/Cntr=0.3,0.1

Type RM Length L Ch R = 1 ,210971  ,645,645,645
BEGIN DESCRIPTION:
TEHUACANA CREEK 127.0
END DESCRIPTION:
XS GIS Cut Line= 3
      3525516.02     10649156.84       3529557.7      10646448.5
      3534057.25     10642344.75
#Sta/Elev= 30
  -109.6   375.4   300.7  350.34   410.3  355.28   719.5  342.61  1208.8   338.8
  1908.2  341.69  1938.2  339.12  1980.2  322.84  2031.2  328.84  2046.2  340.86
  2061.2  341.07  3265.2  336.18  3532.5  336.26  4004.6   336.4  4392.6  336.96
  4531.2  337.24  4925.6  340.32  4996.3  315.93  5031.7  317.15  5074.2  340.78
  5081.6  339.88  5456.6  336.36  6433.6  336.67  7806.5   339.6  7834.8  331.63
    7849  339.55    8234   338.9    9484  340.74 10166.4  352.03 10845.5  375.62
#Mann= 13 ,-1 , 0
  -109.6     .05       0   300.7     .16       0  3265.2      .1       0
  3532.5     .16       0  4004.6     .12       0  4392.6     .16       0
  4531.2     .12       0  4925.6     .16       0  5081.6     .16       0
  5456.6     .16       0  6433.6     .12       0    8234     .05       0
 10166.4     .16       0
#XS Ineff= 2 , 0
         2056.82  345.74
Permanent Ineff=
       F       F
Bank Sta=4925.6,5074.2
XS Rating Curve= 0 ,0
Exp/Cntr=0.3,0.1

Type RM Length L Ch R = 1 ,210326  ,1582,1582,1582
BEGIN DESCRIPTION:
TEHUACANA CREEK 126.0
END DESCRIPTION:
XS GIS Cut Line= 3
      3526016.05     10649781.82      3529703.54      10647073.5
      3534223.88     10643344.74
#Sta/Elev= 30
   111.4  371.13   525.3  355.71   875.9  349.13  1205.9  344.47  1917.2  338.82
  1961.1  330.95  1989.3  339.65  2225.1  340.68  2268.3  320.54  2303.8  339.78
  2525.6  340.22  2682.8  339.22  3523.9   335.2  4438.3  336.79  4941.3  339.81
  4949.2  339.38  4963.5  325.86    4992  316.13  5083.4  340.01    5112  339.97
  6910.1  333.83  8202.6  330.62  8295.7   336.4    9044  336.22  9135.7  336.82
  9485.2  339.12  9671.7  340.88    9843  343.88 10276.8  373.24 10546.4  371.15
#Mann= 17 ,-1 , 0
   111.4     .05       0   525.3     .16       0   875.9     .05       0
  1205.9     .16       0  2525.6     .12       0  2682.8     .16       0
  3523.9     .12       0  4438.3     .16       0  4941.3     .12       0
    5112     .16       0  6910.1     .12       0  8295.7     .16       0
    9044     .05       0  9135.7     .16       0  9485.2     .05       0
  9671.7     .16       0    9843     .05       0
#XS Ineff= 2 , 0
         2352.27  345.31    8175          345.74
Permanent Ineff=
       F       F
Bank Sta=4949.2,5112
XS Rating Curve= 0 ,0
Exp/Cntr=0.3,0.1

Type RM Length L Ch R = 1 ,208744  ,799,799,799
BEGIN DESCRIPTION:
TEHUACANA CREEK 124.0
END DESCRIPTION:
XS GIS Cut Line= 3
      3528549.63     10649960.17      3530149.61     10648160.19
      3534649.64     10643660.16
#Sta/Elev= 30
  2558.5  366.67  3465.5   339.6  3514.7  318.51  3592.2  337.81    3719  315.82
  3762.6   334.4  3857.7  337.31  3975.5  335.21  4017.3  315.08  4059.9   337.5
  4630.3   338.3  4798.7  336.89  4888.6   338.6  5006.2   313.4    5009   312.9
  5012.2   313.4  5108.2   338.9  7080.9  333.62  7484.1  335.26    7574  334.61
  7922.5  333.12  8793.7  335.63  9034.6   336.3  9523.4  335.56  9617.4  335.42
  9719.6  335.27 10491.5  348.22 10857.7  361.04 11064.6  375.94 11330.8   389.2
#Mann= 20 ,-1 , 0
  2558.5     .05       0  3465.5     .16       0  3592.2     .12       0
    3719     .16       0  3857.7     .16       0  4630.3     .12       0
  4798.7     .16       0  5006.2     .07       0  5012.2     .16       0
  7080.9     .12       0    7574     .16       0  7922.5     .12       0
  8793.7     .07       0  9034.6     .07       0  9523.4     .07       0
  9617.4     .05       0  9719.6     .16       0 10491.5     .05       0
 10857.7     .16       0 11064.6     .05       0
Bank Sta=4888.6,7484.1
XS Rating Curve= 0 ,0
Exp/Cntr=0.3,0.1

Type RM Length L Ch R = 1 ,207945  ,1399,1399,1399
BEGIN DESCRIPTION:
TEHUACANA CREEK 123.0
END DESCRIPTION:
XS GIS Cut Line= 3
      3528649.64     10649910.17      3530649.61     10648510.19
      3534649.59     10644510.21
#Sta/Elev= 30
    2584   366.3    3180  338.19  3215.1  337.78  4045.5     336  4132.2  338.11
  4300.6   336.4  4365.7  313.31  4401.4  334.48  4458.1  337.77  4583.3  312.68
    4586  312.18  4589.3  312.68  4651.7  330.68  4830.4  337.61  5017.9  312.77
  5067.7  337.83  6852.6  332.08  7050.9  334.06    7268  333.63  7421.4  333.32
  7496.4  333.17  7608.1  332.81  7799.1  331.55  7895.1  330.67  8163.5  330.92
  8394.2  332.74    8454   332.6    9381  326.83 10446.3  362.15 10682.1  378.57
#Mann= 20 ,-1 , 0
    2584     .05       0    3180     .16       0  3215.1     .05       0
  4045.5     .16       0  4132.2     .12       0  4300.6     .16       0
  4583.3     .07       0  4589.3     .16       0  6852.6     .12       0
  7050.9     .16       0    7268      .1       0  7421.4     .05       0
  7496.4     .16       0  7608.1     .05       0  7799.1     .16       0
  7895.1     .05       0  8163.5     .12       0  8394.2     .07       0
    8454     .12       0 10446.3     .16       0
Bank Sta=4458.1,5067.7
XS Rating Curve= 0 ,0
Exp/Cntr=0.3,0.1

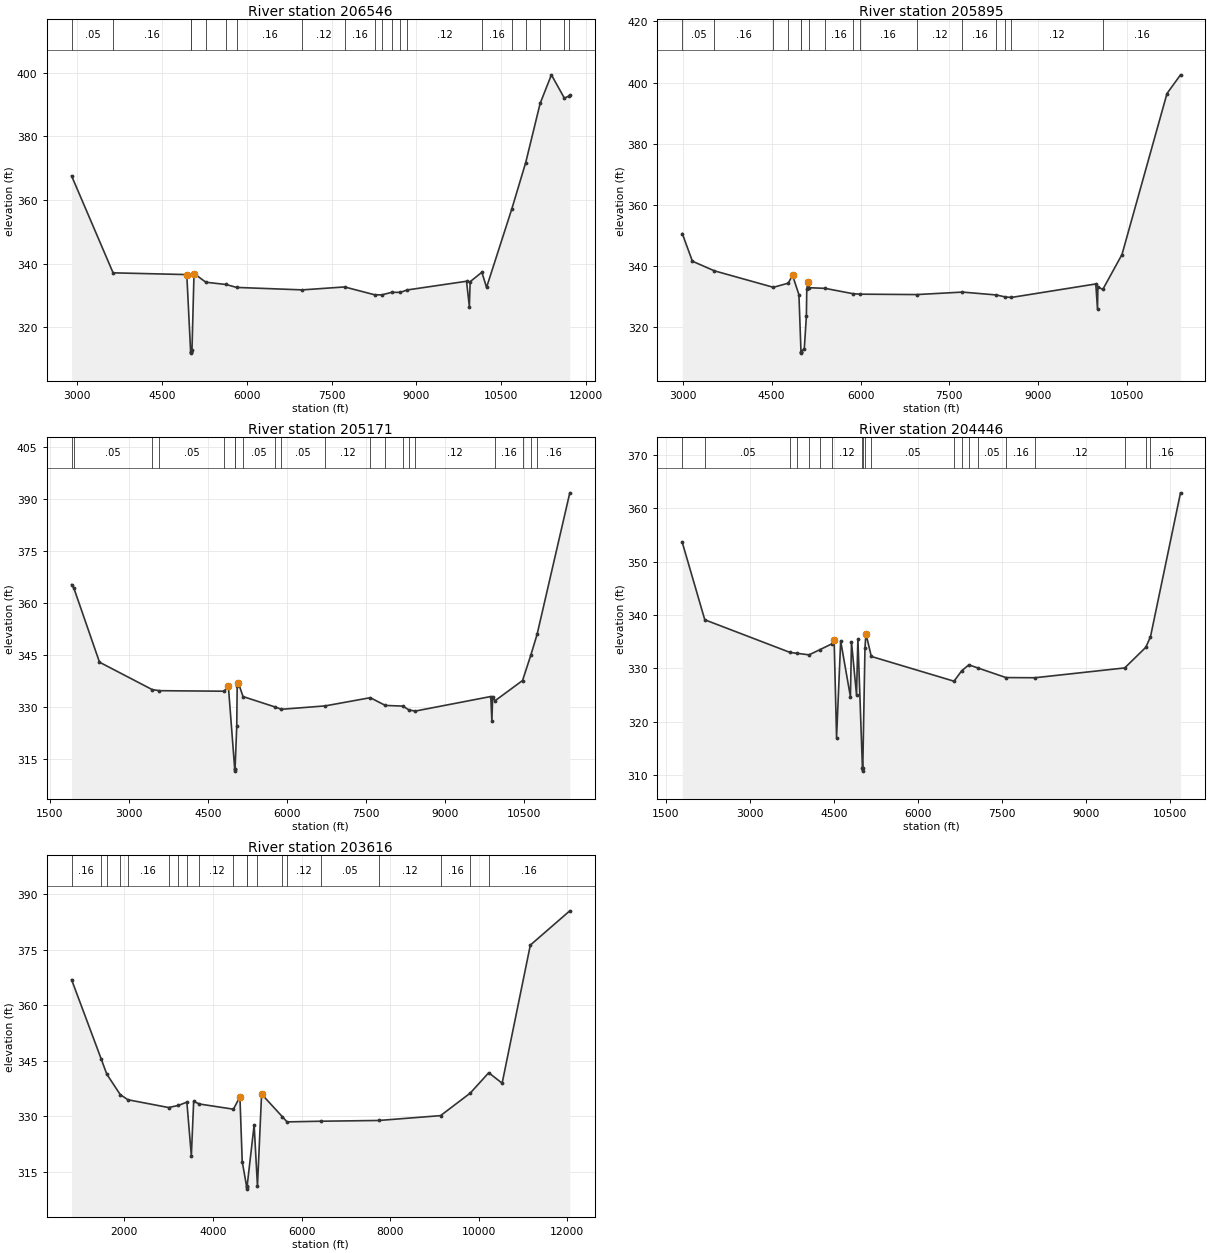
Type RM Length L Ch R = 1 ,206546  ,651,651,651
BEGIN DESCRIPTION:
TEHUACANA CREEK 122.0
END DESCRIPTION:
XS GIS Cut Line= 3
      3528699.65     10650010.18      3530699.61     10649410.19
      3535199.59     10644410.21
#Sta/Elev= 30
  2897.6  367.58  3632.2  337.13    4936  336.58  5003.9  312.42  5006.7  311.92
  5009.9  312.42  5027.8  312.83  5063.7  336.92  5273.8  334.18    5631  333.47
  5818.2  332.55  6980.2  331.78  7728.2   332.7  8257.3  330.25  8384.7   330.2
  8560.1     331  8715.6  331.01  8837.8  331.76  9885.4  334.49  9935.4  326.56
  9949.6  334.36 10156.8   337.3 10239.6  332.55 10688.4  357.31 10932.7  371.77
 11187.5  390.31 11386.9   399.3 11616.6  391.97 11697.1  392.65 11712.4  392.85
#Mann= 20 ,-1 , 0
  2897.6     .05       0  3632.2     .16       0  5003.9     .07       0
  5009.9     .16       0  5273.8     .05       0    5631     .16       0
  5818.2     .16       0  6980.2     .12       0  7728.2     .16       0
  8257.3     .07       0  8384.7     .16       0  8560.1     .12       0
  8715.6     .07       0  8837.8     .12       0 10156.8     .16       0
 10688.4     .16       0 10932.7     .12       0 11187.5     .16       0
 11616.6     .05       0 11697.1     .08       0
Bank Sta=4936,5063.7
XS Rating Curve= 0 ,0
Exp/Cntr=0.3,0.1

Type RM Length L Ch R = 1 ,205895  ,724,724,724
BEGIN DESCRIPTION:
TEHUACANA CREEK 121.0
END DESCRIPTION:
XS GIS Cut Line= 3
      3529099.64     10650060.19      3531099.61     10649860.19
      3535099.63     10644860.17
#Sta/Elev= 30
  2990.5  350.62  3161.3  341.59  3532.4  338.45  4528.8  333.06  4780.2  334.42
  4852.2     337  4960.2  330.65  4994.9  312.05  4997.7  311.55  5000.9  312.05
  5050.9  313.05  5086.1  323.64  5092.5  332.52  5114.9  334.91  5135.5  332.93
  5401.9  332.72  5865.9     331  5987.6  330.82  6951.4  330.69  7721.8   331.5
  8294.1  330.56  8439.6  329.94    8544  329.74  9973.3  334.16 10002.1   325.9
 10008.5  333.21 10091.1  332.36 10415.1  343.76 11175.5   396.4 11403.6  402.51
#Mann= 16 ,-1 , 0
  2990.5     .05       0  3532.4     .16       0  4528.8     .05       0
  4780.2     .16       0  4994.9     .07       0  5000.9     .16       0
  5135.5     .05       0  5401.9     .16       0  5865.9     .12       0
  5987.6     .16       0  6951.4     .12       0  7721.8     .16       0
  8294.1     .07       0  8439.6     .05       0    8544     .12       0
 10091.1     .16       0
Bank Sta=4852.2,5114.9
XS Rating Curve= 0 ,0
Exp/Cntr=0.3,0.1

Type RM Length L Ch R = 1 ,205171  ,725,725,725
BEGIN DESCRIPTION:
TEHUACANA CREEK 120.0
END DESCRIPTION:
XS GIS Cut Line= 3
       3528599.6     10650910.19      3531599.61     10650310.19
      3535599.58     10645310.22
#Sta/Elev= 30
  1912.5  365.28  1955.7  364.27  2442.8  342.93  3444.2  335.03  3580.4  334.72
  4809.9  334.57  4890.3  336.06  5011.3  312.05  5014.1  311.55  5017.3  312.05
  5049.6   324.6  5057.6  335.94  5078.4  337.05  5168.7  333.03  5781.4  330.01
    5897  329.36    6729  330.34  7585.7   332.7  7872.4  330.47  8205.6  330.28
  8319.2  329.17  8440.9  328.85  9874.3  333.04  9895.1  325.97  9909.5  332.78
    9955  331.82 10477.7  337.65 10634.9  344.97 10753.8  350.94   11375  391.71
#Mann= 20 ,-1 , 0
  1912.5     .05       0  1955.7     .05       0  3444.2     .16       0
  3580.4     .05       0  4809.9     .16       0  5011.3     .07       0
  5017.3     .16       0  5168.7     .05       0  5781.4     .16       0
    5897     .05       0    6729     .12       0  7585.7     .16       0
  7872.4     .05       0  8205.6     .12       0  8319.2     .05       0
  8440.9     .12       0    9955     .16       0 10477.7     .16       0
 10634.9     .12       0 10753.8     .16       0
Bank Sta=4890.3,5078.4
XS Rating Curve= 0 ,0
Exp/Cntr=0.3,0.1

Type RM Length L Ch R = 1 ,204446  ,830,830,830
BEGIN DESCRIPTION:
TEHUACANA CREEK 119.0
END DESCRIPTION:
XS GIS Cut Line= 3
      3529099.59      10651960.2      3532125.62      10650786.4
      3536099.59     10646760.21
#Sta/Elev= 30
  1792.8  353.57  2194.9  339.08  3721.9  332.95  3842.9   332.8  4057.7  332.51
  4255.3   333.5  4462.9  334.56  4506.5  335.22  4549.5     317  4623.1   335.1
  4797.2  324.67  4816.4  334.92  4906.2  325.02  4930.7  335.48  5012.1  311.22
  5014.8  310.72  5018.1  311.22  5057.3  333.78    5074   336.5  5170.6  332.21
  6648.6  327.57  6784.7  329.51  6913.8  330.64  7078.1  330.04  7576.9  328.25
  8096.1  328.22  9698.7  330.06 10075.2  333.92 10159.4  335.91 10695.6  362.87
#Mann= 20 ,-1 , 0
  1792.8     .16       0  2194.9     .05       0  3721.9     .05       0
  3842.9     .16       0  4057.7     .05       0  4255.3     .16       0
  4462.9     .12       0  5012.1     .07       0  5018.1     .12       0
  5057.3     .16       0  5170.6     .05       0  6648.6     .12       0
  6784.7     .16       0  6913.8     .12       0  7078.1     .05       0
  7576.9     .16       0  8096.1     .12       0  9698.7     .12       0
 10075.2     .12       0 10159.4     .16       0
Bank Sta=4506.5,5074
XS Rating Curve= 0 ,0
Exp/Cntr=0.3,0.1

Type RM Length L Ch R = 1 ,203616  ,1100,1100,1100
BEGIN DESCRIPTION:
TEHUACANA CREEK 118.0
END DESCRIPTION:
XS GIS Cut Line= 3
      3528799.61     10652210.19      3532799.61     10651010.19
      3537799.61     10646010.18
#Sta/Elev= 30
   807.8  366.87  1473.5  345.54  1601.8  341.36  1907.9  335.79  2080.4  334.42
  2997.5  332.32  3220.5  332.89  3410.4  333.78  3511.8  319.29    3564  333.99
  3694.9  333.27  4461.1  331.87  4608.1  335.21  4660.3  317.69  4758.6  311.01
  4764.4  310.27  4767.7  310.77  4929.1  327.61  5004.3  311.03  5097.1  335.95
  5566.6  329.83  5671.3  328.44  6440.7  328.62  7742.9  328.82  9137.4  330.13
    9807  336.21 10225.2  341.72 10527.6  338.89   11164  376.21   12055  385.47
#Mann= 20 ,-1 , 0
   807.8     .16       0  1473.5     .05       0  1601.8     .16       0
  1907.9     .16       0  2080.4     .16       0  2997.5     .16       0
  3220.5     .16       0  3410.4     .12       0  3694.9     .12       0
  4461.1     .16       0  4758.6     .12       0  4767.7     .16       0
  5004.3     .05       0  5566.6     .16       0  5671.3     .12       0
  6440.7     .05       0  7742.9     .12       0  9137.4     .16       0
    9807     .05       0 10225.2     .16       0
Bank Sta=4608.1,5097.1
XS Rating Curve= 0 ,0
Exp/Cntr=0.3,0.1