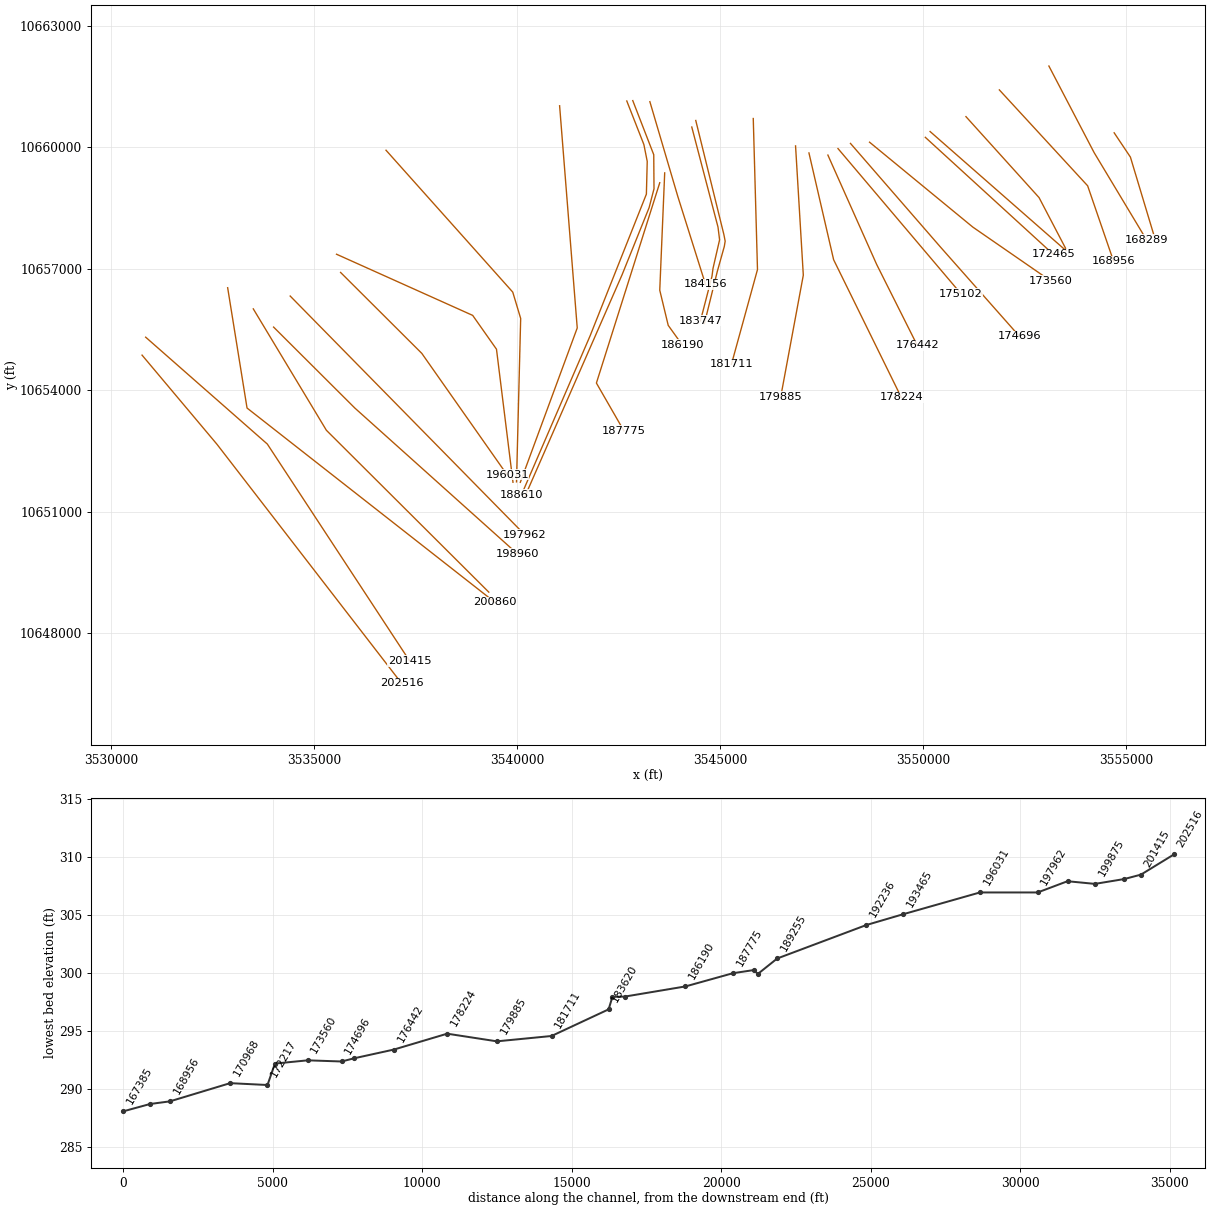
HEC-RAS study TEHUACANA CREEK.prj: TEHUACANA CREEK Base Level Engineering

--- TEHUACANA CREEK.g01 (geometry) --- (continued)

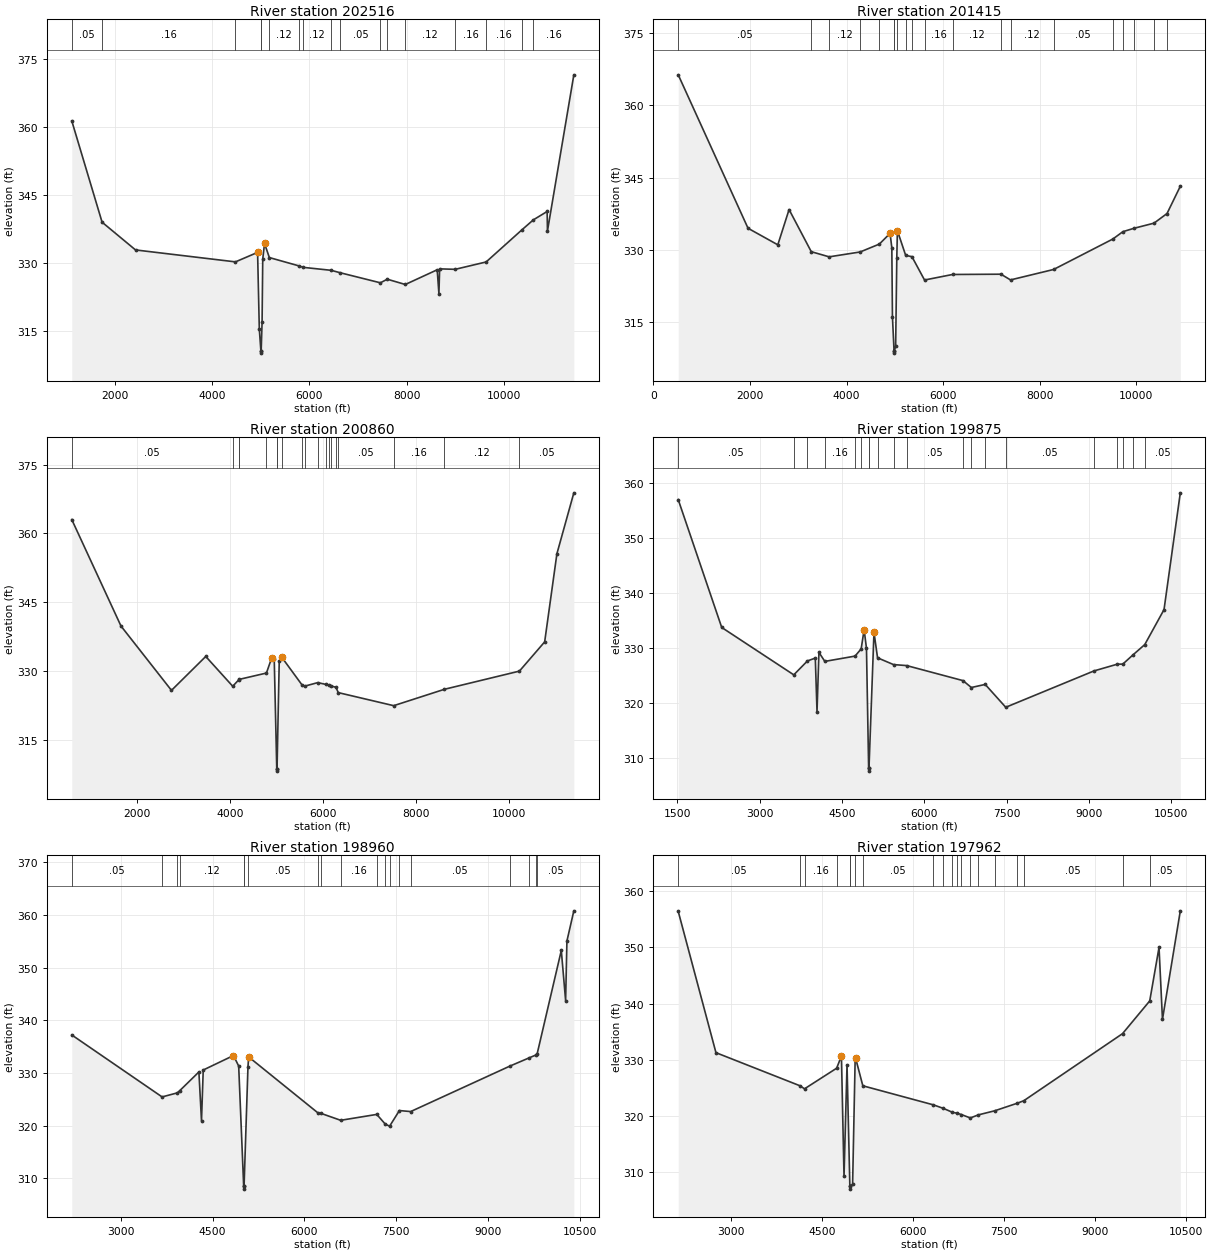
Type RM Length L Ch R = 1 ,202516  ,1101,1101,1101
BEGIN DESCRIPTION:
TEHUACANA CREEK 117.0
END DESCRIPTION:
XS GIS Cut Line= 3
       3530760.4     10654867.05      3532604.99     10652664.39
      3537149.59     10646760.21
#Sta/Elev= 30
  1114.8  361.39  1738.2  339.07  2425.6  332.96  4480.3  330.33  4935.7  332.42
    4971  315.55  5003.3  310.73  5006.1  310.23  5009.3  310.73  5027.9  317.01
  5041.6  330.94  5078.4  334.38  5177.4  331.28  5788.3  329.44  5876.4  329.12
  6448.7  328.47    6640  327.92    7460  325.72  7602.7  326.51    7973  325.35
  8628.8  328.59  8664.1  323.33  8678.6  328.79    8999  328.69  9634.8  330.31
 10366.9  337.35 10605.1  339.58 10889.5  341.43 10895.9  337.13 11438.5  371.53
#Mann= 17 ,-1 , 0
  1114.8     .05       0  1738.2     .16       0  4480.3     .12       0
  5003.3     .07       0  5009.3     .12       0  5177.4     .12       0
  5788.3     .16       0  5876.4     .12       0  6448.7     .16       0
    6640     .05       0    7460     .16       0  7602.7     .08       0
    7973     .12       0    8999     .16       0  9634.8     .16       0
 10366.9     .16       0 10605.1     .16       0
Bank Sta=4935.7,5078.4
XS Rating Curve= 0 ,0
Exp/Cntr=0.3,0.1

Type RM Length L Ch R = 1 ,201415  ,555,555,555
BEGIN DESCRIPTION:
TEHUACANA CREEK 116.0
END DESCRIPTION:
XS GIS Cut Line= 3
      3530849.59     10655310.21      3533844.96     10652670.03
      3537349.62     10647310.17
#Sta/Elev= 30
   513.4  366.35  1958.7  334.45  2575.3  331.01  2808.7  338.34  3268.1  329.58
  3638.3  328.51  4279.7  329.52  4677.8  331.16  4900.3  333.39  4936.2   330.4
  4949.1  316.07  4982.3  308.99  4985.1  308.49  4988.3  308.99  5015.5   309.9
  5039.4  328.37  5051.7  333.96  5223.1  328.81    5353  328.54  5613.7  323.69
  6194.1  324.84  7196.3   324.9  7393.9  323.71    8286  325.88  9512.8  332.21
    9721  333.74  9949.5  334.44 10365.2  335.51 10634.9  337.51 10910.2  343.19
#Mann= 20 ,-1 , 0
   513.4     .05       0  3268.1     .16       0  3638.3     .12       0
  4279.7     .16       0  4677.8     .12       0  4982.3     .07       0
  4988.3     .16       0  5039.4     .05       0  5223.1     .16       0
    5353     .12       0  5613.7     .16       0  6194.1     .12       0
  7196.3     .16       0  7393.9     .12       0    8286     .05       0
  9512.8     .16       0    9721     .16       0  9949.5     .12       0
 10365.2     .16       0 10634.9     .16       0
Bank Sta=4900.3,5051.7
XS Rating Curve= 0 ,0
Exp/Cntr=0.3,0.1

Type RM Length L Ch R = 1 ,200860  ,985,985,985
BEGIN DESCRIPTION:
TEHUACANA CREEK 115.0
END DESCRIPTION:
XS GIS Cut Line= 3
       3532868.4     10656532.91      3533345.83     10653559.79
      3539449.59      10648760.2
#Sta/Elev= 30
   607.4     363  1663.5  339.77  2747.2  325.73  3483.1  333.13  4061.7  326.63
    4198   328.1  4207.2  328.14  4785.5  329.51  4895.5  332.73  4952.7  332.65
    5007  308.61  5009.8  308.11    5013  308.61  5060.2  332.13  5110.9  332.76
  5116.3  332.93  5555.5  326.83  5617.1  326.68  5886.8  327.42  6056.9  327.04
  6131.6  326.82  6176.5  326.69  6276.6   326.4  6327.6  325.24  7516.7  322.39
  8606.9  325.97   10215  329.93 10757.1  336.31 11020.1  355.55 11383.4  368.83
#Mann= 19 ,-1 , 0
   607.4     .05       0  4061.7     .07       0    4198     .16       0
  4207.2     .05       0  4785.5     .16       0    5007     .07       0
    5013     .16       0  5110.9     .05       0  5555.5     .12       0
  5617.1     .05       0  5886.8     .12       0  6056.9     .07       0
  6131.6     .12       0  6176.5     .07       0  6276.6     .12       0
  6327.6     .05       0  7516.7     .16       0  8606.9     .12       0
   10215     .05       0
Bank Sta=4895.5,5116.3
XS Rating Curve= 0 ,0
Exp/Cntr=0.3,0.1

Type RM Length L Ch R = 1 ,199875  ,915,915,915
BEGIN DESCRIPTION:
TEHUACANA CREEK 114.0
END DESCRIPTION:
XS GIS Cut Line= 3
      3533499.61     10656010.18      3535299.61     10653010.19
       3539299.6      10649010.2
#Sta/Elev= 30
  1513.9  356.97  2306.9  333.77  3620.8  325.17  3870.7   327.7  4013.4  328.21
  4044.5   318.5  4079.5  329.24  4187.2  327.61  4737.9  328.57  4849.6  329.88
  4903.6  333.38  4946.4  329.98  4986.1  308.19  4988.9  307.69  4992.1  308.19
  5083.2   332.9  5148.5  328.26  5439.8  327.03  5679.1  326.85  6706.4  324.12
  6858.7  322.87  7111.6  323.43  7486.2  319.28    9095  325.88  9519.1   327.1
  9620.7  327.12  9810.5  328.83   10021  330.66 10372.3  337.01 10669.3  358.21
#Mann= 20 ,-1 , 0
  1513.9     .05       0  3620.8     .16       0  3870.7     .12       0
  4187.2     .16       0  4737.9     .05       0  4849.6     .08       0
  4986.1     .07       0  4992.1     .16       0  5148.5     .05       0
  5439.8     .07       0  5679.1     .05       0  6706.4     .07       0
  6858.7     .05       0  7111.6     .16       0  7486.2     .05       0
    9095     .12       0  9519.1     .05       0  9620.7     .16       0
  9810.5     .16       0   10021     .05       0
Bank Sta=4903.6,5083.2
XS Rating Curve= 0 ,0
Exp/Cntr=0.3,0.1

Type RM Length L Ch R = 1 ,198960  ,998,998,998
BEGIN DESCRIPTION:
TEHUACANA CREEK 113.0
END DESCRIPTION:
XS GIS Cut Line= 3
      3533999.64     10655560.16      3535999.61     10653560.19
      3539999.59     10649960.21
#Sta/Elev= 30
  2197.4   337.2  3674.3  325.43  3923.5   326.2  3963.8  326.63  4276.2  330.17
  4318.7  320.91    4347  330.54  4841.9  333.29  4926.8  331.29  5008.6  308.42
  5011.4  307.92  5014.6  308.42  5078.6  331.17  5089.7  333.03  6218.2  322.44
  6271.2  322.31  6594.6  320.99  7184.7  322.11  7322.4  320.28  7394.6  319.87
  7554.7  322.84    7739  322.65  9360.6  331.28  9668.9  332.81  9781.9  333.37
  9806.9   333.6 10202.1  353.24 10272.7  343.73   10294  355.04 10407.2  360.77
#Mann= 19 ,-1 , 0
  2197.4     .05       0  3674.3     .12       0  3923.5     .16       0
  3963.8     .12       0  5008.6     .07       0  5014.6     .12       0
  5078.6     .05       0  6218.2     .16       0  6271.2     .12       0
  6594.6     .16       0  7184.7     .05       0  7322.4     .07       0
  7394.6     .05       0  7554.7     .16       0    7739     .05       0
  9360.6     .16       0  9668.9     .05       0  9781.9     .16       0
  9806.9     .05       0
Bank Sta=4841.9,5089.7
XS Rating Curve= 0 ,0
Exp/Cntr=0.3,0.1

Type RM Length L Ch R = 1 ,197962  ,1931,1931,1931
BEGIN DESCRIPTION:
TEHUACANA CREEK 112.0
END DESCRIPTION:
XS GIS Cut Line= 2
      3534408.59     10656326.79      3540189.28     10650424.59
#Sta/Elev= 30
  2138.2  356.43  2758.8  331.26  4144.2  325.35  4216.1  324.82  4744.6  328.49
  4823.6  330.67  4866.1  309.21  4915.6  329.11  4962.1  307.45  4964.8  306.95
  4968.1  307.45  5007.5  307.85  5049.1  329.96  5057.1  330.27  5175.7  325.36
  6337.9  321.96  6501.9  321.33  6649.3  320.64  6726.8  320.47  6796.7  320.24
    6944  319.63  7076.8  320.18    7347  320.91  7718.9  322.26  7824.2   322.7
    9449  334.65  9896.5  340.48 10049.5  350.01 10106.1  337.19 10399.7  356.53
#Mann= 20 ,-1 , 0
  2138.2     .05       0  4144.2     .12       0  4216.1     .16       0
  4744.6     .12       0  4962.1     .07       0  4968.1     .12       0
  5049.1     .16       0  5175.7     .05       0  6337.9     .16       0
  6501.9     .05       0  6649.3     .05       0  6726.8     .16       0
  6796.7     .07       0    6944     .16       0  7076.8     .16       0
    7347     .05       0  7718.9     .16       0  7824.2     .05       0
    9449     .16       0  9896.5     .05       0
Bank Sta=4823.6,5057.1
XS Rating Curve= 0 ,0
Exp/Cntr=0.3,0.1

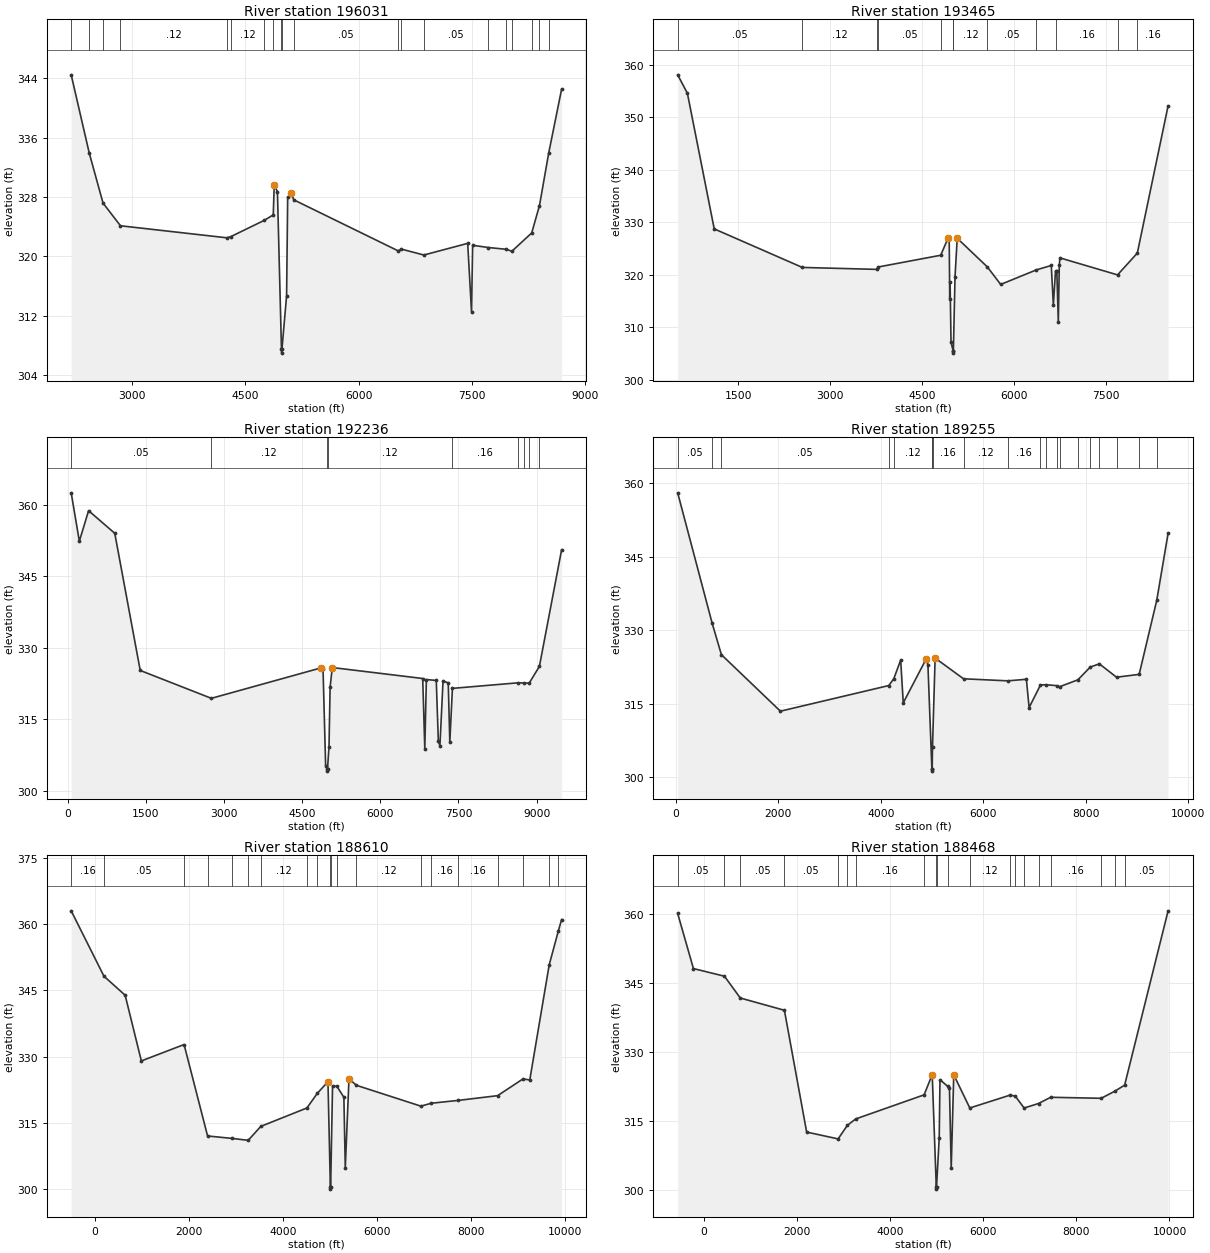
Type RM Length L Ch R = 1 ,196031  ,2566,2566,2566
BEGIN DESCRIPTION:
TEHUACANA CREEK 110.0
END DESCRIPTION:
XS GIS Cut Line= 3
      3535649.59      10656910.2      3537649.61     10654910.19
       3539749.6      10651910.2
#Sta/Elev= 30
  2196.4  344.45  2435.1  333.92  2617.9  327.17  2848.7  324.11  4255.7  322.49
  4309.3  322.65  4751.1  324.84  4870.8  325.58  4883.4   329.6  4925.9  328.72
  4979.4  307.45  4982.2  306.95  4985.4  307.45  5047.1  314.68  5061.5  327.94
  5110.3  328.46  5141.3  327.61  6523.8  320.73  6565.3  320.97  6863.6  320.17
  7443.9  321.74  7494.5  312.52  7509.3  321.48  7718.8  321.18  7954.6  320.94
  8028.9  320.68  8291.3  323.15    8394  326.84    8516  333.91  8686.8  342.52
#Mann= 20 ,-1 , 0
  2196.4     .05       0  2435.1     .16       0  2617.9     .16       0
  2848.7     .12       0  4255.7     .16       0  4309.3     .12       0
  4751.1     .16       0  4870.8     .12       0  4979.4     .07       0
  4985.4     .12       0  5141.3     .05       0  6523.8     .07       0
  6565.3     .12       0  6863.6     .05       0  7718.8     .16       0
  7954.6     .12       0  8028.9     .16       0  8291.3     .12       0
    8394     .16       0    8516     .05       0
Bank Sta=4883.4,5110.3
XS Rating Curve= 0 ,0
Exp/Cntr=0.3,0.1

Type RM Length L Ch R = 1 ,193465  ,1229,1229,1229
BEGIN DESCRIPTION:
TEHUACANA CREEK 109.0
END DESCRIPTION:
XS GIS Cut Line= 4
      3535549.62     10657360.18      3538902.51     10655848.93
      3539488.45     10655013.42      3539894.65     10651726.45
#Sta/Elev= 30
   509.5  358.07   668.1  354.56  1106.5  328.73  2545.7  321.39  3757.7  321.02
    3788  321.48  4805.7  323.71  4923.5  326.91  4944.4   326.8  4953.1  315.41
  4959.2  318.63  4974.1  307.15  5006.8  305.57  5009.5  305.07  5012.8  305.57
  5039.4   319.6  5075.2  326.95  5568.8  321.47  5785.3  318.15  6369.8  320.93
  6611.6  321.76  6645.4  314.23  6680.6  320.68  6702.2  320.75  6726.5  311.01
  6742.5  321.79  6752.6  323.21  7693.9  319.97  8016.9  324.12  8519.7  352.17
#Mann= 12 ,-1 , 0
   509.5     .05       0  2545.7     .12       0  3757.7     .16       0
    3788     .05       0  4805.7     .12       0  5006.8     .07       0
  5012.8     .12       0  5568.8     .05       0  6369.8     .12       0
  6680.6     .16       0  7693.9     .05       0  8016.9     .16       0
Bank Sta=4923.5,5075.2
XS Rating Curve= 0 ,0
Exp/Cntr=0.3,0.1

Type RM Length L Ch R = 1 ,192236  ,2981,2981,2981
BEGIN DESCRIPTION:
TEHUACANA CREEK 108.0
END DESCRIPTION:
XS GIS Cut Line= 4
      3536768.31     10659929.71      3539889.06     10656424.45
      3540084.37     10655773.41       3539981.5      10651735.2
#Sta/Elev= 30
    67.5  362.52   224.1  352.37   401.4  358.78   903.9  354.03  1392.4  325.26
  2757.8  319.41  4859.1  325.79  4900.9  325.64  4950.9  305.27    4981  304.64
  4983.7  304.14    4987  304.64  5015.7  309.29  5036.6  321.73  5078.3  325.87
  6814.1  323.57  6854.1   308.8  6884.1  323.35  7074.1  323.17  7114.1  310.43
  7144.2  309.49  7204.2  323.06  7304.2  322.64  7334.2  310.18  7384.2   321.5
  8646.9  322.67    8749  322.63    8857  322.59  9053.3   326.1  9479.9  350.58
#Mann= 9 ,-1 , 0
    67.5     .05       0  2757.8     .12       0    4981     .07       0
    4987     .12       0  7384.2     .16       0  8646.9     .05       0
    8749     .16       0    8857     .05       0  9053.3     .16       0
Bank Sta=4859.1,5078.3
XS Rating Curve= 0 ,0
Exp/Cntr=0.3,0.1

Type RM Length L Ch R = 1 ,189255  ,645,645,645
BEGIN DESCRIPTION:
Mapping XS 778dbe2d
END DESCRIPTION:
XS GIS Cut Line= 3
      3541043.06     10661028.86      3541477.09     10655538.38
      3540075.36     10651724.21
#Sta/Elev= 30
    36.1  358.03   710.5  331.37   889.3  325.01    2041  313.48  4155.7  318.71
  4253.5  320.09  4388.3  323.92  4438.5  315.18  4889.9  324.22    4920  322.93
  4996.9  301.75  4999.7  301.25  5002.9  301.75  5009.3  306.17  5060.4  324.32
  5615.1  320.09  6480.7  319.67  6841.6  319.99  6894.8  314.22  7116.8  318.83
  7229.5  318.87  7434.8  318.69  7488.5  318.46  7846.4  319.88  8088.6  322.48
  8265.5  323.14  8600.9  320.41  9042.5  320.99  9385.2  336.07  9607.3  349.77
#Mann= 20 ,-1 , 0
    36.1     .05       0   710.5     .16       0   889.3     .05       0
  4155.7     .16       0  4253.5     .12       0  4996.9     .07       0
  5002.9     .12       0  5009.3     .16       0  5615.1     .12       0
  6480.7     .16       0  7116.8     .05       0  7229.5     .16       0
  7434.8     .12       0  7488.5     .16       0  7846.4     .12       0
  8088.6     .16       0  8265.5     .12       0  8600.9     .16       0
  9042.5     .05       0  9385.2     .16       0
Bank Sta=4889.9,5060.4
XS Rating Curve= 0 ,0
Exp/Cntr=0.3,0.1

Type RM Length L Ch R = 1 ,188610  ,142,142,142
BEGIN DESCRIPTION:
TEHUACANA CREEK 107.0
END DESCRIPTION:
XS GIS Cut Line= 6
      3542697.36     10661147.17      3543118.35     10660070.81
      3543200.82     10659654.14      3543179.91     10658845.17
       3541793.6     10655342.73      3540104.28     10651417.04
#Sta/Elev= 30
  -504.9  363.05   192.2  348.22   643.4   343.9   987.5     329  1896.9  332.72
  2396.3  311.98  2920.1  311.42  3260.8  310.99  3528.8  314.15    4510  318.33
  4731.9  321.66  4957.9   324.3  5008.7  300.42  5011.5  299.92  5014.7  300.42
  5055.1  323.35  5149.5  323.22  5296.2  320.75  5325.9  304.72  5404.5  324.94
  5562.8  323.47  6935.2  318.74  7152.8   319.4  7731.5  320.05  8566.1  321.12
  9107.8  324.93  9250.8  324.68  9664.2   350.8  9860.6  358.56  9928.2  361.07
#Mann= 20 ,-1 , 0
  -504.9     .16       0   192.2     .05       0  1896.9     .16       0
  2396.3     .05       0  2920.1     .05       0  3260.8     .16       0
  3528.8     .12       0    4510     .16       0  4731.9     .12       0
  5008.7     .07       0  5014.7     .12       0  5149.5     .16       0
  5562.8     .12       0  6935.2     .05       0  7152.8     .16       0
  7731.5     .16       0  8566.1     .16       0  9107.8     .05       0
  9664.2     .16       0  9860.6     .05       0
Bank Sta=4957.9,5404.5
XS Rating Curve= 0 ,0
Exp/Cntr=0.3,0.1

Type RM Length L Ch R = 1 ,188468  ,693,693,693
BEGIN DESCRIPTION:
TEHUACANA CREEK 106.0
END DESCRIPTION:
XS GIS Cut Line= 6
       3542844.9     10661155.91      3543361.41     10659819.07
      3543367.61     10658977.06      3543247.81     10658513.52
      3542581.15     10656852.06      3540187.03     10651368.63
#Sta/Elev= 30
  -559.6  360.07  -221.3  348.11   444.7  346.45   785.2  341.72  1731.8  339.06
  2209.8  312.63  2885.2  311.15  3084.4   314.1  3262.4  315.48  4731.6  320.71
  4905.6   325.1  4992.6  300.75  4995.4  300.25  4998.6  300.75  5055.8  311.36
  5072.3     324    5236  322.57  5275.6  322.22  5313.3  304.76    5368  325.06
  5712.5  317.86  6580.6  320.66    6689  320.42  6878.8  317.85  7187.7  318.83
  7448.4  320.18  8533.2  319.96  8835.1  321.55  9036.8  322.82  9970.1  360.64
#Mann= 20 ,-1 , 0
  -559.6     .05       0   444.7     .05       0   785.2     .05       0
  1731.8     .05       0  2885.2     .16       0  3084.4     .16       0
  3262.4     .16       0  4731.6     .12       0  4992.6     .07       0
  4998.6     .12       0    5236     .16       0  5712.5     .12       0
  6580.6     .16       0    6689     .05       0  6878.8     .05       0
  7187.7     .05       0  7448.4     .16       0  8533.2     .05       0
  8835.1     .16       0  9036.8     .05       0
Bank Sta=4905.6,5368
XS Rating Curve= 0 ,0
Exp/Cntr=0.3,0.1

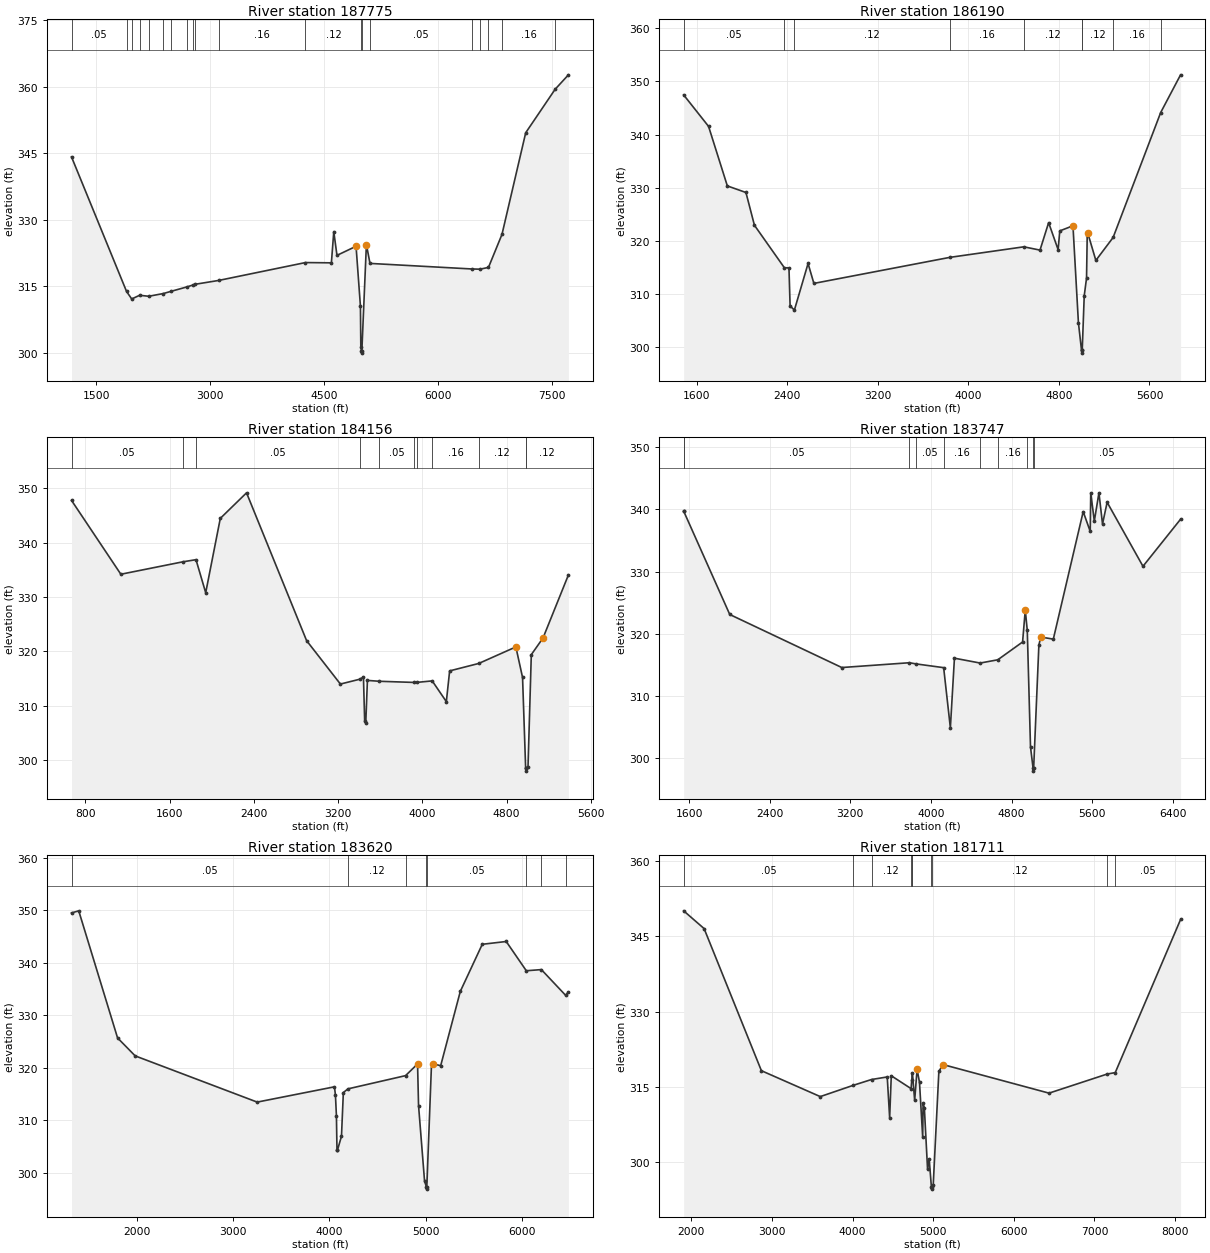
Type RM Length L Ch R = 1 ,187775  ,1585,1585,1585
BEGIN DESCRIPTION:
TEHUACANA CREEK 105.0
END DESCRIPTION:
XS GIS Cut Line= 3
      3543509.29     10659127.16       3541949.1     10654176.91
      3542625.41     10652997.69
#Sta/Elev= 30
  1172.1  344.18  1897.4  313.88  1965.5  312.18  2069.7  313.01  2189.9  312.79
    2382   313.4  2486.1  313.91  2694.3   314.9    2775  315.34  2798.4  315.48
  3110.7  316.35  4255.8  320.38  4597.5  320.32    4629  327.35  4670.9     322
  4922.5  324.05  4980.2  310.57  4985.4  301.45  4992.9  300.48  4995.7  299.98
  4998.9  300.48  5058.8  324.44  5106.3  320.19    6445  318.94  6557.5  318.89
    6668  319.29    6846  326.73  7158.6  349.62  7546.3  359.41  7721.8  362.67
#Mann= 20 ,-1 , 0
  1172.1     .05       0  1897.4     .08       0  1965.5     .16       0
  2069.7     .07       0  2189.9     .07       0    2382     .12       0
  2486.1     .05       0  2694.3     .12       0    2775     .16       0
  2798.4     .12       0  3110.7     .16       0  4255.8     .12       0
  4992.9     .07       0  4998.9     .12       0  5106.3     .05       0
    6445     .12       0  6557.5     .16       0    6668     .12       0
    6846     .16       0  7546.3     .05       0
Bank Sta=4922.5,5058.8
XS Rating Curve= 0 ,0
Exp/Cntr=0.3,0.1

Type RM Length L Ch R = 1 ,186190  ,2034,2034,2034
BEGIN DESCRIPTION:
TEHUACANA CREEK 104.0
END DESCRIPTION:
XS GIS Cut Line= 4
      3543630.81     10659370.19      3543509.28     10656470.89
      3543717.61     10655602.83       3544064.7     10655116.91
#Sta/Elev= 30
  1483.1  347.47  1703.3  341.54  1869.2  330.33  2033.6  329.09  2108.7  322.92
  2372.9  314.93  2413.9  314.88  2423.9  307.71    2462  306.96  2582.7  315.72
  2634.1  311.97  3834.7  316.87  4489.7  318.86  4632.5  318.24  4708.7  323.41
  4792.7  318.32  4807.3  321.86  4923.8  322.82  4971.9   304.6  4999.6  299.34
  5002.4  298.84  5005.6  299.34  5023.3  309.63  5043.8  312.97  5049.8  321.08
  5054.9  321.44  5126.1   316.3  5278.7  320.62  5699.1  344.15  5874.8  351.25
#Mann= 9 ,-1 , 0
  1483.1     .05       0  2372.9     .16       0    2462     .12       0
  3834.7     .16       0  4489.7     .12       0  4999.6     .07       0
  5005.6     .12       0  5278.7     .16       0  5699.1     .05       0
Bank Sta=4923.8,5054.9
XS Rating Curve= 0 ,0
Exp/Cntr=0.3,0.1

Type RM Length L Ch R = 1 ,184156  ,409,409,409
BEGIN DESCRIPTION:
TEHUACANA CREEK 103.0
END DESCRIPTION:
XS GIS Cut Line= 3
      3543265.93     10661129.83      3543951.88     10658794.83
      3544636.44     10656613.81
#Sta/Elev= 30
   667.3  347.77  1135.9  334.18  1725.3  336.47  1849.6  336.86  1941.8  330.78
  2080.5  344.46  2329.7  349.16  2900.2  321.96  3221.1  313.98  3407.6  314.88
    3440  315.27  3451.7  307.13  3462.2  306.88  3477.7  314.65  3590.8  314.49
  3917.6  314.28  3944.2  314.28  4093.1  314.56  4227.3  310.75  4258.7   316.4
  4535.3  317.77  4887.6  320.81  4951.2  315.19  4980.6  298.46  4983.4  297.96
  4986.6  298.46  5002.9   298.7  5034.3  319.39  5145.7  322.46  5386.9  334.06
#Mann= 11 ,-1 , 0
   667.3     .05       0  1725.3     .16       0  1849.6     .05       0
  3407.6     .16       0  3590.8     .05       0  3917.6     .16       0
  3944.2     .05       0  4093.1     .16       0  4535.3     .12       0
  4980.6     .07       0  4986.6     .12       0
Bank Sta=4887.6,5145.7
XS Rating Curve= 0 ,0
Exp/Cntr=0.3,0.1

Type RM Length L Ch R = 1 ,183747  ,127,127,127
BEGIN DESCRIPTION:
TEHUACANA CREEK 101.0
END DESCRIPTION:
XS GIS Cut Line= 6
      3544297.75     10660503.45      3544943.59     10658031.23
      3544982.79     10657716.33      3544821.33      10657013.2
      3544795.29     10656815.28      3544511.33     10655714.31
#Sta/Elev= 30
  1545.6  339.66  1546.9  339.66  2003.2   323.1  3115.3  314.58  3786.6  315.35
  3852.8  315.16  4126.2  314.56  4192.8   304.9  4233.2  316.08  4488.3   315.3
  4663.1  315.82  4909.6  318.68  4936.2  323.81  4956.1  320.55  4988.2  301.81
  5013.6  298.44  5016.3  297.94  5019.6  298.44  5071.3  318.17  5089.6  319.48
  5214.6  319.14  5511.1  339.62  5580.9  336.44  5586.1  342.62  5621.6   338.1
  5667.4  342.64  5702.9  337.63  5748.8  341.12  6104.5  330.84  6477.6   338.4
#Mann= 10 ,-1 , 0
  1545.6     .08       0  1546.9     .05       0  3786.6     .12       0
  3852.8     .05       0  4126.2     .16       0  4488.3     .05       0
  4663.1     .16       0  4956.1     .05       0  5013.6     .04       0
  5019.6     .05       0
Bank Sta=4936.2,5089.6
XS Rating Curve= 0 ,0
Exp/Cntr=0.3,0.1

Type RM Length L Ch R = 1 ,183620  ,1909,1909,1909
BEGIN DESCRIPTION:
TEHUACANA CREEK 100.0
END DESCRIPTION:
XS GIS Cut Line= 6
        3544396.     10660665.23       3545088.7     10657844.95
      3545119.95     10657683.49      3545099.11     10657553.29
      3544927.24      10656938.7      3544609.52     10655648.74
#Sta/Elev= 30
  1317.5  349.45  1392.6  349.85  1796.4  325.65  1979.5  322.23  3248.3  313.43
  4051.5  316.34  4061.8   314.8  4072.1  310.85  4077.9  304.33  4083.1  304.29
  4124.7  306.94  4144.1  315.25  4191.7  315.95  4790.8  318.47  4915.8  320.69
  4926.1  312.77  4988.4  298.43  5006.2  297.36  5008.9  296.86  5012.2  297.36
  5061.1  320.82  5071.5  320.75  5156.1  320.36  5360.5  334.52  5588.7  343.48
  5837.8  344.01  6046.6  338.44  6203.2  338.66  6454.5  333.78  6484.6  334.39
#Mann= 8 ,-1 , 0
  1317.5     .05       0  4191.7     .12       0  4790.8     .05       0
  5006.2     .04       0  5012.2     .05       0  6046.6     .12       0
  6203.2     .05       0  6454.5     .12       0
Bank Sta=4915.8,5071.5
XS Rating Curve= 0 ,0
Exp/Cntr=0.3,0.1

Type RM Length L Ch R = 1 ,181711  ,1826,1826,1826
BEGIN DESCRIPTION:
TEHUACANA CREEK 99.0
END DESCRIPTION:
XS GIS Cut Line= 3
      3545811.79     10660713.87      3545915.95     10656981.24
      3545274.11     10654639.39
#Sta/Elev= 30
  1905.8  350.11  2159.6  346.56  2869.9   318.2  3600.1  313.03  4006.9  315.27
  4235.5  316.44  4430.5  316.95  4460.5  308.78  4480.5  317.19  4726.2  314.62
  4734.2  316.25  4742.6  317.79  4770.6  312.26  4800.6  318.48  4830.6  315.87
  4870.2  304.94  4875.2  311.66  4890.6  310.83  4930.7  298.49  4950.7   300.6
  4977.7  295.06  4980.4  294.56  4983.7  295.06  5000.7  295.35  5070.7  318.04
  5120.7  319.43  6436.8  313.72  7157.9  317.53  7258.1  317.82  8068.1  348.38
#Mann= 10 ,-1 , 0
  1905.8     .05       0  4006.9     .16       0  4235.5     .12       0
  4726.2     .05       0  4734.2     .16       0  4742.6     .12       0
  4977.7     .07       0  4983.7     .12       0  7157.9     .16       0
  7258.1     .05       0
Bank Sta=4800.6,5120.7
XS Rating Curve= 0 ,0
Exp/Cntr=0.3,0.1

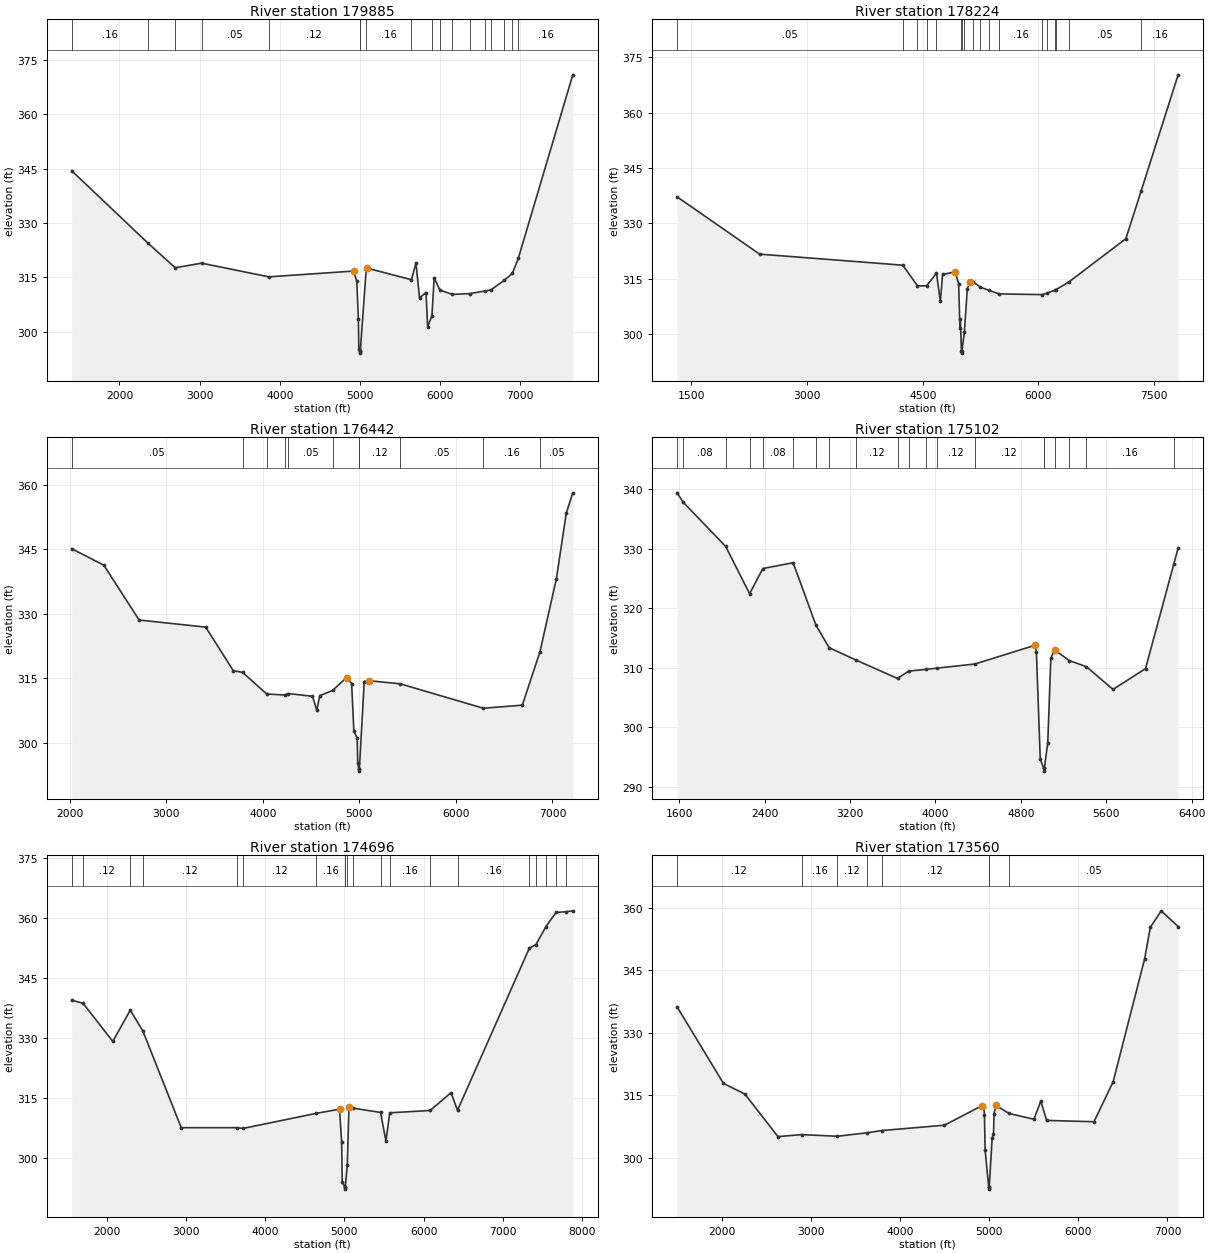
Type RM Length L Ch R = 1 ,179885  ,1661,1661,1661
BEGIN DESCRIPTION:
TEHUACANA CREEK 98.0
END DESCRIPTION:
XS GIS Cut Line= 3
      3546853.45     10660036.78      3547044.42     10656842.35
      3546488.86     10653838.84
#Sta/Elev= 30
  1403.8  344.39  2358.8  324.37  2695.8  317.65  3024.1  318.91  3864.9  315.14
  4921.4  316.73  4962.1  313.98  4982.4  303.52  4987.6  295.12  4999.7   294.6
  5002.5   294.1  5005.7   294.6  5080.3  317.38  5084.1  317.58  5644.7  314.34
  5700.9     319  5745.1  309.35  5826.5  310.81  5846.8  301.39  5899.7  304.37
  5928.2  314.85  6000.1  311.48    6156   310.3    6372  310.52  6560.8  311.22
  6637.6  311.57  6803.7  314.18  6904.2  316.12  6977.9   320.2  7658.4  370.85
#Mann= 18 ,-1 , 0
  1403.8     .16       0  2358.8     .05       0  2695.8     .16       0
  3024.1     .05       0  3864.9     .12       0  4999.7     .07       0
  5005.7     .12       0  5080.3     .16       0  5644.7     .12       0
  5899.7     .16       0  6000.1     .05       0    6156     .16       0
    6372     .05       0  6560.8     .16       0  6637.6     .05       0
  6803.7     .16       0  6904.2     .12       0  6977.9     .16       0
Bank Sta=4921.4,5084.1
XS Rating Curve= 0 ,0
Exp/Cntr=0.3,0.1

Type RM Length L Ch R = 1 ,178224  ,1782,1782,1782
BEGIN DESCRIPTION:
TEHUACANA CREEK 97.0
END DESCRIPTION:
XS GIS Cut Line= 3
      3547183.32     10659863.16      3547790.95     10657224.29
       3549457.6     10653821.55
#Sta/Elev= 30
  1314.2  337.17  2384.4  321.62  4241.5  318.62  4431.5  313.01  4549.3  313.02
  4677.7  316.45  4728.2  308.79    4757   316.1  4920.1  316.81  4965.1  313.61
    4982  301.49  4987.6  303.96  5001.5  295.26  5004.3  294.76  5007.5  295.26
  5039.1   300.4  5077.6  312.26    5117  314.12  5146.2  314.16  5247.4  312.66
  5360.5  311.77    5492  310.82  6050.1  310.64  6110.3  311.03  6217.4   311.9
    6226  311.96  6395.4  314.09  7133.4  325.82  7331.3  338.75  7811.1  370.27
#Mann= 18 ,-1 , 0
  1314.2     .05       0  4241.5     .16       0  4431.5     .12       0
  4549.3     .07       0  4677.7     .12       0  5001.5     .07       0
  5007.5     .12       0  5039.1     .16       0  5146.2     .05       0
  5247.4     .16       0  5360.5     .05       0    5492     .16       0
  6050.1     .05       0  6110.3     .16       0  6217.4     .12       0
    6226     .16       0  6395.4     .05       0  7331.3     .16       0
Bank Sta=4920.1,5117
XS Rating Curve= 0 ,0
Exp/Cntr=0.3,0.1

Type RM Length L Ch R = 1 ,176442  ,1340,1340,1340
BEGIN DESCRIPTION:
TEHUACANA CREEK 95.0
END DESCRIPTION:
XS GIS Cut Line= 3
      3547649.62     10659810.17      3548849.61     10657110.19
      3549849.61     10655110.19
#Sta/Elev= 30
  2020.1  345.12  2353.2  341.28  2718.4  328.53  3407.8  326.88  3694.4  316.74
  3789.6  316.36    4040  311.33  4225.8  311.09  4260.8  311.43  4514.4   310.8
  4558.9  307.54  4589.7  310.93  4723.2  312.17  4867.4  315.15    4920  313.76
  4942.6   302.8  4977.5  301.06  4983.1  295.22  4994.1  293.89  4996.8  293.39
  5000.1  293.89  5050.2  314.22  5100.5  314.41  5422.2   313.7  6283.9  308.02
  6688.1  308.73  6870.5  321.13  7040.3  338.06  7143.7   353.4  7210.8  358.11
#Mann= 11 ,-1 , 0
  2020.1     .05       0  3789.6     .12       0    4040     .05       0
  4225.8     .12       0  4260.8     .05       0  4723.2     .12       0
  4994.1     .07       0  5000.1     .12       0  5422.2     .05       0
  6283.9     .16       0  6870.5     .05       0
Bank Sta=4867.4,5100.5
XS Rating Curve= 0 ,0
Exp/Cntr=0.3,0.1

Type RM Length L Ch R = 1 ,175102  ,406,406,406
BEGIN DESCRIPTION:
TEHUACANA CREEK 94.0
END DESCRIPTION:
XS GIS Cut Line= 2
      3547898.07     10659971.65      3550925.14      10656385.8
#Sta/Elev= 30
  1580.9  339.39  1639.2  337.79  2036.2  330.39  2260.2  322.44  2384.4  326.67
  2668.1  327.65  2881.1  317.17  3005.3  313.37  3253.7  311.32  3645.4   308.2
  3750.5  309.44  3912.5  309.72  4016.7  309.94  4371.4  310.63    4933  313.78
  4946.1  312.72  4982.4  294.64  5014.6  293.13  5017.3  292.63  5020.6  293.13
  5052.7  297.41  5081.3  311.59  5116.4  313.02  5116.6     313  5254.5  311.21
  5415.4  310.17  5663.8  306.36  5968.1  309.85  6234.3   327.5  6273.6  330.12
#Mann= 20 ,-1 , 0
  1580.9      .1       0  1639.2     .08       0  2036.2      .1       0
  2260.2     .08       0  2384.4     .08       0  2668.1     .12       0
  2881.1     .08       0  3005.3     .08       0  3253.7     .12       0
  3645.4     .08       0  3750.5     .12       0  3912.5     .08       0
  4016.7     .12       0  4371.4     .12       0  5014.6     .07       0
  5020.6     .16       0  5116.6     .12       0  5254.5     .12       0
  5415.4     .16       0  6234.3     .16       0
Bank Sta=4933,5116.4
XS Rating Curve= 0 ,0
Exp/Cntr=0.3,0.1

Type RM Length L Ch R = 1 ,174696  ,1136,1136,1136
BEGIN DESCRIPTION:
TEHUACANA CREEK 93.0
END DESCRIPTION:
XS GIS Cut Line= 3
      3548205.77     10660098.41       3550416.5     10657543.82
      3552369.53     10655328.44
#Sta/Elev= 30
  1554.1  339.47  1698.7  338.68    2073  329.18  2293.9  336.99  2452.3  331.84
  2938.3  307.68  3640.6  307.68  3719.8   307.5  4643.8  311.25  4938.2  312.29
  4965.2  304.18  4972.8  294.16  5004.9  292.86  5007.7  292.36  5010.9  292.86
  5036.2  298.36  5057.3  312.82  5108.5  312.56  5456.5  311.48  5524.9  304.37
  5572.8  311.39  6083.1  311.97  6347.4  316.41  6429.1  312.03  7336.1  352.41
  7420.9  353.35  7547.2  357.84  7673.6  361.34    7806  361.54  7885.8  361.75
#Mann= 20 ,-1 , 0
  1554.1     .16       0  1698.7     .12       0  2293.9     .12       0
  2452.3     .12       0  3640.6     .07       0  3719.8     .12       0
  4643.8     .16       0  5004.9     .07       0  5010.9     .12       0
  5036.2     .16       0  5108.5     .12       0  5456.5     .12       0
  5572.8     .16       0  6083.1     .12       0  6429.1     .16       0
  7336.1     .16       0  7420.9     .05       0  7547.2     .08       0
  7673.6     .08       0    7806     .08       0
Bank Sta=4938.2,5057.3
XS Rating Curve= 0 ,0
Exp/Cntr=0.3,0.1

Type RM Length L Ch R = 1 ,173560  ,1095,1095,1095
BEGIN DESCRIPTION:
TEHUACANA CREEK 92.0
END DESCRIPTION:
XS GIS Cut Line= 3
      3548675.55     10660128.89      3551219.34     10658030.28
      3553129.07     10656706.49
#Sta/Elev= 30
  1498.1  336.25  2018.9  317.86    2260  315.28    2630  305.08  2895.6  305.56
  3296.9  305.16  3627.7  305.99  3793.3  306.53    4498  307.82  4917.8   312.5
  4940.6  312.25  4946.7  310.25  4954.3  301.79  4994.4  292.96  4997.1  292.46
  5000.4  292.96  5033.2  304.79    5048  305.65  5054.1  310.51    5076  312.57
  5223.7  310.63  5501.3  309.25    5579  313.62  5644.6  308.97  6175.5  308.65
  6390.4  318.26    6743  347.73  6807.9  355.39  6930.1  359.32  7119.5  355.55
#Mann= 8 ,-1 , 0
  1498.1     .12       0  2895.6     .16       0  3296.9     .12       0
  3627.7     .07       0  3793.3     .12       0  4994.4     .07       0
  5000.4     .12       0  5223.7     .05       0
Bank Sta=4917.8,5076
XS Rating Curve= 0 ,0
Exp/Cntr=0.3,0.1

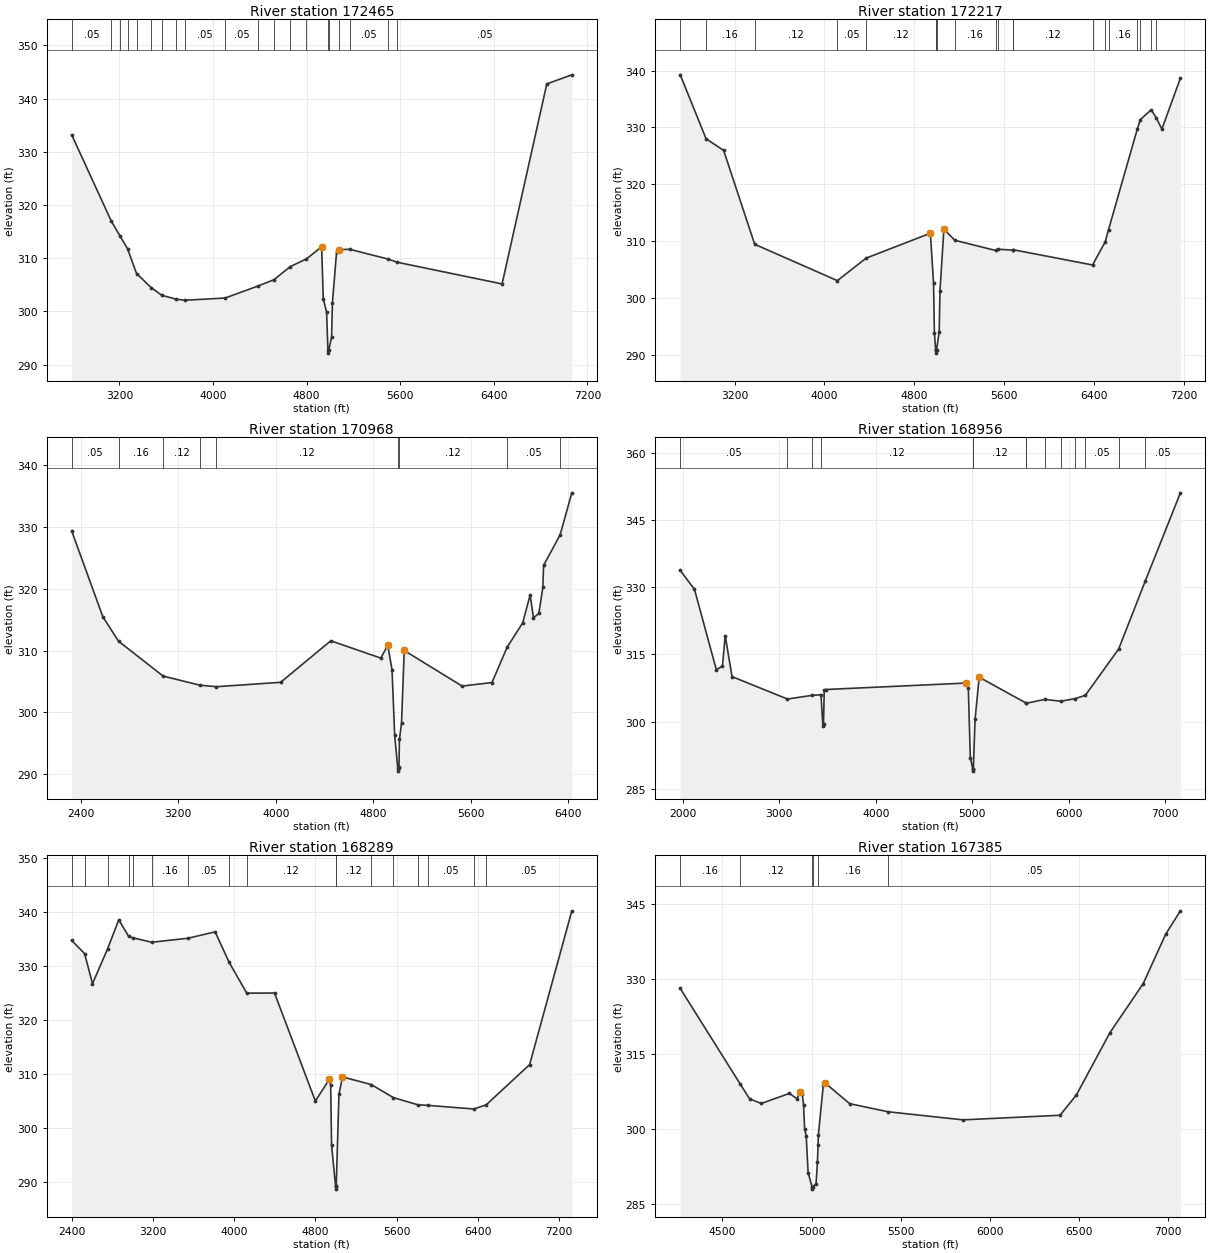
Type RM Length L Ch R = 1 ,172465  ,248,248,248
BEGIN DESCRIPTION:
Mapping XS 1cacf678
END DESCRIPTION:
XS GIS Cut Line= 2
        3550049.     10660249.02      3553199.99     10657358.44
#Sta/Elev= 30
  2791.4  333.19  3129.9  316.99  3206.7  314.11    3269  311.79    3346  307.13
  3471.4  304.49  3561.4  303.05  3686.2   302.3    3764  302.12  4103.5  302.53
  4381.6  304.77  4520.7  305.97  4659.8  308.43  4798.9  309.88  4928.4  312.15
  4942.6  302.35  4970.9  299.88  4982.1  292.68  4984.9  292.18  4988.1  292.68
  5013.5  295.17  5020.3   301.6    5056  311.16    5077  311.62  5168.8  311.69
  5494.3  309.86  5575.1  309.25  6471.1  305.18  6853.4  342.75  7067.4  344.46
#Mann= 20 ,-1 , 0
  2791.4     .05       0  3129.9     .16       0  3206.7     .05       0
    3269     .16       0    3346     .05       0  3471.4     .16       0
  3561.4     .05       0  3686.2     .16       0    3764     .05       0
  4103.5     .05       0  4381.6     .16       0  4520.7     .12       0
  4659.8     .12       0  4798.9     .12       0  4982.1     .07       0
  4988.1     .12       0    5077     .12       0  5168.8     .05       0
  5494.3     .12       0  5575.1     .05       0
Bank Sta=4928.4,5077
XS Rating Curve= 0 ,0
Exp/Cntr=0.3,0.1

Type RM Length L Ch R = 1 ,172217  ,1249,1249,1249
BEGIN DESCRIPTION:
TEHUACANA CREEK 91.0
END DESCRIPTION:
XS GIS Cut Line= 2
      3550166.14     10660392.29      3553512.51     10657449.57
#Sta/Elev= 30
  2714.9  339.24  2944.7  328.02  3101.6  325.95  3378.2  309.46  4114.5  303.07
  4371.3  307.03  4943.4   311.4  4971.8  302.65  4979.3  293.89  4990.6  290.83
  4993.3  290.33  4996.6  290.83  4998.4  290.92    5022  294.07  5028.7  301.21
  5063.8   312.1    5162  310.16  5524.3  308.37  5545.9  308.59  5677.8  308.43
  5682.4   308.5  6388.4  305.82  6501.4   309.9  6530.5  312.01  6787.5  329.74
  6814.8  331.38  6910.9   333.1  6956.9  331.65    7006   329.7  7171.1  338.66
#Mann= 20 ,-1 , 0
  2714.9     .05       0  2944.7     .16       0  3378.2     .12       0
  4114.5     .05       0  4371.3     .12       0  4990.6     .04       0
  4996.6     .12       0  4998.4     .05       0    5162     .16       0
  5524.3     .05       0  5545.9     .12       0  5677.8     .05       0
  5682.4     .12       0  6388.4     .16       0  6501.4     .12       0
  6530.5     .16       0  6787.5     .05       0  6814.8     .08       0
  6910.9     .05       0  6956.9     .08       0
Bank Sta=4943.4,5063.8
XS Rating Curve= 0 ,0
Exp/Cntr=0.3,0.1

Type RM Length L Ch R = 1 ,170968  ,2012,2012,2012
BEGIN DESCRIPTION:
TEHUACANA CREEK 90.0
END DESCRIPTION:
XS GIS Cut Line= 3
      3551049.61     10660760.19      3552849.61     10658760.19
      3553501.72     10657509.63
#Sta/Elev= 30
  2326.7  329.36    2582  315.48  2710.9  311.51  3076.5  305.87  3377.2   304.4
  3512.4  304.15  4040.2  304.86  4451.3  311.58  4861.6  308.78  4918.4  310.84
  4953.5  306.91  4975.2  296.28  5000.6  290.99  5003.4  290.49  5006.6  290.99
  5010.3  291.16  5014.1  295.61  5031.3  298.24  5053.4  310.01  5528.1  304.25
  5773.1  304.83  5897.9  310.56    6025  314.49  6085.6  318.99  6113.3   315.3
  6157.5  316.01  6190.3  320.27  6196.1  323.78  6331.3   328.7  6427.8  335.52
#Mann= 9 ,-1 , 0
  2326.7     .05       0  2710.9     .16       0  3076.5     .12       0
  3377.2     .16       0  3512.4     .12       0  5000.6     .07       0
  5006.6     .12       0  5897.9     .05       0  6331.3     .08       0
Bank Sta=4918.4,5053.4
XS Rating Curve= 0 ,0
Exp/Cntr=0.3,0.1

Type RM Length L Ch R = 1 ,168956  ,667,667,667
BEGIN DESCRIPTION:
TEHUACANA CREEK 89.0
END DESCRIPTION:
XS GIS Cut Line= 3
      3551871.88     10661420.93      3554046.36     10659051.14
      3554684.37     10657189.17
#Sta/Elev= 30
  1972.1  333.76  2119.8  329.52  2346.1  311.56  2409.6  312.36    2438  319.19
  2508.9  310.03  3083.5  305.02  3340.4  305.85  3431.2  305.99  3450.4  298.95
  3457.2  299.41  3464.6  306.96  3478.8  307.15  4936.4  308.59    4958  307.58
    4979  291.94  5004.3  289.42  5007.1  288.92  5010.3  289.42  5028.3  300.57
  5070.9   309.9  5556.4  304.13  5557.7  304.06  5749.8  304.94  5918.8  304.53
  6069.1  305.14  6171.4  305.85  6516.6   316.2  6791.1  331.31  7156.6  351.08
#Mann= 14 ,-1 , 0
  1972.1     .05       0  3083.5     .07       0  3340.4     .16       0
  3431.2     .12       0  5004.3     .07       0  5010.3     .12       0
  5556.4     .07       0  5557.7     .12       0  5749.8     .07       0
  5918.8     .12       0  6069.1     .07       0  6171.4     .05       0
  6516.6     .16       0  6791.1     .05       0
Bank Sta=4936.4,5070.9
XS Rating Curve= 0 ,0
Exp/Cntr=0.3,0.1

Type RM Length L Ch R = 1 ,168289  ,904,904,904
BEGIN DESCRIPTION:
TEHUACANA CREEK 88.0
END DESCRIPTION:
XS GIS Cut Line= 3
      3553091.97     10662010.95      3554206.54     10659870.35
      3555499.62     10657710.18
#Sta/Elev= 30
  2396.7   334.7  2524.6  332.26  2601.7   326.7  2750.4  333.12  2861.3  338.53
  2957.9  335.46  2998.7   335.2  3184.4  334.37  3541.3   335.1  3811.2  336.29
  3948.8  330.66  4122.9  324.95  4396.6  324.97    4799  304.99  4937.6  309.03
  4950.1  307.92    4959  296.81  4998.8  289.19  5001.5  288.69  5004.8  289.19
  5031.7  306.21  5066.7  309.45  5350.1  308.04  5568.4  305.62  5810.6  304.29
  5906.1  304.19  6362.2  303.52  6483.7  304.29  6911.5  311.73  7327.7  340.18
#Mann= 17 ,-1 , 0
  2396.7     .05       0  2524.6     .16       0  2750.4     .05       0
  2957.9     .16       0  2998.7     .05       0  3184.4     .16       0
  3541.3     .05       0  3948.8     .16       0  4122.9     .12       0
  4998.8     .07       0  5004.8     .12       0  5350.1     .16       0
  5568.4     .05       0  5810.6     .12       0  5906.1     .05       0
  6362.2     .12       0  6483.7     .05       0
Bank Sta=4937.6,5066.7
XS Rating Curve= 0 ,0
Exp/Cntr=0.3,0.1

Type RM Length L Ch R = 1 ,167385  ,912,912,912
BEGIN DESCRIPTION:
TEHUACANA CREEK 87.0
END DESCRIPTION:
XS GIS Cut Line= 3
      3554699.63     10660360.15      3555099.61     10659760.19
       3555699.6     10657760.22
#Sta/Elev= 30
  4262.8  328.14  4600.1  309.02  4651.9   306.1    4718  305.16  4875.7  307.17
  4919.3  306.11  4934.3  307.47  4947.8  307.15  4955.3  304.93  4961.3  300.15
  4970.3  298.72  4980.9  291.37  5002.6  288.55  5005.4  288.05  5008.6  288.55
  5025.6  289.16  5033.5  293.55  5036.7  296.87  5038.7  298.95  5066.5  308.92
  5077.8  309.22  5214.4  305.12  5431.1   303.5  5850.4  301.89  6395.9  302.81
  6487.3  306.84  6676.1  319.31  6863.1  329.12  6989.3  338.99  7071.9  343.65
#Mann= 6 ,-1 , 0
  4262.8     .16       0  4600.1     .12       0  5002.6     .07       0
  5008.6     .12       0  5036.7     .16       0  5431.1     .05       0
Bank Sta=4934.3,5077.8
XS Rating Curve= 0 ,0
Exp/Cntr=0.3,0.1