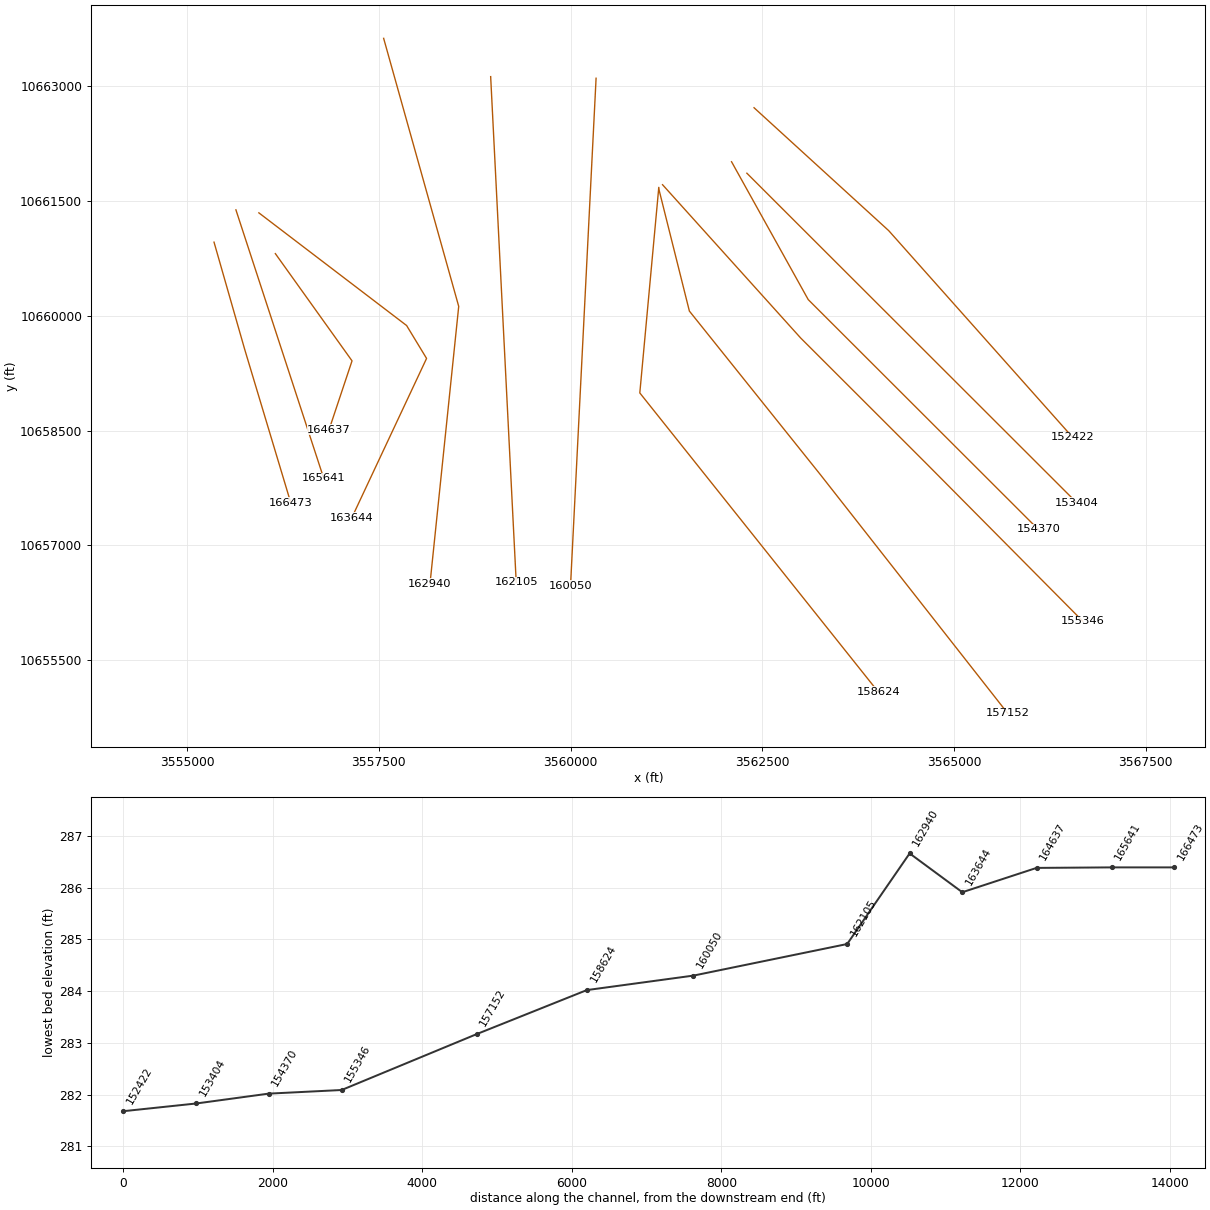
HEC-RAS study TEHUACANA CREEK.prj: TEHUACANA CREEK Base Level Engineering

--- TEHUACANA CREEK.g01 (geometry) --- (continued)

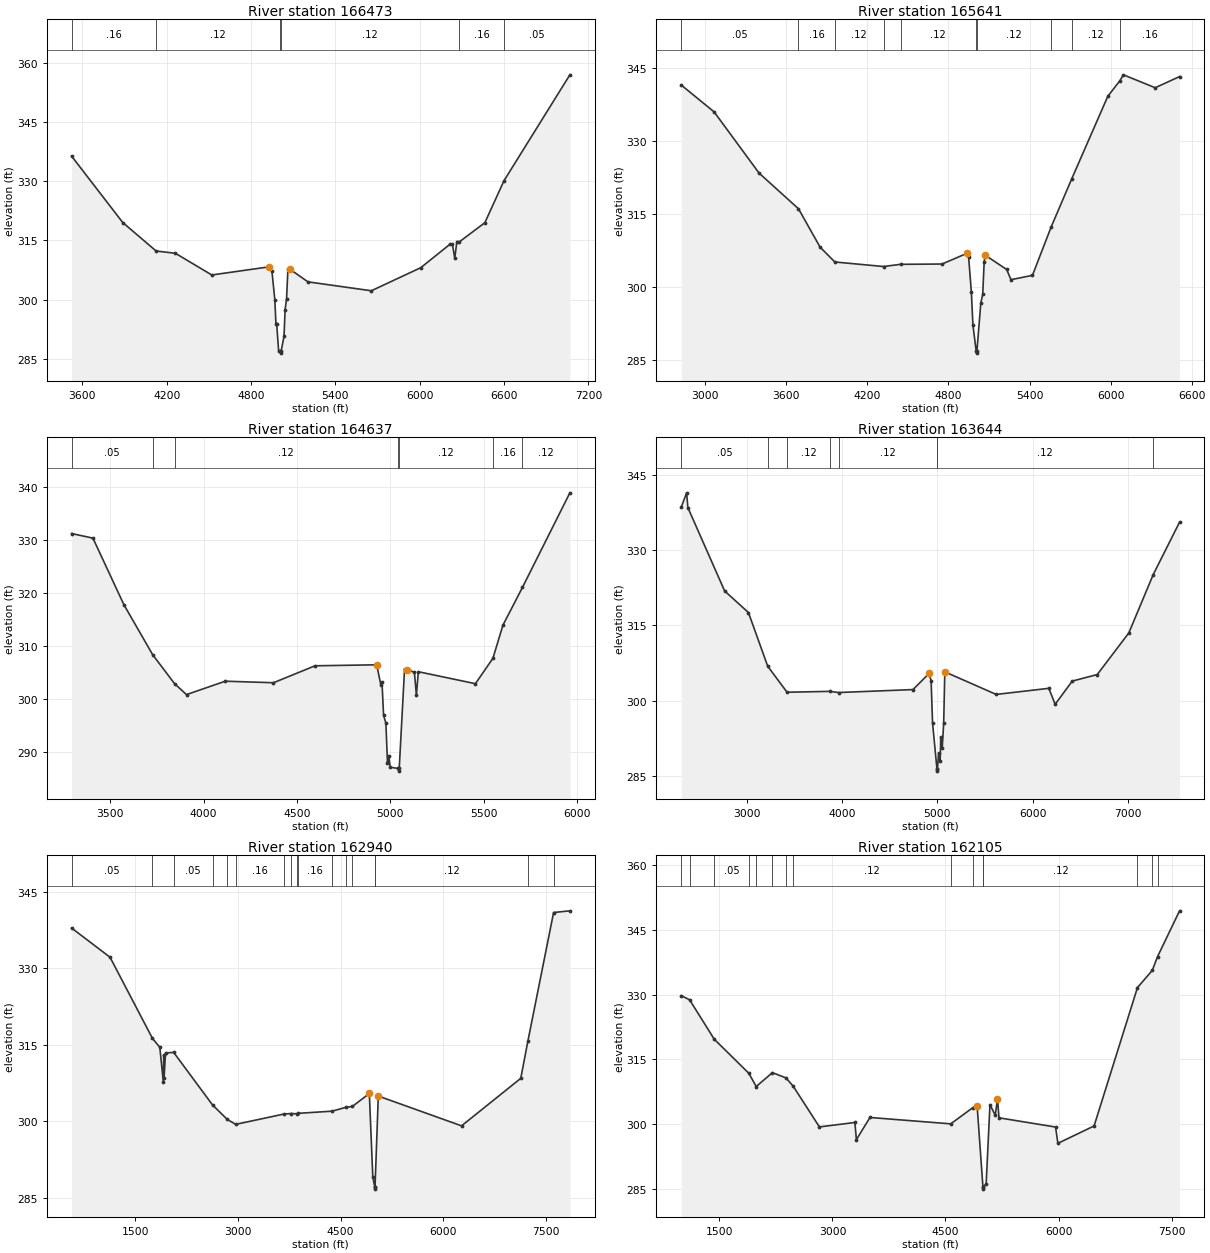
Type RM Length L Ch R = 1 ,166473  ,832,832,832
BEGIN DESCRIPTION:
TEHUACANA CREEK 86.0
END DESCRIPTION:
XS GIS Cut Line= 3
      3555349.61     10660960.18      3555749.61     10659560.19
      3556349.62     10657560.16
#Sta/Elev= 30
  3523.8  336.44  3887.8  319.56  4124.9  312.33  4262.2  311.75  4520.9  306.24
  4929.1  308.31  4948.6  307.28  4969.4  299.95  4977.2  293.89  4982.4  293.89
  4996.3  287.04  5008.1  286.89  5010.9  286.39  5014.1  286.89  5034.6  290.62
  5042.5   297.4  5052.9  300.23  5062.5  307.77  5073.8  307.77  5205.1  304.49
  5655.8  302.23  6007.3  308.09  6216.1  314.07  6232.7  313.99  6249.2  310.45
    6264  314.73  6281.7  314.65  6463.2  319.52  6599.3  330.18  7067.9  357.08
#Mann= 6 ,-1 , 0
  3523.8     .16       0  4124.9     .12       0  5008.1     .07       0
  5014.1     .12       0  6281.7     .16       0  6599.3     .05       0
Bank Sta=4929.1,5073.8
XS Rating Curve= 0 ,0
Exp/Cntr=0.3,0.1

Type RM Length L Ch R = 1 ,165641  ,1004,1004,1004
BEGIN DESCRIPTION:
TEHUACANA CREEK 85.0
END DESCRIPTION:
XS GIS Cut Line= 2
       3555635.2     10661381.69      3556780.95     10657875.02
#Sta/Elev= 30
  2821.6  341.45  3065.1  335.93  3397.9  323.36  3689.3  316.05  3849.5  308.16
  3958.6  305.11  4318.9  304.18  4445.3  304.63  4752.6  304.69  4937.7   306.9
  4949.2  306.05  4969.3  298.97    4981  292.13  5004.7  286.89  5007.4  286.39
  5010.7  286.89  5039.5  296.73  5053.5  298.45    5064  305.04  5071.4  306.51
  5230.8  303.57  5262.7  301.47  5421.7  302.37  5560.5  312.33    5712  322.16
  5979.8  339.16  6068.6  342.32    6095  343.55  6330.5   340.9  6510.7  343.19
#Mann= 10 ,-1 , 0
  2821.6     .05       0  3689.3     .16       0  3958.6     .12       0
  4318.9     .16       0  4445.3     .12       0  5004.7     .07       0
  5010.7     .12       0  5560.5     .16       0    5712     .12       0
  6068.6     .16       0
Bank Sta=4937.7,5071.4
XS Rating Curve= 0 ,0
Exp/Cntr=0.3,0.1

Type RM Length L Ch R = 1 ,164637  ,993,993,993
BEGIN DESCRIPTION:
TEHUACANA CREEK 84.0
END DESCRIPTION:
XS GIS Cut Line= 3
       3556149.6      10660810.2      3557149.61     10659410.19
       3556849.6     10658510.16
#Sta/Elev= 30
  3292.9  331.27  3407.2   330.4  3573.1  317.83  3727.4  308.37  3844.6   302.9
  3908.6  300.84  4116.3  303.37  4374.4  303.08  4596.8  306.28  4927.4  306.47
  4949.5  302.66  4955.6  303.21  4964.2  296.91  4976.5  295.46  4985.1  288.01
  4991.3  289.31  4999.9  287.12    5042  286.88  5044.8  286.38    5048  286.88
  5076.6  305.73  5087.2  305.53  5129.3  305.07  5139.9  300.73  5150.4  305.16
  5456.1   302.9  5549.9   307.7  5603.7  313.97  5707.9  321.08  5962.1  338.96
#Mann= 7 ,-1 , 0
  3292.9     .05       0  3727.4     .16       0  3844.6     .12       0
    5042     .07       0    5048     .12       0  5549.9     .16       0
  5707.9     .12       0
Bank Sta=4927.4,5087.2
XS Rating Curve= 0 ,0
Exp/Cntr=0.3,0.1

Type RM Length L Ch R = 1 ,163644  ,704,704,704
BEGIN DESCRIPTION:
TEHUACANA CREEK 83.0
END DESCRIPTION:
XS GIS Cut Line= 4
      3555934.39     10661342.79      3557861.46     10659871.45
      3558121.88     10659441.76       3557145.3     10657358.39
#Sta/Elev= 30
  2314.7  338.56    2371  341.43  2384.2  338.48    2770  321.85  3019.4  317.55
  3221.7  306.84  3424.8  301.65  3873.2  301.82  3965.3  301.59    4746  302.18
  4914.6  305.39    4936  303.95  4951.2  295.52    4997  286.41  4999.7  285.91
    5003  286.41  5015.5  289.58    5031  287.91  5036.8  292.76  5052.3  290.44
  5067.8  295.42  5079.8  305.72  5618.9  301.21  6171.1  302.43  6237.4  299.24
  6416.5  303.87  6679.2  305.18  7010.5  313.49  7266.3  325.12  7542.6  335.58
#Mann= 8 ,-1 , 0
  2314.7     .05       0  3221.7     .16       0  3424.8     .12       0
  3873.2     .16       0  3965.3     .12       0    4997     .07       0
    5003     .12       0  7266.3     .16       0
Bank Sta=4914.6,5079.8
XS Rating Curve= 0 ,0
Exp/Cntr=0.3,0.1

Type RM Length L Ch R = 1 ,162940  ,835,835,835
BEGIN DESCRIPTION:
Mapping XS 71ed379f
END DESCRIPTION:
XS GIS Cut Line= 3
      3557561.98     10663621.47      3558541.15     10660121.45
      3558166.14      10656496.4
#Sta/Elev= 30
   570.7  337.91  1132.4  332.17  1751.9  316.25  1859.6   314.5  1911.5  307.62
  1916.7  313.03  1921.9  308.52  1942.7  313.39  2062.3  313.49  2629.8  303.18
  2846.5  300.33  2968.6  299.37  3673.6   301.4  3782.1   301.5  3866.6  301.44
    3875  301.53  4375.6  301.96  4573.6   302.7  4672.5  302.89  4920.2  305.43
  4970.4  289.13  4997.6  287.16  5000.3  286.66  5003.6  287.16    5051  304.93
  6267.3  299.08  7131.9   308.4  7236.1   315.7  7611.7  340.95  7849.5  341.28
#Mann= 17 ,-1 , 0
   570.7     .05       0  1751.9     .16       0  2062.3     .05       0
  2629.8     .12       0  2846.5     .05       0  2968.6     .16       0
  3673.6     .12       0  3782.1     .16       0  3866.6     .12       0
    3875     .16       0  4375.6     .12       0  4573.6     .16       0
  4672.5     .12       0  4997.6     .07       0  5003.6     .12       0
  7236.1     .16       0  7611.7     .05       0
Bank Sta=4920.2,5051
XS Rating Curve= 0 ,0
Exp/Cntr=0.3,0.1

Type RM Length L Ch R = 1 ,162105  ,2055,2055,2055
BEGIN DESCRIPTION:
TEHUACANA CREEK 82.0
END DESCRIPTION:
XS GIS Cut Line= 2
      3558957.81     10663121.48      3559291.15     10656517.29
#Sta/Elev= 30
   993.5  329.78    1104  328.83  1431.5  319.68  1890.1  311.78  1988.1  308.71
  2203.1  311.93  2382.9  310.71    2478  308.81  2827.1  299.34  3297.7  300.37
  3317.7   296.4    3498  301.53  4569.5  300.05  4861.3  303.79  4919.8  304.24
  4996.9  285.41  4999.6  284.91  5002.9  285.41  5039.9  286.17    5090   304.5
  5160.1  302.06  5190.1  305.73  5210.2  301.45  5961.1  299.31  5991.1  295.53
  6471.8  299.56  7047.6  331.66  7244.2  335.64  7313.8  338.83  7606.1  349.46
#Mann= 15 ,-1 , 0
   993.5     .05       0    1104     .16       0  1431.5     .05       0
  1890.1     .16       0  1988.1     .12       0  2203.1     .16       0
  2382.9     .05       0    2478     .12       0  4569.5     .16       0
  4861.3     .12       0  4996.9     .07       0  5002.9     .12       0
  7047.6     .16       0  7244.2     .12       0  7313.8     .16       0
Bank Sta=4919.8,5190.1
XS Rating Curve= 0 ,0
Exp/Cntr=0.3,0.1

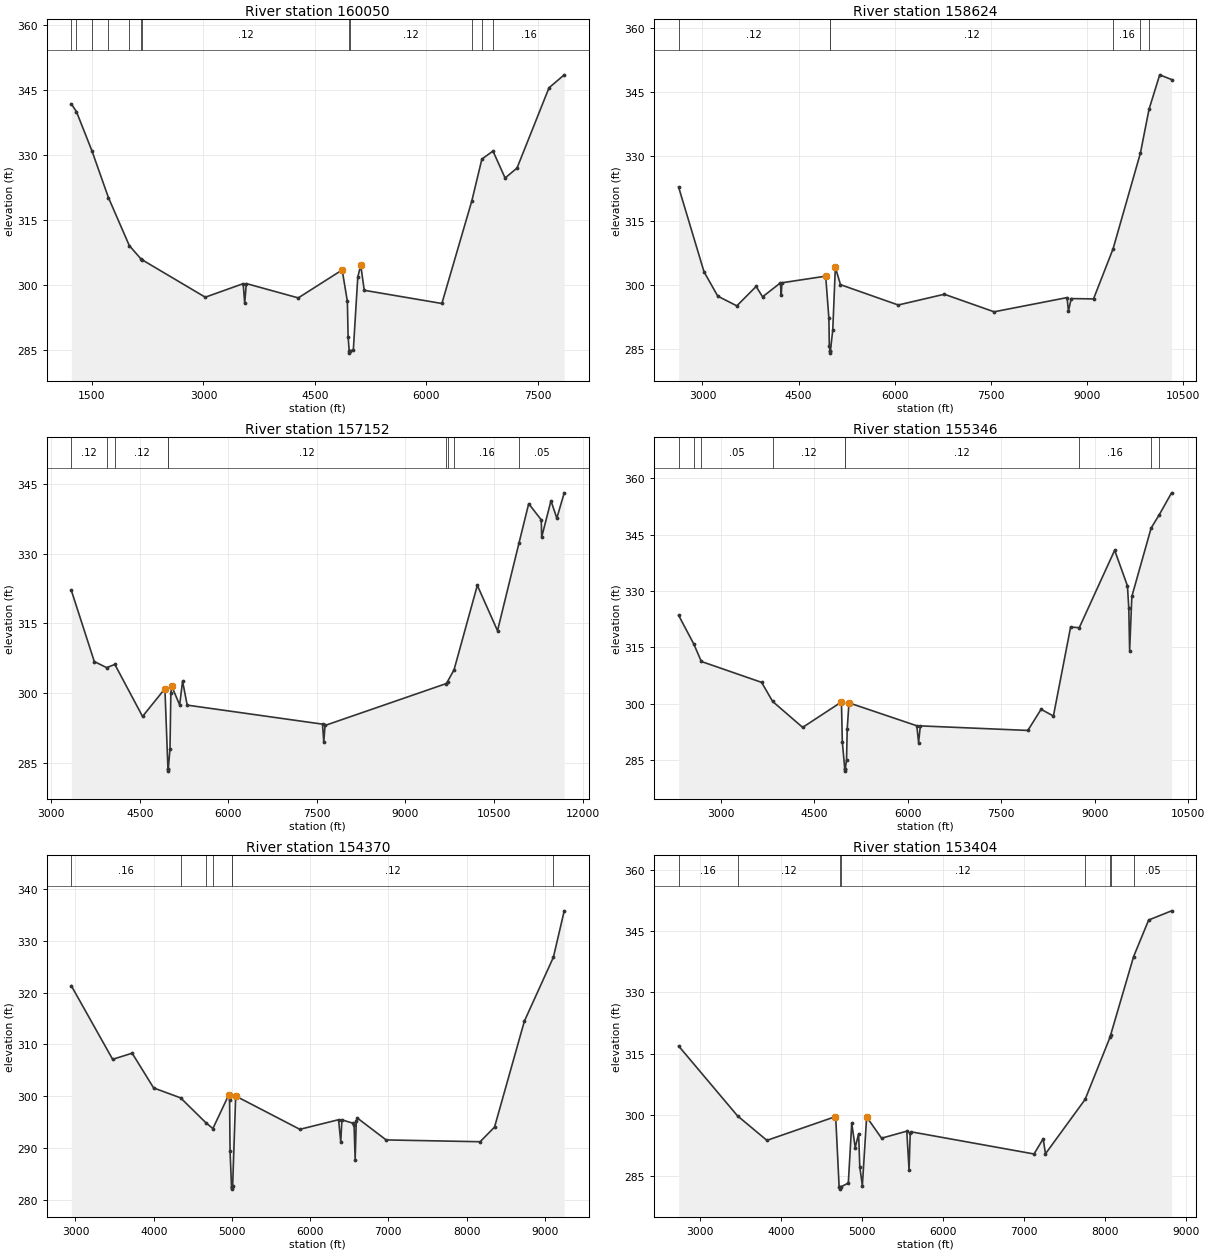
Type RM Length L Ch R = 1 ,160050  ,1426,1426,1426
BEGIN DESCRIPTION:
TEHUACANA CREEK 81.0
END DESCRIPTION:
XS GIS Cut Line= 2
      3560332.81     10663100.59      3559999.48     10656475.57
#Sta/Elev= 30
  1221.5  341.74  1290.8  339.95  1497.8  330.98    1721  320.15    2002  309.08
  2157.8  306.03  2172.5  305.83  3024.2  297.19  3534.8  300.31  3554.8  295.77
  3576.8  300.33  4275.8  297.03  4866.5  303.47  4936.6  296.23  4946.6  288.08
  4961.2   284.8    4964   284.3  4967.2   284.8  5016.7  285.03  5076.8  301.84
  5116.8  304.58  5163.8  298.78  6208.2  295.74  6611.1  319.37  6746.9  329.03
    6896  330.87  7059.3  324.66  7219.5  326.95    7650  345.45  7854.9  348.44
#Mann= 12 ,-1 , 0
  1221.5     .05       0  1290.8     .16       0  1497.8     .12       0
    1721     .16       0    2002     .12       0  2157.8     .16       0
  2172.5     .12       0  4961.2     .07       0  4967.2     .12       0
  6611.1     .16       0  6746.9     .12       0    6896     .16       0
Bank Sta=4866.5,5116.8
XS Rating Curve= 0 ,0
Exp/Cntr=0.3,0.1

Type RM Length L Ch R = 1 ,158624  ,1472,1472,1472
BEGIN DESCRIPTION:
TEHUACANA CREEK 80.0
END DESCRIPTION:
XS GIS Cut Line= 3
      3561150.52     10661673.49      3560903.13     10658991.24
      3564014.76     10655085.42
#Sta/Elev= 30
    2629  322.79  3024.5  303.03  3238.8  297.34  3536.1  295.07  3837.4   299.6
  3937.8  297.18  4215.8  300.43  4229.1  297.61  4239.1  300.46    4922  302.01
  4972.2  292.13  4978.5  285.74  4989.3  284.52    4992  284.02  4995.3  284.52
  5032.5  289.42  5072.6  304.06    5153  300.02  6053.2  295.27  6772.3  297.78
  7548.7  293.68  8686.6     297  8708.5  293.83  8750.5  296.77  9099.3  296.69
  9404.4  308.41  9830.8  330.79  9964.7     341 10131.3  349.06 10316.4  347.96
#Mann= 6 ,-1 , 0
    2629     .12       0  4989.3     .07       0  4995.3     .12       0
  9404.4     .16       0  9830.8     .12       0  9964.7     .05       0
Bank Sta=4922,5072.6
XS Rating Curve= 0 ,0
Exp/Cntr=0.3,0.1

Type RM Length L Ch R = 1 ,157152  ,1806,1806,1806
BEGIN DESCRIPTION:
TEHUACANA CREEK 79.0
END DESCRIPTION:
XS GIS Cut Line= 4
      3561149.62     10661660.14      3561549.61     10660060.19
      3563257.95     10657924.76      3565701.95     10654806.99
#Sta/Elev= 30
    3342  322.12  3731.1  306.78  3939.5  305.47  4079.4  306.15    4548  294.95
  4926.8  300.93  4977.9  283.67  4980.6  283.17  4983.9  283.67  5012.8  287.97
  5027.2  299.93  5041.6   301.5  5176.1  297.42  5225.7  302.55  5304.1  297.39
  7594.9  293.29  7616.5  289.45  7638.1  293.01  9685.5  302.01  9711.3  302.45
  9822.1     305 10216.2  323.19 10557.9  313.42   10920  332.22 11085.9  340.78
 11299.2  337.29 11305.6  333.57 11462.9   341.4 11562.3  337.66 11687.4  343.12
#Mann= 9 ,-1 , 0
    3342     .12       0  3939.5     .05       0  4079.4     .12       0
  4977.9     .07       0  4983.9     .12       0  9685.5     .16       0
  9711.3     .05       0  9822.1     .16       0   10920     .05       0
Bank Sta=4926.8,5041.6
XS Rating Curve= 0 ,0
Exp/Cntr=0.3,0.1

Type RM Length L Ch R = 1 ,155346  ,976,976,976
BEGIN DESCRIPTION:
TEHUACANA CREEK 78.0
END DESCRIPTION:
XS GIS Cut Line= 4
      3561199.63     10661710.17      3562999.61     10659710.19
      3564622.66     10658087.14      3566681.13     10656010.11
#Sta/Elev= 30
  2322.7  323.54  2565.5  315.92  2686.8  311.27  3654.2  305.71  3830.6  300.64
  4312.7  293.73  4935.3   300.5  4949.5  289.84  4989.1  282.59  4991.8  282.09
  4995.1  282.59  5016.9  285.03  5027.5  293.21  5055.8  300.26  6144.8  294.16
  6173.1   289.7  6201.3  294.13  7926.7  292.92  8138.8  298.54  8336.8  296.76
  8612.6  320.42    8752  320.27  9319.7  340.87  9524.8   331.4    9546  325.56
  9560.1  314.19  9595.5  328.58  9904.5  346.76 10037.4  350.38   10233  356.15
#Mann= 9 ,-1 , 0
  2322.7     .12       0  2565.5     .16       0  2686.8     .05       0
  3830.6     .12       0  4989.1     .07       0  4995.1     .12       0
    8752     .16       0  9904.5     .05       0 10037.4     .16       0
Bank Sta=4935.3,5055.8
XS Rating Curve= 0 ,0
Exp/Cntr=0.3,0.1

Type RM Length L Ch R = 1 ,154370  ,966,966,966
BEGIN DESCRIPTION:
TEHUACANA CREEK 77.0
END DESCRIPTION:
XS GIS Cut Line= 3
      3562099.62     10662010.17      3563099.61     10660210.19
      3566099.58     10657210.22
#Sta/Elev= 30
  2946.8  321.37  3475.3  307.13  3724.7  308.32  3999.2   301.6  4344.5  299.67
    4665   294.9  4756.8  293.74  4960.1  300.27  4970.4  299.31  4976.2  289.46
  4994.9  282.52  4997.6  282.02  5000.9  282.52  5009.4  282.61  5048.3  300.03
  5868.6  293.59  6363.5  295.45  6391.8  291.14    6406  295.42  6547.4  294.78
  6561.5  294.47  6575.7  287.73  6589.8  295.16    6604  295.77  6971.7  291.54
  8173.7  291.19  8357.6  294.02  8739.4  314.53  9110.3  326.89  9248.5  335.86
#Mann= 7 ,-1 , 0
  2946.8     .16       0  4344.5     .12       0    4665     .16       0
  4756.8     .12       0  4994.9     .07       0  5000.9     .12       0
  9110.3     .16       0
Bank Sta=4960.1,5048.3
XS Rating Curve= 0 ,0
Exp/Cntr=0.3,0.1

Type RM Length L Ch R = 1 ,153404  ,982,982,982
BEGIN DESCRIPTION:
TEHUACANA CREEK 76.0
END DESCRIPTION:
XS GIS Cut Line= 3
       3562299.6      10661860.2      3563899.61     10660260.19
      3566599.59     10657560.21
#Sta/Elev= 30
  2737.6  316.84  3464.6  299.74  3826.6  293.76  4660.9   299.5  4675.1  299.45
  4717.5  282.35  4728.7  282.33  4731.4  281.83  4734.7  282.33  4830.7  283.32
  4873.1  297.95  4915.5     292  4957.9  295.38  4972.1  287.29  5003.9  282.66
  5056.9   299.5  5240.8  294.29  5551.9  296.01  5580.2  286.56  5594.3  295.56
  5608.5  295.84  7121.7  290.43  7234.8  294.15  7263.1  290.48  7752.1  303.78
    8063  319.16  8067.4  319.57  8350.6  338.74  8535.9  347.67  8818.7  349.92
#Mann= 8 ,-1 , 0
  2737.6     .16       0  3464.6     .12       0  4728.7     .07       0
  4734.7     .12       0  7752.1     .16       0    8063     .12       0
  8067.4     .16       0  8350.6     .05       0
Bank Sta=4660.9,5056.9
XS Rating Curve= 0 ,0
Exp/Cntr=0.3,0.1

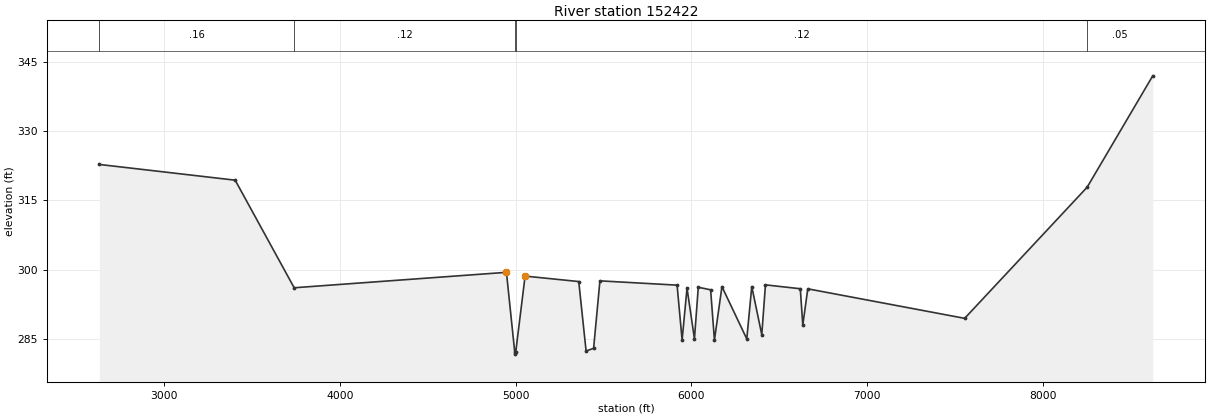
Type RM Length L Ch R = 1 ,152422  ,2048,2048,2048
BEGIN DESCRIPTION:
TEHUACANA CREEK 75.0
END DESCRIPTION:
XS GIS Cut Line= 3
      3562392.96     10662715.33      3564149.61     10661110.19
      3566549.58     10658410.22
#Sta/Elev= 30
  2632.1  322.81  3404.8   319.4  3740.4  296.07  4947.8  299.42  4994.8  282.18
  4997.5  281.68  5000.8  282.18  5053.9   298.6  5359.1  297.42  5400.9  282.35
  5443.6  282.94  5479.5  297.57  5918.5  296.64    5947  284.73    5975  295.99
  6017.2  284.99    6039  296.18  6109.2  295.63  6130.9  284.72  6173.6  296.32
  6314.9  284.98  6343.3  296.33  6400.2  285.89  6421.1   296.7  6619.3  295.86
  6633.5  287.97  6661.9  295.84  7554.2  289.44  8251.1  317.88  8624.1  342.03
#Mann= 5 ,-1 , 0
  2632.1     .16       0  3740.4     .12       0  4994.8     .07       0
  5000.8     .12       0  8251.1     .05       0
Bank Sta=4947.8,5053.9
XS Rating Curve= 0 ,0
Exp/Cntr=0.3,0.1