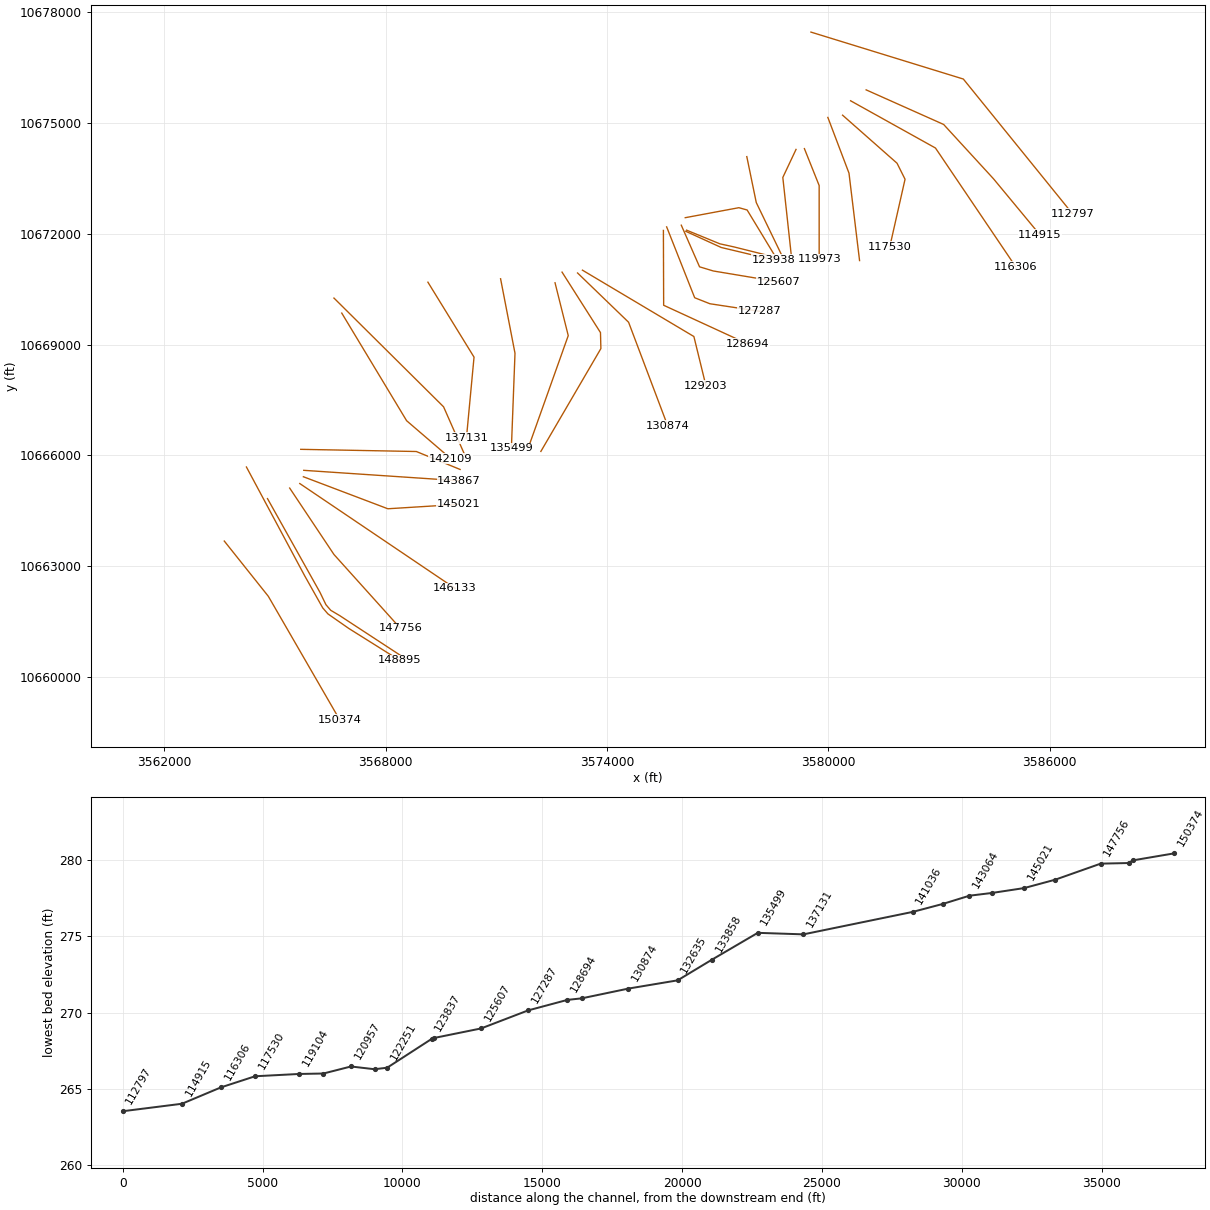
HEC-RAS study TEHUACANA CREEK.prj: TEHUACANA CREEK Base Level Engineering

--- TEHUACANA CREEK.g01 (geometry) --- (continued)

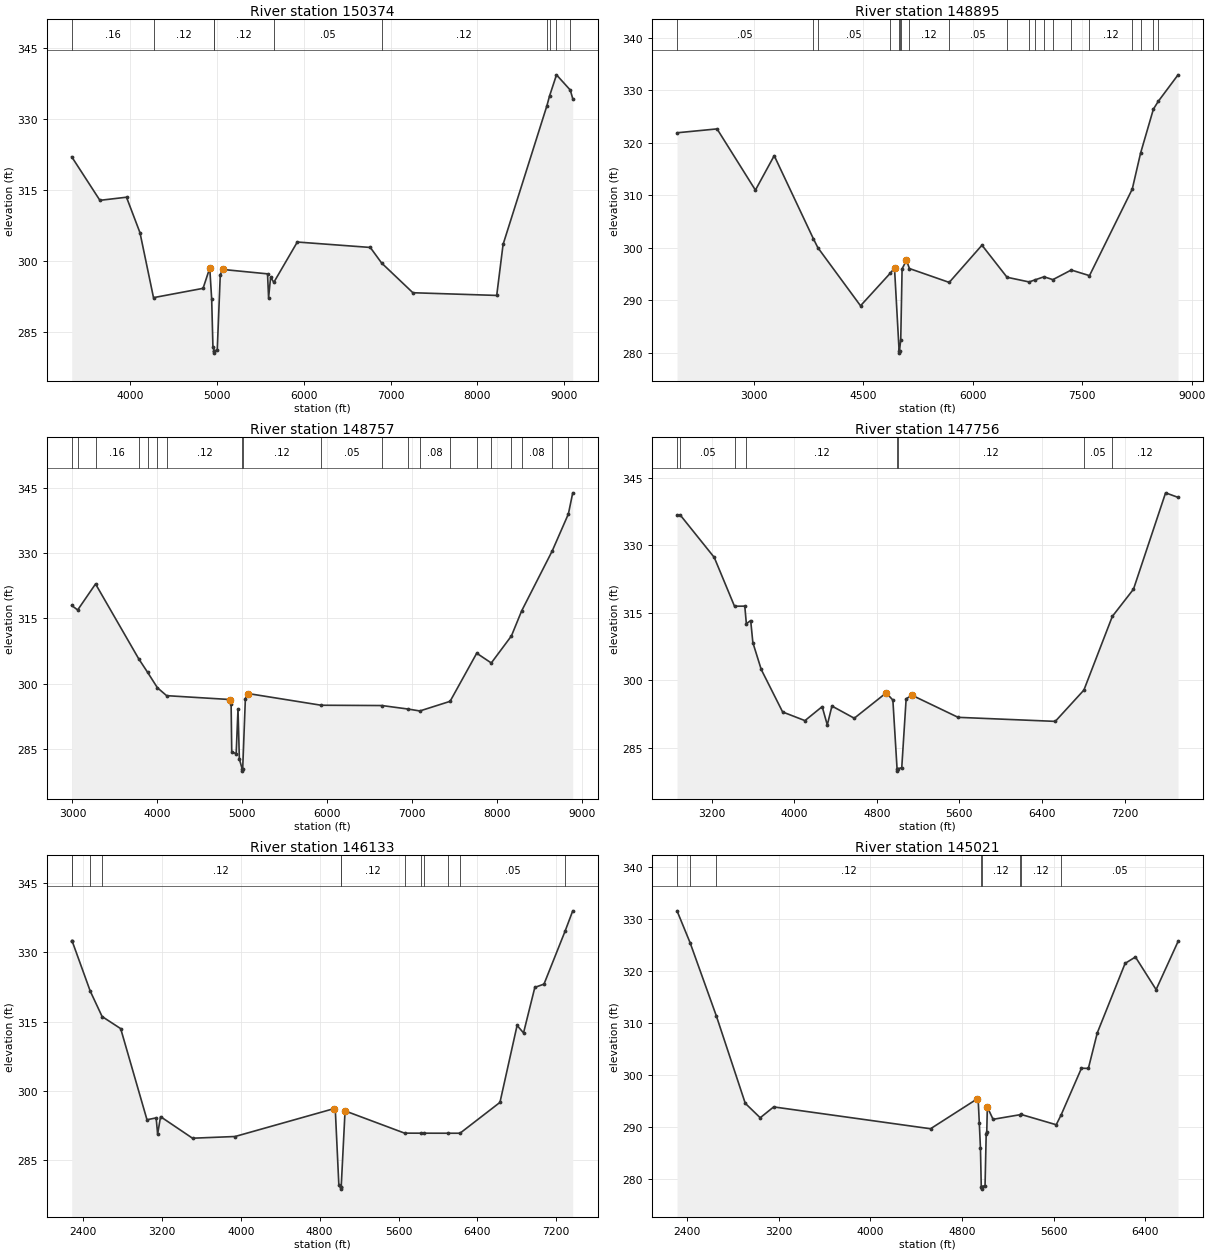
Type RM Length L Ch R = 1 ,150374  ,1479,1479,1479
BEGIN DESCRIPTION:
TEHUACANA CREEK 74.0
END DESCRIPTION:
XS GIS Cut Line= 3
       3563627.3     10663674.22      3564820.87     10662176.83
      3566752.16     10658835.05
#Sta/Elev= 30
  3323.6     322  3648.5  312.78    3955  313.44  4110.3  305.93  4266.3  292.17
  4837.4  294.14  4914.5  298.44  4936.7  291.88  4951.1  281.82  4962.5  280.92
  4965.2  280.42  4968.5  280.92  5000.7     281  5035.9  297.04  5064.8  298.14
  5580.5  297.21  5592.7  292.16  5615.8  296.49    5653  295.41  5923.6  303.95
  6764.9   302.8  6895.6   299.5  7255.8  293.21    8222  292.64  8295.3  303.44
  8800.2   332.8  8830.3  334.85  8910.9  339.36  9069.9  336.13  9098.2  334.31
#Mann= 10 ,-1 , 0
  3323.6     .16       0  4266.3     .12       0  4962.5     .07       0
  4968.5     .12       0    5653     .05       0  6895.6     .12       0
  8800.2     .16       0  8830.3     .05       0  8910.9     .16       0
  9069.9     .05       0
Bank Sta=4914.5,5064.8
XS Rating Curve= 0 ,0
Exp/Cntr=0.3,0.1

Type RM Length L Ch R = 1 ,148895  ,138,138,138
BEGIN DESCRIPTION:
TEHUACANA CREEK 73.0
END DESCRIPTION:
XS GIS Cut Line= 6
      3564227.08     10665681.27      3565807.49     10662730.25
      3566295.77      10661862.2      3566436.83     10661699.44
      3567002.69     10661305.12      3568372.52     10660445.73
#Sta/Elev= 30
  1947.3  321.93  2495.7  322.67  3021.4  311.01    3279  317.57  3814.7  301.78
  3877.5  300.04  4461.9  288.98  4870.4   295.2  4927.5  296.17  4990.3  280.46
    4993  279.96  4996.3  280.46    5013  282.53  5031.5  296.01  5090.7  297.63
  5132.3  296.07  5677.3  293.43    6126  300.52  6469.6  294.41    6772  293.52
  6852.3  293.91    6976   294.5    7098  293.96  7349.7  295.79  7599.4  294.72
  8185.5   311.2    8299  318.02  8475.4  326.44  8542.2  327.92  8813.2  332.97
#Mann= 20 ,-1 , 0
  1947.3     .05       0  3814.7     .16       0  3877.5     .05       0
  4870.4     .12       0  4990.3     .07       0  4996.3     .12       0
    5013     .05       0  5132.3     .12       0  5677.3     .05       0
  6469.6     .12       0    6772     .12       0  6852.3     .05       0
    6976     .16       0    7098     .12       0  7349.7     .12       0
  7599.4     .12       0  8185.5     .05       0    8299     .16       0
  8475.4     .16       0  8542.2     .05       0
Bank Sta=4927.5,5090.7
XS Rating Curve= 0 ,0
Exp/Cntr=0.3,0.1

Type RM Length L Ch R = 1 ,148757  ,1001,1001,1001
BEGIN DESCRIPTION:
TEHUACANA CREEK 72.0
END DESCRIPTION:
XS GIS Cut Line= 6
      3564798.38     10664824.43      3566219.82     10662285.37
      3566382.58       10661949.      3566512.78     10661797.09
       3566751.5     10661656.03      3568541.08     10660484.66
#Sta/Elev= 30
  2991.7     318  3061.9  316.97  3272.3  322.97  3780.6   305.7  3884.9   302.6
  4000.5  299.03  4109.2   297.2  4853.2  296.31  4868.8  295.23  4876.1  284.24
  4928.2   283.8  4949.9  294.12  4965.9  282.59  4999.1  280.29  5001.9  279.79
  5005.1  280.29  5036.7  296.54  5068.6  297.69  5928.9  294.99  6644.2  294.92
  6953.4  294.11    7091  293.67  7447.3  295.89  7760.9  306.99  7932.6  304.74
  8169.7  310.98    8290  316.75  8651.2  330.63  8840.3  339.11  8891.8  343.99
#Mann= 20 ,-1 , 0
  2991.7     .12       0  3061.9     .05       0  3272.3     .16       0
  3780.6     .05       0  3884.9     .12       0  4000.5     .05       0
  4109.2     .12       0  4999.1     .07       0  5005.1     .12       0
  5928.9     .05       0  6644.2     .12       0  6953.4     .05       0
    7091     .08       0  7447.3     .05       0  7760.9     .05       0
  7932.6     .05       0  8169.7     .12       0    8290     .08       0
  8651.2     .05       0  8840.3     .08       0
Bank Sta=4853.2,5068.6
XS Rating Curve= 0 ,0
Exp/Cntr=0.3,0.1

Type RM Length L Ch R = 1 ,147756  ,1623,1623,1623
BEGIN DESCRIPTION:
TEHUACANA CREEK 71.0
END DESCRIPTION:
XS GIS Cut Line= 3
      3565399.59     10665110.21      3566599.61     10663310.19
      3568399.62     10661310.17
#Sta/Elev= 30
  2864.5  336.66  2897.2  336.64  3225.1  327.26  3421.3  316.41    3521  316.43
  3536.1  312.53  3578.1  313.22  3599.2  308.32  3680.3  302.35  3887.6   292.9
  4103.9  290.98  4270.7  294.09  4320.3  290.01  4365.3  294.22  4581.7  291.51
  4891.1  297.15  4955.7  295.54  4996.3  280.25  4999.1  279.75  5002.3  280.25
  5041.7  280.52  5084.3  295.84  5141.1  296.62  5587.3  291.71  6529.1  290.81
  6806.4  297.77  7081.8  314.15  7286.9   320.2  7597.9  341.62  7718.6  340.61
#Mann= 8 ,-1 , 0
  2864.5     .12       0  2897.2     .05       0  3421.3     .16       0
  3536.1     .12       0  4996.3     .07       0  5002.3     .12       0
  6806.4     .05       0  7081.8     .12       0
Bank Sta=4891.1,5141.1
XS Rating Curve= 0 ,0
Exp/Cntr=0.3,0.1

Type RM Length L Ch R = 1 ,146133  ,1112,1112,1112
BEGIN DESCRIPTION:
TEHUACANA CREEK 69.0
END DESCRIPTION:
XS GIS Cut Line= 2
      3565673.14     10665232.96      3569883.18      10662390.1
#Sta/Elev= 30
  2286.6  332.51  2290.6  332.46  2474.3   321.6  2594.7  316.09    2783  313.47
  3049.8  293.73  3142.7  294.13  3157.7   290.6  3187.3   294.4  3511.3  289.73
    3943   290.1  4944.1  296.13    4959  295.94    4995  279.63    5013   279.2
  5015.8   278.7    5019   279.2    5058  295.65  5661.6  290.83  5824.2  290.82
  5856.2  290.82  6100.8  290.81  6223.5  290.81  6628.6  297.49  6802.4  314.17
  6867.6  312.54  6982.2   322.4  7075.2  323.12  7289.4  334.61  7366.6  338.99
#Mann= 12 ,-1 , 0
  2286.6     .12       0  2290.6     .05       0  2474.3     .16       0
  2594.7     .12       0    5013     .07       0    5019     .12       0
  5661.6     .07       0  5824.2     .16       0  5856.2     .07       0
  6100.8     .16       0  6223.5     .05       0  7289.4     .16       0
Bank Sta=4944.1,5058
XS Rating Curve= 0 ,0
Exp/Cntr=0.3,0.1

Type RM Length L Ch R = 1 ,145021  ,1154,1154,1154
BEGIN DESCRIPTION:
TEHUACANA CREEK 68.0
END DESCRIPTION:
XS GIS Cut Line= 3
      3565770.81     10665417.43      3568060.26     10664549.39
      3569980.87     10664668.75
#Sta/Elev= 30
  2312.7  331.53  2426.9   325.4    2657   311.3  2908.2  294.61  3038.7  291.84
  3156.3  293.92  4525.2  289.73  4930.9  295.44  4940.9  295.34  4950.9  290.87
  4960.9  285.99  4967.9  278.65  4970.7  278.15  4973.9  278.65    5001  278.81
  5010.9  288.64    5016   289.2    5021  293.88  5071.1  291.54    5308  292.43
  5314.5  292.48  5622.2   290.5  5665.5  292.41  5842.6  301.35  5902.7   301.3
  5980.5  308.12  6223.4  321.45  6313.5  322.68  6493.9  316.42  6685.5  325.65
#Mann= 8 ,-1 , 0
  2312.7     .12       0  2426.9     .05       0    2657     .12       0
  4967.9     .07       0  4973.9     .12       0    5308     .16       0
  5314.5     .12       0  5665.5     .05       0
Bank Sta=4930.9,5021
XS Rating Curve= 0 ,0
Exp/Cntr=0.3,0.1

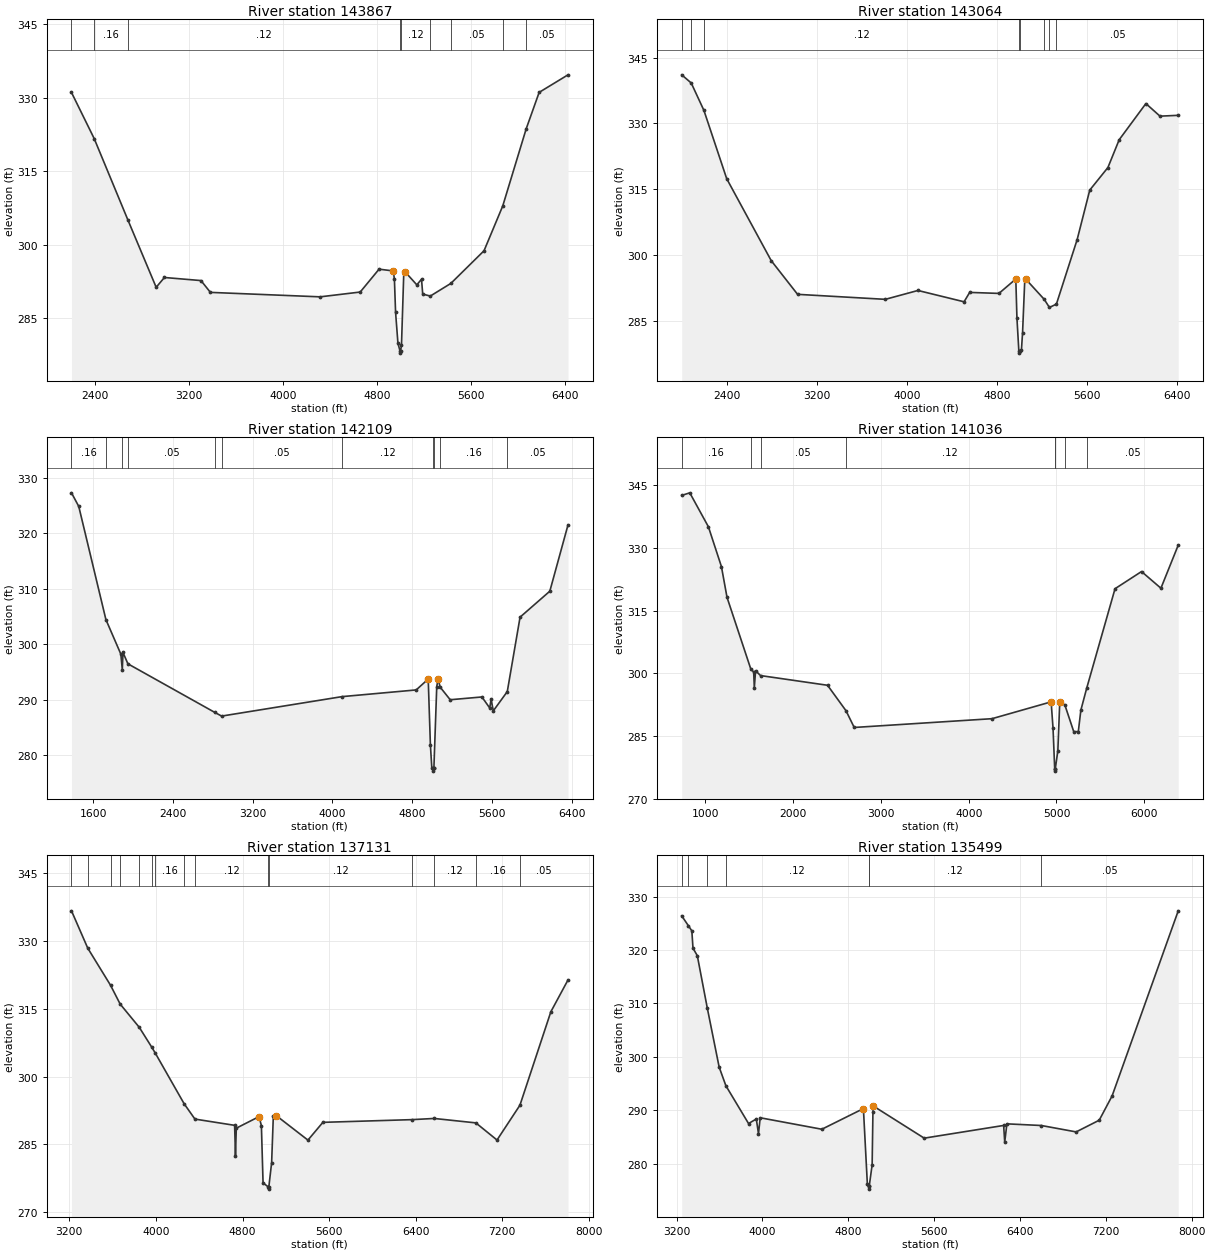
Type RM Length L Ch R = 1 ,143867  ,803,803,803
BEGIN DESCRIPTION:
TEHUACANA CREEK 67.0
END DESCRIPTION:
XS GIS Cut Line= 2
      3565781.62     10665591.06      3569991.68     10665308.94
#Sta/Elev= 30
  2202.6  331.04  2395.2  321.64  2681.5  305.04  2922.2  291.27  2992.4  293.27
    3303  292.64  3383.2  290.23  4315.3  289.32  4656.1   290.3  4816.4  294.97
  4936.7  294.61  4946.7  292.95  4956.7  286.16  4976.8  279.83  4993.8  278.33
  4996.6  277.83  4999.8  278.33  5006.9  279.49  5026.9  294.57  5036.9  294.44
  5137.2  291.77  5177.2  292.91  5187.3  289.88  5251.9  289.48  5426.3  292.06
  5708.4  298.73  5867.5  307.88  6066.4   323.6  6176.8  331.06  6422.1  334.64
#Mann= 9 ,-1 , 0
  2202.6     .12       0  2395.2     .16       0  2681.5     .12       0
  4993.8     .07       0  4999.8     .12       0  5251.9     .16       0
  5426.3     .05       0  5867.5     .16       0  6066.4     .05       0
Bank Sta=4936.7,5036.9
XS Rating Curve= 0 ,0
Exp/Cntr=0.3,0.1

Type RM Length L Ch R = 1 ,143064  ,955,955,955
BEGIN DESCRIPTION:
TEHUACANA CREEK 66.0
END DESCRIPTION:
XS GIS Cut Line= 3
      3565699.58     10666160.19      3568832.01     10666101.17
      3570018.19     10665615.07
#Sta/Elev= 30
  1995.6  341.08  2080.1  339.22    2193  332.97  2395.7   317.4  2791.3  298.73
  3025.8  291.05  3805.9  289.91    4096  291.93  4506.1  289.35  4556.1  291.49
  4816.1  291.26  4966.2  294.54  4976.2  285.67  4993.2  278.15  4995.9  277.65
  4999.2  278.15  5016.2  278.35  5026.2  282.25  5046.2  294.47  5056.2  294.47
  5218.5  289.92  5265.1  288.06  5327.2  288.82  5511.6  303.52  5623.8  314.81
  5785.2  319.95  5885.3  326.28  6122.9  334.53  6248.2  331.66  6410.5  331.85
#Mann= 8 ,-1 , 0
  1995.6     .12       0  2080.1     .16       0    2193     .12       0
  4993.2     .07       0  4999.2     .12       0  5218.5     .05       0
  5265.1     .16       0  5327.2     .05       0
Bank Sta=4966.2,5056.2
XS Rating Curve= 0 ,0
Exp/Cntr=0.3,0.1

Type RM Length L Ch R = 1 ,142109  ,1073,1073,1073
BEGIN DESCRIPTION:
TEHUACANA CREEK 65.0
END DESCRIPTION:
XS GIS Cut Line= 3
      3566810.89     10669852.62      3568568.69     10666935.98
      3569765.58     10665908.21
#Sta/Elev= 30
    1382  327.32  1454.9  324.87  1727.4  304.45  1877.3  298.22  1891.9  295.43
  1898.7  298.53  1948.1  296.47  2821.5  287.69  2888.9  287.04  4096.5  290.55
  4841.3  291.76    4962  293.72  4983.9  281.84  4998.2  277.67  5009.5  277.61
  5012.2  277.11  5015.5  277.61  5019.1  277.73  5047.6  292.37  5061.9  293.75
  5081.9  292.26  5182.6  289.99  5500.8  290.49  5579.5   288.5    5593  290.11
    5615  287.98  5755.5  291.46  5883.8  304.89  6182.3  309.57    6365  321.54
#Mann= 11 ,-1 , 0
    1382     .16       0  1727.4     .12       0  1891.9     .16       0
  1948.1     .05       0  2821.5     .16       0  2888.9     .05       0
  4096.5     .12       0  5009.5     .07       0  5015.5     .12       0
  5081.9     .16       0  5755.5     .05       0
Bank Sta=4962,5061.9
XS Rating Curve= 0 ,0
Exp/Cntr=0.3,0.1

Type RM Length L Ch R = 1 ,141036  ,3905,3905,3905
BEGIN DESCRIPTION:
TEHUACANA CREEK 64.0
END DESCRIPTION:
XS GIS Cut Line= 3
      3566599.64     10670260.16      3569570.65     10667312.84
      3570164.13     10665964.49
#Sta/Elev= 30
   729.3  342.58   821.2   343.2  1033.3  335.08  1181.8  325.55  1245.5  318.19
  1518.3  300.92  1549.5  300.34  1556.6  296.49  1570.7  300.61  1627.8  299.46
    2391  297.14  2601.6  291.04    2695  287.04  4264.8  289.14    4939  293.17
  4960.8   286.8  4979.7  277.09  4982.4  276.59  4985.7  277.09  5015.4  281.42
  5037.3  293.18  5095.5  292.42  5196.4  286.05  5248.6  286.04  5277.7  291.18
  5343.3  296.37  5667.1  320.25    5969  324.36    6190  320.37  6387.4  330.68
#Mann= 8 ,-1 , 0
   729.3     .16       0  1518.3     .12       0  1627.8     .05       0
  2601.6     .12       0  4979.7     .07       0  4985.7     .12       0
  5095.5     .16       0  5343.3     .05       0
Bank Sta=4939,5037.3
XS Rating Curve= 0 ,0
Exp/Cntr=0.3,0.1

Type RM Length L Ch R = 1 ,137131  ,1632,1632,1632
BEGIN DESCRIPTION:
TEHUACANA CREEK 63.0
END DESCRIPTION:
XS GIS Cut Line= 3
      3569145.96      10670690.3      3570395.95     10668659.07
      3570189.78     10666467.18
#Sta/Elev= 30
  3220.1  336.67  3370.4  328.41  3580.7  320.21  3669.6  316.05  3846.4   310.9
  3960.2  306.56    3992  305.29  4260.6     294  4360.4  290.61    4727  289.23
  4734.9  282.48  4742.4   288.6    4953  291.16  4974.3  289.14  4989.7   276.5
  5037.2  275.62    5040  275.12  5043.2  275.62  5068.9  280.99  5084.4  291.21
  5111.5  291.38  5404.2  285.96  5542.3  289.89  6367.2  290.49  6570.3  290.75
  6955.4  289.77  7150.8  285.98  7362.5  293.68  7648.2  314.35  7806.7  321.39
#Mann= 15 ,-1 , 0
  3220.1     .16       0  3370.4     .05       0  3580.7     .16       0
  3669.6     .05       0  3846.4     .16       0  3960.2     .12       0
    3992     .16       0  4260.6     .05       0  4360.4     .12       0
  5037.2     .07       0  5043.2     .12       0  6367.2     .16       0
  6570.3     .12       0  6955.4     .16       0  7362.5     .05       0
Bank Sta=4953,5111.5
XS Rating Curve= 0 ,0
Exp/Cntr=0.3,0.1

Type RM Length L Ch R = 1 ,135499  ,1641,1641,1641
BEGIN DESCRIPTION:
TEHUACANA CREEK 62.0
END DESCRIPTION:
XS GIS Cut Line= 3
       3571115.5     10670782.79      3571506.12     10668764.59
       3571408.5      10666194.1
#Sta/Elev= 30
  3247.2  326.42  3308.1  324.61  3341.5  323.61  3352.3  320.36  3392.5  318.96
  3486.1  309.09  3596.2  298.08  3659.1  294.58  3870.1  287.51  3942.5  288.36
  3962.8   285.6  3978.7  288.59  4553.3  286.44  4940.7  290.31  4977.7   276.1
  4988.6  275.72  4991.3  275.22  4994.6  275.72  5022.1  279.78  5029.5  289.67
  5034.6  290.77  5507.4  284.77  6247.9  287.15  6257.9  284.03    6278  287.45
  6599.2  287.14  6923.6  285.94  7138.6  288.13  7258.7  292.68  7875.2  327.36
#Mann= 7 ,-1 , 0
  3247.2     .16       0  3308.1     .05       0  3486.1     .16       0
  3659.1     .12       0  4988.6     .07       0  4994.6     .12       0
  6599.2     .05       0
Bank Sta=4940.7,5034.6
XS Rating Curve= 0 ,0
Exp/Cntr=0.3,0.1

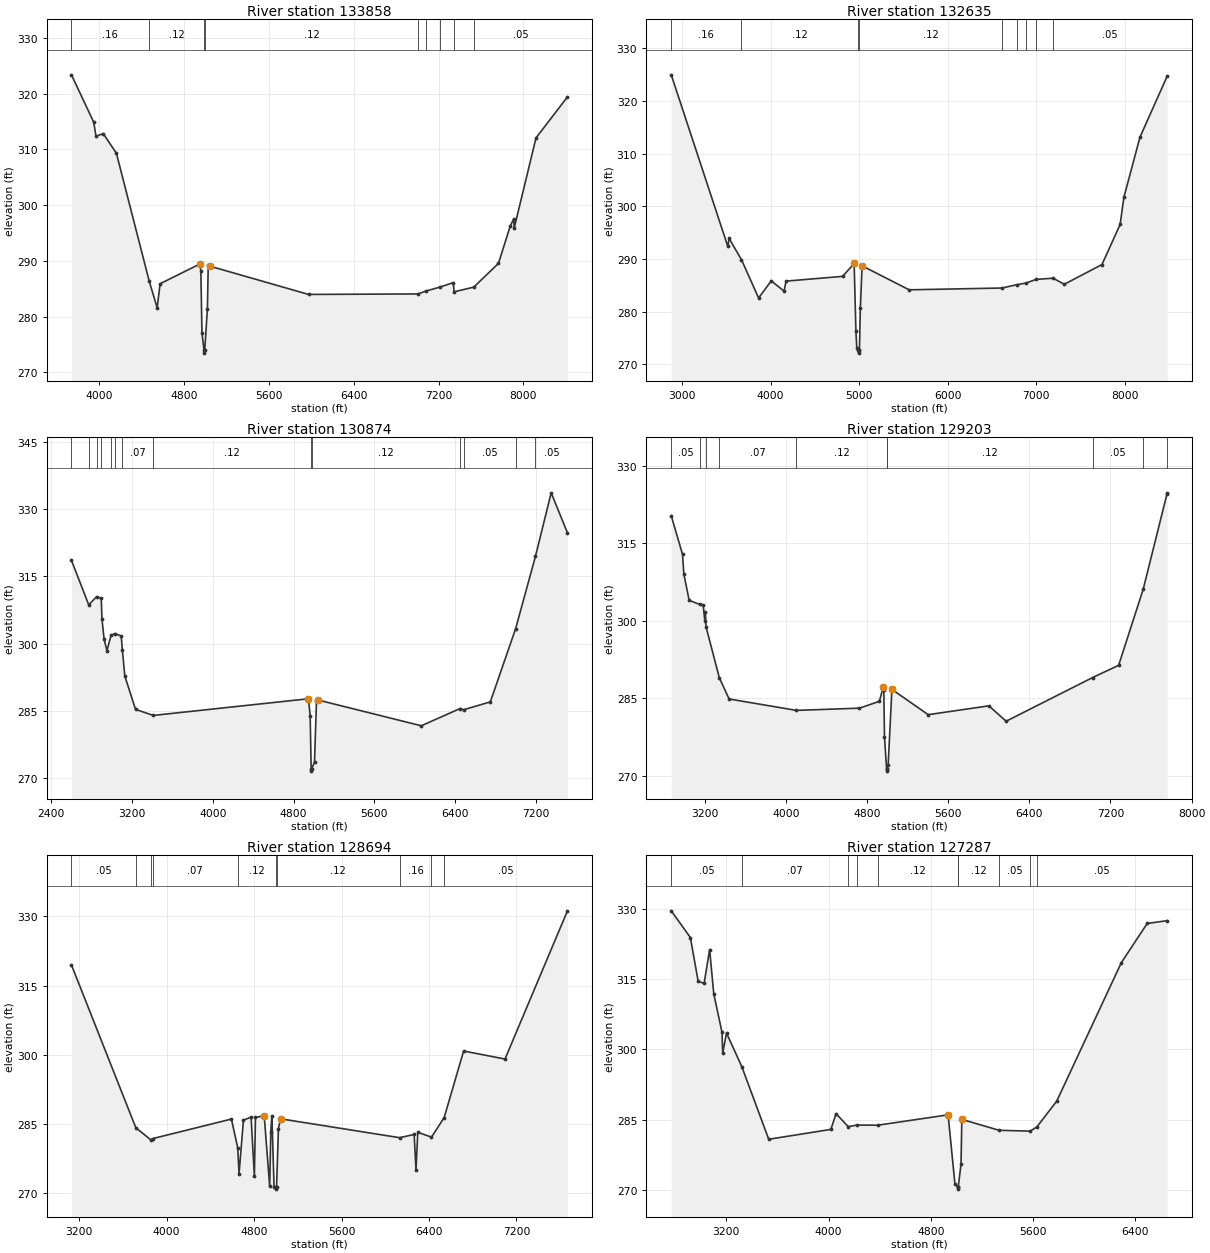
Type RM Length L Ch R = 1 ,133858  ,1223,1223,1223
BEGIN DESCRIPTION:
TEHUACANA CREEK 61.0
END DESCRIPTION:
XS GIS Cut Line= 3
       3572591.2     10670674.28      3572949.26     10669242.02
      3571875.04     10666225.52
#Sta/Elev= 30
  3736.8  323.39  3947.2  314.87  3967.8  312.39  4037.1  312.83  4160.8  309.31
  4469.3  286.44    4545  281.59  4573.1  285.91  4949.4  289.47  4957.3   288.2
  4967.6  277.07  4987.6  273.96  4990.4  273.46  4993.6  273.96  5019.2  281.43
  5026.7  289.26  5039.8  289.08  5973.1  283.99  7006.3  284.08  7080.4   284.6
  7214.6  285.32  7338.1  286.11    7346  284.46  7531.3   285.3  7764.4  289.56
  7877.1  296.35  7907.9  297.51  7913.2  295.92  8118.4  312.07  8415.2  319.43
#Mann= 9 ,-1 , 0
  3736.8     .16       0  4469.3     .12       0  4987.6     .07       0
  4993.6     .12       0  7006.3     .05       0  7080.4      .1       0
  7214.6     .05       0    7346     .16       0  7531.3     .05       0
Bank Sta=4949.4,5039.8
XS Rating Curve= 0 ,0
Exp/Cntr=0.3,0.1

Type RM Length L Ch R = 1 ,132635  ,1761,1761,1761
BEGIN DESCRIPTION:
TEHUACANA CREEK 60.0
END DESCRIPTION:
XS GIS Cut Line= 4
      3572781.46     10670963.05       3573823.1     10669324.63
      3573833.95     10668890.61      3572207.27     10666103.56
#Sta/Elev= 30
  2877.8  324.94  3516.3  292.39  3531.5  293.87  3671.1  289.85  3864.7  282.58
  4007.4  285.83  4153.1  283.87  4174.3  285.78  4812.7  286.68  4943.8  289.13
  4963.8  276.33  4973.8  273.06  4990.8  272.61  4993.6  272.11  4996.8  272.61
  5003.8   272.7  5013.8  280.63  5033.8  288.68  5565.2  284.13  6614.3  284.47
  6778.1  285.09  6885.6  285.41    6999  286.11  7191.4  286.33    7318  285.18
  7743.4  288.93  7948.1  296.53  7991.1  301.71    8173  313.13  8480.5  324.71
#Mann= 9 ,-1 , 0
  2877.8     .16       0  3671.1     .12       0  4990.8     .07       0
  4996.8     .12       0  6614.3     .07       0  6778.1     .12       0
  6885.6     .07       0    6999     .12       0  7191.4     .05       0
Bank Sta=4943.8,5033.8
XS Rating Curve= 0 ,0
Exp/Cntr=0.3,0.1

Type RM Length L Ch R = 1 ,130874  ,1671,1671,1671
BEGIN DESCRIPTION:
TEHUACANA CREEK 59.0
END DESCRIPTION:
XS GIS Cut Line= 3
      3573201.92     10670939.86      3574584.71     10669604.81
      3575642.01     10666805.31
#Sta/Elev= 30
  2598.6  318.56  2769.7  308.63  2847.6  310.47  2893.7  310.07    2901  305.43
  2922.1  300.95  2950.3  298.43  2990.6  301.83  3029.3  302.24  3091.8   301.7
  3103.1  298.55  3127.1  292.79  3233.3  285.33  3409.9  283.99  4946.4   287.7
  4963.9  283.93  4973.6  272.07  4976.4  271.57  4979.6  272.07  5006.8  273.63
  5026.3  287.14  5038.7  287.44  6064.9  281.68  6450.1  285.53  6483.6  285.25
    6749  287.01    7000  303.36  7195.8  319.43  7351.9  333.61  7513.2  324.69
#Mann= 14 ,-1 , 0
  2598.6     .16       0  2769.7     .12       0  2847.6      .1       0
  2893.7     .12       0  2990.6     .05       0  3029.3     .12       0
  3103.1     .07       0  3409.9     .12       0  4973.6     .07       0
  4979.6     .12       0  6450.1     .07       0  6483.6     .05       0
    7000     .16       0  7195.8     .05       0
Bank Sta=4946.4,5038.7
XS Rating Curve= 0 ,0
Exp/Cntr=0.3,0.1

Type RM Length L Ch R = 1 ,129203  ,509,509,509
BEGIN DESCRIPTION:
TEHUACANA CREEK 58.0
END DESCRIPTION:
XS GIS Cut Line= 3
      3573333.84     10671016.27      3576354.67     10669217.66
      3576680.96     10667884.76
#Sta/Elev= 30
  2871.3  320.38  2982.8  312.87  2995.5  309.07  3048.1     304  3151.8   303.2
  3186.3  303.07  3201.9  300.08  3207.7   301.7  3213.3  298.93  3345.2     289
  3441.4   284.9  4104.1  282.69  4726.5  283.12  4923.2  284.45  4960.2  287.28
    4966  286.63  4972.9  277.56  4993.2  271.43  4995.9  270.93  4999.2  271.43
  5008.8  272.04  5045.8  286.76  5403.5  281.86  6001.9  283.57  6171.3  280.59
  7024.1  289.05  7280.1  291.41  7522.5  306.15    7757  324.61  7759.3  324.81
#Mann= 10 ,-1 , 0
  2871.3     .05       0  3151.8     .07       0  3213.3     .05       0
  3345.2     .07       0  4104.1     .12       0  4993.2     .07       0
  4999.2     .12       0  7024.1     .05       0  7522.5     .16       0
    7757     .05       0
Bank Sta=4960.2,5045.8
XS Rating Curve= 0 ,0
Exp/Cntr=0.3,0.1

Type RM Length L Ch R = 1 ,128694  ,1407,1407,1407
BEGIN DESCRIPTION:
TEHUACANA CREEK 57.0
END DESCRIPTION:
XS GIS Cut Line= 3
      3575528.29      10672092.7      3575535.23     10670064.88
      3577813.01     10669016.27
#Sta/Elev= 30
  3130.7  319.46    3719  284.16  3856.8  281.51  3875.2   281.8  4593.2  286.03
  4650.6  279.85  4663.2  274.22  4703.2  285.81  4773.2  286.43  4803.2  273.62
  4813.2  286.37  4893.2  286.75  4943.2  271.42  4953.2  283.23  4963.2  286.78
  4983.2   271.4  5000.2  271.33    5003  270.83  5006.2  271.33  5023.2  283.98
  5043.2  286.08  6131.6  281.99  6264.2  282.69  6281.2  274.96  6297.3  283.16
  6422.7  282.11  6538.9  286.36  6716.6  300.79  7095.1  299.05  7666.1   331.2
#Mann= 10 ,-1 , 0
  3130.7     .05       0    3719     .07       0  3856.8     .12       0
  3875.2     .07       0  4650.6     .12       0  5000.2     .07       0
  5006.2     .12       0  6131.6     .16       0  6422.7     .12       0
  6538.9     .05       0
Bank Sta=4893.2,5043.2
XS Rating Curve= 0 ,0
Exp/Cntr=0.3,0.1

Type RM Length L Ch R = 1 ,127287  ,1680,1680,1680
BEGIN DESCRIPTION:
TEHUACANA CREEK 56.0
END DESCRIPTION:
XS GIS Cut Line= 4
      3575616.41      10672189.4      3576375.94     10670268.87
      3576788.27     10670106.11      3578144.64     10669899.94
#Sta/Elev= 30
  2769.5  329.59  2919.2  323.89  2980.2  314.54  3026.7  314.09  3069.8  321.31
    3102  311.89  3166.5  303.66  3172.2  299.21  3201.9  303.48  3321.3  296.32
  3532.2  280.79  4018.4   282.9  4059.1  286.25  4154.2  283.49  4222.8  283.83
  4384.3  283.79  4935.5  286.01  4989.2  271.19  5009.2  270.64  5011.9  270.14
  5015.2  270.64  5036.5  275.47    5043  285.04  5333.9  282.71  5577.9  282.53
  5629.8  283.42  5785.2  288.93  6290.9  318.52  6493.2  326.89    6650  327.49
#Mann= 10 ,-1 , 0
  2769.5     .05       0  3321.3     .07       0  4154.2     .12       0
  4222.8     .07       0  4384.3     .12       0  5009.2     .07       0
  5015.2     .12       0  5333.9     .05       0  5577.9     .12       0
  5629.8     .05       0
Bank Sta=4935.5,5043
XS Rating Curve= 0 ,0
Exp/Cntr=0.3,0.1

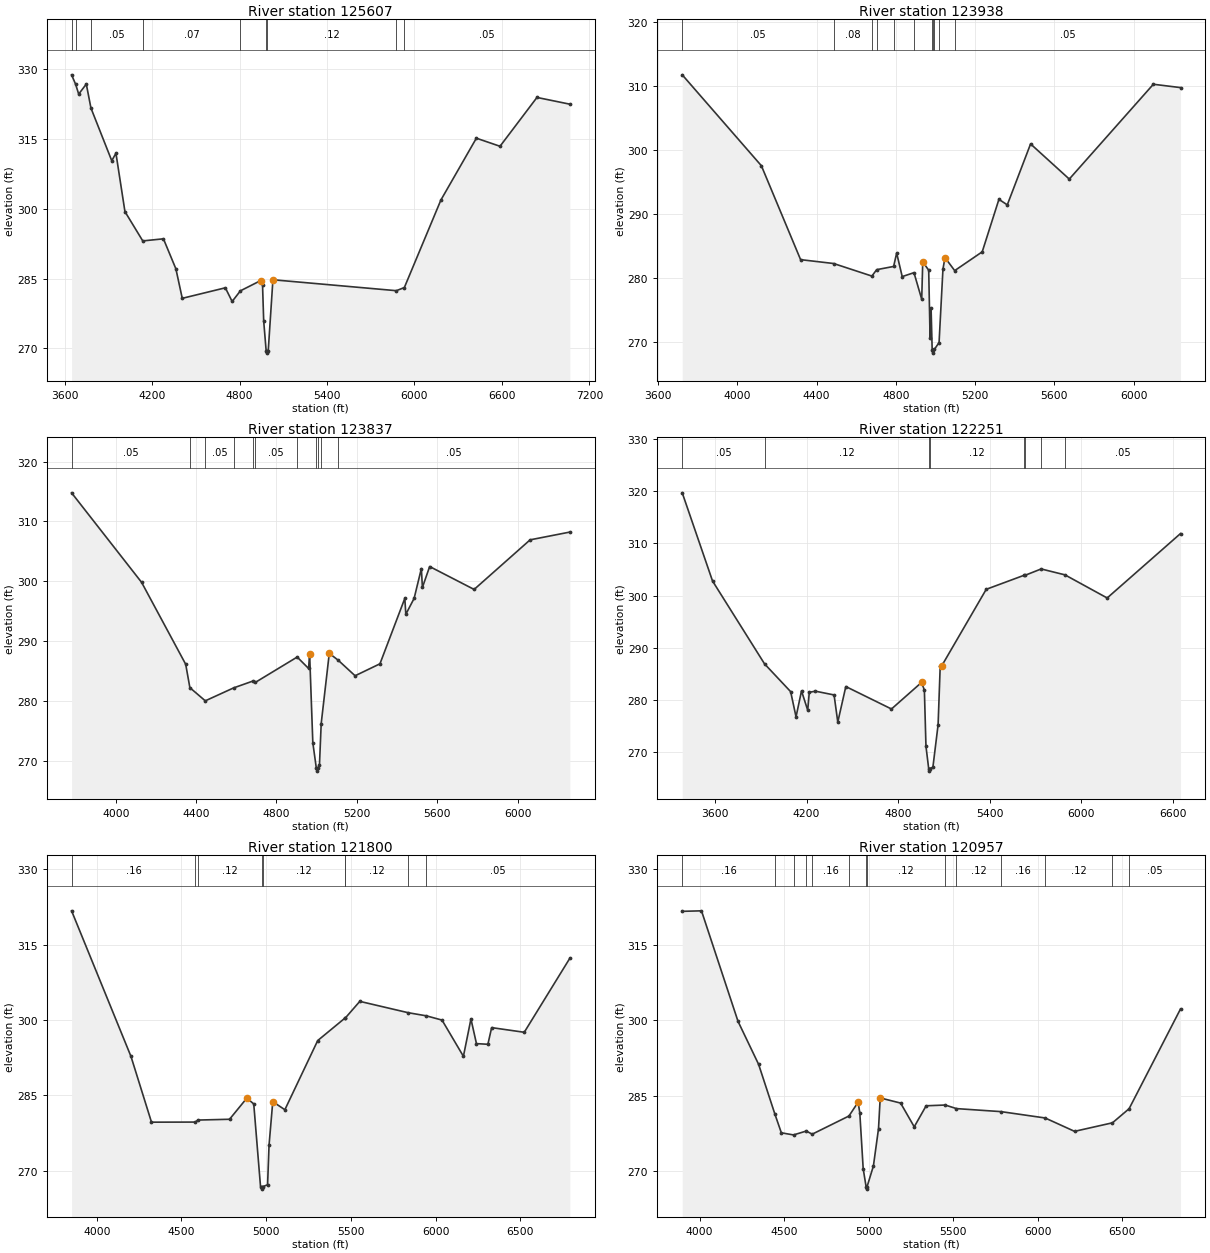
Type RM Length L Ch R = 1 ,125607  ,1669,1669,1669
BEGIN DESCRIPTION:
TEHUACANA CREEK 55.0
END DESCRIPTION:
XS GIS Cut Line= 4
      3576013.06     10672235.38      3576507.85     10671106.92
      3576881.11     10670994.07      3578651.97     10670698.93
#Sta/Elev= 30
  3648.1  328.78  3675.7  326.76  3696.9  324.64  3749.1  326.79  3780.9  321.64
  3923.6  310.32  3952.4  311.92  4014.1  299.38  4136.3  293.08  4278.1  293.53
  4363.5  287.08  4407.2  280.74  4702.7     283  4749.4  280.06    4806  282.35
  4944.8  284.55  4957.9  283.56  4965.7  275.88  4982.6  269.46  4985.4  268.96
  4988.6  269.46    4997   269.5    5029  284.73  5875.7  282.38  5930.5  283.06
  6181.1  301.87  6424.4  315.16  6586.6  313.42    6840  323.92  7065.5  322.47
#Mann= 9 ,-1 , 0
  3648.1     .05       0  3675.7     .08       0  3780.9     .05       0
  4136.3     .07       0    4806     .12       0  4982.6     .07       0
  4988.6     .12       0  5875.7     .16       0  5930.5     .05       0
Bank Sta=4944.8,5029
XS Rating Curve= 0 ,0
Exp/Cntr=0.3,0.1

Type RM Length L Ch R = 1 ,123938  ,101,101,101
BEGIN DESCRIPTION:
TEHUACANA CREEK 54.0
END DESCRIPTION:
XS GIS Cut Line= 3
      3576136.34     10672068.71      3577094.65     10671631.22
      3578515.58     10671292.91
#Sta/Elev= 30
  3722.3  311.72  4121.6  297.55  4319.5  282.91    4486  282.31  4679.2  280.35
  4703.4  281.35  4788.9  281.85  4804.2  283.94  4832.2  280.27  4891.6  280.88
  4930.6  276.74  4935.8  282.56  4965.9  281.27  4972.8  270.71  4977.9  275.32
  4983.4  268.84  4986.2  268.34  4989.4  268.84  4994.3  268.91  5018.2  269.99
  5037.8  281.44  5048.1  283.23    5097   281.2  5235.9  284.13  5320.2  292.31
  5362.4  291.45  5479.9  300.95  5675.2  295.47  6099.4  310.25  6236.4  309.73
#Mann= 11 ,-1 , 0
  3722.3     .05       0    4486     .08       0  4679.2     .05       0
  4703.4     .12       0  4788.9     .16       0  4891.6     .05       0
  4983.4     .07       0  4989.4     .05       0  4994.3     .08       0
  5018.2     .12       0    5097     .05       0
Bank Sta=4935.8,5048.1
XS Rating Curve= 0 ,0
Exp/Cntr=0.3,0.1

Type RM Length L Ch R = 1 ,123837  ,1586,1586,1586
BEGIN DESCRIPTION:
Mapping XS 9e6b3d4b
END DESCRIPTION:
XS GIS Cut Line= 4
      3576157.13     10672099.98      3577058.19     10671730.18
       3577438.4     10671646.85      3578521.73     10671376.02
#Sta/Elev= 30
  3780.1  314.79  4128.7  299.82  4348.1  286.13  4368.9  282.22  4445.6  280.02
  4586.4  282.18  4681.3  283.31  4695.1  283.11    4903  287.34  4959.7  285.43
  4964.8  287.92  4980.8  273.02  4998.2  268.77    5001  268.27  5004.2  268.77
  5013.8  269.26  5022.5  276.23  5062.7  287.96  5107.4   286.8  5191.2  284.21
  5314.9  286.21  5438.6  297.14  5443.7  294.49    5485  297.15    5521  302.13
  5526.2  298.97  5562.3  302.47  5783.7  298.64  6062.2  306.93    6260  308.23
#Mann= 11 ,-1 , 0
  3780.1     .05       0  4368.9     .12       0  4445.6     .05       0
  4586.4     .12       0  4681.3     .08       0  4695.1     .05       0
    4903     .12       0  4998.2     .07       0  5004.2     .12       0
  5022.5     .08       0  5107.4     .05       0
Bank Sta=4964.8,5062.7
XS Rating Curve= 0 ,0
Exp/Cntr=0.3,0.1

Type RM Length L Ch R = 1 ,122251  ,451,451,451
BEGIN DESCRIPTION:
Mapping XS f194b4d9
END DESCRIPTION:
XS GIS Cut Line= 4
      3576120.66     10672438.51      3577573.82     10672709.35
      3577797.78     10672646.85      3578604.69     10671315.26
#Sta/Elev= 30
  3384.6  319.69  3583.3   302.8  3924.4  286.93  4095.6  281.61  4130.9  276.79
  4166.8  281.76  4207.5  278.05  4217.7  281.49  4258.3   281.7  4380.4  280.98
  4404.7  275.78  4457.4  282.59  4756.8  278.29  4954.9   283.4  4972.6  281.88
    4983  271.14  5000.8  266.89  5003.5  266.39  5006.8  266.89  5028.4  267.12
  5062.6  275.28  5076.4  286.49  5086.8  286.57  5378.2  301.21  5626.5   303.9
  5630.1  303.86  5738.5  305.11  5894.5  303.98  6171.4  299.55  6652.3  311.89
#Mann= 8 ,-1 , 0
  3384.6     .05       0  3924.4     .12       0  5000.8     .07       0
  5006.8     .12       0  5626.5     .05       0  5630.1     .12       0
  5738.5     .16       0  5894.5     .05       0
Bank Sta=4954.9,5086.8
XS Rating Curve= 0 ,0
Exp/Cntr=0.3,0.1

Type RM Length L Ch R = 1 ,121800  ,843,843,843
BEGIN DESCRIPTION:
TEHUACANA CREEK 53.0
END DESCRIPTION:
XS GIS Cut Line= 3
      3577788.66     10674093.69       3578045.2     10672848.29
      3578772.63     10671344.54
#Sta/Elev= 30
    3851  321.74  4201.7  292.73  4322.8  279.63  4582.2  279.65  4596.2  280.05
  4783.7  280.21  4885.8  284.42  4926.6  283.27  4966.6  266.81  4974.7  266.79
  4977.4  266.29  4980.7  266.79  5008.3  267.16  5016.9  275.02  5038.9  283.72
  5110.4  282.11  5304.3  295.89    5465  300.36    5468  300.41  5552.8   303.7
  5838.6  301.44  5945.5  300.82  6038.3  299.97  6164.6  292.75  6209.1  300.19
  6241.6  295.28  6309.1  295.15  6331.3  298.47  6523.8  297.54    6793  312.29
#Mann= 9 ,-1 , 0
    3851     .16       0  4582.2     .05       0  4596.2     .12       0
  4974.7     .07       0  4980.7     .12       0    5465     .16       0
    5468     .12       0  5838.6     .16       0  5945.5     .05       0
Bank Sta=4885.8,5038.9
XS Rating Curve= 0 ,0
Exp/Cntr=0.3,0.1

Type RM Length L Ch R = 1 ,120957  ,984,984,984
BEGIN DESCRIPTION:
Mapping XS c657259b
END DESCRIPTION:
XS GIS Cut Line= 3
      3579122.88     10674288.59      3578764.79     10673529.01
      3578992.63     10671435.03
#Sta/Elev= 30
  3896.9  321.67  4010.7  321.77  4226.8   299.8  4348.4  291.27  4444.4  281.41
  4482.9  277.66  4554.8  277.24  4630.3  278.01  4665.3  277.39  4882.7     281
  4936.7  283.74  4946.7  281.65  4966.8  270.53  4983.9  266.97  4986.7  266.47
  4989.9  266.97  5027.2  271.07  5057.4  278.48  5067.4  284.59  5188.1  283.57
  5268.6  278.85    5339  283.03  5451.7  283.18  5518.4  282.47  5781.8  281.87
  6042.5  280.61  6216.6  277.95  6440.9  279.65  6539.1  282.45    6843  302.27
#Mann= 14 ,-1 , 0
  3896.9     .16       0  4444.4     .07       0  4554.8     .12       0
  4630.3     .07       0  4665.3     .16       0  4882.7     .12       0
  4983.9     .07       0  4989.9     .12       0  5451.7     .16       0
  5518.4     .12       0  5781.8     .16       0  6042.5     .12       0
  6440.9     .16       0  6539.1     .05       0
Bank Sta=4936.7,5067.4
XS Rating Curve= 0 ,0
Exp/Cntr=0.3,0.1

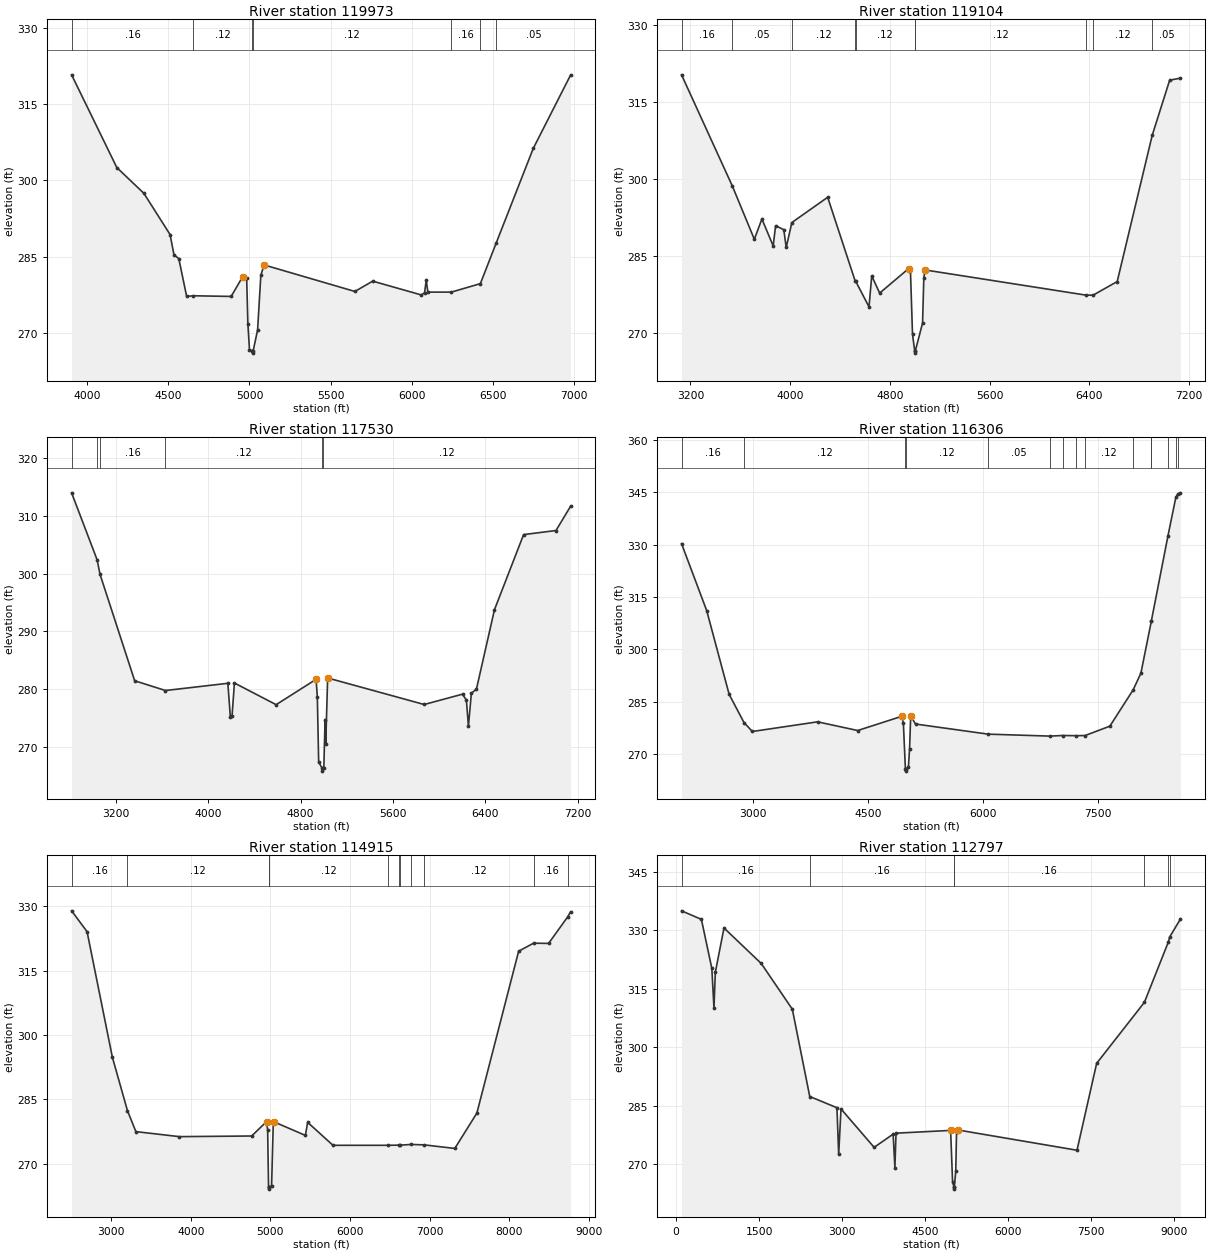
Type RM Length L Ch R = 1 ,119973  ,869,869,869
BEGIN DESCRIPTION:
TEHUACANA CREEK 52.0
END DESCRIPTION:
XS GIS Cut Line= 3
       3579349.6     10674310.21      3579749.61     10673310.19
      3579749.61     10671310.14
#Sta/Elev= 30
  3903.2  320.79  4181.9  302.54  4348.8  297.47  4510.4  289.35  4534.6  285.36
  4564.2  284.62  4612.7  277.18  4653.5   277.3  4887.4  277.17  4958.7  281.09
  4982.8  280.88  4990.3  271.77  5000.3  266.66  5017.3  266.51    5020  266.01
  5023.3  266.51  5050.3  270.58  5070.3  281.34  5090.3  283.37  5650.3  278.15
  5760.3  280.18  6060.3  277.46  6080.3  277.91  6090.3  280.41  6100.3  278.02
  6245.3  278.02  6424.3  279.69  6522.3  287.72  6750.3   306.3  6980.3  320.73
#Mann= 7 ,-1 , 0
  3903.2     .16       0  4653.5     .12       0  5017.3     .07       0
  5023.3     .12       0  6245.3     .16       0  6424.3     .12       0
  6522.3     .05       0
Bank Sta=4958.7,5090.3
XS Rating Curve= 0 ,0
Exp/Cntr=0.3,0.1

Type RM Length L Ch R = 1 ,119104  ,1574,1574,1574
BEGIN DESCRIPTION:
Mapping XS 1d257704
END DESCRIPTION:
XS GIS Cut Line= 3
      3579985.37      10675156.1      3580558.29     10673645.68
      3580844.68     10671276.46
#Sta/Elev= 30
  3128.7  320.25  3536.1  298.57  3712.6  288.18  3773.2  292.14  3863.7  286.89
  3883.1  290.83  3948.7  290.05  3968.2  286.58  4013.6  291.45  4300.8  296.37
  4520.3  280.12  4525.9  279.98  4632.4     275  4654.1  281.05  4717.9  277.69
  4951.1  282.48  4964.8  282.05  4981.3  269.66  4998.5  266.48  5001.2  265.98
  5004.5  266.48  5061.9  271.84    5072  280.67  5082.1   282.2  6369.8   277.3
  6429.7  277.28  6623.2  279.94  6903.9  308.45    7044  319.21  7130.6   319.6
#Mann= 10 ,-1 , 0
  3128.7     .16       0  3536.1     .05       0  4013.6     .12       0
  4520.3     .16       0  4525.9     .12       0  4998.5     .07       0
  5004.5     .12       0  6369.8     .07       0  6429.7     .12       0
  6903.9     .05       0
Bank Sta=4951.1,5082.1
XS Rating Curve= 0 ,0
Exp/Cntr=0.3,0.1

Type RM Length L Ch R = 1 ,117530  ,1224,1224,1224
BEGIN DESCRIPTION:
Mapping XS bb60a182
END DESCRIPTION:
XS GIS Cut Line= 4
      3580384.78     10675216.37      3581860.48     10673914.28
      3582077.49     10673480.25      3581665.17     10671657.39
#Sta/Elev= 30
    2817  313.99  3038.6  302.36  3062.9   299.9  3363.2  281.47  3630.3  279.78
  4170.5  281.03  4192.3  275.16  4206.5  275.29  4227.4  281.08  4588.8  277.33
  4934.9  281.72  4945.7  278.69  4957.3   267.4  4987.4  266.33  4990.1  265.83
  4993.4  266.33    5002  266.41  5012.7  274.73  5018.3  270.45  5035.1  281.95
  5871.4  277.36  6203.3  279.15  6237.2  278.11  6254.6   273.6  6280.4  279.34
  6323.6  279.98  6480.2  293.76  6732.6  306.76  7013.3  307.47  7139.2  311.65
#Mann= 6 ,-1 , 0
    2817     .16       0  3038.6     .05       0  3062.9     .16       0
  3630.3     .12       0  4987.4     .07       0  4993.4     .12       0
Bank Sta=4934.9,5035.1
XS Rating Curve= 0 ,0
Exp/Cntr=0.3,0.1

Type RM Length L Ch R = 1 ,116306  ,1391,1391,1391
BEGIN DESCRIPTION:
TEHUACANA CREEK 51.0
END DESCRIPTION:
XS GIS Cut Line= 3
      3580601.76     10675607.01      3582902.14     10674326.61
      3585072.14     10671115.01
#Sta/Elev= 30
  2064.6   330.3  2392.8   311.1  2685.5  287.11    2879  279.03  2988.5  276.46
  3839.2  279.23  4362.5  276.74  4937.2  280.81  4958.5  278.87  4985.1   265.6
  4987.8   265.1  4991.1   265.6  5024.1  266.21    5039  271.36    5054   280.9
    5117   278.6  6064.9   275.7  6868.2  275.14  7037.8  275.31  7206.2  275.26
  7329.3   275.3  7652.4  277.99  7956.8  288.43  8056.9  293.16  8192.8  308.02
  8194.5  308.26  8410.1  332.53  8513.3  343.62  8536.5  344.47  8573.3  344.87
#Mann= 15 ,-1 , 0
  2064.6     .16       0    2879     .12       0  4985.1     .07       0
  4991.1     .12       0  6064.9     .05       0  6868.2     .12       0
  7037.8      .1       0  7206.2     .05       0  7329.3     .12       0
  7956.8     .16       0  8192.8     .12       0  8194.5     .16       0
  8410.1     .12       0  8513.3     .16       0  8536.5     .12       0
Bank Sta=4937.2,5054
XS Rating Curve= 0 ,0
Exp/Cntr=0.3,0.1

Type RM Length L Ch R = 1 ,114915  ,2118,2118,2118
BEGIN DESCRIPTION:
TEHUACANA CREEK 50.0
END DESCRIPTION:
XS GIS Cut Line= 4
      3581023.28      10675902.6      3583123.39     10674965.12
      3584473.76     10673493.77      3585732.22     10671974.94
#Sta/Elev= 30
  2502.1  328.93  2696.3  324.07  3014.6  294.76  3203.5  282.35  3309.6  277.44
    3856  276.27    4765  276.42  4951.4  279.78  4965.6  277.79  4976.8  264.53
  4979.5  264.03  4982.8  264.53  5014.9  264.71  5036.5  279.71  5043.3  279.73
  5439.8  276.56  5468.1  279.61  5786.3  274.25  6477.9  274.25  6618.3  274.29
  6633.2  274.29  6771.2  274.45  6932.2  274.35  7317.1  273.52  7594.6  281.76
  8119.4  319.51  8307.1  321.39  8495.8  321.33  8736.3  327.54  8771.5   328.7
#Mann= 11 ,-1 , 0
  2502.1     .16       0  3203.5     .12       0  4976.8     .07       0
  4982.8     .12       0  6477.9     .05       0  6618.3     .12       0
  6633.2     .16       0  6771.2     .05       0  6932.2     .12       0
  8307.1     .16       0  8736.3     .12       0
Bank Sta=4951.4,5043.3
XS Rating Curve= 0 ,0
Exp/Cntr=0.3,0.1

Type RM Length L Ch R = 1 ,112797  ,2799,2799,2799
BEGIN DESCRIPTION:
TEHUACANA CREEK 49.0
END DESCRIPTION:
XS GIS Cut Line= 3
      3579526.95     10677468.25       3583657.5     10676196.02
      3586610.25     10672551.62
#Sta/Elev= 30
    97.3  334.96   455.8  332.77   644.2   320.2     683  309.98     707  319.14
   863.9  330.56  1536.7  321.45  2098.6  309.71  2413.1  287.31  2904.3  284.43
  2935.7  272.43  2977.6  284.13    3576  274.26  3919.3  277.65  3951.2  269.08
  3971.6   277.9  4957.9  278.61  4993.1  265.45  5018.8  264.04  5021.6  263.54
  5024.8  264.04  5050.6   268.2    5065  278.29  5093.7  278.71  7240.6  273.52
  7595.6  295.82  8458.3  311.48  8891.2  326.97  8914.7  328.24  9109.8  332.87
#Mann= 7 ,-1 , 0
    97.3     .16       0  2413.1     .16       0  5018.8     .07       0
  5024.8     .16       0  8458.3     .16       0  8891.2      .1       0
  8914.7     .16       0
Bank Sta=4957.9,5093.7
XS Rating Curve= 0 ,0
Exp/Cntr=0.3,0.1