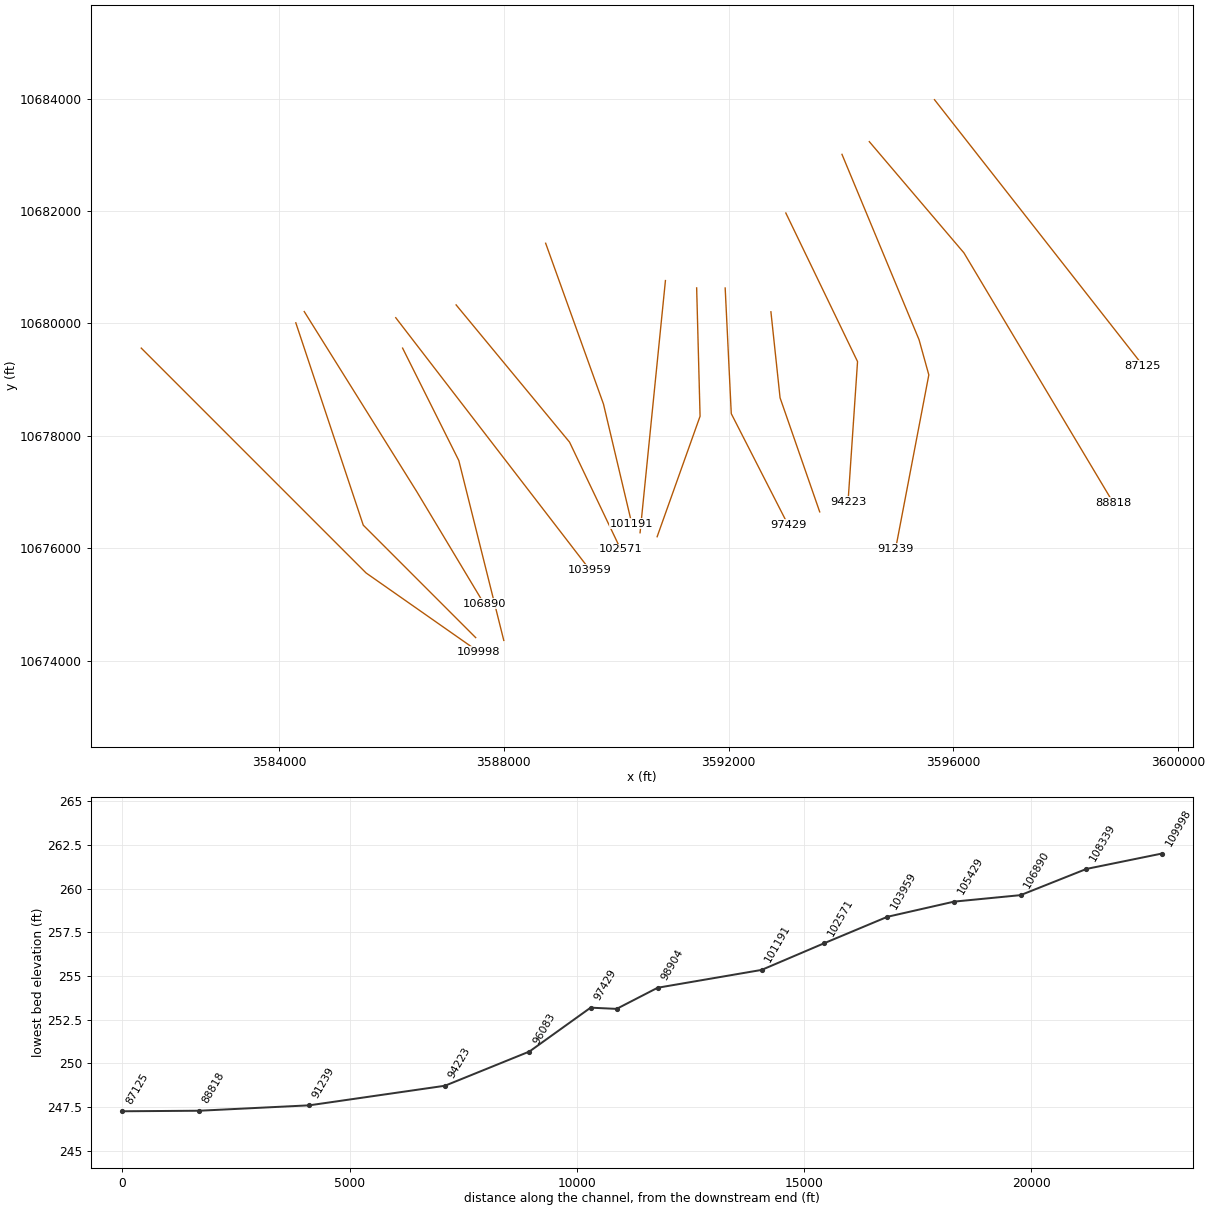
HEC-RAS study TEHUACANA CREEK.prj: TEHUACANA CREEK Base Level Engineering

--- TEHUACANA CREEK.g01 (geometry) --- (continued)

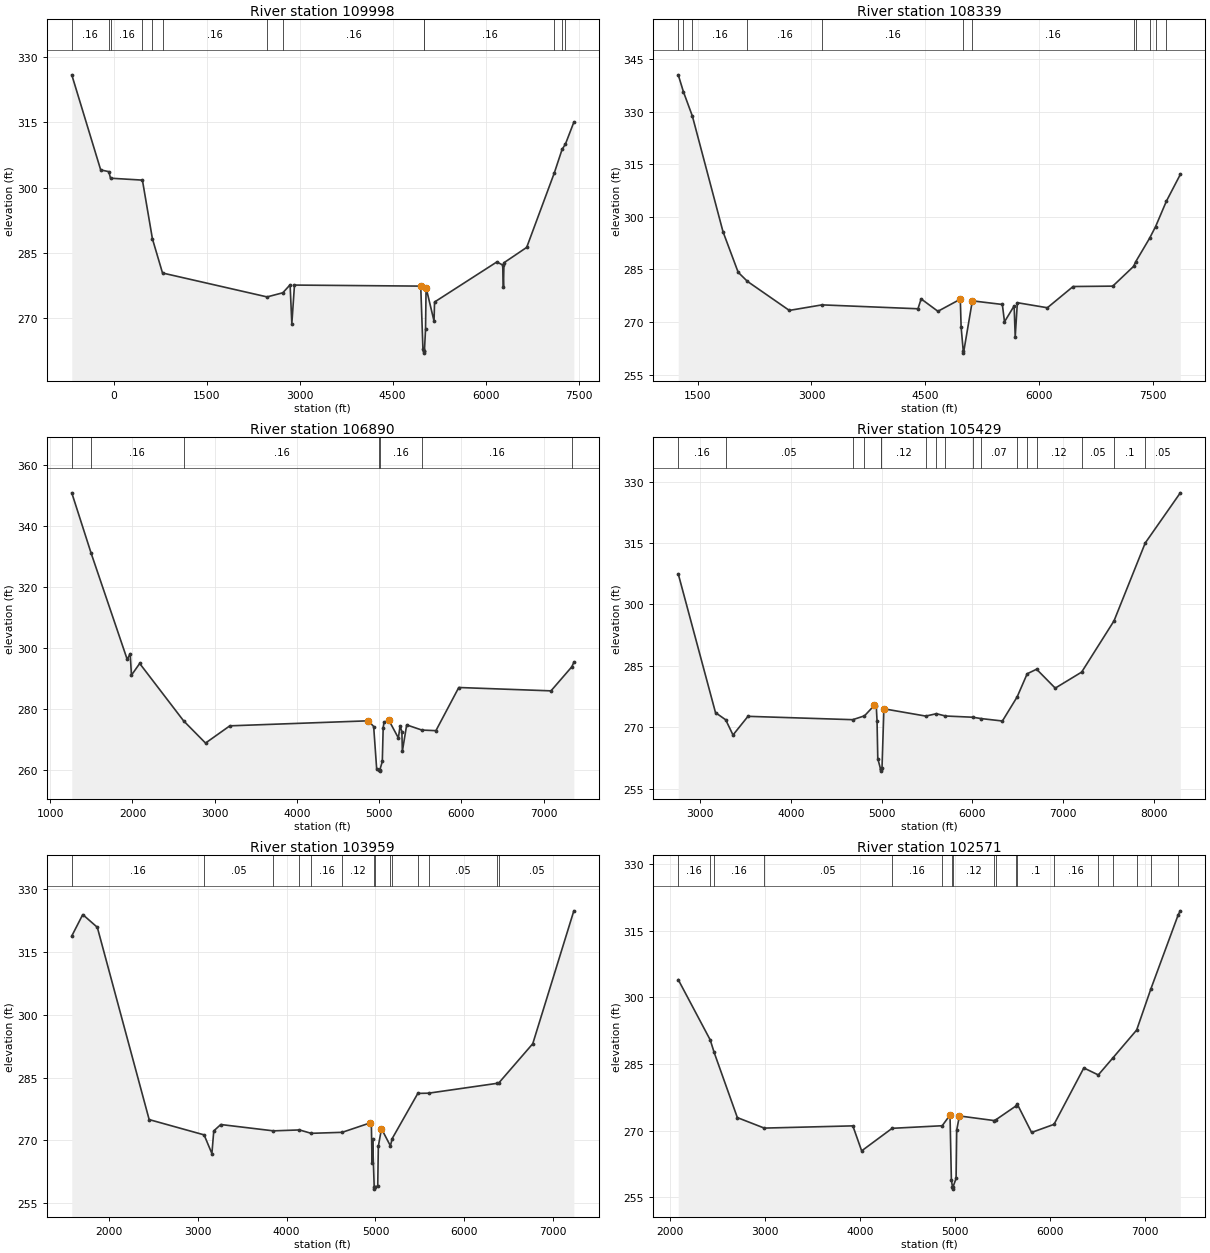
Type RM Length L Ch R = 1 ,109998  ,1659,1659,1659
BEGIN DESCRIPTION:
TEHUACANA CREEK 48.0
END DESCRIPTION:
XS GIS Cut Line= 3
      3581549.63     10679560.17      3585549.61     10675560.19
      3587549.58     10674160.21
#Sta/Elev= 30
    -676  325.92  -209.3  304.08   -78.9  303.69     -51  302.18   463.4  301.74
     625  288.25   787.7  280.41  2474.5  274.92  2728.2  275.87  2845.4   277.7
  2873.6  268.77  2916.1  277.64  4952.5   277.4  4988.2  262.96  5006.2  262.51
  5008.9  262.01  5012.2  262.51  5030.1  267.55  5038.8  277.05    5167  269.37
  5175.7  273.75  6179.2  282.94  6274.3  282.25  6286.9  277.22  6295.2  282.77
  6661.4  286.29  7107.9  303.43  7232.1  308.78  7286.5  310.02  7422.1  315.04
#Mann= 13 ,-1 , 0
    -676     .16       0   -78.9     .05       0     -51     .16       0
   463.4     .05       0     625     .16       0   787.7     .16       0
  2474.5     .16       0  2728.2     .16       0  5006.2     .07       0
  5012.2     .16       0  7107.9     .05       0  7232.1     .16       0
  7286.5     .05       0
Bank Sta=4952.5,5038.8
XS Rating Curve= 0 ,0
Exp/Cntr=0.3,0.1

Type RM Length L Ch R = 1 ,108339  ,1449,1449,1449
BEGIN DESCRIPTION:
TEHUACANA CREEK 47.0
END DESCRIPTION:
XS GIS Cut Line= 3
      3584299.61      10680010.2      3585499.61     10676410.19
      3587499.63     10674410.17
#Sta/Elev= 30
  1242.8  340.55  1311.6  335.69  1429.2  328.78  1833.1   295.8  2033.4   284.2
  2155.9   281.6    2708  273.32  3139.6   274.9  4405.1  273.79  4447.2   276.6
  4668.6  273.07  4963.8  276.52  4974.3  268.65  5002.9  261.63  5005.7  261.13
  5122.4  276.05  5518.4  275.02  5546.7  270.07  5673.9  274.61  5688.1  265.76
  5716.4  275.52  6112.3  274.08  6451.8  280.14    6975  280.25  7250.3   285.9
  7277.1  287.19  7460.9  293.92  7540.3  297.26  7682.3  304.49    7866  312.12
#Mann= 12 ,-1 , 0
  1242.8     .16       0  1311.6     .05       0  1429.2     .16       0
  2155.9     .16       0  3139.6     .16       0  5002.9     .07       0
  5122.4     .16       0  7250.3     .05       0  7277.1     .12       0
  7460.9     .16       0  7540.3     .12       0  7682.3     .16       0
Bank Sta=4963.8,5122.4
XS Rating Curve= 0 ,0
Exp/Cntr=0.3,0.1

Type RM Length L Ch R = 1 ,106890  ,1461,1461,1461
BEGIN DESCRIPTION:
TEHUACANA CREEK 46.0
END DESCRIPTION:
XS GIS Cut Line= 3
      3584449.64     10680210.15      3586449.61     10677010.19
       3587649.6     10675010.21
#Sta/Elev= 30
  1262.2  350.88  1496.3   331.2  1936.1  296.28  1972.6  298.13    1988  291.09
  2088.2  294.93  2621.8  276.13  2888.9  268.83  3184.3  274.48  4870.1  276.13
  4933.7  274.25  4970.3  260.33  5003.9  260.13  5006.6  259.63  5009.9  260.13
  5038.7  262.81  5049.3  273.87  5059.1  275.59  5117.4  276.35    5234  270.52
  5255.4  274.51  5276.8  272.52  5282.6  266.13  5335.1  274.79  5520.4  273.09
  5690.8   272.9  5968.7  287.05  7090.2  285.95  7343.5  293.84  7368.1  295.32
#Mann= 7 ,-1 , 0
  1262.2     .16       0  1496.3     .16       0  2621.8     .16       0
  5003.9     .07       0  5009.9     .16       0  5520.4     .16       0
  7343.5      .1       0
Bank Sta=4870.1,5117.4
XS Rating Curve= 0 ,0
Exp/Cntr=0.3,0.1

Type RM Length L Ch R = 1 ,105429  ,1470,1470,1470
BEGIN DESCRIPTION:
TEHUACANA CREEK 45.0
END DESCRIPTION:
XS GIS Cut Line= 3
       3586199.6     10679560.21      3587199.61     10677560.19
      3587999.61     10674360.17
#Sta/Elev= 30
  2758.1  307.46    3169  273.55  3281.4   271.8  3361.9  268.09  3526.8  272.65
  4681.5  271.83  4811.3  272.77  4918.7  275.31  4941.1  275.14  4949.5  271.61
  4957.9  262.32  4988.4  259.76  4991.1  259.26  4994.4  259.76  5004.5  260.12
  5025.1  274.49  5486.5  272.71  5603.9  273.29    5704  272.73    6005  272.43
  6093.4  272.11  6331.6  271.51  6494.2   277.4  6604.7  283.05  6708.4  284.16
    6914  279.54  7205.2  283.46    7562  295.98  7905.8     315  8292.7  327.26
#Mann= 17 ,-1 , 0
  2758.1     .16       0  3281.4     .05       0  4681.5     .16       0
  4811.3     .12       0  4988.4     .07       0  4994.4     .12       0
  5486.5     .07       0  5603.9     .12       0    5704     .07       0
    6005     .12       0  6093.4     .07       0  6494.2     .12       0
  6604.7     .07       0  6708.4     .12       0  7205.2     .05       0
    7562      .1       0  7905.8     .05       0
Bank Sta=4918.7,5025.1
XS Rating Curve= 0 ,0
Exp/Cntr=0.3,0.1

Type RM Length L Ch R = 1 ,103959  ,1388,1388,1388
BEGIN DESCRIPTION:
TEHUACANA CREEK 44.0
END DESCRIPTION:
XS GIS Cut Line= 2
      3586077.42     10680100.99      3589527.92     10675619.68
#Sta/Elev= 30
  1579.1  318.81  1702.8  323.93  1866.8  320.89  2450.9  274.99  3069.8  271.34
  3157.7  266.88  3178.7  272.29  3257.6  273.81    3851   272.3    4144  272.52
  4276.3  271.71  4625.2  271.95  4939.1  274.19  4953.6  274.31  4961.8  264.65
  4968.1  270.24    4986  258.89  4988.7  258.39    4992  258.89  5025.6  259.13
  5032.5  268.61  5067.8  272.81  5168.5  268.72  5188.9  270.47  5477.4  281.24
  5597.6  281.29  6372.5  283.65  6389.3  283.73  6772.1   293.1  7234.9  324.82
#Mann= 14 ,-1 , 0
  1579.1     .16       0  3069.8     .05       0    3851     .16       0
    4144     .05       0  4276.3     .16       0  4625.2     .12       0
    4986     .07       0    4992     .12       0  5168.5     .05       0
  5188.9     .12       0  5477.4      .1       0  5597.6     .05       0
  6372.5      .1       0  6389.3     .05       0
Bank Sta=4939.1,5067.8
XS Rating Curve= 0 ,0
Exp/Cntr=0.3,0.1

Type RM Length L Ch R = 1 ,102571  ,1380,1380,1380
BEGIN DESCRIPTION:
TEHUACANA CREEK 43.0
END DESCRIPTION:
XS GIS Cut Line= 3
      3587151.64     10680328.85      3589169.86     10677887.46
      3590081.33     10675977.71
#Sta/Elev= 30
  2087.2  303.97  2423.8  290.42  2464.8  287.63  2709.3  272.96  2992.7   270.6
  3924.8   271.1  4017.3  265.48  4338.3  270.55    4865  271.13  4947.3  273.53
  4961.7  258.98    4973  257.38  4975.8  256.88    4979  257.38  5011.2  259.28
  5017.7  270.15  5046.3  273.33  5409.4   272.3  5429.8  272.47  5643.1   275.6
  5654.4  276.02  5805.8  269.62  6041.7  271.44  6355.6  284.12  6507.8  282.55
    6661  286.37  6911.4  292.64  7061.3   301.9  7349.5  318.59  7370.9  319.44
#Mann= 18 ,-1 , 0
  2087.2     .16       0  2423.8     .05       0  2464.8     .16       0
  2992.7     .05       0  4338.3     .16       0    4865     .12       0
    4973     .07       0    4979     .12       0  5409.4     .05       0
  5429.8     .16       0  5643.1     .05       0  5654.4      .1       0
  6041.7     .16       0  6507.8     .05       0    6661     .16       0
  6911.4      .1       0  7061.3     .16       0  7349.5     .05       0
Bank Sta=4947.3,5046.3
XS Rating Curve= 0 ,0
Exp/Cntr=0.3,0.1

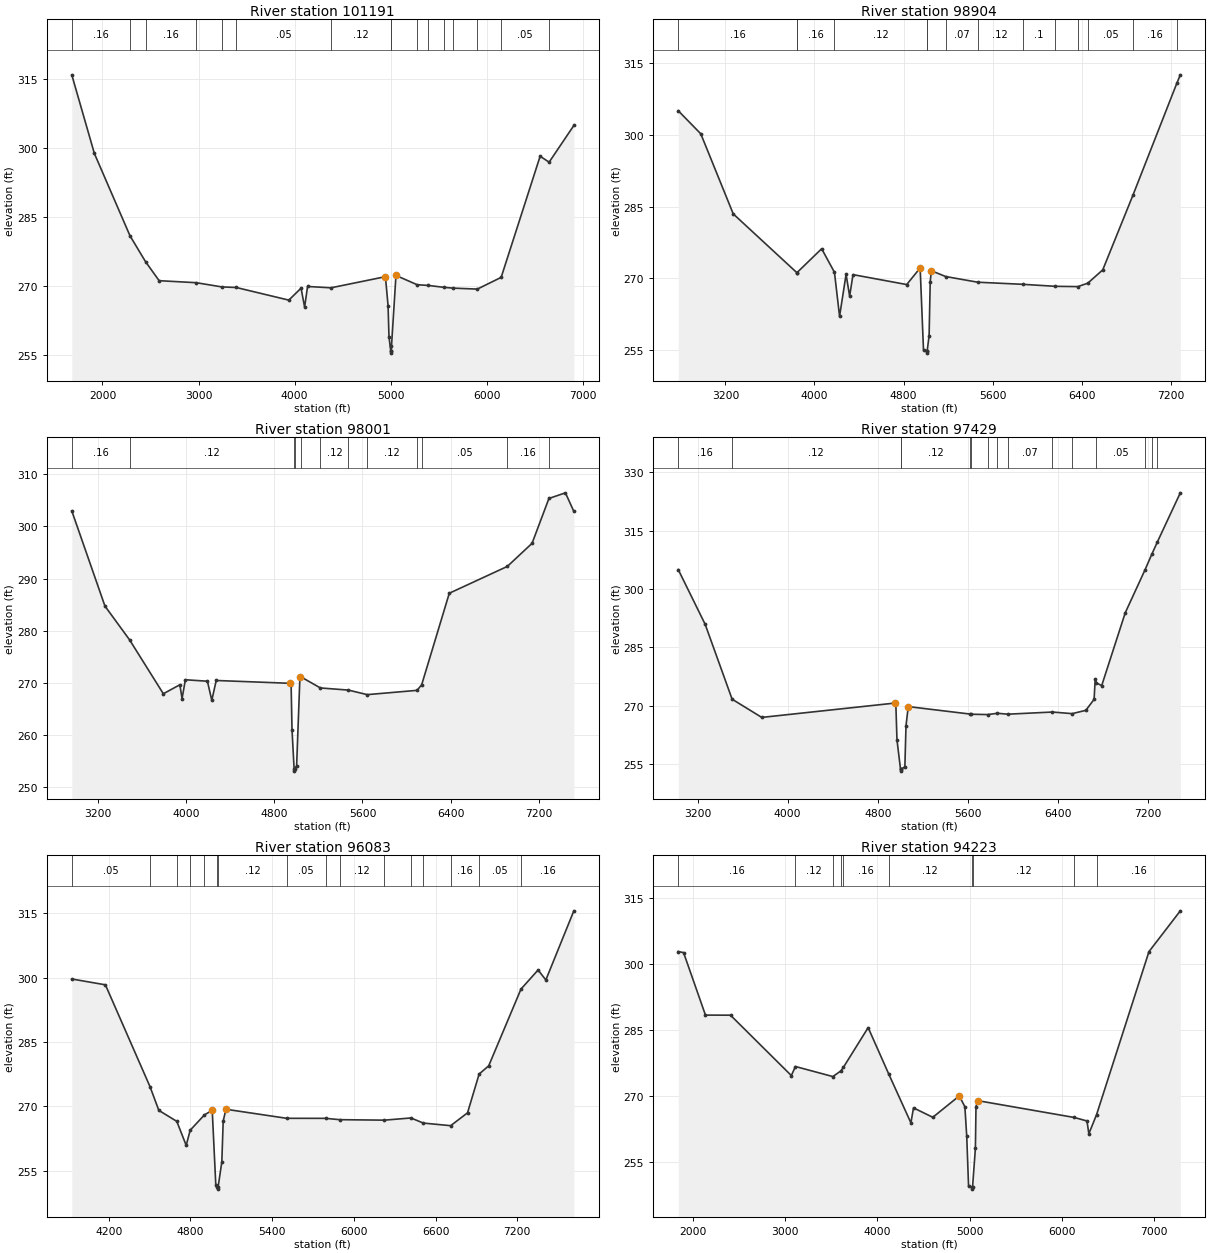
Type RM Length L Ch R = 1 ,101191  ,2287,2287,2287
BEGIN DESCRIPTION:
TEHUACANA CREEK 42.0
END DESCRIPTION:
XS GIS Cut Line= 3
      3588744.68     10681425.71      3589773.33     10678565.48
       3590276.8     10676438.74
#Sta/Elev= 30
  1680.3  315.89  1915.6  298.78  2286.4  280.87  2448.7  275.22  2589.5  271.11
  2976.3  270.67  3243.1  269.75  3391.9  269.63  3939.1  266.88  4066.6  269.48
  4103.5  265.36  4134.2  269.85    4378  269.56  4944.4  271.98    4972  265.71
  4981.5  258.94  4999.8  255.85  5002.5  255.35  5005.8  255.85  5007.6  256.81
  5054.2  272.25  5274.7  270.23  5388.6  270.08    5550  269.67  5649.8  269.49
    5901  269.28    6149  271.83  6554.5  298.18  6648.1  296.89  6905.4  304.87
#Mann= 17 ,-1 , 0
  1680.3     .16       0  2286.4     .05       0  2448.7     .16       0
  2976.3     .05       0  3243.1     .07       0  3391.9     .05       0
    4378     .12       0  4999.8     .07       0  5005.8     .12       0
  5007.6     .07       0  5274.7     .12       0  5388.6     .07       0
    5550      .1       0  5649.8     .16       0    5901      .1       0
    6149     .05       0  6648.1     .16       0
Bank Sta=4944.4,5054.2
XS Rating Curve= 0 ,0
Exp/Cntr=0.3,0.1

Type RM Length L Ch R = 1 ,98904   ,903,903,903
BEGIN DESCRIPTION:
TEHUACANA CREEK 41.0
END DESCRIPTION:
XS GIS Cut Line= 2
      3590875.76     10680761.64      3590424.56     10676275.67
#Sta/Elev= 30
  2776.5  305.09    2979  300.26  3270.4  283.49  3841.7  271.18  3843.1  271.19
  4064.4  276.19  4179.3  271.26  4225.2  262.04  4283.7  270.82  4315.7  266.26
  4345.8  270.77  4828.2  268.69  4948.9  272.17    4979  254.96  5006.2  254.83
  5008.9  254.33  5012.2  254.83  5029.3  257.99  5039.3  269.29  5049.4  271.59
  5177.9  270.37  5466.3  269.18  5870.4  268.74  6162.9  268.32  6365.1  268.26
  6454.5  268.98  6588.6  271.77  6859.8  287.41  7255.5  310.95  7285.1  312.61
#Mann= 14 ,-1 , 0
  2776.5     .16       0  3841.7     .12       0  3843.1     .16       0
  4179.3     .12       0  5006.2     .07       0  5012.2     .12       0
  5177.9     .07       0  5466.3     .12       0  5870.4      .1       0
  6162.9     .16       0  6365.1      .1       0  6454.5     .05       0
  6859.8     .16       0  7255.5     .05       0
Bank Sta=4948.9,5049.4
XS Rating Curve= 0 ,0
Exp/Cntr=0.3,0.1

Type RM Length L Ch R = 1 ,98001   ,572,572,572
BEGIN DESCRIPTION:
TEHUACANA CREEK 40.0
END DESCRIPTION:
XS GIS Cut Line= 3
      3591431.31     10680631.41      3591492.08     10678348.47
      3590728.34     10676204.81
#Sta/Elev= 30
    2960  302.97  3261.3  284.73  3484.4  278.28  3791.5  267.94  3941.6  269.66
  3961.6  267.02  3991.6  270.62  4191.7  270.34  4231.7  266.68  4271.7  270.48
  4941.9  269.94  4951.9  269.71    4960  261.08  4978.9  253.62  4981.7  253.12
  4984.9  253.62  5001.9  254.11    5032  271.21  5039.7  271.19  5217.8  269.05
  5472.1  268.64  5642.8  267.77  6095.5  268.59  6137.5  269.66  6388.4  287.19
  6915.6  292.33    7140  296.75  7293.1  305.34  7442.9  306.42  7519.4  302.86
#Mann= 12 ,-1 , 0
    2960     .16       0  3484.4     .12       0  4978.9     .07       0
  4984.9     .12       0  5039.7     .07       0  5217.8     .12       0
  5472.1     .07       0  5642.8     .12       0  6095.5      .1       0
  6137.5     .05       0  6915.6     .16       0  7293.1     .05       0
Bank Sta=4941.9,5032
XS Rating Curve= 0 ,0
Exp/Cntr=0.3,0.1

Type RM Length L Ch R = 1 ,97429   ,1346,1346,1346
BEGIN DESCRIPTION:
TEHUACANA CREEK 39.0
END DESCRIPTION:
XS GIS Cut Line= 3
      3591938.84       10680629.      3592047.34     10678393.75
      3593056.46     10676418.92
#Sta/Elev= 30
    3029  304.97  3268.1   290.9  3507.2  271.67  3770.2  266.99  4950.1  270.67
  4960.1  270.51  4970.1  261.24  5001.7  253.69  5004.4  253.19  5007.7  253.69
  5040.2  254.32  5050.2  264.81  5070.2  269.77  5616.4  267.86  5625.5  267.81
  5774.3  267.72  5861.8  268.05  5953.7  267.82  6349.6  268.37  6524.9  267.96
    6646  268.81  6719.5  271.63  6729.2  276.77  6740.8  275.85  6786.9  275.16
  6995.9  293.87  7172.6  304.98  7231.2  308.88  7280.5  312.04  7484.6  324.69
#Mann= 15 ,-1 , 0
    3029     .16       0  3507.2     .12       0  5001.7     .07       0
  5007.7     .12       0  5616.4     .07       0  5625.5     .12       0
  5774.3     .07       0  5861.8     .12       0  5953.7     .07       0
  6349.6     .12       0  6524.9     .16       0  6740.8     .05       0
  7172.6     .16       0  7231.2      .1       0  7280.5     .16       0
Bank Sta=4950.1,5070.2
XS Rating Curve= 0 ,0
Exp/Cntr=0.3,0.1

Type RM Length L Ch R = 1 ,96083   ,1860,1860,1860
BEGIN DESCRIPTION:
TEHUACANA CREEK 38.0
END DESCRIPTION:
XS GIS Cut Line= 3
      3592752.64      10680205.8       3592915.4     10678675.87
      3593620.68     10676646.82
#Sta/Elev= 30
  3928.7  299.67  4175.7  298.31  4503.5  274.55  4567.9  269.04  4699.9  266.48
    4769  260.88  4798.1  264.41    4903  267.99  4960.1  269.05  4986.2  251.72
  4997.3  251.18  5000.1  250.68  5003.3  251.18  5030.5  257.02  5040.6  266.54
  5060.7   269.3  5506.7  267.19  5793.4  267.18  5895.8  266.87  6224.3  266.76
  6419.2  267.27  6510.3  266.08  6710.8  265.47  6834.6  268.46  6919.9  277.51
  6990.1  279.42  7227.1  297.31  7352.8  301.77  7409.8  299.44  7615.4  315.56
#Mann= 16 ,-1 , 0
  3928.7     .05       0  4503.5     .12       0  4699.9     .07       0
  4798.1     .05       0    4903     .12       0  4997.3     .07       0
  5003.3     .12       0  5506.7     .05       0  5793.4     .07       0
  5895.8     .12       0  6224.3     .07       0  6419.2     .12       0
  6510.3     .07       0  6710.8     .16       0  6919.9     .05       0
  7227.1     .16       0
Bank Sta=4960.1,5060.7
XS Rating Curve= 0 ,0
Exp/Cntr=0.3,0.1

Type RM Length L Ch R = 1 ,94223   ,2984,2984,2984
BEGIN DESCRIPTION:
TEHUACANA CREEK 37.0
END DESCRIPTION:
XS GIS Cut Line= 3
      3593017.74     10681963.75      3594293.77     10679320.55
      3594124.55     10676821.36
#Sta/Elev= 30
  1841.6  302.84  1899.5  302.59  2136.6  288.36  2407.9  288.34    3067  274.59
  3111.5  276.65  3516.8  274.36  3604.9  275.66  3631.6  276.48  3899.4  285.51
  4121.5  274.98  4362.6  263.82  4390.8  267.23  4599.8  265.08  4887.3  269.96
  4947.4  267.47  4967.5  260.77  4987.5  249.33  5024.6  249.22  5027.4  248.72
  5030.6  249.22  5061.5  258.07  5067.7  267.52  5087.8  268.87  6132.9  265.04
  6270.5  264.24  6290.5  261.33  6373.8  265.66    6942  302.82  7281.6  312.11
#Mann= 10 ,-1 , 0
  1841.6     .16       0  3111.5     .12       0  3516.8     .16       0
  3604.9     .12       0  3631.6     .16       0  4121.5     .12       0
  5024.6     .07       0  5030.6     .12       0  6132.9     .05       0
  6373.8     .16       0
#XS Ineff= 2 , 0
         3863.64  284.16
Permanent Ineff=
       F       F
Bank Sta=4887.3,5087.8
XS Rating Curve= 0 ,0
Exp/Cntr=0.3,0.1

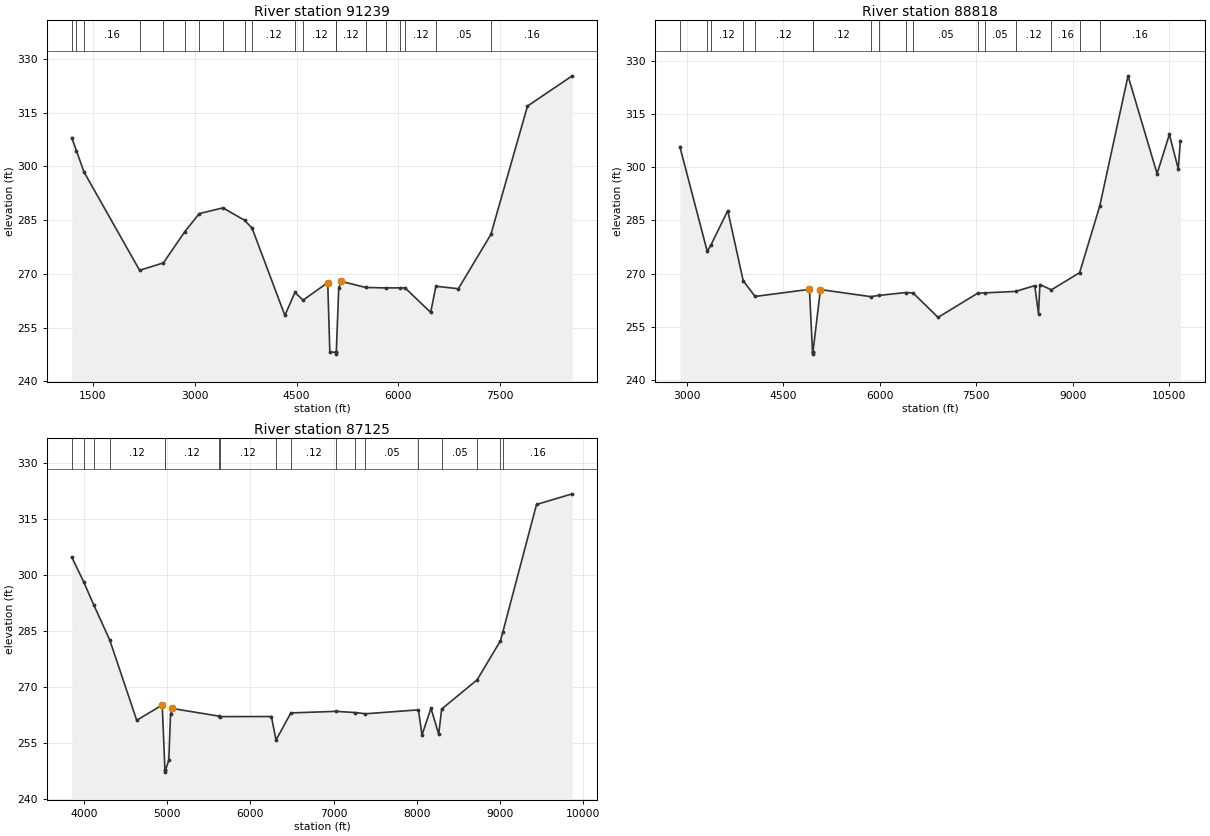
Type RM Length L Ch R = 1 ,91239   ,2421,2421,2421
BEGIN DESCRIPTION:
TEHUACANA CREEK 36.0
END DESCRIPTION:
XS GIS Cut Line= 4
      3594016.86     10683007.19      3595388.39     10679708.58
        3595562.     10679083.58      3594971.91     10675994.28
#Sta/Elev= 30
  1191.5  308.04  1260.7  304.39  1373.2  298.42  2191.1  270.99  2541.5  273.07
  2854.9  281.75  3068.5  286.82  3418.2  288.42  3735.3  284.96  3845.4   282.8
  4328.9  258.41  4476.6  264.82  4597.2  262.67  4959.4  267.57  4990.5   248.2
  5079.4   248.1  5082.2   247.6  5085.4   248.1  5121.8  266.19  5161.3   267.9
  5519.4   266.2  5824.3  266.08  6019.2  266.09  6097.3  266.09  6474.8  259.24
  6551.3  266.54    6882  265.86  7360.6     281  7899.4  316.83  8557.7  325.27
#Mann= 20 ,-1 , 0
  1191.5     .16       0  1260.7     .05       0  1373.2     .16       0
  2191.1     .16       0  2541.5     .05       0  2854.9     .16       0
  3068.5     .05       0  3418.2     .12       0  3735.3     .16       0
  3845.4     .12       0  4476.6     .05       0  4597.2     .12       0
  5079.4     .07       0  5085.4     .12       0  5519.4     .12       0
  5824.3     .12       0  6019.2     .05       0  6097.3     .12       0
  6551.3     .05       0  7360.6     .16       0
#XS Ineff= 2 , 0
         2926.25  280.25
Permanent Ineff=
       F       F
Bank Sta=4959.4,5161.3
XS Rating Curve= 0 ,0
Exp/Cntr=0.3,0.1

Type RM Length L Ch R = 1 ,88818   ,1693,1693,1693
BEGIN DESCRIPTION:
TEHUACANA CREEK 35.0
END DESCRIPTION:
XS GIS Cut Line= 3
      3594502.98     10683232.87        3596187.     10681253.71
      3598843.27     10676809.24
#Sta/Elev= 30
  2894.9  305.81  3320.3  276.28  3375.7  278.01  3639.2  287.77  3878.8  268.02
  4062.7  263.56  4908.7  265.57  4956.2  247.79    4959  247.29  4962.2  247.79
  5078.9   265.5  5859.1  263.51  5983.3  263.84  6405.3  264.67  6516.9  264.56
  6906.7  257.66  7521.4  264.47    7633  264.57    8110  264.98  8408.5  266.61
  8466.9  258.72  8488.3  266.92    8667  265.43  9105.9  270.27  9418.8  289.09
  9857.9   325.8 10309.2  298.19 10499.9  309.27   10638  299.58 10671.3   307.5
#Mann= 17 ,-1 , 0
  2894.9     .12       0  3320.3     .16       0  3375.7     .12       0
  3878.8     .16       0  4062.7     .12       0  4956.2     .07       0
  4962.2     .12       0  5859.1     .07       0  5983.3     .12       0
  6405.3     .07       0  6516.9     .05       0  7521.4     .07       0
    7633     .05       0    8110     .12       0    8667     .16       0
  9105.9     .05       0  9418.8     .16       0
Bank Sta=4908.7,5078.9
XS Rating Curve= 0 ,0
Exp/Cntr=0.3,0.1

Type RM Length L Ch R = 1 ,87125   ,1633,1633,1633
BEGIN DESCRIPTION:
TEHUACANA CREEK 34.0
END DESCRIPTION:
XS GIS Cut Line= 2
      3595662.72     10683979.37      3599371.04     10679250.22
#Sta/Elev= 30
  3855.9  304.92  3998.4  298.33  4119.2  292.16  4313.3  282.64  4636.6  261.16
  4943.1  265.26  4975.3  247.76  4978.1  247.26  4981.3  247.76  5021.7  250.45
  5042.5  262.73  5063.3  264.32  5624.7  262.27  5637.7  262.14  6253.9  262.16
  6309.1  255.87  6487.8  263.13  7029.5  263.55  7262.1  263.22    7383   262.9
  8018.5  263.95  8061.9  257.21  8169.5   264.4  8262.5  257.42    8298  264.17
  8724.1     272  9003.5  282.45  9031.3  284.72  9436.9  318.99  9865.6  321.85
#Mann= 18 ,-1 , 0
  3855.9     .16       0  3998.4     .12       0  4119.2     .16       0
  4313.3     .12       0  4975.3     .07       0  4981.3     .12       0
  5624.7     .07       0  5637.7     .12       0  6309.1     .05       0
  6487.8     .12       0  7029.5     .05       0  7262.1     .07       0
    7383     .05       0  8018.5     .12       0    8298     .05       0
  8724.1     .16       0  9003.5     .05       0  9031.3     .16       0
Bank Sta=4943.1,5063.3
XS Rating Curve= 0 ,0
Exp/Cntr=0.3,0.1