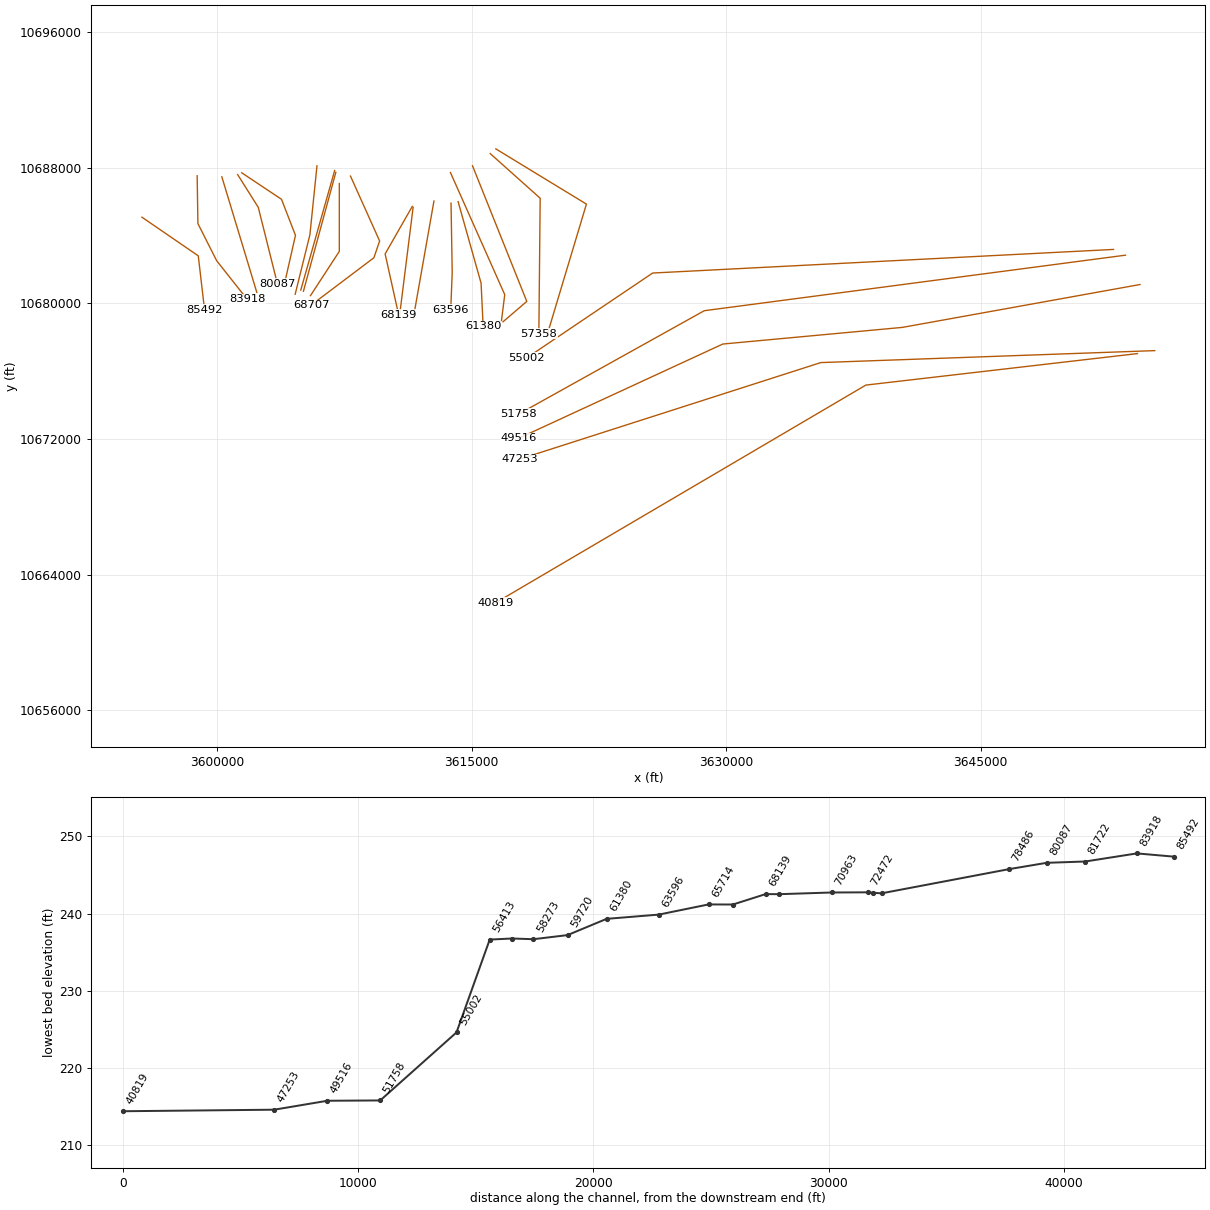
HEC-RAS study TEHUACANA CREEK.prj: TEHUACANA CREEK Base Level Engineering

--- TEHUACANA CREEK.g01 (geometry) --- (continued)

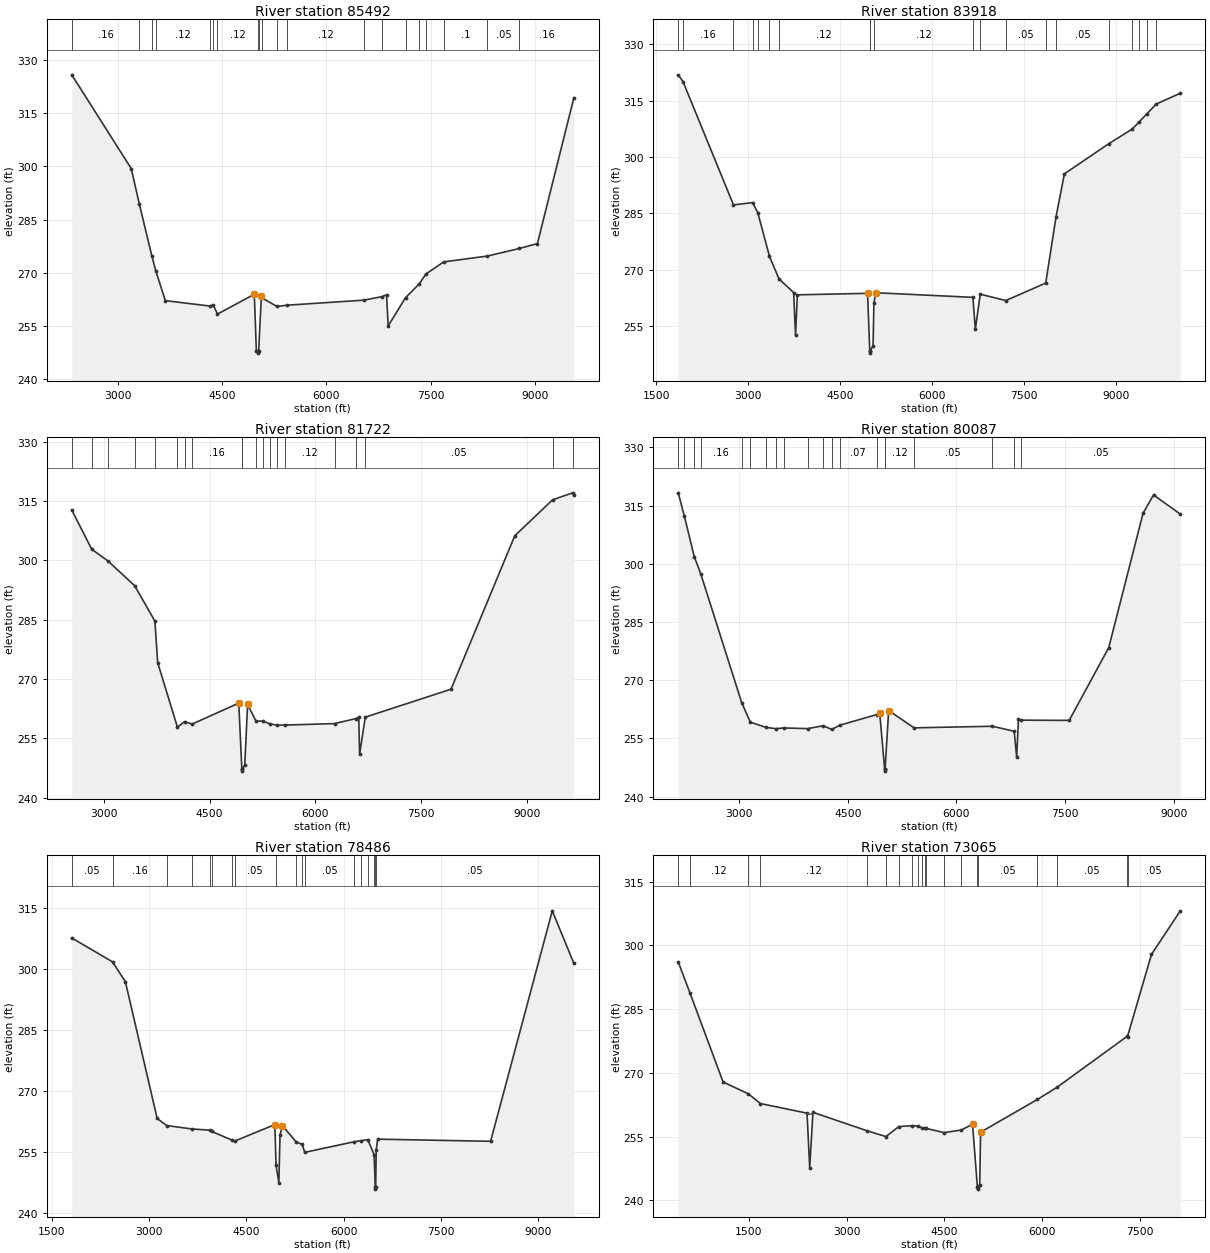
Type RM Length L Ch R = 1 ,85492   ,1574,1574,1574
BEGIN DESCRIPTION:
TEHUACANA CREEK 33.0
END DESCRIPTION:
XS GIS Cut Line= 3
      3595566.44     10685076.27      3598886.74     10682797.62
      3599255.67     10679629.22
#Sta/Elev= 30
  2339.8  325.83  3194.3  299.42    3310   289.5  3489.9  274.82  3548.5  270.52
  3684.3  262.18  4329.1  260.64  4373.1  260.97  4434.4  258.38  4963.4  263.97
  4993.2  248.07    5020  247.88  5022.7  247.38    5026  247.88  5064.9  263.42
  5069.2  262.98  5290.4  260.53  5439.2   260.9  6538.3  262.31  6794.4  263.29
  6864.8   263.8  6887.7  255.04  7136.9  263.01  7333.4  266.87  7431.6  269.71
  7686.7   273.1  8312.2  274.74  8774.7  276.88  9032.9  278.26  9556.6  319.36
#Mann= 20 ,-1 , 0
  2339.8     .16       0    3310     .12       0  3489.9     .16       0
  3548.5     .12       0  4329.1     .07       0  4373.1     .16       0
  4434.4     .12       0    5020     .07       0    5026     .12       0
  5069.2     .07       0  5290.4     .05       0  5439.2     .12       0
  6538.3     .05       0  6794.4     .12       0  7136.9     .12       0
  7333.4     .16       0  7431.6     .05       0  7686.7      .1       0
  8312.2     .05       0  8774.7     .16       0
Bank Sta=4963.4,5064.9
XS Rating Curve= 0 ,0
Exp/Cntr=0.3,0.1

Type RM Length L Ch R = 1 ,83918   ,2196,2196,2196
BEGIN DESCRIPTION:
TEHUACANA CREEK 32.0
END DESCRIPTION:
XS GIS Cut Line= 4
      3598821.64      10687521.3      3598865.04     10684700.11
      3599971.81     10682508.27      3601773.01     10680229.65
#Sta/Elev= 30
  1859.5   321.9  1938.3  320.05  2759.8  287.27  3072.6  287.88  3155.3  285.22
  3346.6  273.56  3501.1  267.58  3740.8   263.9  3770.8   252.6  3800.8  263.32
  4945.2  263.72  4980.4   248.3  4983.2   247.8  4986.4   248.3  5034.4  249.78
  5048.2  261.27    5079  263.88  6661.2  262.65    6701  254.17  6780.9   263.5
  7197.2   261.8  7847.9  266.45  8015.4  284.05  8152.1  295.54  8875.3  303.56
  9256.8  307.45  9373.4  309.43  9494.6  311.49    9651  314.14   10041     317
#Mann= 20 ,-1 , 0
  1859.5     .05       0  1938.3     .16       0  2759.8     .12       0
  3072.6     .16       0  3155.3     .12       0  3346.6     .16       0
  3501.1     .12       0  4980.4     .07       0  4986.4     .16       0
  5048.2     .12       0  6661.2     .07       0  6780.9     .05       0
  7197.2     .05       0  7847.9     .16       0  8015.4     .05       0
  8875.3     .16       0  9256.8     .12       0  9373.4     .16       0
  9494.6     .12       0    9651     .16       0
Bank Sta=4945.2,5079
XS Rating Curve= 0 ,0
Exp/Cntr=0.3,0.1

Type RM Length L Ch R = 1 ,81722   ,1635,1635,1635
BEGIN DESCRIPTION:
TEHUACANA CREEK 31.0
END DESCRIPTION:
XS GIS Cut Line= 2
      3600275.64     10687456.18      3602336.78     10680643.55
#Sta/Elev= 30
  2546.9  312.73    2830  302.81    3056  299.91  3437.4  293.63  3725.2  284.66
  3765.1  274.14  4044.8  257.86  4146.1  259.25  4253.6  258.64  4914.3  263.94
    4958  247.25  4960.7  246.75    4964  247.25  4999.1  248.32  5039.7  263.59
    5157  259.44  5259.7  259.35  5360.9  258.66  5462.1  258.37  5563.4  258.39
    6272  258.76  6575.7  260.03  6615.1  260.35  6627.7  251.06    6708  260.39
  7923.3  267.45  8827.6  306.23  9362.9   315.3  9647.8  317.07  9664.5  316.62
#Mann= 20 ,-1 , 0
  2546.9     .05       0    2830     .16       0    3056     .05       0
  3437.4     .08       0  3725.2     .05       0  4044.8     .16       0
  4146.1     .05       0  4253.6     .16       0    4958     .03       0
    4964     .05       0    5157     .05       0  5259.7     .07       0
  5360.9     .12       0  5462.1     .07       0  5563.4     .12       0
    6272     .05       0  6575.7     .07       0    6708     .05       0
  9362.9     .16       0  9647.8     .05       0
Bank Sta=4914.3,5039.7
XS Rating Curve= 0 ,0
Exp/Cntr=0.3,0.1

Type RM Length L Ch R = 1 ,80087   ,1601,1601,1601
BEGIN DESCRIPTION:
Mapping XS 0550fcb2
END DESCRIPTION:
XS GIS Cut Line= 3
      3601208.82     10687586.36      3602424.07     10685654.97
      3603552.54      10681141.1
#Sta/Elev= 30
  2158.2  318.27  2243.2  312.23  2379.8   301.8  2469.3   297.4  3034.6  264.22
  3154.1   259.2  3368.8  257.85  3504.8  257.52  3623.8   257.7  3944.7  257.53
  4163.2  258.27  4278.2  257.32  4391.2  258.42  4897.2  261.13    4941  261.59
    5009  247.08  5011.7  246.58    5015  247.08  5064.7  262.19  5415.8  257.73
  6498.6  258.14  6798.8  256.84  6832.5  250.15  6857.1  259.93  6898.9  259.71
    7558  259.65  8104.3  278.39  8578.5  313.02  8722.8  317.73  9092.9  312.78
#Mann= 20 ,-1 , 0
  2158.2     .16       0  2243.2     .16       0  2379.8     .05       0
  2469.3     .16       0  3034.6     .12       0  3154.1     .07       0
  3368.8     .12       0  3504.8     .07       0  3623.8     .12       0
  3944.7     .05       0  4163.2     .07       0  4278.2     .05       0
  4391.2     .07       0  4897.2     .05       0    5009     .07       0
    5015     .12       0  5415.8     .05       0  6498.6     .07       0
  6798.8     .12       0  6898.9     .05       0
Bank Sta=4941,5064.7
XS Rating Curve= 0 ,0
Exp/Cntr=0.3,0.1

Type RM Length L Ch R = 1 ,78486   ,5421,5421,5421
BEGIN DESCRIPTION:
Mapping XS b74d5d6e
END DESCRIPTION:
XS GIS Cut Line= 4
      3601447.51      10687694.9      3603791.26      10686132.4
      3604615.91     10684005.67      3604030.21     10681424.23
#Sta/Elev= 30
  1805.2  307.63  2433.5  301.75  2632.5  296.84  3122.2  263.18  3268.3  261.42
  3658.7  260.58    3936  260.28  3962.3  259.97  4269.9  257.89  4315.6  257.58
  4938.2  261.66  4956.3  251.66  4999.8  247.37  5017.2  259.01  5053.4  261.43
  5266.3  257.39  5359.8  256.76  5398.9  254.82  6164.5  257.44  6268.1  257.69
  6371.7  257.94  6468.3  254.27  6487.6  246.26  6490.4  245.76  6493.6  246.26
  6501.4  255.37  6522.8  258.07  8266.1  257.54  9217.4  314.31  9550.1  301.38
#Mann= 18 ,-1 , 0
  1805.2     .05       0  2433.5     .16       0  3268.3     .12       0
  3658.7     .16       0    3936     .12       0  3962.3     .16       0
  4269.9     .12       0  4315.6     .05       0  4956.3     .12       0
  5266.3     .05       0  5359.8     .12       0  5398.9     .05       0
  6164.5     .07       0  6268.1     .05       0  6371.7     .12       0
  6468.3     .05       0  6487.6     .07       0  6493.6     .05       0
Bank Sta=4938.2,5053.4
XS Rating Curve= 0 ,0
Exp/Cntr=0.3,0.1

Type RM Length L Ch R = 1 ,73065   ,381,381,381
BEGIN DESCRIPTION:
Mapping XS d6cf8573
END DESCRIPTION:
XS GIS Cut Line= 3
      3605883.49     10688104.66      3605466.82     10684042.12
      3604598.77     10680535.21
#Sta/Elev= 30
   419.9  296.11   598.6  288.85    1108  267.83  1495.4  265.05  1679.5  262.77
  2394.7   260.5  2434.9  247.71  2485.1   260.7  3311.8  256.37  3603.5  254.99
  3801.4  257.34  3999.3  257.55  4098.3  257.47  4157.3  257.05  4197.2  256.98
    4213  256.95  4494.1  255.92  4759.9  256.54  4931.2   257.9  5005.9  243.12
  5008.6  242.62  5011.9  243.12  5041.4   243.7  5055.4  256.03    5927  263.74
  6227.7   266.6  7305.5  278.64  7307.1  278.54  7674.8  297.88  8116.5  308.13
#Mann= 20 ,-1 , 0
   419.9     .05       0   598.6     .12       0  1495.4     .16       0
  1679.5     .12       0  3311.8     .07       0  3603.5     .12       0
  3801.4     .07       0  3999.3     .05       0  4098.3     .07       0
  4157.3     .05       0  4197.2     .07       0    4213     .05       0
  4494.1     .07       0  4759.9     .05       0  5005.9     .03       0
  5011.9     .05       0    5927     .16       0  6227.7     .05       0
  7305.5     .16       0  7307.1     .05       0
#XS Ineff= 1 ,-1
 2394.49 2483.55  260.34
Permanent Ineff=
       F
Bank Sta=4931.2,5055.4
XS Rating Curve= 0 ,0
Exp/Cntr=0.3,0.1

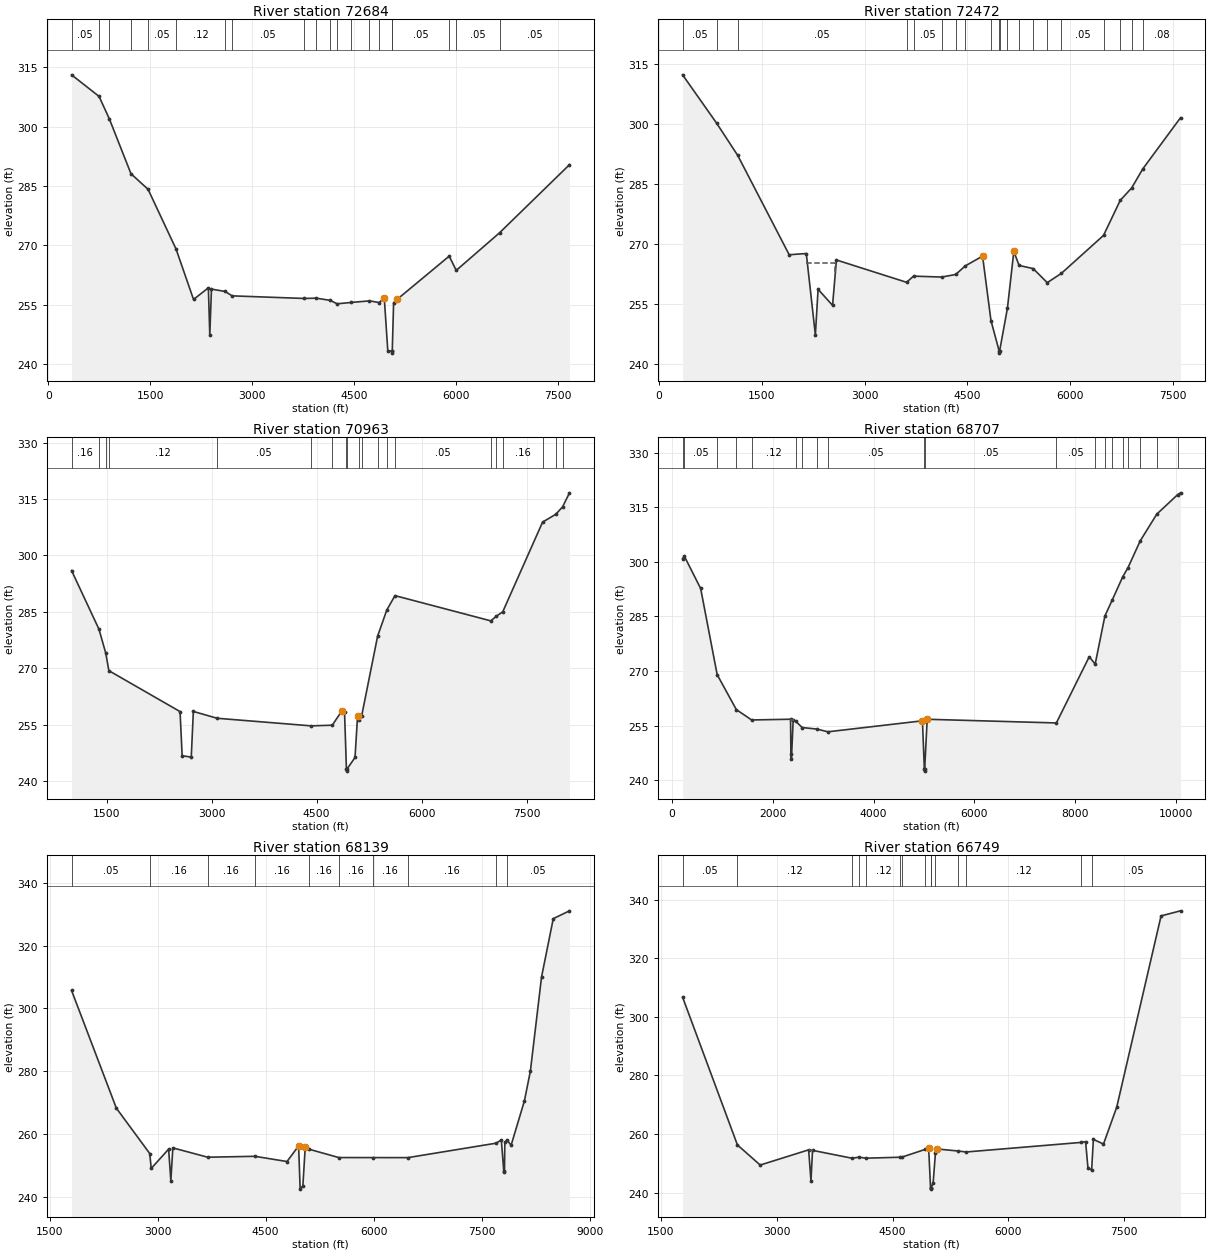
Type RM Length L Ch R = 1 ,72684   ,212,212,212
BEGIN DESCRIPTION:
Mapping XS b20a86de
END DESCRIPTION:
XS GIS Cut Line= 2
      3606925.16     10687826.88      3604928.61     10680778.19
#Sta/Elev= 30
   339.4  313.11   743.6  307.66   894.7  301.99  1213.7  288.08  1464.9  284.15
  1877.1  269.02    2134  256.28  2352.3  259.22  2373.1  247.28  2397.7   258.9
  2598.4   258.3  2701.5  257.19  3765.9  256.53    3938  256.61  4144.1  256.05
  4247.1  255.18  4453.2  255.52  4722.9  255.92  4865.4   255.5  4940.2  256.71
  4992.2   243.3  5051.6   243.2  5054.3   242.7  5057.6   243.2  5077.7  255.44
  5127.3  256.27  5895.8  267.24  5998.9  263.63  6636.9  273.15  7665.4  290.38
#Mann= 20 ,-1 , 0
   339.4     .05       0   743.6     .08       0   894.7     .05       0
  1213.7     .05       0  1464.9     .05       0  1877.1     .12       0
  2598.4     .07       0  2701.5     .05       0  3765.9     .07       0
    3938     .05       0  4144.1     .08       0  4247.1     .05       0
  4453.2     .08       0  4722.9     .05       0  4865.4     .08       0
  5051.6     .07       0  5057.6     .05       0  5895.8     .08       0
  5998.9     .05       0  6636.9     .05       0
#XS Ineff= 1 ,-1
 2345.32 2404.25  258.86
Permanent Ineff=
       F
Bank Sta=4940.2,5127.3
XS Rating Curve= 0 ,0
Exp/Cntr=0.3,0.1

Type RM Length L Ch R = 1 ,72472   ,1509,1509,1509
BEGIN DESCRIPTION:
Mapping XS 15fbb473
END DESCRIPTION:
XS GIS Cut Line= 2
       3606994.6      10687722.7      3605084.86     10680708.75
#Sta/Elev= 30
   342.7  312.37     839  300.29  1147.2  292.22    1899  267.36  2148.7  267.67
  2281.1  247.31  2320.8  258.72  2532.1   254.7  2588.8  266.05  3612.2  260.47
  3714.9  262.01  4125.7  261.78  4331.1  262.43  4466.5  264.54  4722.1  267.02
  4844.7   250.9  4964.7  243.25  4967.4  242.75  4970.7  243.25  5085.3  254.02
  5178.5  268.19  5255.5  264.68  5460.9   263.9  5666.3  260.38  5871.8  262.69
    6488   272.2  6731.9  280.96  6898.9  284.08  7061.2  288.84    7612  301.64
#Mann= 20 ,-1 , 0
   342.7     .05       0     839     .05       0  1147.2     .05       0
  3612.2     .08       0  3714.9     .05       0  4125.7     .08       0
  4331.1     .05       0  4466.5     .08       0  4844.7      .1       0
  4964.7     .07       0  4970.7      .1       0  5085.3     .08       0
  5255.5     .05       0  5460.9     .08       0  5666.3     .05       0
  5871.8     .05       0    6488     .08       0  6731.9     .08       0
  6898.9     .05       0  7061.2     .08       0
#XS Ineff= 1 ,-1
 2149.12 2570.65  265.24
Permanent Ineff=
       F
Bank Sta=4722.1,5178.5
XS Rating Curve= 0 ,0
Exp/Cntr=0.3,0.1

Type RM Length L Ch R = 1 ,70963   ,2256,2256,2256
BEGIN DESCRIPTION:
TEHUACANA CREEK 30.0
END DESCRIPTION:
XS GIS Cut Line= 3
      3607199.61     10687060.16      3607199.61     10683060.19
       3605500.5      10680450.8
#Sta/Elev= 30
   999.8     296  1391.3  280.42  1489.3  274.01  1532.2  269.42  2549.8  258.54
  2579.8  246.81  2709.8  246.46  2739.8  258.58  3078.6  256.77  4423.7  254.75
  4724.8  254.93  4859.8  258.68  4899.8   258.4  4926.8  243.23  4929.5  242.73
  4932.8  243.23  5049.5  246.35  5085.8  257.34  5107.2  256.25  5143.3  257.29
  5372.2  278.57  5503.5  285.52  5620.4  289.34    6989  282.64  7064.3  283.81
    7160  285.05  7729.3  308.86  7918.4  310.95  8015.3  312.93  8113.6  316.64
#Mann= 20 ,-1 , 0
   999.8     .16       0  1391.3     .12       0  1489.3     .16       0
  1532.2     .12       0  3078.6     .05       0  4423.7     .07       0
  4724.8     .05       0  4926.8     .07       0  4932.8     .05       0
  5107.2     .16       0  5143.3     .12       0  5372.2     .05       0
  5503.5     .16       0  5620.4     .05       0    6989     .16       0
  7064.3     .05       0    7160     .16       0  7729.3     .05       0
  7918.4     .16       0  8015.3     .05       0
#XS Ineff= 1 ,-1
 2536.36 2751.14  258.42
Permanent Ineff=
       F
Bank Sta=4859.8,5085.8
XS Rating Curve= 0 ,0
Exp/Cntr=0.3,0.1

Type RM Length L Ch R = 1 ,68707   ,568,568,568
BEGIN DESCRIPTION:
TEHUACANA CREEK 29.0
END DESCRIPTION:
XS GIS Cut Line= 4
      3607857.29     10687501.11      3609576.02     10683673.03
      3609237.48     10682683.44      3605533.85     10679887.16
#Sta/Elev= 30
   208.8  300.86   243.7  301.52   567.3  292.66   895.1     269  1275.9   259.4
  1579.2  256.56  2351.8  256.76  2358.3  247.26  2369.3  245.79  2403.6  256.58
  2450.9  256.24  2582.8  254.48  2873.3  254.06  3093.3  253.31  4969.5  256.33
  5007.5  243.01  5010.2  242.51  5013.5  243.01  5063.4  256.75  7627.5  255.74
  8279.9  273.92  8397.9   271.9  8590.9  285.12  8737.9  289.55  8946.2  295.92
  9046.4   298.3  9292.9  305.77  9621.1  313.09 10036.1  318.45 10091.6  318.93
#Mann= 20 ,-1 , 0
   208.8     .08       0   243.7     .05       0   895.1     .16       0
  1275.9     .12       0  1579.2     .12       0  2450.9     .07       0
  2582.8     .12       0  2873.3     .05       0  3093.3     .05       0
  5007.5     .03       0  5013.5     .05       0  7627.5     .05       0
  8397.9     .16       0  8590.9     .12       0  8737.9     .16       0
  8946.2     .16       0  9046.4     .05       0  9292.9     .16       0
  9621.1     .12       0 10036.1     .05       0
#XS Ineff= 1 ,-1
 2345.64 2412.58  256.56
Permanent Ineff=
       F
Bank Sta=4969.5,5063.4
XS Rating Curve= 0 ,0
Exp/Cntr=0.3,0.1

Type RM Length L Ch R = 1 ,68139   ,1390,1390,1390
BEGIN DESCRIPTION:
TEHUACANA CREEK 28.0
END DESCRIPTION:
XS GIS Cut Line= 3
      3611499.61     10685710.19      3609899.61     10682910.19
       3610699.6     10679310.21
#Sta/Elev= 30
  1805.1  305.71    2427  268.27  2890.6  253.84  2910.8   249.1  3152.6  255.24
  3183.6  245.15    3211  255.64  3695.8  252.67  4349.8  252.96  4796.1   251.3
  4957.3  256.27  4978.6  242.52  5016.3  243.53  5049.2  255.93    5103  255.21
  5515.3  252.56  5984.7  252.55  6474.4  252.54  7700.8  257.14  7771.5  258.17
  7806.1  248.07  7815.1  248.26  7820.2   257.4  7850.5  258.16  7907.3  256.47
  8091.7  270.57  8174.9  280.07  8329.8     310  8492.5  328.55  8717.8  331.04
#Mann= 10 ,-1 , 0
  1805.1     .05       0  2890.6     .16       0  3695.8     .16       0
  4349.8     .16       0    5103     .16       0  5515.3     .16       0
  5984.7     .16       0  6474.4     .16       0  7700.8     .16       0
  7850.5     .05       0
Bank Sta=4957.3,5049.2
XS Rating Curve= 0 ,0
Exp/Cntr=0.3,0.1

Type RM Length L Ch R = 1 ,66749   ,1035,1035,1035
BEGIN DESCRIPTION:
TEHUACANA CREEK 27.0
END DESCRIPTION:
XS GIS Cut Line= 3
      3611549.61     10685660.21      3611149.61     10682460.19
      3610749.61     10679260.22
#Sta/Elev= 30
  1780.5  306.76  2490.8  256.27  2785.8   249.4  3413.1  254.59  3443.4  244.04
  3463.5  254.42  3976.5  251.72  4062.1  252.08  4161.4  251.75  4602.4  252.07
  4624.1  252.13  4922.7  254.74  4967.6  255.34  4992.3  241.67  4995.1  241.17
  4998.3  241.67  5025.6  243.19  5055.1  253.35    5076  254.89    5353  254.19
  5452.3  253.86  6941.7  257.13  7000.8   257.4  7031.1  248.49  7078.8  247.66
  7101.6  258.16  7232.6  256.58  7403.9  269.17  7978.4  334.53  8230.3  336.26
#Mann= 15 ,-1 , 0
  1780.5     .05       0  2490.8     .12       0  3976.5     .12       0
  4062.1     .12       0  4161.4     .12       0  4602.4     .07       0
  4624.1     .12       0  4922.7     .07       0  4992.3     .07       0
  4998.3     .07       0  5055.1     .12       0    5353     .08       0
  5452.3     .12       0  6941.7     .12       0  7078.8     .05       0
#XS Ineff= 1 ,-1
 3411.87 3465.84  254.46
Permanent Ineff=
       F
Bank Sta=4967.6,5076
XS Rating Curve= 0 ,0
Exp/Cntr=0.3,0.1

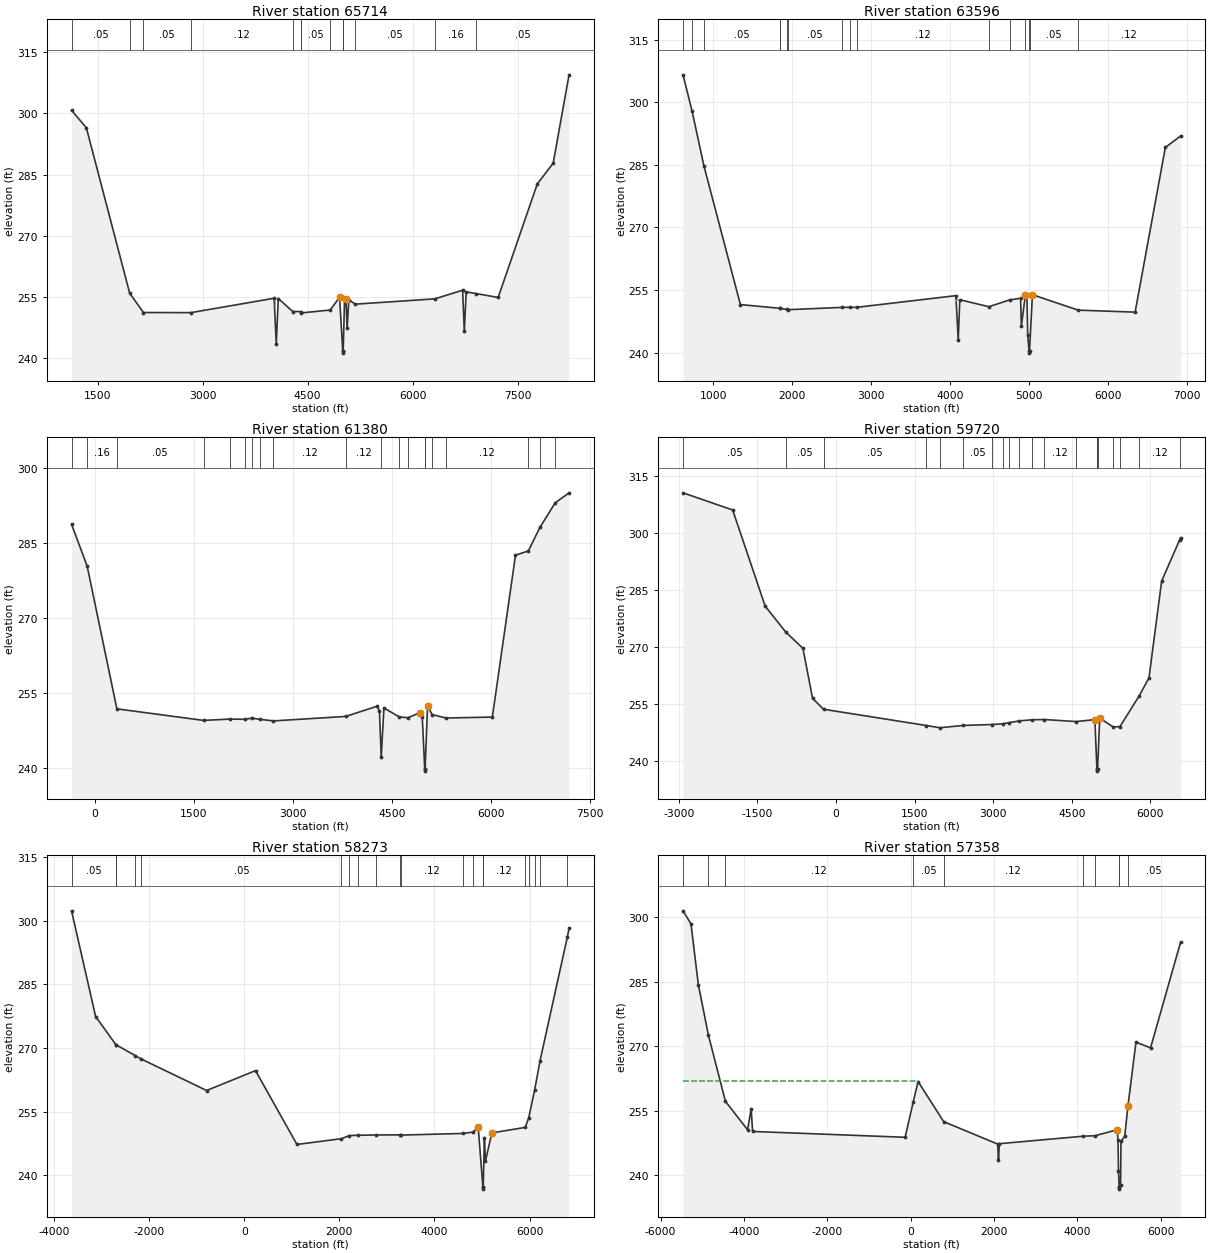
Type RM Length L Ch R = 1 ,65714   ,2118,2118,2118
BEGIN DESCRIPTION:
TEHUACANA CREEK 26.0
END DESCRIPTION:
XS GIS Cut Line= 2
      3612777.41     10686028.44      3611545.07     10679033.56
#Sta/Elev= 30
    1129  300.78  1340.5   296.5  1958.9  255.89    2156  251.15  2833.8  251.12
  4021.1  254.65  4051.6  243.47  4080.7  254.58  4287.6  251.39  4399.5  251.38
  4410.1  251.05  4822.1  251.76  4955.3   254.9  5000.8  241.68  5003.6  241.18
  5006.8  241.68  5026.4  254.14  5046.7  254.47  5063.1  247.32  5087.3  254.22
  5181.2   253.2  6317.3   254.5  6711.9  256.63  6736.5  246.53  6762.7  256.21
  6909.7  255.79  7219.6  254.84  7778.2  282.71  8005.1   287.8  8231.6  309.49
#Mann= 13 ,-1 , 0
    1129     .05       0  1958.9     .12       0    2156     .05       0
  2833.8     .12       0  4287.6     .05       0  4399.5     .07       0
  4410.1     .05       0  4822.1     .07       0  5000.8     .07       0
  5006.8     .07       0  5181.2     .05       0  6317.3     .16       0
  6909.7     .05       0
#XS Ineff= 1 ,-1
 4027.02 4082.23  253.91
Permanent Ineff=
       F
Bank Sta=4955.3,5046.7
XS Rating Curve= 0 ,0
Exp/Cntr=0.3,0.1

Type RM Length L Ch R = 1 ,63596   ,2216,2216,2216
BEGIN DESCRIPTION:
TEHUACANA CREEK 25.0
END DESCRIPTION:
XS GIS Cut Line= 3
      3613784.35     10685906.85       3613853.8     10681827.02
        3613767.     10679605.04
#Sta/Elev= 30
   616.1  306.54   730.6  297.88   880.2  284.77  1342.9  251.49  1843.5   250.6
  1851.1  250.58  1932.4  250.32    1949  250.27  2635.1  250.82  2733.1  250.84
  2815.1  250.83  4073.3  253.63  4103.3  243.04  4123.3  252.65  4491.7  250.98
  4758.6  252.64  4893.5     253  4903.5  246.42  4953.6  253.75  4955.2  253.72
  4973.6  253.43  4983.6   244.2  5000.6  240.36  5003.3  239.86  5006.6  240.36
  5043.6  253.86  5622.6  250.16  6344.6  249.68  6727.6  289.14  6920.2  291.88
#Mann= 16 ,-1 , 0
   616.1     .05       0   730.6     .16       0   880.2     .05       0
  1843.5     .07       0  1851.1     .05       0  1932.4     .07       0
    1949     .05       0  2635.1     .12       0  2733.1     .07       0
  2815.1     .12       0  4491.7     .05       0  4758.6     .07       0
  4955.2     .05       0  5000.6     .03       0  5006.6     .05       0
  5622.6     .12       0
#XS Ineff= 1 ,-1
  4077.4 4124.17   252.5
Permanent Ineff=
       F
Bank Sta=4953.6,5043.6
XS Rating Curve= 0 ,0
Exp/Cntr=0.3,0.1

Type RM Length L Ch R = 1 ,61380   ,1660,1660,1660
BEGIN DESCRIPTION:
TEHUACANA CREEK 24.0
END DESCRIPTION:
XS GIS Cut Line= 3
      3614201.02     10685993.67      3615555.19     10681184.66
      3615676.72      10678649.9
#Sta/Elev= 30
  -354.1  288.82  -117.1  280.41   332.3   251.8    1645  249.48  2050.7  249.75
  2271.2   249.7  2379.2  249.94  2499.3   249.7  2700.8  249.38  3798.4  250.28
  4269.1  252.31  4308.3  251.45  4335.4  242.12  4376.4  251.98  4605.7   250.2
  4738.1  250.01  4916.7     251  4956.8  250.17  4993.8  239.81  4996.6  239.31
  4999.8  239.81  5036.9  252.39  5105.7  250.66  5314.1  249.96    6018  250.15
  6368.4   282.6    6564  283.48  6739.9  288.22  6970.3  293.12  7179.6  295.12
#Mann= 20 ,-1 , 0
  -354.1     .16       0  -117.1     .16       0   332.3     .05       0
    1645     .07       0  2050.7     .05       0  2271.2     .07       0
  2379.2     .05       0  2499.3     .07       0  2700.8     .12       0
  3798.4     .12       0  4335.4     .07       0  4605.7     .12       0
  4738.1     .07       0  4993.8     .07       0  4999.8     .07       0
  5105.7     .07       0  5314.1     .12       0    6564     .16       0
  6739.9     .16       0  6970.3     .16       0
#XS Ineff= 1 ,-1
 4297.48 4376.07  251.62
Permanent Ineff=
       F
Bank Sta=4916.7,5036.9
XS Rating Curve= 0 ,0
Exp/Cntr=0.3,0.1

Type RM Length L Ch R = 1 ,59720   ,1447,1447,1447
BEGIN DESCRIPTION:
TEHUACANA CREEK 23.0
END DESCRIPTION:
XS GIS Cut Line= 3
      3613749.62     10687710.16      3616949.61     10680510.19
      3616749.61     10678910.19
#Sta/Elev= 30
 -2917.1  310.64 -1969.9  306.11 -1350.2  280.74  -953.7  273.85    -630  269.61
    -446  256.41  -236.7  253.53  1724.1  249.24    1984  248.65    2432  249.26
  2975.6   249.5    3178  249.67    3306  249.99  3499.5  250.46  3732.7  250.74
    3972  250.82  4586.2  250.28  4940.1   250.8  4979.1   237.7  4981.9   237.2
  4985.1   237.7  4991.6  237.74  5032.5  251.18  5289.5  248.86  5418.8  248.95
  5786.8  257.09  5972.3  261.81  6214.1  287.36  6558.7  298.27  6574.4  298.79
#Mann= 20 ,-1 , 0
 -2917.1     .05       0  -953.7     .05       0  -236.7     .05       0
  1724.1     .07       0    1984     .05       0    2432     .05       0
  2975.6     .07       0    3178     .07       0    3306     .12       0
  3499.5     .12       0  3732.7     .07       0    3972     .12       0
  4586.2     .12       0  4979.1     .07       0  4985.1     .12       0
  4991.6     .07       0  5289.5     .07       0  5418.8     .12       0
  5786.8     .12       0  6558.7     .16       0
Bank Sta=4940.1,5032.5
XS Rating Curve= 0 ,0
Exp/Cntr=0.3,0.1

Type RM Length L Ch R = 1 ,58273   ,915,915,915
BEGIN DESCRIPTION:
TEHUACANA CREEK 22.0
END DESCRIPTION:
XS GIS Cut Line= 3
      3615049.63     10688110.15      3618249.61     10680110.19
      3616849.63     10678910.21
#Sta/Elev= 30
 -3630.7  302.39 -3124.5  277.43 -2699.7   270.8 -2688.6  270.71 -2291.9  268.22
 -2163.8  267.39  -791.4  259.96   237.2  264.65  1108.2  247.22  2043.1  248.58
  2209.8  249.32  2389.9  249.39  2770.9  249.46    3285  249.49  3289.9  249.43
  4606.3  249.82  4816.9  250.17 4918.18  251.43  5018.2  237.17  5020.9  236.67
  5024.2  237.17  5049.7  248.85  5070.6  243.21  5205.6  249.95    5909  251.25
  5982.6  253.54  6107.2  260.17  6220.3  267.04  6792.1  296.14  6829.4  298.27
#Mann= 20 ,-1 , 0
 -3630.7     .05       0 -2699.7     .08       0 -2688.6     .05       0
 -2291.9     .15       0 -2163.8     .05       0  2043.1     .07       0
  2209.8     .05       0  2389.9     .07       0  2770.9     .12       0
    3285     .07       0  3289.9     .12       0  4606.3     .07       0
  4816.9     .12       0  5018.2     .07       0  5024.2     .12       0
    5909     .16       0  5982.6     .12       0  6107.2     .16       0
  6220.3     .12       0  6792.1     .16       0
Bank Sta=4918.18,5205.6
XS Rating Curve= 0 ,0
Exp/Cntr=0.3,0.1

Type RM Length L Ch R = 1 ,57358   ,945,945,945
BEGIN DESCRIPTION:
TEHUACANA CREEK 21.0
END DESCRIPTION:
XS GIS Cut Line= 3
      3616095.88     10688825.53      3619038.62      10686195.3
      3618960.49     10678200.55
#Sta/Elev= 30
   -5463  301.51 -5272.2  298.49 -5095.8  284.35 -4853.6  272.57   -4445  257.19
 -3912.9  250.56 -3827.6  255.49 -3792.5  250.18    -131  248.82    62.1  257.01
   179.1  261.79   793.8  252.46  2089.2  247.24  2109.2  243.43  2129.2  247.33
  4138.6  249.07    4425  249.18  4959.3  250.58  4979.3  248.15  4989.3  241.01
  5006.3  237.26    5009  236.76  5012.3  237.26  5039.3  237.71  5049.3  247.88
  5139.3  249.07  5217.6  256.15  5409.3  270.95  5759.3  269.63    6479  294.17
#Mann= 10 ,-1 , 0
   -5463     .05       0 -4853.6     .16       0   -4445     .12       0
    62.1     .05       0   793.8     .12       0  4138.6     .07       0
    4425     .12       0  5006.3     .07       0  5012.3     .12       0
  5217.6     .05       0
#XS Ineff= 2 , 0
          172.73  261.84
Permanent Ineff=
       F       F
Bank Sta=4959.3,5217.6
XS Rating Curve= 0 ,0
Exp/Cntr=0.3,0.1

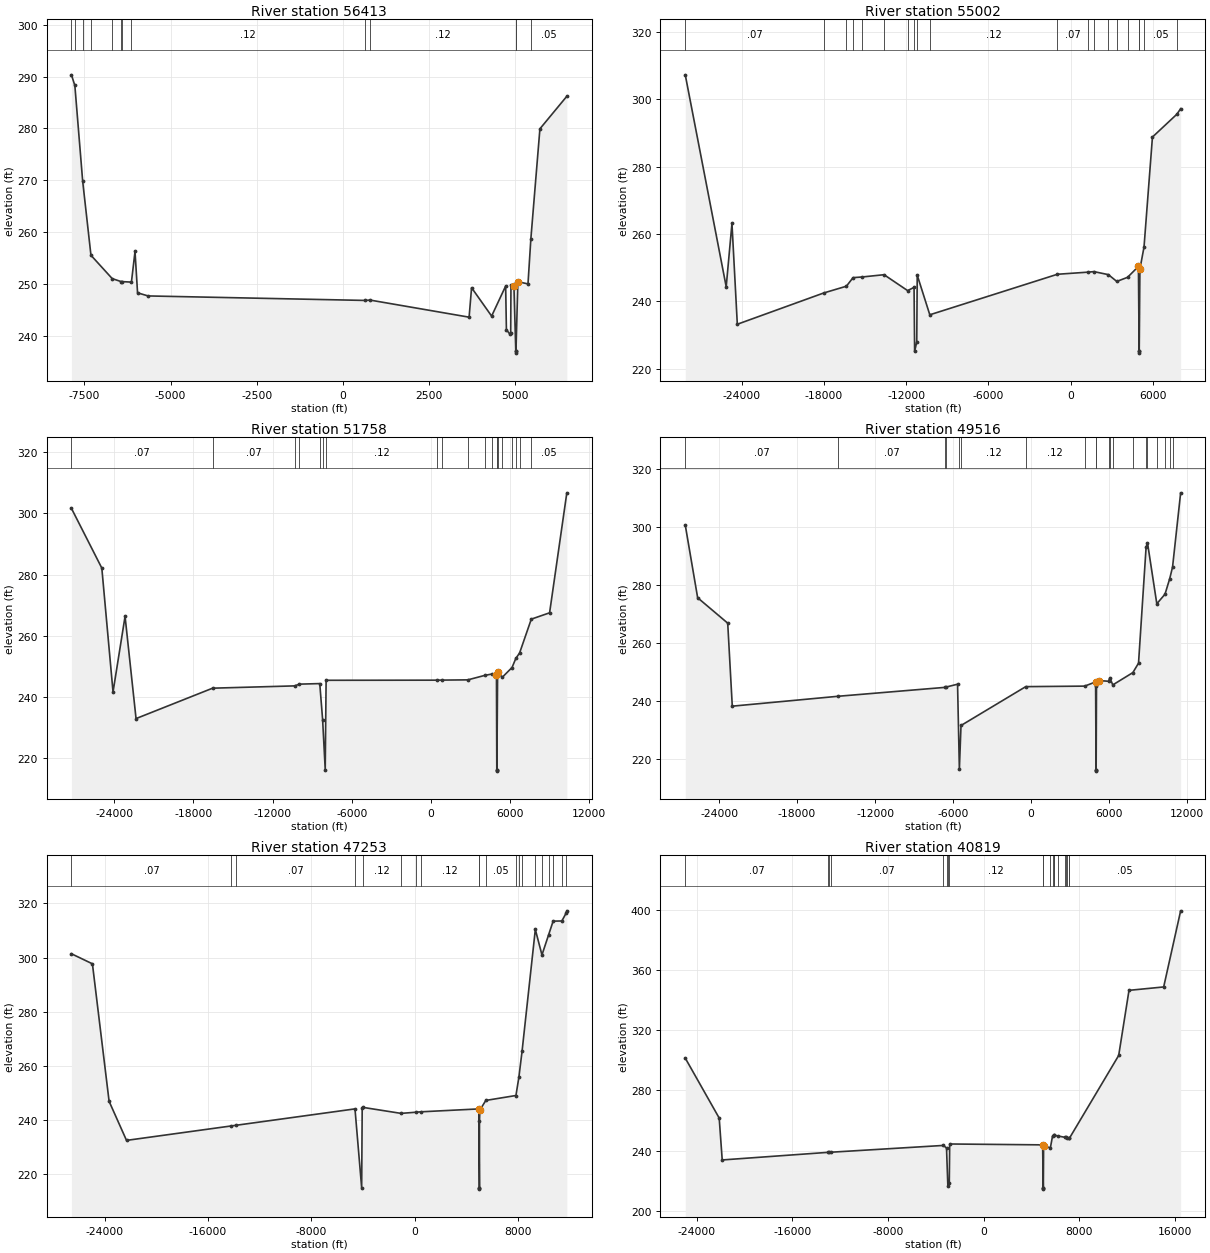
Type RM Length L Ch R = 1 ,56413   ,1411,1411,1411
BEGIN DESCRIPTION:
TEHUACANA CREEK 20.0
END DESCRIPTION:
XS GIS Cut Line= 3
      3616425.73     10689103.31      3621764.31     10685848.08
      3619429.24     10678070.29
#Sta/Elev= 30
 -7878.3  290.34 -7779.3  288.28 -7551.6  269.77   -7312  255.51 -6694.8     251
 -6436.4  250.43 -6401.7  250.42 -6137.5  250.33 -6033.5  256.24 -5959.9  248.26
   -5654  247.66   648.1  246.79   786.4  246.86  3660.1  243.56  3731.4  249.25
  4313.1  243.77  4720.3  249.57  4742.1  241.16  4835.2  240.34  4866.5  240.56
  4874.3  249.74  4960.5  249.58  5013.9  237.12  5016.6  236.62  5019.9  237.12
  5075.3  250.41  5368.3  249.98  5452.2  258.73  5714.4  279.92  6495.2   286.2
#Mann= 13 ,-1 , 0
 -7878.3     .16       0 -7779.3     .12       0 -7551.6     .16       0
   -7312     .12       0 -6694.8     .07       0 -6436.4     .12       0
 -6401.7     .07       0 -6137.5     .12       0   648.1     .07       0
   786.4     .12       0  5013.9     .07       0  5019.9     .12       0
  5452.2     .05       0
Bank Sta=4960.5,5075.3
XS Rating Curve= 0 ,0
Exp/Cntr=0.3,0.1

Type RM Length L Ch R = 1 ,55002   ,3244,3244,3244
BEGIN DESCRIPTION:
TEHUACANA CREEK 19.0
END DESCRIPTION:
XS GIS Cut Line= 3
      3652833.06     10683175.37      3625668.09     10681783.01
      3618251.42       10676783.
#Sta/Elev= 30
  -28120  307.27-25132.6  244.31-24712.1   263.1-24321.6  233.16-18012.1  242.46
-16363.7  244.46  -15876  247.01-15225.3   247.2-13614.3  247.88  -11897  243.16
  -11426  244.11-11384.6  225.08-11229.7  227.88-11194.4  247.75-10276.9  235.97
  -968.6  248.01  1293.6  248.65  1696.1   248.8    2753   247.9  3365.8  245.88
  4154.7  247.11  4945.3  250.35    4997  225.08  4999.8  224.58    5003  225.08
  5053.2  249.56  5352.8   256.1  5967.7  288.78  7748.1  295.56  8025.3  297.21
#Mann= 20 ,-1 , 0
  -28120     .07       0-18012.1     .07       0-16363.7     .12       0
  -15876     .05       0-15225.3     .07       0-13614.3     .07       0
  -11897     .12       0  -11426     .05       0-11229.7     .12       0
-10276.9     .12       0  -968.6     .07       0  1293.6     .12       0
  1696.1     .07       0    2753     .07       0  3365.8     .07       0
  4154.7     .12       0    4997     .07       0    5003     .12       0
  5352.8     .05       0  7748.1     .16       0
Bank Sta=4945.3,5053.2
XS Rating Curve= 0 ,0
Exp/Cntr=0.3,0.1

Type RM Length L Ch R = 1 ,51758   ,2242,2242,2242
BEGIN DESCRIPTION:
TEHUACANA CREEK 18.0
END DESCRIPTION:
XS GIS Cut Line= 3
      3653536.17     10682836.83      3628711.93     10679562.09
      3617774.52     10673468.39
#Sta/Elev= 30
-27253.8  301.66-24949.9  282.13-24100.1  241.64  -23188  266.34-22355.2  232.93
-16550.2  242.87-10331.1  243.62 -9968.1  244.19 -8426.1  244.37 -8208.7  232.53
   -8012  216.25 -7944.7  245.45   453.1  245.49   841.8  245.51  2800.3  245.59
  4074.4  247.04  4663.1  247.53  4970.9  247.06    4997  216.25  4999.8  215.75
    5003  216.25  5057.8  248.07  5062.2  248.04    5413  246.44  6151.9  249.63
  6438.6  252.59  6725.2  254.38  7612.1  265.44  8999.2  267.51 10305.9  306.74
#Mann= 20 ,-1 , 0
-27253.8     .07       0-16550.2     .07       0-10331.1     .12       0
 -9968.1     .07       0 -8426.1     .12       0 -8208.7     .05       0
 -7944.7     .12       0   453.1     .07       0   841.8     .12       0
  2800.3     .07       0  4074.4     .12       0  4663.1     .05       0
    4997     .03       0    5003     .05       0  5062.2     .12       0
    5413     .12       0  6151.9     .12       0  6438.6     .12       0
  6725.2     .05       0  7612.1     .05       0
Bank Sta=4970.9,5057.8
XS Rating Curve= 0 ,0
Exp/Cntr=0.3,0.1

Type RM Length L Ch R = 1 ,49516   ,2263,2263,2263
BEGIN DESCRIPTION:
TEHUACANA CREEK 17.0
END DESCRIPTION:
XS GIS Cut Line= 4
      3654389.29      10681105.2      3640390.17      10678578.3
      3629801.34     10677595.95      3617778.73     10672040.37
#Sta/Elev= 30
-26600.5  300.76-25647.1  275.63-23334.6  266.85-22983.3  238.16-14845.1  241.58
 -6639.8  244.65 -6532.5  244.77 -5655.9  245.75 -5516.6  216.39 -5390.3  231.48
    -411  244.91  4122.4  245.09  4962.1  246.54    4997  216.21  4999.8  215.71
    5003  216.21  5030.9  245.29  5234.2  247.01  5954.7  246.77  6061.7  247.99
  6281.3   245.5    7828  249.76  8263.6  253.02  8845.6  293.05  8952.7  294.64
  9670.2  273.54 10300.6  276.87 10665.9  282.28   10880  286.22 11503.3  311.89
#Mann= 20 ,-1 , 0
-26600.5     .07       0-14845.1     .07       0 -6639.8     .12       0
 -6532.5     .07       0 -5516.6     .05       0 -5390.3     .12       0
    -411     .12       0  4122.4     .12       0    4997     .07       0
    5003     .12       0  5954.7     .05       0  6061.7     .07       0
  6281.3     .05       0    7828     .05       0  8845.6     .08       0
  8952.7     .05       0  9670.2     .16       0 10300.6     .16       0
 10665.9     .16       0   10880     .05       0
Bank Sta=4962.1,5234.2
XS Rating Curve= 0 ,0
Exp/Cntr=0.3,0.1

Type RM Length L Ch R = 1 ,47253   ,6434,6434,6434
BEGIN DESCRIPTION:
Mapping XS 874d2eaf
END DESCRIPTION:
XS GIS Cut Line= 3
      3655262.18      10677207.9      3635576.73     10676502.34
      3617834.18     10670808.06
#Sta/Elev= 30
-26569.4  301.43-24945.8  297.72  -23655  246.96-22307.5  232.54-14207.9  237.87
-13812.4  238.13 -4628.7  244.17 -4112.2  215.05 -4070.9  244.61 -4017.7  244.73
 -1065.3  242.51    61.7  242.93   478.7  243.09  4951.4  244.16    4997  215.05
  4999.8  214.55    5003  215.05  5003.9  239.75  5035.7  243.73  5493.2  247.29
  7824.9  249.11  8054.3  255.89    8297  265.36  9325.3   310.4  9838.4     301
 10351.6   308.4 10703.1  313.47   11378  313.54 11705.3  316.41 11762.6  317.28
#Mann= 20 ,-1 , 0
-26569.4     .07       0-14207.9     .07       0-13812.4     .07       0
 -4628.7     .12       0 -4017.7     .12       0 -1065.3     .07       0
    61.7     .07       0   478.7     .12       0    4997     .07       0
    5003     .12       0  5493.2     .05       0  7824.9     .05       0
  8054.3     .16       0    8297     .05       0  9325.3     .05       0
  9838.4     .16       0 10351.6     .16       0 10703.1     .05       0
   11378     .12       0 11705.3     .16       0
Bank Sta=4951.4,5035.7
XS Rating Curve= 0 ,0
Exp/Cntr=0.3,0.1

Type RM Length L Ch R = 1 ,40819   ,4631,4631,4631
BEGIN DESCRIPTION:
TEHUACANA CREEK 15.0
END DESCRIPTION:
XS GIS Cut Line= 3
      3654240.08     10677032.96      3638232.98     10675175.14
      3616410.04     10662336.58
#Sta/Elev= 30
-24946.9  301.52-22108.2  261.63-21855.8  233.76-12985.2  238.83-12886.1  238.86
-12786.9  238.89   -3352  243.42 -3094.8  241.71 -2982.5  216.33 -2863.6  218.53
 -2830.1  244.38  4943.3   243.8    4997  214.85  4999.8  214.35    5003  214.85
  5024.6  243.32  5590.4   241.8  5771.2  249.58  5883.4   250.2  5926.3  250.14
    6188  249.75  6785.7  248.86  6893.4   248.7  7005.6  248.53  7140.3  248.33
  7187.6  248.26 11305.1  303.27 12168.2  346.59   15068  348.85   16487  399.49
#Mann= 20 ,-1 , 0
-24946.9     .07       0-12985.2     .05       0-12886.1     .08       0
-12786.9     .07       0   -3352     .12       0 -3094.8     .07       0
 -2982.5     .05       0 -2863.6     .12       0    4997     .07       0
    5003     .12       0  5590.4     .07       0  5771.2     .12       0
  5883.4     .05       0  5926.3     .07       0    6188     .05       0
  6785.7     .05       0  6893.4     .07       0  7005.6     .05       0
  7140.3     .07       0  7187.6     .05       0
Bank Sta=4943.3,5024.6
XS Rating Curve= 0 ,0
Exp/Cntr=0.3,0.1