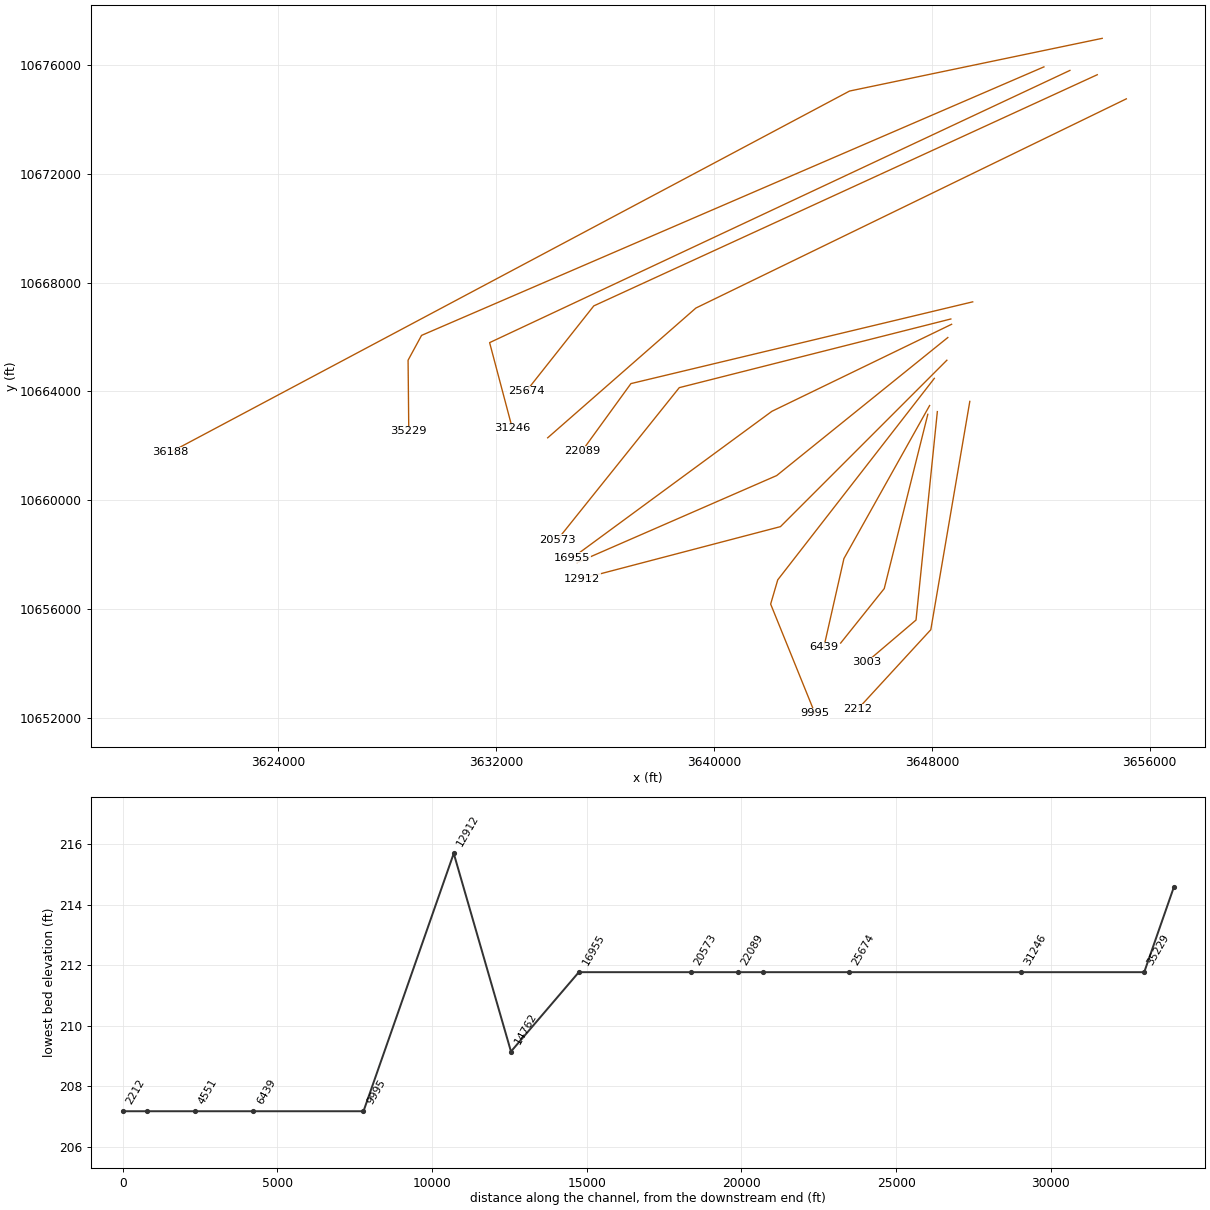
HEC-RAS study TEHUACANA CREEK.prj: TEHUACANA CREEK Base Level Engineering

--- TEHUACANA CREEK.g01 (geometry) --- (continued)

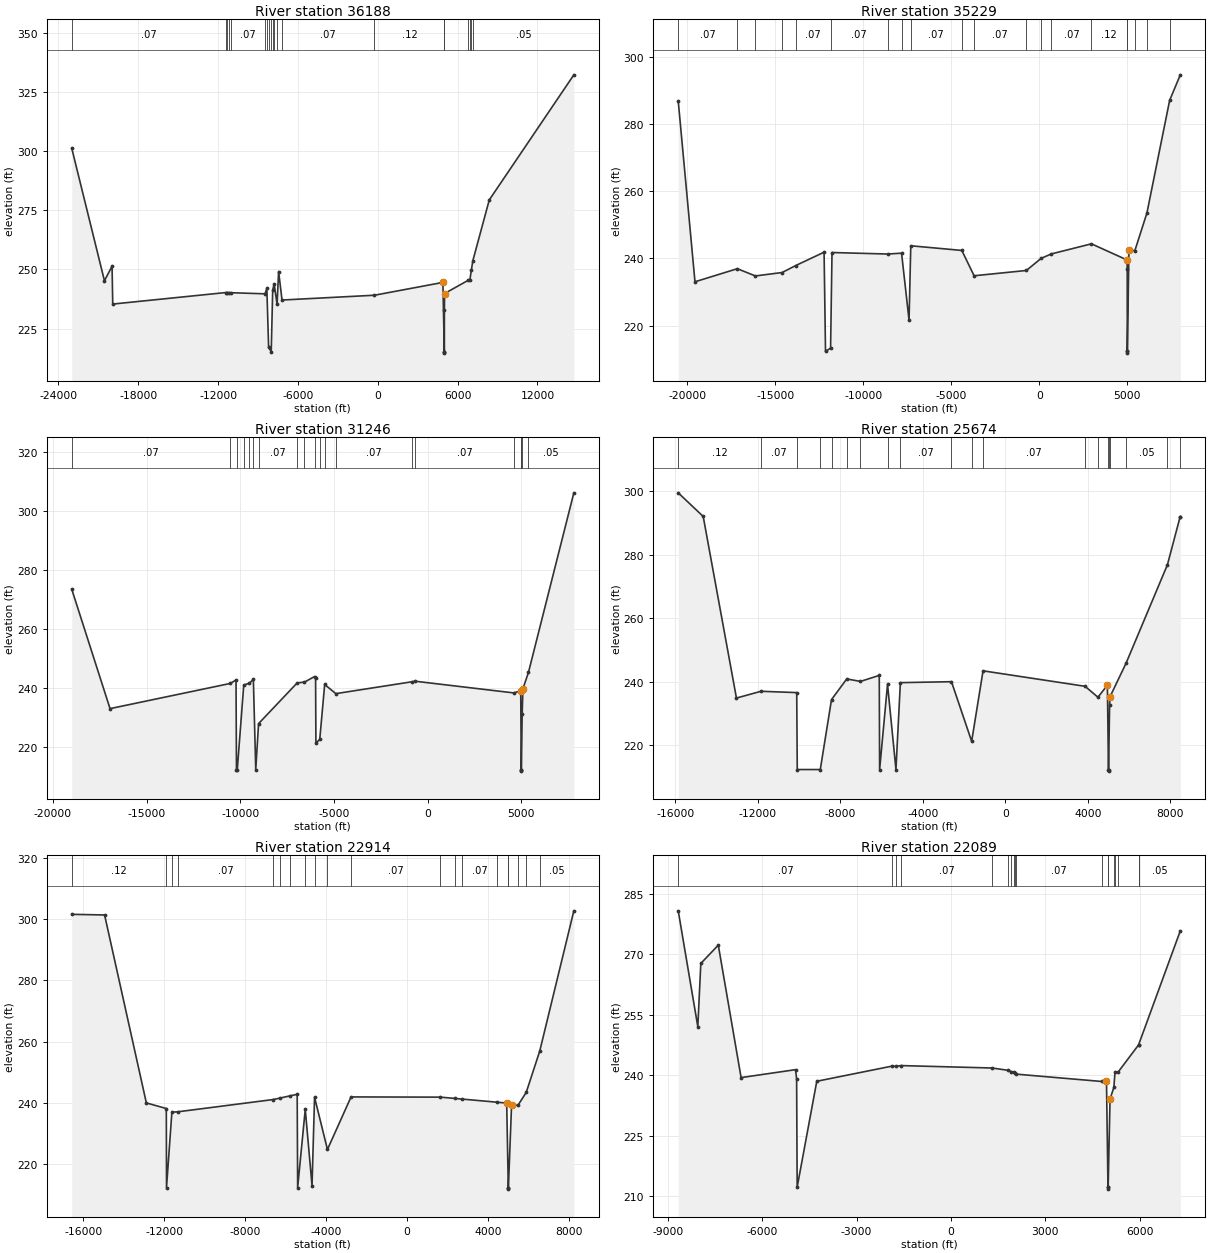
Type RM Length L Ch R = 1 ,36188   ,959,959,959
BEGIN DESCRIPTION:
TEHUACANA CREEK 14.0
END DESCRIPTION:
XS GIS Cut Line= 3
      3654254.39     10676967.53      3644974.86     10675031.76
      3620028.79     10661762.48
#Sta/Elev= 30
-23001.1   301.3-20545.4  245.23-19972.5   251.4-19921.4  235.36-11433.5  240.23
-11303.9  240.21-11168.7  240.19-11060.4  240.17 -8478.3   239.7 -8339.2  241.97
 -8206.5  217.02 -8009.8  215.17   -7900  241.27 -7790.2  243.92 -7570.6  235.24
 -7455.4  249.15 -7198.1  237.07  -251.5   239.1  4892.9  244.53    4997  215.08
  4999.8  214.58    5003  215.08  5003.3  232.88  5019.1  239.82  6780.4  245.38
  6922.9  245.69  7032.7  249.82  7142.4  253.71  8377.7  279.47 14733.8  332.45
#Mann= 20 ,-1 , 0
-23001.1     .07       0-11433.5     .05       0-11303.9     .07       0
-11168.7     .05       0-11060.4     .07       0 -8478.3     .05       0
 -8339.2     .07       0 -8206.5     .05       0 -8009.8     .07       0
   -7900     .12       0 -7790.2     .12       0 -7570.6     .05       0
 -7198.1     .07       0  -251.5     .12       0    4997     .07       0
    5003     .12       0  6780.4     .07       0  6922.9     .05       0
  7032.7     .07       0  7142.4     .05       0
Bank Sta=4892.9,5019.1
XS Rating Curve= 0 ,0
Exp/Cntr=0.3,0.1

Type RM Length L Ch R = 1 ,35229   ,3983,3983,3983
BEGIN DESCRIPTION:
TEHUACANA CREEK 13.0
END DESCRIPTION:
XS GIS Cut Line= 4
      3652113.21     10675919.26      3629257.66      10666058.4
      3628762.87     10665146.94       3628788.9     10662543.99
#Sta/Elev= 30
-20521.4  286.88  -19570  233.03  -17163  236.93-16136.6  234.77-14619.2  235.79
-13846.6  237.86-12233.1  241.85-12151.7  212.27-11863.6  213.27-11782.9  241.75
 -8626.8   241.3 -7829.6  241.55 -7404.6  221.61 -7306.2  243.76 -4405.2  242.37
 -3708.5  234.82  -735.2   236.4    99.7     240     677  241.33  2959.9  244.34
  4981.1  239.54  4994.4  236.92    4997  212.27  4999.8  211.77    5003  212.27
  5090.4  242.53  5425.8  242.27  6113.6  253.53  7405.5  287.11  8010.8   294.7
#Mann= 20 ,-1 , 0
-20521.4     .07       0  -17163     .05       0-16136.6     .07       0
-14619.2     .05       0-13846.6     .07       0-11863.6     .07       0
 -8626.8     .12       0 -7829.6     .05       0 -7306.2     .07       0
 -4405.2     .07       0 -3708.5     .07       0  -735.2     .07       0
    99.7     .12       0     677     .07       0  2959.9     .12       0
    4997     .07       0    5003     .12       0  5425.8     .05       0
  6113.6     .12       0  7405.5     .12       0
Bank Sta=4981.1,5090.4
XS Rating Curve= 0 ,0
Exp/Cntr=0.3,0.1

Type RM Length L Ch R = 1 ,31246   ,5572,5572,5572
BEGIN DESCRIPTION:
TEHUACANA CREEK 12.0
END DESCRIPTION:
XS GIS Cut Line= 3
      3653068.13     10675789.08      3631757.34     10665792.54
      3632590.68     10662646.66
#Sta/Elev= 30
-18990.2  273.39-16948.4  232.95-10534.7  241.48-10224.4  242.65-10201.5  212.27
-10157.9  212.27 -9812.2  240.96 -9512.7  241.55 -9299.2  242.87 -9172.4  212.27
 -9021.1  227.87 -6957.4  241.69 -6574.9  241.92   -6036  243.82 -5978.9   243.4
 -5961.6  221.24 -5757.1  222.51 -5493.9  241.13 -4898.5  238.03  -807.9  242.08
  -657.1  242.23  4591.3  238.28  4968.9  238.95    4997  212.27  4999.8  211.77
    5003  212.27  5045.6  231.19  5084.4  239.67  5380.5  245.21  7803.1  306.08
#Mann= 20 ,-1 , 0
-18990.2     .07       0-10534.7     .12       0-10157.9     .05       0
 -9812.2     .12       0 -9512.7     .12       0 -9299.2     .05       0
 -9021.1     .07       0 -6957.4     .07       0 -6574.9     .12       0
   -6036     .05       0 -5757.1     .07       0 -5493.9     .07       0
 -4898.5     .07       0  -807.9     .08       0  -657.1     .07       0
  4591.3     .12       0    4997     .07       0    5003     .12       0
  5045.6     .07       0  5380.5     .05       0
Bank Sta=4968.9,5084.4
XS Rating Curve= 0 ,0
Exp/Cntr=0.3,0.1

Type RM Length L Ch R = 1 ,25674   ,2760,2760,2760
BEGIN DESCRIPTION:
Mapping XS 74c18680
END DESCRIPTION:
XS GIS Cut Line= 3
      3654072.49      10675631.1      3635582.86      10667141.5
      3633104.02     10664009.07
#Sta/Elev= 30
-15859.7  299.53-14649.4  292.08-13037.8  234.81-11845.9  236.95-10115.8  236.53
-10089.5  212.27 -8973.5  212.27 -8429.4  234.33 -7689.9  240.84 -7024.5  240.06
 -6114.2  241.96 -6096.7  212.27 -5713.4  239.14 -5305.1  212.27 -5090.8  239.67
 -2613.4  239.97 -1634.6  221.17 -1082.5   243.4  3862.7  238.52  4487.2  235.07
  4945.3  238.88    4997  212.27  4999.8  211.77    5003  212.27  5052.2  232.67
  5065.4  235.14  5848.9  245.78  7855.5  276.84  8463.4  291.78  8480.4  292.01
#Mann= 20 ,-1 , 0
-15859.7     .12       0-11845.9     .07       0-10115.8     .05       0
 -8973.5     .05       0 -8429.4     .07       0 -7689.9     .07       0
 -7024.5     .12       0 -5713.4     .07       0 -5090.8     .07       0
 -2613.4     .12       0 -1634.6     .07       0 -1082.5     .07       0
  3862.7     .07       0  4487.2     .12       0    4997     .07       0
    5003     .12       0  5052.2     .07       0  5848.9     .05       0
  7855.5     .05       0  8463.4     .08       0
Bank Sta=4945.3,5065.4
XS Rating Curve= 0 ,0
Exp/Cntr=0.3,0.1

Type RM Length L Ch R = 1 ,22914   ,825,825,825
BEGIN DESCRIPTION:
TEHUACANA CREEK 11.0
END DESCRIPTION:
XS GIS Cut Line= 3
      3655140.16     10674745.67      3639332.86     10667063.37
      3633890.12     10662297.72
#Sta/Elev= 30
-16572.8  301.56-14950.9  301.36-12887.4  239.94-11900.8  238.11-11891.3  212.27
-11625.8  236.92-11329.7  237.04 -6615.7  241.05 -6282.7  241.53 -5777.7  242.26
 -5433.7  242.75 -5411.2  212.27   -5035  237.85 -4700.8  212.92   -4576  241.79
 -3939.2  224.73   -2772   241.9  1641.2  241.83  2381.4  241.39  2710.3   241.2
  4443.4  240.17  4918.6  239.89    4997  212.27  4999.8  211.77    5003  212.27
  5159.7  239.34  5473.2  239.15  5883.6  243.37  6551.3  256.88  8236.7  302.71
#Mann= 20 ,-1 , 0
-16572.8     .12       0-11900.8     .05       0-11625.8     .12       0
-11329.7     .07       0 -6615.7     .12       0 -6282.7     .07       0
 -5777.7     .07       0   -5035     .05       0   -4576     .12       0
 -3939.2     .12       0   -2772     .07       0  1641.2     .12       0
  2381.4     .12       0  2710.3     .07       0  4443.4     .07       0
    4997     .07       0    5003     .07       0  5473.2     .05       0
  5883.6     .12       0  6551.3     .05       0
Bank Sta=4918.6,5159.7
XS Rating Curve= 0 ,0
Exp/Cntr=0.3,0.1

Type RM Length L Ch R = 1 ,22089   ,1516,1516,1516
BEGIN DESCRIPTION:
TEHUACANA CREEK 10.0
END DESCRIPTION:
XS GIS Cut Line= 3
      3649498.12     10667290.51       3636946.7     10664288.13
      3635149.62      10661810.2
#Sta/Elev= 30
 -8669.2  280.79 -8046.6  252.07   -7951  267.74 -7395.2  272.28   -6670  239.43
 -4938.3   241.4 -4904.5   239.1 -4886.9  212.27 -4263.4  238.52 -1856.3   242.3
 -1756.6   242.2 -1587.3  242.41  1311.8  241.81    1813  241.24  1927.9  240.92
  2008.7   240.7  2033.1  240.63  2077.6  240.29  4793.8  238.47  4949.7  238.51
    4997  212.27  4999.8  211.77    5003  212.27  5062.5  234.11  5183.8     237
  5219.6  240.74  5329.2   240.9  5967.9  247.52    5969  247.53  7297.3  275.83
#Mann= 18 ,-1 , 0
 -8669.2     .07       0 -1856.3     .05       0 -1756.6     .08       0
 -1587.3     .07       0  1311.8     .12       0    1813     .07       0
  1927.9     .12       0  2008.7     .07       0  2033.1     .12       0
  2077.6     .07       0  4793.8     .12       0    4997     .07       0
    5003     .12       0  5183.8     .07       0  5219.6     .05       0
  5329.2     .12       0  5967.9     .07       0    5969     .05       0
Bank Sta=4949.7,5062.5
XS Rating Curve= 0 ,0
Exp/Cntr=0.3,0.1

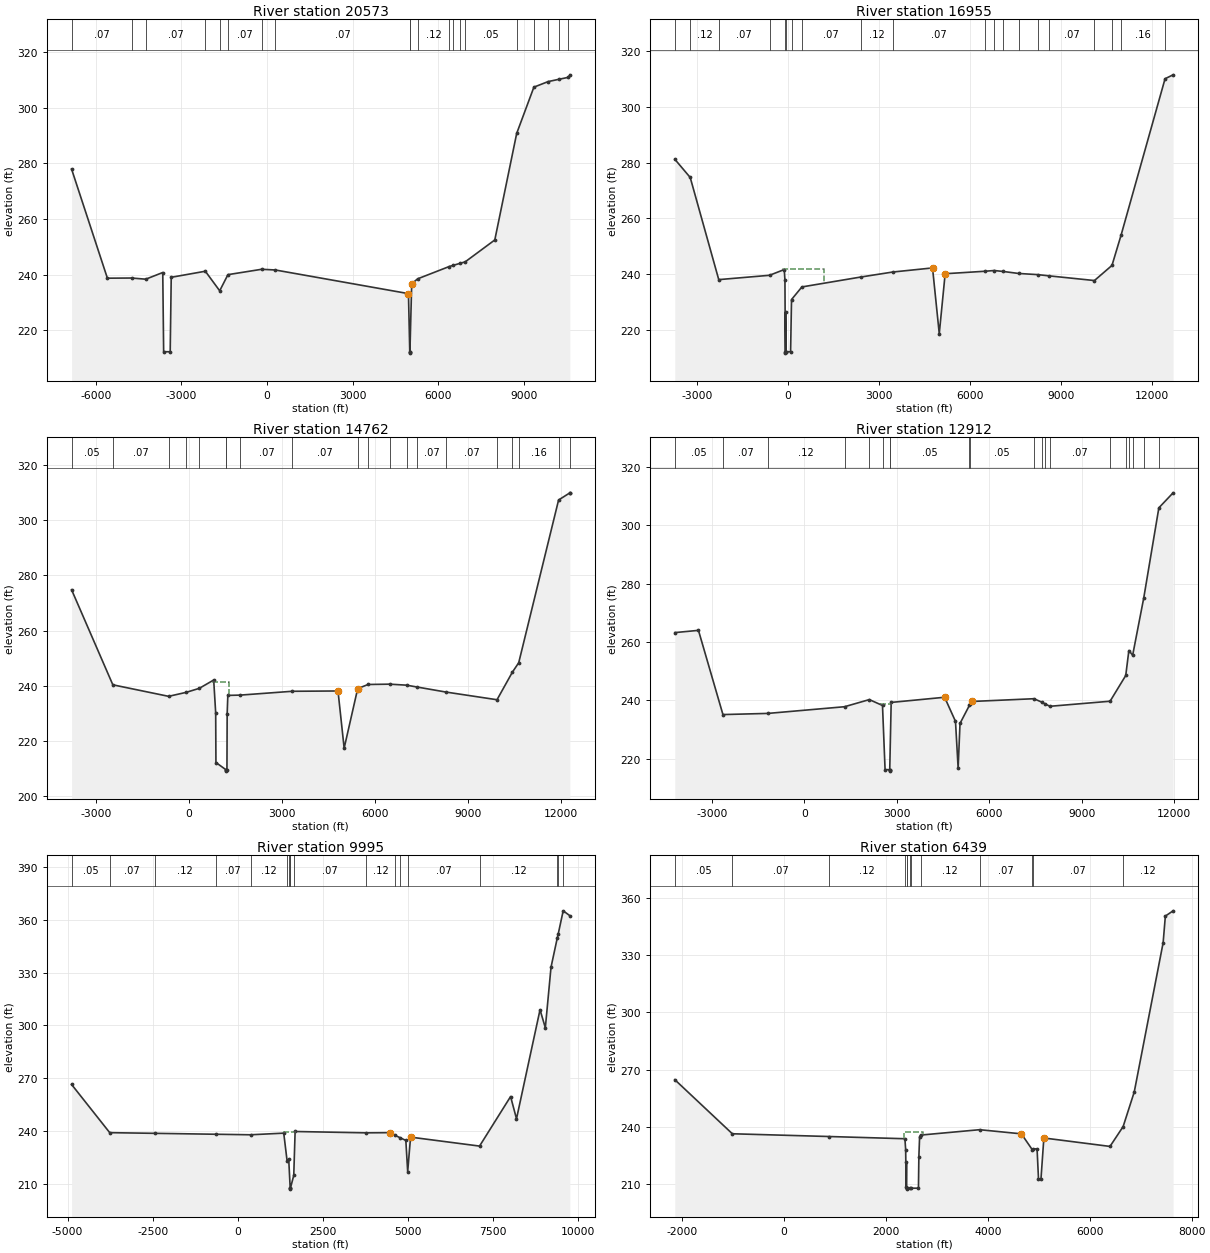
Type RM Length L Ch R = 1 ,20573   ,3618,3618,3618
BEGIN DESCRIPTION:
Mapping XS a715be54
END DESCRIPTION:
XS GIS Cut Line= 3
      3648695.22     10666661.18      3638722.94     10664139.65
      3634244.16     10658549.86
#Sta/Elev= 30
 -6845.3  277.91 -5591.4   238.7 -4741.5  238.76 -4248.5  238.34 -3652.3  240.74
 -3621.3  212.27 -3391.7  212.27 -3355.9  239.02 -2161.3   241.2 -1658.6  234.17
 -1370.1  239.97  -189.5   241.9   288.7  241.65  4951.6  233.15    4997  212.27
  4999.8  211.77    5003  212.27  5065.3  236.72  5275.6  238.48  6380.8   242.9
    6505  243.27  6769.9  244.07  6939.5  244.58    7975  252.44  8741.7  290.73
  9343.9  307.35  9842.1  309.35 10214.1  310.16 10553.7  310.89 10603.6  311.78
#Mann= 20 ,-1 , 0
 -6845.3     .07       0 -4741.5     .12       0 -4248.5     .07       0
 -2161.3     .12       0 -1658.6     .07       0 -1370.1     .07       0
  -189.5     .05       0   288.7     .07       0    4997     .07       0
    5003     .07       0  5275.6     .12       0  6380.8     .05       0
    6505     .07       0  6769.9     .12       0  6939.5     .05       0
  8741.7     .16       0  9343.9     .05       0  9842.1     .16       0
 10214.1     .05       0 10553.7     .08       0
Bank Sta=4951.6,5065.3
XS Rating Curve= 0 ,0
Exp/Cntr=0.3,0.1

Type RM Length L Ch R = 1 ,16955   ,2193,2193,2193
BEGIN DESCRIPTION:
TEHUACANA CREEK 9.0
END DESCRIPTION:
XS GIS Cut Line= 3
      3648722.97     10666466.05      3642125.72     10663271.59
      3634799.32     10657889.64
#Sta/Elev= 30
 -3721.9  281.22 -3214.1  274.69 -2273.7   238.1  -600.9  239.65  -115.1  241.71
   -92.5  237.98   -78.5  212.27   -75.7  211.77   -72.5  212.27   -69.9  226.47
   -62.8  212.27    93.7  212.27   124.8  230.97   466.4  235.48  2401.5  239.02
  3458.5  240.82  4771.6  242.29  4993.1  218.75  5187.5  240.21  6485.1  241.09
  6803.7  241.36  7109.9  241.01  7604.5  240.31  8236.3  239.89  8601.9  239.46
 10106.9  237.77 10685.2  243.19 10986.7   254.1 12434.3  310.06 12698.8  311.46
#Mann= 20 ,-1 , 0
 -3721.9     .05       0 -3214.1     .12       0 -2273.7     .07       0
  -600.9     .12       0   -78.5     .07       0   -72.5     .05       0
   124.8     .12       0   466.4     .07       0  2401.5     .12       0
  3458.5     .07       0  6485.1     .05       0  6803.7     .12       0
  7109.9     .07       0  7604.5     .07       0  8236.3     .07       0
  8601.9     .07       0 10106.9     .05       0 10685.2     .05       0
 10986.7     .16       0 12434.3     .05       0
#XS Ineff= 1 ,-1
 -144.32 1205.68  241.75
Permanent Ineff=
       F
Bank Sta=4771.6,5187.5
XS Rating Curve= 0 ,0
Exp/Cntr=0.3,0.1

Type RM Length L Ch R = 1 ,14762   ,1850,1850,1850
BEGIN DESCRIPTION:
TEHUACANA CREEK 8.0
END DESCRIPTION:
XS GIS Cut Line= 3
      3648584.09     10665979.96      3642299.33     10660910.48
       3634973.8     10657716.41
#Sta/Elev= 30
 -3777.1   274.8 -2446.8  240.39  -648.1  236.22   -75.5  237.68   341.2  239.12
   805.3  242.13   869.3  230.22   877.3  212.27  1200.6  209.65  1203.3  209.15
  1206.6  209.65  1232.3  209.65  1239.3   229.9  1261.1  236.56    1667  236.67
  3336.4  238.05  4813.2  238.16  5011.4  217.46  5448.1  239.02  5783.2  240.51
  6478.8  240.63  7024.1  240.26  7359.5   239.6    8288  237.78  9940.2  234.99
 10436.3  244.98 10639.6  248.37 11925.7  307.29 12285.2  309.84   12289  309.88
#Mann= 20 ,-1 , 0
 -3777.1     .05       0 -2446.8     .07       0  -648.1     .12       0
   -75.5     .07       0   341.2     .12       0  1200.6     .07       0
  1206.6     .12       0    1667     .07       0  3336.4     .07       0
  5448.1     .05       0  5783.2     .05       0  6478.8     .05       0
  7024.1     .05       0  7359.5     .07       0    8288     .07       0
  9940.2     .05       0 10436.3     .12       0 10639.6     .16       0
 11925.7     .05       0 12285.2     .05       0
#XS Ineff= 1 ,-1
  755.68  1287.5  241.45
Permanent Ineff=
       F
Bank Sta=4813.2,5448.1
XS Rating Curve= 0 ,0
Exp/Cntr=0.3,0.1

Type RM Length L Ch R = 1 ,12912   ,2917,2917,2917
BEGIN DESCRIPTION:
TEHUACANA CREEK 7.0
END DESCRIPTION:
XS GIS Cut Line= 3
      3648549.32     10665146.59      3642438.22     10659035.48
      3635146.56     10657125.76
#Sta/Elev= 30
 -4208.1  263.23 -3440.1     264 -2645.1   235.1   -1184   235.5  1302.2  237.79
  2108.7  240.24  2536.1  238.22  2619.8   216.2  2765.3  216.19    2768  215.69
  2771.3  216.19  2817.8  239.27  4552.8  241.04  4906.2  232.77  4992.1  216.73
  5053.1  232.06  5357.3  238.24  5380.1  238.86  5426.3  239.59  7454.1  240.54
  7699.7   239.4  7802.2  238.85  7971.7  237.94  9926.3  239.68 10434.6  248.51
 10535.9  257.07 10659.5  255.48   11019  275.11 11509.8  306.05 11971.9   311.2
#Mann= 20 ,-1 , 0
 -4208.1     .05       0 -2645.1     .07       0   -1184     .12       0
  1302.2     .07       0  2108.7     .12       0  2536.1     .05       0
  2765.3     .07       0  2771.3     .05       0  5357.3     .05       0
  5380.1     .05       0  7454.1     .07       0  7699.7     .07       0
  7802.2     .05       0  7971.7     .07       0  9926.3     .05       0
 10434.6     .08       0 10535.9      .1       0 10659.5     .05       0
   11019     .12       0 11509.8     .05       0
#XS Ineff= 1 ,-1
 2464.23 2842.36  238.71
Permanent Ineff=
       F
Bank Sta=4552.8,5426.3
XS Rating Curve= 0 ,0
Exp/Cntr=0.3,0.1

Type RM Length L Ch R = 1 ,9995    ,3556,3556,3556
BEGIN DESCRIPTION:
TEHUACANA CREEK 6.0
END DESCRIPTION:
XS GIS Cut Line= 4
      3648089.27      10664480.9       3642338.4     10657080.73
      3642077.99     10656190.98      3643705.08     10652177.46
#Sta/Elev= 30
   -4882  266.53 -3761.9   239.2 -2436.2  238.82  -647.4   238.3   372.8     238
  1347.3  238.93  1447.4  222.92  1493.6  224.13  1536.9  207.68  1539.6  207.18
  1542.9  207.68  1641.2  214.94  1681.2  239.86  3758.4   239.1 4463.64   239.2
  4611.8  237.72    4764  236.33  4932.1   234.8  4986.3  217.16    5071  236.67
  7096.5  231.59  8007.7  259.68    8181  247.07  8872.3  308.92  9027.7  298.66
  9194.6  333.02  9377.7  349.54  9403.4  351.63  9551.8     365  9747.9  362.25
#Mann= 18 ,-1 , 0
   -4882     .05       0 -3761.9     .07       0 -2436.2     .12       0
  -647.4     .07       0   372.8     .12       0  1447.4     .08       0
  1493.6     .05       0  1536.9     .07       0  1542.9     .05       0
  1641.2     .07       0  3758.4     .12       0  4611.8     .07       0
    4764     .12       0  4986.3     .07       0  7096.5     .12       0
  9377.7     .16       0  9403.4     .12       0  9551.8     .16       0
#XS Ineff= 1 ,-1
 1341.98 1712.89  239.48
Permanent Ineff=
       F
Bank Sta=4463.64,5071
XS Rating Curve= 0 ,0
Exp/Cntr=0.3,0.1

Type RM Length L Ch R = 1 ,6439    ,1888,1888,1888
BEGIN DESCRIPTION:
TEHUACANA CREEK 4.0
END DESCRIPTION:
XS GIS Cut Line= 3
      3647915.67     10663482.66      3644768.96     10657861.98
       3644031.1     10654606.73
#Sta/Elev= 30
 -2143.5  264.69 -1014.2  236.27   877.9  234.83  2372.9  233.66  2387.3  227.88
  2397.6  208.25  2403.3  221.48  2406.1  207.68  2408.9  207.18  2412.1  207.68
  2472.1  207.68  2488.3  207.68  2638.4  207.68  2646.5   224.3  2661.3   234.8
  2681.8  235.58  3838.3  238.41  4658.8  236.23  4875.5  227.77  4884.6   228.3
  4966.4  228.34  4994.2  212.74  5042.4  212.28  5099.7  234.06  6397.7  229.62
  6655.7  240.06  6873.6  258.23  7440.9  336.71    7484  350.65  7635.9  353.42
#Mann= 13 ,-1 , 0
 -2143.5     .05       0 -1014.2     .07       0   877.9     .12       0
  2372.9     .07       0  2406.1     .07       0  2412.1     .07       0
  2472.1     .12       0  2488.3     .05       0  2681.8     .12       0
  3838.3     .07       0  4875.5     .05       0  4884.6     .07       0
  6655.7     .12       0
#XS Ineff= 1 ,-1
 2346.78 2718.33  237.33
Permanent Ineff=
       F
Bank Sta=4658.8,5099.7
XS Rating Curve= 0 ,0
Exp/Cntr=0.3,0.1

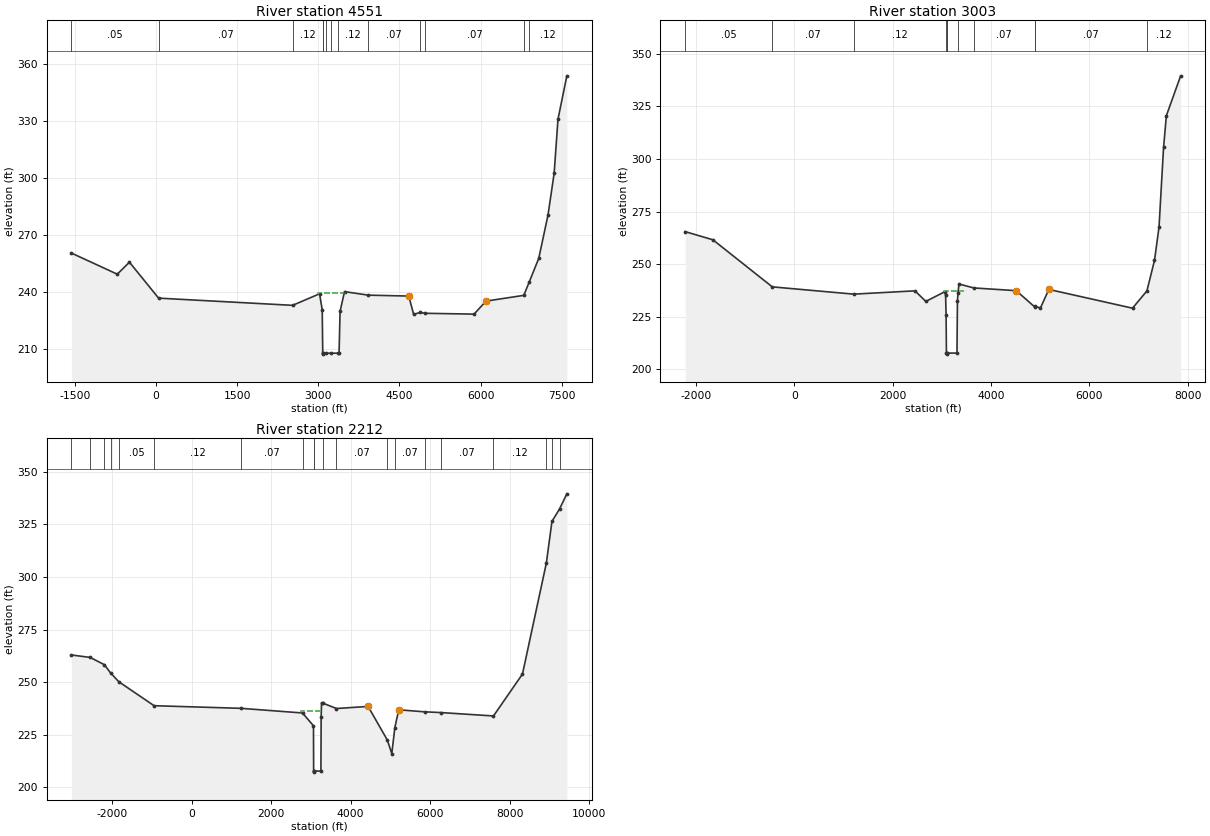
Type RM Length L Ch R = 1 ,4551    ,1548,1548,1548
BEGIN DESCRIPTION:
TEHUACANA CREEK 3.0
END DESCRIPTION:
XS GIS Cut Line= 3
      3647849.61     10663160.19      3646249.61     10656760.19
      3644649.62     10654760.21
#Sta/Elev= 30
 -1563.7  260.33  -715.9  249.23  -491.7  255.55    47.6  236.63  2524.9  232.84
  3023.3  238.92  3072.2  230.51  3082.1  207.68  3084.9  207.18  3088.1  207.68
  3136.6  207.68  3229.1  207.68  3358.9  207.68    3384  207.68  3402.1  229.67
  3484.5  240.05  3924.9   238.2  4672.5  237.72  4762.7  228.05  4884.1  229.15
  4971.2  228.66  5879.3  228.22  6100.2  235.07  6798.7  238.09  6901.9   245.3
  7075.1  257.54  7246.4  280.35    7360  302.32  7430.4  330.66  7594.5  353.56
#Mann= 13 ,-1 , 0
 -1563.7     .05       0    47.6     .07       0  2524.9     .12       0
  3082.1     .07       0  3088.1     .12       0  3136.6     .07       0
  3229.1     .05       0  3358.9     .12       0  3924.9     .07       0
  4884.1     .05       0  4971.2     .07       0  6798.7     .05       0
  6901.9     .12       0
#XS Ineff= 1 ,-1
 2988.64 3539.77  239.25
Permanent Ineff=
       F
Bank Sta=4672.5,6100.2
XS Rating Curve= 0 ,0
Exp/Cntr=0.3,0.1

Type RM Length L Ch R = 1 ,3003    ,791,791,791
BEGIN DESCRIPTION:
TEHUACANA CREEK 2.0
END DESCRIPTION:
XS GIS Cut Line= 3
      3648199.61     10663260.19      3647416.53     10655605.04
      3645599.61     10654060.19
#Sta/Elev= 30
 -2221.9  265.45   -1659  261.58    -451  239.18    1206  235.72  2452.4  237.29
  2673.5  232.26  3065.6  236.95  3075.6  235.36  3085.7  225.73  3092.7  207.68
  3095.5  207.18  3098.7  207.68  3113.6  207.68  3306.8  207.68  3316.9  232.58
  3329.1  236.37    3347  240.55  3649.8  238.67  4513.7  237.37  4889.3  229.61
  4898.3  229.85  5005.7  229.16  5176.5  237.96    6879  229.04  7171.7  237.26
    7326  251.75  7418.3  267.63  7510.5  305.49  7567.6  320.61  7858.1  339.59
#Mann= 11 ,-1 , 0
 -2221.9     .05       0    -451     .07       0    1206     .12       0
  3092.7     .07       0  3098.7     .12       0  3113.6     .05       0
  3329.1     .12       0  3649.8     .07       0  4889.3     .05       0
  4898.3     .07       0  7171.7     .12       0
#XS Ineff= 1 ,-1
    3050 3459.09  237.15
Permanent Ineff=
       F
Bank Sta=4513.7,5176.5
XS Rating Curve= 0 ,0
Exp/Cntr=0.3,0.1

Type RM Length L Ch R = 1 ,2212    ,0,0,0
BEGIN DESCRIPTION:
TEHUACANA CREEK 1.0
END DESCRIPTION:
XS GIS Cut Line= 3
      3649391.62     10663634.79      3647959.33     10655249.37
      3645278.18     10652333.95
#Sta/Elev= 30
 -3027.7  262.89 -2555.9  261.73 -2198.4  258.26 -2043.9  254.39 -1836.2  250.17
  -947.8  238.77  1238.8  237.52  2787.6  235.31  3063.9  229.21  3067.5  207.68
  3070.2  207.18  3073.5  207.68  3250.9  207.68  3256.6  233.27  3266.8  240.19
  3309.1  239.92  3642.5  237.43  4438.3  238.42  4922.1  222.44  5034.5  215.99
  5111.7  228.38  5209.9  236.82  5865.6  235.85  6266.8  235.51  7593.7  233.89
  8323.4  253.82  8924.7  306.64  9065.3  326.43  9255.3  332.29    9440  339.53
#Mann= 20 ,-1 , 0
 -3027.7     .05       0 -2555.9     .16       0 -2198.4     .05       0
 -2043.9     .16       0 -1836.2     .05       0  -947.8     .12       0
  1238.8     .07       0  2787.6     .12       0  3067.5    .033       0
  3073.5     .05       0  3309.1     .12       0  3642.5     .07       0
  4922.1     .05       0  5111.7     .07       0  5865.6     .12       0
  6266.8     .07       0  7593.7     .12       0  8924.7     .12       0
  9065.3     .05       0  9255.3     .16       0
#XS Ineff= 1 ,-1
 2753.41 3294.32  236.45
Permanent Ineff=
       F
Bank Sta=4438.3,5209.9
XS Rating Curve= 0 ,0
Exp/Cntr=0.3,0.1

Chan Stop Cuts=-1
Use User Specified Reach Order=0
Composite Channel Slope=5