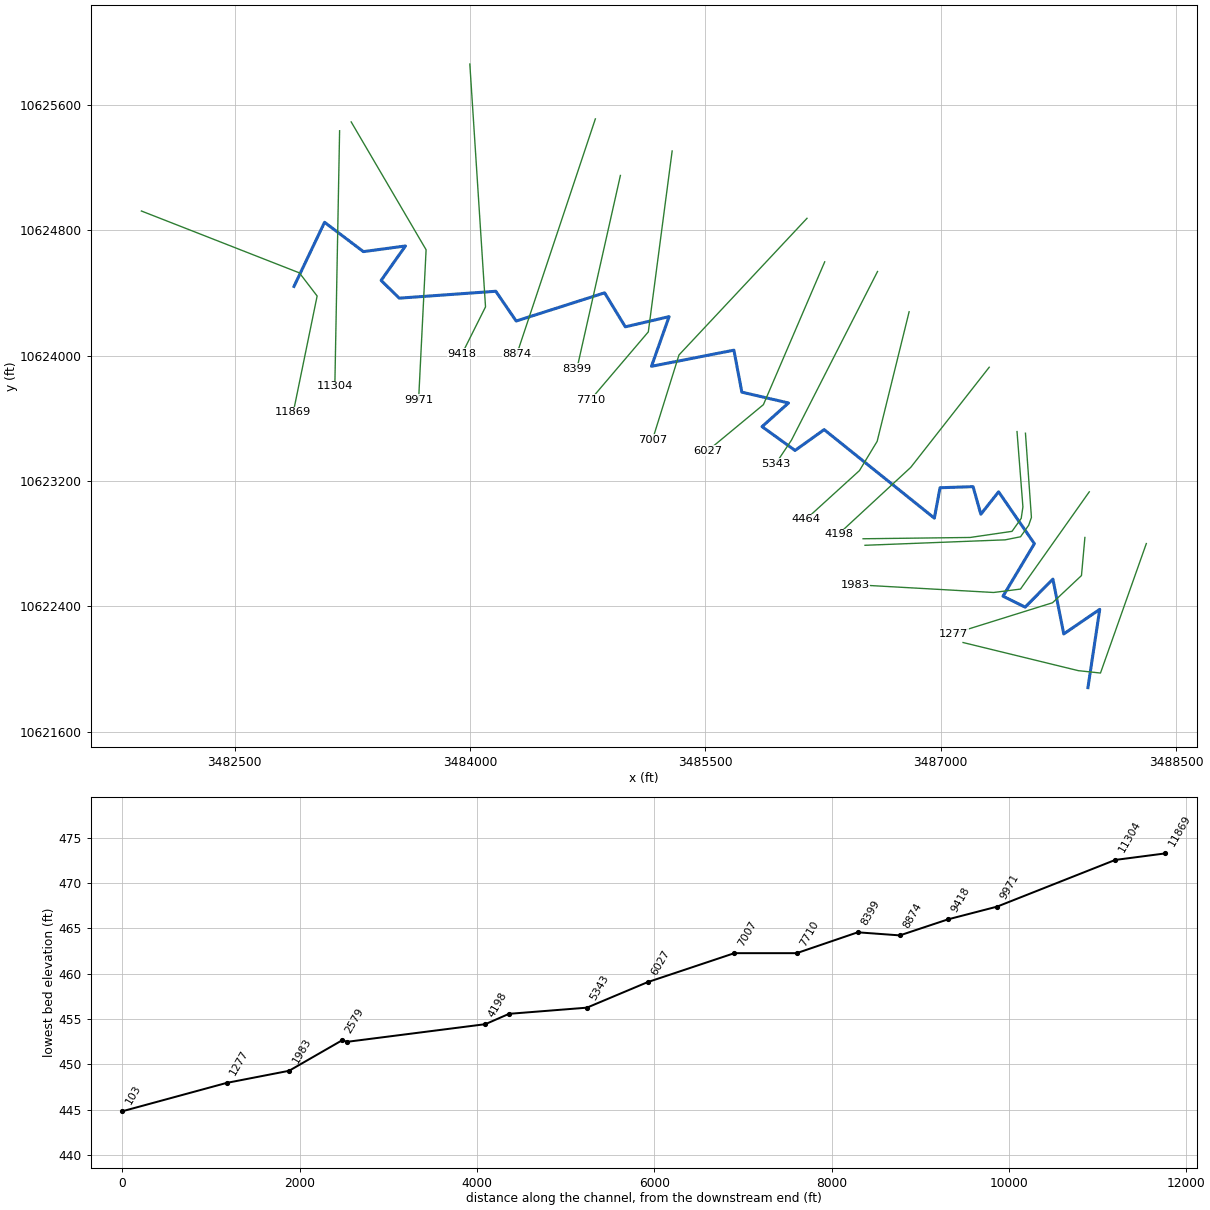
--- UNT002 IN CCTC.prj (project) ---

Proj Title=UNT002 IN CCTC Base Level Engineering
Current Plan=p01
Default Exp/Contr=0.3,0.1
English Units
Geom File=g01
Flow File=f01
Plan File=p01
BEGIN DESCRIPTION:
UNT002 IN CCTC
END DESCRIPTION:

--- UNT002 IN CCTC.p01 (plan) ---

Plan Title=Multiple Run
Short Identifier=Multiple
Geom File=g01
Flow File=f01
Subcritical Flow
K Sum by GR= 0
Std Step Tol= 0.01
Critical Tol= 0.01
Num of Std Step Trials= 20
Max Error Tol= 0.3
Flow Tol Ratio= 0.001
Split Flow NTrial= 30
Split Flow Tol= 0.02
Split Flow Ratio= 0.02
Log Output Level= 0
Friction Slope Method= 1
Unsteady Friction Slope Method= 2
Unsteady Bridges Friction Slope Method= 1
Parabolic Critical Depth
Global Vel Dist=  1 , 1 , 1
Global Log Level= 0
CheckData=True
Encroach Param= -1, 0, 0, 0
BEGIN DESCRIPTION:
Multiple Run
END DESCRIPTION:

--- UNT002 IN CCTC.f01 (steady flow) ---

Flow Title=Multiple
Number of Profiles=7
Profile Names=10-year,25-year,50-year,1pct_min,100-year,1pct_plu,500-year
River Rch & RM= UNT002 IN CCTC,Reach-1,11869
    2115    2993    3738    3399    4597    6217    6942
Boundary for River Rch & Prof#=UNT002 IN CCTC,Reach-1,1
Up Type=0
Dn Type=3
Dn Slope=0.005
Boundary for River Rch & Prof#=UNT002 IN CCTC,Reach-1,2
Up Type=0
Dn Type=3
Dn Slope=0.005
Boundary for River Rch & Prof#=UNT002 IN CCTC,Reach-1,3
Up Type=0
Dn Type=3
Dn Slope=0.005
Boundary for River Rch & Prof#=UNT002 IN CCTC,Reach-1,4
Up Type=0
Dn Type=3
Dn Slope=0.005
Boundary for River Rch & Prof#=UNT002 IN CCTC,Reach-1,5
Up Type=0
Dn Type=3
Dn Slope=0.005
Boundary for River Rch & Prof#=UNT002 IN CCTC,Reach-1,6
Up Type=0
Dn Type=3
Dn Slope=0.005
Boundary for River Rch & Prof#=UNT002 IN CCTC,Reach-1,7
Up Type=0
Dn Type=3
Dn Slope=0.005

--- UNT002 IN CCTC.g01 (geometry) ---

Geom Title=Existing Conditions

River Reach=UNT002 IN CCTC,Reach-1
Reach XY= 30
      3482879.00     10624441.00      3483073.75     10624850.00
      3483321.50     10624663.00      3483589.25     10624699.00
      3483434.25     10624479.00      3483549.75     10624366.00
      3484165.00     10624410.00      3484295.00     10624220.00
      3484858.50     10624400.00      3484990.50     10624183.00
      3485269.50     10624248.00      3485157.25     10623931.00
      3485682.50     10624034.00      3485733.25     10623766.00
      3486030.50     10623697.00      3485862.00     10623546.00
      3486072.25     10623394.00      3486257.75     10623527.00
      3486960.00     10622962.00      3486996.25     10623156.00
      3487206.75     10623163.00      3487256.25     10622987.00
      3487369.50     10623130.00      3487597.50     10622799.00
      3487397.50     10622464.00      3487538.75     10622394.00
      3487715.50     10622573.00      3487784.75     10622223.00
      3488014.00     10622380.00      3487938.75     10621880.00

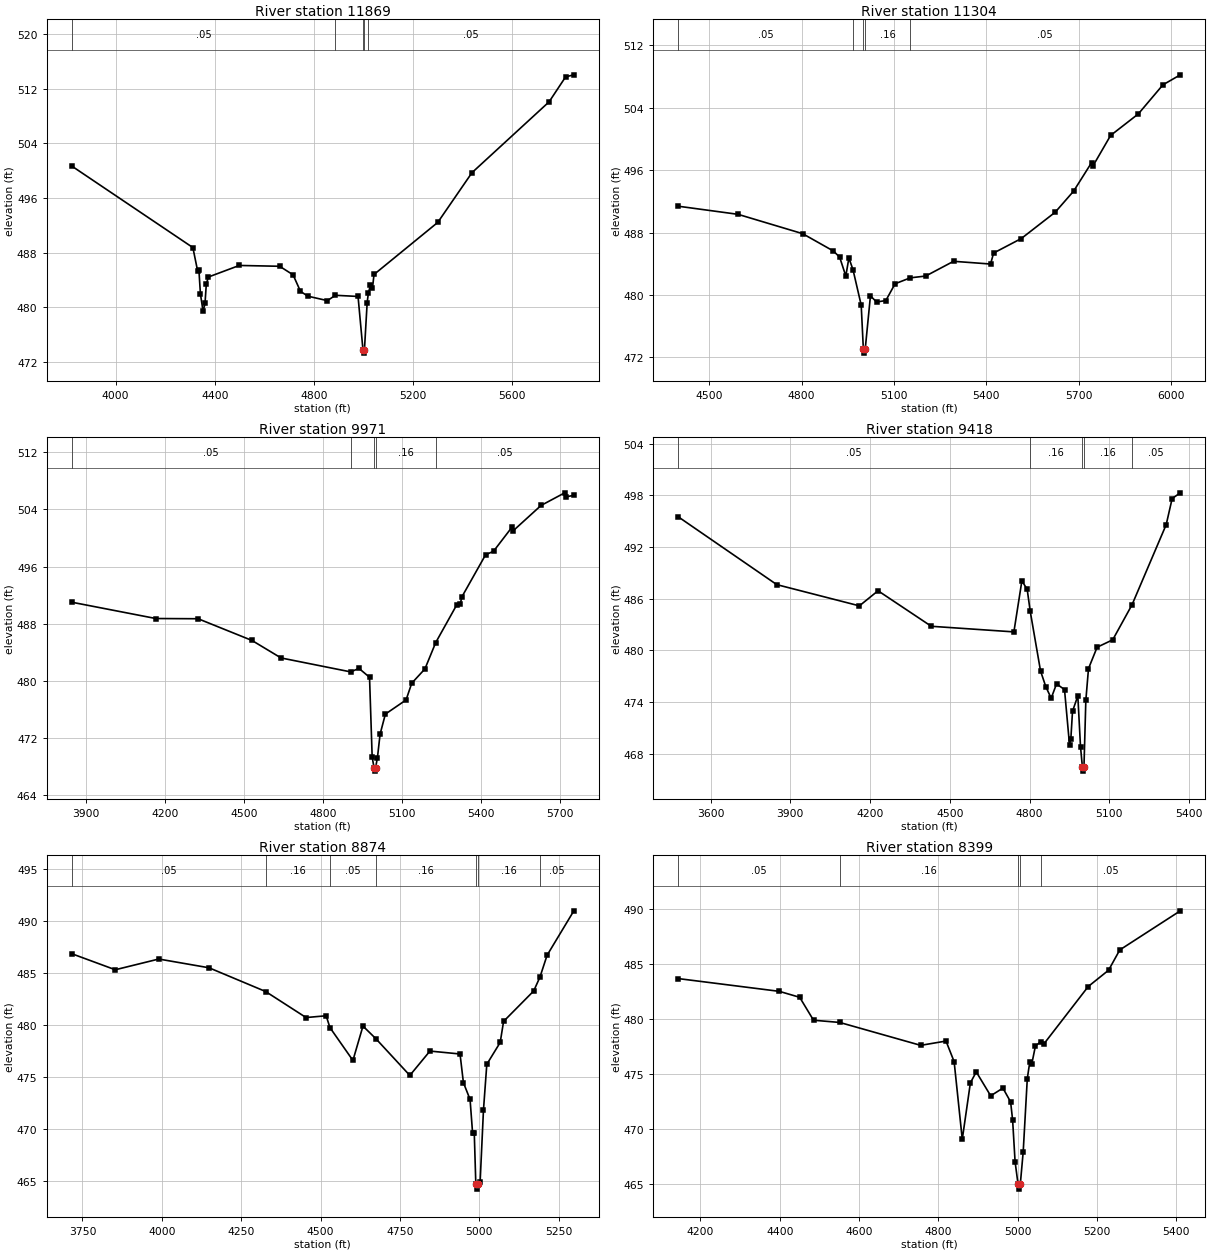
Type RM Length L Ch R = 1,11869,565,565,565
BEGIN DESCRIPTION:
UNT002 IN CCTC 15.0
END DESCRIPTION:
XS GIS Cut Line= 4
      3481906.60     10624922.23      3482913.58     10624527.25
      3483026.43     10624379.68      3482874.56     10623637.71
#Sta/Elev= 30
  3823.0  500.67  4311.4  488.73  4330.5  485.32  4335.8  485.40  4341.8  481.96
  4352.6  479.37  4360.3  480.54  4365.6  483.40  4374.1  484.42  4498.6  486.11
  4661.3  485.99  4715.5  484.74  4745.3  482.32  4775.1  481.61  4853.8  480.96
  4886.4  481.74  4977.5  481.57  4997.3  473.77  5000.0  473.27  5003.3  473.77
  5014.3  480.68  5019.2  482.09  5027.4  483.20  5035.6  482.76  5041.9  484.79
  5299.1  492.42  5437.0  499.70  5748.1  510.08  5814.6  513.73  5847.8  514.03
#Mann=5,-1,0
  3823.0    0.05       0  4886.4    0.16       0  4997.3    0.07       0
  5003.3    0.16       0  5019.2    0.05       0
Bank Sta=4997.3,5003.3
Exp/Cntr=0.3,0.1

Type RM Length L Ch R = 1,11304,1333,1333,1333
BEGIN DESCRIPTION:
UNT002 IN CCTC 14.0
END DESCRIPTION:
XS GIS Cut Line= 2
      3483169.66     10625434.36      3483139.30     10623803.85
#Sta/Elev= 30
  4399.1  491.38  4593.3  490.34  4803.3  487.86  4903.4  485.63  4923.4  484.85
  4943.4  482.43  4953.4  484.75  4966.9  483.22  4993.4  478.70  5000.4  473.05
  5003.1  472.55  5006.4  473.05  5023.4  479.89  5043.4  479.10  5073.4  479.29
  5103.4  481.44  5152.8  482.20  5202.9  482.43  5293.4  484.32  5413.5  483.97
  5423.5  485.38  5513.5  487.24  5623.5  490.61  5683.5  493.32  5741.6  496.96
  5746.6  496.57  5803.5  500.45  5893.5  503.21  5973.5  506.94  6029.9  508.22
#Mann=5,-1,0
  4399.1    0.05       0  4966.9    0.16       0  5000.4    0.07       0
  5006.4    0.16       0  5152.8    0.05       0
Bank Sta=5000.4,5006.4
Exp/Cntr=0.3,0.1

Type RM Length L Ch R = 1,9971,553,553,553
BEGIN DESCRIPTION:
UNT002 IN CCTC 13.0
END DESCRIPTION:
XS GIS Cut Line= 3
      3483243.46     10625490.75      3483720.87     10624674.82
      3483673.13     10623715.64
#Sta/Elev= 30
  3847.0  491.01  4166.2  488.73  4326.5  488.70  4531.2  485.66  4641.3  483.22
  4905.8  481.27  4937.1  481.76  4977.2  480.52  4987.2  469.37  4994.2  467.90
  4997.0  467.40  5000.2  467.90  5007.2  469.28  5017.2  472.55  5037.3  475.37
  5115.9  477.35  5137.4  479.69  5187.5  481.69  5228.3  485.36  5307.6  490.60
  5321.6  490.77  5327.6  491.75  5417.7  497.64  5447.8  498.13  5517.3  501.47
  5522.3  500.99  5628.0  504.53  5718.0  506.30  5723.0  505.74  5752.7  505.95
#Mann=5,-1,0
  3847.0    0.05       0  4905.8    0.16       0  4994.2    0.07       0
  5000.2    0.16       0  5228.3    0.05       0
Bank Sta=4994.2,5000.2
Exp/Cntr=0.3,0.1

Type RM Length L Ch R = 1,9418,544,544,544
BEGIN DESCRIPTION:
UNT002 IN CCTC 12.0
END DESCRIPTION:
XS GIS Cut Line= 3
      3483999.61     10625860.20      3484099.61     10624310.19
      3483949.63     10624010.23
#Sta/Elev= 30
  3478.3  495.50  3849.1  487.63  4159.7  485.17  4229.9  486.92  4430.3  482.80
  4740.9  482.15  4771.0  488.08  4791.0  487.07  4802.3  484.54  4841.1  477.62
  4861.2  475.77  4881.2  474.46  4901.3  476.12  4931.3  475.46  4950.1  469.07
  4955.1  469.72  4961.4  472.94  4981.4  474.73  4991.5  468.83  4998.5  466.50
  5001.2  466.00  5004.5  466.50  5011.5  474.20  5021.5  477.89  5053.9  480.37
  5112.6  481.23  5185.5  485.31  5313.8  494.59  5336.2  497.62  5366.9  498.28
#Mann=5,-1,0
  3478.3    0.05       0  4802.3    0.16       0  4998.5    0.07       0
  5004.5    0.16       0  5185.5    0.05       0
Bank Sta=4998.5,5004.5
Exp/Cntr=0.3,0.1

Type RM Length L Ch R = 1,8874,475,475,475
BEGIN DESCRIPTION:
UNT002 IN CCTC 11.0
END DESCRIPTION:
XS GIS Cut Line= 3
      3484799.60     10625510.16      3484399.61     10624310.19
      3484299.61     10624010.20
#Sta/Elev= 30
  3716.4  486.84  3853.4  485.30  3990.4  486.33  4148.6  485.49  4326.9  483.21
  4454.2  480.71  4517.5  480.88  4529.3  479.75  4601.8  476.59  4633.4  479.89
  4674.3  478.67  4781.0  475.15  4844.3  477.49  4939.1  477.21  4949.7  474.46
  4970.7  472.84  4978.6  469.63  4983.9  469.63  4988.8  464.73  4991.6  464.23
  4994.8  464.73  5002.4  464.95  5012.9  471.83  5023.4  476.22  5065.6  478.32
  5076.2  480.34  5171.0  483.26  5190.8  484.60  5213.2  486.69  5297.5  490.96
#Mann=7,-1,0
  3716.4    0.05       0  4326.9    0.16       0  4529.3    0.05       0
  4674.3    0.16       0  4988.8    0.07       0  4994.8    0.16       0
  5190.8    0.05       0
Bank Sta=4988.8,4994.8
Exp/Cntr=0.3,0.1

Type RM Length L Ch R = 1,8399,689,689,689
BEGIN DESCRIPTION:
UNT002 IN CCTC 10.0
END DESCRIPTION:
XS GIS Cut Line= 2
      3484959.14     10625149.09      3484681.71     10623913.66
#Sta/Elev= 30
  4144.1  483.68  4399.2  482.52  4450.4  481.98  4485.3  479.90  4551.2  479.70
  4755.5  477.62  4819.4  478.01  4839.9  476.14  4860.4  469.09  4880.9  474.22
  4895.7  475.21  4932.1  473.04  4962.9  473.74  4982.3  472.49  4987.4  470.84
  4993.6  467.06  5000.9  465.07  5003.6  464.57  5006.9  465.07  5014.1  467.97
  5024.4  474.60  5030.7  476.12  5035.9  475.97  5044.9  477.56  5058.2  477.95
  5065.4  477.71  5178.1  482.96  5229.4  484.44  5257.6  486.28  5410.3  489.83
#Mann=5,-1,0
  4144.1    0.05       0  4551.2    0.16       0  5000.9    0.07       0
  5006.9    0.16       0  5058.2    0.05       0
Bank Sta=5000.9,5006.9
Exp/Cntr=0.3,0.1

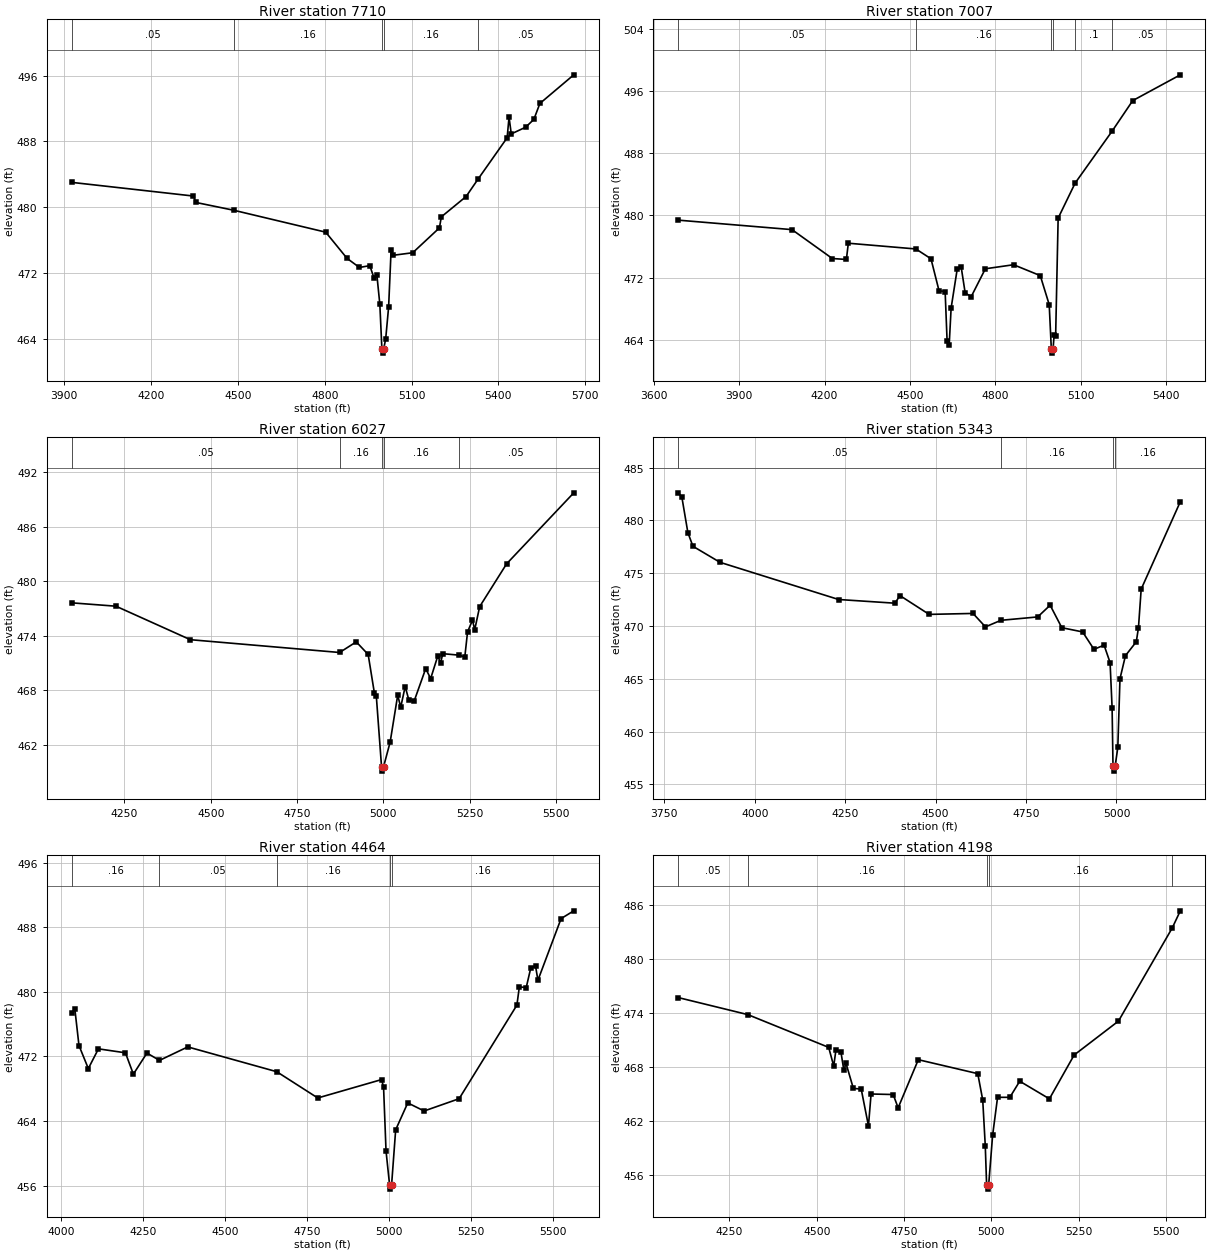
Type RM Length L Ch R = 1,7710,703,703,703
BEGIN DESCRIPTION:
UNT002 IN CCTC 9.0
END DESCRIPTION:
XS GIS Cut Line= 3
      3485288.99     10625305.29      3485137.09     10624150.78
      3484768.16     10623716.75
#Sta/Elev= 30
  3926.3  483.02  4346.6  481.36  4355.1  480.58  4486.2  479.63  4803.5  476.97
  4877.1  473.79  4919.9  472.68  4955.8  472.90  4970.3  471.41  4980.4  471.72
  4990.5  468.19  4997.6  462.77  5000.3  462.27  5003.6  462.77  5010.7  464.00
  5020.8  467.87  5029.4  474.80  5034.5  474.15  5104.1  474.47  5196.3  477.49
  5202.9  478.83  5288.4  481.30  5329.4  483.40  5430.2  488.44  5436.8  490.95
  5444.5  488.91  5493.9  489.72  5522.5  490.67  5543.3  492.61  5660.4  496.09
#Mann=5,-1,0
  3926.3    0.05       0  4486.2    0.16       0  4997.6    0.07       0
  5003.6    0.16       0  5329.4    0.05       0
Bank Sta=4997.6,5003.6
Exp/Cntr=0.3,0.1

Type RM Length L Ch R = 1,7007,980,980,980
BEGIN DESCRIPTION:
UNT002 IN CCTC 8.0
END DESCRIPTION:
XS GIS Cut Line= 3
      3486148.34     10624875.58      3485332.40     10624003.21
      3485163.13     10623460.69
#Sta/Elev= 30
  3686.4  479.39  4085.6  478.17  4227.2  474.45  4276.6  474.33  4283.4  476.42
  4520.7  475.68  4573.6  474.42  4601.9  470.31  4623.4  470.18  4630.2  463.89
  4637.6  463.35  4644.4  468.08  4665.9  473.12  4679.6  473.38  4693.8  470.00
  4715.2  469.56  4764.6  473.13  4863.7  473.65  4957.4  472.25  4988.8  468.52
  4996.3  462.77  4999.0  462.27  5002.3  462.77  5006.1  464.61  5011.4  464.49
  5020.2  479.65  5080.0  484.17  5209.7  490.85  5282.1  494.78  5449.2  498.10
#Mann=6,-1,0
  3686.4    0.05       0  4520.7    0.16       0  4996.3    0.07       0
  5002.3    0.16       0  5080.0     0.1       0  5209.7    0.05       0
Bank Sta=4996.3,5002.3
Exp/Cntr=0.3,0.1

Type RM Length L Ch R = 1,6027,684,684,684
BEGIN DESCRIPTION:
UNT002 IN CCTC 7.0
END DESCRIPTION:
XS GIS Cut Line= 3
      3486261.23     10624597.85      3485870.59     10623686.37
      3485514.70     10623391.24
#Sta/Elev= 30
  4097.5  477.61  4225.5  477.24  4441.0  473.55  4873.3  472.14  4921.5  473.31
  4956.0  471.92  4974.1  467.65  4979.5  467.38  4994.7  459.57  4997.4  459.07
  5000.7  459.57  5019.7  462.28  5041.5  467.43  5050.3  466.12  5063.2  468.39
  5073.8  466.91  5089.2  466.79  5122.6  470.36  5137.0  469.27  5157.8  471.77
  5165.6  470.96  5172.1  472.01  5218.2  471.85  5235.9  471.65  5243.8  474.40
  5258.1  475.70  5264.6  474.65  5278.9  477.19  5357.0  481.91  5551.5  489.73
#Mann=5,-1,0
  4097.5    0.05       0  4873.3    0.16       0  4994.7    0.07       0
  5000.7    0.16       0  5218.2    0.05       0
Bank Sta=4994.7,5000.7
Exp/Cntr=0.3,0.1

Type RM Length L Ch R = 1,5343,879,879,879
BEGIN DESCRIPTION:
UNT002 IN CCTC 6.0
END DESCRIPTION:
XS GIS Cut Line= 3
      3486597.84     10624536.18      3486049.61     10623460.19
      3485949.60     10623310.18
#Sta/Elev= 30
  3788.7  482.61  3798.4  482.23  3815.1  478.85  3829.1  477.55  3904.0  476.03
  4231.9  472.51  4387.6  472.16  4401.5  472.88  4482.2  471.10  4603.5  471.19
  4637.8  469.92  4680.7  470.54  4782.3  470.86  4816.7  471.97  4849.0  469.84
  4906.5  469.44  4937.9  467.79  4965.8  468.19  4982.4  466.54  4988.0  462.28
  4990.5  456.76  4993.3  456.26  4996.5  456.76  5003.8  458.50  5009.8  465.01
  5024.9  467.19  5054.9  468.51  5060.9  469.85  5068.4  473.49  5176.6  481.77
#Mann=4,-1,0
  3788.7    0.05       0  4680.7    0.16       0  4990.5    0.07       0
  4996.5    0.16       0
Bank Sta=4990.5,4996.5
Exp/Cntr=0.3,0.1

Type RM Length L Ch R = 1,4464,266,266,266
BEGIN DESCRIPTION:
UNT002 IN CCTC 5.0
END DESCRIPTION:
XS GIS Cut Line= 4
      3486799.21     10624279.19      3486595.42     10623452.00
      3486482.57     10623265.36      3486140.98     10622954.04
#Sta/Elev= 30
  4032.3  477.39  4041.6  477.90  4054.3  473.35  4082.8  470.50  4113.7  472.94
  4196.1  472.45  4220.3  469.81  4261.8  472.42  4300.0  471.51  4386.3  473.18
  4658.0  470.11  4783.1  466.86  4978.2  469.14  4984.0  468.16  4991.5  460.29
  5002.4  456.08  5005.1  455.58  5008.4  456.08  5020.9  462.92  5057.8  466.25
  5107.8  465.25  5214.6  466.77  5390.9  478.35  5398.4  480.61  5419.3  480.52
  5433.5  482.99  5447.7  483.21  5455.1  481.43  5525.8  489.06  5564.5  490.02
#Mann=5,-1,0
  4032.3    0.16       0  4300.0    0.05       0  4658.0    0.16       0
  5002.4    0.07       0  5008.4    0.16       0
Bank Sta=5002.4,5008.4
Exp/Cntr=0.3,0.1

Type RM Length L Ch R = 1,4198,1556,1556,1556
BEGIN DESCRIPTION:
UNT002 IN CCTC 4.0
END DESCRIPTION:
XS GIS Cut Line= 3
      3487309.67     10623925.09      3486809.64     10623286.17
      3486349.60     10622860.18
#Sta/Elev= 30
  4103.4  475.72  4302.5  473.83  4534.2  470.19  4548.7  468.11  4555.1  469.93
  4569.5  469.64  4577.6  467.66  4584.0  468.40  4604.9  465.63  4627.4  465.56
  4648.2  461.47  4655.7  465.01  4719.1  464.95  4733.2  463.47  4791.0  468.82
  4961.4  467.27  4975.6  464.34  4982.9  459.24  4986.7  454.94  4989.5  454.44
  4992.7  454.94  5003.9  460.41  5018.1  464.64  5053.3  464.64  5081.6  466.43
  5166.6  464.47  5237.5  469.34  5364.5  473.11  5518.6  483.46  5541.7  485.36
#Mann=5,-1,0
  4103.4    0.05       0  4302.5    0.16       0  4986.7    0.07       0
  4992.7    0.16       0  5518.6    0.05       0
Bank Sta=4986.7,4992.7
Exp/Cntr=0.3,0.1

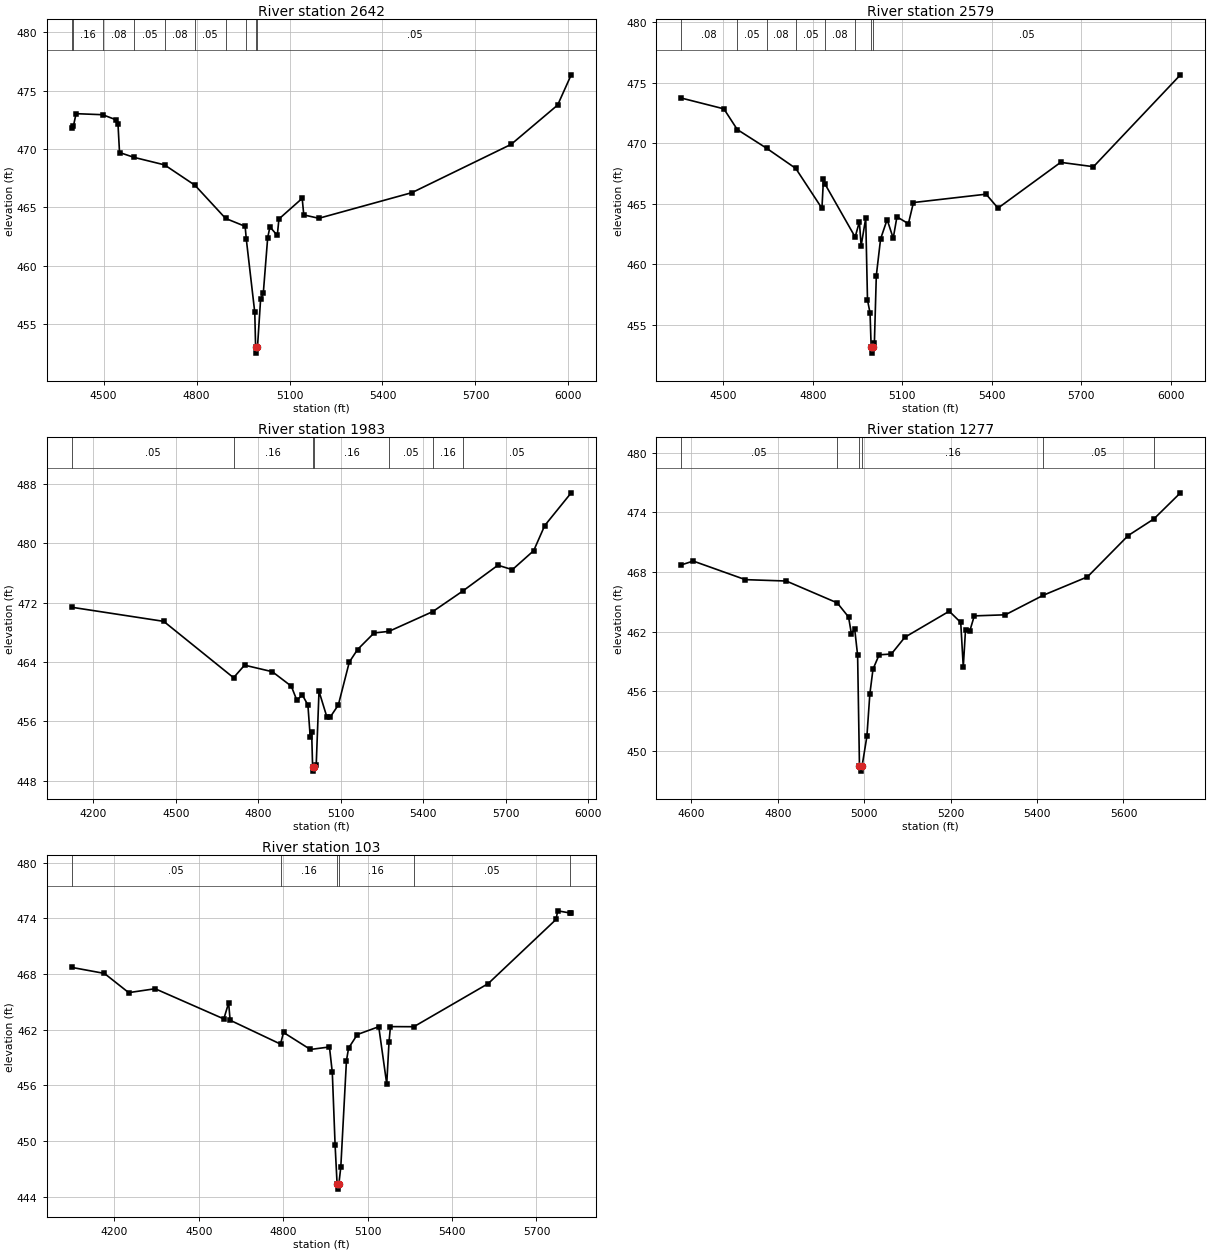
Type RM Length L Ch R = 1,2642,63,63,63
BEGIN DESCRIPTION:
UNT002 IN CCTC 3.0
END DESCRIPTION:
XS GIS Cut Line= 6
      3487486.80     10623514.44      3487524.41     10623034.01
      3487513.56     10622960.23      3487454.97     10622877.76
      3487188.04     10622838.70      3486505.89     10622830.41
#Sta/Elev= 30
  4397.0  471.84  4402.7  471.97  4411.3  473.03  4497.1  472.94  4541.5  472.49
  4546.5  472.16  4551.5  469.70  4598.7  469.28  4696.7  468.64  4795.0  466.89
  4893.7  464.05  4956.8  463.37  4960.6  462.26  4987.9  455.99  4990.6  453.00
  4993.4  452.50  4996.6  453.00  5006.7  457.11  5015.4  457.64  5029.6  462.41
  5036.9  463.32  5060.6  462.59  5065.8  464.00  5140.9  465.77  5146.0  464.35
  5194.6  464.06  5495.1  466.26  5815.2  470.40  5965.2  473.77  6008.9  476.36
#Mann=10,-1,0
  4397.0    0.05       0  4402.7    0.16       0  4497.1    0.08       0
  4598.7    0.05       0  4696.7    0.08       0  4795.0    0.05       0
  4893.7    0.08       0  4960.6    0.05       0  4990.6    0.04       0
  4996.6    0.05       0
Bank Sta=4990.6,4996.6
Exp/Cntr=0.3,0.1

Type RM Length L Ch R = 1,2579,596,596,596
BEGIN DESCRIPTION:
Mapping XS 98bf1397
END DESCRIPTION:
XS GIS Cut Line= 6
      3487540.62     10623504.05      3487578.66     10622966.74
      3487561.30     10622916.82      3487509.22     10622843.04
      3487411.56     10622823.51      3486518.09     10622788.75
#Sta/Elev= 30
  4357.5  473.73  4501.7  472.83  4546.7  471.12  4644.8  469.58  4742.8  467.91
  4830.7  464.61  4835.7  467.00  4840.9  466.62  4942.1  462.24  4956.3  463.50
  4962.2  461.52  4977.6  463.80  4983.5  457.04  4992.1  455.96  4995.8  453.15
  4998.6  452.65  5001.8  453.15  5006.6  453.46  5013.1  459.06  5027.4  462.08
  5049.4  463.68  5069.8  462.14  5082.3  463.91  5120.7  463.34  5137.6  465.09
  5381.3  465.78  5421.3  464.63  5631.5  468.41  5741.6  468.05  6033.3  475.64
#Mann=8,-1,0
  4357.5    0.08       0  4546.7    0.05       0  4644.8    0.08       0
  4742.8    0.05       0  4840.9    0.08       0  4942.1    0.05       0
  4995.8   0.035       0  5001.8    0.05       0
Bank Sta=4995.8,5001.8
Exp/Cntr=0.3,0.1

Type RM Length L Ch R = 1,1983,706,706,706
BEGIN DESCRIPTION:
Mapping XS 079fbe7a
END DESCRIPTION:
XS GIS Cut Line= 4
      3487947.25     10623129.95      3487508.86     10622509.26
      3487337.42     10622487.55      3486453.33     10622537.39
#Sta/Elev= 30
  4120.8  471.37  4455.9  469.47  4710.1  461.88  4750.2  463.57  4851.2  462.69
  4920.3  460.74  4940.4  458.85  4960.6  459.55  4980.7  458.20  4989.2  453.87
  4994.3  454.62  4997.9  449.80  5000.6  449.30  5003.9  449.80  5011.0  450.18
  5021.1  460.05  5049.9  456.58  5061.3  456.55  5091.4  458.20  5131.4  463.99
  5161.5  465.68  5221.6  467.91  5275.5  468.12  5434.9  470.78  5544.2  473.55
  5672.3  477.03  5724.8  476.43  5802.5  478.99  5842.6  482.37  5939.0  486.78
#Mann=7,-1,0
  4120.8    0.05       0  4710.1    0.16       0  4997.9    0.07       0
  5003.9    0.16       0  5275.5    0.05       0  5434.9    0.16       0
  5544.2    0.05       0
Bank Sta=4997.9,5003.9
Exp/Cntr=0.3,0.1

Type RM Length L Ch R = 1,1277,1174,1174,1174
BEGIN DESCRIPTION:
UNT002 IN CCTC 2.0
END DESCRIPTION:
XS GIS Cut Line= 4
      3487919.38     10622838.70      3487897.67     10622595.64
      3487713.21     10622422.03      3487084.18     10622225.35
#Sta/Elev= 30
  4575.5  468.71  4604.1  469.11  4724.6  467.24  4819.5  467.10  4937.4  464.90
  4963.6  463.48  4970.4  461.75  4977.7  462.32  4984.6  459.63  4988.9  448.46
  4991.6  447.96  4994.9  448.46  5006.1  451.46  5012.9  455.71  5020.2  458.22
  5034.4  459.67  5062.7  459.75  5094.0  461.44  5196.7  464.06  5223.3  462.93
  5229.2  458.44  5234.4  462.20  5244.2  462.06  5254.7  463.59  5326.6  463.70
  5414.5  465.67  5516.7  467.52  5611.0  471.68  5670.4  473.35  5731.9  475.98
#Mann=6,-1,0
  4575.5    0.05       0  4937.4    0.16       0  4988.9    0.07       0
  4994.9    0.16       0  5414.5    0.05       0  5670.4    0.16       0
Bank Sta=4988.9,4994.9
Exp/Cntr=0.3,0.1

Type RM Length L Ch R = 1,103,0,0,0
BEGIN DESCRIPTION:
UNT002 IN CCTC 1.0
END DESCRIPTION:
XS GIS Cut Line= 4
      3488310.91     10622799.86      3488018.74     10621973.42
      3487877.68     10621988.61      3487143.05     10622168.18
#Sta/Elev= 30
  4048.6  468.72  4164.9  468.07  4251.3  466.00  4345.2  466.42  4589.2  463.17
  4606.3  464.89  4611.6  463.03  4790.6  460.46  4801.3  461.71  4896.8  459.88
  4964.5  460.15  4974.6  457.41  4984.6  449.55  4991.7  445.34  4994.4  444.84
  4997.7  445.34  5004.8  447.21  5024.9  458.69  5032.5  460.03  5063.6  461.49
  5139.6  462.33  5168.0  456.16  5176.1  460.70  5181.2  462.34  5264.3  462.33
  5528.3  466.97  5769.4  473.88  5775.4  474.81  5820.3  474.57  5823.3  474.56
#Mann=6,-1,0
  4048.6    0.05       0  4790.6    0.16       0  4991.7    0.07       0
  4997.7    0.16       0  5264.3    0.05       0  5820.3    0.16       0
Bank Sta=4991.7,4997.7
Exp/Cntr=0.3,0.1

Chan Stop Cuts=-1