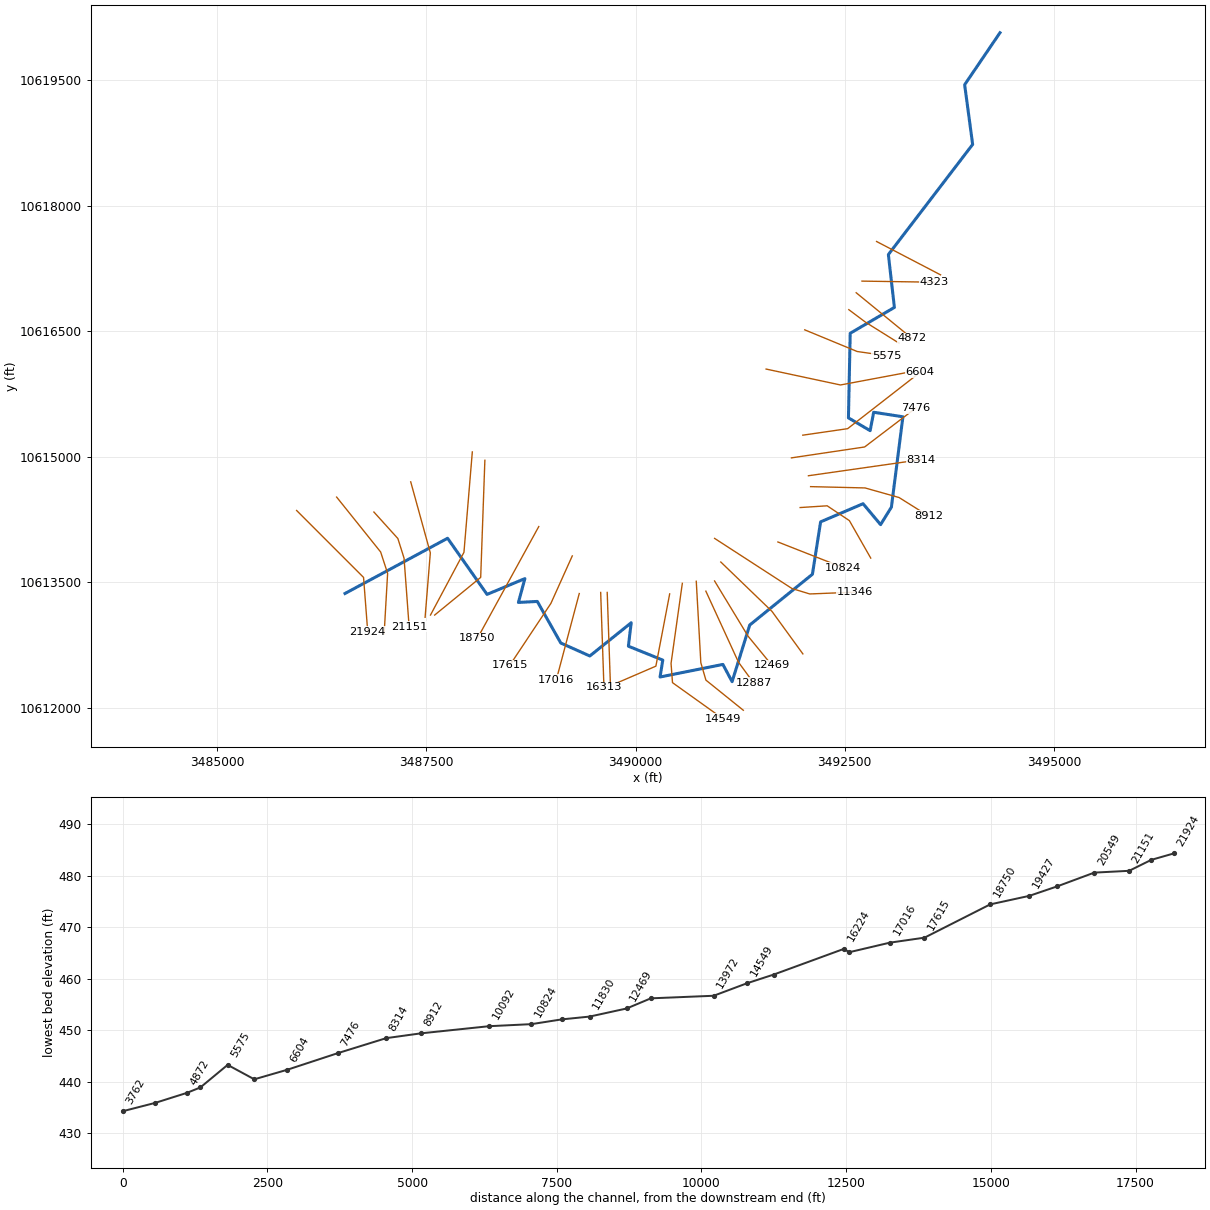
--- UNT003 IN CCTC.prj (project) ---

Proj Title=UNT003 IN CCTC Base Level Engineering
Current Plan=p01
Default Exp/Contr=0.3,0.1
English Units
Geom File=g01
Flow File=f01
Plan File=p01
Y Axis Title=Elevation
X Axis Title(PF)=Main Channel Distance
X Axis Title(XS)=Station
BEGIN DESCRIPTION:
UNT003 IN CCTC
END DESCRIPTION:
DSS Export Rating Curves= 0
DSS Export Rating Curve Sorted= 0
DSS Export Volume Flow Curves= 0
DXF OffsetX= 0
DXF OffsetY= 0
DXF ScaleX= 1
DXF ScaleY= 10

--- UNT003 IN CCTC.p01 (plan) ---

Plan Title=Multiple Run
Short Identifier=Multiple
Geom File=g01
Flow File=f01
Subcritical Flow
K Sum by GR= 0
Std Step Tol= 0.01
Critical Tol= 0.01
Num of Std Step Trials= 20
Max Error Tol= 0.3
Flow Tol Ratio= 0.001
Split Flow NTrial= 30
Split Flow Tol= 0.02
Split Flow Ratio= 0.02
Log Output Level= 0
Friction Slope Method= 1
Unsteady Friction Slope Method= 2
Unsteady Bridges Friction Slope Method= 1
Parabolic Critical Depth
Global Vel Dist=  1 , 1 , 1
Global Log Level= 0
CheckData=True
Encroach Param= -1, 0, 0, 0
BEGIN DESCRIPTION:
Multiple Run
END DESCRIPTION:

--- UNT003 IN CCTC.f01 (steady flow) ---

Flow Title=Multiple
Number of Profiles=7
Profile Names=10-year,25-year,50-year,1pct_min,100-year,1pct_plu,500-year
River Rch & RM= UNT003 IN CCTC,Reach-1,21924
    1429    1969    2413    2157    2917    3945    4252
River Rch & RM= UNT003 IN CCTC,Reach-1,14549
    2498    3523    4386    3972    5371    7264    8041
Boundary for River Rch & Prof#=UNT003 IN CCTC,Reach-1,1
Up Type=0
Dn Type=3
Dn Slope=0.005
Boundary for River Rch & Prof#=UNT003 IN CCTC,Reach-1,2
Up Type=0
Dn Type=3
Dn Slope=0.005
Boundary for River Rch & Prof#=UNT003 IN CCTC,Reach-1,3
Up Type=0
Dn Type=3
Dn Slope=0.005
Boundary for River Rch & Prof#=UNT003 IN CCTC,Reach-1,4
Up Type=0
Dn Type=3
Dn Slope=0.005
Boundary for River Rch & Prof#=UNT003 IN CCTC,Reach-1,5
Up Type=0
Dn Type=3
Dn Slope=0.005
Boundary for River Rch & Prof#=UNT003 IN CCTC,Reach-1,6
Up Type=0
Dn Type=3
Dn Slope=0.005
Boundary for River Rch & Prof#=UNT003 IN CCTC,Reach-1,7
Up Type=0
Dn Type=3
Dn Slope=0.005

--- UNT003 IN CCTC.g01 (geometry) ---

Geom Title=Existing Conditions

River Reach=UNT003 IN CCTC,Reach-1
Reach XY= 30
      3486528.00     10613368.00      3487754.00     10614028.00
      3488225.75     10613357.00      3488678.00     10613546.00
      3488600.50     10613261.00      3488826.25     10613273.00
      3489107.00     10612776.00      3489454.00     10612621.00
      3489948.50     10613018.00      3489915.00     10612738.00
      3490326.00     10612572.00      3490293.50     10612370.00
      3491044.50     10612520.00      3491154.50     10612314.00
      3491365.25     10612991.00      3492114.50     10613598.00
      3492212.25     10614224.00      3492719.75     10614441.00
      3492929.25     10614191.00      3493058.50     10614400.00
      3493196.00     10615480.00      3492846.50     10615534.00
      3492804.50     10615314.00      3492545.00     10615467.00
      3492566.00     10616478.00      3493094.25     10616787.00
      3493022.25     10617419.00      3494029.50     10618735.00
      3493934.00     10619449.00      3494356.00     10620070.00

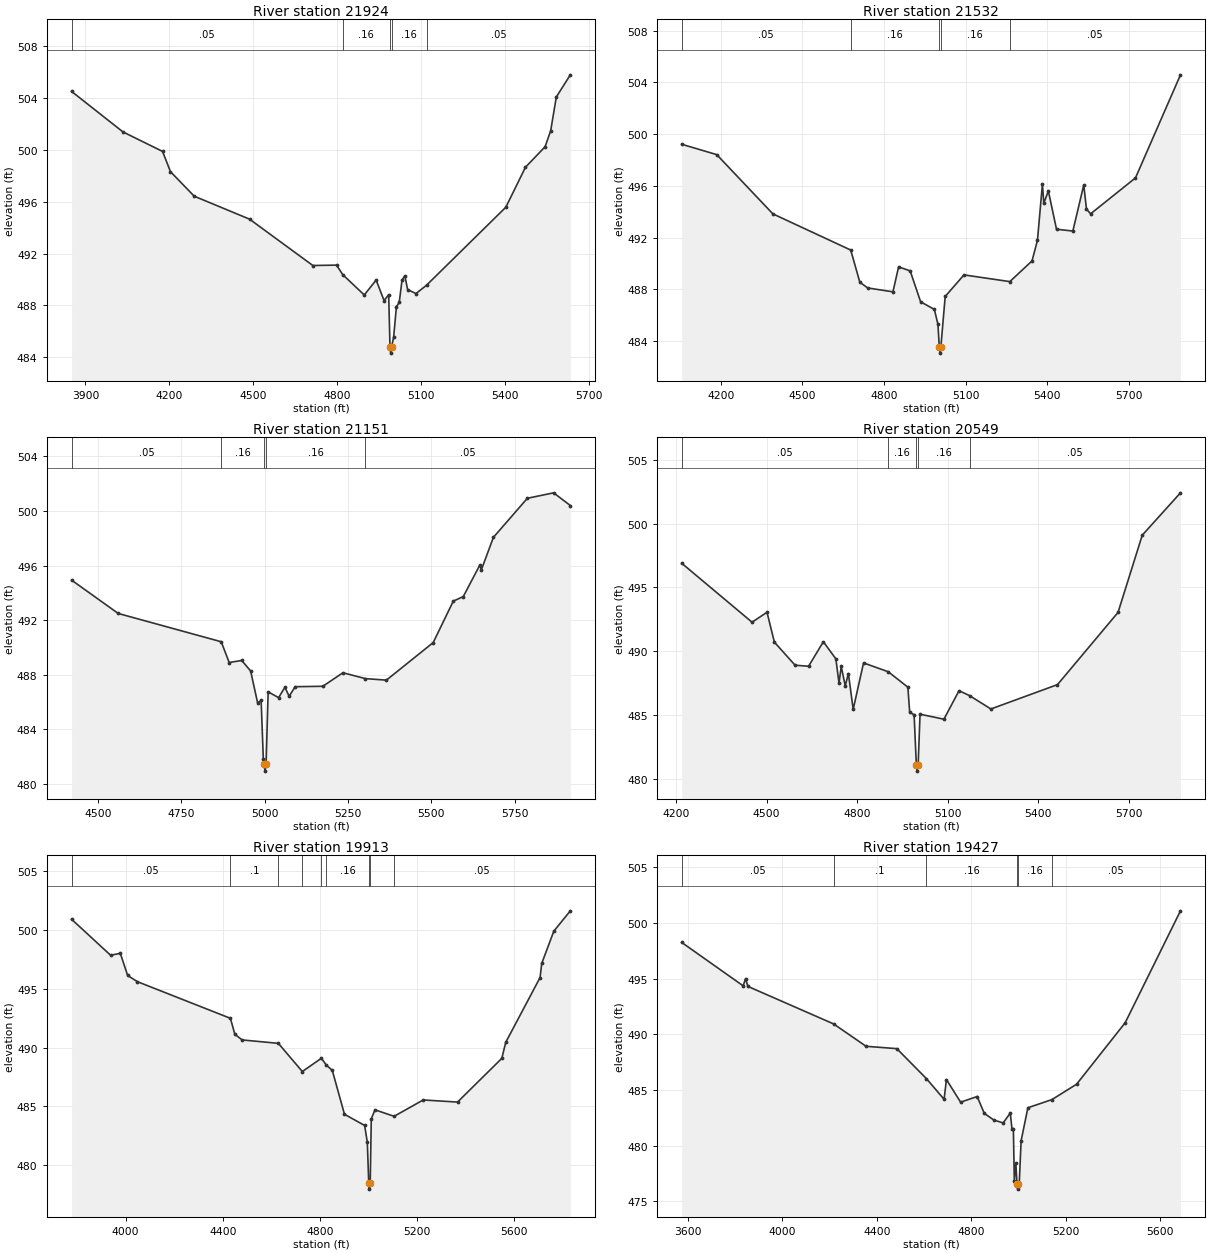
Type RM Length L Ch R = 1,21924,392,392,392
BEGIN DESCRIPTION:
UNT003 IN CCTC 33.0
END DESCRIPTION:
XS GIS Cut Line= 3
      3485949.64     10614360.16      3486749.61     10613560.19
      3486799.61     10612910.14
#Sta/Elev= 30
  3850.5  504.49  4034.3  501.37  4175.7  499.87  4204.0  498.31  4288.9  496.42
  4486.9  494.65  4713.1  491.08  4798.0  491.11  4819.8  490.38  4897.0  488.81
  4939.4  489.96  4967.7  488.38  4984.3  488.83  4988.9  484.83  4991.6  484.33
  4994.9  484.83  5001.9  485.55  5011.9  487.90  5022.0  488.24  5032.0  489.96
  5042.0  490.29  5052.0  489.22  5082.1  488.92  5119.5  489.56  5403.1  495.57
  5473.3  498.65  5543.5  500.23  5563.5  501.46  5583.6  504.06  5633.8  505.77
#Mann=5,-1,0
  3850.5    0.05       0  4819.8    0.16       0  4988.9    0.07       0
  4994.9    0.16       0  5119.5    0.05       0
Bank Sta=4988.9,4994.9
Exp/Cntr=0.3,0.1

Type RM Length L Ch R = 1,21532,381,381,381
BEGIN DESCRIPTION:
UNT003 IN CCTC 32.0
END DESCRIPTION:
XS GIS Cut Line= 4
      3486427.88     10614520.30      3486953.94     10613864.02
      3487037.27     10613608.82      3486995.61     10612884.97
#Sta/Elev= 30
  4056.1  499.22  4184.8  498.42  4391.2  493.84  4677.7  491.04  4711.3  488.55
  4740.1  488.11  4833.0  487.81  4853.8  489.74  4896.4  489.43  4934.8  487.04
  4985.4  486.45  4998.6  485.29  5003.4  483.57  5006.2  483.07  5009.4  483.57
  5025.2  487.45  5094.2  489.12  5263.0  488.60  5344.6  490.20  5364.6  491.79
  5382.9  496.15  5387.9  494.66  5404.7  495.61  5434.7  492.65  5494.8  492.51
  5534.9  496.07  5544.9  494.22  5560.0  493.84  5725.2  496.62  5890.7  504.59
#Mann=5,-1,0
  4056.1    0.05       0  4677.7    0.16       0  5003.4    0.07       0
  5009.4    0.16       0  5263.0    0.05       0
Bank Sta=5003.4,5009.4
Exp/Cntr=0.3,0.1

Type RM Length L Ch R = 1,21151,602,602,602
BEGIN DESCRIPTION:
UNT003 IN CCTC 31.0
END DESCRIPTION:
XS GIS Cut Line= 4
      3486873.40     10614341.68      3487159.83     10614024.87
      3487233.62     10613790.49      3487294.39     10612970.16
#Sta/Elev= 30
  4421.2  494.93  4561.0  492.49  4869.8  490.42  4893.7  488.90  4931.3  489.05
  4958.0  488.28  4979.0  485.94  4989.5  486.12  4996.1  481.81  4998.3  481.45
  5001.1  480.95  5004.3  481.45  5010.5  486.75  5041.9  486.33  5060.8  487.09
  5073.4  486.43  5091.6  487.13  5174.5  487.16  5234.7  488.15  5302.4  487.72
  5365.1  487.61  5505.4  490.36  5565.6  493.39  5595.7  493.73  5644.9  496.02
  5649.9  495.69  5685.9  498.06  5787.7  500.92  5866.4  501.32  5916.6  500.39
#Mann=5,-1,0
  4421.2    0.05       0  4869.8    0.16       0  4998.3    0.07       0
  5004.3    0.16       0  5302.4    0.05       0
Bank Sta=4998.3,5004.3
Exp/Cntr=0.3,0.1

Type RM Length L Ch R = 1,20549,636,636,636
BEGIN DESCRIPTION:
UNT003 IN CCTC 30.0
END DESCRIPTION:
XS GIS Cut Line= 3
      3487313.32     10614702.56      3487547.69     10613853.61
      3487485.29     10613083.94
#Sta/Elev= 30
  4218.6  496.89  4451.7  492.27  4501.2  493.05  4525.6  490.71  4594.3  488.90
  4639.0  488.82  4687.9  490.74  4729.4  489.40  4739.8  487.50  4747.2  488.80
  4760.5  487.28  4770.9  488.25  4786.8  485.44  4821.1  489.08  4902.9  488.39
  4968.0  487.18  4974.1  485.21  4988.7  485.02  4996.1  481.10  4998.9  480.60
  5002.1  481.10  5008.4  485.06  5087.5  484.67  5137.6  486.90  5172.3  486.52
  5243.2  485.47  5463.9  487.38  5664.6  493.04  5744.8  499.09  5871.5  502.41
#Mann=5,-1,0
  4218.6    0.05       0  4902.9    0.16       0  4996.1    0.07       0
  5002.1    0.16       0  5172.3    0.05       0
Bank Sta=4996.1,5002.1
Exp/Cntr=0.3,0.1

Type RM Length L Ch R = 1,19913,486,486,486
BEGIN DESCRIPTION:
UNT003 IN CCTC 29.0
END DESCRIPTION:
XS GIS Cut Line= 3
      3488049.61     10615060.24      3487949.61     10613860.19
      3487549.61     10613110.19
#Sta/Elev= 30
  3777.7  500.92  3938.3  497.86  3978.4  498.02  4008.5  496.14  4048.7  495.61
  4431.8  492.49  4450.1  491.13  4480.2  490.65  4629.3  490.36  4728.0  487.96
  4806.6  489.09  4825.6  488.54  4851.5  488.05  4901.6  484.32  4984.7  483.37
  4995.7  481.93  5001.6  478.45  5004.3  477.95  5007.6  478.45  5012.0  483.93
  5027.2  484.70  5106.1  484.15  5225.9  485.54  5367.2  485.36  5549.6  489.08
  5565.9  490.45  5707.2  495.96  5714.0  497.16  5763.9  499.91  5831.9  501.64
#Mann=9,-1,0
  3777.7    0.05       0  4431.8     0.1       0  4629.3    0.05       0
  4728.0     0.1       0  4806.6    0.05       0  4825.6    0.16       0
  5001.6    0.07       0  5007.6    0.16       0  5106.1    0.05       0
Bank Sta=5001.6,5007.6
Exp/Cntr=0.3,0.1

Type RM Length L Ch R = 1,19427,677,677,677
BEGIN DESCRIPTION:
UNT003 IN CCTC 28.0
END DESCRIPTION:
XS GIS Cut Line= 3
      3488199.61     10614960.16      3488149.61     10613560.19
      3487599.61     10613110.19
#Sta/Elev= 30
  3573.5  498.25  3833.6  494.35  3843.6  495.00  3853.7  494.30  4216.6  490.93
  4354.0  488.92  4484.1  488.71  4609.7  486.01  4684.2  484.16  4694.2  485.93
  4754.2  483.90  4824.3  484.41  4854.3  482.90  4894.3  482.30  4934.3  482.04
  4964.4  482.92  4971.9  481.45  4977.6  481.45  4981.5  476.85  4988.0  478.42
  4992.9  476.59  4995.6  476.09  4998.9  476.59  5002.4  476.60  5010.3  480.43
  5039.0  483.40  5140.4  484.13  5245.0  485.51  5451.0  491.04  5685.0  501.09
#Mann=6,-1,0
  3573.5    0.05       0  4216.6     0.1       0  4609.7    0.16       0
  4992.9    0.07       0  4998.9    0.16       0  5140.4    0.05       0
Bank Sta=4992.9,4998.9
Exp/Cntr=0.3,0.1

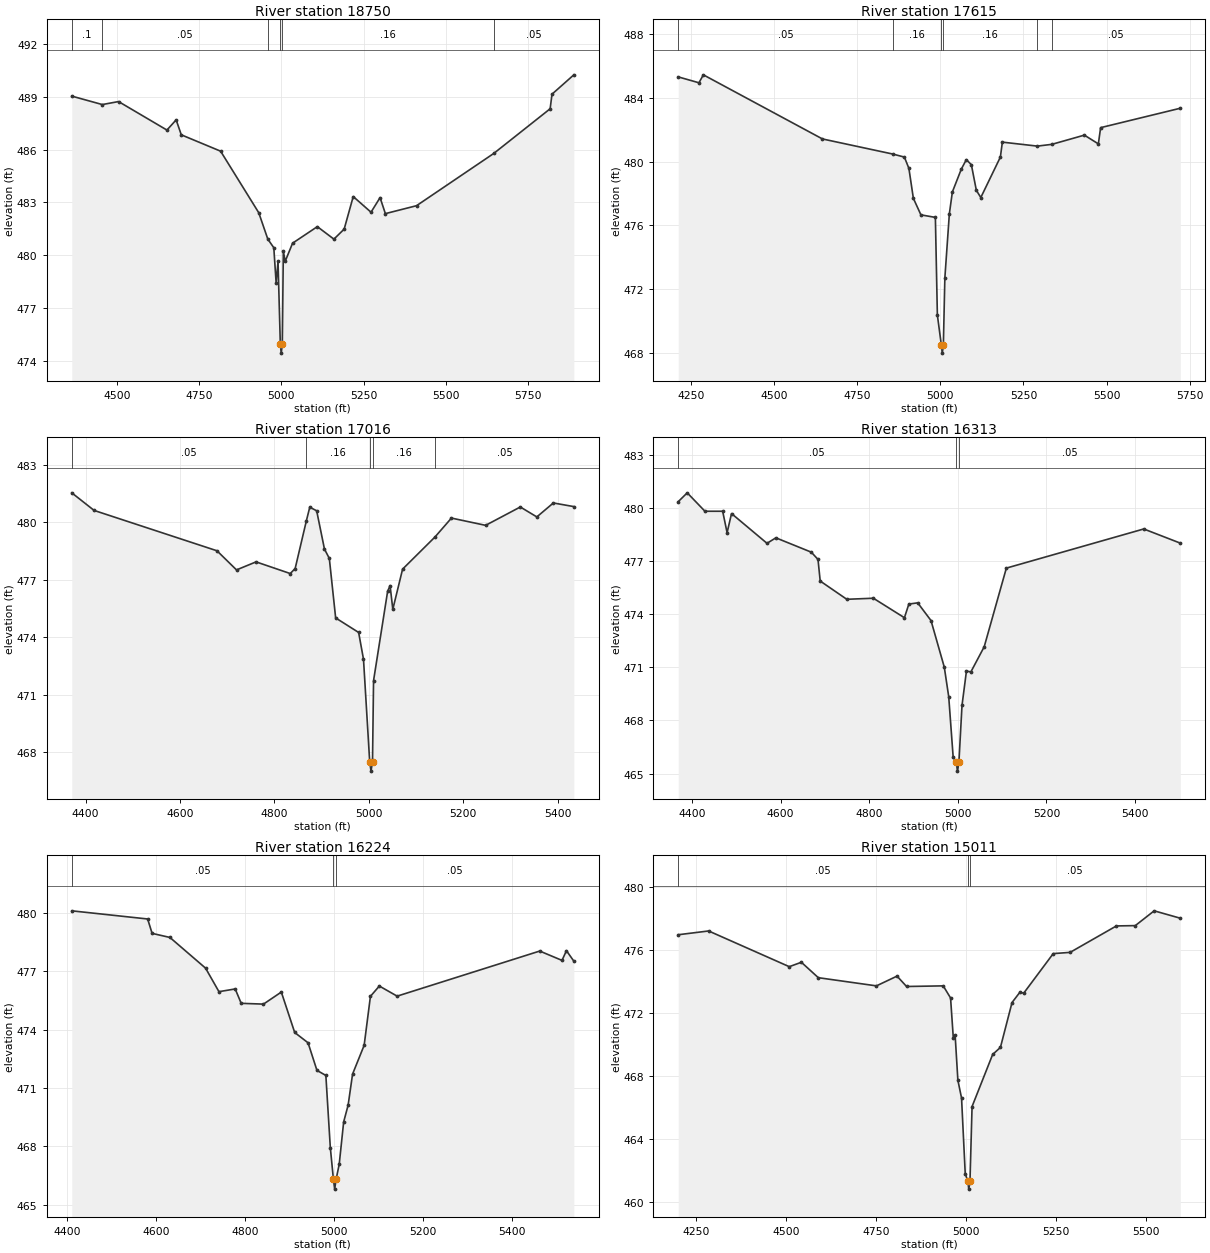
Type RM Length L Ch R = 1,18750,1135,1135,1135
BEGIN DESCRIPTION:
UNT003 IN CCTC 27.0
END DESCRIPTION:
XS GIS Cut Line= 2
      3488843.87     10614168.10      3488110.37     10612831.32
#Sta/Elev= 30
  4363.4  489.04  4456.1  488.56  4505.5  488.73  4652.4  487.11  4680.4  487.69
  4696.0  486.84  4815.4  485.91  4931.3  482.41  4958.8  480.91  4977.0  480.42
  4984.1  478.41  4989.8  479.64  4996.8  474.93  4999.5  474.43  5002.8  474.93
  5005.9  480.22  5011.6  479.65  5034.0  480.68  5109.2  481.62  5159.5  480.91
  5190.7  481.48  5218.2  483.33  5272.2  482.44  5299.7  483.27  5315.8  482.36
  5410.4  482.81  5644.9  485.78  5816.2  488.32  5821.9  489.15  5888.2  490.25
#Mann=6,-1,0
  4363.4     0.1       0  4456.1    0.05       0  4958.8    0.16       0
  4996.8    0.07       0  5002.8    0.16       0  5644.9    0.05       0
Bank Sta=4996.8,5002.8
Exp/Cntr=0.3,0.1

Type RM Length L Ch R = 1,17615,599,599,599
BEGIN DESCRIPTION:
UNT003 IN CCTC 26.0
END DESCRIPTION:
XS GIS Cut Line= 3
      3489244.25     10613817.02      3488988.19     10613248.48
      3488497.75     10612510.65
#Sta/Elev= 30
  4212.0  485.33  4274.3  484.96  4287.5  485.46  4645.6  481.43  4857.3  480.48
  4891.9  480.29  4905.5  479.58  4918.9  477.70  4941.6  476.66  4985.1  476.50
  4991.1  470.36  5003.1  468.47  5005.8  467.97  5009.1  468.47  5013.6  472.69
  5027.1  476.72  5036.2  478.10  5063.2  479.54  5078.2  480.13  5093.3  479.81
  5108.3  478.20  5121.7  477.75  5180.5  480.29  5186.5  481.23  5291.7  480.98
  5335.1  481.09  5433.0  481.67  5475.1  481.12  5481.9  482.14  5721.5  483.36
#Mann=6,-1,0
  4212.0    0.05       0  4857.3    0.16       0  5003.1    0.07       0
  5009.1    0.16       0  5291.7     0.1       0  5335.1    0.05       0
Bank Sta=5003.1,5009.1
Exp/Cntr=0.3,0.1

Type RM Length L Ch R = 1,17016,703,703,703
BEGIN DESCRIPTION:
Mapping XS 6570e3b9
END DESCRIPTION:
XS GIS Cut Line= 2
      3489327.67     10613367.49      3489054.43     10612339.59
#Sta/Elev= 30
  4370.8  481.55  4418.1  480.63  4678.4  478.52  4719.8  477.52  4761.2  477.94
  4833.6  477.33  4844.0  477.59  4867.9  480.10  4875.0  480.80  4889.6  480.61
  4906.1  478.61  4916.4  478.12  4929.8  475.01  4978.5  474.25  4988.8  472.85
  5001.9  467.50  5004.7  467.00  5007.9  467.50  5010.1  471.73  5039.9  476.40
  5045.1  476.70  5050.9  475.46  5071.6  477.56  5140.2  479.24  5175.1  480.23
  5247.5  479.85  5321.0  480.81  5356.0  480.29  5391.0  481.02  5434.4  480.83
#Mann=5,-1,0
  4370.8    0.05       0  4867.9    0.16       0  5001.9    0.07       0
  5007.9    0.16       0  5140.2    0.05       0
Bank Sta=5001.9,5007.9
Exp/Cntr=0.3,0.1

Type RM Length L Ch R = 1,16313,89,89,89
BEGIN DESCRIPTION:
Mapping XS e4a62438
END DESCRIPTION:
XS GIS Cut Line= 2
      3489583.74     10613380.44      3489622.80     10612247.71
#Sta/Elev= 30
  4368.8  480.35  4389.1  480.85  4429.1  479.81  4469.1  479.81  4479.1  478.60
  4489.1  479.68  4569.2  478.00  4589.2  478.31  4669.2  477.50  4684.3  477.09
  4689.3  475.87  4749.3  474.84  4809.3  474.90  4879.4  473.80  4889.4  474.57
  4909.4  474.64  4939.4  473.64  4969.4  471.01  4979.4  469.34  4989.4  465.94
  4996.4  465.64  4999.2  465.14  5002.4  465.64  5009.4  468.85  5019.4  470.79
  5029.4  470.74  5059.5  472.16  5109.5  476.60  5419.7  478.81  5502.2  478.01
#Mann=3,-1,0
  4368.8    0.05       0  4996.4    0.04       0  5002.4    0.05       0
Bank Sta=4996.4,5002.4
Exp/Cntr=0.3,0.1

Type RM Length L Ch R = 1,16224,1213,1213,1213
BEGIN DESCRIPTION:
UNT003 IN CCTC 25.0
END DESCRIPTION:
XS GIS Cut Line= 2
      3489661.86     10613380.46      3489700.87     10612253.64
#Sta/Elev= 30
  4411.1  480.12  4581.5  479.70  4591.5  478.96  4631.5  478.75  4711.6  477.17
  4741.6  475.96  4778.1  476.10  4791.6  475.36  4841.6  475.32  4881.7  475.94
  4911.7  473.86  4941.7  473.33  4961.7  471.91  4981.7  471.65  4991.7  467.94
  4998.7  466.30  5001.5  465.80  5004.7  466.30  5011.7  467.08  5021.7  469.26
  5031.7  470.12  5041.7  471.72  5067.7  473.20  5081.8  475.72  5101.8  476.25
  5141.8  475.73  5462.0  478.05  5512.0  477.57  5522.0  478.07  5538.6  477.53
#Mann=3,-1,0
  4411.1    0.05       0  4998.7    0.04       0  5004.7    0.05       0
Bank Sta=4998.7,5004.7
Exp/Cntr=0.3,0.1

Type RM Length L Ch R = 1,15011,462,462,462
BEGIN DESCRIPTION:
UNT003 IN CCTC 24.0
END DESCRIPTION:
XS GIS Cut Line= 3
      3490408.39     10613363.12      3490243.46     10612499.41
      3489770.38     10612295.42
#Sta/Elev= 30
  4200.7  476.98  4285.1  477.22  4509.1  474.95  4542.7  475.23  4589.8  474.25
  4751.2  473.73  4808.4  474.35  4834.9  473.69  4936.7  473.73  4957.1  472.96
  4964.7  470.42  4969.8  470.59  4977.4  467.73  4987.6  466.60  4997.8  461.80
  5005.0  461.31  5007.7  460.81  5011.0  461.31  5016.8  466.06  5074.0  469.37
  5095.6  469.82  5127.8  472.67  5149.5  473.32  5160.4  473.27  5242.2  475.78
  5289.2  475.86  5417.7  477.54  5470.2  477.56  5522.6  478.50  5595.2  478.03
#Mann=3,-1,0
  4200.7    0.05       0  5005.0    0.03       0  5011.0    0.05       0
Bank Sta=5005,5011
Exp/Cntr=0.3,0.1

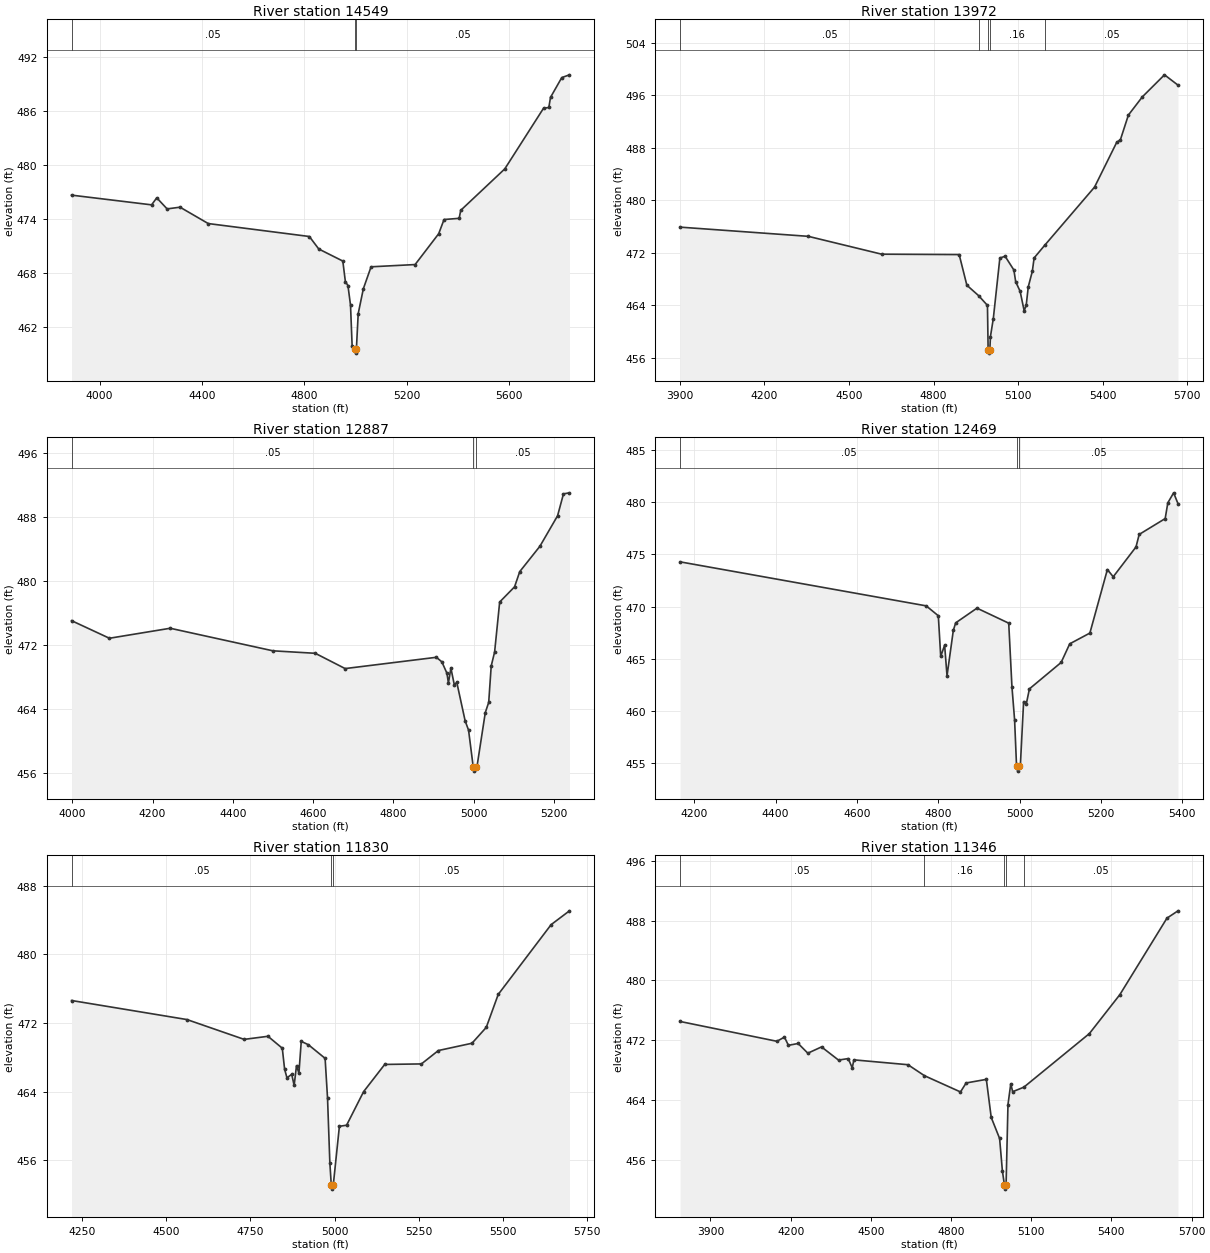
Type RM Length L Ch R = 1,14549,577,577,577
BEGIN DESCRIPTION:
UNT003 IN CCTC 23.0
END DESCRIPTION:
XS GIS Cut Line= 4
      3490559.59     10613489.65      3490424.82     10612532.33
      3490442.18     10612302.30      3491049.84     10611868.26
#Sta/Elev= 30
  3890.8  476.69  4203.3  475.61  4223.5  476.39  4263.9  475.16  4314.4  475.35
  4424.5  473.53  4819.3  472.09  4856.1  470.70  4950.0  469.36  4960.0  467.07
  4970.0  466.64  4980.1  464.45  4986.4  459.91  4997.1  459.62  4999.9  459.12
  5003.1  459.62  5010.1  463.51  5030.2  466.28  5060.3  468.72  5232.3  468.97
  5324.4  472.40  5345.3  473.98  5404.3  474.11  5410.5  475.00  5582.5  479.61
  5733.7  486.35  5754.5  486.44  5761.0  487.56  5804.9  489.76  5835.0  490.07
#Mann=3,-1,0
  3890.8    0.05       0  4997.1   0.035       0  5003.1    0.05       0
Bank Sta=4997.1,5003.1
Exp/Cntr=0.3,0.1

Type RM Length L Ch R = 1,13972,1085,1085,1085
BEGIN DESCRIPTION:
UNT003 IN CCTC 22.0
END DESCRIPTION:
XS GIS Cut Line= 4
      3490726.25     10613514.01      3490780.72     10612541.01
      3490841.49     10612332.68      3491288.56     10611972.41
#Sta/Elev= 30
  3901.2  475.88  4355.7  474.48  4616.1  471.76  4890.9  471.70  4918.2  467.03
  4959.7  465.45  4991.2  463.96  4993.6  457.19  4996.3  456.69  4999.6  457.19
  5001.8  459.21  5012.0  461.96  5035.2  471.17  5053.7  471.45  5084.9  469.35
  5091.4  467.55  5107.1  466.10  5121.5  463.12  5128.8  464.04  5135.9  466.78
  5150.3  469.15  5156.7  471.19  5194.5  473.13  5371.0  481.98  5449.4  488.78
  5462.8  489.21  5491.0  492.95  5540.6  495.73  5619.0  499.08  5666.9  497.51
#Mann=5,-1,0
  3901.2    0.05       0  4959.7    0.16       0  4993.6    0.07       0
  4999.6    0.16       0  5194.5    0.05       0
Bank Sta=4993.6,4999.6
Exp/Cntr=0.3,0.1

Type RM Length L Ch R = 1,12887,418,418,418
BEGIN DESCRIPTION:
UNT003 IN CCTC 21.0
END DESCRIPTION:
XS GIS Cut Line= 3
      3490840.85     10613395.89      3491231.12     10612546.24
      3491410.97     10612299.78
#Sta/Elev= 30
  3998.3  475.00  4092.6  472.80  4244.0  474.05  4499.8  471.23  4605.3  470.92
  4679.7  469.01  4906.9  470.42  4920.6  469.85  4933.3  468.42  4936.9  467.20
  4943.1  469.06  4951.6  466.99  4957.8  467.28  4978.6  462.47  4987.1  461.31
  4998.8  456.69  5001.5  456.19  5004.8  456.69  5008.0  456.73  5028.8  463.51
  5037.3  464.79  5043.5  469.33  5052.0  471.08  5064.6  477.33  5101.7  479.23
  5114.6  481.13  5164.8  484.30  5208.8  488.11  5223.5  490.85  5238.4  490.98
#Mann=3,-1,0
  3998.3    0.05       0  4998.8   0.035       0  5004.8    0.05       0
Bank Sta=4998.8,5004.8
Exp/Cntr=0.3,0.1

Type RM Length L Ch R = 1,12469,639,639,639
BEGIN DESCRIPTION:
UNT003 IN CCTC 20.0
END DESCRIPTION:
XS GIS Cut Line= 3
      3490945.01     10613517.43      3491344.92     10612858.22
      3491632.33     10612508.11
#Sta/Elev= 30
  4165.4  474.29  4770.4  470.07  4800.2  469.12  4806.1  465.22  4815.7  466.30
  4821.6  463.36  4837.1  467.72  4842.9  468.44  4895.2  469.85  4973.3  468.41
  4981.2  462.31  4987.7  459.15  4992.5  454.72  4995.3  454.22  4998.5  454.72
  5002.0  454.85  5009.9  460.89  5016.4  460.65  5024.2  462.11  5102.1  464.64
  5123.3  466.43  5172.8  467.46  5215.8  473.55  5230.2  472.86  5286.2  475.72
  5294.0  476.92  5357.9  478.44  5364.4  479.95  5378.7  480.91  5389.4  479.87
#Mann=3,-1,0
  4165.4    0.05       0  4992.5   0.035       0  4998.5    0.05       0
Bank Sta=4992.5,4998.5
Exp/Cntr=0.3,0.1

Type RM Length L Ch R = 1,11830,484,484,484
BEGIN DESCRIPTION:
UNT003 IN CCTC 19.0
END DESCRIPTION:
XS GIS Cut Line= 3
      3491019.38     10613744.21      3491631.33     10613153.95
      3492000.25     10612646.14
#Sta/Elev= 30
  4219.3  474.63  4561.8  472.41  4731.6  470.10  4802.3  470.46  4844.8  469.07
  4851.7  466.62  4858.7  465.62  4872.8  466.03  4880.0  464.73  4887.0  467.04
  4894.2  466.17  4901.1  469.87  4922.5  469.47  4971.9  467.89  4979.1  463.26
  4986.0  455.70  4990.2  453.15  4993.0  452.65  4996.2  453.15  5014.3  459.97
  5035.7  460.10  5086.2  464.01  5148.8  467.18  5257.8  467.24  5308.1  468.80
  5407.9  469.65  5450.3  471.50  5485.8  475.34  5642.8  483.47  5697.2  485.08
#Mann=3,-1,0
  4219.3    0.05       0  4990.2   0.035       0  4996.2    0.05       0
Bank Sta=4990.2,4996.2
Exp/Cntr=0.3,0.1

Type RM Length L Ch R = 1,11346,522,522,522
BEGIN DESCRIPTION:
UNT003 IN CCTC 18.0
END DESCRIPTION:
XS GIS Cut Line= 4
      3490945.61     10614026.32      3491870.05     10613427.39
      3492082.72     10613362.29      3492620.87     10613383.99
#Sta/Elev= 30
  3786.5  474.51  4148.7  471.86  4176.7  472.42  4191.8  471.32  4228.1  471.57
  4264.3  470.27  4315.5  471.11  4379.1  469.35  4415.4  469.55  4430.5  468.31
  4436.5  469.38  4638.9  468.73  4700.7  467.26  4835.4  465.09  4856.5  466.29
  4932.1  466.77  4950.3  461.69  4981.7  458.87  4992.1  454.56  4999.9  452.60
  5002.7  452.10  5005.9  452.60  5013.0  463.40  5023.5  466.18  5030.5  465.12
  5072.5  465.73  5317.5  472.89  5431.6  478.10  5607.7  488.32  5649.0  489.30
#Mann=5,-1,0
  3786.5    0.05       0  4700.7    0.16       0  4999.9    0.07       0
  5005.9    0.16       0  5072.5    0.05       0
Bank Sta=4999.9,5005.9
Exp/Cntr=0.3,0.1

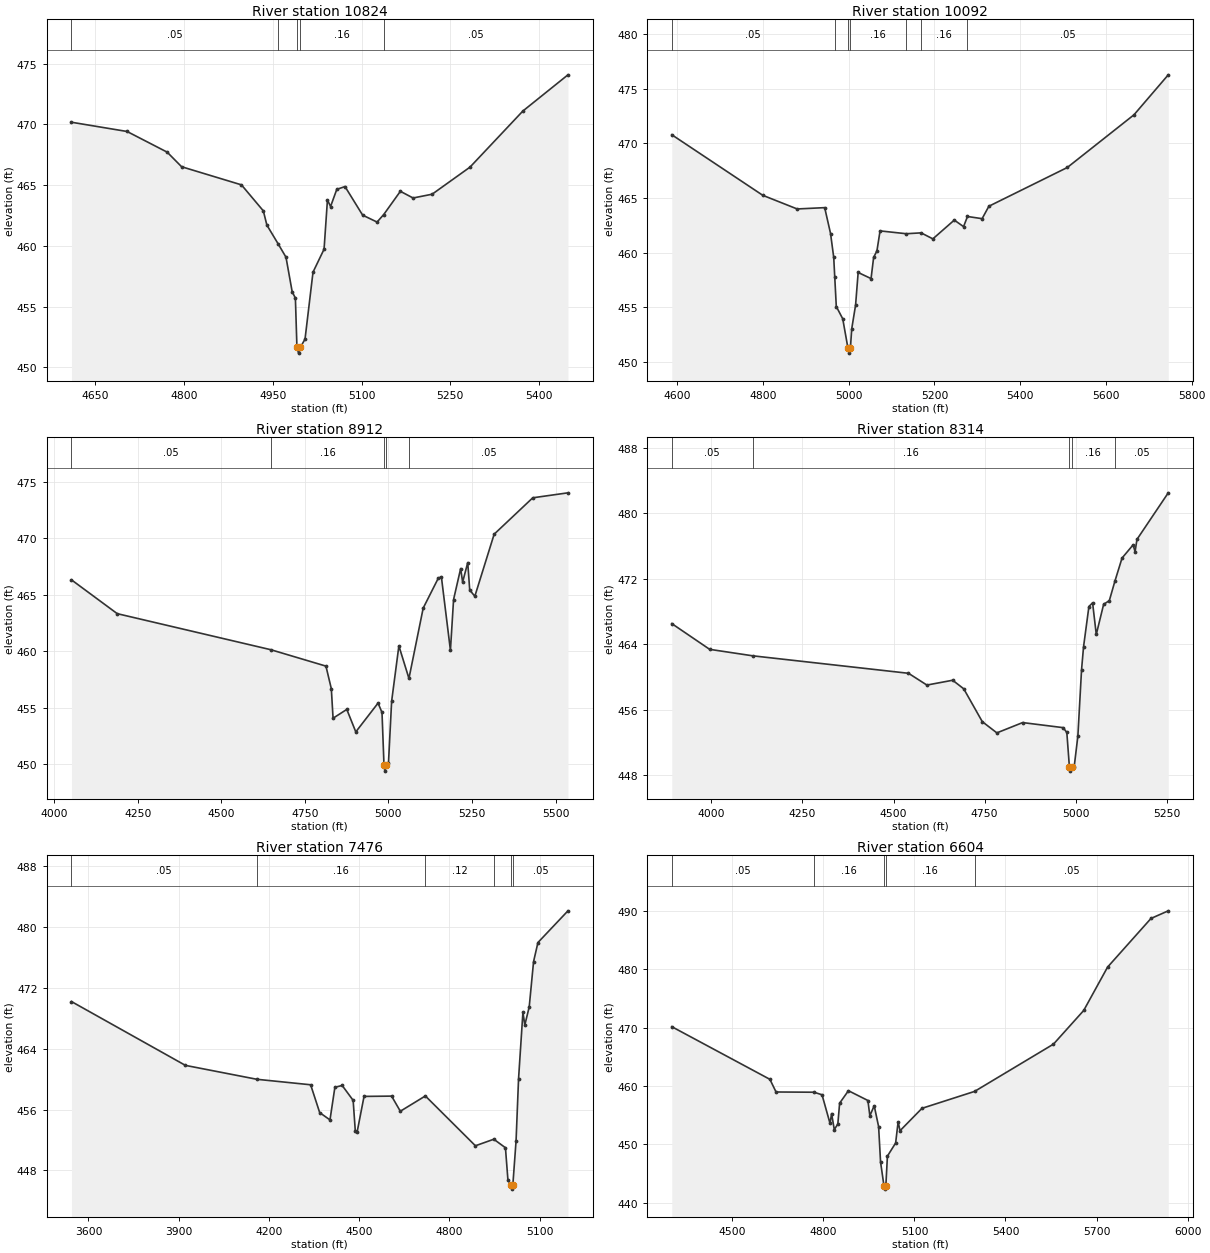
Type RM Length L Ch R = 1,10824,732,732,732
BEGIN DESCRIPTION:
UNT003 IN CCTC 17.0
END DESCRIPTION:
XS GIS Cut Line= 2
      3491702.12     10613983.69      3492483.35     10613676.40
#Sta/Elev= 30
  4609.6  470.17  4703.6  469.41  4771.4  467.71  4795.8  466.51  4897.0  465.02
  4934.0  462.88  4940.0  461.71  4959.0  460.17  4972.3  459.07  4982.8  456.22
  4988.2  455.71  4990.8  451.68  4993.5  451.18  4996.8  451.68  5004.5  452.33
  5018.0  457.84  5036.7  459.73  5042.4  463.78  5047.7  463.24  5058.2  464.65
  5072.1  464.88  5101.9  462.53  5126.3  461.96  5137.6  462.58  5165.7  464.49
  5187.2  463.94  5219.4  464.25  5283.5  466.48  5372.8  471.09  5449.1  474.07
#Mann=5,-1,0
  4609.6    0.05       0  4959.0    0.16       0  4990.8    0.07       0
  4996.8    0.16       0  5137.6    0.05       0
Bank Sta=4990.8,4996.8
Exp/Cntr=0.3,0.1

Type RM Length L Ch R = 1,10092,1180,1180,1180
BEGIN DESCRIPTION:
UNT003 IN CCTC 16.0
END DESCRIPTION:
XS GIS Cut Line= 4
      3491967.74     10614395.15      3492290.64     10614415.99
      3492556.26     10614238.90      3492811.45     10613791.01
#Sta/Elev= 30
  4587.1  470.79  4799.4  465.24  4879.6  463.99  4943.8  464.11  4957.5  461.74
  4964.9  459.55  4967.3  457.75  4970.9  455.05  4985.9  453.93  4997.9  451.28
  5000.7  450.78  5003.9  451.28  5006.9  453.01  5015.9  455.18  5021.9  458.17
  5052.0  457.61  5058.0  459.55  5065.7  460.15  5073.0  461.98  5134.2  461.72
  5168.7  461.80  5196.2  461.25  5246.2  462.97  5267.8  462.37  5277.0  463.30
  5311.1  463.10  5326.9  464.24  5509.9  467.79  5665.5  472.62  5745.4  476.28
#Mann=7,-1,0
  4587.1    0.05       0  4967.3    0.16       0  4997.9    0.07       0
  5003.9    0.16       0  5134.2    0.05       0  5168.7    0.16       0
  5277.0    0.05       0
Bank Sta=4997.9,5003.9
Exp/Cntr=0.3,0.1

Type RM Length L Ch R = 1,8912,598,598,598
BEGIN DESCRIPTION:
UNT003 IN CCTC 15.0
END DESCRIPTION:
XS GIS Cut Line= 4
      3492092.71     10614645.15      3492743.76     10614629.53
      3493150.01     10614514.94      3493498.97     10614296.19
#Sta/Elev= 30
  4052.0  466.31  4188.9  463.32  4648.4  460.13  4813.2  458.68  4829.3  456.68
  4834.5  454.07  4875.6  454.85  4902.5  452.86  4969.1  455.41  4980.9  454.58
  4986.9  449.89  4989.6  449.39  4992.9  449.89  5000.2  450.07  5009.7  455.57
  5031.4  460.47  5061.5  457.59  5104.1  463.81  5149.0  466.44  5158.5  466.59
  5185.6  460.08  5195.0  464.57  5216.2  467.31  5222.1  466.11  5237.4  467.84
  5243.3  465.41  5258.6  464.86  5316.4  470.35  5431.9  473.57  5537.2  474.01
#Mann=5,-1,0
  4052.0    0.05       0  4648.4    0.16       0  4986.9    0.07       0
  4992.9    0.16       0  5061.5    0.05       0
Bank Sta=4986.9,4992.9
Exp/Cntr=0.3,0.1

Type RM Length L Ch R = 1,8314,838,838,838
BEGIN DESCRIPTION:
UNT003 IN CCTC 14.0
END DESCRIPTION:
XS GIS Cut Line= 2
      3492066.71     10614775.36      3493415.12     10614967.99
#Sta/Elev= 30
  3891.6  466.51  3995.5  463.36  4113.4  462.57  4541.0  460.43  4591.5  458.99
  4662.2  459.58  4692.6  458.53  4743.5  454.51  4783.5  453.14  4854.2  454.40
  4965.3  453.78  4975.4  453.19  4982.5  448.96  4985.2  448.46  4988.5  448.96
  4995.6  449.00  5005.7  452.74  5015.8  460.87  5021.3  463.68  5036.0  468.60
  5046.1  469.05  5056.2  465.18  5076.4  468.87  5092.0  469.32  5107.1  471.67
  5126.9  474.53  5157.2  476.14  5162.7  475.31  5167.8  476.81  5253.7  482.51
#Mann=5,-1,0
  3891.6    0.05       0  4113.4    0.16       0  4982.5    0.07       0
  4988.5    0.16       0  5107.1    0.05       0
Bank Sta=4982.5,4988.5
Exp/Cntr=0.3,0.1

Type RM Length L Ch R = 1,7476,872,872,872
BEGIN DESCRIPTION:
UNT003 IN CCTC 13.0
END DESCRIPTION:
XS GIS Cut Line= 3
      3491863.60     10614988.91      3492738.55     10615119.11
      3493347.90     10615582.63
#Sta/Elev= 30
  3543.6  470.20  3922.3  461.81  4160.0  459.98  4338.5  459.26  4368.6  455.60
  4402.8  454.64  4419.1  458.93  4443.3  459.17  4479.8  457.21  4486.9  453.21
  4493.2  453.09  4516.0  457.73  4607.6  457.77  4636.6  455.78  4719.8  457.79
  4886.2  451.24  4947.3  452.10  4986.0  450.98  4994.2  446.78  5004.5  446.04
  5007.2  445.54  5010.5  446.04  5021.3  451.88  5029.6  460.06  5044.1  468.80
  5050.4  467.12  5065.0  469.49  5079.5  475.46  5094.0  477.96  5193.8  482.13
#Mann=6,-1,0
  3543.6    0.05       0  4160.0    0.16       0  4719.8    0.12       0
  4947.3    0.05       0  5004.5   0.035       0  5010.5    0.05       0
Bank Sta=5004.5,5010.5
Exp/Cntr=0.3,0.1

Type RM Length L Ch R = 1,6604,568,568,568
BEGIN DESCRIPTION:
UNT003 IN CCTC 12.0
END DESCRIPTION:
XS GIS Cut Line= 3
      3491999.58     10615260.18      3492535.43     10615337.86
      3493399.64     10616010.21
#Sta/Elev= 30
  4300.1  470.18  4623.5  461.15  4643.7  458.98  4768.8  458.94  4795.3  458.50
  4821.7  453.58  4826.8  455.28  4835.7  452.52  4847.4  453.49  4853.3  457.06
  4882.3  459.20  4946.5  457.52  4952.9  454.90  4967.3  456.62  4981.8  453.04
  4988.2  446.98  4999.6  442.82  5002.4  442.32  5005.6  442.82  5010.8  447.98
  5037.9  450.23  5046.1  453.86  5052.4  452.34  5124.8  456.18  5298.2  459.08
  5558.2  467.19  5657.8  472.96  5736.5  480.40  5879.5  488.74  5936.5  490.05
#Mann=5,-1,0
  4300.1    0.05       0  4768.8    0.16       0  4999.6    0.07       0
  5005.6    0.16       0  5298.2    0.05       0
Bank Sta=4999.6,5005.6
Exp/Cntr=0.3,0.1

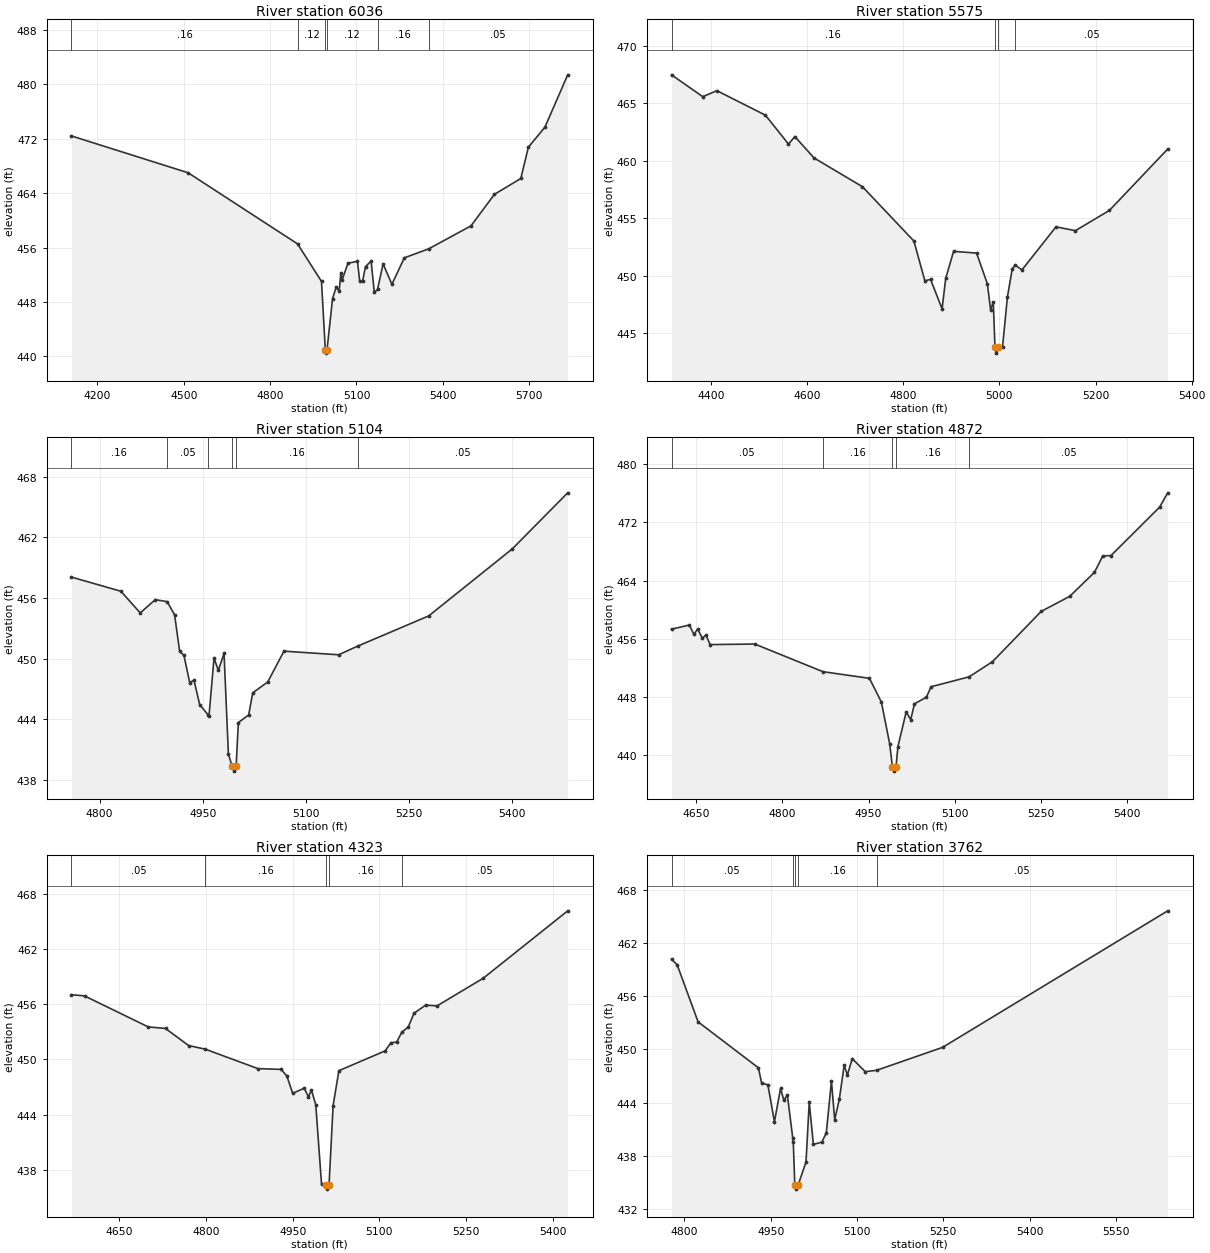
Type RM Length L Ch R = 1,6036,461,461,461
BEGIN DESCRIPTION:
UNT003 IN CCTC 11.0
END DESCRIPTION:
XS GIS Cut Line= 3
      3491560.62     10616050.43      3492449.61     10615860.19
      3493249.65     10616010.20
#Sta/Elev= 30
  4110.3  472.42  4515.4  467.00  4895.3  456.54  4978.5  451.02  4991.7  440.97
  4994.4  440.47  4997.7  440.97  5016.9  448.50  5029.6  450.18  5039.8  449.59
  5045.7  452.26  5050.8  451.30  5070.3  453.69  5103.4  453.98  5111.0  451.11
  5121.2  451.06  5131.3  453.20  5150.8  454.01  5161.9  449.39  5173.0  449.85
  5192.4  453.60  5222.9  450.59  5266.1  454.49  5350.6  455.81  5497.6  459.19
  5579.0  463.83  5670.6  466.16  5696.8  470.76  5754.5  473.72  5833.4  481.41
#Mann=6,-1,0
  4110.3    0.16       0  4895.3    0.12       0  4991.7    0.07       0
  4997.7    0.12       0  5173.0    0.16       0  5350.6    0.05       0
Bank Sta=4991.7,4997.7
Exp/Cntr=0.3,0.1

Type RM Length L Ch R = 1,5575,471,471,471
BEGIN DESCRIPTION:
UNT003 IN CCTC 10.0
END DESCRIPTION:
XS GIS Cut Line= 3
      3492022.46     10616519.17      3492649.61     10616260.19
      3492999.64     10616210.18
#Sta/Elev= 30
  4318.1  467.47  4383.1  465.57  4412.5  466.09  4513.5  463.96  4561.4  461.45
  4574.7  462.10  4614.6  460.24  4715.3  457.74  4822.2  453.02  4845.1  449.56
  4856.9  449.68  4880.9  447.12  4888.4  449.76  4904.8  452.12  4952.6  451.97
  4975.0  449.31  4981.9  447.02  4987.4  447.73  4990.9  443.77  4993.7  443.27
  4996.9  443.77  5006.7  443.84  5016.8  448.16  5026.9  450.62  5033.0  450.92
  5047.1  450.51  5117.8  454.25  5158.2  453.92  5228.9  455.68  5350.2  461.02
#Mann=4,-1,0
  4318.1    0.16       0  4990.9    0.07       0  4996.9    0.16       0
  5033.0    0.05       0
Bank Sta=4990.9,4996.9
Exp/Cntr=0.3,0.1

Type RM Length L Ch R = 1,5104,232,232,232
BEGIN DESCRIPTION:
UNT003 IN CCTC 9.0
END DESCRIPTION:
XS GIS Cut Line= 3
      3492549.58     10616760.21      3492749.61     10616610.19
      3493149.58     10616360.21
#Sta/Elev= 30
  4759.0  458.07  4830.9  456.67  4859.0  454.53  4880.9  455.84  4898.2  455.64
  4909.0  454.34  4916.3  450.74  4922.6  450.33  4930.9  447.65  4937.2  447.87
  4945.5  445.46  4957.5  444.47  4959.0  444.33  4966.3  450.06  4972.6  448.85
  4980.9  450.52  4987.2  440.60  4992.5  439.39  4995.2  438.89  4998.5  439.39
  5001.7  443.69  5016.7  444.44  5022.6  446.63  5044.4  447.70  5068.0  450.75
  5147.6  450.39  5175.0  451.24  5278.5  454.23  5400.0  460.85  5480.7  466.40
#Mann=6,-1,0
  4759.0    0.16       0  4898.2    0.05       0  4957.5    0.16       0
  4992.5    0.07       0  4998.5    0.16       0  5175.0    0.05       0
Bank Sta=4992.5,4998.5
Exp/Cntr=0.3,0.1

Type RM Length L Ch R = 1,4872,549,549,549
BEGIN DESCRIPTION:
UNT003 IN CCTC 8.0
END DESCRIPTION:
XS GIS Cut Line= 2
      3492637.58     10616962.52      3493305.28     10616416.23
#Sta/Elev= 30
  4607.4  457.34  4638.5  457.91  4646.4  456.61  4652.9  457.37  4660.8  456.13
  4667.3  456.50  4674.6  455.22  4752.1  455.30  4870.7  451.50  4951.5  450.59
  4972.3  447.33  4986.7  441.60  4991.6  438.34  4994.3  437.84  4997.6  438.34
  5001.0  441.19  5015.4  445.97  5023.3  444.91  5029.8  447.09  5050.6  447.99
  5058.5  449.43  5124.7  450.79  5165.4  452.87  5250.1  459.78  5299.7  461.85
  5342.7  465.14  5357.1  467.40  5371.4  467.45  5456.1  474.11  5470.1  476.07
#Mann=5,-1,0
  4607.4    0.05       0  4870.7    0.16       0  4991.6    0.07       0
  4997.6    0.16       0  5124.7    0.05       0
Bank Sta=4991.6,4997.6
Exp/Cntr=0.3,0.1

Type RM Length L Ch R = 1,4323,561,561,561
BEGIN DESCRIPTION:
UNT003 IN CCTC 7.0
END DESCRIPTION:
XS GIS Cut Line= 2
      3492706.96     10617101.44      3493565.47     10617088.43
#Sta/Elev= 30
  4567.3  457.03  4589.9  456.90  4700.0  453.53  4730.0  453.36  4770.0  451.50
  4798.7  451.11  4890.0  448.99  4930.0  448.91  4940.0  448.19  4950.0  446.31
  4970.0  446.86  4977.4  445.92  4982.4  446.68  4990.0  445.06  5000.0  436.40
  5007.0  436.39  5009.7  435.89  5013.0  436.39  5020.0  444.97  5030.0  448.77
  5110.0  450.92  5120.0  451.80  5130.0  451.88  5138.9  452.95  5150.0  453.51
  5160.0  455.02  5180.0  455.89  5200.0  455.82  5280.0  458.83  5425.9  466.15
#Mann=5,-1,0
  4567.3    0.05       0  4798.7    0.16       0  5007.0    0.07       0
  5013.0    0.16       0  5138.9    0.05       0
Bank Sta=5007,5013
Exp/Cntr=0.3,0.1

Type RM Length L Ch R = 1,3762,348,348,348
BEGIN DESCRIPTION:
UNT003 IN CCTC 6.0
END DESCRIPTION:
XS GIS Cut Line= 2
      3492880.97     10617575.16      3493645.81     10617176.49
#Sta/Elev= 30
  4777.6  460.14  4787.3  459.55  4823.8  453.10  4928.6  447.93  4934.3  446.20
  4945.1  446.02  4956.5  441.86  4967.2  445.61  4972.8  444.28  4979.0  444.87
  4988.4  439.99  4989.3  439.52  4991.9  434.77  4994.7  434.27  4997.9  434.77
  5011.4  437.32  5017.0  444.06  5024.2  439.30  5039.1  439.57  5046.7  440.62
  5055.6  446.44  5061.2  442.09  5069.3  444.38  5077.7  448.21  5083.3  447.13
  5091.8  448.96  5114.4  447.49  5134.3  447.65  5248.8  450.23  5640.1  465.60
#Mann=5,-1,0
  4777.6    0.05       0  4988.4    0.16       0  4991.9    0.07       0
  4997.9    0.16       0  5134.3    0.05       0
Bank Sta=4991.9,4997.9
Exp/Cntr=0.3,0.1