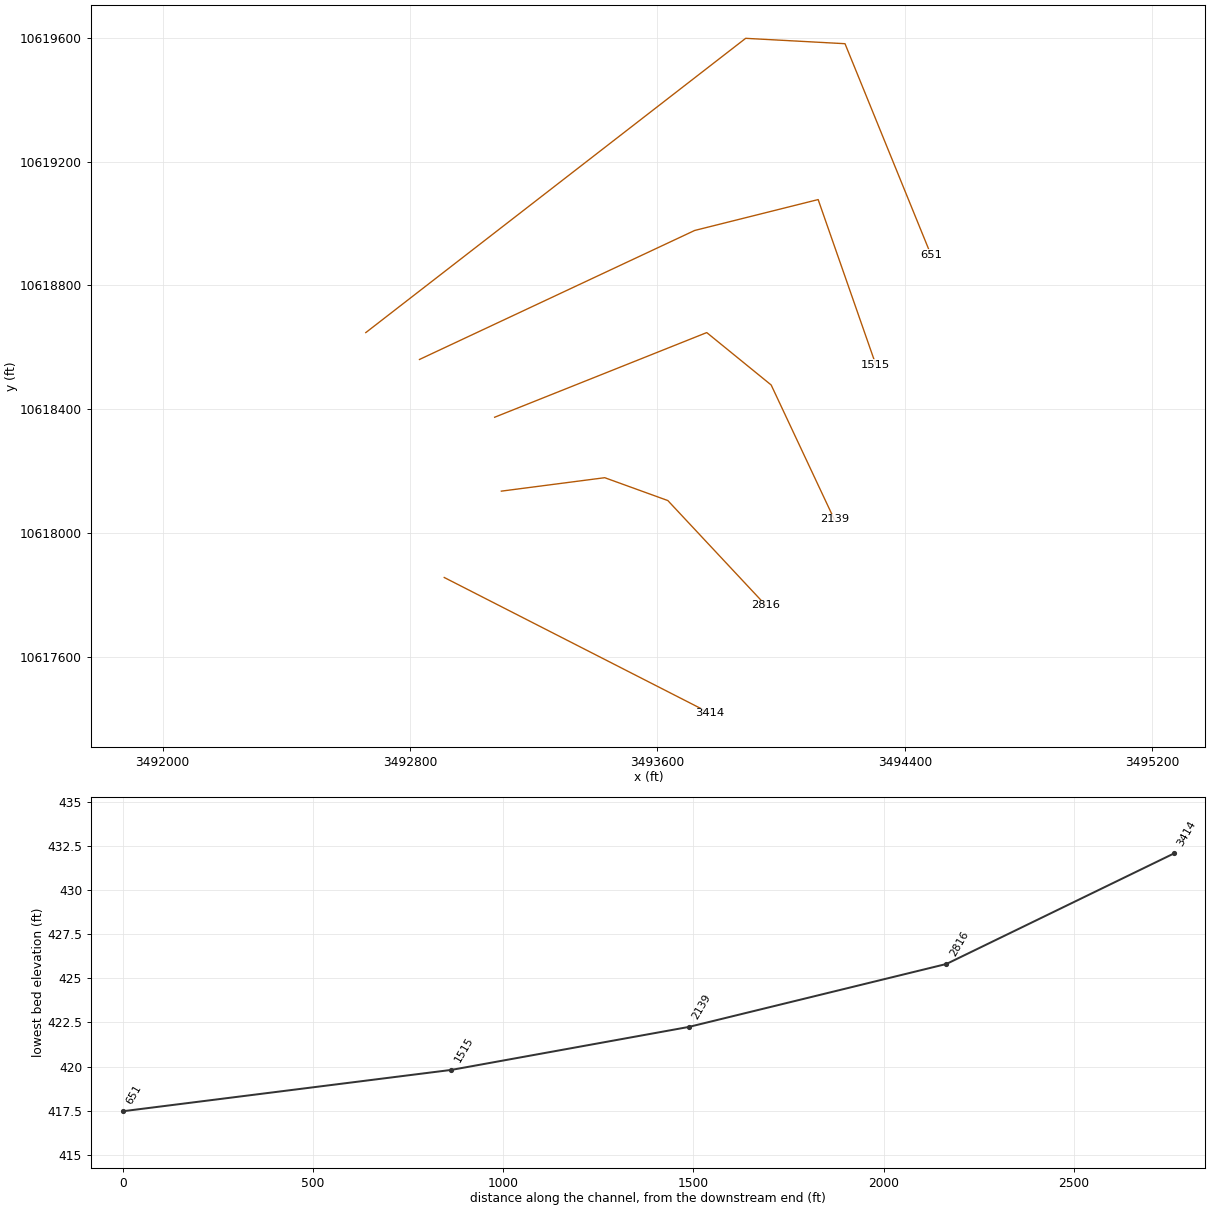
HEC-RAS study UNT003 IN CCTC.prj: UNT003 IN CCTC Base Level Engineering

--- UNT003 IN CCTC.g01 (geometry) --- (continued)

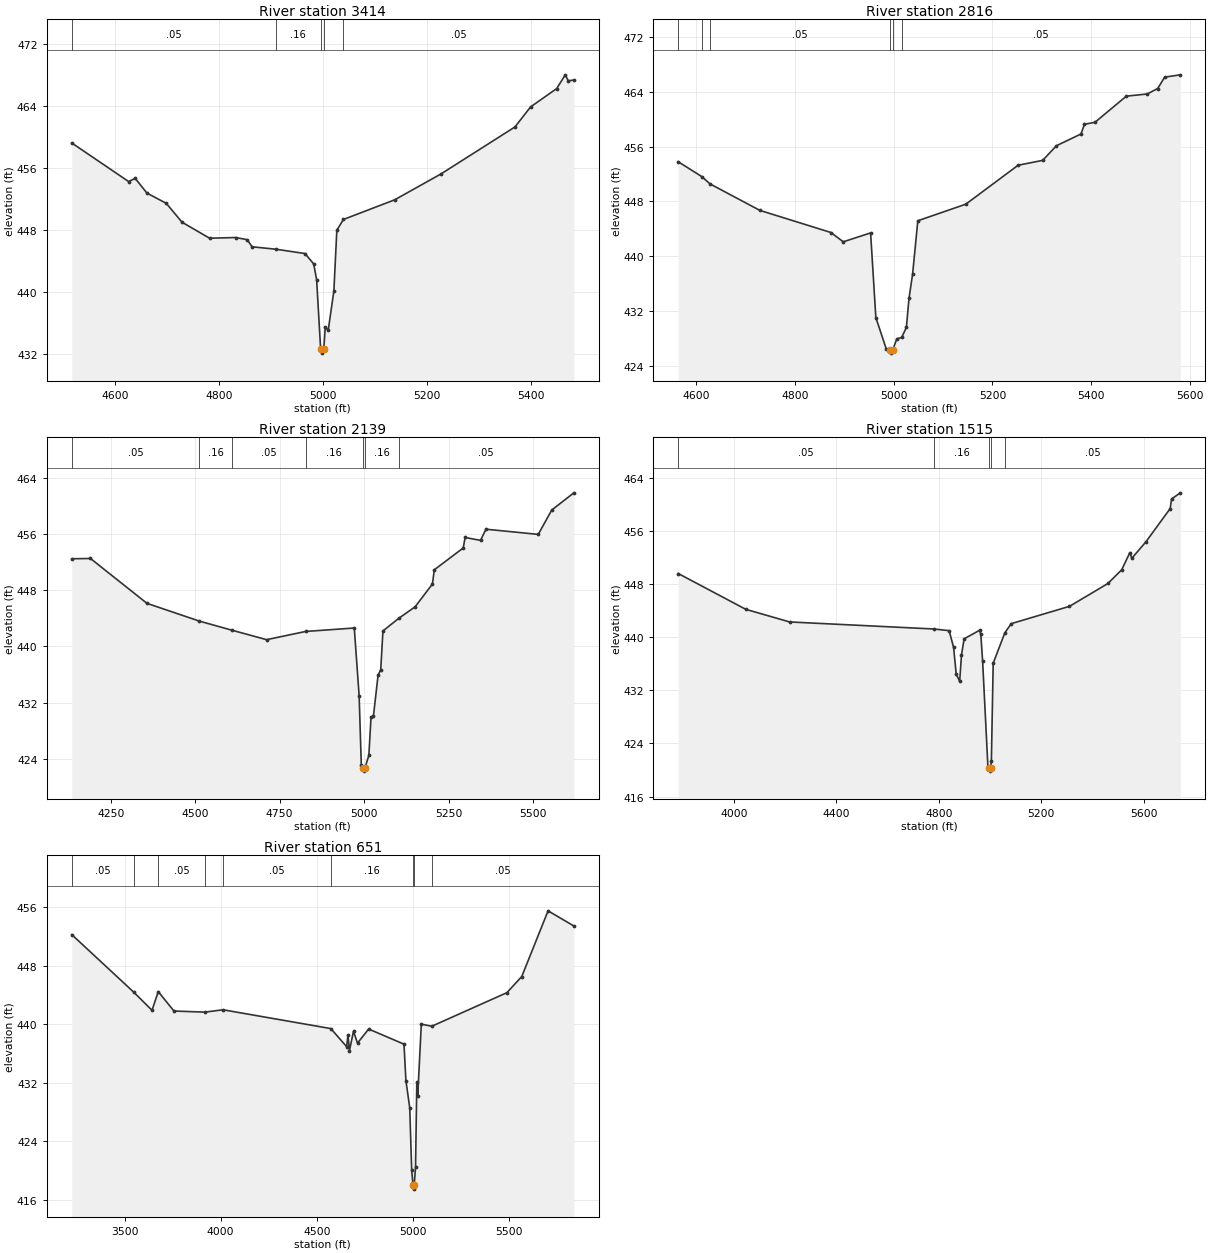
Type RM Length L Ch R = 1,3414,598,598,598
BEGIN DESCRIPTION:
UNT003 IN CCTC 5.0
END DESCRIPTION:
XS GIS Cut Line= 2
      3492910.98     10617856.65      3493770.33     10617418.29
#Sta/Elev= 30
  4516.8  459.20  4626.0  454.22  4638.7  454.63  4661.2  452.73  4698.3  451.41
  4728.6  448.97  4781.6  446.90  4831.7  446.99  4853.9  446.71  4863.3  445.79
  4908.9  445.48  4965.0  444.92  4981.7  443.57  4987.3  441.53  4995.0  432.56
  4997.7  432.06  5001.0  432.56  5003.9  435.42  5009.5  434.99  5020.4  440.07
  5026.1  447.93  5038.7  449.32  5137.3  451.86  5226.2  455.20  5368.4  461.27
  5398.4  463.86  5448.5  466.22  5465.1  468.00  5470.7  467.23  5481.5  467.33
#Mann=5,-1,0
  4516.8    0.05       0  4908.9    0.16       0  4995.0    0.07       0
  5001.0    0.16       0  5038.7    0.05       0
Bank Sta=4995,5001
Exp/Cntr=0.3,0.1

Type RM Length L Ch R = 1,2816,677,677,677
BEGIN DESCRIPTION:
UNT003 IN CCTC 4.0
END DESCRIPTION:
XS GIS Cut Line= 4
      3493095.66     10618135.60      3493429.89     10618179.01
      3493633.88     10618105.22      3493950.69     10617766.71
#Sta/Elev= 30
  4563.2  453.80  4610.9  451.63  4627.6  450.56  4728.5  446.69  4872.7  443.45
  4897.6  442.09  4953.1  443.39  4963.7  431.02  4985.0  426.38  4992.0  426.31
  4994.7  425.81  4998.0  426.31  5006.3  427.90  5016.0  428.10  5025.6  429.56
  5031.0  433.86  5038.2  437.36  5048.8  445.17  5146.0  447.59  5252.1  453.29
  5301.9  454.00  5329.7  456.14  5379.5  457.86  5386.4  459.27  5407.9  459.57
  5471.4  463.39  5513.9  463.71  5534.9  464.51  5549.1  466.17  5580.8  466.51
#Mann=6,-1,0
  4563.2    0.05       0  4610.9    0.16       0  4627.6    0.05       0
  4992.0    0.07       0  4998.0    0.05       0  5016.0    0.05       0
Bank Sta=4992,4998
Exp/Cntr=0.3,0.1

Type RM Length L Ch R = 1,2139,624,624,624
BEGIN DESCRIPTION:
UNT003 IN CCTC 3.0
END DESCRIPTION:
XS GIS Cut Line= 4
      3493073.96     10618374.31      3493759.75     10618647.76
      3493968.08     10618478.49      3494171.90     10618044.82
#Sta/Elev= 30
  4134.9  452.49  4190.3  452.53  4357.5  446.14  4512.7  443.61  4610.1  442.30
  4711.6  440.97  4827.3  442.14  4971.0  442.63  4985.4  432.95  4991.8  423.08
  4996.8  422.75  4999.5  422.25  5002.8  422.75  5014.1  424.48  5020.6  429.96
  5027.6  430.05  5041.4  435.90  5049.3  436.70  5055.8  442.21  5102.3  444.00
  5150.8  445.64  5202.3  448.89  5207.8  450.92  5293.5  454.03  5299.0  455.52
  5344.6  455.11  5360.7  456.70  5515.4  455.96  5555.4  459.43  5620.8  461.88
#Mann=7,-1,0
  4134.9    0.05       0  4512.7    0.16       0  4610.1    0.05       0
  4827.3    0.16       0  4996.8    0.07       0  5002.8    0.16       0
  5102.3    0.05       0
Bank Sta=4996.8,5002.8
Exp/Cntr=0.3,0.1

Type RM Length L Ch R = 1,1515,864,864,864
BEGIN DESCRIPTION:
UNT003 IN CCTC 2.0
END DESCRIPTION:
XS GIS Cut Line= 4
      3492830.92     10618560.95      3493720.69     10618977.62
      3494119.99     10619077.44      3494306.35     10618544.37
#Sta/Elev= 30
  3783.4  449.57  4047.0  444.18  4218.0  442.28  4780.5  441.22  4840.2  440.97
  4857.6  438.47  4867.9  434.43  4881.4  433.34  4888.5  437.32  4898.8  439.74
  4958.8  441.02  4963.9  440.41  4970.9  436.40  4991.6  420.48  4997.0  420.32
  4999.7  419.82  5003.0  420.32  5005.1  421.38  5012.2  436.07  5057.6  440.64
  5082.4  442.02  5309.8  444.63  5459.8  448.07  5513.6  450.14  5545.4  452.72
  5552.9  451.86  5608.9  454.39  5702.8  459.36  5708.1  460.79  5742.2  461.72
#Mann=5,-1,0
  3783.4    0.05       0  4780.5    0.16       0  4997.0    0.07       0
  5003.0    0.16       0  5057.6    0.05       0
Bank Sta=4997,5003
Exp/Cntr=0.3,0.1

Type RM Length L Ch R = 1,651,0,0,0
BEGIN DESCRIPTION:
UNT003 IN CCTC 1.0
END DESCRIPTION:
XS GIS Cut Line= 4
      3492657.33     10618647.76      3493885.62     10619598.28
      3494206.80     10619580.92      3494484.56     10618899.52
#Sta/Elev= 30
  3225.8  452.28  3548.8  444.39  3643.0  441.93  3675.5  444.48  3757.1  441.83
  3918.2  441.68  4012.7  442.00  4572.7  439.43  4655.3  436.95  4661.7  438.58
  4669.8  436.43  4690.7  439.07  4711.5  437.44  4769.4  439.37  4953.2  437.30
  4963.2  432.33  4983.2  428.58  4993.2  420.08  5000.2  417.98  5003.0  417.48
  5006.2  417.98  5013.3  420.49  5019.8  432.07  5024.8  430.26  5043.3  440.04
  5097.6  439.75  5488.4  444.34  5565.7  446.55  5702.4  455.53  5836.4  453.46
#Mann=9,-1,0
  3225.8    0.05       0  3548.8    0.16       0  3675.5    0.05       0
  3918.2    0.16       0  4012.7    0.05       0  4572.7    0.16       0
  5000.2    0.07       0  5006.2    0.16       0  5097.6    0.05       0
Bank Sta=5000.2,5006.2
Exp/Cntr=0.3,0.1

Chan Stop Cuts=-1