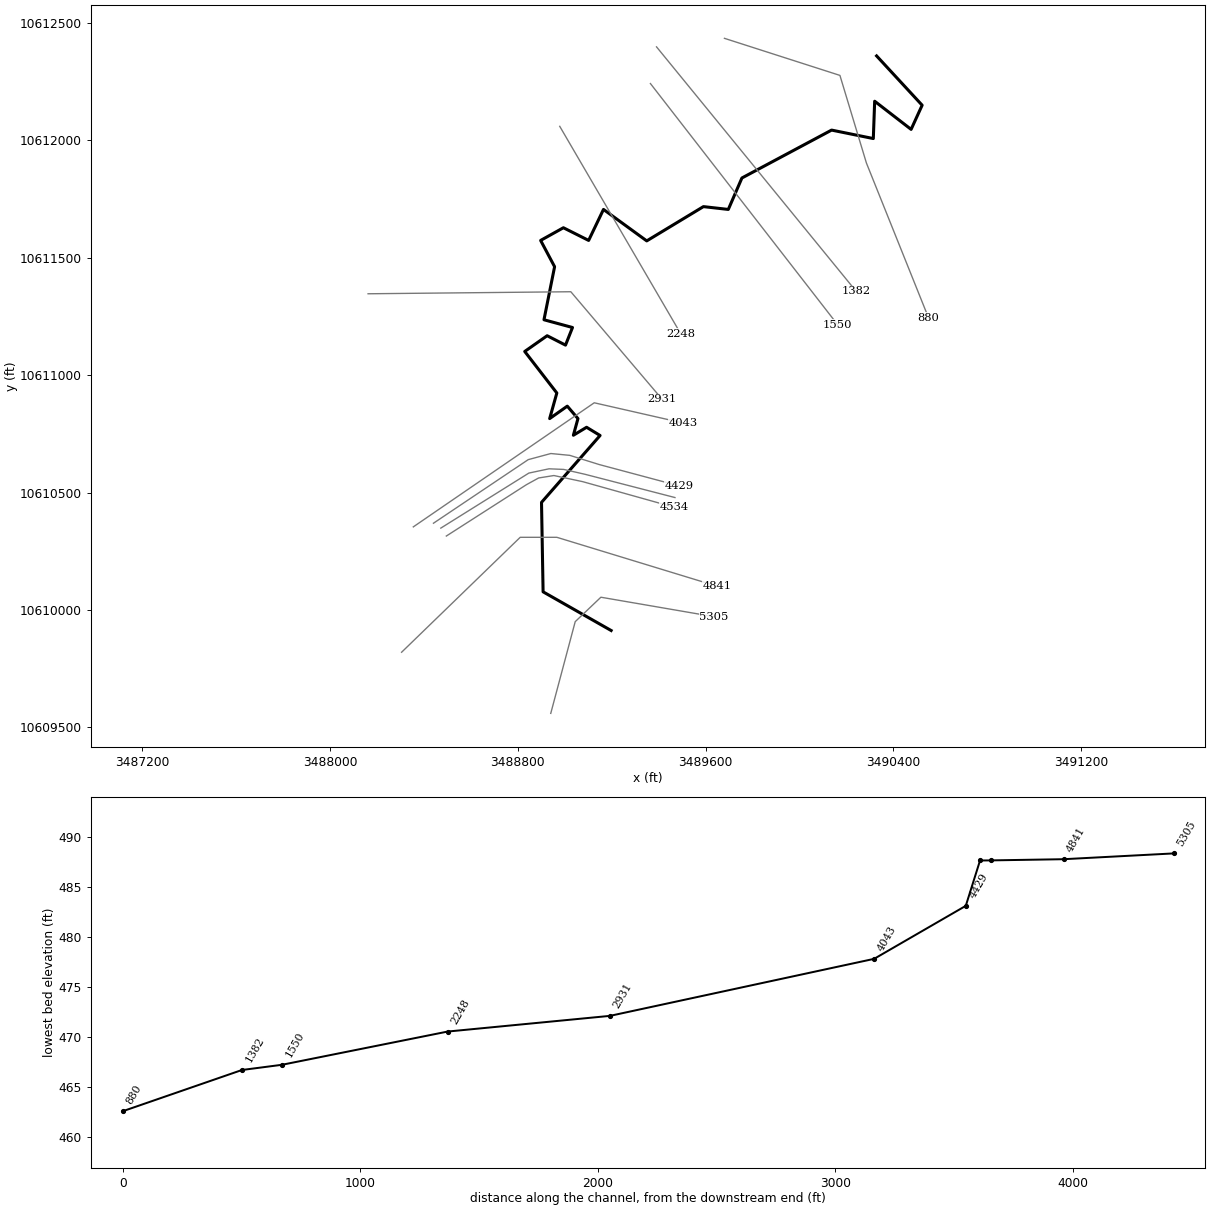
--- UNT004 IN CCTC.prj (project) ---

Proj Title=UNT004 IN CCTC Base Level Engineering
Current Plan=p01
Default Exp/Contr=0.3,0.1
English Units
Geom File=g01
Flow File=f01
Plan File=p01
BEGIN DESCRIPTION:
UNT004 IN CCTC
END DESCRIPTION:

--- UNT004 IN CCTC.p01 (plan) ---

Plan Title=Multiple Run
Short Identifier=Multiple
Geom File=g01
Flow File=f01
Subcritical Flow
K Sum by GR= 0
Std Step Tol= 0.01
Critical Tol= 0.01
Num of Std Step Trials= 20
Max Error Tol= 0.3
Flow Tol Ratio= 0.001
Split Flow NTrial= 30
Split Flow Tol= 0.02
Split Flow Ratio= 0.02
Log Output Level= 0
Friction Slope Method= 1
Unsteady Friction Slope Method= 2
Unsteady Bridges Friction Slope Method= 1
Parabolic Critical Depth
Global Vel Dist=  1 , 1 , 1
Global Log Level= 0
CheckData=True
Encroach Param= -1, 0, 0, 0
BEGIN DESCRIPTION:
Multiple Run
END DESCRIPTION:

--- UNT004 IN CCTC.f01 (steady flow) ---

Flow Title=Multiple
Number of Profiles=7
Profile Names=10-year,25-year,50-year,1pct_min,100-year,1pct_plu,500-year
River Rch & RM= UNT004 IN CCTC,Reach-1,5305
    1186    1626    1988    1776    2401    3248    3491
Boundary for River Rch & Prof#=UNT004 IN CCTC,Reach-1,1
Up Type=0
Dn Type=3
Dn Slope=0.005
Boundary for River Rch & Prof#=UNT004 IN CCTC,Reach-1,2
Up Type=0
Dn Type=3
Dn Slope=0.005
Boundary for River Rch & Prof#=UNT004 IN CCTC,Reach-1,3
Up Type=0
Dn Type=3
Dn Slope=0.005
Boundary for River Rch & Prof#=UNT004 IN CCTC,Reach-1,4
Up Type=0
Dn Type=3
Dn Slope=0.005
Boundary for River Rch & Prof#=UNT004 IN CCTC,Reach-1,5
Up Type=0
Dn Type=3
Dn Slope=0.005
Boundary for River Rch & Prof#=UNT004 IN CCTC,Reach-1,6
Up Type=0
Dn Type=3
Dn Slope=0.005
Boundary for River Rch & Prof#=UNT004 IN CCTC,Reach-1,7
Up Type=0
Dn Type=3
Dn Slope=0.005

--- UNT004 IN CCTC.g01 (geometry) ---

Geom Title=Existing Conditions

River Reach=UNT004 IN CCTC,Reach-1
Reach XY= 30
      3489197.61     10609912.19      3488907.75     10610077.00
      3488901.00     10610458.00      3489150.50     10610743.00
      3489093.00     10610778.00      3489036.75     10610744.00
      3489056.25     10610815.00      3489010.75     10610868.00
      3488935.75     10610815.00      3488966.25     10610924.00
      3488829.50     10611101.00      3488925.00     10611168.00
      3489003.25     10611128.00      3489033.00     10611203.00
      3488911.50     10611236.00      3488956.75     10611462.00
      3488897.25     10611574.00      3488994.25     10611628.00
      3489101.75     10611574.00      3489165.00     10611706.00
      3489349.25     10611572.00      3489590.75     10611718.00
      3489696.75     10611706.00      3489754.75     10611840.00
      3490136.75     10612044.00      3490314.50     10612008.00
      3490320.25     10612167.00      3490475.50     10612047.00
      3490522.50     10612150.00      3490328.50     10612360.00

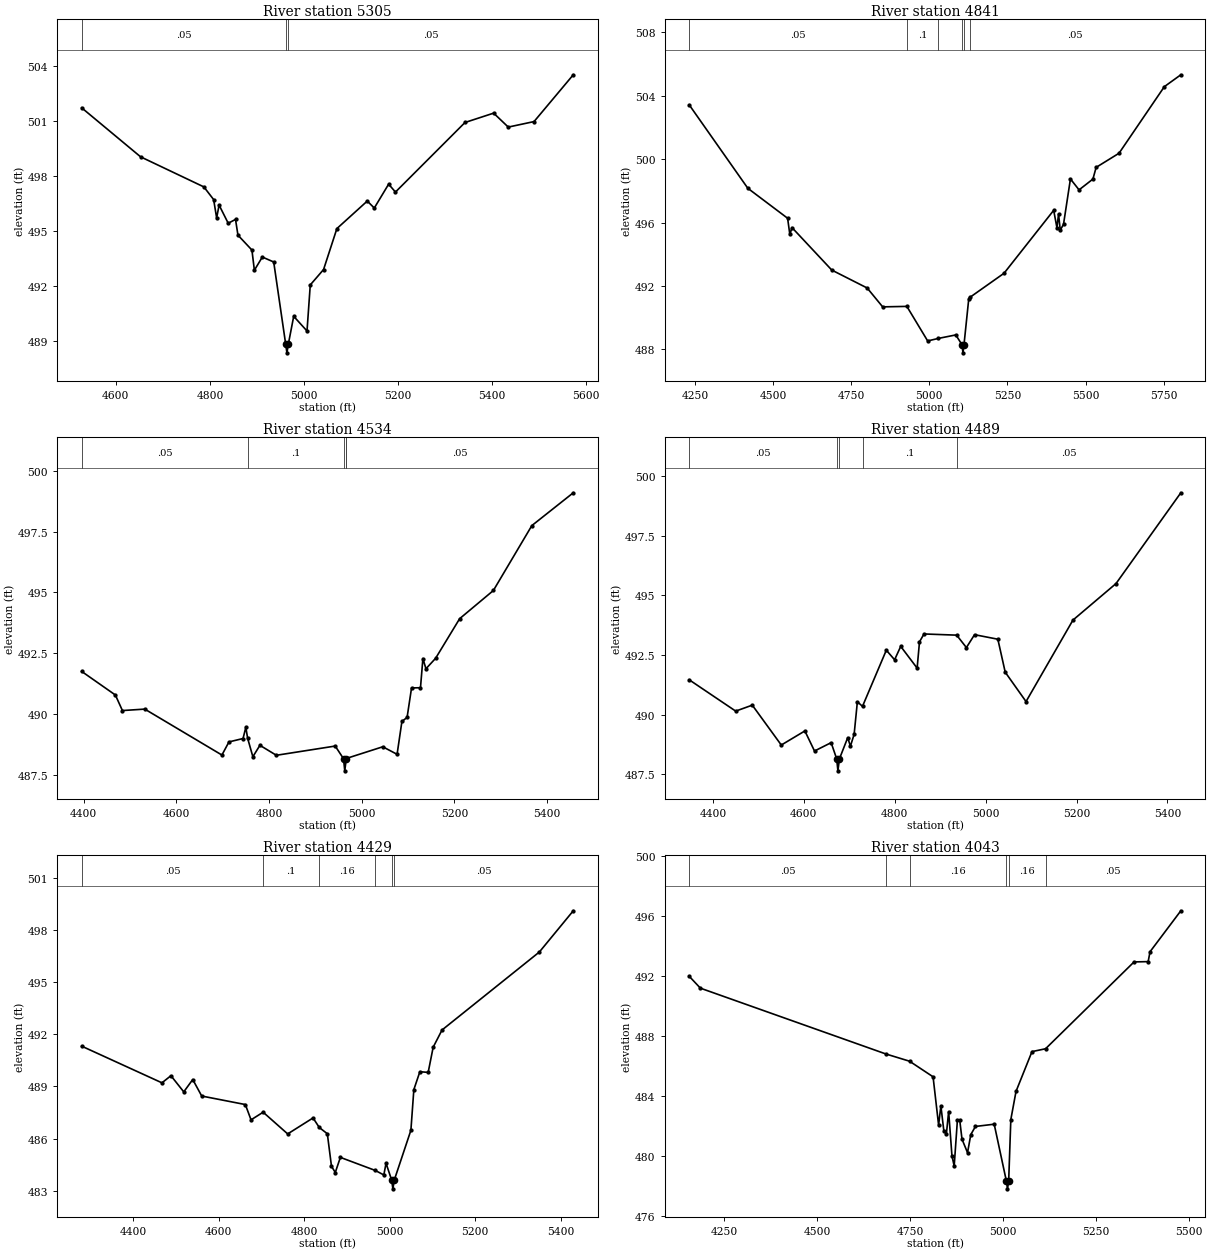
Type RM Length L Ch R = 1,5305,464,464,464
BEGIN DESCRIPTION:
UNT004 IN CCTC 7.0
END DESCRIPTION:
XS GIS Cut Line= 4
      3488940.37     10609559.19      3489044.54     10609949.85
      3489153.92     10610054.02      3489636.47     10609971.00
#Sta/Elev= 30
  4527.4  501.71  4652.6  499.04  4787.2  497.40  4807.9  496.71  4814.3  495.71
  4819.5  496.41  4838.9  495.42  4854.4  495.63  4859.6  494.77  4889.3  493.96
  4894.5  492.86  4911.4  493.58  4935.6  493.31  4960.9  488.86  4963.7  488.36
  4966.9  488.86  4978.1  490.35  5006.4  489.55  5013.3  492.06  5041.6  492.90
  5069.9  495.13  5134.5  496.63  5149.4  496.25  5179.9  497.55  5194.4  497.12
  5342.2  500.91  5403.1  501.42  5434.2  500.66  5489.0  500.96  5572.4  503.51
#Mann=3,-1,0
  4527.4    0.05       0  4960.9   0.035       0  4966.9    0.05       0
Bank Sta=4960.9,4966.9
Exp/Cntr=0.3,0.1

Type RM Length L Ch R = 1,4841,307,307,307
BEGIN DESCRIPTION:
UNT004 IN CCTC 6.0
END DESCRIPTION:
XS GIS Cut Line= 4
      3488304.96     10609819.64      3488810.17     10610309.23
      3488966.42     10610309.23      3489648.76     10610100.88
#Sta/Elev= 30
  4231.7  503.42  4419.2  498.16  4546.5  496.27  4553.6  495.25  4560.6  495.68
  4687.9  493.00  4801.1  491.87  4850.7  490.68  4928.1  490.71  4994.7  488.53
  5028.9  488.69  5084.7  488.91  5104.9  488.28  5107.6  487.78  5110.9  488.28
  5126.2  491.19  5129.9  491.28  5239.1  492.80  5398.0  496.77  5408.4  495.67
  5413.6  496.54  5418.9  495.52  5429.4  495.88  5451.6  498.75  5479.2  498.06
  5523.5  498.74  5533.9  499.48  5607.1  500.37  5752.1  504.57  5804.9  505.32
#Mann=6,-1,0
  4231.7    0.05       0  4928.1     0.1       0  5028.9    0.16       0
  5104.9    0.07       0  5110.9    0.16       0  5129.9    0.05       0
Bank Sta=5104.9,5110.9
Exp/Cntr=0.3,0.1

Type RM Length L Ch R = 1,4534,45,45,45
BEGIN DESCRIPTION:
Mapping XS 24e89498
END DESCRIPTION:
XS GIS Cut Line= 6
      3488495.48     10610314.63      3488836.61     10610533.36
      3488888.69     10610562.01      3488953.79     10610572.42
      3489076.19     10610546.38      3489465.73     10610437.31
#Sta/Elev= 30
  4395.7  491.75  4468.4  490.78  4483.6  490.14  4531.8  490.20  4698.3  488.31
  4713.5  488.85  4743.9  488.99  4749.9  489.45  4753.8  489.00  4765.1  488.24
  4780.3  488.71  4815.8  488.30  4942.8  488.68  4960.7  488.16  4963.4  487.66
  4966.7  488.16  4966.9  488.17  5045.4  488.65  5076.3  488.34  5086.7  489.69
  5097.9  489.86  5107.5  491.07  5126.8  491.08  5132.0  492.28  5138.6  491.86
  5159.4  492.29  5211.3  493.92  5284.1  495.08  5367.1  497.75  5456.5  499.10
#Mann=5,-1,0
  4395.7    0.05       0  4753.8     0.1       0  4960.7   0.035       0
  4966.7     0.1       0  4966.9    0.05       0
Bank Sta=4960.7,4966.7
Exp/Cntr=0.3,0.1

Type RM Length L Ch R = 1,4489,60,60,60
BEGIN DESCRIPTION:
Mapping XS bf76dd84
END DESCRIPTION:
XS GIS Cut Line= 6
      3488471.99     10610348.44      3488847.02     10610582.84
      3488932.96     10610601.07      3488995.46     10610598.46
      3489086.61     10610577.63      3489469.46     10610478.66
#Sta/Elev= 30
  4347.9  491.46  4450.1  490.15  4486.6  490.40  4550.4  488.73  4602.3  489.32
  4623.5  488.48  4660.1  488.83  4672.3  488.15  4675.0  487.65  4678.3  488.15
  4696.6  489.04  4702.5  488.68  4710.7  489.18  4717.8  490.54  4729.1  490.35
  4781.5  492.70  4799.7  492.30  4813.2  492.86  4849.3  491.95  4854.5  493.05
  4864.4  493.38  4936.3  493.33  4957.7  492.81  4975.6  493.35  5026.9  493.16
  5043.1  491.78  5088.9  490.55  5192.1  493.96  5286.9  495.49  5429.5  499.29
#Mann=5,-1,0
  4347.9    0.05       0  4672.3   0.035       0  4678.3    0.05       0
  4729.1     0.1       0  4936.3    0.05       0
Bank Sta=4672.3,4678.3
Exp/Cntr=0.3,0.1

Type RM Length L Ch R = 1,4429,386,386,386
BEGIN DESCRIPTION:
Mapping XS 823b0c99
END DESCRIPTION:
XS GIS Cut Line= 6
      3488440.74     10610369.28      3488844.42     10610640.13
      3488940.77     10610666.17      3489021.50     10610658.36
      3489146.50     10610619.30      3489486.08     10610528.57
#Sta/Elev= 30
  4279.6  491.32  4467.3  489.21  4488.3  489.62  4518.3  488.69  4539.3  489.40
  4560.3  488.45  4662.3  487.96  4675.6  487.08  4703.9  487.52  4761.3  486.27
  4820.6  487.19  4835.2  486.64  4854.0  486.28  4863.7  484.41  4872.6  484.05
  4884.5  484.92  4965.9  484.17  4986.1  483.91  4991.3  484.58  5004.5  483.61
  5007.3  483.11  5010.5  483.61  5049.4  486.48  5056.3  488.82  5070.4  489.85
  5089.8  489.81  5101.5  491.26  5122.2  492.25  5349.9  496.74  5429.1  499.11
#Mann=6,-1,0
  4279.6    0.05       0  4703.9     0.1       0  4835.2    0.16       0
  4965.9    0.05       0  5004.5   0.035       0  5010.5    0.05       0
Bank Sta=5004.5,5010.5
Exp/Cntr=0.3,0.1

Type RM Length L Ch R = 1,4043,1112,1112,1112
BEGIN DESCRIPTION:
UNT004 IN CCTC 5.0
END DESCRIPTION:
XS GIS Cut Line= 3
      3488354.84     10610353.67      3489125.67     10610882.32
      3489503.32     10610796.37
#Sta/Elev= 30
  4156.4  491.97  4186.4  491.18  4685.5  486.79  4748.8  486.31  4812.1  485.27
  4827.0  482.05  4833.1  483.33  4841.2  481.64  4848.0  481.48  4854.0  482.95
  4862.9  480.00  4868.9  479.32  4877.6  482.40  4883.8  482.38  4889.9  481.11
  4904.8  480.21  4913.6  481.42  4926.1  481.96  4976.5  482.11  5009.4  478.30
  5012.2  477.80  5015.4  478.30  5021.2  482.42  5035.2  484.30  5078.1  486.95
  5114.6  487.14  5352.6  492.93  5390.5  492.95  5395.6  493.61  5478.4  496.34
#Mann=6,-1,0
  4156.4    0.05       0  4685.5     0.1       0  4748.8    0.16       0
  5009.4    0.07       0  5015.4    0.16       0  5114.6    0.05       0
Bank Sta=5009.4,5015.4
Exp/Cntr=0.3,0.1

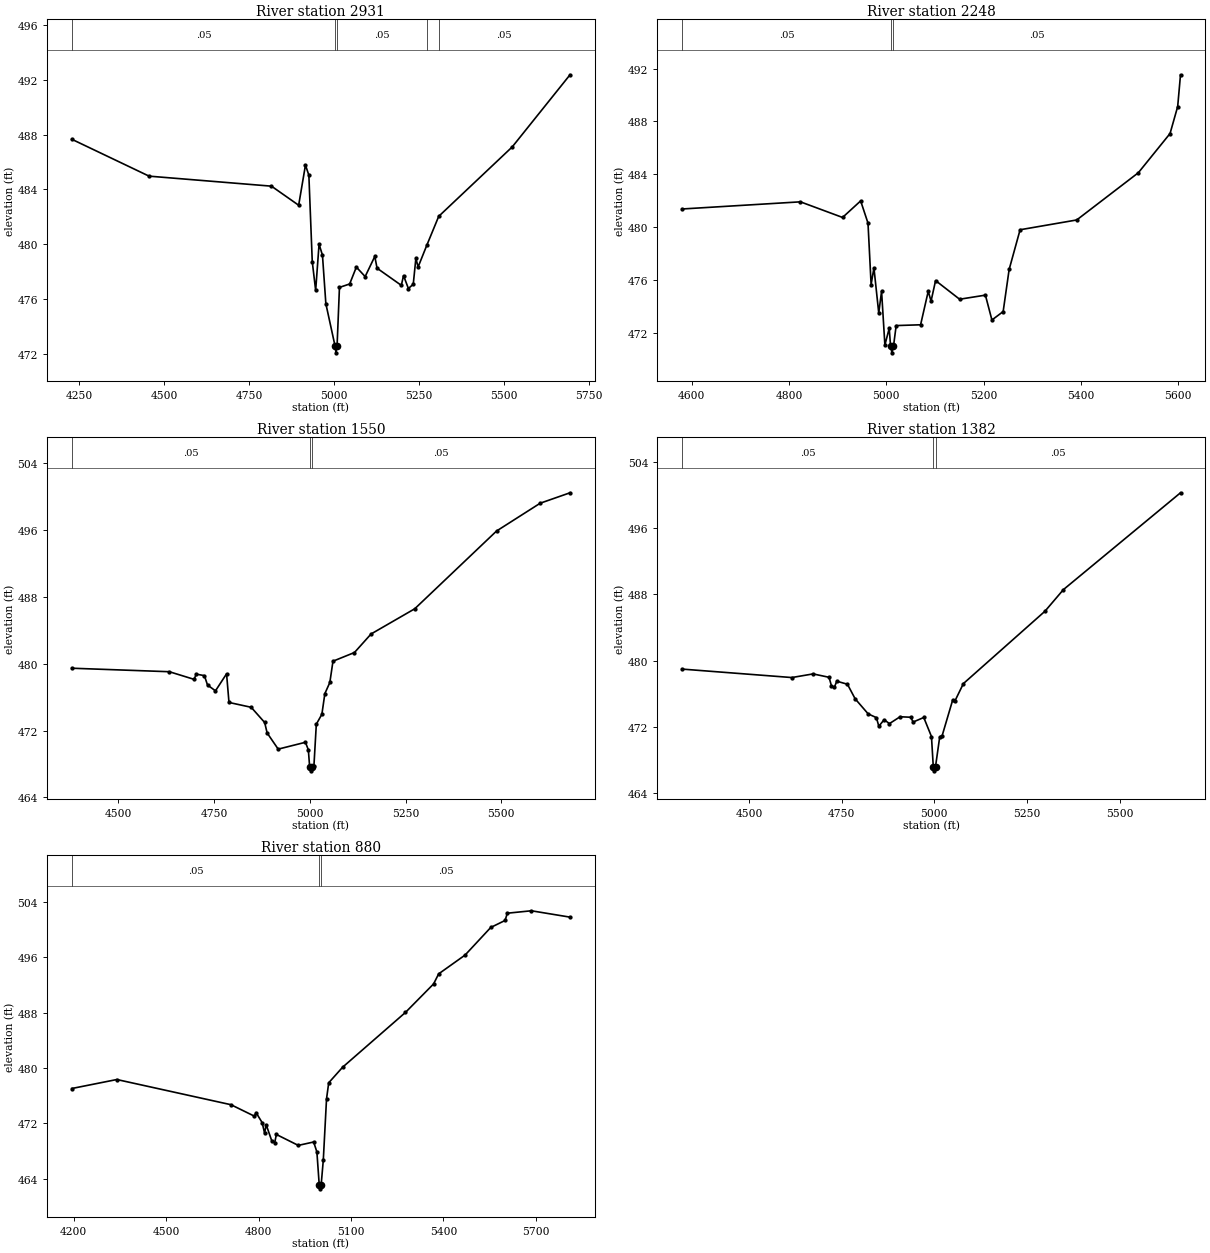
Type RM Length L Ch R = 1,2931,683,683,683
BEGIN DESCRIPTION:
UNT004 IN CCTC 4.0
END DESCRIPTION:
XS GIS Cut Line= 3
      3488162.14     10611346.73      3489025.84     10611355.41
      3489415.51     10610896.46
#Sta/Elev= 30
  4227.8  487.66  4455.3  484.97  4815.3  484.24  4895.3  482.85  4915.3  485.78
  4925.3  485.04  4935.3  478.74  4945.3  476.64  4955.3  480.01  4965.3  479.21
  4975.3  475.67  5002.3  472.59  5005.1  472.09  5008.3  472.59  5015.3  476.86
  5045.3  477.11  5065.0  478.34  5090.9  477.65  5119.3  479.12  5125.9  478.26
  5197.3  477.01  5203.8  477.72  5218.1  476.78  5232.4  477.09  5240.1  478.98
  5246.7  478.35  5272.4  479.94  5307.3  482.04  5523.5  487.10  5693.6  492.36
#Mann=5,-1,0
  4227.8    0.05       0  5002.3   0.035       0  5008.3    0.05       0
  5272.4    0.16       0  5307.3    0.05       0
Bank Sta=5002.3,5008.3
Exp/Cntr=0.3,0.1

Type RM Length L Ch R = 1,2248,698,698,698
BEGIN DESCRIPTION:
Mapping XS 46f3cfae
END DESCRIPTION:
XS GIS Cut Line= 2
      3488978.68     10612059.98      3489494.70     10611175.38
#Sta/Elev= 30
  4580.8  481.39  4823.7  481.93  4910.3  480.75  4947.5  482.00  4962.6  480.32
  4969.0  475.68  4974.8  476.94  4984.7  473.53  4990.5  475.17  4997.3  471.11
  5006.2  472.37  5009.0  471.02  5011.8  470.52  5015.0  471.02  5020.5  472.58
  5070.7  472.64  5086.4  475.17  5092.2  474.43  5101.5  475.98  5150.9  474.57
  5203.9  474.88  5217.3  473.00  5240.4  473.64  5252.7  476.82  5275.2  479.82
  5391.6  480.56  5518.3  484.13  5583.4  487.09  5599.1  489.13  5604.9  491.53
#Mann=3,-1,0
  4580.8    0.05       0  5009.0   0.035       0  5015.0    0.05       0
Bank Sta=5009,5015
Exp/Cntr=0.3,0.1

Type RM Length L Ch R = 1,1550,168,168,168
BEGIN DESCRIPTION:
UNT004 IN CCTC 3.0
END DESCRIPTION:
XS GIS Cut Line= 2
      3489364.94     10612242.30      3490162.96     10611214.41
#Sta/Elev= 30
  4378.2  479.48  4633.1  479.06  4697.4  478.15  4703.7  478.77  4724.6  478.59
  4732.7  477.47  4753.5  476.77  4782.5  478.81  4788.8  475.38  4846.8  474.80
  4882.0  472.98  4888.4  471.73  4917.3  469.79  4988.5  470.61  4996.1  469.70
  4999.4  467.69  5002.2  467.19  5005.4  467.69  5010.6  467.75  5016.9  472.78
  5031.4  473.96  5039.2  476.44  5052.2  477.77  5060.4  480.32  5116.5  481.36
  5159.9  483.58  5274.0  486.60  5487.6  495.91  5601.6  499.24  5679.5  500.49
#Mann=3,-1,0
  4378.2    0.05       0  4999.4    0.04       0  5005.4    0.05       0
Bank Sta=4999.4,5005.4
Exp/Cntr=0.3,0.1

Type RM Length L Ch R = 1,1382,502,502,502
BEGIN DESCRIPTION:
UNT004 IN CCTC 2.0
END DESCRIPTION:
XS GIS Cut Line= 2
      3489390.98     10612398.55      3490241.68     10611356.88
#Sta/Elev= 30
  4319.5  478.97  4615.3  477.95  4672.7  478.39  4715.8  477.98  4722.3  476.93
  4730.2  476.78  4736.6  477.51  4765.4  477.14  4786.2  475.38  4821.3  473.56
  4843.6  473.10  4850.1  472.06  4864.4  472.85  4878.8  472.38  4907.5  473.21
  4936.2  473.15  4942.7  472.57  4971.4  473.12  4992.2  470.82  4997.1  467.17
  4999.9  466.67  5003.1  467.17  5014.5  470.78  5020.9  470.90  5049.7  475.27
  5056.1  475.17  5078.4  477.22  5298.6  485.97  5348.3  488.58  5664.4  500.29
#Mann=3,-1,0
  4319.5    0.05       0  4997.1    0.04       0  5003.1    0.05       0
Bank Sta=4997.1,5003.1
Exp/Cntr=0.3,0.1

Type RM Length L Ch R = 1,880,0,0,0
BEGIN DESCRIPTION:
UNT004 IN CCTC 1.0
END DESCRIPTION:
XS GIS Cut Line= 4
      3489680.35     10612434.90      3490172.26     10612277.00
      3490285.10     10611903.73      3490549.62     10611244.60
#Sta/Elev= 30
  4194.0  477.04  4340.3  478.34  4710.6  474.70  4786.8  473.04  4792.0  473.56
  4811.8  472.11  4819.7  470.59  4824.9  471.80  4843.1  469.46  4852.6  469.22
  4857.9  470.40  4929.0  468.82  4978.9  469.31  4989.4  467.87  4997.1  463.04
  4999.9  462.54  5003.1  463.04  5010.2  466.70  5020.7  475.56  5027.8  477.87
  5072.9  480.12  5276.8  488.04  5368.1  492.16  5384.5  493.61  5470.3  496.33
  5553.6  500.32  5600.0  501.33  5607.4  502.38  5685.4  502.73  5810.8  501.81
#Mann=3,-1,0
  4194.0    0.05       0  4997.1   0.035       0  5003.1    0.05       0
Bank Sta=4997.1,5003.1
Exp/Cntr=0.3,0.1

Chan Stop Cuts=-1