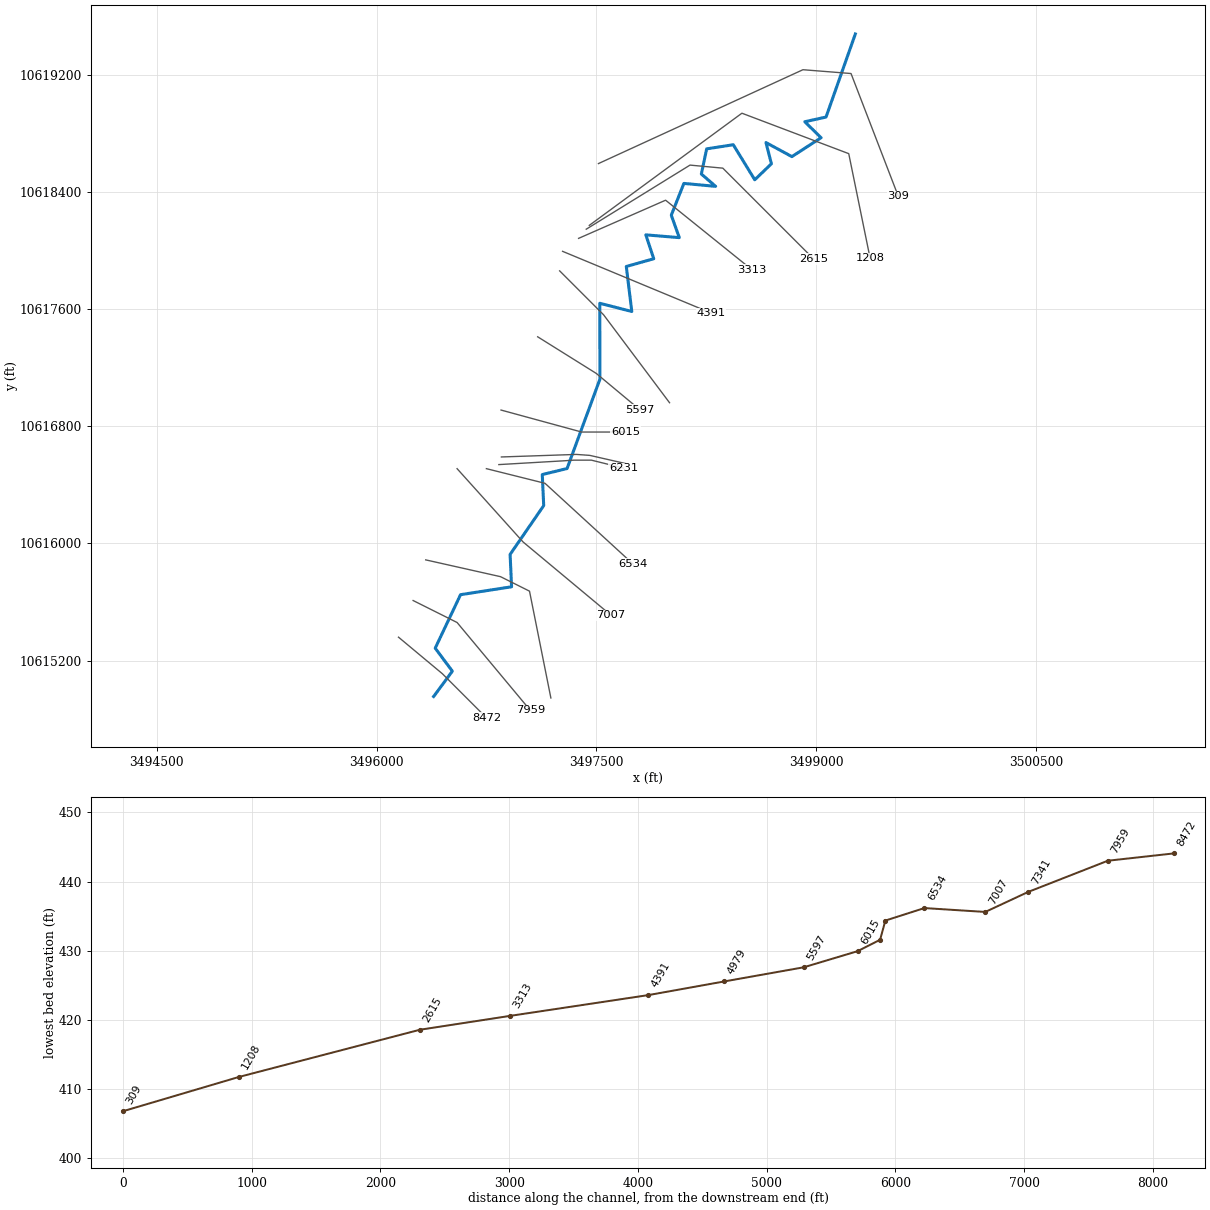
--- UNT008 IN CCTC.prj (project) ---

Proj Title=UNT008 IN CCTC Base Level Engineering
Current Plan=p01
Default Exp/Contr=0.3,0.1
English Units
Geom File=g01
Flow File=f01
Plan File=p01
BEGIN DESCRIPTION:
UNT008 IN CCTC
END DESCRIPTION:

--- UNT008 IN CCTC.p01 (plan) ---

Plan Title=Multiple Run
Short Identifier=Multiple
Geom File=g01
Flow File=f01
Subcritical Flow
K Sum by GR= 0
Std Step Tol= 0.01
Critical Tol= 0.01
Num of Std Step Trials= 20
Max Error Tol= 0.3
Flow Tol Ratio= 0.001
Split Flow NTrial= 30
Split Flow Tol= 0.02
Split Flow Ratio= 0.02
Log Output Level= 0
Friction Slope Method= 1
Unsteady Friction Slope Method= 2
Unsteady Bridges Friction Slope Method= 1
Parabolic Critical Depth
Global Vel Dist=  1 , 1 , 1
Global Log Level= 0
CheckData=True
Encroach Param= -1, 0, 0, 0
BEGIN DESCRIPTION:
Multiple Run
END DESCRIPTION:

--- UNT008 IN CCTC.f01 (steady flow) ---

Flow Title=Multiple
Number of Profiles=7
Profile Names=10-year,25-year,50-year,1pct_min,100-year,1pct_plu,500-year
River Rch & RM= UNT008 IN CCTC,Reach-1,8472
     992    1344    1631    1445    1954    2643    2798
River Rch & RM= UNT008 IN CCTC,Reach-1,6231
    1211    1657    2022    1802    2436    3295    3526
Boundary for River Rch & Prof#=UNT008 IN CCTC,Reach-1,1
Up Type=0
Dn Type=3
Dn Slope=0.005
Boundary for River Rch & Prof#=UNT008 IN CCTC,Reach-1,2
Up Type=0
Dn Type=3
Dn Slope=0.005
Boundary for River Rch & Prof#=UNT008 IN CCTC,Reach-1,3
Up Type=0
Dn Type=3
Dn Slope=0.005
Boundary for River Rch & Prof#=UNT008 IN CCTC,Reach-1,4
Up Type=0
Dn Type=3
Dn Slope=0.005
Boundary for River Rch & Prof#=UNT008 IN CCTC,Reach-1,5
Up Type=0
Dn Type=3
Dn Slope=0.005
Boundary for River Rch & Prof#=UNT008 IN CCTC,Reach-1,6
Up Type=0
Dn Type=3
Dn Slope=0.005
Boundary for River Rch & Prof#=UNT008 IN CCTC,Reach-1,7
Up Type=0
Dn Type=3
Dn Slope=0.005

--- UNT008 IN CCTC.g01 (geometry) ---

Geom Title=Existing Conditions

River Reach=UNT008 IN CCTC,Reach-1
Reach XY= 30
      3496389.50     10614955.00      3496517.25     10615128.00
      3496400.25     10615285.00      3496573.25     10615650.00
      3496921.50     10615704.00      3496911.50     10615925.00
      3497140.75     10616258.00      3497131.00     10616470.00
      3497300.25     10616511.00      3497524.50     10617121.00
      3497523.50     10617639.00      3497742.00     10617583.00
      3497704.50     10617890.00      3497891.75     10617943.00
      3497837.75     10618106.00      3498066.25     10618087.00
      3498011.50     10618240.00      3498097.50     10618457.00
      3498314.25     10618437.00      3498216.75     10618521.00
      3498253.00     10618693.00      3498434.50     10618721.00
      3498581.25     10618482.00      3498695.00     10618591.00
      3498657.50     10618736.00      3498834.75     10618640.00
      3499034.00     10618769.00      3498922.50     10618878.00
      3499067.75     10618910.00      3499267.75     10619477.00

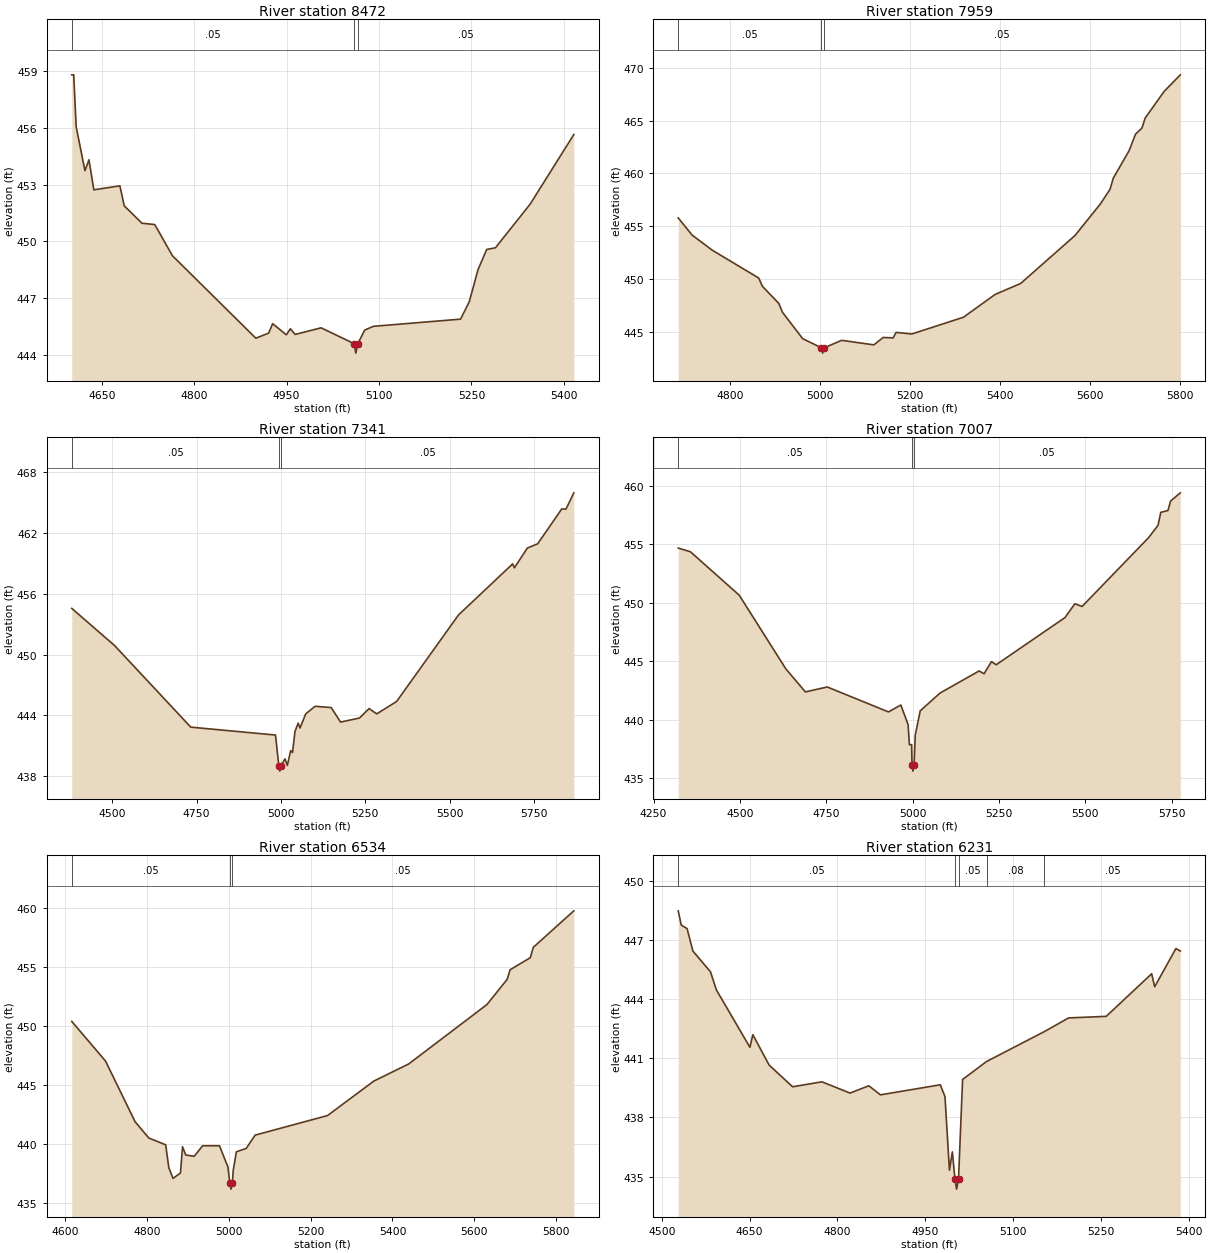
Type RM Length L Ch R = 1,8472,513,513,513
BEGIN DESCRIPTION:
UNT008 IN CCTC 11.0
END DESCRIPTION:
XS GIS Cut Line= 3
      3496149.64     10615360.16      3496449.61     10615110.19
      3496749.58     10614810.22
#Sta/Elev= 30
  4601.4  458.82  4604.6  458.82  4608.5  456.08  4622.8  453.74  4629.3  454.32
  4637.2  452.73  4679.5  452.94  4686.6  451.88  4715.3  450.96  4736.1  450.89
  4764.7  449.24  4900.1  444.87  4920.9  445.14  4927.4  445.64  4949.6  445.05
  4956.1  445.37  4963.9  445.07  5006.0  445.42  5059.6  444.58  5062.3  444.08
  5065.6  444.58  5076.7  445.30  5090.9  445.50  5232.3  445.88  5246.4  446.80
  5260.6  448.50  5274.7  449.57  5288.9  449.66  5345.4  451.98  5416.1  455.66
#Mann=3,-1,0
  4601.4    0.05       0  5059.6    0.03       0  5065.6    0.05       0
Bank Sta=5059.6,5065.6
Exp/Cntr=0.3,0.1

Type RM Length L Ch R = 1,7959,618,618,618
BEGIN DESCRIPTION:
UNT008 IN CCTC 10.0
END DESCRIPTION:
XS GIS Cut Line= 3
      3496249.58     10615610.20      3496549.61     10615460.19
      3497049.63     10614860.16
#Sta/Elev= 30
  4684.3  455.80  4715.1  454.18  4759.8  452.75  4863.2  450.12  4871.6  449.33
  4907.9  447.72  4916.3  446.87  4961.0  444.39  5002.8  443.52  5005.5  443.02
  5008.8  443.52  5047.7  444.23  5119.3  443.80  5140.1  444.50  5162.3  444.46
  5168.8  444.98  5203.9  444.83  5318.5  446.41  5388.8  448.56  5446.0  449.61
  5566.5  454.13  5623.1  457.12  5644.6  458.51  5651.7  459.55  5686.9  462.15
  5701.2  463.71  5715.5  464.29  5722.7  465.24  5765.0  467.76  5800.8  469.32
#Mann=3,-1,0
  4684.3    0.05       0  5002.8   0.035       0  5008.8    0.05       0
Bank Sta=5002.8,5008.8
Exp/Cntr=0.3,0.1

Type RM Length L Ch R = 1,7341,334,334,334
BEGIN DESCRIPTION:
UNT008 IN CCTC 9.0
END DESCRIPTION:
XS GIS Cut Line= 4
      3496335.52     10615887.63      3496845.98     10615773.04
      3497043.90     10615674.08      3497189.70     10614945.06
#Sta/Elev= 30
  4380.0  454.57  4507.2  450.89  4732.7  442.85  4983.8  442.07  4993.7  439.01
  4996.4  438.51  4999.7  439.01  5011.8  439.72  5019.0  439.07  5028.6  440.53
  5034.2  440.35  5041.4  442.41  5050.9  443.24  5056.5  442.77  5073.3  444.16
  5101.2  444.91  5148.8  444.78  5176.7  443.35  5232.8  443.75  5261.0  444.68
  5283.8  444.16  5342.6  445.38  5526.1  453.92  5686.6  458.96  5691.7  458.57
  5730.1  460.52  5760.7  460.94  5832.1  464.38  5844.7  464.37  5867.9  465.97
#Mann=3,-1,0
  4380.0    0.05       0  4993.7    0.03       0  4999.7    0.05       0
Bank Sta=4993.7,4999.7
Exp/Cntr=0.3,0.1

Type RM Length L Ch R = 1,7007,473,473,473
BEGIN DESCRIPTION:
UNT008 IN CCTC 8.0
END DESCRIPTION:
XS GIS Cut Line= 3
      3496549.63     10616510.17      3496999.61     10616010.19
      3497599.63     10615510.17
#Sta/Elev= 30
  4321.6  454.67  4357.1  454.35  4498.3  450.64  4632.9  444.36  4689.7  442.38
  4753.2  442.80  4930.3  440.67  4966.2  441.26  4987.2  439.58  4990.9  437.87
  4997.5  437.87  4998.4  436.11  5001.2  435.61  5004.4  436.11  5007.9  438.69
  5022.2  440.76  5079.5  442.28  5192.8  444.17  5207.1  443.93  5228.6  444.97
  5242.2  444.70  5441.4  448.73  5470.0  449.91  5490.9  449.68  5683.5  455.56
  5710.8  456.61  5718.7  457.72  5739.5  457.88  5747.3  458.69  5775.3  459.39
#Mann=3,-1,0
  4321.6    0.05       0  4998.4    0.03       0  5004.4    0.05       0
Bank Sta=4998.4,5004.4
Exp/Cntr=0.3,0.1

Type RM Length L Ch R = 1,6534,303,303,303
BEGIN DESCRIPTION:
UNT008 IN CCTC 7.0
END DESCRIPTION:
XS GIS Cut Line= 3
      3496749.58     10616510.19      3497149.61     10616410.19
      3497749.63     10615860.17
#Sta/Elev= 30
  4616.7  450.37  4699.2  447.01  4771.3  441.88  4804.8  440.50  4846.1  439.92
  4853.8  437.97  4864.1  437.08  4882.1  437.53  4887.3  439.76  4895.0  439.06
  4915.7  438.95  4936.3  439.84  4977.5  439.84  4998.1  438.05  5002.8  436.67
  5005.6  436.17  5008.8  436.67  5011.0  437.74  5018.7  439.33  5042.9  439.62
  5064.5  440.74  5241.5  442.40  5354.6  445.32  5439.4  446.76  5630.6  451.79
  5680.2  453.93  5687.3  454.74  5736.6  455.76  5744.0  456.64  5843.0  459.73
#Mann=3,-1,0
  4616.7    0.05       0  5002.8   0.035       0  5008.8    0.05       0
Bank Sta=5002.8,5008.8
Exp/Cntr=0.3,0.1

Type RM Length L Ch R = 1,6231,41,41,41
BEGIN DESCRIPTION:
Mapping XS 3a9d23f9
END DESCRIPTION:
XS GIS Cut Line= 5
      3496834.56     10616537.94      3497281.60     10616563.98
      3497346.71     10616568.32      3497466.06     10616568.32
      3497684.95     10616514.14
#Sta/Elev= 30
  4528.0  448.47  4533.1  447.75  4543.1  447.57  4553.1  446.43  4583.1  445.38
  4593.2  444.46  4650.5  441.55  4655.5  442.19  4683.3  440.65  4723.4  439.55
  4773.5  439.80  4821.6  439.23  4853.6  439.60  4873.6  439.14  4975.8  439.65
  4983.8  439.05  4991.4  435.32  4996.4  436.25  5000.9  434.86  5003.6  434.36
  5006.9  434.86  5013.9  439.92  5054.8  440.83  5153.8  442.35  5195.0  443.04
  5259.3  443.12  5337.0  445.28  5342.1  444.62  5378.4  446.56  5385.9  446.43
#Mann=5,-1,0
  4528.0    0.05       0  5000.9    0.04       0  5006.9    0.05       0
  5054.8    0.08       0  5153.8    0.05       0
Bank Sta=5000.9,5006.9
Exp/Cntr=0.3,0.1

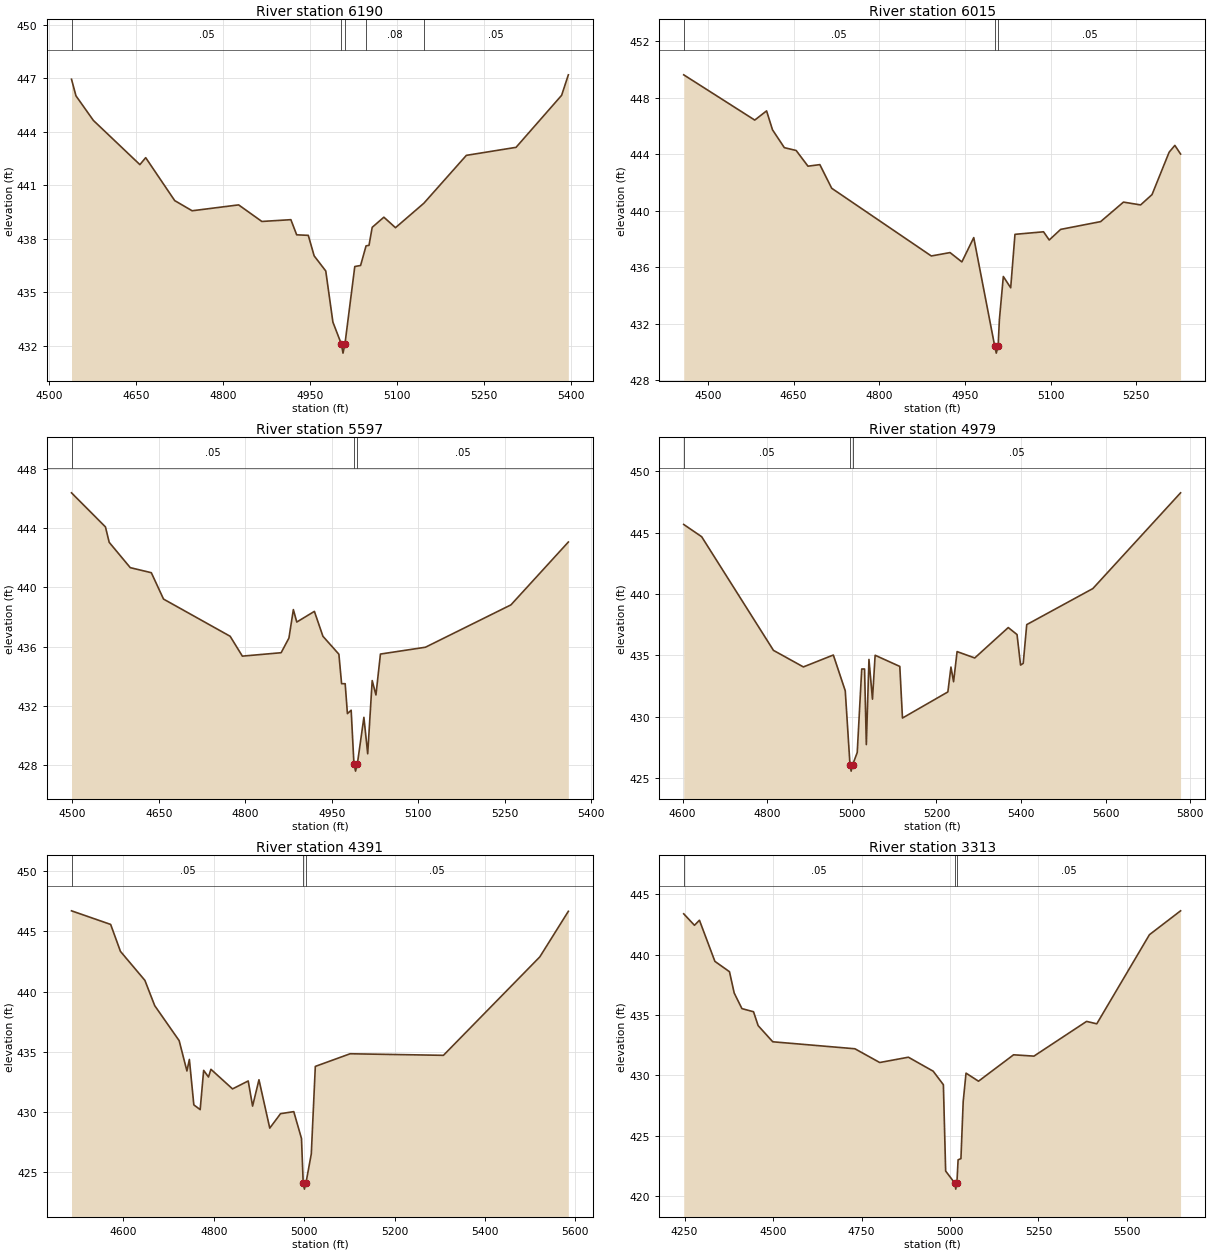
Type RM Length L Ch R = 1,6190,175,175,175
BEGIN DESCRIPTION:
Mapping XS 708f2b5f
END DESCRIPTION:
XS GIS Cut Line= 4
      3496851.90     10616590.02      3497364.07     10616607.38
      3497455.21     10616600.87      3497700.96     10616544.83
#Sta/Elev= 30
  4539.2  446.95  4546.9  446.02  4576.9  444.64  4657.0  442.16  4667.0  442.55
  4717.0  440.14  4747.0  439.57  4827.1  439.90  4867.1  438.97  4917.1  439.07
  4927.1  438.22  4947.1  438.19  4957.2  437.04  4977.2  436.19  4989.5  433.32
  5004.2  432.08  5006.9  431.58  5010.2  432.08  5027.2  436.44  5037.2  436.50
  5046.6  437.60  5051.7  437.63  5057.2  438.64  5077.3  439.21  5097.3  438.62
  5146.1  439.99  5219.4  442.68  5305.0  443.13  5383.5  446.05  5395.1  447.20
#Mann=5,-1,0
  4539.2    0.05       0  5004.2    0.04       0  5010.2    0.05       0
  5046.6    0.08       0  5146.1    0.05       0
Bank Sta=5004.2,5010.2
Exp/Cntr=0.3,0.1

Type RM Length L Ch R = 1,6015,418,418,418
BEGIN DESCRIPTION:
UNT008 IN CCTC 6.0
END DESCRIPTION:
XS GIS Cut Line= 3
      3496849.63     10616910.18      3497399.61     10616760.19
      3497699.64     10616760.19
#Sta/Elev= 30
  4457.5  449.61  4581.9  446.41  4602.6  447.06  4613.0  445.72  4633.7  444.46
  4654.4  444.26  4675.1  443.15  4695.9  443.26  4716.6  441.59  4891.1  436.80
  4923.9  437.04  4944.6  436.38  4965.4  438.10  5002.1  430.43  5004.9  429.93
  5008.1  430.43  5010.3  432.29  5017.2  435.35  5030.1  434.55  5037.6  438.33
  5087.6  438.51  5097.6  437.93  5117.6  438.68  5187.6  439.23  5227.6  440.61
  5257.6  440.41  5277.6  441.14  5307.6  444.14  5317.6  444.62  5327.6  444.01
#Mann=3,-1,0
  4457.5    0.05       0  5002.1   0.035       0  5008.1    0.05       0
Bank Sta=5002.1,5008.1
Exp/Cntr=0.3,0.1

Type RM Length L Ch R = 1,5597,618,618,618
BEGIN DESCRIPTION:
UNT008 IN CCTC 5.0
END DESCRIPTION:
XS GIS Cut Line= 3
      3497099.65     10617410.16      3497499.61     10617160.19
      3497799.64     10616910.17
#Sta/Elev= 30
  4498.6  446.38  4557.5  444.08  4564.0  443.04  4600.6  441.33  4637.1  440.99
  4658.3  439.21  4773.9  436.70  4795.1  435.36  4862.4  435.59  4875.9  436.58
  4883.6  438.50  4889.5  437.66  4920.1  438.38  4934.9  436.70  4962.6  435.49
  4967.3  433.50  4973.5  433.50  4977.4  431.48  4983.9  431.71  4988.7  428.10
  4991.5  427.60  4994.7  428.10  5006.0  431.23  5012.6  428.77  5020.4  433.71
  5026.9  432.74  5034.7  435.50  5112.8  435.96  5261.2  438.82  5360.8  443.06
#Mann=3,-1,0
  4498.6    0.05       0  4988.7   0.035       0  4994.7    0.05       0
Bank Sta=4988.7,4994.7
Exp/Cntr=0.3,0.1

Type RM Length L Ch R = 1,4979,588,588,588
BEGIN DESCRIPTION:
UNT008 IN CCTC 4.0
END DESCRIPTION:
XS GIS Cut Line= 3
      3497249.61     10617860.19      3497549.61     10617560.19
      3497999.63     10616960.16
#Sta/Elev= 30
  4602.6  445.67  4645.0  444.67  4814.7  435.40  4885.4  434.05  4956.2  435.02
  4984.4  432.10  4995.6  426.05  4998.3  425.55  5001.6  426.05  5012.7  427.07
  5023.3  433.88  5030.0  433.88  5034.2  427.71  5040.4  434.66  5048.7  431.42
  5055.0  435.00  5113.3  434.09  5119.6  429.88  5226.9  432.01  5234.2  434.04
  5240.4  432.84  5248.7  435.30  5290.4  434.78  5369.6  437.26  5390.4  436.69
  5398.7  434.20  5405.0  434.34  5413.3  437.50  5569.6  440.44  5776.9  448.25
#Mann=3,-1,0
  4602.6    0.05       0  4995.6   0.035       0  5001.6    0.05       0
Bank Sta=4995.6,5001.6
Exp/Cntr=0.3,0.1

Type RM Length L Ch R = 1,4391,1078,1078,1078
BEGIN DESCRIPTION:
Mapping XS b59ee331
END DESCRIPTION:
XS GIS Cut Line= 2
      3497269.61     10617993.52      3498284.90     10617571.78
#Sta/Elev= 30
  4485.2  446.71  4571.8  445.58  4593.5  443.34  4647.6  440.93  4669.3  438.83
  4723.4  435.92  4740.6  433.40  4746.0  434.36  4755.9  430.58  4769.9  430.19
  4777.6  433.45  4788.3  432.90  4793.7  433.54  4841.5  431.91  4876.2  432.57
  4885.9  430.48  4900.0  432.67  4923.9  428.65  4947.7  429.85  4977.0  430.02
  4994.1  427.79  4997.9  424.08  5000.6  423.58  5003.9  424.08  5015.8  426.51
  5024.7  433.78  5101.7  434.83  5308.2  434.70  5521.4  442.88  5584.6  446.67
#Mann=3,-1,0
  4485.2    0.05       0  4997.9   0.035       0  5003.9    0.05       0
Bank Sta=4997.9,5003.9
Exp/Cntr=0.3,0.1

Type RM Length L Ch R = 1,3313,698,698,698
BEGIN DESCRIPTION:
Mapping XS 8909a84c
END DESCRIPTION:
XS GIS Cut Line= 3
      3497378.92     10618082.05      3497972.72     10618342.48
      3498561.29     10617868.50
#Sta/Elev= 30
  4247.6  443.39  4278.0  442.44  4292.0  442.86  4335.7  439.45  4376.9  438.59
  4390.3  436.82  4412.1  435.53  4444.9  435.27  4457.9  434.12  4499.2  432.78
  4731.4  432.20  4801.5  431.06  4882.5  431.50  4952.6  430.34  4981.4  429.22
  4987.8  422.06  5013.6  421.06  5016.4  420.56  5019.6  421.06  5023.0  422.99
  5031.0  423.09  5037.4  427.82  5045.4  430.18  5080.6  429.51  5179.8  431.70
  5237.3  431.59  5386.1  434.47  5414.9  434.27  5563.7  441.66  5651.7  443.64
#Mann=3,-1,0
  4247.6    0.05       0  5013.6    0.03       0  5019.6    0.05       0
Bank Sta=5013.6,5019.6
Exp/Cntr=0.3,0.1

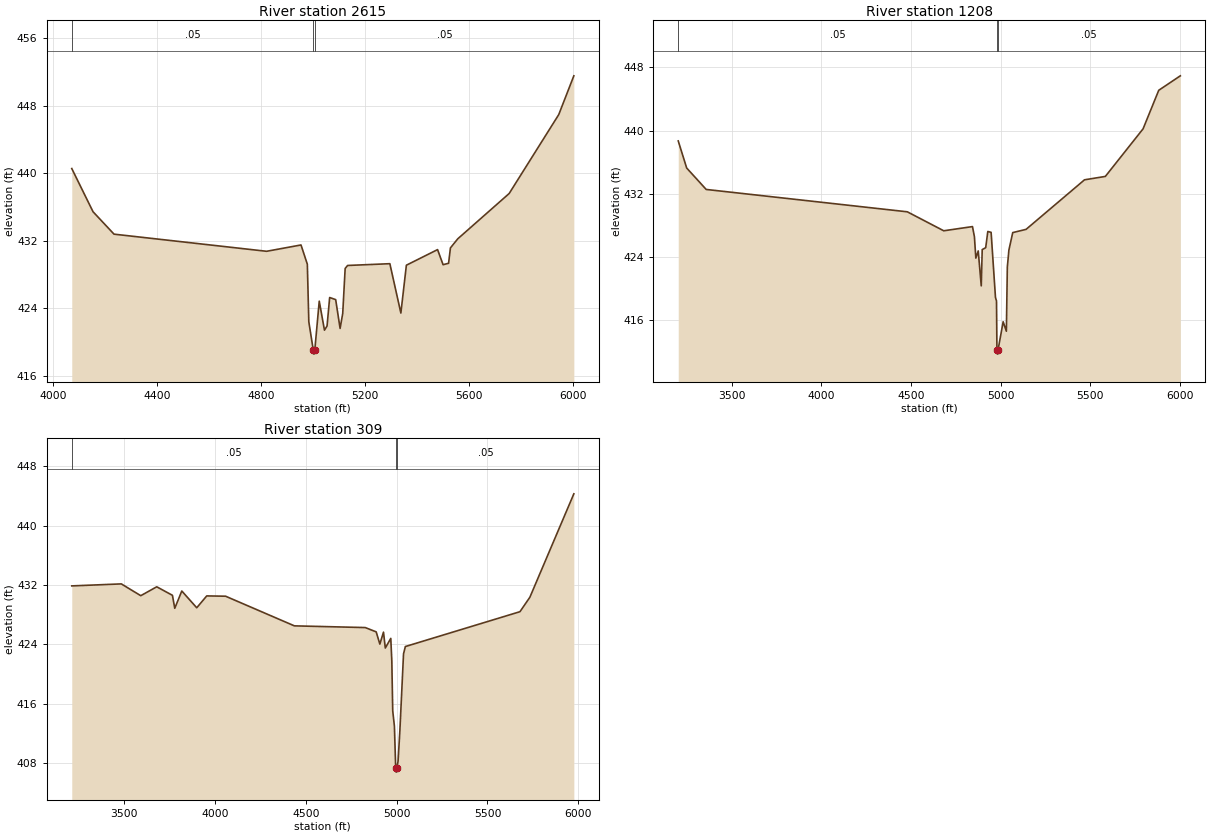
Type RM Length L Ch R = 1,2615,1407,1407,1407
BEGIN DESCRIPTION:
UNT008 IN CCTC 3.0
END DESCRIPTION:
XS GIS Cut Line= 4
      3497431.07     10618144.58      3498139.38     10618582.06
      3498363.34     10618561.23      3498983.16     10617941.42
#Sta/Elev= 30
  4071.0  440.56  4152.9  435.44  4233.8  432.78  4821.5  430.75  4954.0  431.50
  4978.4  429.22  4984.1  422.40  5001.2  419.06  5003.9  418.56  5007.2  419.06
  5024.3  424.84  5044.4  421.40  5054.4  421.90  5064.4  425.27  5087.6  425.02
  5104.6  421.61  5114.7  423.37  5124.1  428.71  5133.6  429.07  5296.3  429.28
  5338.7  423.43  5359.9  429.10  5480.1  430.95  5501.3  429.16  5522.5  429.33
  5529.6  431.15  5557.9  432.23  5755.9  437.60  5946.8  446.95  6005.0  451.55
#Mann=3,-1,0
  4071.0    0.05       0  5001.2    0.03       0  5007.2    0.05       0
Bank Sta=5001.2,5007.2
Exp/Cntr=0.3,0.1

Type RM Length L Ch R = 1,1208,899,899,899
BEGIN DESCRIPTION:
UNT008 IN CCTC 2.0
END DESCRIPTION:
XS GIS Cut Line= 4
      3497451.91     10618170.62      3498493.55     10618936.23
      3499222.72     10618660.19      3499368.55     10617946.65
#Sta/Elev= 30
  3200.9  438.70  3248.1  435.27  3356.9  432.56  4478.8  429.73  4681.9  427.33
  4842.3  427.86  4853.0  426.59  4861.0  423.87  4874.4  424.78  4891.2  420.36
  4896.6  424.95  4916.0  425.19  4927.8  427.24  4946.2  427.13  4970.6  418.88
  4976.3  418.44  4978.7  412.22  4981.4  411.72  4984.7  412.22  5013.4  415.82
  5031.3  414.62  5036.7  422.73  5045.4  424.88  5066.8  427.10  5141.3  427.51
  5467.2  433.78  5583.5  434.21  5793.9  440.23  5881.3  445.11  6001.6  446.94
#Mann=3,-1,0
  3200.9    0.05       0  4978.7   0.035       0  4984.7    0.05       0
Bank Sta=4978.7,4984.7
Exp/Cntr=0.3,0.1

Type RM Length L Ch R = 1,309,0,0,0
BEGIN DESCRIPTION:
UNT008 IN CCTC 1.0
END DESCRIPTION:
XS GIS Cut Line= 4
      3497514.41     10618592.49      3498910.22     10619233.11
      3499238.34     10619207.06      3499561.25     10618368.55
#Sta/Elev= 30
  3211.9  431.89  3484.6  432.16  3591.7  430.57  3679.7  431.77  3766.0  430.62
  3778.8  428.87  3817.5  431.20  3899.8  428.94  3954.8  430.54  4058.4  430.50
  4437.2  426.50  4827.3  426.27  4887.5  425.69  4907.6  424.04  4927.7  425.65
  4937.7  423.51  4967.8  424.81  4973.5  421.77  4978.5  415.05  4987.8  412.96
  4994.9  407.27  4997.6  406.77  5000.9  407.27  5007.9  408.25  5017.9  412.37
  5038.0  422.73  5048.0  423.71  5678.8  428.41  5733.4  430.36  5975.4  444.31
#Mann=3,-1,0
  3211.9    0.05       0  4994.9   0.035       0  5000.9    0.05       0
Bank Sta=4994.9,5000.9
Exp/Cntr=0.3,0.1

Chan Stop Cuts=-1