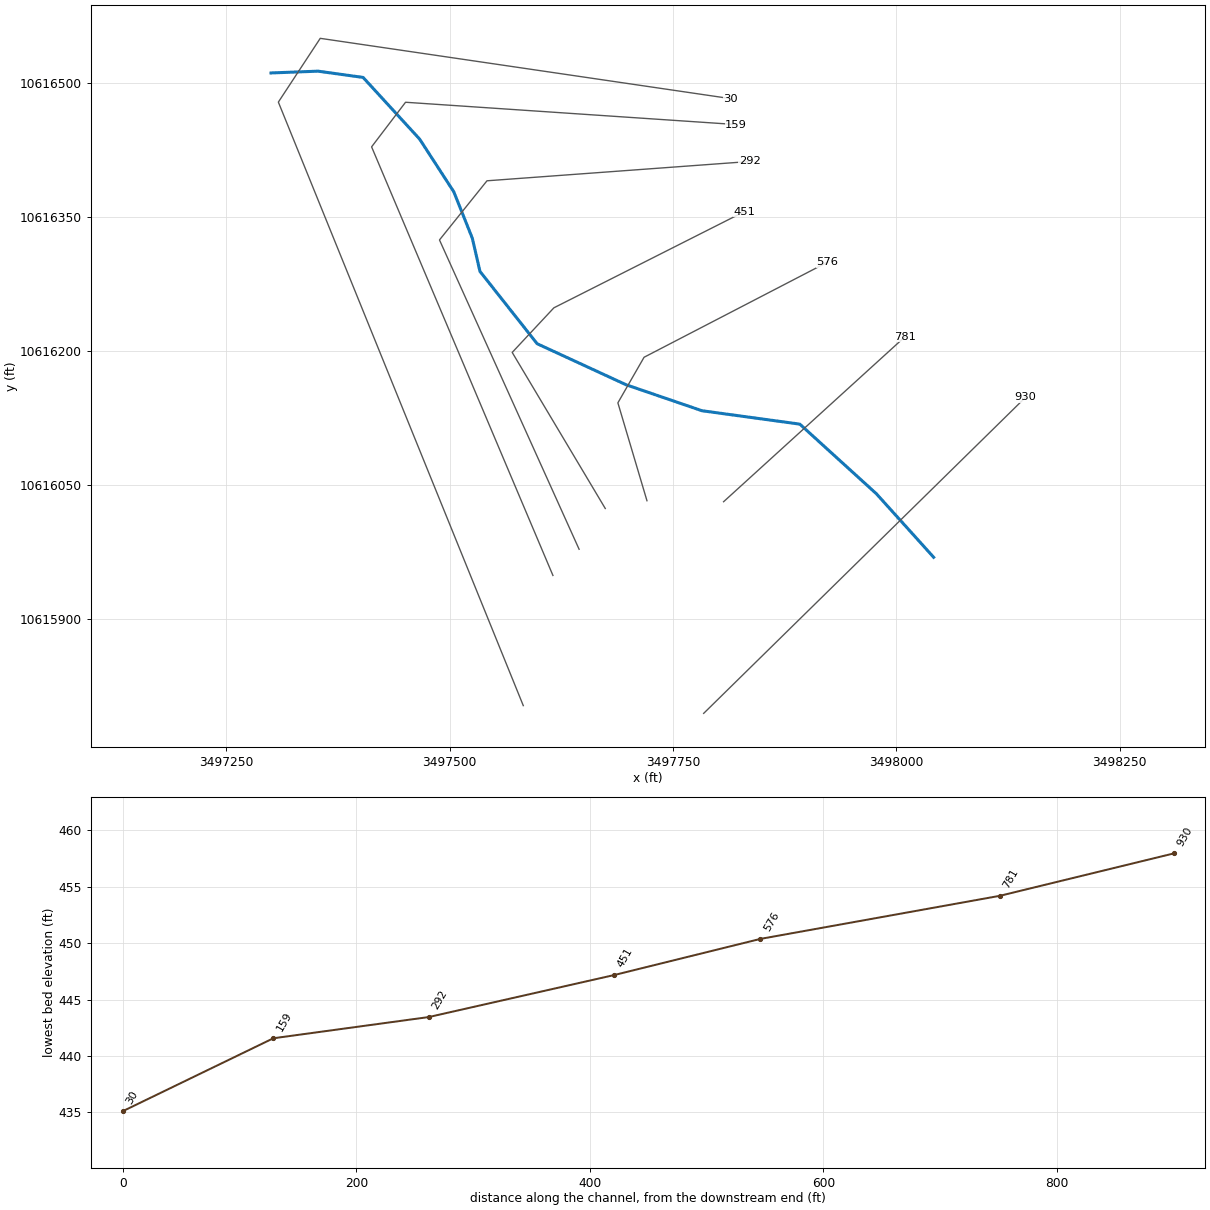
--- UNT010 IN CCTC.prj (project) ---

Proj Title=UNT010 IN CCTC Base Level Engineering
Current Plan=p01
Default Exp/Contr=0.3,0.1
English Units
Geom File=g01
Flow File=f01
Plan File=p01
Y Axis Title=Elevation
X Axis Title(PF)=Main Channel Distance
X Axis Title(XS)=Station
BEGIN DESCRIPTION:
UNT010 IN CCTC
END DESCRIPTION:
DSS Export Rating Curves= 0
DSS Export Rating Curve Sorted= 0
DSS Export Volume Flow Curves= 0
DXF OffsetX= 0
DXF OffsetY= 0
DXF ScaleX= 1
DXF ScaleY= 10

--- UNT010 IN CCTC.p01 (plan) ---

Plan Title=Multiple Run
Short Identifier=Multiple
Geom File=g01
Flow File=f01
Subcritical Flow
K Sum by GR= 0
Std Step Tol= 0.01
Critical Tol= 0.01
Num of Std Step Trials= 20
Max Error Tol= 0.3
Flow Tol Ratio= 0.001
Split Flow NTrial= 30
Split Flow Tol= 0.02
Split Flow Ratio= 0.02
Log Output Level= 0
Friction Slope Method= 1
Unsteady Friction Slope Method= 2
Unsteady Bridges Friction Slope Method= 1
Parabolic Critical Depth
Global Vel Dist=  1 , 1 , 1
Global Log Level= 0
CheckData=True
Encroach Param= -1, 0, 0, 0
BEGIN DESCRIPTION:
Multiple Run
END DESCRIPTION:

--- UNT010 IN CCTC.f01 (steady flow) ---

Flow Title=Multiple
Program Version=4.10
Number of Profiles= 7
Profile Names=10-year,25-year,50-year,1pct_min,100-year,1pct_plu,500-year
River Rch & RM=UNT010 IN CCTC,Reach-1         ,930
      83      93     100      80     108     146     122
Boundary for River Rch & Prof#=UNT010 IN CCTC,Reach-1         , 1
Up Type= 0
Dn Type= 3
Dn Slope=0.035
Boundary for River Rch & Prof#=UNT010 IN CCTC,Reach-1         , 2
Up Type= 0
Dn Type= 3
Dn Slope=0.035
Boundary for River Rch & Prof#=UNT010 IN CCTC,Reach-1         , 3
Up Type= 0
Dn Type= 3
Dn Slope=0.035
Boundary for River Rch & Prof#=UNT010 IN CCTC,Reach-1         , 4
Up Type= 0
Dn Type= 3
Dn Slope=0.035
Boundary for River Rch & Prof#=UNT010 IN CCTC,Reach-1         , 5
Up Type= 0
Dn Type= 3
Dn Slope=0.035
Boundary for River Rch & Prof#=UNT010 IN CCTC,Reach-1         , 6
Up Type= 0
Dn Type= 3
Dn Slope=0.035
Boundary for River Rch & Prof#=UNT010 IN CCTC,Reach-1         , 7
Up Type= 0
Dn Type= 3
Dn Slope=0.035
DSS Import GetInterval= 0
DSS Import GetPeak= 0
DSS Import FillOption= 0

--- UNT010 IN CCTC.g01 (geometry) ---

Geom Title=Existing Conditions
Program Version=4.10

River Reach=UNT010 IN CCTC  ,Reach-1
Reach XY= 13
      3498041.75       10615969.      3497977.75       10616040.
        3497892.       10616118.       3497782.5       10616133.
      3497697.75       10616162.        3497598.       10616208.
        3497534.       10616289.       3497525.5       10616326.
      3497504.75       10616378.       3497466.5       10616437.
      3497403.25       10616506.      3497352.75       10616513.
      3497300.25       10616511.

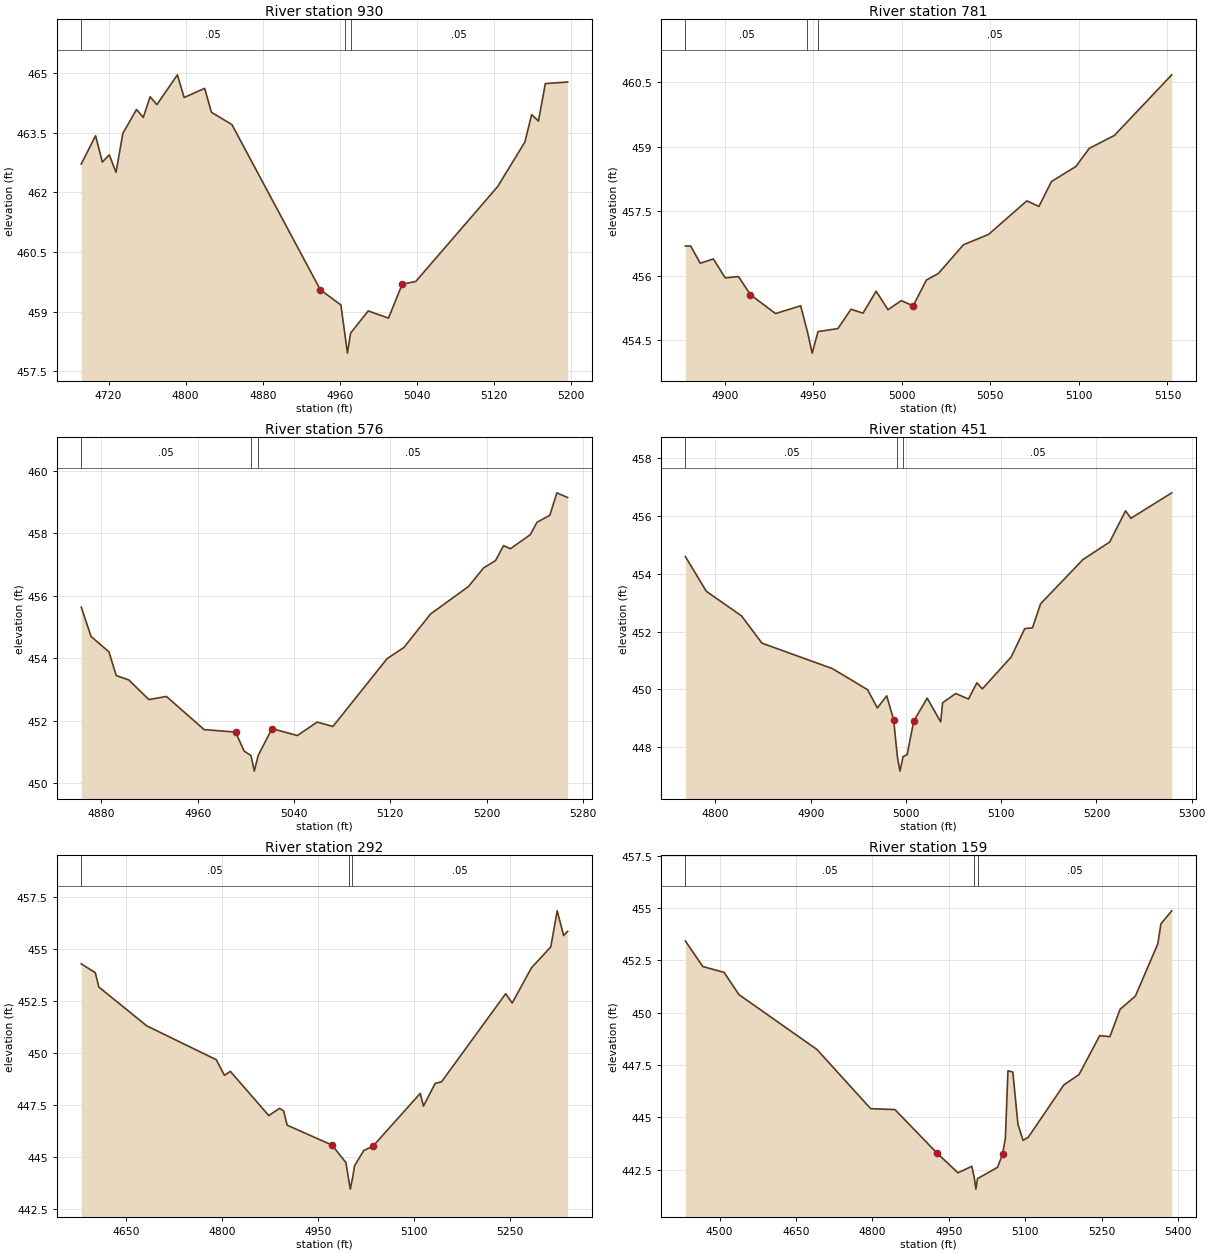
Type RM Length L Ch R = 1 ,930     ,149,149,149
BEGIN DESCRIPTION:
UNT010 IN CCTC 2.0
END DESCRIPTION:
XS GIS Cut Line= 2
      3497784.38     10615794.33      3498144.56     10616148.01
#Sta/Elev= 30
  4691.6  462.71  4706.5  463.42  4713.5  462.76  4720.7  462.94  4727.7   462.5
  4734.8  463.48    4749  464.08    4756  463.88  4763.1   464.4  4770.1   464.2
  4791.4  464.95  4798.4  464.38  4819.7  464.61  4826.7  464.01    4848   463.7
  4939.8  459.55  4961.1  459.17  4965.1  458.46  4967.9  457.96  4971.1  458.46
  4989.4  459.02  5010.5  458.84  5024.7  459.69  5038.8  459.76  5123.7  462.14
    5152  463.26  5159.1  463.95  5166.1  463.79  5173.3  464.73  5196.4  464.77
#Mann= 3 ,-1 , 0
  4691.6     .05       0  4965.1     .03       0  4971.1     .05       0
Bank Sta=4939.8,5024.7
XS Rating Curve= 0 ,0
Exp/Cntr=0.3,0.1

Type RM Length L Ch R = 1 ,781     ,205,205,205
BEGIN DESCRIPTION:
Mapping XS 5da35cb9
END DESCRIPTION:
XS GIS Cut Line= 2
      3497806.66     10616031.17       3498009.8     10616215.94
#Sta/Elev= 30
  4877.8  456.69  4880.8  456.69  4886.2  456.29  4893.6  456.39  4900.3  455.95
  4907.8  455.98  4914.5  455.56  4928.7  455.12  4942.9   455.3  4946.7   454.7
  4949.4   454.2  4952.7   454.7  4963.9  454.77  4971.3  455.22  4978.1  455.13
  4985.5  455.64  4992.2  455.21  4999.7  455.42  5006.4   455.3  5013.9   455.9
  5020.6  456.05  5034.8  456.72    5049  456.96  5070.6  457.74  5077.4  457.61
  5084.5  458.19  5098.3  458.54  5105.8  458.96    5120  459.26  5152.4  460.67
#Mann= 3 ,-1 , 0
  4877.8     .05       0  4946.7    .035       0  4952.7     .05       0
Bank Sta=4914.5,5006.4
XS Rating Curve= 0 ,0
Exp/Cntr=0.3,0.1

Type RM Length L Ch R = 1 ,576     ,125,125,125
BEGIN DESCRIPTION:
Mapping XS 791049a3
END DESCRIPTION:
XS GIS Cut Line= 4
      3497720.92     10616032.29      3497688.38     10616141.84
      3497717.68     10616192.84      3497922.76     10616299.17
#Sta/Elev= 30
  4863.2  455.63  4871.4  454.69  4886.2   454.2  4892.3  453.44  4902.7   453.3
  4919.4  452.67    4934  452.77  4965.3  451.71  4991.4  451.63  4998.6  451.02
  5004.2  450.88    5007  450.38  5010.2  450.88  5021.7  451.74  5042.8  451.52
  5059.2  451.95  5072.3  451.81  5117.3  453.98  5131.3  454.34  5153.4  455.41
  5184.9  456.29  5197.6  456.89  5207.4  457.12  5214.1   457.6  5219.8   457.5
  5236.3  457.95  5241.9  458.35  5252.5  458.57  5258.4  459.29  5267.3  459.14
#Mann= 3 ,-1 , 0
  4863.2     .05       0  5004.2     .03       0  5010.2     .05       0
Bank Sta=4991.4,5021.7
XS Rating Curve= 0 ,0
Exp/Cntr=0.3,0.1

Type RM Length L Ch R = 1 ,451     ,159,159,159
BEGIN DESCRIPTION:
Mapping XS dc247de7
END DESCRIPTION:
XS GIS Cut Line= 4
      3497674.26      10616023.6      3497570.11     10616198.26
      3497616.77     10616248.18      3497830.12     10616355.93
#Sta/Elev= 30
  4768.4  454.59  4790.4  453.39  4827.4  452.54  4848.8   451.6  4922.8  450.72
  4959.8  449.99    4970  449.36  4979.8  449.78  4987.1  448.95    4991  447.68
  4993.7  447.18    4997  447.68  5001.3  447.75  5008.1   448.9  5022.3   449.7
  5036.5  448.88  5038.5  449.54  5052.3  449.86  5065.7  449.67  5074.5  450.23
  5080.2  450.02  5110.5  451.12  5124.7   452.1  5132.9  452.13  5141.4  452.96
    5186  454.49  5213.9  455.09  5230.6  456.17  5236.2  455.91  5279.1  456.79
#Mann= 3 ,-1 , 0
  4768.4     .05       0    4991     .03       0    4997     .05       0
Bank Sta=4987.1,5008.1
XS Rating Curve= 0 ,0
Exp/Cntr=0.3,0.1

Type RM Length L Ch R = 1 ,292     ,133,133,133
BEGIN DESCRIPTION:
Mapping XS d8acf295
END DESCRIPTION:
XS GIS Cut Line= 4
      3497644.98     10615977.99      3497488.73     10616324.13
       3497541.9     10616390.32      3497835.83     10616411.93
#Sta/Elev= 30
  4580.2   454.3  4602.2  453.87  4607.7  453.18  4682.6  451.31  4791.1  449.68
  4803.7  448.93    4813  449.12  4873.1  446.99  4889.8  447.34  4896.2  447.22
  4901.7  446.53  4971.8  445.57  4993.4  444.73  4997.6  443.95  5000.3  443.45
  5003.6  443.95    5007  444.58  5021.4  445.31  5035.8  445.52  5109.5  448.06
  5114.5  447.45  5132.8  448.54  5142.8  448.62  5242.9  452.86  5253.1  452.41
  5283.2  454.11  5313.3  455.11  5323.3  456.85  5333.4  455.66  5339.6  455.86
#Mann= 3 ,-1 , 0
  4580.2     .05       0  4997.6     .03       0  5003.6     .05       0
Bank Sta=4971.8,5035.8
XS Rating Curve= 0 ,0
Exp/Cntr=0.3,0.1

Type RM Length L Ch R = 1 ,159     ,129,129,129
BEGIN DESCRIPTION:
Mapping XS 0ef172e3
END DESCRIPTION:
XS GIS Cut Line= 4
      3497615.69     10615948.67      3497412.77      10616428.3
      3497450.75     10616478.21      3497820.71     10616453.26
#Sta/Elev= 30
    4433  453.42  4467.2   452.2    4509  451.92  4538.1  450.86  4691.1  448.24
  4796.7  445.41  4844.1  445.37    4926  443.31  4967.9  442.35    4995  442.66
  5000.2  442.07    5003  441.57  5006.2  442.07  5045.4  442.61  5055.4  443.24
  5060.9     444  5065.9  447.22  5075.5  447.16  5085.5  444.67  5095.5   443.9
  5105.6  444.04  5175.7  446.55  5205.4  447.04  5245.9   448.9  5265.9  448.85
    5286  450.16    5316  450.79  5359.9  453.28  5366.1  454.24  5387.3  454.86
#Mann= 3 ,-1 , 0
    4433     .05       0  5000.2     .03       0  5006.2     .05       0
Bank Sta=4926,5055.4
XS Rating Curve= 0 ,0
Exp/Cntr=0.3,0.1

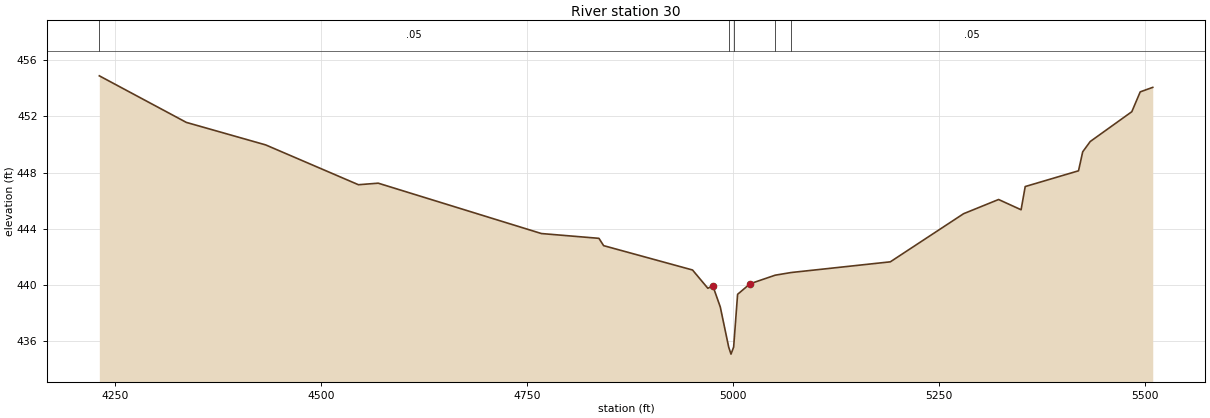
Type RM Length L Ch R = 1 ,30      ,0,0,0
BEGIN DESCRIPTION:
UNT010 IN CCTC 1.0
END DESCRIPTION:
XS GIS Cut Line= 4
      3497582.52     10615802.99      3497308.43     10616478.38
      3497355.31     10616549.74      3497814.71     10616482.24
#Sta/Elev= 30
  4230.7  454.88  4336.3  451.57  4432.6  449.97  4545.2  447.14  4569.2  447.25
  4767.3  443.67  4837.1  443.33  4842.8  442.81  4950.7  441.08  4969.3  439.78
  4975.3  439.96  4984.4  438.45  4994.6   435.6  4997.4   435.1  5000.6   435.6
  5005.4  439.35  5020.5   440.1    5051  440.71  5070.4   440.9  5190.8  441.66
  5279.7  445.08  5322.2  446.09  5349.5  445.36  5354.5  447.01  5419.2  448.13
  5424.3  449.48  5433.4  450.21  5483.9  452.33  5494.1  453.74  5509.3  454.06
#Mann= 5 ,-1 , 0
  4230.7     .05       0  4994.6     .03       0  5000.6     .05       0
    5051     .08       0  5070.4     .05       0
Bank Sta=4975.3,5020.5
XS Rating Curve= 0 ,0
Exp/Cntr=0.3,0.1

Chan Stop Cuts=-1
Use User Specified Reach Order=0
Composite Channel Slope=5