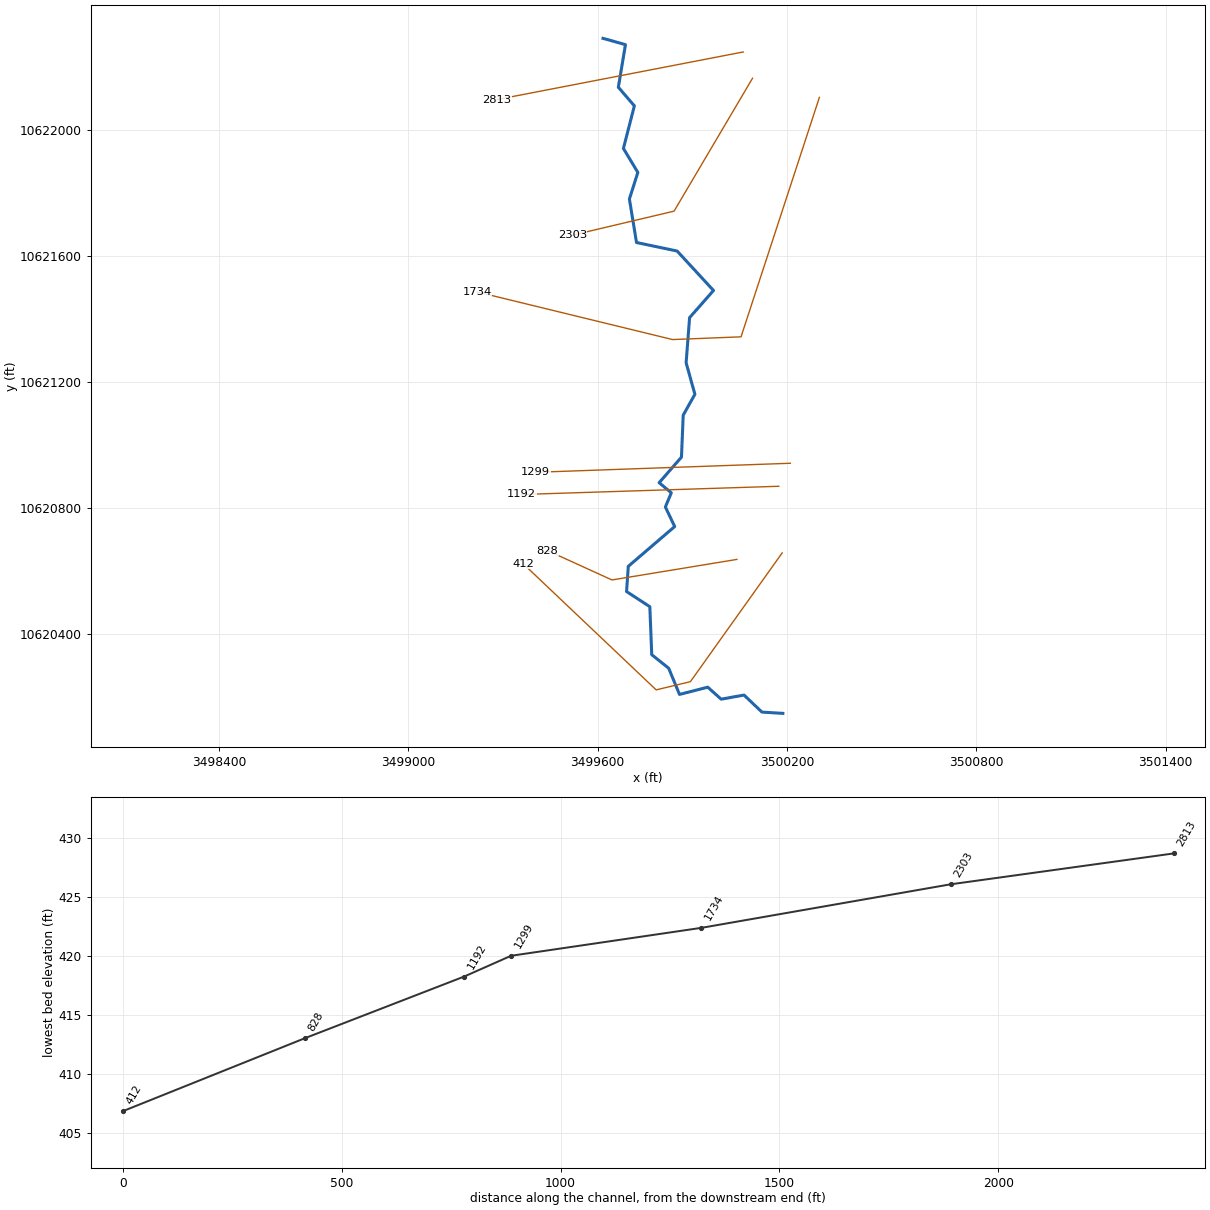
--- UNT012 IN CCTC.prj (project) ---

Proj Title=UNT012 IN CCTC Base Level Engineering
Current Plan=p01
Default Exp/Contr=0.3,0.1
English Units
Geom File=g01
Flow File=f01
Plan File=p01
Y Axis Title=Elevation
X Axis Title(PF)=Main Channel Distance
X Axis Title(XS)=Station
BEGIN DESCRIPTION:
UNT012 IN CCTC
END DESCRIPTION:
DSS Export Rating Curves= 0
DSS Export Rating Curve Sorted= 0
DSS Export Volume Flow Curves= 0
DXF OffsetX= 0
DXF OffsetY= 0
DXF ScaleX= 1
DXF ScaleY= 10

--- UNT012 IN CCTC.p01 (plan) ---

Plan Title=Multiple Run
Short Identifier=Multiple
Geom File=g01
Flow File=f01
Subcritical Flow
K Sum by GR= 0
Std Step Tol= 0.01
Critical Tol= 0.01
Num of Std Step Trials= 20
Max Error Tol= 0.3
Flow Tol Ratio= 0.001
Split Flow NTrial= 30
Split Flow Tol= 0.02
Split Flow Ratio= 0.02
Log Output Level= 0
Friction Slope Method= 1
Unsteady Friction Slope Method= 2
Unsteady Bridges Friction Slope Method= 1
Parabolic Critical Depth
Global Vel Dist=  1 , 1 , 1
Global Log Level= 0
CheckData=True
Encroach Param= -1, 0, 0, 0
BEGIN DESCRIPTION:
Multiple Run
END DESCRIPTION:

--- UNT012 IN CCTC.f01 (steady flow) ---

Flow Title=Multiple
Number of Profiles=7
Profile Names=10-year,25-year,50-year,1pct_min,100-year,1pct_plu,500-year
River Rch & RM= UNT012 IN CCTC,Reach-1,2813
     520     674     793     683     924    1249    1248
Boundary for River Rch & Prof#=UNT012 IN CCTC,Reach-1,1
Up Type=0
Dn Type=3
Dn Slope=0.005
Boundary for River Rch & Prof#=UNT012 IN CCTC,Reach-1,2
Up Type=0
Dn Type=3
Dn Slope=0.005
Boundary for River Rch & Prof#=UNT012 IN CCTC,Reach-1,3
Up Type=0
Dn Type=3
Dn Slope=0.005
Boundary for River Rch & Prof#=UNT012 IN CCTC,Reach-1,4
Up Type=0
Dn Type=3
Dn Slope=0.005
Boundary for River Rch & Prof#=UNT012 IN CCTC,Reach-1,5
Up Type=0
Dn Type=3
Dn Slope=0.005
Boundary for River Rch & Prof#=UNT012 IN CCTC,Reach-1,6
Up Type=0
Dn Type=3
Dn Slope=0.005
Boundary for River Rch & Prof#=UNT012 IN CCTC,Reach-1,7
Up Type=0
Dn Type=3
Dn Slope=0.005

--- UNT012 IN CCTC.g01 (geometry) ---

Geom Title=Existing Conditions

River Reach=UNT012 IN CCTC,Reach-1
Reach XY= 30
      3499617.25     10622289.00      3499688.50     10622269.00
      3499666.00     10622134.00      3499716.75     10622075.00
      3499682.00     10621940.00      3499727.75     10621864.00
      3499701.00     10621780.00      3499723.50     10621642.00
      3499852.25     10621615.00      3499967.50     10621490.00
      3499891.75     10621404.00      3499880.75     10621261.00
      3499908.50     10621161.00      3499871.50     10621095.00
      3499866.00     10620962.00      3499795.25     10620881.00
      3499833.75     10620849.00      3499815.00     10620804.00
      3499844.50     10620742.00      3499697.50     10620616.00
      3499692.00     10620536.00      3499765.75     10620488.00
      3499771.75     10620336.00      3499825.50     10620293.00
      3499859.75     10620210.00      3499949.25     10620233.00
      3499991.75     10620195.00      3500064.25     10620208.00
      3500121.00     10620154.00      3500187.25     10620150.00

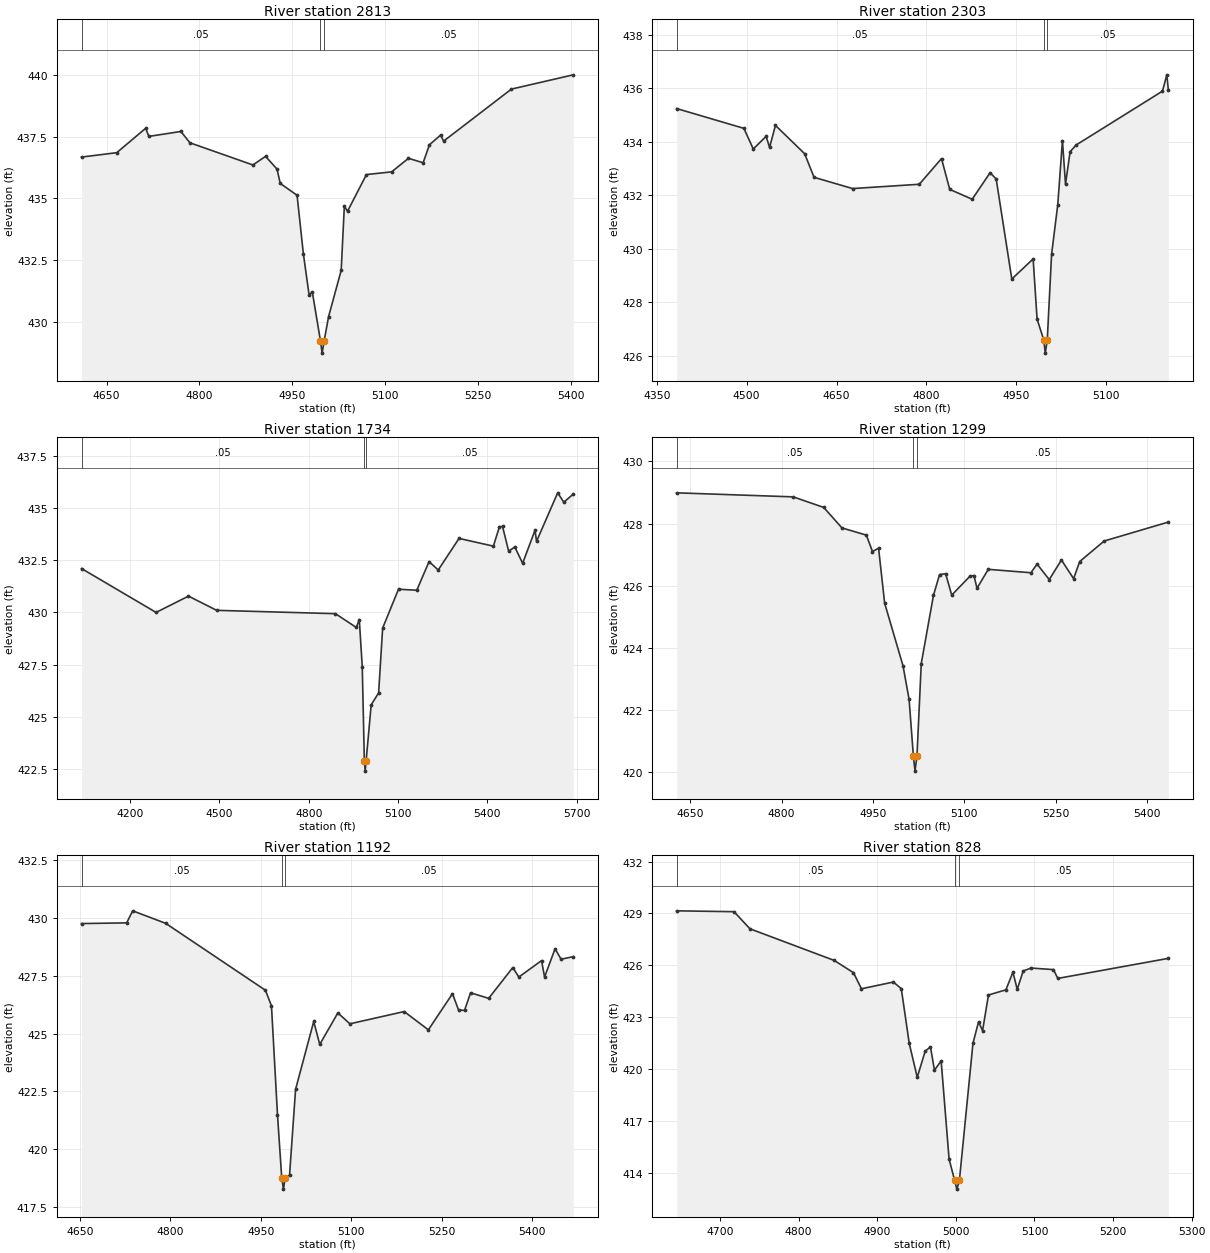
Type RM Length L Ch R = 1,2813,510,510,510
BEGIN DESCRIPTION:
UNT012 IN CCTC 1.0
END DESCRIPTION:
XS GIS Cut Line= 2
      3500061.60     10622245.81      3499281.44     10622094.98
#Sta/Elev= 30
  4609.6  436.68  4666.6  436.86  4713.3  437.85  4718.4  437.52  4770.2  437.72
  4784.8  437.26  4886.6  436.36  4907.0  436.71  4925.6  436.19  4930.7  435.61
  4957.9  435.13  4968.1  432.75  4977.4  431.07  4982.5  431.21  4995.7  429.22
  4998.4  428.72  5001.7  429.22  5008.8  430.20  5029.2  432.08  5034.3  434.69
  5039.4  434.48  5070.0  435.97  5110.7  436.08  5137.9  436.63  5161.6  436.45
  5171.8  437.18  5189.7  437.57  5194.8  437.33  5304.2  439.44  5404.2  440.02
#Mann=3,-1,0
  4609.6    0.05       0  4995.7   0.035       0  5001.7    0.05       0
Bank Sta=4995.7,5001.7
Exp/Cntr=0.3,0.1

Type RM Length L Ch R = 1,2303,569,569,569
BEGIN DESCRIPTION:
Mapping XS ed71035f
END DESCRIPTION:
XS GIS Cut Line= 3
      3500091.18     10622162.61      3499842.59     10621741.42
      3499519.97     10621665.10
#Sta/Elev= 30
  4383.1  435.24  4495.3  434.50  4511.0  433.73  4532.4  434.20  4538.2  433.79
  4548.0  434.61  4596.8  433.55  4612.4  432.67  4676.7  432.25  4788.0  432.41
  4825.1  433.37  4838.8  432.22  4876.3  431.85  4906.1  432.84  4916.3  432.61
  4942.4  428.87  4978.0  429.62  4984.6  427.37  4995.6  426.60  4998.3  426.10
  5001.6  426.60  5008.8  429.80  5019.1  431.65  5026.9  434.04  5032.0  432.41
  5039.7  433.63  5049.9  433.88  5193.8  435.89  5201.1  436.50  5203.7  435.92
#Mann=3,-1,0
  4383.1    0.05       0  4995.6    0.03       0  5001.6    0.05       0
Bank Sta=4995.6,5001.6
Exp/Cntr=0.3,0.1

Type RM Length L Ch R = 1,1734,435,435,435
BEGIN DESCRIPTION:
Mapping XS 2d257252
END DESCRIPTION:
XS GIS Cut Line= 4
      3500303.01     10622101.87      3500054.74     10621343.19
      3499837.73     10621334.51      3499218.70     10621485.37
#Sta/Elev= 30
  4036.4  432.10  4287.0  430.00  4395.9  430.78  4490.6  430.10  4889.8  429.94
  4959.9  429.28  4969.9  429.66  4979.9  427.40  4986.9  422.91  4989.7  422.41
  4992.9  422.91  5009.9  425.58  5034.9  426.15  5048.4  429.25  5101.7  431.11
  5163.1  431.06  5204.3  432.43  5235.2  432.03  5305.1  433.54  5420.5  433.17
  5441.0  434.10  5451.3  434.11  5471.9  432.93  5492.5  433.13  5518.8  432.35
  5560.5  433.93  5565.6  433.40  5636.6  435.72  5657.2  435.27  5689.0  435.66
#Mann=3,-1,0
  4036.4    0.05       0  4986.9   0.035       0  4992.9    0.05       0
Bank Sta=4986.9,4992.9
Exp/Cntr=0.3,0.1

Type RM Length L Ch R = 1,1299,107,107,107
BEGIN DESCRIPTION:
Mapping XS fb2a08cc
END DESCRIPTION:
XS GIS Cut Line= 2
      3500210.93     10620942.55      3499404.14     10620913.92
#Sta/Elev= 30
  4627.6  428.99  4819.0  428.86  4869.1  428.52  4899.1  427.86  4939.1  427.63
  4949.1  427.10  4959.1  427.21  4969.1  425.44  4999.2  423.43  5009.2  422.35
  5016.2  420.54  5018.9  420.04  5022.2  420.54  5029.2  423.50  5049.2  425.69
  5059.2  426.36  5069.2  426.39  5079.2  425.70  5109.2  426.31  5115.7  426.33
  5120.7  425.92  5139.2  426.53  5209.3  426.42  5219.3  426.70  5239.3  426.20
  5259.3  426.83  5279.3  426.23  5289.3  426.78  5329.4  427.44  5434.9  428.05
#Mann=3,-1,0
  4627.6    0.05       0  5016.2    0.04       0  5022.2    0.05       0
Bank Sta=5016.2,5022.2
Exp/Cntr=0.3,0.1

Type RM Length L Ch R = 1,1192,364,364,364
BEGIN DESCRIPTION:
Mapping XS 9e3031a0
END DESCRIPTION:
XS GIS Cut Line= 2
      3500174.47     10620869.63      3499359.39     10620843.59
#Sta/Elev= 30
  4652.5  429.75  4727.4  429.78  4737.4  430.30  4792.1  429.76  4957.5  426.87
  4967.5  426.20  4977.5  421.49  4984.5  418.78  4987.3  418.28  4990.5  418.78
  4997.5  418.88  5007.5  422.59  5037.6  425.52  5047.6  424.53  5077.6  425.89
  5097.6  425.42  5187.6  425.95  5227.7  425.16  5267.7  426.72  5277.7  426.02
  5287.7  426.00  5297.7  426.76  5327.7  426.52  5367.7  427.85  5377.7  427.44
  5415.4  428.15  5420.4  427.44  5437.8  428.66  5447.8  428.21  5468.0  428.32
#Mann=3,-1,0
  4652.5    0.05       0  4984.5   0.035       0  4990.5    0.05       0
Bank Sta=4984.5,4990.5
Exp/Cntr=0.3,0.1

Type RM Length L Ch R = 1,828,416,416,416
BEGIN DESCRIPTION:
Mapping XS 73ba272d
END DESCRIPTION:
XS GIS Cut Line= 3
      3500041.63     10620637.86      3499645.80     10620572.76
      3499441.55     10620665.84
#Sta/Elev= 30
  4644.8  429.15  4717.8  429.10  4738.1  428.11  4845.3  426.28  4869.8  425.57
  4879.9  424.64  4920.5  425.03  4930.6  424.65  4940.7  421.48  4950.9  419.52
  4961.0  421.03  4967.7  421.28  4972.8  419.93  4981.3  420.47  4991.4  414.79
  4998.5  413.55  5001.3  413.05  5004.5  413.55  5021.8  421.49  5028.9  422.73
  5034.0  422.22  5041.5  424.28  5063.7  424.58  5072.6  425.60  5078.1  424.61
  5085.7  425.67  5095.6  425.84  5124.2  425.75  5129.7  425.24  5270.4  426.40
#Mann=3,-1,0
  4644.8    0.05       0  4998.5   0.035       0  5004.5    0.05       0
Bank Sta=4998.5,5004.5
Exp/Cntr=0.3,0.1

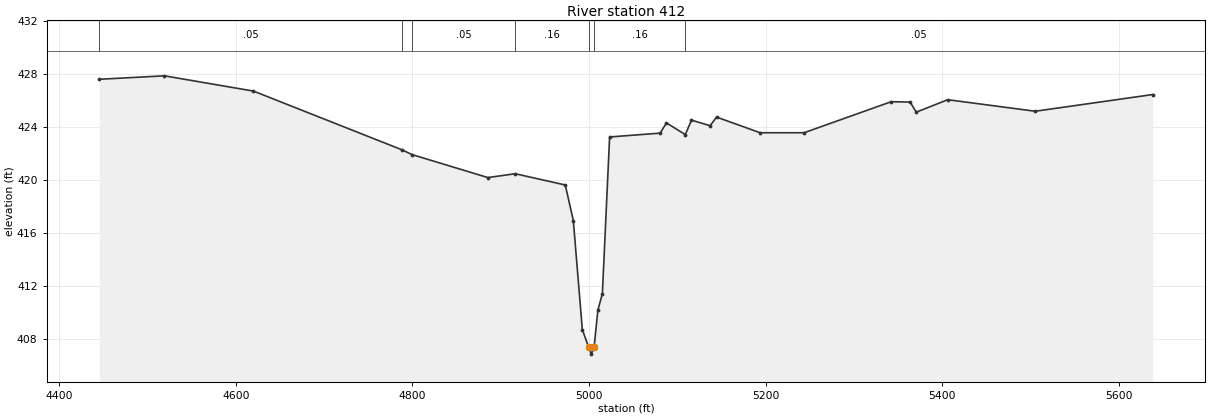
Type RM Length L Ch R = 1,412,0,0,0
BEGIN DESCRIPTION:
UNT012 IN CCTC 2.0
END DESCRIPTION:
XS GIS Cut Line= 4
      3500185.08     10620658.46      3499894.30     10620250.50
      3499785.80     10620224.46      3499364.81     10620623.75
#Sta/Elev= 30
  4445.4  427.58  4519.1  427.84  4619.9  426.69  4787.8  422.27  4799.6  421.90
  4885.4  420.17  4916.3  420.46  4973.0  419.61  4982.1  416.93  4992.3  408.71
  4999.6  407.36  5002.4  406.86  5005.6  407.36  5009.9  410.17  5015.0  411.42
  5023.2  423.23  5080.4  423.52  5087.6  424.29  5108.9  423.41  5115.9  424.50
  5137.0  424.08  5144.3  424.73  5193.6  423.55  5243.4  423.55  5342.1  425.89
  5363.5  425.86  5370.4  425.10  5406.0  426.04  5505.1  425.17  5638.2  426.43
#Mann=7,-1,0
  4445.4    0.05       0  4787.8    0.16       0  4799.6    0.05       0
  4916.3    0.16       0  4999.6    0.07       0  5005.6    0.16       0
  5108.9    0.05       0
Bank Sta=4999.6,5005.6
Exp/Cntr=0.3,0.1

Chan Stop Cuts=-1