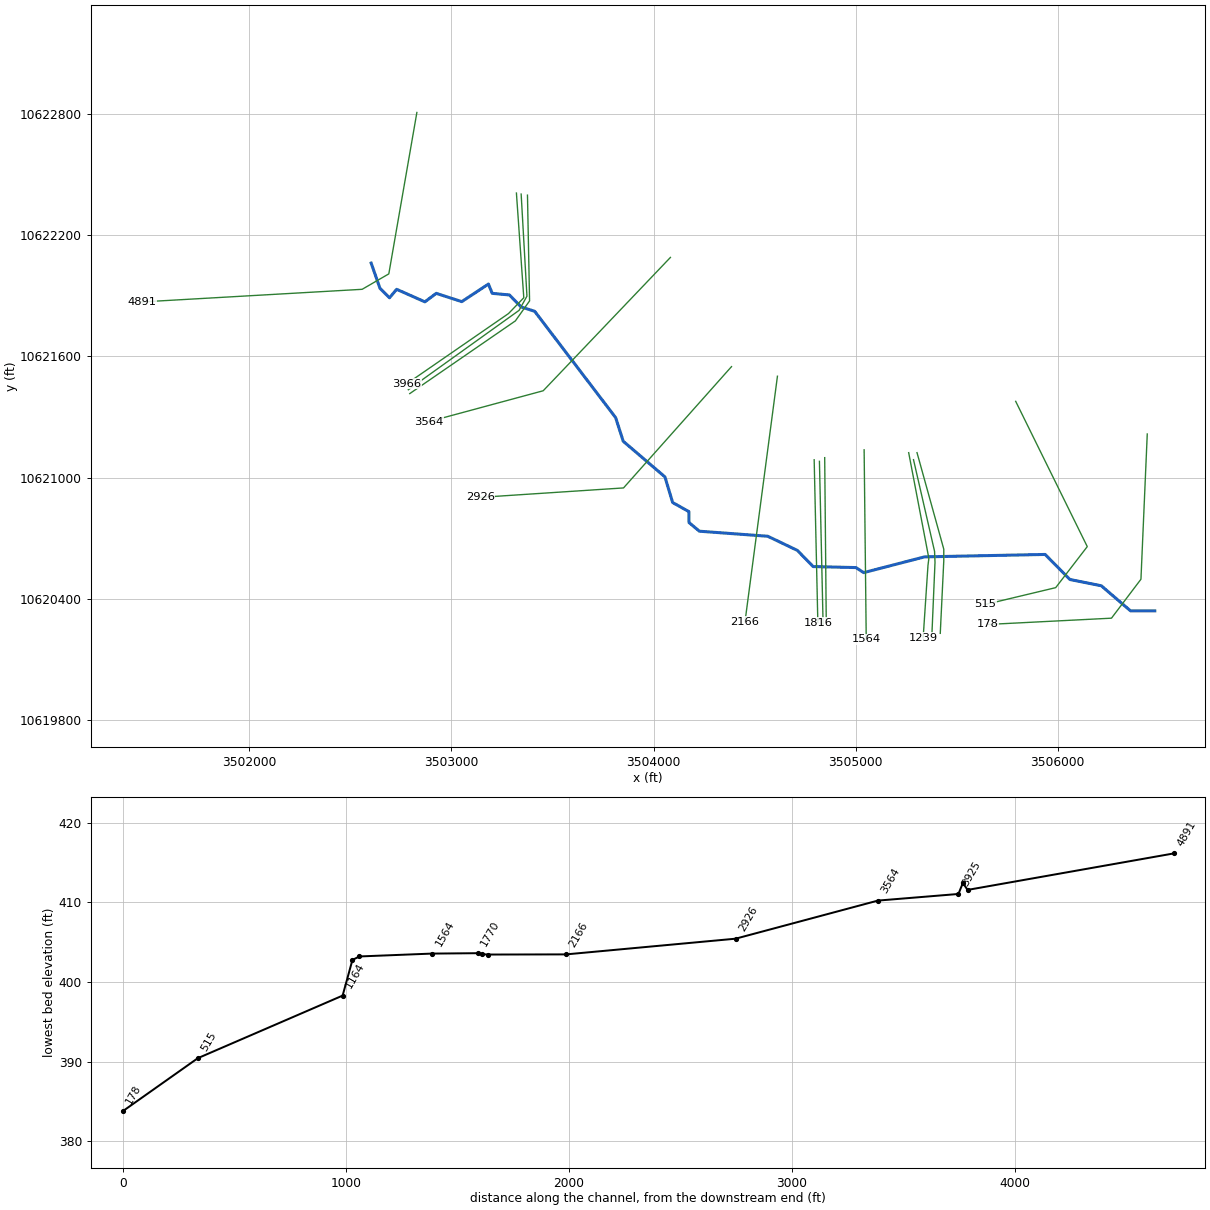
--- UNT013 IN CCTC.prj (project) ---

Proj Title=UNT013 IN CCTC Base Level Engineering
Current Plan=p01
Default Exp/Contr=0.3,0.1
English Units
Geom File=g01
Flow File=f01
Plan File=p01
BEGIN DESCRIPTION:
UNT013 IN CCTC
END DESCRIPTION:

--- UNT013 IN CCTC.p01 (plan) ---

Plan Title=Multiple Run
Short Identifier=Multiple
Geom File=g01
Flow File=f01
Subcritical Flow
K Sum by GR= 0
Std Step Tol= 0.01
Critical Tol= 0.01
Num of Std Step Trials= 20
Max Error Tol= 0.3
Flow Tol Ratio= 0.001
Split Flow NTrial= 30
Split Flow Tol= 0.02
Split Flow Ratio= 0.02
Log Output Level= 0
Friction Slope Method= 1
Unsteady Friction Slope Method= 2
Unsteady Bridges Friction Slope Method= 1
Parabolic Critical Depth
Global Vel Dist=  1 , 1 , 1
Global Log Level= 0
CheckData=True
Encroach Param= -1, 0, 0, 0
BEGIN DESCRIPTION:
Multiple Run
END DESCRIPTION:

--- UNT013 IN CCTC.f01 (steady flow) ---

Flow Title=Multiple
Number of Profiles=7
Profile Names=10-year,25-year,50-year,1pct_min,100-year,1pct_plu,500-year
River Rch & RM= UNT013 IN CCTC,Reach-1,4891
     962    1293    1559    1373    1857    2512    2626
River Rch & RM= UNT013 IN CCTC,Reach-1,178
    1046    1412    1707    1506    2037    2755    2892
Boundary for River Rch & Prof#=UNT013 IN CCTC,Reach-1,1
Up Type=0
Dn Type=3
Dn Slope=0.005
Boundary for River Rch & Prof#=UNT013 IN CCTC,Reach-1,2
Up Type=0
Dn Type=3
Dn Slope=0.005
Boundary for River Rch & Prof#=UNT013 IN CCTC,Reach-1,3
Up Type=0
Dn Type=3
Dn Slope=0.005
Boundary for River Rch & Prof#=UNT013 IN CCTC,Reach-1,4
Up Type=0
Dn Type=3
Dn Slope=0.005
Boundary for River Rch & Prof#=UNT013 IN CCTC,Reach-1,5
Up Type=0
Dn Type=3
Dn Slope=0.005
Boundary for River Rch & Prof#=UNT013 IN CCTC,Reach-1,6
Up Type=0
Dn Type=3
Dn Slope=0.005
Boundary for River Rch & Prof#=UNT013 IN CCTC,Reach-1,7
Up Type=0
Dn Type=3
Dn Slope=0.005

--- UNT013 IN CCTC.g01 (geometry) ---

Geom Title=Existing Conditions

River Reach=UNT013 IN CCTC,Reach-1
Reach XY= 30
      3502602.65     10622061.71      3502646.25     10621937.00
      3502693.50     10621890.00      3502728.75     10621932.00
      3502868.50     10621870.00      3502924.75     10621912.00
      3503051.00     10621871.00      3503183.00     10621958.00
      3503201.75     10621912.00      3503287.00     10621904.00
      3503344.25     10621845.00      3503412.00     10621823.00
      3503812.50     10621297.00      3503850.00     10621180.00
      3504056.25     10621004.00      3504094.50     10620877.00
      3504174.75     10620832.00      3504175.50     10620778.00
      3504226.75     10620735.00      3504565.25     10620710.00
      3504711.75     10620640.00      3504789.75     10620560.00
      3505002.00     10620555.00      3505039.75     10620530.00
      3505341.00     10620608.00      3505937.50     10620620.00
      3506060.50     10620496.00      3506215.75     10620465.00
      3506360.25     10620341.00      3506480.25     10620341.00

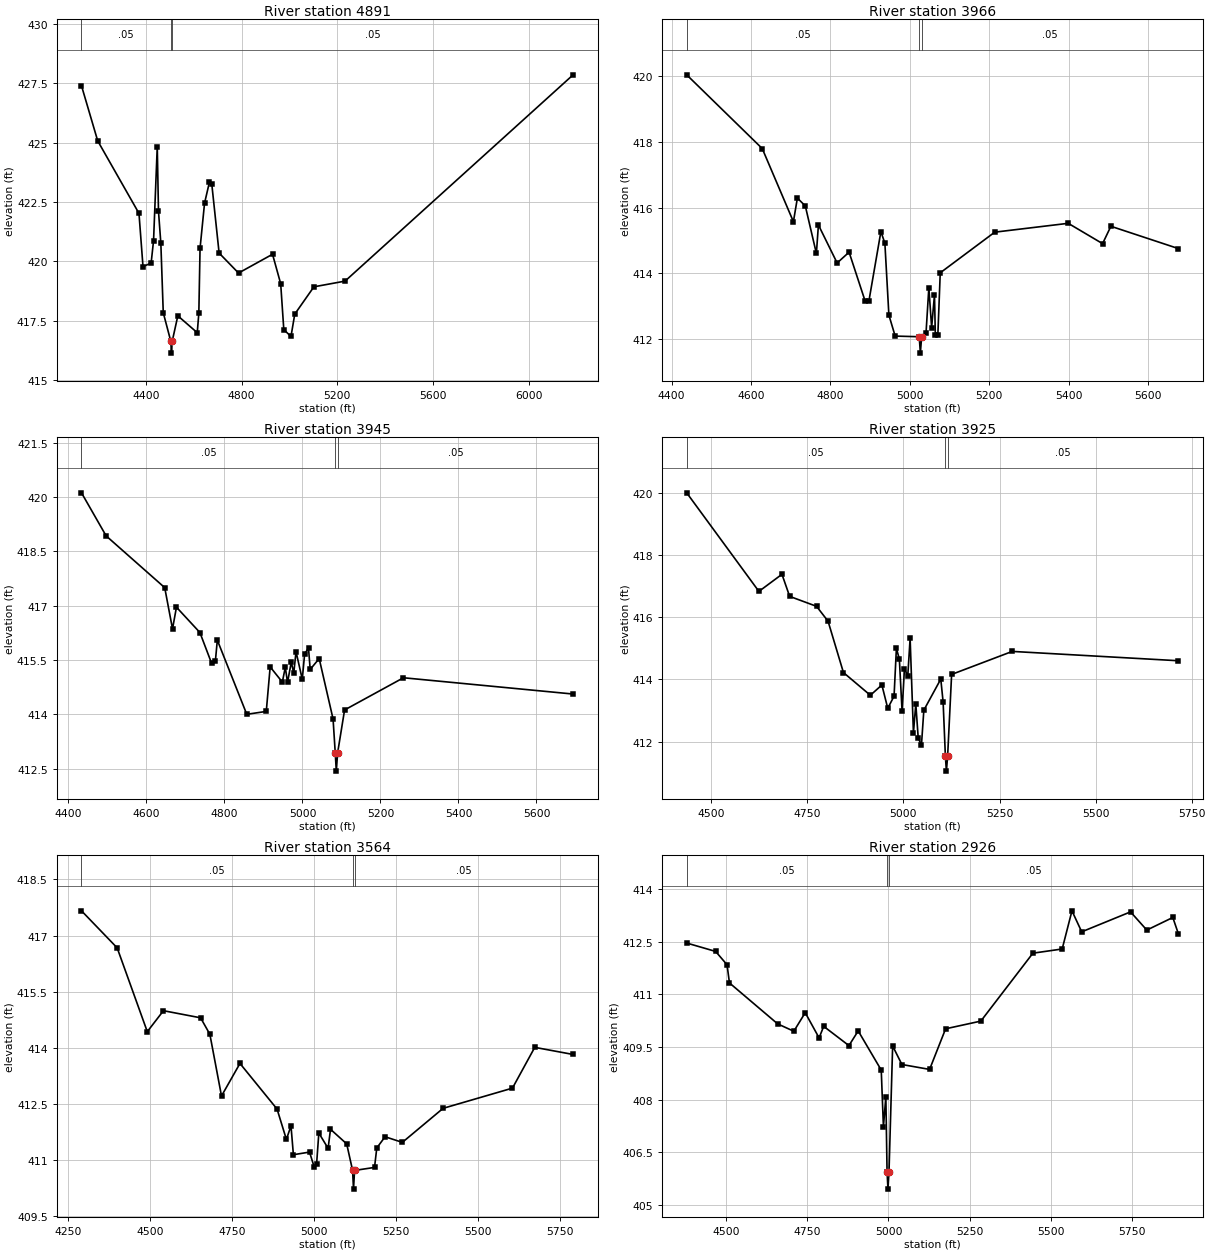
Type RM Length L Ch R = 1,4891,925,925,925
BEGIN DESCRIPTION:
UNT013 IN CCTC 5.0
END DESCRIPTION:
XS GIS Cut Line= 4
      3502828.91     10622806.98      3502690.02     10622008.39
      3502558.08     10621932.00      3501467.80     10621869.50
#Sta/Elev= 30
  4131.1  427.39  4198.9  425.07  4371.4  422.02  4388.2  419.78  4422.2  419.93
  4432.3  420.87  4447.8  424.83  4452.9  422.12  4462.8  420.76  4472.9  417.84
  4504.4  416.64  4507.2  416.14  4510.4  416.64  4533.8  417.71  4615.0  417.00
  4621.6  417.82  4626.7  420.55  4645.5  422.45  4665.8  423.33  4675.9  423.24
  4706.4  420.35  4787.6  419.51  4929.7  420.30  4963.8  419.06  4976.8  417.13
  5006.8  416.84  5022.6  417.78  5102.6  418.93  5232.8  419.17  6186.2  427.85
#Mann=3,-1,0
  4131.1    0.05       0  4504.4   0.035       0  4510.4    0.05       0
Bank Sta=4504.4,4510.4
Exp/Cntr=0.3,0.1

Type RM Length L Ch R = 1,3966,21,21,21
BEGIN DESCRIPTION:
UNT013 IN CCTC 4.0
END DESCRIPTION:
XS GIS Cut Line= 4
      3503321.47     10622408.40      3503357.93     10621890.21
      3503282.41     10621812.08      3502779.81     10621465.22
#Sta/Elev= 30
  4437.9  420.05  4628.3  417.80  4706.8  415.57  4716.8  416.29  4736.8  416.05
  4764.7  414.60  4769.8  415.47  4817.0  414.31  4847.1  414.64  4887.2  413.16
  4897.2  413.16  4927.3  415.27  4937.3  414.91  4947.4  412.72  4963.2  412.08
  5023.9  412.06  5026.7  411.56  5029.9  412.06  5040.9  412.16  5048.1  413.56
  5055.1  412.34  5062.3  413.34  5064.4  412.12  5070.8  412.12  5076.8  414.01
  5214.1  415.25  5399.3  415.52  5485.9  414.90  5506.8  415.43  5676.7  414.75
#Mann=3,-1,0
  4437.9    0.05       0  5023.9   0.035       0  5029.9    0.05       0
Bank Sta=5023.9,5029.9
Exp/Cntr=0.3,0.1

Type RM Length L Ch R = 1,3945,20,20,20
BEGIN DESCRIPTION:
Mapping XS 6427ddee
END DESCRIPTION:
XS GIS Cut Line= 4
      3503344.91     10622403.26      3503373.55     10621898.02
      3503334.49     10621827.71      3502786.57     10621435.01
#Sta/Elev= 30
  4433.4  420.12  4496.6  418.93  4646.8  417.50  4666.8  416.36  4676.9  416.96
  4737.0  416.26  4767.0  415.41  4776.7  415.47  4781.7  416.05  4857.2  414.00
  4907.2  414.08  4917.2  415.31  4948.4  414.89  4956.0  415.30  4961.7  414.88
  4971.3  415.44  4977.7  415.14  4983.5  415.73  4999.5  414.97  5005.6  415.67
  5015.5  415.83  5019.8  415.24  5042.9  415.54  5078.5  413.87  5084.1  412.93
  5086.8  412.43  5090.1  412.93  5108.0  414.12  5259.0  415.01  5694.0  414.56
#Mann=3,-1,0
  4433.4    0.05       0  5084.1   0.035       0  5090.1    0.05       0
Bank Sta=5084.1,5090.1
Exp/Cntr=0.3,0.1

Type RM Length L Ch R = 1,3925,361,361,361
BEGIN DESCRIPTION:
UNT013 IN CCTC 3.0
END DESCRIPTION:
XS GIS Cut Line= 4
      3503376.16     10622398.00      3503386.57     10621874.58
      3503316.26     10621775.63      3502793.72     10621415.91
#Sta/Elev= 30
  4436.0  420.00  4623.9  416.83  4683.9  417.38  4703.9  416.67  4773.9  416.35
  4803.9  415.87  4843.9  414.22  4913.9  413.49  4943.9  413.82  4959.2  413.07
  4975.6  413.46  4981.7  415.00  4989.4  414.65  4996.5  412.97  5002.6  414.34
  5011.3  414.11  5017.4  415.32  5026.0  412.28  5032.2  413.21  5038.5  412.11
  5046.9  411.89  5053.1  413.01  5097.2  414.01  5103.3  413.27  5109.1  411.55
  5111.8  411.05  5115.1  411.55  5125.4  414.16  5283.2  414.90  5715.3  414.60
#Mann=3,-1,0
  4436.0    0.05       0  5109.1   0.035       0  5115.1    0.05       0
Bank Sta=5109.1,5115.1
Exp/Cntr=0.3,0.1

Type RM Length L Ch R = 1,3564,638,638,638
BEGIN DESCRIPTION:
Mapping XS c4900737
END DESCRIPTION:
XS GIS Cut Line= 3
      3504083.62     10622089.86      3503454.03     10621430.00
      3502886.70     10621276.76
#Sta/Elev= 30
  4290.5  417.66  4399.3  416.67  4491.2  414.43  4540.5  414.99  4653.8  414.80
  4682.1  414.36  4717.6  412.71  4773.9  413.58  4887.1  412.36  4915.5  411.55
  4929.6  411.91  4936.9  411.14  4986.2  411.21  5000.4  410.81  5007.6  410.88
  5014.5  411.72  5042.8  411.31  5050.1  411.82  5099.5  411.43  5117.5  410.72
  5120.3  410.22  5123.5  410.72  5184.4  410.80  5191.3  411.32  5216.6  411.62
  5269.3  411.47  5393.6  412.38  5605.2  412.92  5673.2  414.01  5790.2  413.82
#Mann=3,-1,0
  4290.5    0.05       0  5117.5    0.03       0  5123.5    0.05       0
Bank Sta=5117.5,5123.5
Exp/Cntr=0.3,0.1

Type RM Length L Ch R = 1,2926,760,760,760
BEGIN DESCRIPTION:
Mapping XS 28181bf2
END DESCRIPTION:
XS GIS Cut Line= 3
      3504385.84     10621549.46      3503851.49     10620949.18
      3503142.79     10620902.54
#Sta/Elev= 30
  4378.6  412.47  4467.7  412.23  4502.8  411.85  4510.3  411.33  4658.8  410.16
  4708.5  409.95  4743.6  410.48  4786.3  409.76  4800.5  410.09  4878.2  409.54
  4906.7  409.96  4977.7  408.84  4984.4  407.22  4991.9  408.08  4995.6  405.94
  4998.4  405.44  5001.6  405.94  5012.8  409.53  5041.3  409.00  5126.6  408.86
  5175.9  410.02  5284.4  410.24  5444.7  412.18  5534.9  412.30  5565.0  413.39
  5595.0  412.79  5745.4  413.36  5795.5  412.84  5875.6  413.20  5892.5  412.74
#Mann=3,-1,0
  4378.6    0.05       0  4995.6    0.03       0  5001.6    0.05       0
Bank Sta=4995.6,5001.6
Exp/Cntr=0.3,0.1

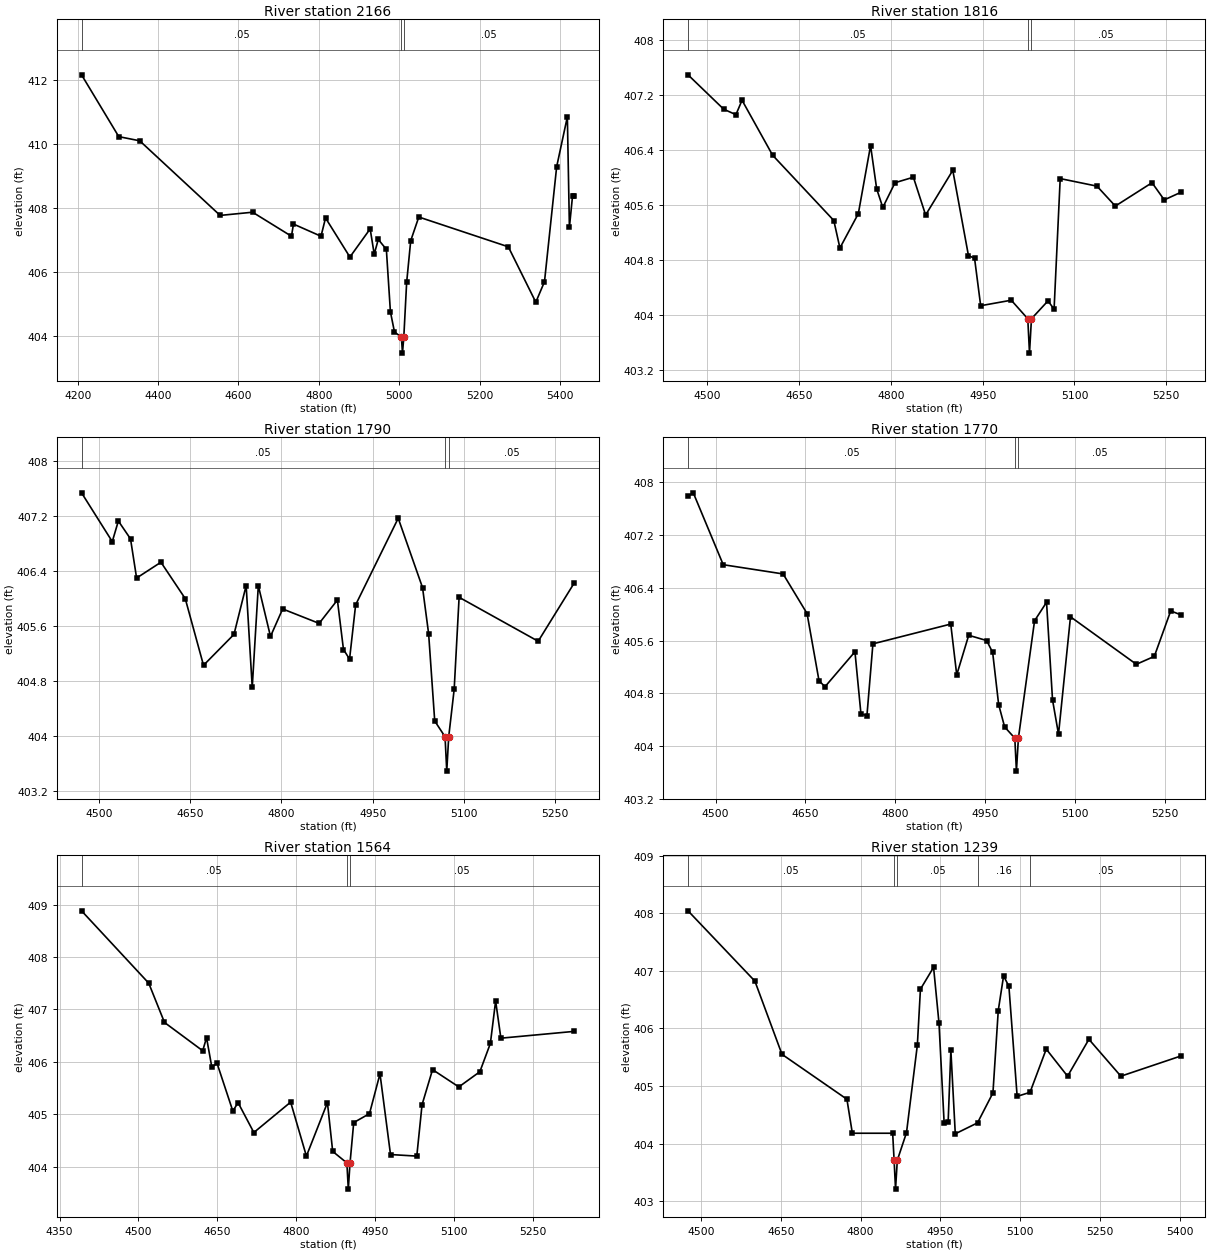
Type RM Length L Ch R = 1,2166,350,350,350
BEGIN DESCRIPTION:
Mapping XS 2f4b002b
END DESCRIPTION:
XS GIS Cut Line= 2
      3504613.13     10621502.00      3504452.53     10620286.66
#Sta/Elev= 30
  4209.6  412.16  4302.2  410.23  4354.3  410.10  4554.4  407.77  4635.1  407.87
  4731.8  407.12  4736.8  407.50  4805.3  407.12  4816.6  407.69  4877.2  406.47
  4927.6  407.35  4937.7  406.56  4947.8  407.02  4967.9  406.71  4978.0  404.76
  4988.1  404.13  5005.3  403.97  5008.0  403.47  5011.3  403.97  5018.4  405.68
  5028.5  406.98  5048.6  407.72  5271.3  406.79  5339.7  405.06  5361.3  405.70
  5391.6  409.29  5418.2  410.85  5423.3  407.40  5431.2  408.39  5435.5  408.39
#Mann=3,-1,0
  4209.6    0.05       0  5005.3    0.03       0  5011.3    0.05       0
Bank Sta=5005.3,5011.3
Exp/Cntr=0.3,0.1

Type RM Length L Ch R = 1,1816,26,26,26
BEGIN DESCRIPTION:
Mapping XS ba40408c
END DESCRIPTION:
XS GIS Cut Line= 2
      3504794.85     10621088.47      3504813.03     10620283.18
#Sta/Elev= 30
  4468.3  407.50  4526.6  407.00  4546.6  406.92  4556.6  407.13  4606.6  406.33
  4706.6  405.38  4716.6  404.98  4746.7  405.48  4766.7  406.47  4776.7  405.84
  4786.7  405.57  4806.7  405.93  4836.7  406.01  4856.7  405.46  4901.1  406.11
  4926.7  404.87  4936.7  404.83  4946.7  404.14  4996.7  404.22  5023.7  403.95
  5026.5  403.45  5029.7  403.95  5056.7  404.21  5066.7  404.09  5076.7  405.99
  5136.8  405.88  5166.8  405.59  5226.8  405.93  5246.8  405.68  5273.8  405.79
#Mann=3,-1,0
  4468.3    0.05       0  5023.7    0.03       0  5029.7    0.05       0
Bank Sta=5023.7,5029.7
Exp/Cntr=0.3,0.1

Type RM Length L Ch R = 1,1790,20,20,20
BEGIN DESCRIPTION:
Mapping XS 49bdfeeb
END DESCRIPTION:
XS GIS Cut Line= 2
      3504820.89     10621080.69      3504839.12     10620270.79
#Sta/Elev= 30
  4471.4  407.54  4521.9  406.83  4531.9  407.13  4551.9  406.87  4561.9  406.30
  4601.9  406.53  4641.9  406.00  4671.9  405.03  4722.0  405.48  4742.0  406.19
  4752.0  404.71  4762.0  406.19  4782.0  405.45  4802.0  405.85  4862.0  405.64
  4892.0  405.98  4902.0  405.26  4912.0  405.12  4922.0  405.91  4992.0  407.17
  5032.0  406.16  5042.0  405.49  5052.0  404.22  5069.0  403.99  5071.8  403.49
  5075.0  403.99  5084.0  404.68  5092.1  406.02  5222.1  405.38  5281.5  406.23
#Mann=3,-1,0
  4471.4    0.05       0  5069.0    0.03       0  5075.0    0.05       0
Bank Sta=5069,5075
Exp/Cntr=0.3,0.1

Type RM Length L Ch R = 1,1770,206,206,206
BEGIN DESCRIPTION:
Mapping XS e2b9c190
END DESCRIPTION:
XS GIS Cut Line= 2
      3504846.93     10621098.96      3504854.75     10620276.00
#Sta/Elev= 30
  4453.8  407.79  4462.6  407.84  4512.6  406.75  4612.6  406.61  4652.6  406.01
  4672.6  404.99  4682.6  404.90  4732.6  405.43  4742.6  404.49  4752.6  404.46
  4762.6  405.55  4892.6  405.85  4902.6  405.08  4922.6  405.68  4952.6  405.60
  4962.6  405.42  4972.6  404.63  4982.6  404.29  4999.6  404.12  5002.3  403.62
  5005.6  404.12  5032.6  405.90  5052.6  406.18  5062.6  404.70  5072.6  404.18
  5092.6  405.96  5202.6  405.24  5232.6  405.36  5260.0  406.05  5276.8  405.99
#Mann=3,-1,0
  4453.8    0.05       0  4999.6    0.03       0  5005.6    0.05       0
Bank Sta=4999.6,5005.6
Exp/Cntr=0.3,0.1

Type RM Length L Ch R = 1,1564,325,325,325
BEGIN DESCRIPTION:
Mapping XS bd7378d7
END DESCRIPTION:
XS GIS Cut Line= 2
      3505042.07     10621137.93      3505052.49     10620200.49
#Sta/Elev= 30
  4391.8  408.88  4519.6  407.50  4549.6  406.75  4622.3  406.21  4629.6  406.46
  4639.6  405.90  4649.6  405.97  4679.6  405.06  4689.6  405.22  4719.6  404.65
  4789.6  405.23  4819.6  404.20  4859.6  405.22  4869.6  404.29  4896.6  404.07
  4899.3  403.57  4902.6  404.07  4909.6  404.84  4939.6  405.01  4959.6  405.77
  4979.6  404.23  5029.6  404.20  5039.6  405.18  5059.6  405.85  5109.6  405.52
  5149.6  405.81  5169.6  406.35  5179.6  407.16  5189.6  406.45  5329.3  406.58
#Mann=3,-1,0
  4391.8    0.05       0  4896.6   0.035       0  4902.6    0.05       0
Bank Sta=4896.6,4902.6
Exp/Cntr=0.3,0.1

Type RM Length L Ch R = 1,1239,31,31,31
BEGIN DESCRIPTION:
Mapping XS 1007fcfe
END DESCRIPTION:
XS GIS Cut Line= 5
      3505262.56     10621123.63      3505353.70     10620646.23
      3505362.38     10620600.65      3505358.04     10620565.93
      3505334.17     10620207.84
#Sta/Elev= 30
  4475.7  408.04  4601.4  406.82  4652.3  405.55  4774.4  404.77  4784.6  404.18
  4860.4  404.18  4863.1  403.71  4865.8  403.21  4869.1  403.71  4886.4  404.19
  4906.8  405.71  4912.6  406.68  4937.3  407.06  4947.5  406.09  4957.2  404.35
  4964.7  404.38  4969.8  405.62  4978.1  404.17  5019.9  404.36  5048.9  404.88
  5058.9  406.31  5068.9  406.91  5078.9  406.73  5094.4  404.82  5118.6  404.89
  5149.1  405.64  5189.2  405.17  5229.3  405.81  5289.4  405.17  5402.0  405.52
#Mann=5,-1,0
  4475.7    0.05       0  4863.1    0.03       0  4869.1    0.05       0
  5019.9    0.16       0  5118.6    0.05       0
Bank Sta=4863.1,4869.1
Exp/Cntr=0.3,0.1

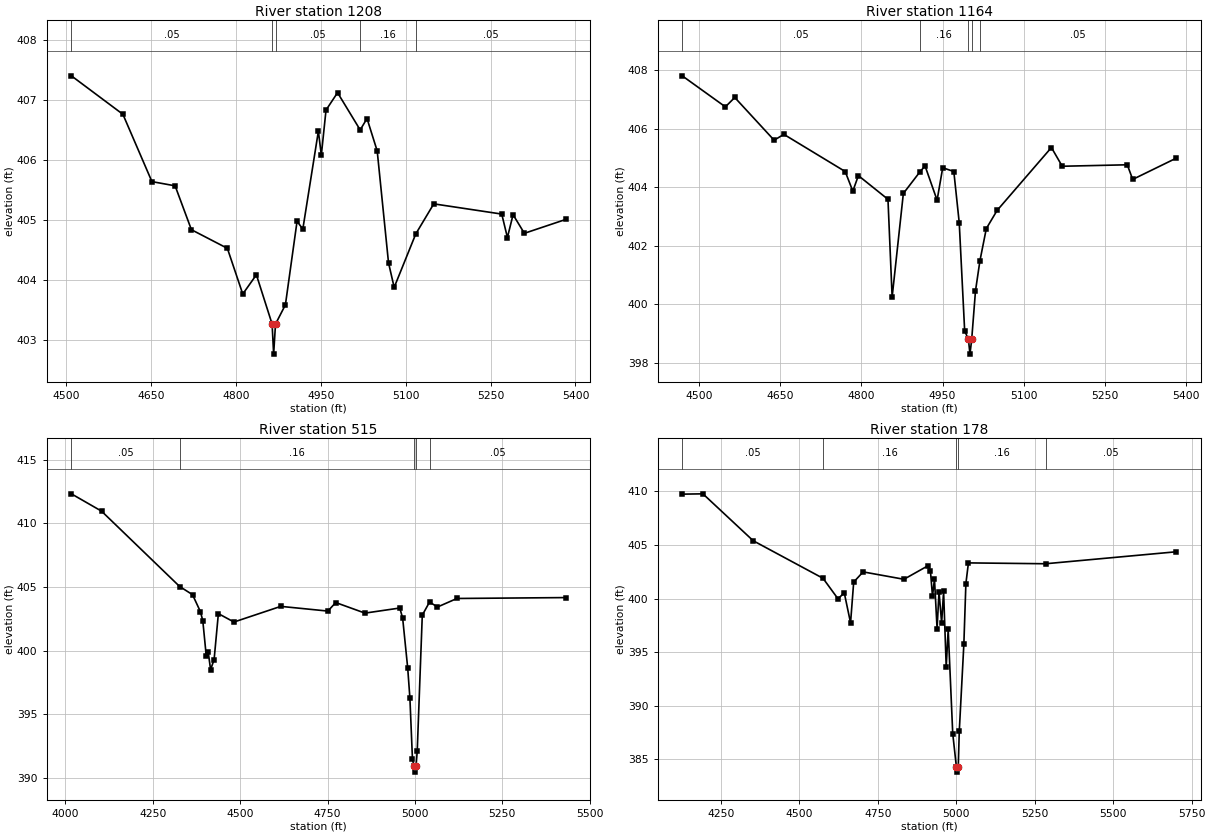
Type RM Length L Ch R = 1,1208,44,44,44
BEGIN DESCRIPTION:
Mapping XS 77be3c97
END DESCRIPTION:
XS GIS Cut Line= 4
      3505286.42     10621088.97      3505390.60     10620635.38
      3505392.77     10620581.12      3505377.57     10620227.35
#Sta/Elev= 30
  4508.8  407.40  4599.9  406.76  4651.2  405.64  4692.2  405.57  4721.0  404.84
  4784.6  404.53  4811.8  403.77  4835.9  404.09  4863.7  403.27  4866.4  402.77
  4869.7  403.27  4887.2  403.59  4907.8  404.98  4918.0  404.85  4945.5  406.48
  4950.7  406.08  4959.0  406.83  4979.4  407.12  5019.4  406.50  5031.5  406.69
  5049.5  406.15  5069.5  404.29  5079.5  403.88  5117.7  404.77  5149.5  405.27
  5269.7  405.10  5279.7  404.71  5289.7  405.09  5309.7  404.78  5382.6  405.01
#Mann=5,-1,0
  4508.8    0.05       0  4863.7    0.03       0  4869.7    0.05       0
  5019.4    0.16       0  5117.7    0.05       0
Bank Sta=4863.7,4869.7
Exp/Cntr=0.3,0.1

Type RM Length L Ch R = 1,1164,649,649,649
BEGIN DESCRIPTION:
Mapping XS 3118b9d8
END DESCRIPTION:
XS GIS Cut Line= 4
      3505303.78     10621123.69      3505436.17     10620646.23
      3505436.17     10620587.63      3505418.81     10620229.52
#Sta/Elev= 30
  4469.3  407.81  4549.0  406.75  4566.3  407.07  4639.0  405.61  4657.0  405.81
  4770.2  404.54  4784.3  403.87  4794.6  404.40  4849.2  403.59  4856.9  400.25
  4877.6  403.79  4908.7  404.54  4917.7  404.73  4939.9  403.56  4950.3  404.67
  4970.8  404.54  4980.8  402.79  4990.8  399.10  4997.8  398.80  5000.6  398.30
  5003.8  398.80  5010.8  400.46  5019.0  401.49  5030.8  402.59  5050.7  403.21
  5151.0  405.36  5171.0  404.72  5291.1  404.77  5301.1  404.27  5381.9  405.00
#Mann=5,-1,0
  4469.3    0.05       0  4908.7    0.16       0  4997.8    0.07       0
  5003.8    0.16       0  5019.0    0.05       0
Bank Sta=4997.8,5003.8
Exp/Cntr=0.3,0.1

Type RM Length L Ch R = 1,515,337,337,337
BEGIN DESCRIPTION:
UNT013 IN CCTC 2.0
END DESCRIPTION:
XS GIS Cut Line= 4
      3505792.06     10621377.60      3506146.24     10620658.81
      3505989.99     10620455.69      3505642.83     10620372.78
#Sta/Elev= 30
  4016.9  412.31  4103.2  410.95  4326.8  405.03  4363.6  404.39  4386.1  403.06
  4393.0  402.35  4403.0  399.55  4408.5  399.89  4415.3  398.50  4425.4  399.29
  4437.6  402.90  4482.2  402.24  4616.2  403.47  4751.0  403.10  4773.5  403.77
  4857.2  402.94  4956.8  403.34  4965.0  402.55  4979.5  398.62  4985.8  396.25
  4993.1  391.45  4997.4  390.95  5000.1  390.45  5003.4  390.95  5006.7  392.08
  5021.2  402.78  5042.0  403.81  5064.7  403.42  5120.4  404.09  5431.4  404.16
#Mann=5,-1,0
  4016.9    0.05       0  4326.8    0.16       0  4997.4    0.07       0
  5003.4    0.16       0  5042.0    0.05       0
Bank Sta=4997.4,5003.4
Exp/Cntr=0.3,0.1

Type RM Length L Ch R = 1,178,0,0,0
BEGIN DESCRIPTION:
UNT013 IN CCTC 1.0
END DESCRIPTION:
XS GIS Cut Line= 4
      3506443.11     10621216.06      3506411.86     10620497.36
      3506266.03     10620304.65      3505652.98     10620273.47
#Sta/Elev= 30
  4126.7  409.75  4192.6  409.78  4352.8  405.40  4575.4  401.89  4623.0  399.98
  4643.1  400.53  4663.1  397.73  4673.1  401.54  4703.1  402.49  4833.2  401.80
  4909.7  403.06  4917.8  402.53  4924.2  400.21  4930.5  401.83  4938.8  397.19
  4945.0  400.64  4953.3  397.71  4959.6  400.66  4967.9  393.62  4974.2  397.11
  4988.7  387.39  5000.3  384.29  5003.0  383.79  5006.3  384.29  5009.5  387.59
  5024.1  395.72  5030.6  401.40  5038.7  403.33  5284.6  403.25  5701.6  404.37
#Mann=5,-1,0
  4126.7    0.05       0  4575.4    0.16       0  5000.3    0.07       0
  5006.3    0.16       0  5284.6    0.05       0
Bank Sta=5000.3,5006.3
Exp/Cntr=0.3,0.1

Chan Stop Cuts=-1