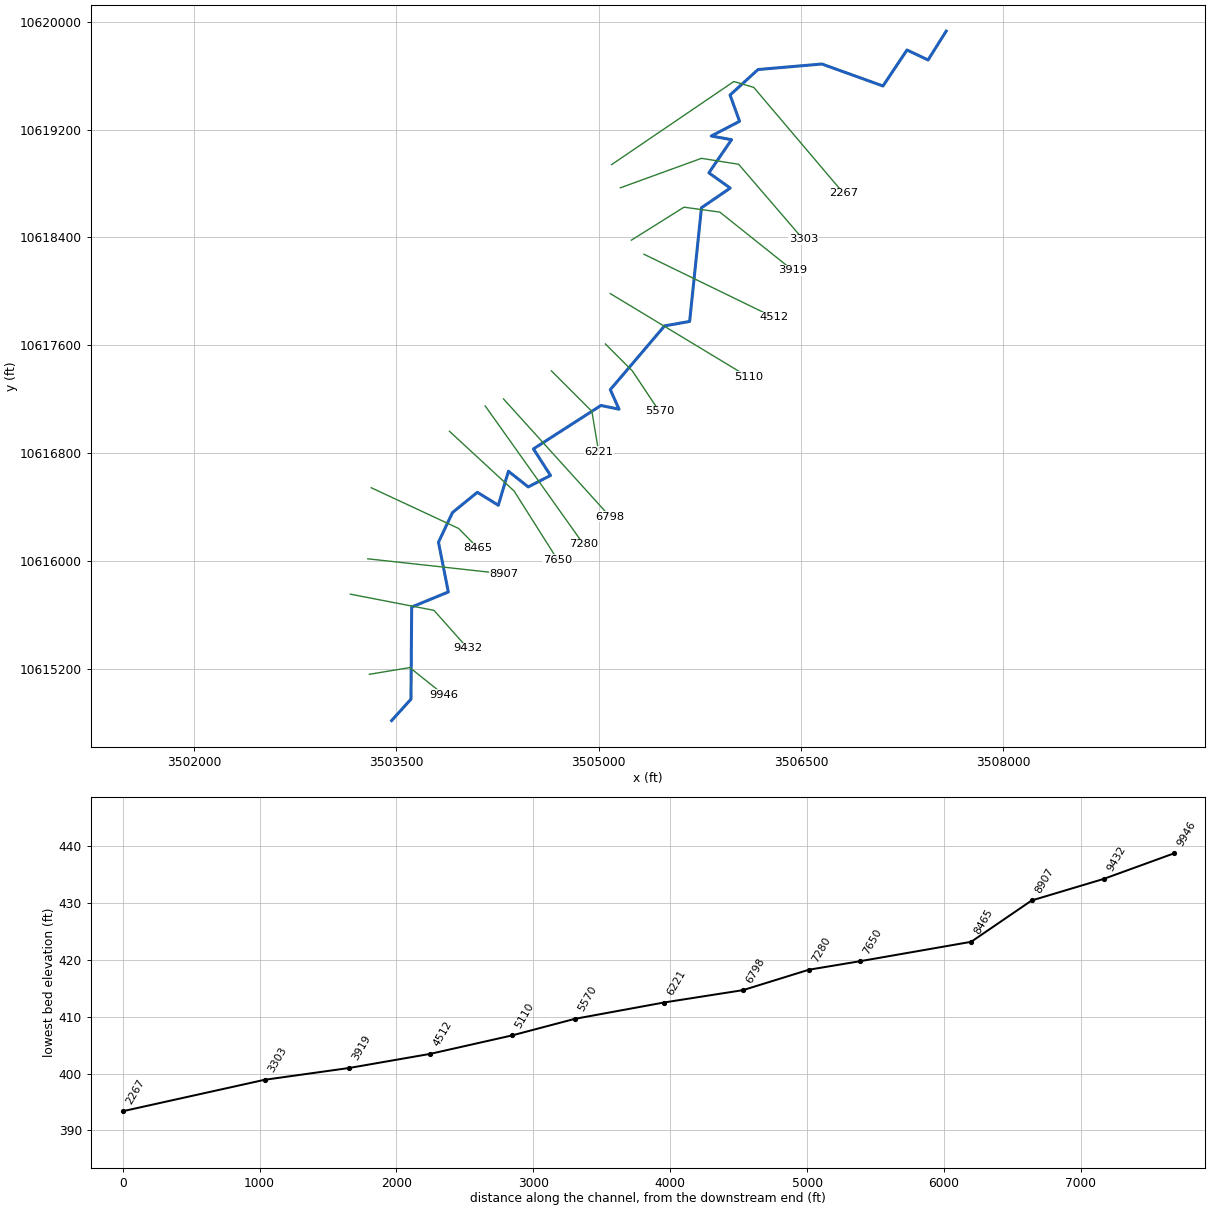
--- UNT014 IN CCTC.prj (project) ---

Proj Title=UNT014 IN CCTC Base Level Engineering
Current Plan=p01
Default Exp/Contr=0.3,0.1
English Units
Geom File=g01
Flow File=f01
Plan File=p01
BEGIN DESCRIPTION:
UNT014 IN CCTC
END DESCRIPTION:

--- UNT014 IN CCTC.p01 (plan) ---

Plan Title=Multiple Run
Short Identifier=Multiple
Geom File=g01
Flow File=f01
Subcritical Flow
K Sum by GR= 0
Std Step Tol= 0.01
Critical Tol= 0.01
Num of Std Step Trials= 20
Max Error Tol= 0.3
Flow Tol Ratio= 0.001
Split Flow NTrial= 30
Split Flow Tol= 0.02
Split Flow Ratio= 0.02
Log Output Level= 0
Friction Slope Method= 1
Unsteady Friction Slope Method= 2
Unsteady Bridges Friction Slope Method= 1
Parabolic Critical Depth
Global Vel Dist=  1 , 1 , 1
Global Log Level= 0
CheckData=True
Encroach Param= -1, 0, 0, 0
BEGIN DESCRIPTION:
Multiple Run
END DESCRIPTION:

--- UNT014 IN CCTC.f01 (steady flow) ---

Flow Title=Multiple
Number of Profiles=7
Profile Names=10-year,25-year,50-year,1pct_min,100-year,1pct_plu,500-year
River Rch & RM= UNT014 IN CCTC,Reach-1,9946
    1172    1602    1955    1741    2354    3184    3404
Boundary for River Rch & Prof#=UNT014 IN CCTC,Reach-1,1
Up Type=0
Dn Type=3
Dn Slope=0.005
Boundary for River Rch & Prof#=UNT014 IN CCTC,Reach-1,2
Up Type=0
Dn Type=3
Dn Slope=0.005
Boundary for River Rch & Prof#=UNT014 IN CCTC,Reach-1,3
Up Type=0
Dn Type=3
Dn Slope=0.005
Boundary for River Rch & Prof#=UNT014 IN CCTC,Reach-1,4
Up Type=0
Dn Type=3
Dn Slope=0.005
Boundary for River Rch & Prof#=UNT014 IN CCTC,Reach-1,5
Up Type=0
Dn Type=3
Dn Slope=0.005
Boundary for River Rch & Prof#=UNT014 IN CCTC,Reach-1,6
Up Type=0
Dn Type=3
Dn Slope=0.005
Boundary for River Rch & Prof#=UNT014 IN CCTC,Reach-1,7
Up Type=0
Dn Type=3
Dn Slope=0.005

--- UNT014 IN CCTC.g01 (geometry) ---

Geom Title=Existing Conditions

River Reach=UNT014 IN CCTC,Reach-1
Reach XY= 30
      3503464.50     10614817.00      3503608.00     10614976.00
      3503613.25     10615659.00      3503885.00     10615771.00
      3503812.00     10616140.00      3503916.00     10616360.00
      3504100.25     10616510.00      3504255.75     10616414.00
      3504330.75     10616666.00      3504477.50     10616550.00
      3504642.75     10616635.00      3504516.25     10616832.00
      3505017.00     10617154.00      3505151.00     10617126.00
      3505086.00     10617271.00      3505488.50     10617744.00
      3505674.50     10617777.00      3505762.25     10618620.00
      3505975.50     10618766.00      3505817.25     10618879.00
      3505985.25     10619125.00      3505834.75     10619152.00
      3506044.75     10619261.00      3505974.25     10619456.00
      3506181.50     10619645.00      3506655.00     10619686.00
      3507108.25     10619523.00      3507286.25     10619790.00
      3507442.50     10619716.00      3507577.00     10619930.00

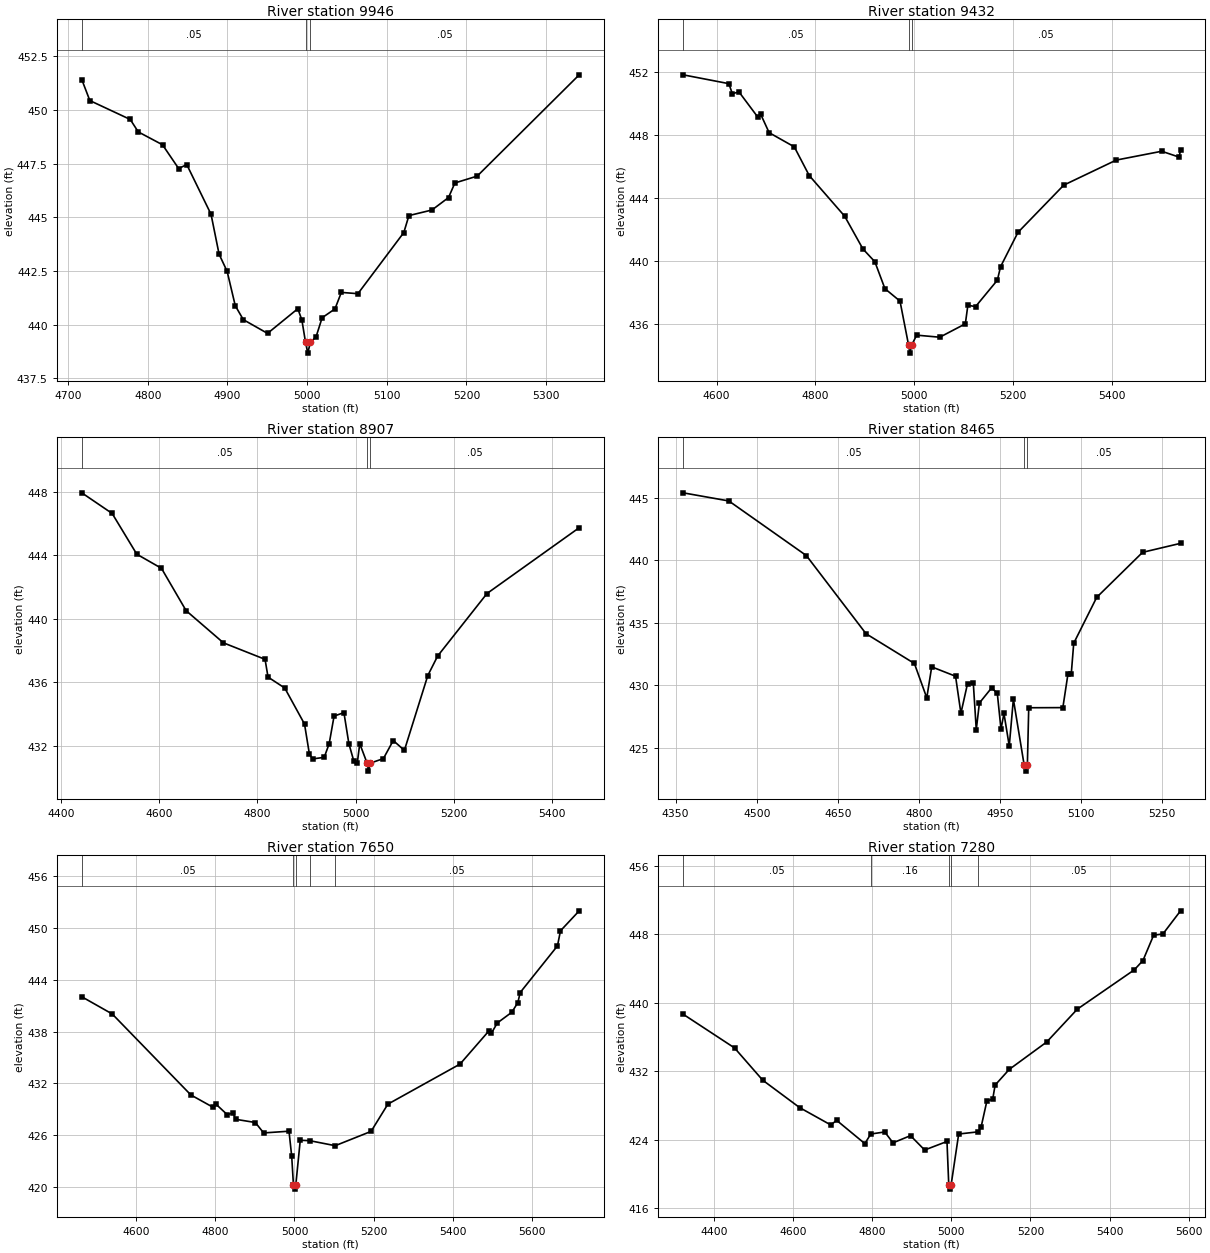
Type RM Length L Ch R = 1,9946,514,514,514
BEGIN DESCRIPTION:
UNT014 IN CCTC 15.0
END DESCRIPTION:
XS GIS Cut Line= 3
      3503299.66     10615160.20      3503599.61     10615210.19
      3503849.57     10615010.22
#Sta/Elev= 30
  4717.3  451.42  4727.4  450.44  4778.1  449.56  4788.2  448.98  4818.6  448.38
  4838.9  447.27  4849.0  447.46  4879.5  445.14  4889.6  443.28  4899.7  442.48
  4909.9  440.88  4920.0  440.23  4950.4  439.59  4988.4  440.74  4993.5  440.21
  4998.1  439.17  5000.9  438.67  5004.1  439.17  5011.3  439.43  5018.9  440.32
  5035.0  440.73  5043.0  441.50  5063.8  441.44  5121.4  444.29  5127.8  445.08
  5156.7  445.34  5177.5  445.92  5185.5  446.60  5213.5  446.92  5341.5  451.64
#Mann=3,-1,0
  4717.3    0.05       0  4998.1   0.035       0  5004.1    0.05       0
Bank Sta=4998.1,5004.1
Exp/Cntr=0.3,0.1

Type RM Length L Ch R = 1,9432,525,525,525
BEGIN DESCRIPTION:
UNT014 IN CCTC 14.0
END DESCRIPTION:
XS GIS Cut Line= 3
      3503158.76     10615754.48      3503778.56     10615634.69
      3504027.79     10615354.32
#Sta/Elev= 30
  4532.2  451.84  4624.7  451.28  4631.8  450.64  4645.1  450.76  4683.7  449.14
  4688.8  449.36  4706.2  448.17  4757.1  447.27  4787.3  445.45  4859.0  442.87
  4896.0  440.79  4920.1  439.98  4940.5  438.27  4971.0  437.48  4988.4  434.68
  4991.1  434.18  4994.4  434.68  5004.7  435.32  5051.4  435.19  5103.2  436.04
  5108.3  437.22  5123.8  437.13  5168.0  438.81  5174.4  439.66  5209.6  441.84
  5302.3  444.84  5408.5  446.43  5500.5  446.99  5535.6  446.62  5538.6  447.06
#Mann=3,-1,0
  4532.2    0.05       0  4988.4   0.035       0  4994.4    0.05       0
Bank Sta=4988.4,4994.4
Exp/Cntr=0.3,0.1

Type RM Length L Ch R = 1,8907,442,442,442
BEGIN DESCRIPTION:
UNT014 IN CCTC 13.0
END DESCRIPTION:
XS GIS Cut Line= 2
      3503288.08     10616016.84      3504296.60     10615905.94
#Sta/Elev= 30
  4441.6  447.95  4503.5  446.65  4553.8  444.08  4604.1  443.19  4654.4  440.52
  4730.5  438.49  4815.4  437.45  4821.5  436.33  4855.6  435.64  4895.9  433.37
  4905.9  431.47  4912.5  431.17  4936.1  431.27  4946.2  432.13  4956.2  433.87
  4976.3  434.09  4986.4  432.13  4996.5  431.03  5003.6  430.93  5008.6  432.13
  5023.6  430.90  5026.4  430.40  5029.6  430.90  5056.8  431.19  5076.9  432.33
  5099.6  431.71  5147.4  436.43  5167.5  437.66  5268.1  441.60  5456.2  445.75
#Mann=3,-1,0
  4441.6    0.05       0  5023.6   0.035       0  5029.6    0.05       0
Bank Sta=5023.6,5029.6
Exp/Cntr=0.3,0.1

Type RM Length L Ch R = 1,8465,815,815,815
BEGIN DESCRIPTION:
UNT014 IN CCTC 12.0
END DESCRIPTION:
XS GIS Cut Line= 3
      3503313.03     10616543.92      3503961.43     10616241.86
      3504104.65     10616096.03
#Sta/Elev= 30
  4363.9  445.40  4448.4  444.75  4591.8  440.38  4702.1  434.13  4791.5  431.75
  4814.4  429.00  4823.5  431.48  4867.6  430.73  4877.5  427.77  4889.7  430.13
  4900.4  430.20  4905.9  426.46  4911.7  428.59  4934.3  429.80  4944.8  429.36
  4951.6  426.50  4957.1  427.75  4966.9  425.15  4974.5  428.90  4994.4  423.64
  4997.1  423.14  5000.4  423.64  5002.9  428.21  5066.0  428.22  5075.4  430.90
  5081.5  430.90  5086.1  433.37  5128.6  437.04  5213.4  440.64  5283.6  441.36
#Mann=3,-1,0
  4363.9    0.05       0  4994.4   0.035       0  5000.4    0.05       0
Bank Sta=4994.4,5000.4
Exp/Cntr=0.3,0.1

Type RM Length L Ch R = 1,7650,370,370,370
BEGIN DESCRIPTION:
UNT014 IN CCTC 11.0
END DESCRIPTION:
XS GIS Cut Line= 3
      3503893.18     10616962.79      3504372.31     10616520.11
      3504694.90     10616010.21
#Sta/Elev= 30
  4463.1  442.04  4540.0  440.04  4738.4  430.65  4795.1  429.20  4802.0  429.57
  4830.3  428.36  4844.5  428.56  4851.8  427.82  4901.2  427.45  4922.2  426.24
  4986.2  426.44  4993.0  423.54  4997.4  420.22  5000.2  419.72  5003.4  420.22
  5014.6  425.39  5038.7  425.34  5102.9  424.76  5193.4  426.42  5235.8  429.58
  5418.0  434.23  5490.9  438.08  5496.9  437.79  5512.1  439.00  5548.6  440.24
  5563.9  441.36  5569.8  442.53  5663.9  447.94  5671.5  449.69  5718.8  452.01
#Mann=5,-1,0
  4463.1    0.05       0  4997.4   0.035       0  5003.4    0.05       0
  5038.7    0.16       0  5102.9    0.05       0
Bank Sta=4997.4,5003.4
Exp/Cntr=0.3,0.1

Type RM Length L Ch R = 1,7280,482,482,482
BEGIN DESCRIPTION:
UNT014 IN CCTC 10.0
END DESCRIPTION:
XS GIS Cut Line= 2
      3504158.75     10617150.34      3504887.60     10616124.75
#Sta/Elev= 30
  4321.4  438.68  4451.4  434.74  4522.7  430.97  4616.0  427.77  4694.9  425.74
  4709.7  426.28  4781.0  423.56  4796.1  424.68  4831.4  424.92  4852.3  423.65
  4896.6  424.49  4932.3  422.81  4988.8  423.81  4993.3  418.74  4996.1  418.24
  4999.3  418.74  5018.4  424.68  5066.9  424.93  5074.9  425.45  5089.7  428.53
  5104.5  428.76  5110.6  430.40  5146.3  432.23  5241.0  435.43  5318.5  439.27
  5462.5  443.86  5484.5  444.95  5511.6  447.92  5534.9  448.05  5579.6  450.76
#Mann=5,-1,0
  4321.4    0.05       0  4796.1    0.16       0  4993.3    0.07       0
  4999.3    0.16       0  5066.9    0.05       0
Bank Sta=4993.3,4999.3
Exp/Cntr=0.3,0.1

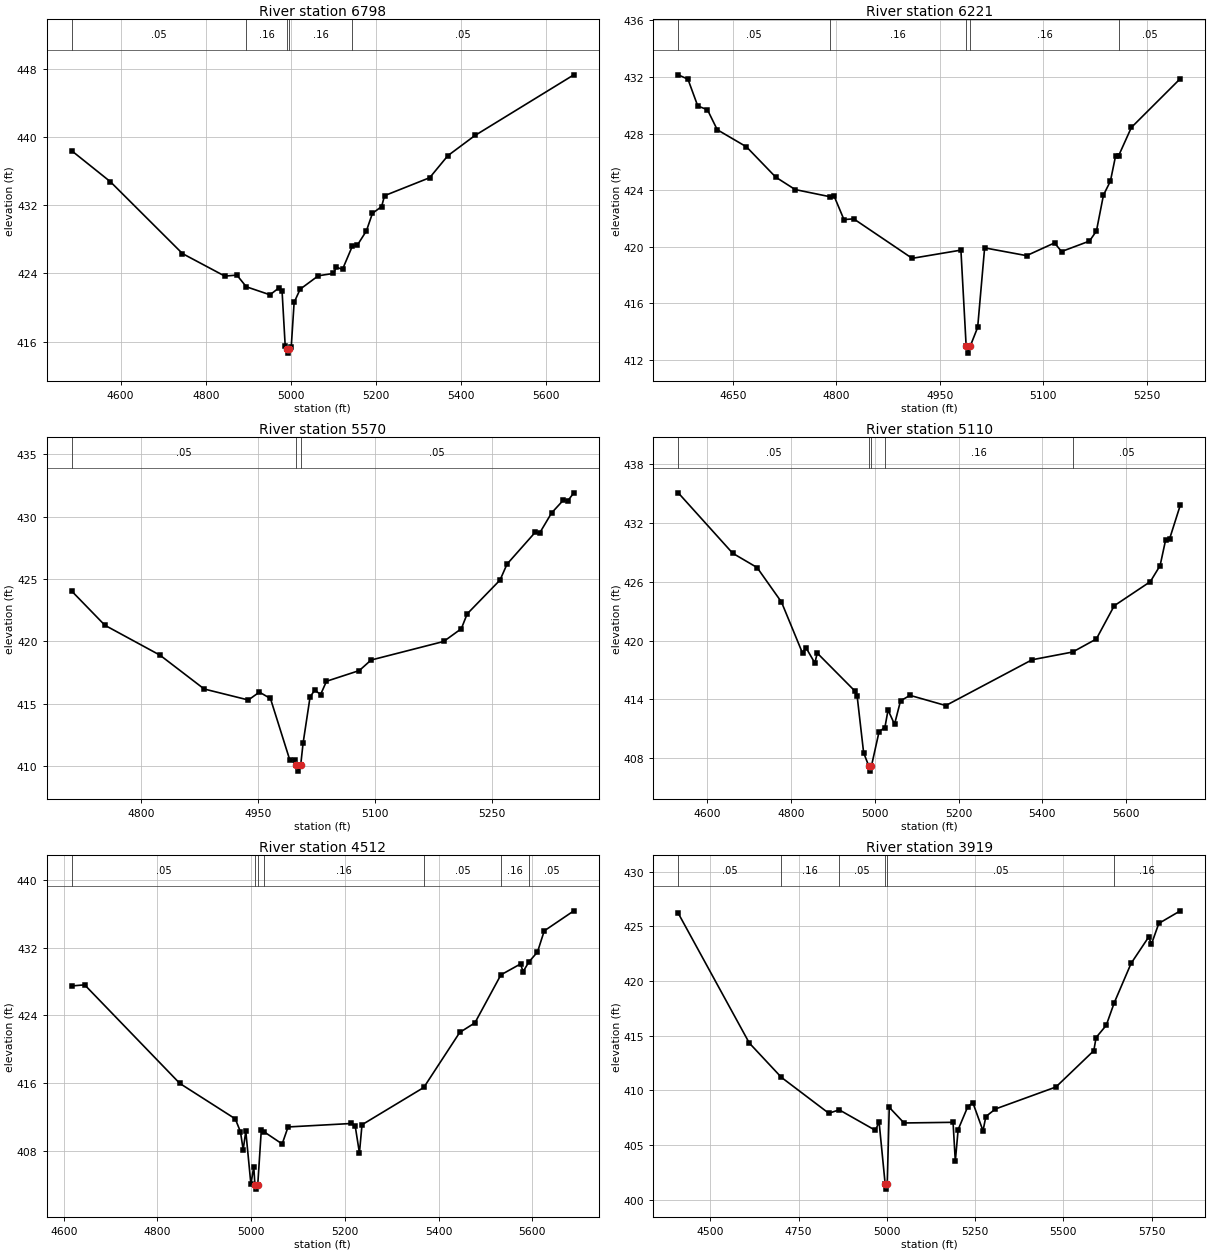
Type RM Length L Ch R = 1,6798,577,577,577
BEGIN DESCRIPTION:
UNT014 IN CCTC 9.0
END DESCRIPTION:
XS GIS Cut Line= 2
      3504294.18     10617202.41      3505085.26     10616328.06
#Sta/Elev= 30
  4485.3  438.37  4575.7  434.76  4745.3  426.32  4844.7  423.68  4873.0  423.80
  4895.2  422.43  4950.8  421.49  4972.4  422.32  4979.2  421.90  4986.6  415.43
  4990.4  415.15  4993.1  414.65  4996.4  415.15  5000.7  415.37  5007.5  420.60
  5021.7  422.15  5064.3  423.72  5099.5  423.99  5106.9  424.72  5121.1  424.47
  5144.5  427.23  5156.2  427.33  5177.2  428.98  5191.4  431.04  5213.0  431.84
  5219.8  433.11  5325.9  435.22  5368.5  437.80  5432.3  440.17  5664.4  447.28
#Mann=5,-1,0
  4485.3    0.05       0  4895.2    0.16       0  4990.4    0.07       0
  4996.4    0.16       0  5144.5    0.05       0
Bank Sta=4990.4,4996.4
Exp/Cntr=0.3,0.1

Type RM Length L Ch R = 1,6221,651,651,651
BEGIN DESCRIPTION:
UNT014 IN CCTC 8.0
END DESCRIPTION:
XS GIS Cut Line= 3
      3504649.61     10617410.19      3504949.61     10617110.19
      3504999.61     10616810.19
#Sta/Elev= 30
  4570.6  432.15  4584.7  431.84  4598.9  429.95  4613.0  429.68  4627.2  428.27
  4669.6  427.06  4712.0  424.92  4740.3  424.04  4791.2  423.53  4796.9  423.56
  4811.0  421.92  4825.2  421.97  4910.0  419.18  4980.7  419.76  4988.3  412.98
  4991.1  412.48  4994.3  412.98  5005.0  414.30  5015.1  419.92  5076.0  419.37
  5116.5  420.27  5126.7  419.66  5167.2  420.40  5177.3  421.11  5187.5  423.65
  5197.6  424.64  5205.2  426.44  5209.5  426.43  5228.0  428.43  5299.0  431.88
#Mann=5,-1,0
  4570.6    0.05       0  4791.2    0.16       0  4988.3    0.07       0
  4994.3    0.16       0  5209.5    0.05       0
Bank Sta=4988.3,4994.3
Exp/Cntr=0.3,0.1

Type RM Length L Ch R = 1,5570,460,460,460
BEGIN DESCRIPTION:
UNT014 IN CCTC 7.0
END DESCRIPTION:
XS GIS Cut Line= 3
      3505049.61     10617610.19      3505249.61     10617410.19
      3505449.61     10617110.19
#Sta/Elev= 30
  4711.3  424.03  4753.7  421.30  4824.4  418.90  4881.0  416.19  4937.6  415.31
  4951.7  415.94  4965.9  415.43  4990.6  410.52  4997.1  410.52  4998.7  410.11
  5001.4  409.61  5004.7  410.11  5007.7  411.84  5016.7  415.56  5022.7  416.10
  5030.2  415.75  5037.7  416.81  5079.8  417.67  5094.8  418.51  5187.9  420.00
  5210.5  421.02  5218.0  422.21  5260.1  424.92  5269.1  426.20  5305.1  428.74
  5311.1  428.71  5326.2  430.30  5341.2  431.32  5347.2  431.29  5354.7  431.91
#Mann=3,-1,0
  4711.3    0.05       0  4998.7   0.035       0  5004.7    0.05       0
Bank Sta=4998.7,5004.7
Exp/Cntr=0.3,0.1

Type RM Length L Ch R = 1,5110,598,598,598
BEGIN DESCRIPTION:
UNT014 IN CCTC 6.0
END DESCRIPTION:
XS GIS Cut Line= 2
      3505085.82     10617983.67      3506110.82     10617364.51
#Sta/Elev= 30
  4531.5  435.08  4661.3  428.92  4719.5  427.46  4777.7  423.94  4828.0  418.72
  4835.9  419.30  4857.3  417.72  4863.1  418.73  4952.4  414.88  4958.2  414.35
  4973.7  408.56  4986.2  407.19  4989.0  406.69  4992.2  407.19  5010.6  410.73
  5024.4  411.14  5031.9  412.92  5047.4  411.47  5061.7  413.86  5084.3  414.42
  5169.7  413.38  5375.4  418.05  5472.2  418.84  5528.7  420.17  5571.4  423.56
  5657.5  426.02  5680.8  427.66  5693.7  430.22  5703.4  430.38  5729.0  433.83
#Mann=5,-1,0
  4531.5    0.05       0  4986.2   0.035       0  4992.2    0.05       0
  5024.4    0.16       0  5472.2    0.05       0
Bank Sta=4986.2,4992.2
Exp/Cntr=0.3,0.1

Type RM Length L Ch R = 1,4512,593,593,593
BEGIN DESCRIPTION:
UNT014 IN CCTC 4.0
END DESCRIPTION:
XS GIS Cut Line= 2
      3505335.87     10618275.31      3506299.40     10617806.57
#Sta/Elev= 30
  4617.2  427.47  4644.7  427.60  4847.7  415.95  4966.1  411.76  4977.2  410.23
  4983.0  408.11  4988.6  410.29  4999.5  404.02  5005.6  406.11  5008.1  403.95
  5010.9  403.45  5014.1  403.95  5021.7  410.44  5026.7  410.26  5066.2  408.79
  5078.8  410.80  5214.1  411.21  5221.9  410.97  5231.1  407.73  5236.6  411.06
  5368.5  415.47  5445.1  421.97  5477.6  423.11  5533.0  428.78  5574.9  430.07
  5580.4  429.16  5592.9  430.32  5611.1  431.48  5625.5  433.98  5688.7  436.35
#Mann=7,-1,0
  4617.2    0.05       0  5008.1   0.035       0  5014.1    0.05       0
  5026.7    0.16       0  5368.5    0.05       0  5533.0    0.16       0
  5592.9    0.05       0
Bank Sta=5008.1,5014.1
Exp/Cntr=0.3,0.1

Type RM Length L Ch R = 1,3919,616,616,616
BEGIN DESCRIPTION:
UNT014 IN CCTC 3.0
END DESCRIPTION:
XS GIS Cut Line= 4
      3505242.14     10618379.50      3505632.73     10618624.27
      3505898.36     10618587.82      3506440.03     10618155.52
#Sta/Elev= 30
  4409.1  426.20  4610.4  414.33  4701.3  411.19  4835.5  407.91  4865.2  408.22
  4967.8  406.34  4977.9  407.14  4995.1  401.47  4997.9  400.97  5001.1  401.47
  5006.8  408.45  5048.6  407.02  5187.5  407.08  5193.9  403.52  5201.9  406.41
  5229.3  408.52  5243.5  408.88  5272.4  406.30  5280.4  407.61  5307.6  408.30
  5478.9  410.31  5586.2  413.63  5592.6  414.83  5621.4  415.95  5644.0  418.01
  5691.9  421.62  5741.5  424.02  5749.5  423.38  5770.3  425.27  5831.2  426.42
#Mann=6,-1,0
  4409.1    0.05       0  4701.3    0.16       0  4865.2    0.05       0
  4995.1   0.035       0  5001.1    0.05       0  5644.0    0.16       0
Bank Sta=4995.1,5001.1
Exp/Cntr=0.3,0.1

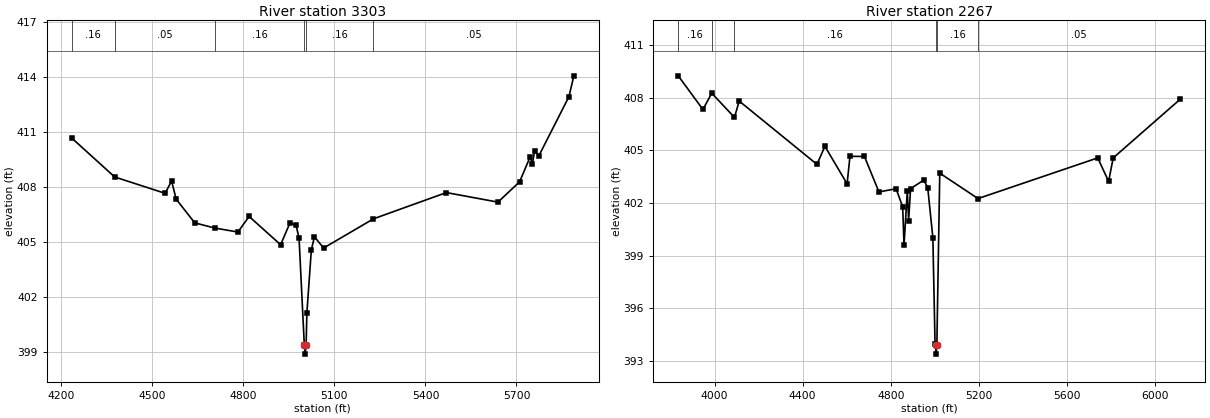
Type RM Length L Ch R = 1,3303,1036,1036,1036
BEGIN DESCRIPTION:
UNT014 IN CCTC 2.0
END DESCRIPTION:
XS GIS Cut Line= 4
      3505160.51     10618767.83      3505762.05     10618986.57
      3506038.09     10618942.30      3506517.18     10618385.10
#Sta/Elev= 30
  4234.5  410.67  4375.9  408.55  4542.1  407.66  4563.4  408.33  4578.6  407.34
  4639.8  406.05  4705.2  405.77  4782.1  405.55  4818.8  406.40  4922.7  404.86
  4953.1  406.03  4973.4  405.94  4983.5  405.21  5000.8  399.40  5003.5  398.90
  5006.8  399.40  5009.2  401.13  5024.0  404.59  5034.2  405.29  5064.5  404.68
  5228.6  406.27  5468.9  407.70  5639.0  407.18  5710.3  408.29  5745.4  409.66
  5752.0  409.23  5759.7  409.96  5773.9  409.71  5872.7  412.92  5889.0  414.06
#Mann=6,-1,0
  4234.5    0.16       0  4375.9    0.05       0  4705.2    0.16       0
  5000.8    0.07       0  5006.8    0.16       0  5228.6    0.05       0
Bank Sta=5000.8,5006.8
Exp/Cntr=0.3,0.1

Type RM Length L Ch R = 1,2267,0,0,0
BEGIN DESCRIPTION:
UNT014 IN CCTC 1.0
END DESCRIPTION:
XS GIS Cut Line= 4
      3505095.39     10618939.70      3506002.22     10619556.17
      3506149.79     10619512.77      3506815.67     10618727.42
#Sta/Elev= 30
  3835.0  409.25  3947.2  407.33  3987.1  408.26  4090.3  406.88  4111.9  407.81
  4465.1  404.20  4501.0  405.23  4601.9  403.09  4614.8  404.66  4680.6  404.65
  4746.4  402.63  4824.3  402.81  4854.2  401.78  4860.3  399.59  4875.2  402.67
  4881.2  401.00  4890.1  402.82  4949.7  403.30  4967.9  402.88  4991.3  400.02
  5001.2  393.97  5003.4  393.88  5006.2  393.38  5009.4  393.88  5022.6  403.70
  5196.4  402.25  5740.0  404.57  5789.4  403.23  5810.2  404.57  6115.0  407.92
#Mann=6,-1,0
  3835.0    0.16       0  3987.1    0.05       0  4090.3    0.16       0
  5003.4    0.07       0  5009.4    0.16       0  5196.4    0.05       0
Bank Sta=5003.4,5009.4
Exp/Cntr=0.3,0.1

Chan Stop Cuts=-1