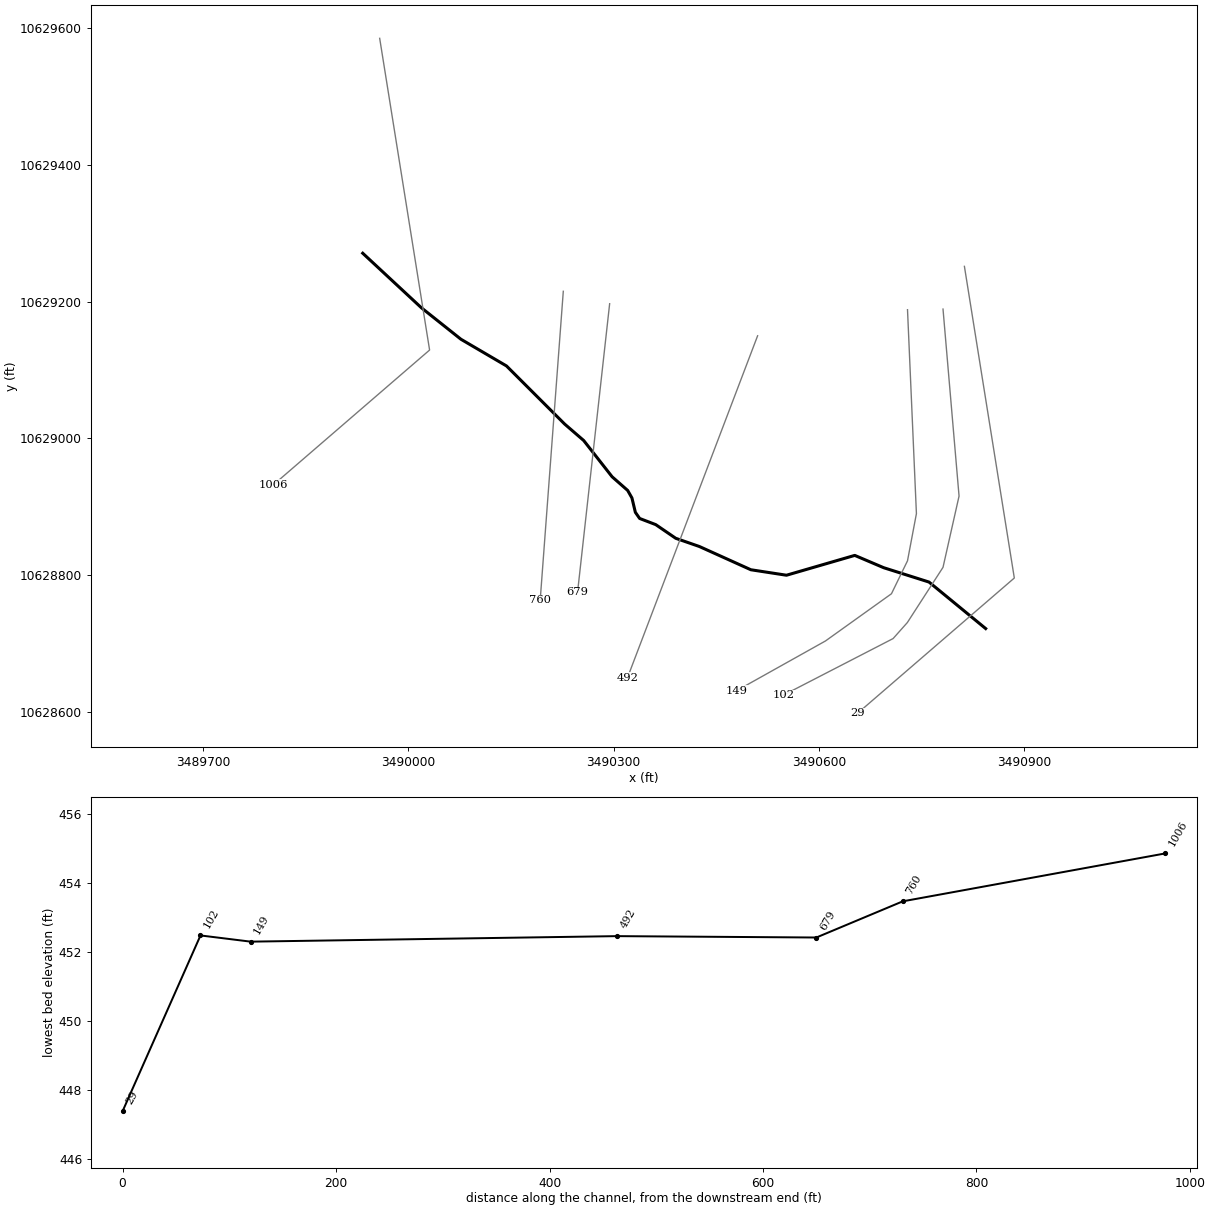
--- UNT019 IN CCTC.prj (project) ---

Proj Title=UNT019 IN CCTC Base Level Engineering
Current Plan=p01
Default Exp/Contr=0.3,0.1
English Units
Geom File=g01
Flow File=f01
Plan File=p01
BEGIN DESCRIPTION:
UNT019 IN CCTC
END DESCRIPTION:

--- UNT019 IN CCTC.p01 (plan) ---

Plan Title=Multiple Run
Short Identifier=Multiple
Geom File=g01
Flow File=f01
Subcritical Flow
K Sum by GR= 0
Std Step Tol= 0.01
Critical Tol= 0.01
Num of Std Step Trials= 20
Max Error Tol= 0.3
Flow Tol Ratio= 0.001
Split Flow NTrial= 30
Split Flow Tol= 0.02
Split Flow Ratio= 0.02
Log Output Level= 0
Friction Slope Method= 1
Unsteady Friction Slope Method= 2
Unsteady Bridges Friction Slope Method= 1
Parabolic Critical Depth
Global Vel Dist=  1 , 1 , 1
Global Log Level= 0
CheckData=True
Encroach Param= -1, 0, 0, 0
BEGIN DESCRIPTION:
Multiple Run
END DESCRIPTION:

--- UNT019 IN CCTC.f01 (steady flow) ---

Flow Title=Multiple
Number of Profiles=7
Profile Names=10-year,25-year,50-year,1pct_min,100-year,1pct_plu,500-year
River Rch & RM= UNT019 IN CCTC,Reach-1,1006
     359     453     524     444     600     812     783
Boundary for River Rch & Prof#=UNT019 IN CCTC,Reach-1,1
Up Type=0
Dn Type=3
Dn Slope=0.005
Boundary for River Rch & Prof#=UNT019 IN CCTC,Reach-1,2
Up Type=0
Dn Type=3
Dn Slope=0.005
Boundary for River Rch & Prof#=UNT019 IN CCTC,Reach-1,3
Up Type=0
Dn Type=3
Dn Slope=0.005
Boundary for River Rch & Prof#=UNT019 IN CCTC,Reach-1,4
Up Type=0
Dn Type=3
Dn Slope=0.005
Boundary for River Rch & Prof#=UNT019 IN CCTC,Reach-1,5
Up Type=0
Dn Type=3
Dn Slope=0.005
Boundary for River Rch & Prof#=UNT019 IN CCTC,Reach-1,6
Up Type=0
Dn Type=3
Dn Slope=0.005
Boundary for River Rch & Prof#=UNT019 IN CCTC,Reach-1,7
Up Type=0
Dn Type=3
Dn Slope=0.005

--- UNT019 IN CCTC.g01 (geometry) ---

Geom Title=Existing Conditions

River Reach=UNT019 IN CCTC,Reach-1
Reach XY= 20
      3489933.49     10629270.81      3490019.25     10629191.00
      3490077.00     10629145.00      3490143.50     10629106.00
      3490228.50     10629021.00      3490256.25     10628997.00
      3490297.75     10628944.00      3490320.50     10628924.00
      3490326.75     10628913.00      3490331.75     10628892.00
      3490338.00     10628883.00      3490361.50     10628874.00
      3490390.75     10628854.00      3490425.25     10628842.00
      3490500.50     10628808.00      3490552.50     10628800.00
      3490652.25     10628829.00      3490694.50     10628811.00
      3490760.75     10628790.00      3490843.50     10628722.00

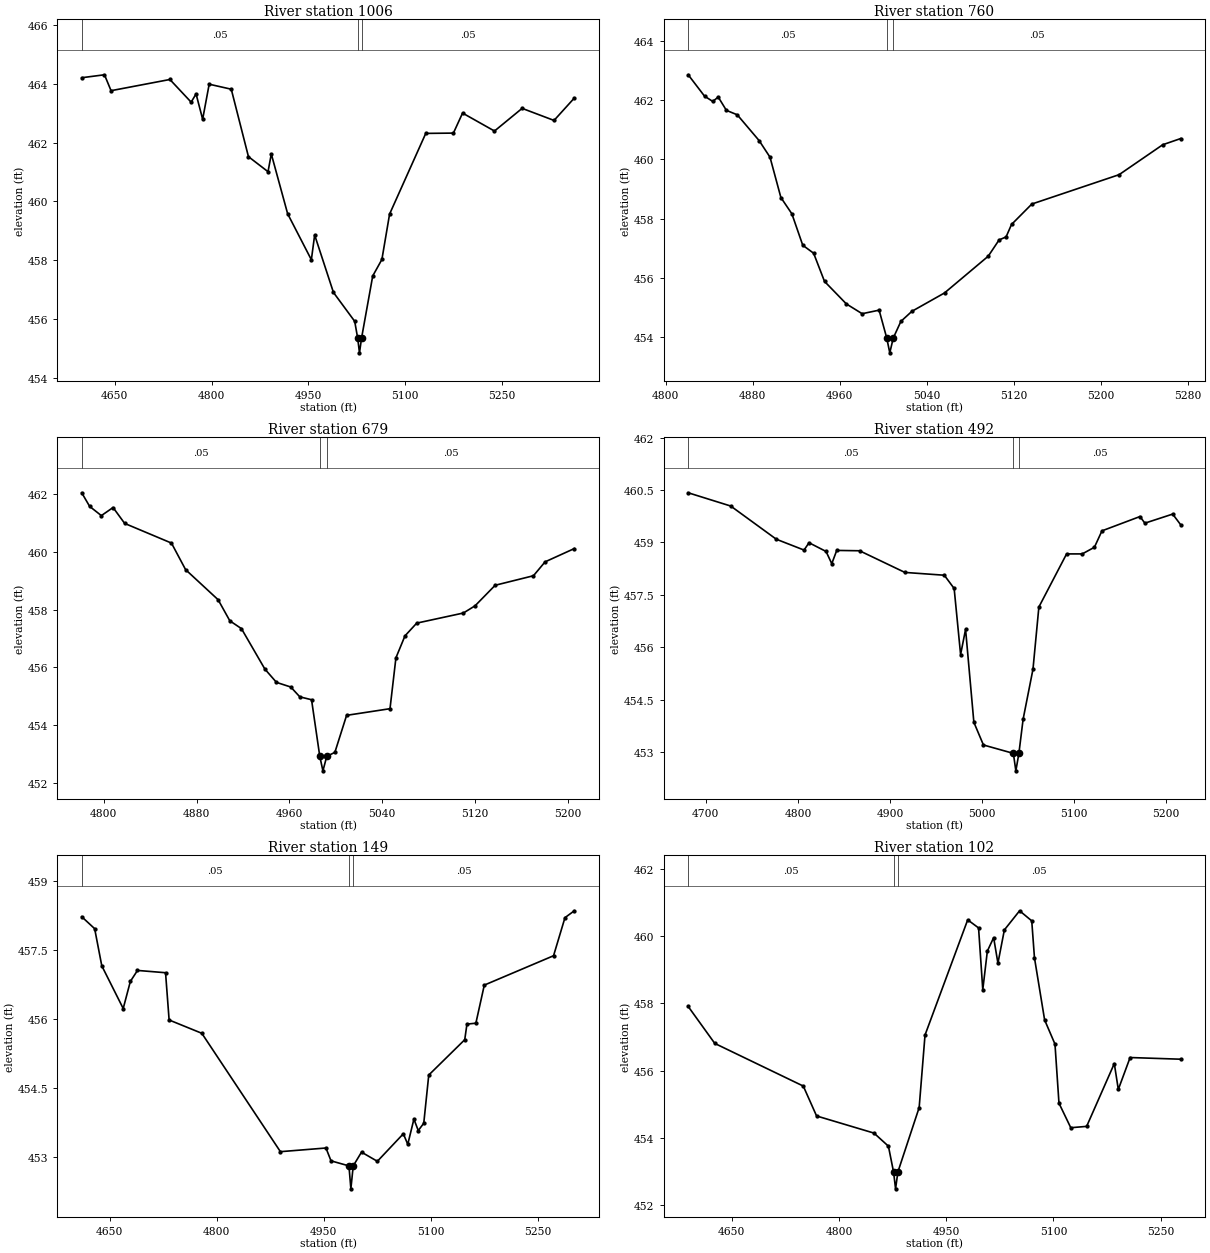
Type RM Length L Ch R = 1,1006,246,246,246
BEGIN DESCRIPTION:
UNT019 IN CCTC 10.0
END DESCRIPTION:
XS GIS Cut Line= 3
      3489958.25     10629585.01      3490031.17     10629129.26
      3489803.32     10628932.48
#Sta/Elev= 30
  4599.1  464.20  4634.3  464.30  4644.5  463.76  4735.6  464.14  4768.5  463.37
  4776.1  463.65  4786.3  462.79  4796.4  463.98  4830.6  463.81  4857.2  461.52
  4887.5  461.01  4892.6  461.61  4917.9  459.58  4954.6  458.02  4959.7  458.86
  4988.8  456.91  5021.7  455.93  5026.3  455.36  5029.1  454.86  5032.3  455.36
  5049.6  457.47  5063.8  458.03  5075.7  459.57  5131.7  462.31  5174.5  462.32
  5188.7  463.00  5238.1  462.39  5280.9  463.16  5330.3  462.75  5361.7  463.51
#Mann=3,-1,0
  4599.1    0.05       0  5026.3   0.035       0  5032.3    0.05       0
Bank Sta=5026.3,5032.3
Exp/Cntr=0.3,0.1

Type RM Length L Ch R = 1,760,81,81,81
BEGIN DESCRIPTION:
Mapping XS 5254f7f8
END DESCRIPTION:
XS GIS Cut Line= 2
      3490226.48     10629215.18      3490192.74     10628763.64
#Sta/Elev= 30
  4820.7  462.85  4835.7  462.13  4843.3  461.95  4848.3  462.10  4855.8  461.65
  4865.8  461.50  4885.9  460.63  4895.9  460.07  4905.9  458.71  4916.0  458.16
  4926.0  457.10  4936.0  456.83  4946.0  455.88  4966.1  455.12  4980.6  454.79
  4996.2  454.91  5003.2  453.97  5006.0  453.47  5009.2  453.97  5016.2  454.53
  5026.3  454.87  5056.3  455.49  5096.5  456.73  5106.5  457.28  5112.9  457.38
  5117.9  457.80  5136.6  458.49  5216.8  459.48  5256.9  460.49  5273.5  460.70
#Mann=3,-1,0
  4820.7    0.05       0  5003.2   0.035       0  5009.2    0.05       0
Bank Sta=5003.2,5009.2
Exp/Cntr=0.3,0.1

Type RM Length L Ch R = 1,679,187,187,187
BEGIN DESCRIPTION:
Mapping XS 5a1ee253
END DESCRIPTION:
XS GIS Cut Line= 2
      3490294.19     10629196.98      3490247.32     10628775.18
#Sta/Elev= 30
  4781.1  462.04  4787.9  461.57  4798.0  461.25  4808.1  461.53  4818.1  460.98
  4858.4  460.30  4870.6  459.38  4898.6  458.34  4908.7  457.61  4918.7  457.34
  4938.9  455.94  4948.9  455.48  4961.2  455.32  4969.0  454.98  4979.1  454.88
  4986.2  452.92  4988.9  452.42  4992.2  452.92  4999.2  453.06  5009.3  454.34
  5046.7  454.57  5051.8  456.33  5059.6  457.09  5069.7  457.53  5109.9  457.88
  5120.0  458.13  5137.3  458.84  5170.3  459.17  5180.3  459.65  5205.5  460.11
#Mann=3,-1,0
  4781.1    0.05       0  4986.2   0.035       0  4992.2    0.05       0
Bank Sta=4986.2,4992.2
Exp/Cntr=0.3,0.1

Type RM Length L Ch R = 1,492,343,343,343
BEGIN DESCRIPTION:
Mapping XS 17982afa
END DESCRIPTION:
XS GIS Cut Line= 2
      3490510.34     10629150.12      3490320.24     10628650.14
#Sta/Elev= 30
  4680.9  460.42  4727.1  460.04  4776.6  459.09  4806.7  458.78  4812.1  458.99
  4830.6  458.74  4836.8  458.39  4842.2  458.77  4867.0  458.76  4916.2  458.14
  4959.0  458.06  4969.7  457.68  4976.7  455.79  4982.1  456.51  4991.1  453.85
  5001.5  453.20  5034.0  452.96  5036.7  452.46  5040.0  452.96  5044.6  453.94
  5055.3  455.37  5061.7  457.15  5091.8  458.67  5108.8  458.67  5122.0  458.86
  5130.2  459.33  5171.5  459.74  5176.8  459.55  5207.0  459.81  5215.8  459.50
#Mann=3,-1,0
  4680.9    0.05       0  5034.0   0.035       0  5040.0    0.05       0
Bank Sta=5034,5040
Exp/Cntr=0.3,0.1

Type RM Length L Ch R = 1,149,47,47,47
BEGIN DESCRIPTION:
Mapping XS df9b2c72
END DESCRIPTION:
XS GIS Cut Line= 6
      3490729.30     10629188.24      3490742.32     10628890.11
      3490729.30     10628821.10      3490705.86     10628772.92
      3490609.51     10628703.91      3490479.27     10628630.98
#Sta/Elev= 30
  4611.0  458.23  4629.1  457.97  4639.1  457.16  4669.1  456.23  4679.1  456.82
  4689.1  457.06  4728.4  457.01  4733.4  455.98  4779.2  455.69  4889.3  453.11
  4953.1  453.19  4960.2  452.91  4985.3  452.80  4988.0  452.30  4991.3  452.80
  5002.9  453.10  5025.1  452.90  5061.5  453.50  5067.7  453.27  5076.3  453.82
  5082.4  453.57  5090.1  453.73  5097.1  454.78  5147.5  455.55  5150.6  455.89
  5163.1  455.91  5174.9  456.74  5271.9  457.38  5287.9  458.21  5301.0  458.36
#Mann=3,-1,0
  4611.0    0.05       0  4985.3   0.035       0  4991.3    0.05       0
Bank Sta=4985.3,4991.3
Exp/Cntr=0.3,0.1

Type RM Length L Ch R = 1,102,73,73,73
BEGIN DESCRIPTION:
Mapping XS 98a9ee83
END DESCRIPTION:
XS GIS Cut Line= 6
      3490781.17     10629189.14      3490804.60     10628915.72
      3490781.17     10628811.55      3490729.08     10628730.82
      3490708.25     10628707.38      3490547.87     10628624.61
#Sta/Elev= 30
  4589.0  457.91  4626.2  456.81  4750.0  455.54  4768.6  454.65  4848.9  454.14
  4869.1  453.75  4876.3  452.98  4879.1  452.48  4882.3  452.98  4912.1  454.90
  4920.3  457.06  4980.0  460.49  4995.2  460.25  5001.1  458.41  5007.5  459.56
  5016.3  459.96  5022.3  459.20  5031.3  460.19  5052.6  460.76  5069.6  460.46
  5073.4  459.36  5087.6  457.51  5102.1  456.79  5107.7  455.03  5124.2  454.30
  5146.4  454.34  5185.1  456.21  5190.7  455.44  5207.2  456.39  5278.1  456.34
#Mann=3,-1,0
  4589.0    0.05       0  4876.3   0.035       0  4882.3    0.05       0
Bank Sta=4876.3,4882.3
Exp/Cntr=0.3,0.1

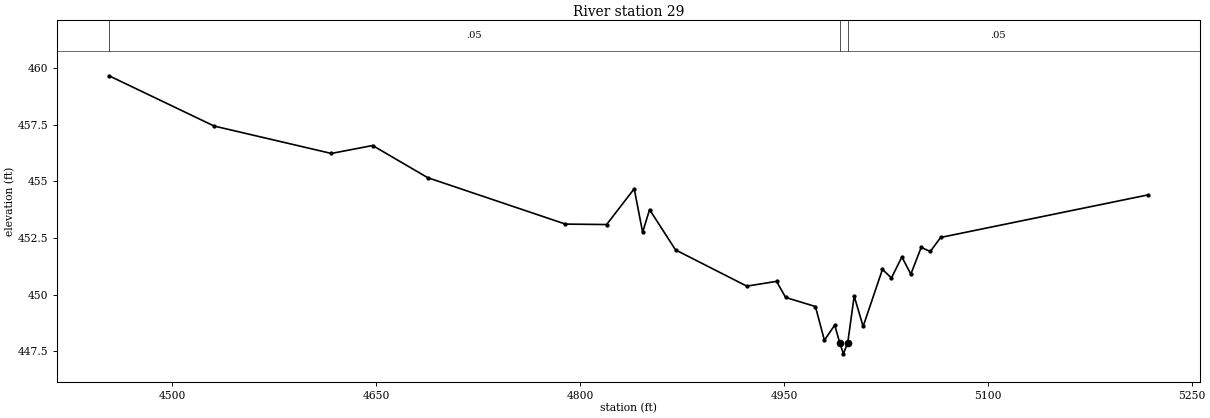
Type RM Length L Ch R = 1,29,0,0,0
BEGIN DESCRIPTION:
UNT019 IN CCTC 1.0
END DESCRIPTION:
XS GIS Cut Line= 3
      3490812.42     10629251.62      3490885.33     10628795.93
      3490656.16     10628598.01
#Sta/Elev= 30
  4453.6  459.66  4530.9  457.44  4617.1  456.23  4647.5  456.58  4688.0  455.16
  4789.3  453.11  4819.6  453.09  4839.9  454.67  4846.1  452.75  4851.2  453.75
  4870.3  451.97  4922.7  450.37  4944.6  450.58  4951.3  449.87  4973.2  449.47
  4979.8  447.98  4987.4  448.65  4991.0  447.88  4993.8  447.38  4997.0  447.88
  5001.7  449.93  5008.3  448.59  5022.5  451.11  5029.1  450.73  5036.8  451.66
  5043.4  450.90  5051.0  452.08  5057.7  451.90  5065.3  452.52  5217.9  454.40
#Mann=3,-1,0
  4453.6    0.05       0  4991.0   0.035       0  4997.0    0.05       0
Bank Sta=4991,4997
Exp/Cntr=0.3,0.1

Chan Stop Cuts=-1