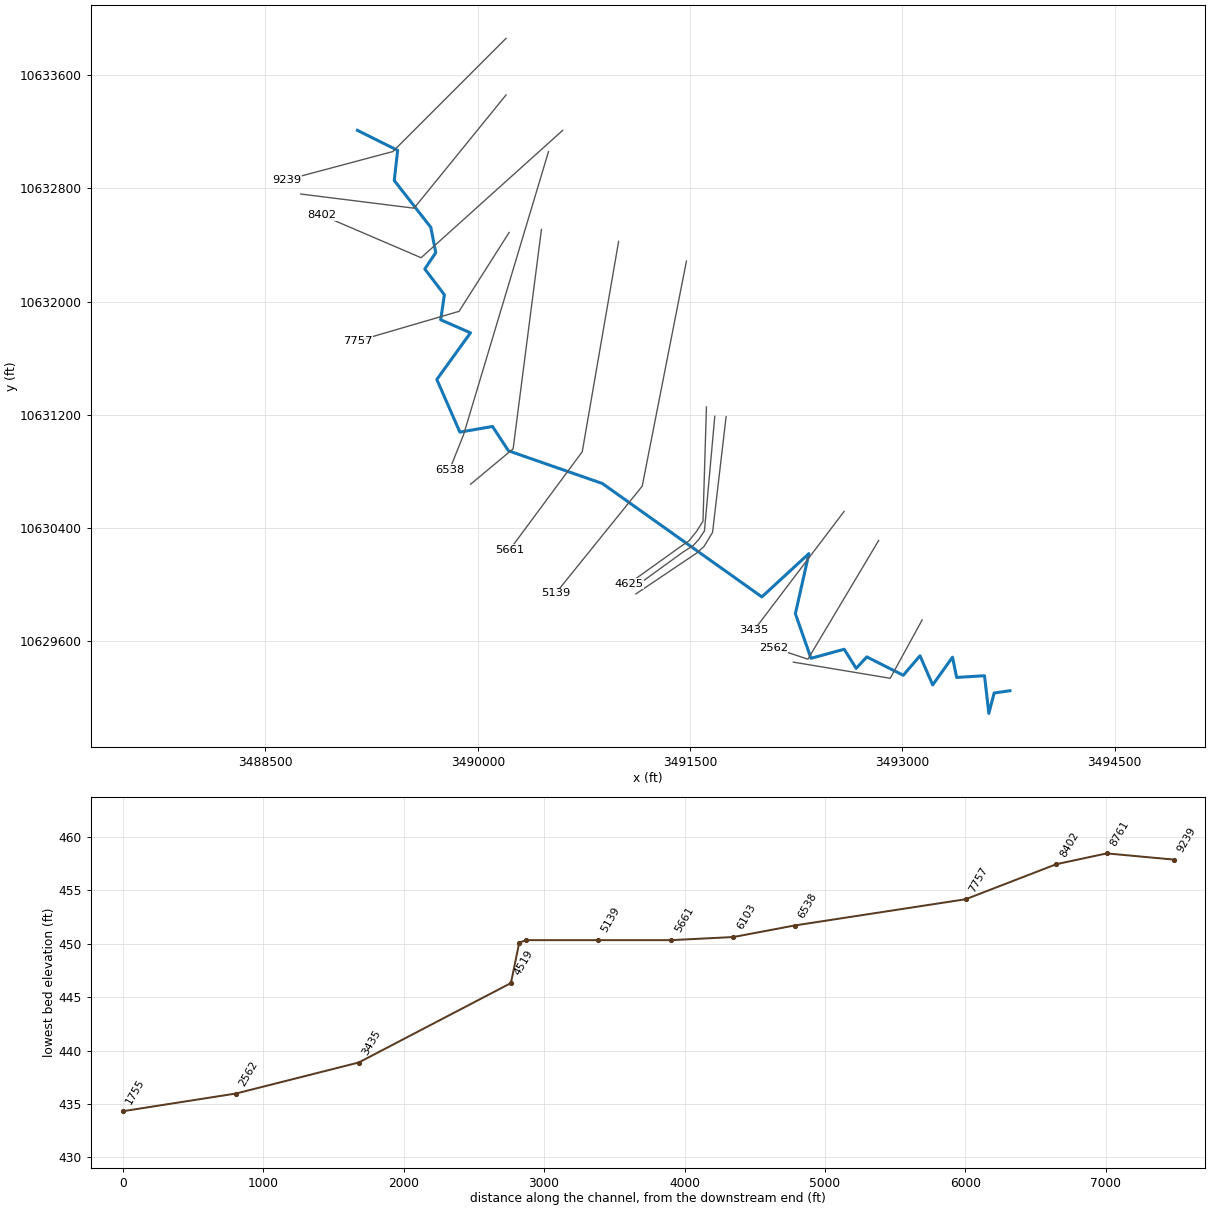
--- UNT020 IN CCTC.prj (project) ---

Proj Title=UNT020 IN CCTC Base Level Engineering
Current Plan=p01
Default Exp/Contr=0.3,0.1
English Units
Geom File=g01
Flow File=f01
Plan File=p01
BEGIN DESCRIPTION:
UNT020 IN CCTC
END DESCRIPTION:

--- UNT020 IN CCTC.p01 (plan) ---

Plan Title=Multiple Run
Short Identifier=Multiple
Geom File=g01
Flow File=f01
Subcritical Flow
K Sum by GR= 0
Std Step Tol= 0.01
Critical Tol= 0.01
Num of Std Step Trials= 20
Max Error Tol= 0.3
Flow Tol Ratio= 0.001
Split Flow NTrial= 30
Split Flow Tol= 0.02
Split Flow Ratio= 0.02
Log Output Level= 0
Friction Slope Method= 1
Unsteady Friction Slope Method= 2
Unsteady Bridges Friction Slope Method= 1
Parabolic Critical Depth
Global Vel Dist=  1 , 1 , 1
Global Log Level= 0
CheckData=True
Encroach Param= -1, 0, 0, 0
BEGIN DESCRIPTION:
Multiple Run
END DESCRIPTION:

--- UNT020 IN CCTC.f01 (steady flow) ---

Flow Title=Multiple
Number of Profiles=7
Profile Names=10-year,25-year,50-year,1pct_min,100-year,1pct_plu,500-year
River Rch & RM= UNT020 IN CCTC,Reach-1,9239
    1629    2270    2805    2526    3416    4620    5057
Boundary for River Rch & Prof#=UNT020 IN CCTC,Reach-1,1
Up Type=0
Dn Type=3
Dn Slope=0.005
Boundary for River Rch & Prof#=UNT020 IN CCTC,Reach-1,2
Up Type=0
Dn Type=3
Dn Slope=0.005
Boundary for River Rch & Prof#=UNT020 IN CCTC,Reach-1,3
Up Type=0
Dn Type=3
Dn Slope=0.005
Boundary for River Rch & Prof#=UNT020 IN CCTC,Reach-1,4
Up Type=0
Dn Type=3
Dn Slope=0.005
Boundary for River Rch & Prof#=UNT020 IN CCTC,Reach-1,5
Up Type=0
Dn Type=3
Dn Slope=0.005
Boundary for River Rch & Prof#=UNT020 IN CCTC,Reach-1,6
Up Type=0
Dn Type=3
Dn Slope=0.005
Boundary for River Rch & Prof#=UNT020 IN CCTC,Reach-1,7
Up Type=0
Dn Type=3
Dn Slope=0.005

--- UNT020 IN CCTC.g01 (geometry) ---

Geom Title=Existing Conditions

River Reach=UNT020 IN CCTC,Reach-1
Reach XY= 30
      3489149.61     10633210.19      3489433.75     10633068.63
      3489409.79     10632855.61      3489668.12     10632524.88
      3489703.02     10632346.24      3489625.42     10632230.61
      3489763.96     10632048.84      3489737.92     10631871.76
      3489948.33     10631779.57      3489710.50     10631450.00
      3489873.50     10631078.00      3490103.75     10631118.00
      3490216.75     10630946.00      3490880.25     10630715.00
      3492007.00     10629914.00      3492339.25     10630220.00
      3492243.75     10629795.00      3492354.25     10629480.00
      3492588.50     10629544.00      3492673.25     10629409.00
      3492748.50     10629490.00      3493005.75     10629360.00
      3493124.25     10629498.00      3493213.75     10629292.00
      3493353.75     10629488.00      3493383.25     10629345.00
      3493580.00     10629357.00      3493610.50     10629091.00
      3493648.00     10629235.00      3493759.50     10629251.00

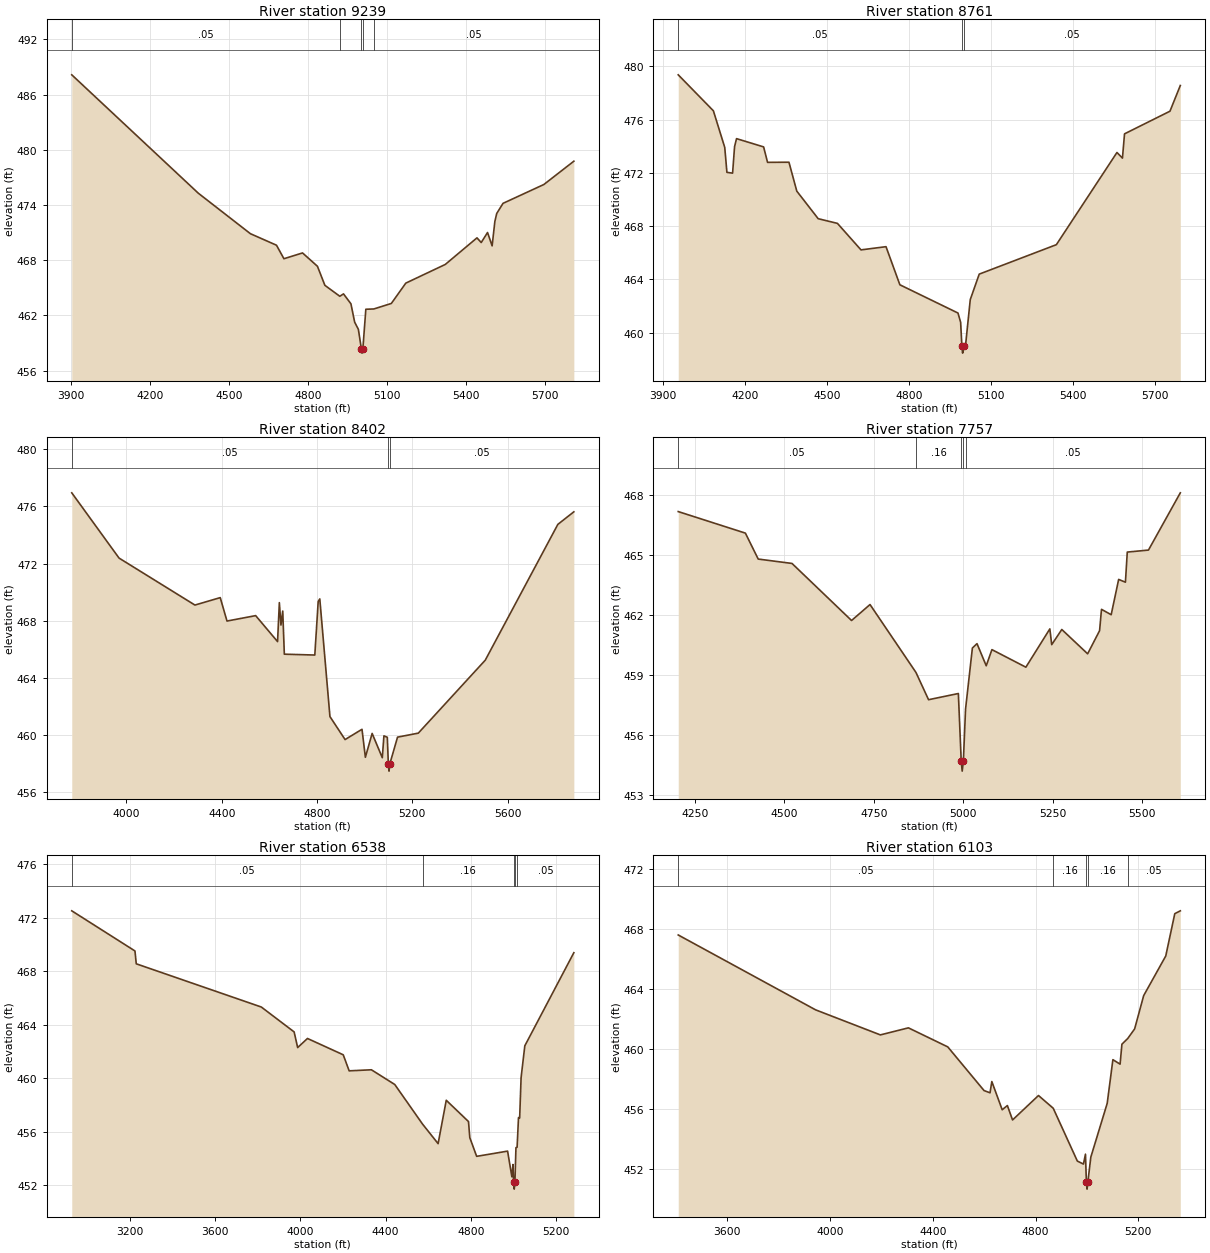
Type RM Length L Ch R = 1,9239,478,478,478
BEGIN DESCRIPTION:
UNT020 IN CCTC 11.0
END DESCRIPTION:
XS GIS Cut Line= 3
      3490199.63     10633860.21      3489399.61     10633060.19
      3488649.61     10632860.19
#Sta/Elev= 30
  3902.4  488.14  4383.3  475.27  4581.2  470.87  4680.2  469.62  4708.5  468.15
  4779.2  468.78  4835.8  467.33  4864.1  465.26  4920.8  464.07  4934.8  464.33
  4963.1  463.25  4977.2  461.26  4991.4  460.47  5002.5  458.39  5005.3  457.89
  5008.5  458.39  5019.7  462.66  5050.0  462.69  5116.6  463.29  5171.6  465.50
  5321.6  467.53  5442.0  470.42  5458.1  469.91  5482.1  471.00  5499.5  469.55
  5509.9  472.20  5517.0  473.07  5540.9  474.17  5696.2  476.22  5810.0  478.75
#Mann=5,-1,0
  3902.4    0.05       0  4920.8    0.16       0  5002.5    0.07       0
  5008.5    0.16       0  5050.0    0.05       0
Bank Sta=5002.5,5008.5
Exp/Cntr=0.3,0.1

Type RM Length L Ch R = 1,8761,359,359,359
BEGIN DESCRIPTION:
UNT020 IN CCTC 10.0
END DESCRIPTION:
XS GIS Cut Line= 3
      3490199.58     10633460.15      3489549.61     10632660.19
      3488749.57     10632760.19
#Sta/Elev= 30
  3956.8  479.36  4085.4  476.66  4127.0  473.91  4134.9  472.04  4155.7  471.98
  4162.9  473.97  4170.1  474.57  4269.2  473.95  4283.6  472.79  4361.9  472.80
  4390.6  470.63  4468.9  468.56  4539.3  468.21  4625.5  466.22  4717.0  466.46
  4767.7  463.60  4980.3  461.48  4990.1  460.78  4994.6  458.97  4997.4  458.47
  5000.6  458.97  5007.7  458.99  5025.3  462.49  5058.1  464.40  5340.3  466.61
  5562.0  473.53  5582.1  473.11  5589.7  474.93  5756.0  476.63  5793.8  478.56
#Mann=3,-1,0
  3956.8    0.05       0  4994.6   0.035       0  5000.6    0.05       0
Bank Sta=4994.6,5000.6
Exp/Cntr=0.3,0.1

Type RM Length L Ch R = 1,8402,645,645,645
BEGIN DESCRIPTION:
UNT020 IN CCTC 9.0
END DESCRIPTION:
XS GIS Cut Line= 3
      3490599.60     10633210.18      3489599.61     10632310.19
      3488899.64     10632610.18
#Sta/Elev= 30
  3770.7  476.95  3969.1  472.38  4287.5  469.09  4393.7  469.61  4422.1  467.97
  4542.4  468.35  4634.3  466.53  4641.8  469.26  4648.5  467.69  4656.0  468.67
  4662.7  465.65  4790.6  465.59  4804.8  469.34  4811.5  469.52  4854.1  461.28
  4917.6  459.67  4988.6  460.39  5002.8  458.43  5031.2  460.10  5073.8  458.40
  5080.6  459.93  5094.8  459.83  5099.2  457.96  5102.0  457.46  5105.2  457.96
  5137.8  459.84  5224.9  460.12  5505.9  465.23  5810.5  474.74  5877.6  475.62
#Mann=3,-1,0
  3770.7    0.05       0  5099.2   0.035       0  5105.2    0.05       0
Bank Sta=5099.2,5105.2
Exp/Cntr=0.3,0.1

Type RM Length L Ch R = 1,7757,1219,1219,1219
BEGIN DESCRIPTION:
UNT020 IN CCTC 8.0
END DESCRIPTION:
XS GIS Cut Line= 3
      3490221.49     10632488.59      3489867.35     10631931.33
      3489154.19     10631723.11
#Sta/Elev= 30
  4203.4  467.19  4391.1  466.11  4426.9  464.81  4521.4  464.59  4687.8  461.73
  4739.4  462.53  4867.7  459.13  4903.0  457.76  4986.3  458.07  4994.3  454.68
  4997.0  454.18  5000.3  454.68  5006.4  457.29  5025.5  460.35  5038.4  460.57
  5064.2  459.46  5080.1  460.27  5175.0  459.39  5242.0  461.31  5247.2  460.52
  5275.4  461.28  5347.6  460.06  5381.0  461.22  5386.3  462.29  5413.4  462.02
  5434.3  463.79  5453.2  463.65  5458.4  465.16  5517.6  465.26  5606.6  468.13
#Mann=5,-1,0
  4203.4    0.05       0  4867.7    0.16       0  4994.3    0.07       0
  5000.3    0.16       0  5006.4    0.05       0
Bank Sta=4994.3,5000.3
Exp/Cntr=0.3,0.1

Type RM Length L Ch R = 1,6538,435,435,435
BEGIN DESCRIPTION:
UNT020 IN CCTC 7.0
END DESCRIPTION:
XS GIS Cut Line= 3
      3490499.61     10633060.19      3489899.61     10631060.19
      3489799.62     10630810.21
#Sta/Elev= 30
  2926.8  472.52  3223.5  469.52  3229.6  468.56  3816.8  465.33  3970.8  463.47
  3987.4  462.30  4033.5  462.98  4201.4  461.76  4229.2  460.56  4333.6  460.64
  4443.3  459.54  4573.8  456.58  4646.8  455.12  4685.1  458.36  4789.5  456.77
  4795.6  455.57  4827.8  454.17  4973.1  454.56  4993.1  452.64  4998.3  453.56
  5001.4  452.22  5004.2  451.72  5007.4  452.22  5012.3  454.82  5017.7  454.85
  5024.3  457.07  5029.7  457.03  5036.4  460.05  5053.9  462.43  5284.1  469.39
#Mann=5,-1,0
  2926.8    0.05       0  4573.8    0.16       0  5001.4    0.07       0
  5007.4    0.16       0  5017.7    0.05       0
Bank Sta=5001.4,5007.4
Exp/Cntr=0.3,0.1

Type RM Length L Ch R = 1,6103,442,442,442
BEGIN DESCRIPTION:
UNT020 IN CCTC 6.0
END DESCRIPTION:
XS GIS Cut Line= 3
      3490449.61     10632510.22      3490249.61     10630960.19
      3489949.61     10630710.19
#Sta/Elev= 30
  3410.0  467.58  3944.4  462.59  4196.5  460.92  4305.5  461.39  4458.7  460.12
  4599.8  457.21  4623.1  457.06  4630.1  457.81  4670.4  455.93  4690.6  456.21
  4710.7  455.25  4811.6  456.88  4869.0  456.03  4962.8  452.51  4986.5  452.31
  4994.4  452.97  4997.9  451.14  5000.6  450.64  5003.9  451.14  5015.2  452.77
  5079.0  456.36  5101.1  459.27  5129.1  458.97  5136.2  460.30  5158.9  460.68
  5185.7  461.32  5220.9  463.54  5306.8  466.18  5341.9  469.00  5363.4  469.19
#Mann=5,-1,0
  3410.0    0.05       0  4869.0    0.16       0  4997.9    0.07       0
  5003.9    0.16       0  5158.9    0.05       0
Bank Sta=4997.9,5003.9
Exp/Cntr=0.3,0.1

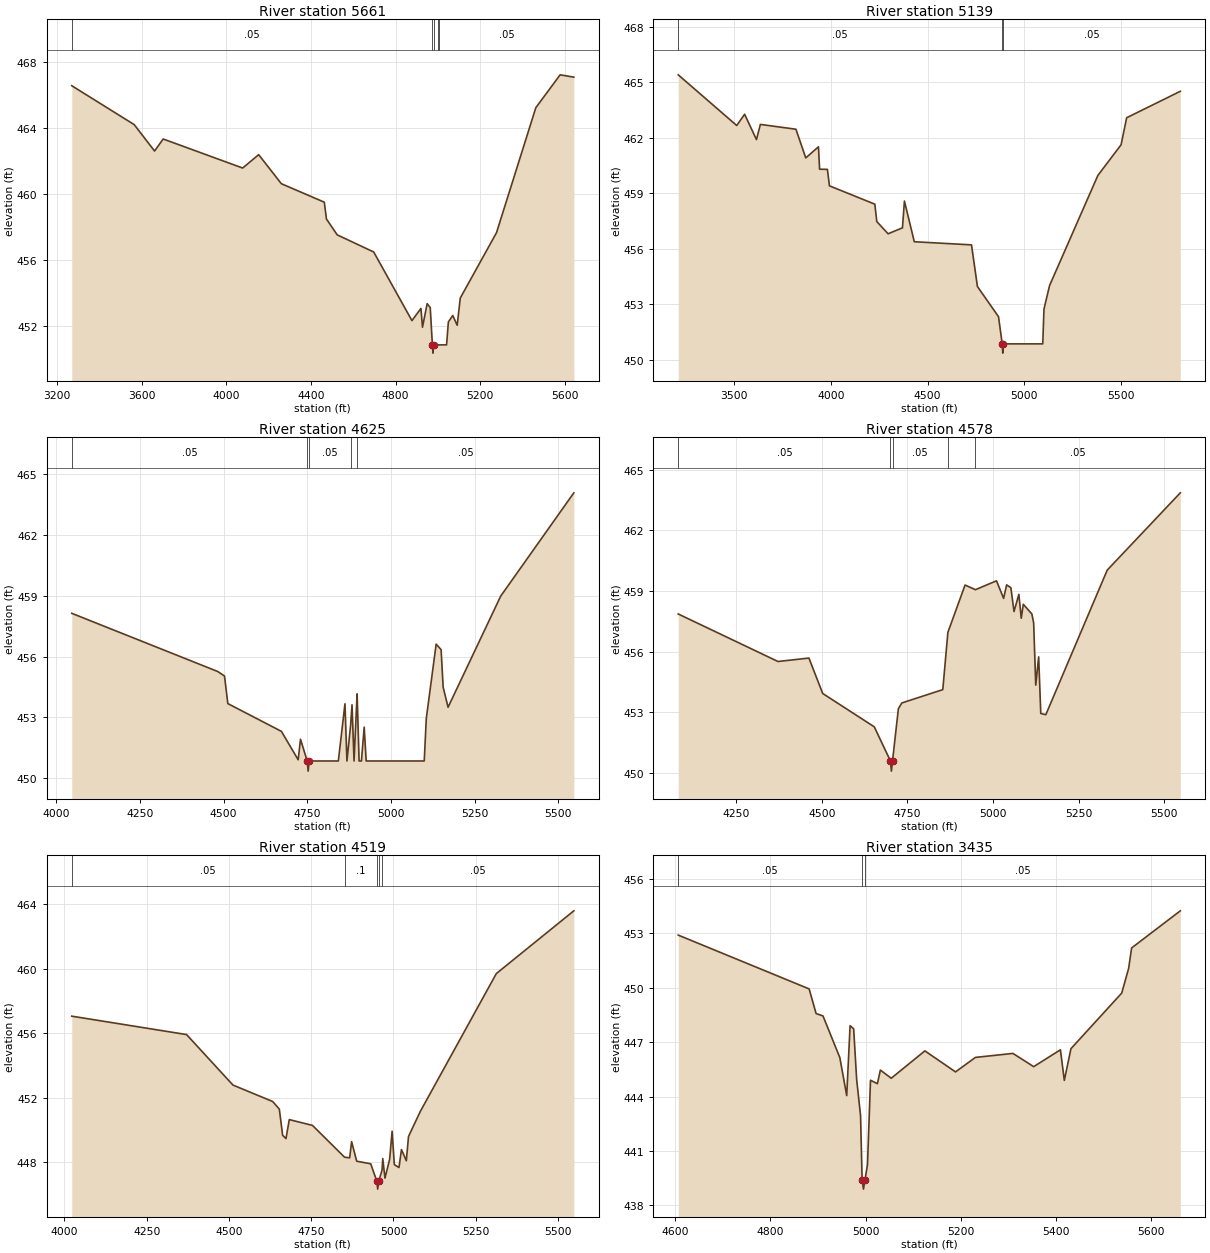
Type RM Length L Ch R = 1,5661,522,522,522
BEGIN DESCRIPTION:
UNT020 IN CCTC 5.0
END DESCRIPTION:
XS GIS Cut Line= 3
      3490994.95     10632425.59      3490738.01     10630939.49
      3490224.44     10630245.49
#Sta/Elev= 30
  3270.1  466.56  3565.2  464.20  3661.2  462.60  3701.8  463.33  4077.3  461.57
  4153.0  462.38  4260.0  460.62  4462.9  459.50  4473.1  458.48  4523.8  457.52
  4696.3  456.48  4876.9  452.32  4919.4  453.06  4926.7  451.92  4948.7  453.35
  4963.3  453.11  4973.4  450.85  4976.2  450.35  4979.4  450.85  5001.2  450.85
  5005.7  450.85  5040.5  450.85  5048.9  452.24  5069.7  452.63  5090.6  452.04
  5105.2  453.69  5276.3  457.65  5462.1  465.23  5576.9  467.22  5641.6  467.08
#Mann=5,-1,0
  3270.1    0.05       0  4973.4   0.035       0  4979.4    0.05       0
  5001.2    0.16       0  5005.7    0.05       0
Bank Sta=4973.4,4979.4
Exp/Cntr=0.3,0.1

Type RM Length L Ch R = 1,5139,514,514,514
BEGIN DESCRIPTION:
UNT020 IN CCTC 4.0
END DESCRIPTION:
XS GIS Cut Line= 3
      3491474.11     10632286.67      3491161.62     10630696.44
      3490550.50     10629939.48
#Sta/Elev= 30
  3212.2  465.39  3514.4  462.65  3555.1  463.26  3616.3  461.89  3636.6  462.71
  3820.1  462.45  3871.0  460.90  3936.5  461.50  3942.4  460.29  3982.8  460.28
  3993.3  459.39  4227.7  458.40  4237.9  457.46  4296.3  456.80  4370.4  457.12
  4380.6  458.57  4431.6  456.37  4727.1  456.20  4757.7  453.95  4866.6  452.32
  4885.8  450.85  4888.6  450.35  4891.8  450.85  5095.1  450.85  5101.5  452.73
  5130.3  454.00  5379.7  459.95  5499.7  461.61  5528.5  463.07  5805.7  464.50
#Mann=3,-1,0
  3212.2    0.05       0  4885.8   0.035       0  4891.8    0.05       0
Bank Sta=4885.8,4891.8
Exp/Cntr=0.3,0.1

Type RM Length L Ch R = 1,4625,47,47,47
BEGIN DESCRIPTION:
UNT020 IN CCTC 3.0
END DESCRIPTION:
XS GIS Cut Line= 6
      3491615.36     10631256.17      3491590.87     10630447.82
      3491543.99     10630374.91      3491491.91     10630309.80
      3491434.62     10630270.74      3491067.43     10630007.71
#Sta/Elev= 30
  4046.7  458.13  4482.9  455.26  4502.9  455.04  4512.9  453.68  4673.0  452.31
  4723.0  450.91  4730.0  451.92  4750.0  450.85  4752.8  450.35  4756.0  450.85
  4843.0  450.85  4862.8  453.67  4868.7  450.85  4879.6  452.60  4883.9  453.62
  4889.9  450.85  4899.1  454.16  4899.9  453.71  4905.0  450.85  4912.0  450.85
  4920.2  452.52  4926.2  450.85  5099.6  450.85  5105.7  452.94  5135.2  456.61
  5150.0  456.34  5156.1  454.49  5170.8  453.50  5328.1  458.98  5546.5  464.07
#Mann=5,-1,0
  4046.7    0.05       0  4750.0   0.035       0  4756.0    0.05       0
  4879.6     0.1       0  4899.9    0.05       0
Bank Sta=4750,4756
Exp/Cntr=0.3,0.1

Type RM Length L Ch R = 1,4578,59,59,59
BEGIN DESCRIPTION:
Mapping XS 427a3c31
END DESCRIPTION:
XS GIS Cut Line= 6
      3491674.39     10631190.19      3491601.29     10630380.11
      3491559.62     10630317.61      3491520.56     10630275.95
      3491447.64     10630229.07      3491096.98     10629974.51
#Sta/Elev= 30
  4080.8  457.87  4372.0  455.52  4462.3  455.69  4502.5  453.94  4653.1  452.29
  4700.3  450.60  4703.1  450.10  4706.3  450.60  4723.4  453.18  4733.4  453.47
  4853.1  454.13  4867.9  456.96  4918.1  459.30  4948.4  459.07  5009.8  459.51
  5030.6  458.64  5039.4  459.31  5051.8  459.17  5061.0  457.99  5075.1  458.84
  5082.1  457.66  5088.1  458.35  5113.1  457.87  5118.3  457.43  5124.4  454.35
  5132.9  455.75  5139.1  452.95  5153.8  452.89  5333.1  460.04  5546.4  463.86
#Mann=5,-1,0
  4080.8    0.05       0  4700.3   0.035       0  4706.3    0.05       0
  4867.9     0.1       0  4948.4    0.05       0
Bank Sta=4700.3,4706.3
Exp/Cntr=0.3,0.1

Type RM Length L Ch R = 1,4519,1084,1084,1084
BEGIN DESCRIPTION:
UNT020 IN CCTC 2.0
END DESCRIPTION:
XS GIS Cut Line= 5
      3491754.25     10631186.76      3491658.58     10630369.70
      3491598.68     10630270.74      3491546.60     10630223.86
      3491117.21     10629935.00
#Sta/Elev= 30
  4022.3  457.05  4371.2  455.91  4512.2  452.78  4633.0  451.76  4653.1  451.29
  4663.2  449.67  4673.3  449.46  4683.4  450.64  4753.8  450.28  4851.4  448.31
  4866.9  448.27  4872.8  449.27  4888.3  448.06  4930.9  447.90  4949.3  446.83
  4952.0  446.33  4955.3  446.83  4965.3  447.51  4967.5  448.22  4974.2  447.01
  4988.4  448.18  4995.9  449.92  5002.6  447.85  5016.8  447.67  5024.3  448.78
  5039.1  448.09  5045.7  449.59  5081.7  451.15  5312.6  459.69  5548.2  463.58
#Mann=5,-1,0
  4022.3    0.05       0  4851.4     0.1       0  4949.3   0.035       0
  4955.3     0.1       0  4965.3    0.05       0
Bank Sta=4949.3,4955.3
Exp/Cntr=0.3,0.1

Type RM Length L Ch R = 1,3435,873,873,873
BEGIN DESCRIPTION:
Mapping XS c5cf23dc
END DESCRIPTION:
XS GIS Cut Line= 2
      3492588.27     10630518.14      3491950.22     10629676.95
#Sta/Elev= 30
  4606.0  452.91  4881.3  449.94  4895.9  448.58  4910.4  448.45  4945.8  446.15
  4960.3  444.05  4967.4  447.91  4974.9  447.74  4981.2  444.94  4989.4  442.95
  4992.7  439.39  4995.5  438.89  4998.7  439.39  5004.0  440.25  5010.3  444.90
  5024.8  444.71  5031.1  445.46  5053.9  445.01  5124.7  446.52  5189.1  445.36
  5231.0  446.16  5309.8  446.38  5353.5  445.65  5409.7  446.58  5417.9  444.89
  5431.8  446.64  5538.6  449.71  5553.2  451.08  5559.4  452.20  5661.8  454.25
#Mann=3,-1,0
  4606.0    0.05       0  4992.7   0.035       0  4998.7    0.05       0
Bank Sta=4992.7,4998.7
Exp/Cntr=0.3,0.1

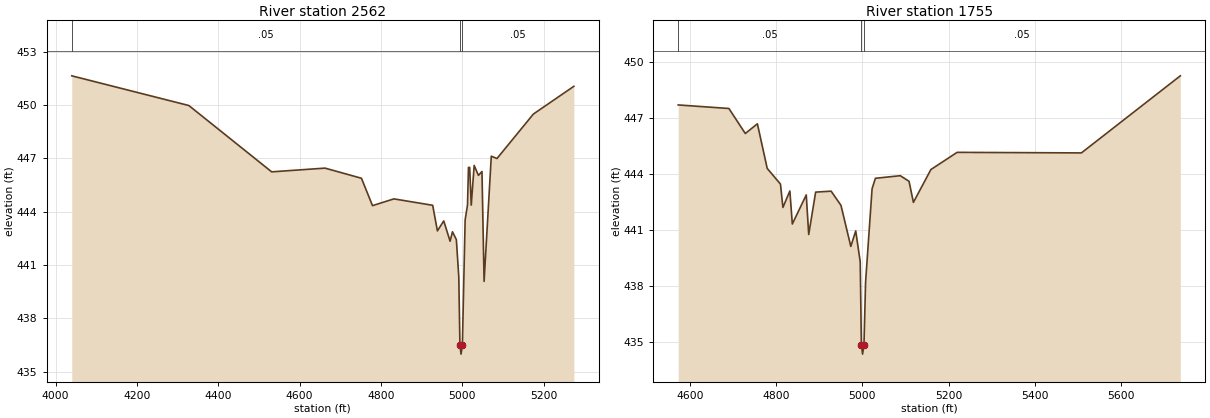
Type RM Length L Ch R = 1,2562,807,807,807
BEGIN DESCRIPTION:
Mapping XS e8188786
END DESCRIPTION:
XS GIS Cut Line= 3
      3492832.09     10630312.42      3492332.09     10629473.88
      3492087.04     10629555.57
#Sta/Elev= 30
  4039.9  451.64  4327.8  449.97  4531.5  446.24  4662.6  446.45  4752.2  445.88
  4779.4  444.34  4832.0  444.72  4927.4  444.36  4939.0  442.92  4954.6  443.48
  4970.2  442.34  4976.0  442.87  4985.6  442.43  4991.6  440.32  4994.4  436.49
  4997.1  435.99  5000.4  436.49  5007.2  443.54  5013.0  444.37  5015.4  446.49
  5018.3  446.49  5022.2  444.37  5029.4  446.60  5039.9  446.04  5048.6  446.26
  5053.8  440.08  5071.5  447.12  5085.5  446.99  5175.0  449.49  5274.5  451.05
#Mann=3,-1,0
  4039.9    0.05       0  4994.4   0.035       0  5000.4    0.05       0
Bank Sta=4994.4,5000.4
Exp/Cntr=0.3,0.1

Type RM Length L Ch R = 1,1755,0,0,0
BEGIN DESCRIPTION:
Mapping XS 593232cb
END DESCRIPTION:
XS GIS Cut Line= 3
      3493139.46     10629751.17      3492913.79     10629338.88
      3492229.25     10629453.04
#Sta/Elev= 30
  4573.3  447.68  4690.8  447.49  4728.8  446.15  4756.8  446.67  4779.6  444.28
  4810.3  443.44  4816.0  442.19  4832.1  443.07  4837.8  441.30  4870.1  442.86
  4875.8  440.74  4891.9  443.01  4927.8  443.06  4950.6  442.30  4973.4  440.10
  4984.8  440.93  4995.2  439.28  4997.9  434.83  5000.7  434.33  5003.9  434.83
  5007.6  438.17  5022.7  443.19  5030.4  443.75  5088.1  443.89  5108.4  443.59
  5118.5  442.46  5159.1  444.22  5219.9  445.14  5508.0  445.11  5737.3  449.24
#Mann=3,-1,0
  4573.3    0.05       0  4997.9   0.035       0  5003.9    0.05       0
Bank Sta=4997.9,5003.9
Exp/Cntr=0.3,0.1

Chan Stop Cuts=-1