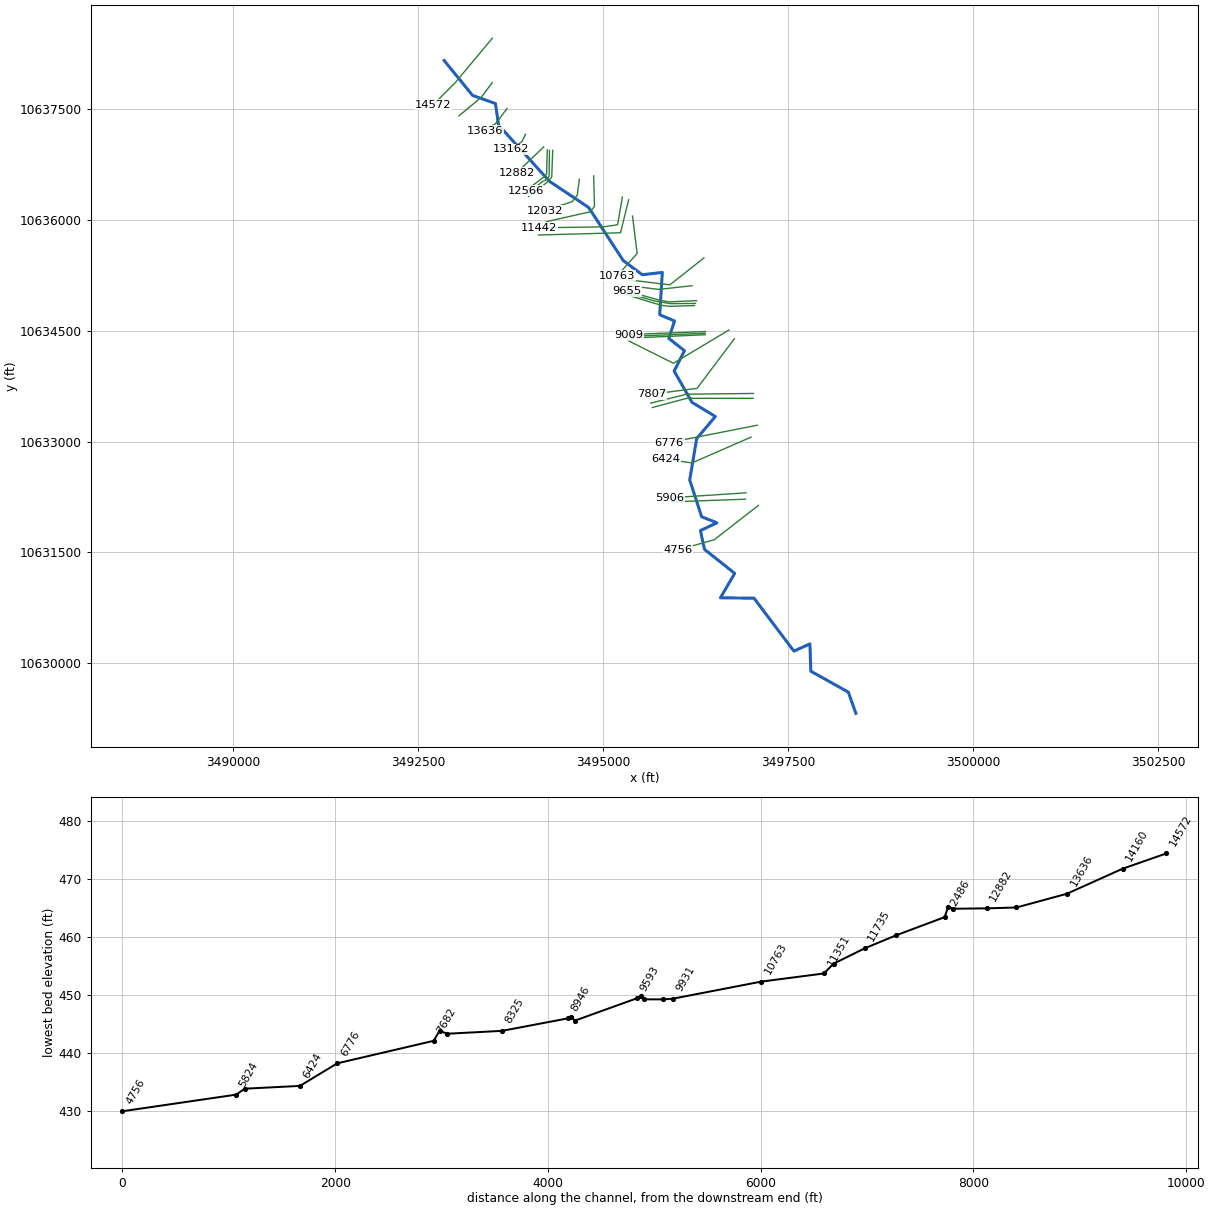
--- UNT021 IN CCTC.prj (project) ---

Proj Title=UNT021 IN CCTC Base Level Engineering
Current Plan=p01
Default Exp/Contr=0.3,0.1
English Units
Geom File=g01
Flow File=f01
Plan File=p01
Y Axis Title=Elevation
X Axis Title(PF)=Main Channel Distance
X Axis Title(XS)=Station
BEGIN DESCRIPTION:
UNT021 IN CCTC
END DESCRIPTION:
DSS Export Rating Curves= 0
DSS Export Rating Curve Sorted= 0
DSS Export Volume Flow Curves= 0
DXF OffsetX= 0
DXF OffsetY= 0
DXF ScaleX= 1
DXF ScaleY= 10

--- UNT021 IN CCTC.p01 (plan) ---

Plan Title=Multiple Run
Program Version=4.10
Short Identifier=Multiple
Geom File=g01
Flow File=f01
Subcritical Flow
K Sum by GR= 0
Std Step Tol= 0.01
Critical Tol= 0.01
Num of Std Step Trials= 20
Max Error Tol= 0.3
Flow Tol Ratio= 0.001
Split Flow NTrial= 30
Split Flow Tol= 0.02
Split Flow Ratio= 0.02
Log Output Level= 0
Friction Slope Method= 1
Unsteady Friction Slope Method= 2
Unsteady Bridges Friction Slope Method= 1
Parabolic Critical Depth
Global Vel Dist= 1 , 1 , 1
Global Log Level= 0
CheckData=True
Encroach Param=-1 ,0,0, 0
BEGIN DESCRIPTION:
Multiple Run
END DESCRIPTION:
Computation Interval=1HOUR
Output Interval=1HOUR
Run HTab= 0
Run UNet= 0
Run PostProcess= 0
Run WQNet= 0
UNET Theta= 1
UNET Theta Warmup= 1
UNET ZTol= 0.02
UNET ZSATol= 0.05
UNET MxIter= 20
UNET MaxInSteps= 0
UNET DtIC= 0
UNET DtMin= 0
UNET MaxCRTS= 20
UNET WFStab= 2
UNET SFStab= 1
UNET WFX= 1
UNET SFX= 1
UNET DSS MLevel= 4
UNET DZMax Abort= 100
UNET Convert EG Bridges= 0
UNET Use Existing IB Tables=-1
UNET Froude Reduction=False
UNET Froude Limit= 1
UNET Froude Power= 10
UNET Time Slicing=0,0, 5
UNET Junction Losses=0
Instantaneous Interval=1HOUR
Write IC File= 0
Write IC File at Sim End=0
Echo Input=False
Echo Parameters=False
Echo Output=False
Write Detailed= 0
WQ AD Non Conservative
WQ ULTIMATE=-1
WQ Max Comp Step=1HOUR
WQ Output Interval=15MIN
WQ Output Selected Increments= 0
WQ Output face flow=0
WQ Output face velocity=0
WQ Output face area=0
WQ Output face dispersion=0
WQ Output cell volume=0
WQ Output cell surface area=0
WQ Output cell continuity=0
WQ Output cumulative cell continuity=0
WQ Output face conc=0
WQ Output face dconc_dx=0
WQ Output face courant=0
WQ Output face peclet=0
WQ Output face adv mass=0
WQ Output face disp mass=0
WQ Output cell mass=0
WQ Output cell source sink temp=0
WQ Output cell source sink nsm=0
WQ Output MaxMinRange=-1
WQ Daily Max Min Mean=-1
WQ Daily Range=0
WQ Daily Time=0
WQ Create Restart=0
WQ Fixed Restart=0
WQ System Summary=0
WQ Use Fixed Temperature=0
Sorting and Armoring Iterations= 10
XS Update Threshold= 0.02
Hydraulics Update Threshold= 0.02
Energy Slope Method= 1
Volume Change Method= 0
XS Weighting Method= 0
Number of US Weighted Cross Sections= 1
Number of DS Weighted Cross Sections= 1
Upstream XS Weight=0.25
Main XS Weight=0.5
Downstream XS Weight=0.25
Number of DS XS's Weighted with US Boundary= 1
Upstream Boundary Weight= 1
Weight of XSs Associated with US Boundary= 0
Number of US XS's Weighted with DS Boundary= 1
Downstream Boundary Weight= 0.5
Weight of XSs Associated with DS Boundary= 0.5
Sediment Output Level= 4
Mass or Volume Output= 0
Output Increment Type= 1
Profile and TS Output Increment= 10
XS Output Flag= 0
XS Output Increment= 10
Disregard all LS=0
Disregard all Conn=0
Disregard all Breaches=0
Disregard all Pumps=0

--- UNT021 IN CCTC.f01 (steady flow) ---

Flow Title=Multiple
Program Version=4.10
Number of Profiles= 7
Profile Names=10-year,25-year,50-year,1pct_min,100-year,1pct_plu,500-year
River Rch & RM=UNT021 IN CCTC,Reach-1         ,14572
     541     702     828     714     966    1307    1310
River Rch & RM=UNT021 IN CCTC,Reach-1         ,11442
     846    1131    1360    1194    1615    2184    2271
River Rch & RM=UNT021 IN CCTC,Reach-1         ,9931
    1234    1685    2054    1827    2471    3341    3564
River Rch & RM=UNT021 IN CCTC,Reach-1         ,7738
    1574    2172    2666    2384    3224    4359    4702
River Rch & RM=UNT021 IN CCTC,Reach-1         ,6776
    1574    2172    2666    2384    3224    4359    4702
Boundary for River Rch & Prof#=UNT021 IN CCTC,Reach-1         , 1
Up Type= 0
Dn Type= 3
Dn Slope=0.005
Boundary for River Rch & Prof#=UNT021 IN CCTC,Reach-1         , 2
Up Type= 0
Dn Type= 3
Dn Slope=0.005
Boundary for River Rch & Prof#=UNT021 IN CCTC,Reach-1         , 3
Up Type= 0
Dn Type= 3
Dn Slope=0.005
Boundary for River Rch & Prof#=UNT021 IN CCTC,Reach-1         , 4
Up Type= 0
Dn Type= 3
Dn Slope=0.005
Boundary for River Rch & Prof#=UNT021 IN CCTC,Reach-1         , 5
Up Type= 0
Dn Type= 3
Dn Slope=0.005
Boundary for River Rch & Prof#=UNT021 IN CCTC,Reach-1         , 6
Up Type= 0
Dn Type= 3
Dn Slope=0.005
Boundary for River Rch & Prof#=UNT021 IN CCTC,Reach-1         , 7
Up Type= 0
Dn Type= 3
Dn Slope=0.005
DSS Import GetInterval= 0
DSS Import GetPeak= 0
DSS Import FillOption= 0

--- UNT021 IN CCTC.g01 (geometry) ---

Geom Title=Existing Conditions
Program Version=4.10

River Reach=UNT021 IN CCTC  ,Reach-1
Reach XY= 30
      3492849.61     10638160.19        3493233.       10637688.
        3493543.       10637577.       3493584.5       10637287.
        3494271.       10636526.        3494804.       10636169.
      3495272.25       10635449.      3495528.25       10635259.
        3495799.       10635290.        3495764.       10634717.
        3495964.       10634633.       3495886.5       10634397.
      3496098.75       10634230.      3495958.75       10633955.
      3496201.25       10633530.        3496516.       10633339.
      3496263.25       10633039.       3496169.5       10632480.
       3496331.5       10631981.      3496536.75       10631900.
      3496314.25       10631794.        3496369.       10631540.
      3496777.75       10631215.        3496585.       10630884.
        3497039.       10630879.      3497577.75       10630162.
      3497794.75       10630260.      3497806.75       10629890.
      3498313.75       10629607.        3498416.       10629319.

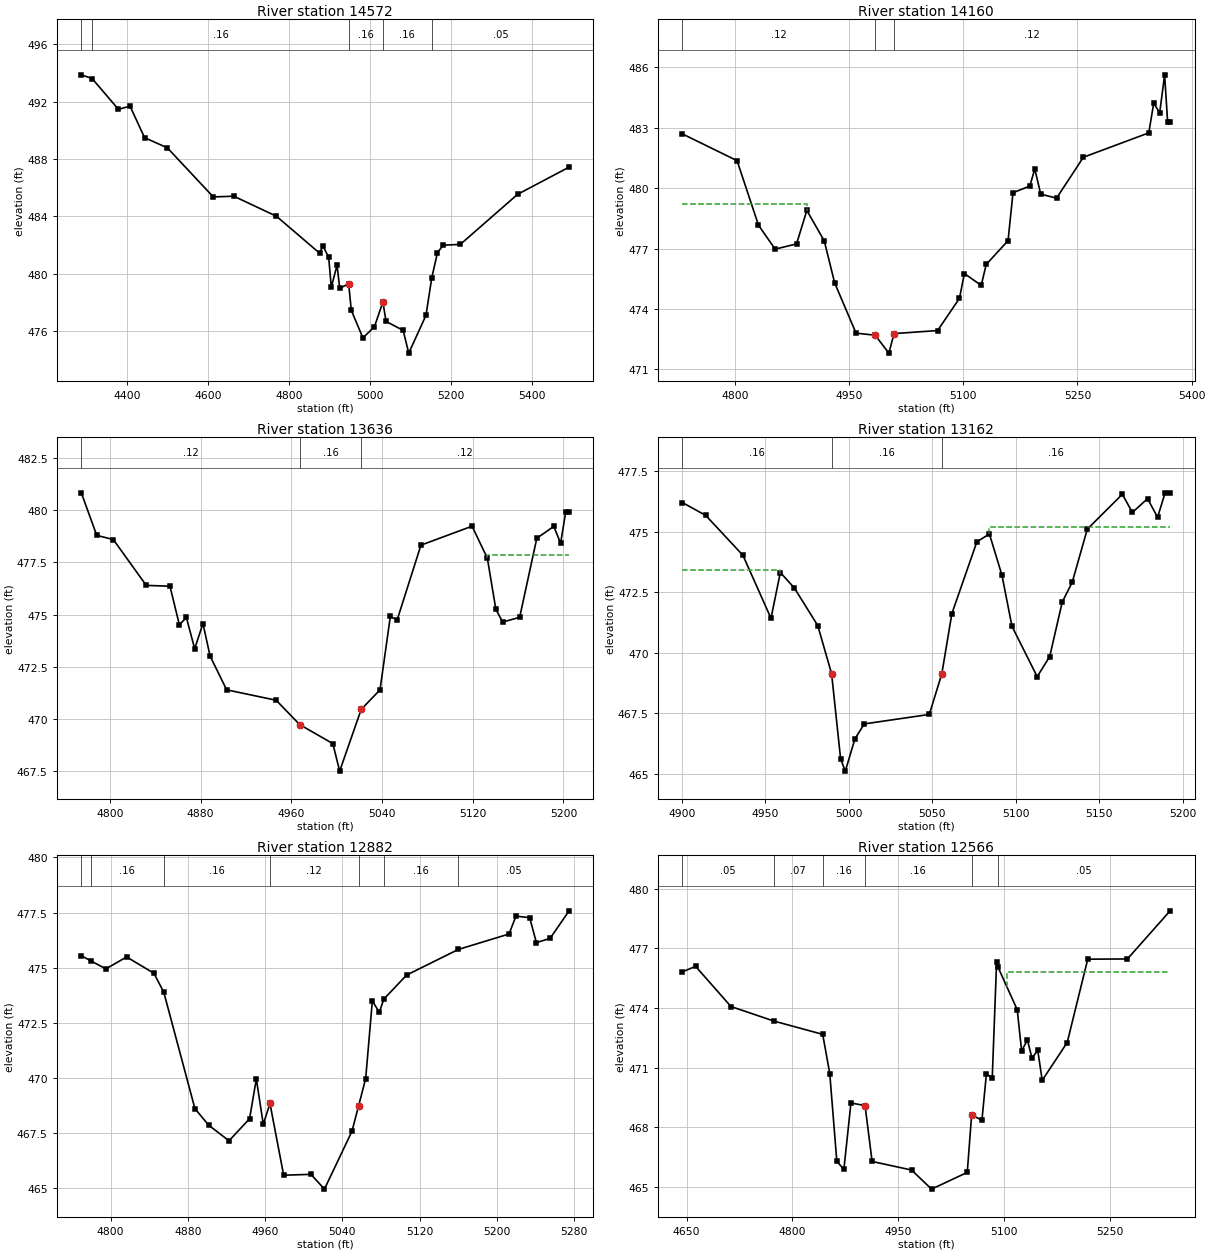
Type RM Length L Ch R = 1 ,14572   ,412,412,412
BEGIN DESCRIPTION:
UNT021 IN CCTC 26.0
END DESCRIPTION:
XS GIS Cut Line= 3
      3493499.61     10638460.19      3492999.61     10637860.19
       3492699.6     10637560.18
#Sta/Elev= 30
  4286.3  493.87  4313.1  493.61  4378.1  491.46  4406.7  491.69  4442.5  489.49
  4499.1  488.77  4612.4  485.35  4663.1   485.4  4768.6     484  4875.3  481.42
  4883.1  481.94  4897.5  481.14    4904  479.05  4918.3  480.59  4924.8  478.97
 4946.93  479.29  4953.4  477.44  4982.1  475.51  5010.7   476.3  5031.5  478.02
  5039.3  476.66  5081.5  476.04  5095.4  474.45    5138  477.09  5152.2   479.7
  5166.3  481.46  5180.5  481.98  5222.9  482.04  5364.3  485.53  5491.6  487.43
#Mann= 5 ,-1 , 0
  4286.3     .05       0  4313.1     .16       0 4946.93     .16       0
  5031.5     .16       0  5152.2     .05       0
Bank Sta=4946.93,5031.5
XS Rating Curve= 0 ,0
Exp/Cntr=0.3,0.1

Type RM Length L Ch R = 1 ,14160   ,524,524,524
BEGIN DESCRIPTION:
UNT021 IN CCTC 25.0
END DESCRIPTION:
XS GIS Cut Line= 3
      3493499.59     10637860.17      3493349.61     10637660.19
       3493049.6     10637410.18
#Sta/Elev= 30
  4731.2  482.69  4803.1  481.36  4831.2  478.16  4853.1  476.97  4881.2  477.23
  4894.7  478.89  4917.6  477.38  4931.2   475.3  4959.3   472.8  4984.4   472.7
  5002.4  471.81  5009.2  472.78  5066.4  472.93  5095.1  474.53  5101.6  475.76
  5123.7  475.17  5130.2  476.21  5158.9  477.39  5165.4  479.77  5187.5   480.1
    5194  480.95  5201.8   479.7  5222.6   479.5  5257.8  481.53  5343.7  482.74
  5350.2  484.22    5358  483.73  5364.5  485.62  5368.4   483.3  5371.7   483.3
#Mann= 3 , 0 , 0
  4731.2     .12       0  4984.4     .16       0  5009.2     .12       0
#XS Ineff= 2 , 0
         4894.49  479.19
Permanent Ineff=
       F       F
Bank Sta=4984.4,5009.2
XS Rating Curve= 0 ,0
Exp/Cntr=0.3,0.1

Type RM Length L Ch R = 1 ,13636   ,474,474,474
BEGIN DESCRIPTION:
UNT021 IN CCTC 24.0
END DESCRIPTION:
XS GIS Cut Line= 3
      3493699.63     10637510.21      3493549.61     10637310.19
      3493399.61     10637210.19
#Sta/Elev= 30
  4774.7  480.84  4788.3   478.8  4802.9   478.6    4832   476.4  4852.9  476.36
  4861.2  474.51  4867.4  474.86  4874.7  473.36    4882  474.57  4888.3  473.01
  4902.9  471.39  4946.6  470.89  4967.4  469.72  4996.6  468.81  5002.6  467.49
  5021.6  470.45  5038.2  471.39  5047.3  474.91  5053.3  474.74  5074.3  478.33
  5119.4  479.24  5132.9   477.7  5140.4  475.25  5146.4  474.64  5161.4  474.87
  5176.5  478.66  5191.5  479.23  5197.5  478.42    5202  479.92    5205  479.92
#Mann= 3 , 0 , 0
  4774.7     .12       0  4967.4     .16       0  5021.6     .12       0
#XS Ineff= 2 , 0
                         5132.61          477.87
Permanent Ineff=
       F       F
Bank Sta=4967.4,5021.6
XS Rating Curve= 0 ,0
Exp/Cntr=0.3,0.1

Type RM Length L Ch R = 1 ,13162   ,280,280,280
BEGIN DESCRIPTION:
UNT021 IN CCTC 23.0
END DESCRIPTION:
XS GIS Cut Line= 3
      3493949.61     10637160.19      3493899.61     10637060.19
       3493749.6     10636960.18
#Sta/Elev= 30
  4900.3  476.21  4914.3  475.68  4936.6  474.03  4953.4  471.43    4959  473.32
  4967.4  472.68  4981.4  471.13  4989.7  469.14  4995.1  465.62  4997.9  465.12
  5003.7  466.46  5009.3  467.07  5048.2  467.46  5055.7  469.14  5061.7  471.62
  5076.7  474.59  5084.2  474.91  5091.7  473.21  5097.7   471.1  5112.8  469.02
  5120.3  469.85  5127.8   472.1  5133.8  472.92  5142.8  475.11  5163.8  476.55
  5169.8   475.8  5178.9  476.37  5184.9   475.6  5189.4  476.61  5192.4  476.61
#Mann= 3 , 0 , 0
  4900.3     .16       0  4989.7     .16       0  5055.7     .16       0
#XS Ineff= 2 , 0
         4958.81  473.41 5084.09           475.2
Permanent Ineff=
       F       F
Bank Sta=4989.7,5055.7
XS Rating Curve= 0 ,0
Exp/Cntr=0.3,0.1

Type RM Length L Ch R = 1 ,12882   ,316,316,316
BEGIN DESCRIPTION:
Mapping XS a5041bbd
END DESCRIPTION:
XS GIS Cut Line= 2
      3494195.66     10636990.29      3493831.06     10636640.87
#Sta/Elev= 30
  4769.7  475.55  4779.6  475.31  4795.2  474.95  4816.6  475.49  4844.9  474.75
  4855.1  473.89  4887.3  468.62  4901.5  467.87  4922.6  467.16  4943.9  468.16
  4950.9  469.96  4958.1  467.91    4965  468.85  4979.2   465.6  5007.5  465.64
  5021.4  464.97  5049.9  467.59  5056.8  468.75  5064.1  469.98    5071   473.5
  5078.2  472.98  5082.9  473.58  5106.5  474.67    5160  475.83  5212.5  476.53
  5219.7  477.34  5233.9  477.27  5240.8  476.14    5255  476.33  5274.7  477.58
#Mann= 7 ,-1 , 0
  4769.7     .05       0  4779.6     .16       0  4855.1     .16       0
    4965     .12       0  5056.8     .16       0  5082.9     .16       0
    5160     .05       0
Bank Sta=4965,5056.8
XS Rating Curve= 0 ,0
Exp/Cntr=0.3,0.1

Type RM Length L Ch R = 1 ,12566   ,47,47,47
BEGIN DESCRIPTION:
Mapping XS 4154e47d
END DESCRIPTION:
XS GIS Cut Line= 4
      3494243.39     10636949.03      3494234.71     10636623.52
       3494206.5     10636588.79      3493950.43     10636395.66
#Sta/Elev= 30
    4644  475.82  4662.8   476.1  4712.9  474.08  4773.6  473.35  4842.9  472.68
  4852.9  470.71  4862.9   466.3  4872.9  465.89  4882.9  469.23  4902.9   469.1
  4912.9  466.29  4968.8  465.86  4997.1   464.9  5047.7  465.74  5053.9  468.63
  5068.5  468.36  5074.8  470.69  5083.1   470.5  5089.3  476.33    5091  476.08
  5118.5  473.92  5124.7  471.85    5133   472.4  5139.3  471.49  5147.6  471.87
  5153.9  470.37  5189.3  472.27  5218.4  476.46  5274.6  476.47  5335.1  478.89
#Mann= 6 ,-1 , 0
    4644     .05       0  4773.6     .07       0  4842.9     .16       0
  4902.9     .16       0  5053.9     .16       0    5091     .05       0
#XS Ineff= 2 , 0
                         5104.09          475.81
Permanent Ineff=
       F       F
Bank Sta=4902.9,5053.9
XS Rating Curve= 0 ,0
Exp/Cntr=0.3,0.1

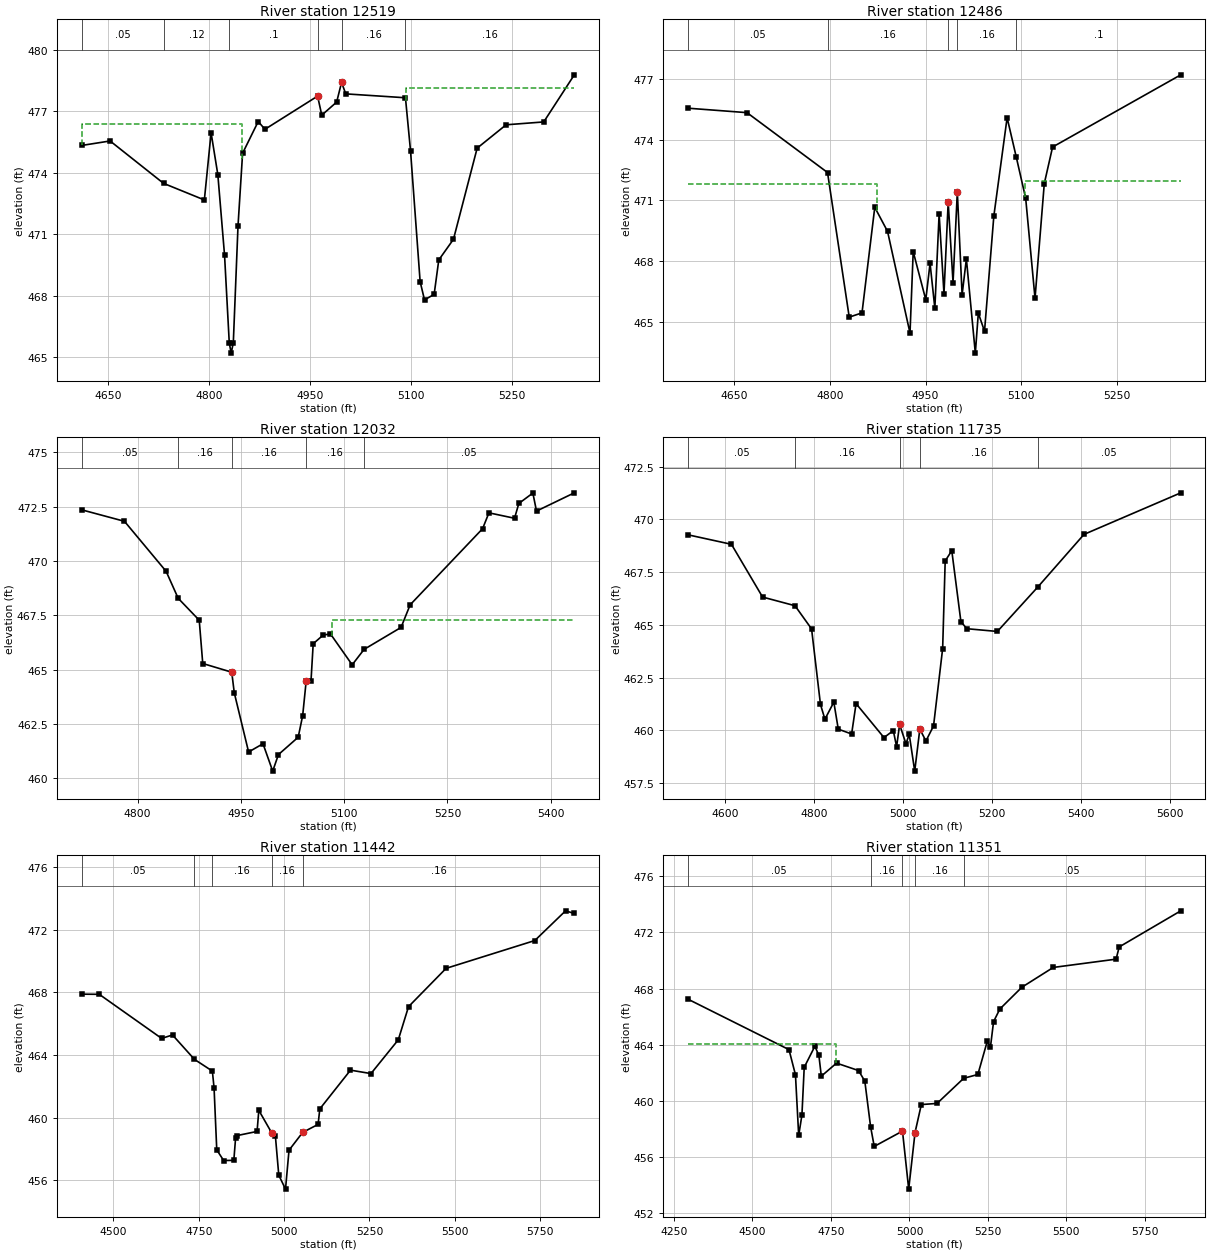
Type RM Length L Ch R = 1 ,12519   ,33,33,33
BEGIN DESCRIPTION:
Mapping XS 88ea7f3b
END DESCRIPTION:
XS GIS Cut Line= 6
      3494273.77     10636942.57      3494269.43     10636701.64
      3494269.43     10636597.47      3494234.71     10636549.73
      3494173.95     10636517.18      3493974.42     10636352.35
#Sta/Elev= 30
  4611.1  475.33  4653.5  475.55  4732.9  473.48  4793.5  472.67  4803.5  475.95
  4813.5  473.91  4823.5  469.97  4830.5  465.69  4833.3  465.19  4836.5  465.69
  4843.5  471.41  4850.3  474.95  4873.5   476.5  4883.5  476.12  4961.7  477.74
  4967.9  476.81    4990  477.45  4997.3  478.41  5003.5  477.85  5092.2  477.66
  5099.7  475.08    5114  468.68  5120.5  467.79  5134.8  468.06  5141.7  469.74
  5163.5  470.75  5198.7   475.2  5241.7  476.34  5297.6  476.48    5343  478.78
#Mann= 6 ,-1 , 0
  4611.1     .05       0  4732.9     .12       0  4830.5      .1       0
  4961.7     .16       0  4997.3     .16       0  5092.2     .16       0
#XS Ineff= 2 , 0
         4849.55  476.38 5092.73          478.16
Permanent Ineff=
       F       F
Bank Sta=4961.7,4997.3
XS Rating Curve= 0 ,0
Exp/Cntr=0.3,0.1

Type RM Length L Ch R = 1 ,12486   ,454,454,454
BEGIN DESCRIPTION:
UNT021 IN CCTC 22.0
END DESCRIPTION:
XS GIS Cut Line= 4
      3494317.18     10636942.52      3494304.15     10636582.28
      3494239.05      10636508.5      3493989.49      10636319.7
#Sta/Elev= 30
  4577.9  475.56  4670.3  475.34  4796.4  472.38  4830.4  465.23  4850.4  465.44
  4870.4  470.66  4890.4  469.47  4925.6  464.44  4930.6  468.47  4950.3  466.09
    4957  467.89  4964.5  465.67  4971.2  470.33  4978.8  466.39  4985.4  470.91
    4993  466.94  4999.7  471.42  5007.2  466.34  5013.9  468.11  5027.9  463.45
  5032.6  465.43  5042.3  464.53  5056.9  470.23  5077.7  475.09    5092  473.15
  5106.8   471.1  5121.4  466.16  5135.9  471.83  5148.9  473.64  5349.7  477.21
#Mann= 5 ,-1 , 0
  4577.9     .05       0  4796.4     .16       0  4985.4     .16       0
  4999.7     .16       0    5092      .1       0
#XS Ineff= 2 , 0
          4873.3  471.83 5106.25          471.97
Permanent Ineff=
       F       F
Bank Sta=4985.4,4999.7
XS Rating Curve= 0 ,0
Exp/Cntr=0.3,0.1

Type RM Length L Ch R = 1 ,12032   ,297,297,297
BEGIN DESCRIPTION:
UNT021 IN CCTC 21.0
END DESCRIPTION:
XS GIS Cut Line= 4
      3494677.42     10636551.94      3494648.77     10636335.76
      3494578.46     10636247.21      3494212.96     10636127.97
#Sta/Elev= 30
  4718.7  472.35    4781  471.82  4841.5  469.52    4859  468.28  4889.6  467.27
  4894.7  465.28  4936.8  464.88  4940.5  463.93  4961.3  461.21  4982.2  461.59
  4996.3  460.33  5004.6  461.09  5033.3  461.89  5039.8  462.88  5044.9  464.47
  5051.9  464.47  5055.1  466.19  5069.7  466.59  5080.2  466.64  5111.7  465.22
    5129  465.93  5182.7  466.94  5195.9  467.98  5301.1  471.48  5310.3  472.21
  5347.5  471.96  5353.7  472.64  5374.1  473.12  5379.4  472.29  5434.3  473.13
#Mann= 5 ,-1 , 0
  4718.7     .05       0    4859     .16       0  4936.8     .16       0
  5044.9     .16       0    5129     .05       0
#XS Ineff= 2 , 0
                         5081.82          467.27
Permanent Ineff=
       F       F
Bank Sta=4936.8,5044.9
XS Rating Curve= 0 ,0
Exp/Cntr=0.3,0.1

Type RM Length L Ch R = 1 ,11735   ,293,293,293
BEGIN DESCRIPTION:
UNT021 IN CCTC 20.0
END DESCRIPTION:
XS GIS Cut Line= 4
      3494871.08     10636597.77      3494881.93     10636181.07
      3494816.83     10636109.45       3494237.4     10635979.25
#Sta/Elev= 30
  4516.3  469.27  4613.9  468.82  4683.9  466.32  4756.7  465.91    4794  464.81
    4814  461.23    4824  460.53    4844  461.34    4854  460.06    4884  459.83
    4894  461.27  4956.7  459.66  4977.7  459.99  4985.1  459.23  4991.9  460.28
  5006.1  459.37  5013.5  459.81  5025.8  458.07  5037.3  460.06    5051   459.5
  5068.1  460.21  5088.6  463.88  5094.3  468.03  5109.1  468.52  5129.6  465.16
  5142.8  464.82  5211.6  464.69  5302.2  466.79  5406.3  469.29  5623.8  471.26
#Mann= 5 ,-1 , 0
  4516.3     .05       0  4756.7     .16       0  4991.9     .16       0
  5037.3     .16       0  5302.2     .05       0
Bank Sta=4991.9,5037.3
XS Rating Curve= 0 ,0
Exp/Cntr=0.3,0.1

Type RM Length L Ch R = 1 ,11442   ,91,91,91
BEGIN DESCRIPTION:
Mapping XS 0c517e3d
END DESCRIPTION:
XS GIS Cut Line= 5
      3495259.54      10636311.3      3495194.43     10635935.84
      3495040.35     10635911.97      3494903.63     10635905.46
      3494133.97     10635894.62
#Sta/Elev= 30
  4406.6  467.89  4458.5  467.88  4641.2  465.06  4673.1  465.28  4737.3  463.72
  4789.8  462.97  4794.8   461.9  4802.7  457.93  4822.9  457.25  4852.7  457.26
  4857.8  458.67  4863.4  458.85  4920.8  459.11  4925.9  460.46  4964.4  458.99
  4974.4  458.83  4984.4  456.31  5004.1  455.42  5014.4  457.91  5054.5  459.05
  5099.6  459.56  5104.6  460.55  5194.5  463.03  5254.5  462.81  5334.5  464.97
  5364.5  467.09  5474.5  469.54  5734.5  471.32  5824.6  473.22  5850.2  473.05
#Mann= 5 ,-1 , 0
  4406.6     .05       0  4737.3     .16       0  4789.8     .16       0
  4964.4     .16       0  5054.5     .16       0
Bank Sta=4964.4,5054.5
XS Rating Curve= 0 ,0
Exp/Cntr=0.3,0.1

Type RM Length L Ch R = 1 ,11351   ,588,588,588
BEGIN DESCRIPTION:
UNT021 IN CCTC 19.0
END DESCRIPTION:
XS GIS Cut Line= 3
       3495343.5     10636272.53      3495233.99     10635827.15
      3494123.55     10635796.99
#Sta/Elev= 30
  4294.7  467.25  4616.3  463.66  4636.9  461.87  4647.2  457.55  4657.5     459
  4664.8   462.4  4698.7   463.9  4711.5  463.25  4719.3  461.77  4767.7   462.7
  4837.8  462.17  4857.8  461.42  4876.2  458.18  4887.8  456.77  4977.8  457.86
  4997.6  453.73  5017.8  457.76  5037.8  459.75  5087.9  459.83  5172.8  461.62
  5217.9  461.89  5247.9  464.26  5257.9  463.83  5267.9  465.65  5287.9  466.55
    5358   468.1    5458  469.51  5658.1   470.1  5668.1  470.97  5864.2  473.54
#Mann= 5 ,-1 , 0
  4294.7     .05       0  4876.2     .16       0  4977.8     .16       0
  5017.8     .16       0  5172.8     .05       0
#XS Ineff= 2 , 0
         4767.61  464.08
Permanent Ineff=
       F       F
Bank Sta=4977.8,5017.8
XS Rating Curve= 0 ,0
Exp/Cntr=0.3,0.1

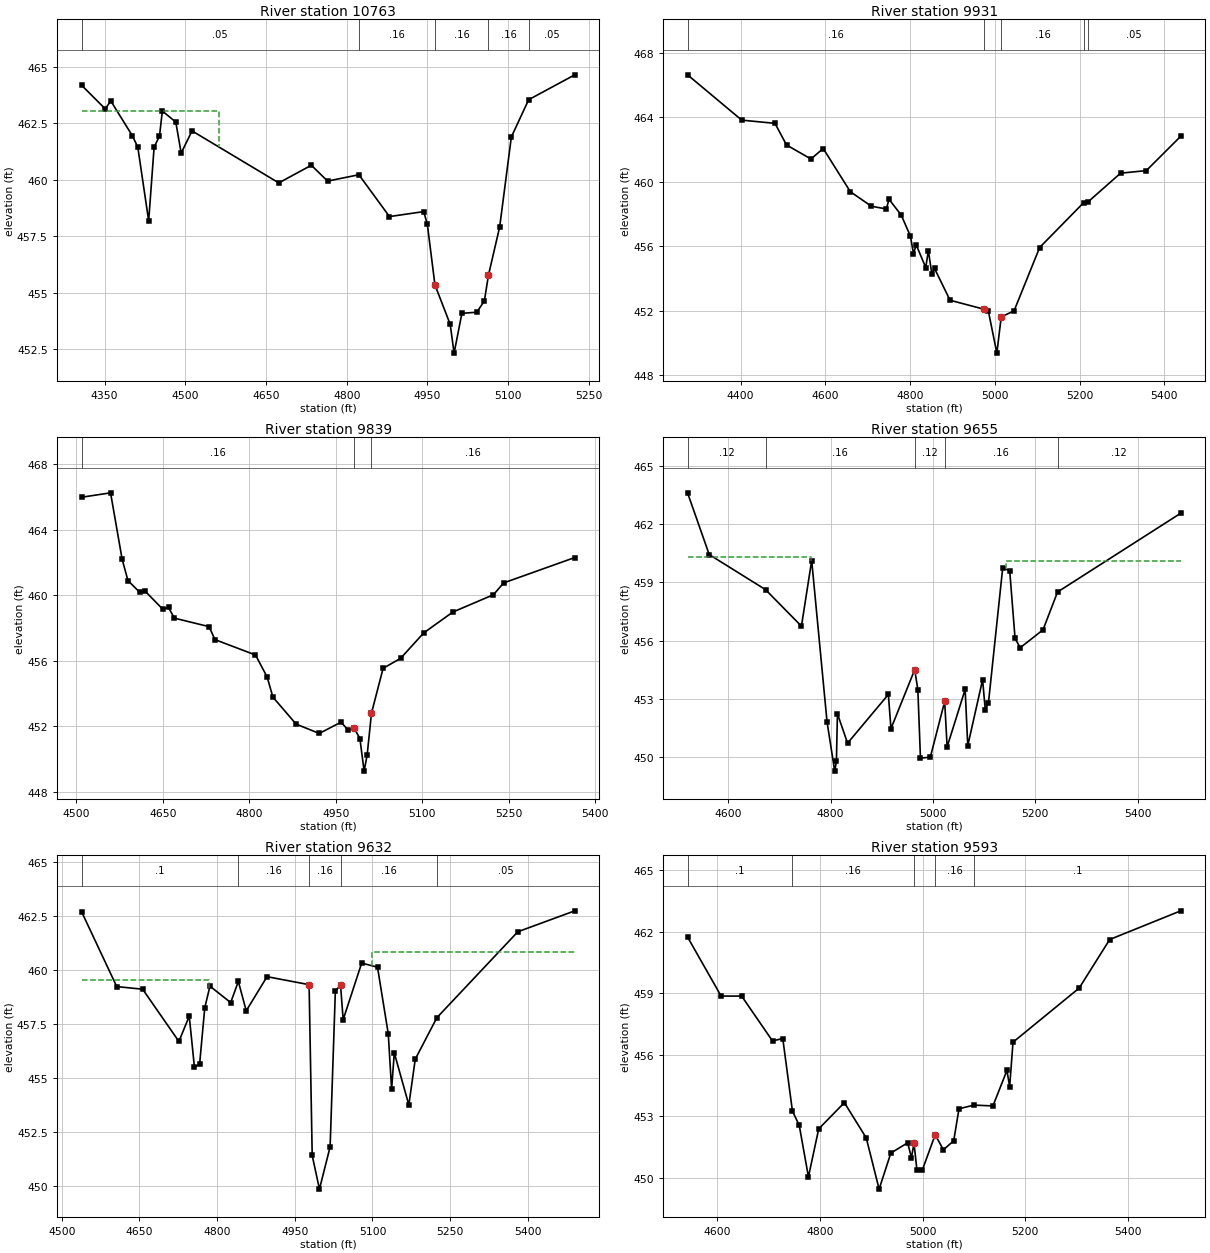
Type RM Length L Ch R = 1 ,10763   ,832,832,832
BEGIN DESCRIPTION:
UNT021 IN CCTC 18.0
END DESCRIPTION:
XS GIS Cut Line= 3
      3495396.25     10636053.94      3495458.76     10635546.09
      3495188.46      10635244.6
#Sta/Elev= 30
  4307.2  464.18  4351.3  463.13  4361.4  463.49  4401.7  461.94  4411.7  461.44
  4431.9  458.18    4442  461.44    4452  461.93  4457.3  463.04  4482.3  462.55
  4492.3  461.18  4512.5  462.16  4673.7  459.86  4734.2  460.64  4764.4  459.94
  4822.6  460.22  4879.4  458.37    4943  458.59  4949.7  458.04  4963.9  455.35
  4992.3   453.6  4999.5  452.33    5014  454.09  5041.7  454.14  5055.8  454.64
  5063.3  455.77  5084.2  457.91  5105.9  461.89  5138.1  463.54  5223.8  464.64
#Mann= 5 ,-1 , 0
  4307.2     .05       0  4822.6     .16       0  4963.9     .16       0
  5063.3     .16       0  5138.1     .05       0
#XS Ineff= 2 , 0
         4563.41  463.06
Permanent Ineff=
       F       F
Bank Sta=4963.9,5063.3
XS Rating Curve= 0 ,0
Exp/Cntr=0.3,0.1

Type RM Length L Ch R = 1 ,9931    ,92,92,92
BEGIN DESCRIPTION:
UNT021 IN CCTC 17.0
END DESCRIPTION:
XS GIS Cut Line= 3
      3496361.99     10635486.89      3495901.89     10635122.29
      3495328.93     10635191.74
#Sta/Elev= 30
  4274.7  466.64  4402.6  463.83  4481.1  463.63  4508.3  462.29    4566  461.42
  4594.9  462.07    4659  459.39  4708.7  458.49  4743.9  458.32  4750.3  458.92
  4779.1  457.94  4800.9  456.63    4808  455.54  4814.4   456.1  4836.9  454.69
  4843.2  455.73  4851.3   454.3  4857.7  454.63  4894.3  452.66  4974.8   452.1
  4984.9  451.97  5004.8  449.38  5015.1  451.63  5045.4     452  5105.8  455.93
  5209.6  458.71  5219.2  458.74  5296.8  460.54  5357.6   460.7  5438.9  462.83
#Mann= 5 ,-1 , 0
  4274.7     .16       0  4974.8     .16       0  5015.1     .16       0
  5209.6     .16       0  5219.2     .05       0
Bank Sta=4974.8,5015.1
XS Rating Curve= 0 ,0
Exp/Cntr=0.3,0.1

Type RM Length L Ch R = 1 ,9839    ,184,184,184
BEGIN DESCRIPTION:
UNT021 IN CCTC 16.0
END DESCRIPTION:
XS GIS Cut Line= 3
       3496199.6     10635110.19      3495749.61     10635060.19
      3495349.58     10635110.19
#Sta/Elev= 30
  4509.1  465.98  4559.4  466.25  4579.5  462.19  4589.6  460.89  4609.7  460.19
  4619.8  460.23  4649.9  459.15    4660  459.25  4670.1   458.6  4730.4  458.08
  4740.5  457.29  4810.9  456.35  4831.1  455.01  4841.1  453.78  4881.4  452.13
  4921.6  451.56  4959.3  452.25  4971.9  451.76    4982  451.89  4992.1  451.25
  4999.4  449.26  5004.7  450.25  5012.2   452.8  5032.4  455.54  5062.6  456.14
  5102.9   457.7  5153.3  458.97  5223.9  460.03  5241.5  460.75    5365   462.3
#Mann= 3 , 0 , 0
  4509.1     .16       0    4982     .16       0  5012.2     .16       0
Bank Sta=4982,5012.2
XS Rating Curve= 0 ,0
Exp/Cntr=0.3,0.1

Type RM Length L Ch R = 1 ,9655    ,23,23,23
BEGIN DESCRIPTION:
Mapping XS 76dac98c
END DESCRIPTION:
XS GIS Cut Line= 4
      3496261.86     10634908.18      3495886.82     10634891.25
       3495755.3     10634915.99      3495317.84     10635038.37
#Sta/Elev= 30
  4520.6  463.61  4562.9  460.43    4673  458.62  4743.1  456.74  4763.1  460.12
  4793.1  451.81  4808.1  449.27  4811.4  449.77  4813.4  452.23  4833.2  450.71
  4912.9  453.22    4918  451.46  4964.4   454.5  4970.5  453.46  4975.6  449.94
  4994.9  449.99  5022.9  452.86  5027.7  450.52  5062.9  453.48    5068  450.58
    5097  453.98  5102.2  452.43  5108.4  452.78  5136.3  459.75    5150  459.59
  5160.4  456.11  5170.5  455.63    5215  456.55  5243.4   458.5  5484.1  462.56
#Mann= 5 ,-1 , 0
  4520.6     .12       0    4673     .16       0  4964.4     .12       0
  5022.9     .16       0  5243.4     .12       0
#XS Ineff= 2 , 0
         4762.73  460.32  5142.5          460.12
Permanent Ineff=
       F       F
Bank Sta=4964.4,5022.9
XS Rating Curve= 0 ,0
Exp/Cntr=0.3,0.1

Type RM Length L Ch R = 1 ,9632    ,39,39,39
BEGIN DESCRIPTION:
Mapping XS 2abf23ab
END DESCRIPTION:
XS GIS Cut Line= 5
      3496247.52     10634870.41      3495905.04     10634867.81
      3495820.41     10634882.13      3495684.99     10634905.57
      3495314.22     10635014.85
#Sta/Elev= 30
  4538.3  462.69  4606.2  459.22  4656.2   459.1  4726.2  456.68  4746.2  457.85
  4756.2  455.49  4766.2  455.63  4776.2  458.25  4786.2  459.24  4826.2  458.48
    4841  459.46  4856.2   458.1  4896.4  459.68  4977.6  459.31  4983.6   451.4
  4997.6  449.84  5018.2   451.8  5028.3  459.01  5038.3  459.29  5043.4  457.69
  5079.1  460.31  5109.7  460.12  5130.5  457.03  5136.9  454.47  5142.1  456.15
  5170.2  453.74  5182.6  455.86  5224.3  457.78  5380.6  461.76  5490.6  462.73
#Mann= 5 ,-1 , 0
  4538.3      .1       0    4841     .16       0  4977.6     .16       0
  5038.3     .16       0  5224.3     .05       0
#XS Ineff= 2 , 0
         4785.23  459.53 5098.86          460.82
Permanent Ineff=
       F       F
Bank Sta=4977.6,5038.3
XS Rating Curve= 0 ,0
Exp/Cntr=0.3,0.1

Type RM Length L Ch R = 1 ,9593    ,584,584,584
BEGIN DESCRIPTION:
Mapping XS 98767ec5
END DESCRIPTION:
XS GIS Cut Line= 5
        3496235.     10634841.66      3495889.53     10634831.24
      3495809.67     10634841.66       3495705.5      10634867.7
      3495297.48     10634994.45
#Sta/Elev= 30
  4542.3  461.75  4607.7  458.87  4647.7  458.87  4707.8  456.68  4727.8   456.8
  4746.6  453.26  4759.9  452.56  4777.8  450.05  4797.8  452.39  4847.8  453.67
  4890.4  451.95  4915.5  449.45  4938.3  451.21  4971.1  451.71  4978.4  450.99
  4983.5  451.68  4989.1  450.39  4999.5  450.37  5024.7   452.1  5040.7  451.37
  5060.8  451.81  5071.1  453.37    5100  453.55  5137.2  453.51  5164.5  455.24
  5169.8  454.45  5176.3  456.62  5305.2  459.26  5364.7  461.63  5503.1  463.03
#Mann= 5 ,-1 , 0
  4542.3      .1       0  4746.6     .16       0  4983.5     .16       0
  5024.7     .16       0    5100      .1       0
Bank Sta=4983.5,5024.7
XS Rating Curve= 0 ,0
Exp/Cntr=0.3,0.1

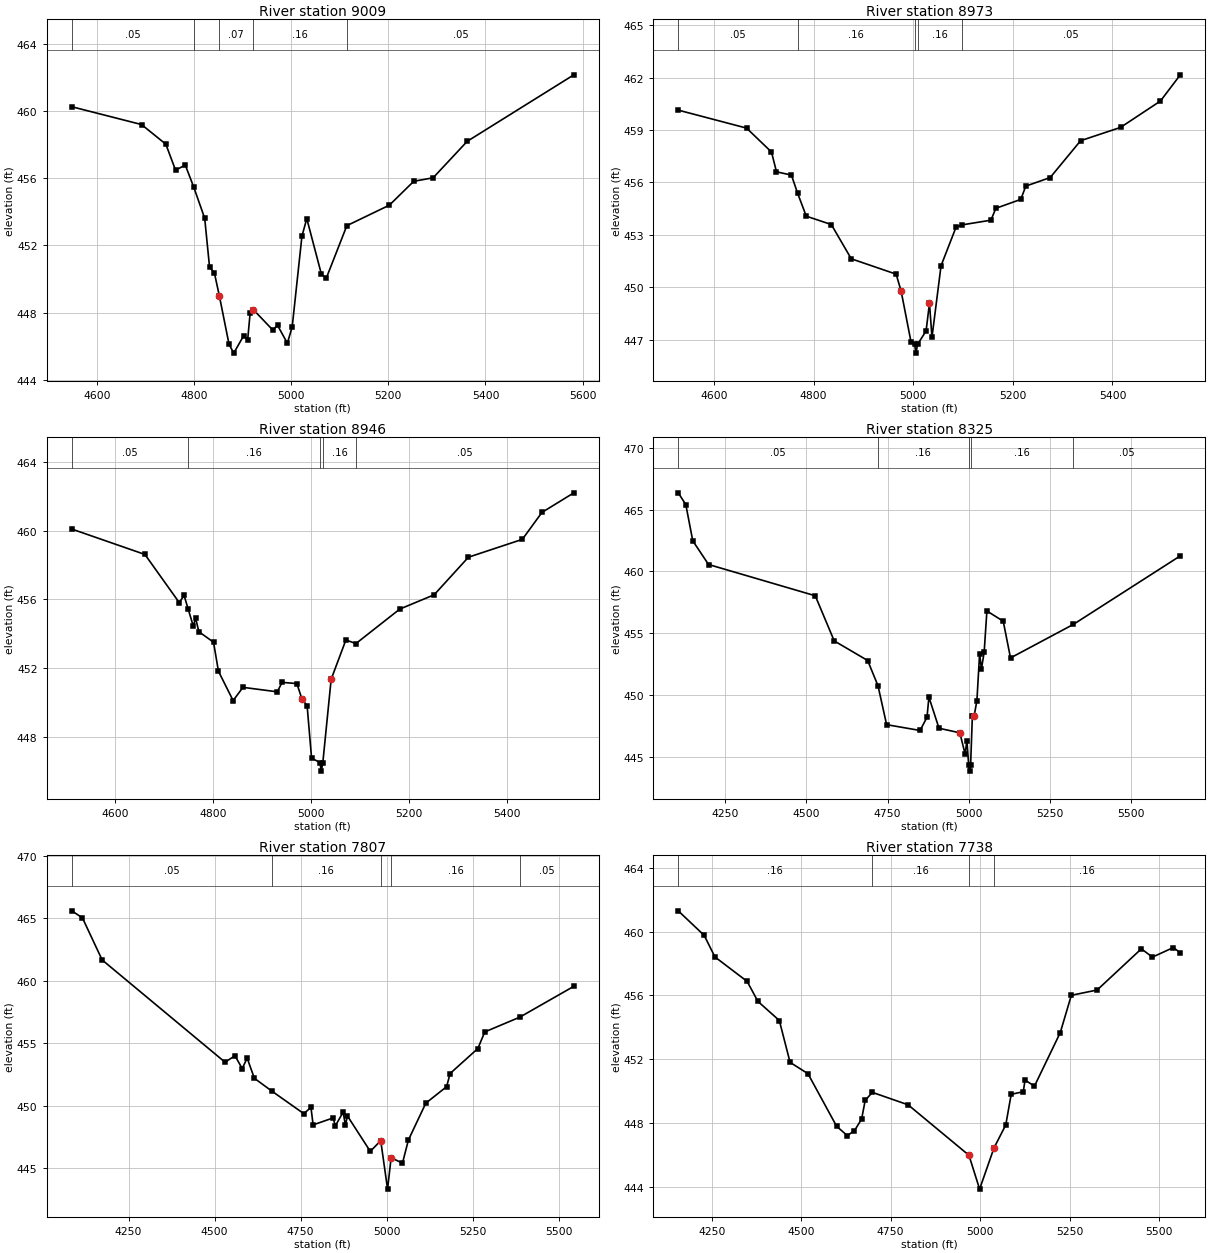
Type RM Length L Ch R = 1 ,9009    ,36,36,36
BEGIN DESCRIPTION:
UNT021 IN CCTC 15.0
END DESCRIPTION:
XS GIS Cut Line= 2
      3496383.12     10634489.77      3495350.14     10634448.54
#Sta/Elev= 30
  4548.2  460.26  4691.8   459.2  4741.9  458.03  4761.9  456.48  4781.9  456.79
  4798.9  455.51  4821.9  453.62  4831.9  450.71  4841.9  450.36    4852  449.01
    4872  446.12  4881.7  445.59    4902  446.62  4910.4  446.39  4915.4  447.96
    4922  448.18    4962  446.97    4972  447.24  4992.1  446.18  5002.1  447.16
  5022.1  452.55  5032.1   453.6  5062.1   450.3  5072.1  450.04  5114.6  453.18
  5202.2   454.4  5252.3  455.82  5292.3  456.03  5362.4   458.2    5582  462.16
#Mann= 5 ,-1 , 0
  4548.2     .05       0  4798.9     .16       0    4852     .07       0
    4922     .16       0  5114.6     .05       0
Bank Sta=4852,4922
XS Rating Curve= 0 ,0
Exp/Cntr=0.3,0.1

Type RM Length L Ch R = 1 ,8973    ,27,27,27
BEGIN DESCRIPTION:
Mapping XS 2257e809
END DESCRIPTION:
XS GIS Cut Line= 2
      3496376.66      10634465.9       3495369.7     10634424.67
#Sta/Elev= 30
  4528.4  460.14  4665.6  459.11  4715.6  457.74  4725.6  456.61  4755.6  456.42
  4767.9  455.39  4785.4  454.07  4835.7  453.59  4875.7  451.63  4965.8  450.75
  4975.8  449.78  4995.8  446.85  5002.8  446.73  5005.6  446.23  5008.8  446.73
  5025.9   447.5  5032.7  449.09  5037.7  447.13  5055.9  451.23  5085.9  453.43
  5097.9  453.57    5156  453.84    5166  454.52    5216  455.03    5226  455.79
    5275  456.28  5336.1  458.39  5416.2  459.15  5496.3  460.66  5536.2  462.16
#Mann= 5 ,-1 , 0
  4528.4     .05       0  4767.9     .16       0  5002.8     .07       0
  5008.8     .16       0  5097.9     .05       0
Bank Sta=4975.8,5032.7
XS Rating Curve= 0 ,0
Exp/Cntr=0.3,0.1

Type RM Length L Ch R = 1 ,8946    ,621,621,621
BEGIN DESCRIPTION:
UNT021 IN CCTC 14.0
END DESCRIPTION:
XS GIS Cut Line= 2
      3496378.83     10634446.37      3495354.54      10634400.8
#Sta/Elev= 30
  4511.7  460.09  4661.1  458.61  4731.1  455.81  4741.1  456.22  4749.4  455.43
  4759.7  454.45  4764.7  454.89  4771.2  454.11  4801.2   453.5  4811.2  451.81
  4841.2   450.1  4861.3  450.87  4931.3  450.61  4941.3  451.16  4971.4  451.09
  4981.4  450.22  4992.3   449.8  5001.4  446.75  5018.4  446.49  5021.2  445.99
  5024.4  446.49  5041.4  451.34  5071.5  453.63    5092  453.42  5181.6  455.43
  5251.7  456.26  5321.7  458.45  5431.8  459.49  5471.9  461.06    5537   462.2
#Mann= 5 ,-1 , 0
  4511.7     .05       0  4749.4     .16       0  5018.4     .07       0
  5024.4     .16       0    5092     .05       0
Bank Sta=4981.4,5041.4
XS Rating Curve= 0 ,0
Exp/Cntr=0.3,0.1

Type RM Length L Ch R = 1 ,8325    ,518,518,518
BEGIN DESCRIPTION:
UNT021 IN CCTC 13.0
END DESCRIPTION:
XS GIS Cut Line= 3
       3496699.6     10634510.18      3495949.61     10634060.19
      3495349.56     10634360.21
#Sta/Elev= 30
  4105.3  466.35  4128.6   465.4    4150  462.47  4198.6  460.55  4527.1  458.02
  4585.4  454.37  4688.4  452.78  4720.2  450.74  4746.7  447.59  4849.7  447.12
  4871.1  448.19  4876.9  449.82    4908   447.3  4972.2  446.93  4988.3  445.21
  4993.9   446.3  4999.3  444.33    5002  443.83  5005.3  444.33  5010.7  448.29
  5016.3  448.32  5024.7  449.54    5033  453.34  5038.6   452.1    5047  453.45
  5055.4  456.79  5105.7  455.96  5128.1  452.99    5322  455.71  5650.8  461.25
#Mann= 5 ,-1 , 0
  4105.3     .05       0  4720.2     .16       0  4999.3     .07       0
  5005.3     .16       0    5322     .05       0
Bank Sta=4972.2,5016.3
XS Rating Curve= 0 ,0
Exp/Cntr=0.3,0.1

Type RM Length L Ch R = 1 ,7807    ,69,69,69
BEGIN DESCRIPTION:
Mapping XS c9aa647d
END DESCRIPTION:
XS GIS Cut Line= 3
      3496772.47      10634390.8      3496269.01     10633720.67
      3495652.81     10633641.05
#Sta/Elev= 30
  4084.8   465.6  4115.7  465.04  4173.1  461.67  4530.2  453.49  4559.3     454
  4580.2  452.98  4594.7  453.81  4615.6   452.2  4665.6  451.19  4759.3  449.37
  4780.1  449.87  4786.4  448.47  4844.7  449.03  4850.9  448.39  4873.6  449.49
  4880.1  448.47  4886.3  449.18  4952.6  446.35  4982.9  447.21  5002.8  443.33
  5013.1  445.84  5046.1  445.41  5063.5  447.27    5114  450.21  5174.5  451.53
  5184.5  452.58  5265.2  454.58  5285.4  455.91  5387.1  457.09  5544.3  459.56
#Mann= 5 ,-1 , 0
  4084.8     .05       0  4665.6     .16       0  4982.9     .07       0
  5013.1     .16       0  5387.1     .05       0
Bank Sta=4982.9,5013.1
XS Rating Curve= 0 ,0
Exp/Cntr=0.3,0.1

Type RM Length L Ch R = 1 ,7738    ,56,56,56
BEGIN DESCRIPTION:
UNT021 IN CCTC 12.0
END DESCRIPTION:
XS GIS Cut Line= 4
      3497032.17     10633651.46      3496119.01     10633641.04
      3496073.87     10633627.15      3495643.84     10633520.94
#Sta/Elev= 30
  4156.2   461.3  4228.8  459.76  4258.8  458.41  4348.8  456.88  4378.8  455.63
  4438.8  454.43  4468.8  451.81  4518.8   451.1  4598.8  447.81  4628.8  447.22
  4648.8  447.53  4668.8  448.26  4678.8  449.43  4698.8  449.93  4798.8  449.15
  4968.8  445.99  4998.6  443.87  5038.8  446.45  5071.7  447.89  5086.9  449.81
  5120.7  449.97  5125.5   450.7  5151.9  450.32    5224  453.67    5255  456.01
  5327.1  456.34  5450.7  458.92  5481.6   458.4  5540.1     459  5559.6  458.67
#Mann= 4 ,-1 , 0
  4156.2     .16       0  4698.8     .16       0  4968.8      .1       0
  5038.8     .16       0
Bank Sta=4968.8,5038.8
XS Rating Curve= 0 ,0
Exp/Cntr=0.3,0.1

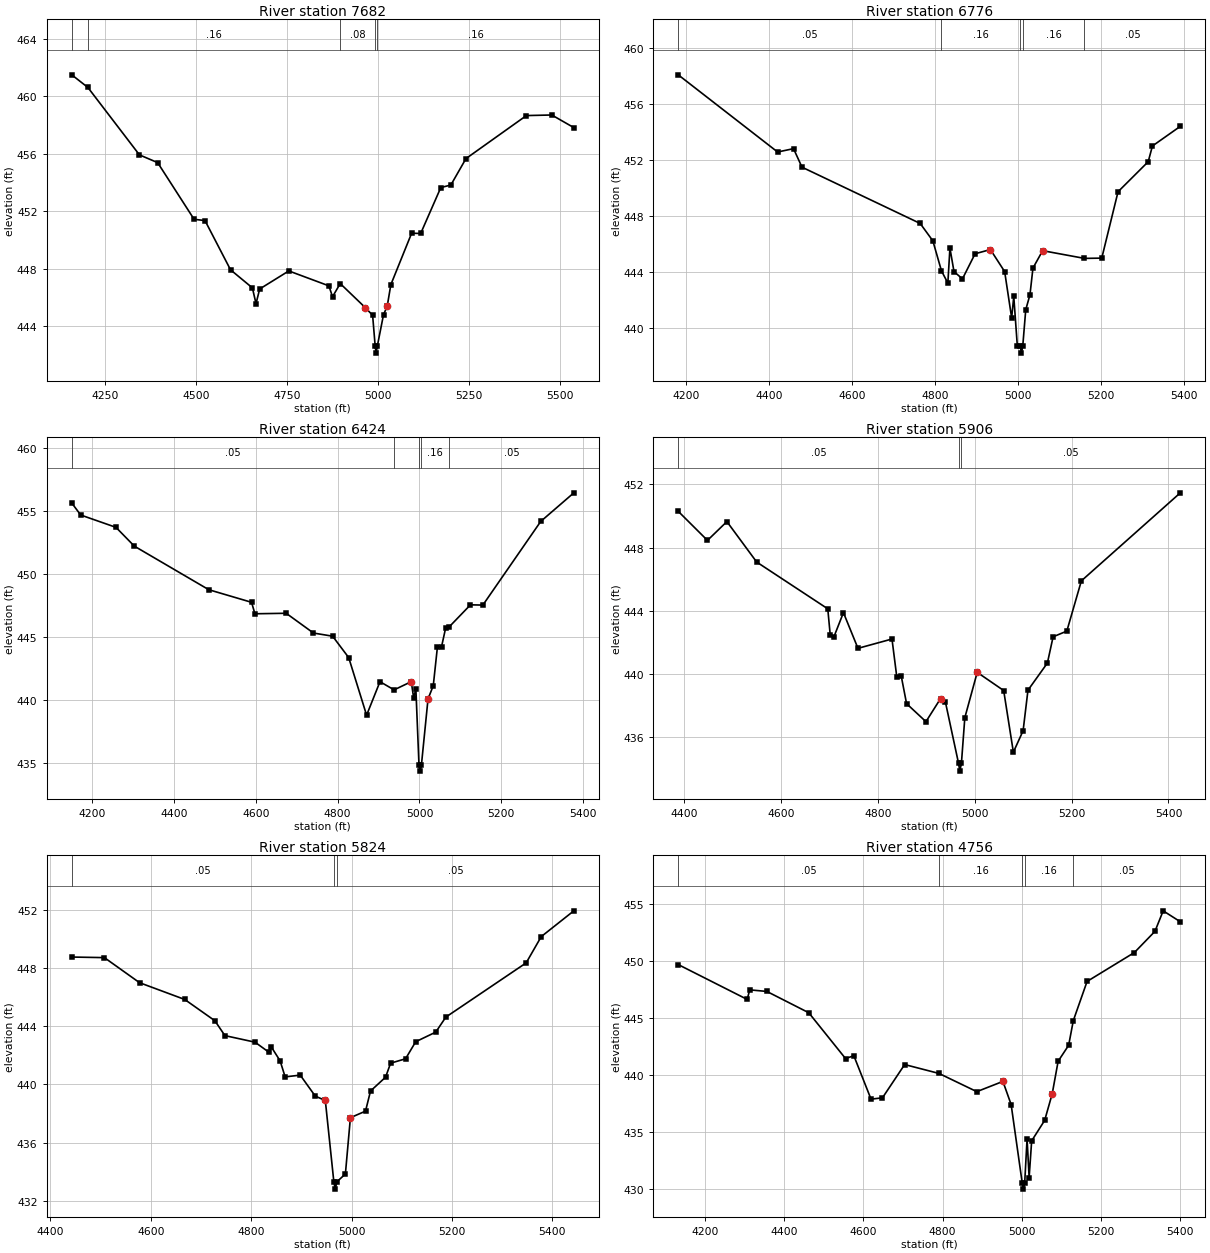
Type RM Length L Ch R = 1 ,7682    ,906,906,906
BEGIN DESCRIPTION:
UNT021 IN CCTC 11.0
END DESCRIPTION:
XS GIS Cut Line= 4
       3497025.3     10633585.49      3496139.85     10633585.49
      3496105.12     10633578.54      3495663.56     10633460.25
#Sta/Elev= 30
  4159.7  461.51  4203.9  460.63  4345.4  455.93  4395.4  455.39  4495.4  451.44
  4525.4  451.35  4595.4  447.92  4655.4  446.66  4665.4  445.56  4675.4  446.58
  4755.4  447.84  4865.4   446.8  4875.4  446.04  4896.5  446.96  4965.4  445.28
  4985.4  444.75  4992.4  442.61  4995.1  442.11  4998.4  442.61  5015.4   444.8
  5025.4  445.37  5035.4  446.88  5092.5  450.47  5117.3  450.45  5172.5  453.65
  5200.2  453.83  5241.6  455.67  5407.5  458.67  5477.2  458.71  5537.7  457.83
#Mann= 5 ,-1 , 0
  4159.7     .08       0  4203.9     .16       0  4896.5     .08       0
  4992.4     .04       0  4998.4     .16       0
Bank Sta=4965.4,5025.4
XS Rating Curve= 0 ,0
Exp/Cntr=0.3,0.1

Type RM Length L Ch R = 1 ,6776    ,352,352,352
BEGIN DESCRIPTION:
Mapping XS b4a31d1d
END DESCRIPTION:
XS GIS Cut Line= 2
      3497082.64     10633221.02      3495893.58     10632986.85
#Sta/Elev= 30
  4180.3  458.06  4420.2  452.56  4458.6   452.8    4479  451.48  4764.3  447.47
  4794.9  446.23  4815.7  444.09  4831.1  443.22  4836.1  445.72  4845.9  444.04
  4866.3  443.52  4896.8  445.31  4933.8  445.61  4968.2  444.04  4985.1  440.74
  4990.2  442.27  4998.8  438.74  5005.9  438.73  5008.7  438.23  5011.9  438.73
  5019.1  441.32  5029.3  442.39  5036.5  444.29  5059.9  445.53  5160.9  444.98
  5202.6     445  5241.9  449.73  5314.7  451.87  5324.9  452.99  5392.2  454.39
#Mann= 5 ,-1 , 0
  4180.3     .05       0  4815.7     .16       0  5005.9     .07       0
  5011.9     .16       0  5160.9     .05       0
Bank Sta=4933.8,5059.9
XS Rating Curve= 0 ,0
Exp/Cntr=0.3,0.1

Type RM Length L Ch R = 1 ,6424    ,518,518,518
BEGIN DESCRIPTION:
UNT021 IN CCTC 10.0
END DESCRIPTION:
XS GIS Cut Line= 3
       3496999.6     10633060.18      3496199.61     10632710.19
      3495849.56      10632760.2
#Sta/Elev= 30
  4150.4  455.61  4172.2  454.66  4258.4  453.68  4303.2  452.19  4485.2  448.73
  4589.7  447.73  4597.9  446.82  4674.3  446.86    4741  445.29  4787.8  445.04
  4827.1  443.34  4870.8  438.77  4903.5  441.43    4938  440.78  4979.9  441.43
  4985.8  440.14  4991.2  440.86  4998.8  434.83  5001.5  434.33  5004.8  434.83
  5020.9  440.06  5033.7  441.11  5043.8  444.17  5053.9   444.2    5064   445.7
  5072.3  445.77  5124.6  447.53  5154.9  447.51  5296.3  454.15  5377.2  456.42
#Mann= 5 ,-1 , 0
  4150.4     .05       0    4938     .16       0  4998.8     .07       0
  5004.8     .16       0  5072.3     .05       0
Bank Sta=4979.9,5020.9
XS Rating Curve= 0 ,0
Exp/Cntr=0.3,0.1

Type RM Length L Ch R = 1 ,5906    ,82,82,82
BEGIN DESCRIPTION:
UNT021 IN CCTC 9.0
END DESCRIPTION:
XS GIS Cut Line= 2
      3496929.77     10632305.54      3495895.88     10632237.83
#Sta/Elev= 30
  4388.4  450.29  4448.7  448.45  4488.8  449.64  4550.3  447.08    4697  444.12
    4702  442.48  4709.2  442.31  4729.3  443.88  4759.3  441.62  4829.5  442.21
  4839.5  439.79  4848.7  439.85  4859.6  438.12  4899.6  436.98  4929.7  438.44
  4939.7  438.23  4966.8  434.35  4969.5  433.85  4972.8  434.35  4979.8  437.23
  5005.4   440.1    5060  438.95    5080  435.05  5100.1  436.41  5110.1  438.97
  5150.2  440.69    5162  442.35  5190.3  442.71  5220.3  445.89  5424.5  451.46
#Mann= 3 ,-1 , 0
  4388.4     .05       0  4966.8    .035       0  4972.8     .05       0
Bank Sta=4929.7,5005.4
XS Rating Curve= 0 ,0
Exp/Cntr=0.3,0.1

Type RM Length L Ch R = 1 ,5824    ,1068,1068,1068
BEGIN DESCRIPTION:
UNT021 IN CCTC 8.0
END DESCRIPTION:
XS GIS Cut Line= 2
      3496924.57      10632219.6      3495924.64     10632183.15
#Sta/Elev= 30
  4442.5  448.74  4507.5   448.7  4577.6  446.98  4667.6  445.83  4727.7  444.37
  4747.7  443.35  4807.7   442.9  4835.4  442.21  4840.4  442.56  4857.7  441.62
  4867.7  440.52  4897.8  440.64  4927.8   439.2  4947.8   438.9  4964.8  433.32
  4967.6  432.82  4970.8  433.32  4987.8  433.86  4997.8  437.72  5027.9  438.17
  5037.9  439.55  5067.9   440.5  5077.9  441.46  5107.7  441.76  5127.9  442.93
  5167.9  443.59    5188  444.62  5348.1  448.34  5378.1  450.14  5443.1  451.91
#Mann= 3 ,-1 , 0
  4442.5     .05       0  4964.8     .04       0  4970.8     .05       0
Bank Sta=4947.8,4997.8
XS Rating Curve= 0 ,0
Exp/Cntr=0.3,0.1

Type RM Length L Ch R = 1 ,4756    ,644,644,644
BEGIN DESCRIPTION:
UNT021 IN CCTC 7.0
END DESCRIPTION:
XS GIS Cut Line= 3
      3497098.18     10632135.41      3496500.96     10631670.12
      3496007.92     10631531.24
#Sta/Elev= 30
  4131.8  449.68  4306.1  446.62  4312.5  447.46  4355.9  447.32  4461.8  445.45
  4554.9  441.42  4575.7  441.68  4619.2  437.86  4648.1  437.98  4704.2   440.9
    4791  440.12  4886.6  438.52  4952.6  439.42  4973.4  437.39  5001.6  430.46
  5004.3  429.96  5007.6  430.46  5013.7  434.38  5018.9  430.98  5025.3   434.2
  5058.2     436  5077.3  438.34  5092.2  441.19  5118.8  442.59  5130.6  444.76
  5165.4   448.2  5285.1  450.74    5337   452.6  5357.8   454.4  5401.1  453.44
#Mann= 5 ,-1 , 0
  4131.8     .05       0    4791     .16       0  5001.6     .07       0
  5007.6     .16       0  5130.6     .05       0
Bank Sta=4952.6,5077.3
XS Rating Curve= 0 ,0
Exp/Cntr=0.3,0.1