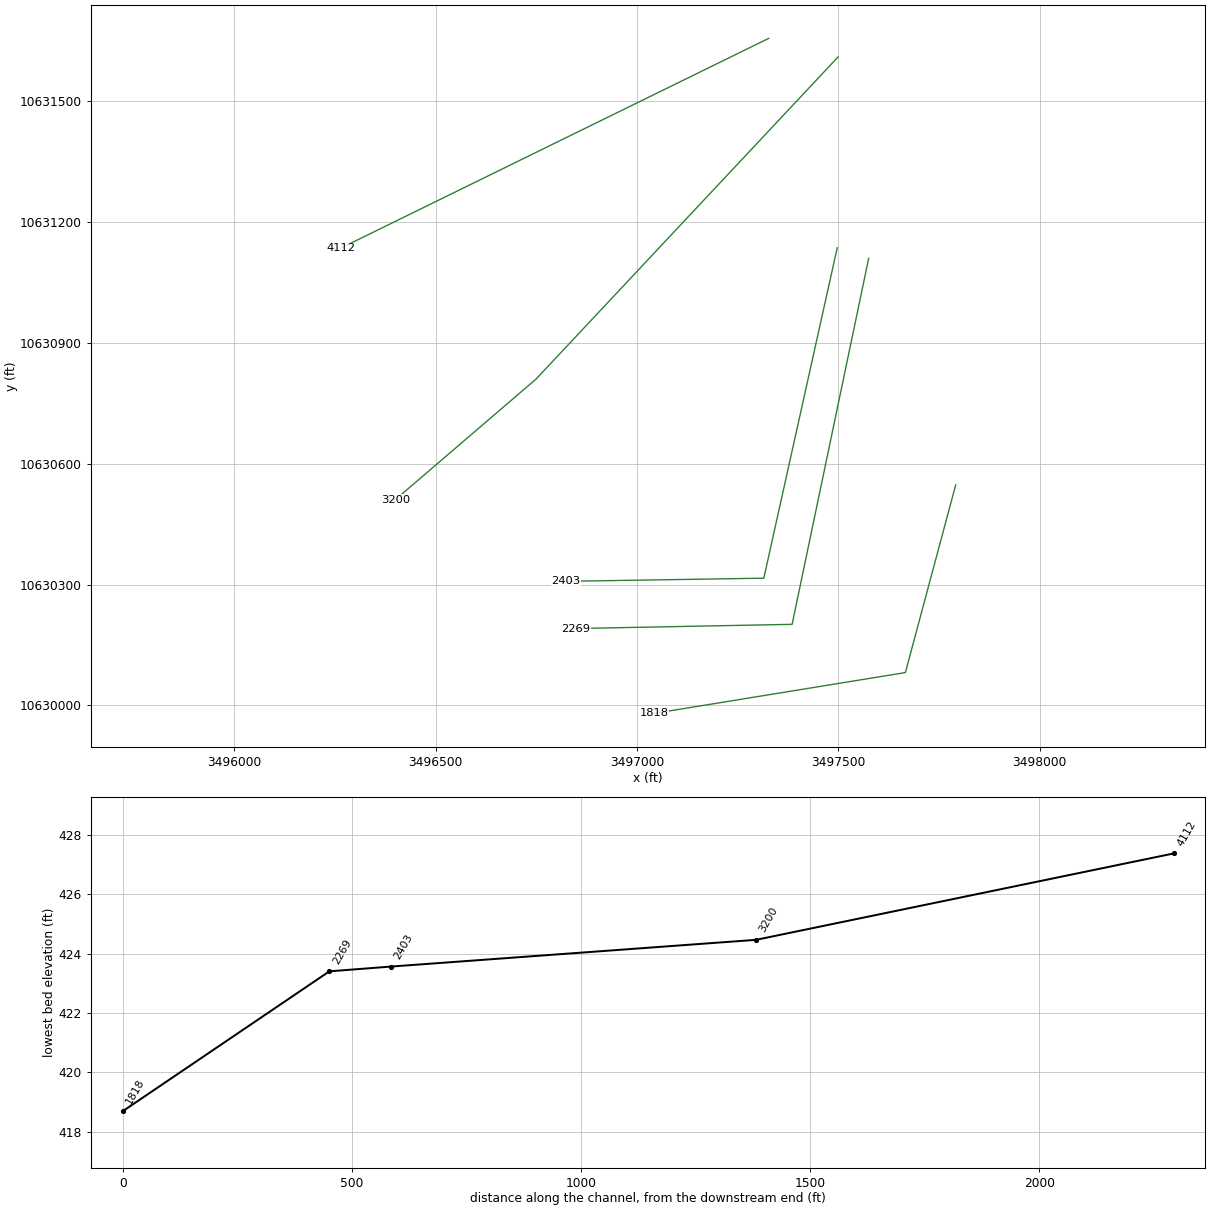
HEC-RAS study UNT021 IN CCTC.prj: UNT021 IN CCTC Base Level Engineering

--- UNT021 IN CCTC.g01 (geometry) --- (continued)

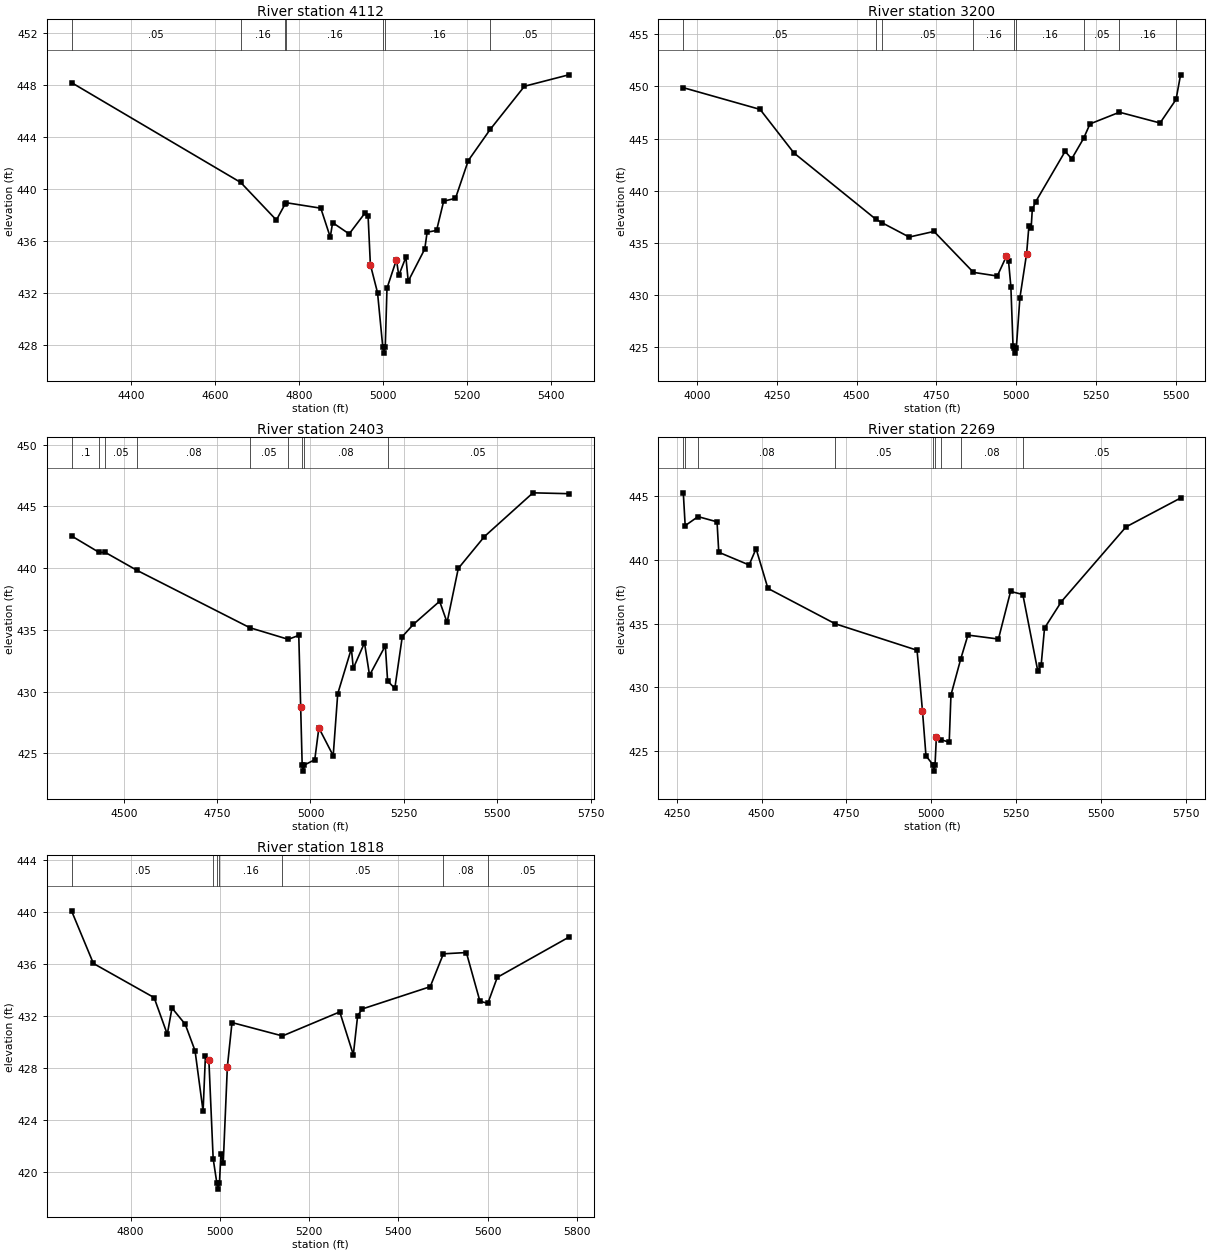
Type RM Length L Ch R = 1 ,4112    ,912,912,912
BEGIN DESCRIPTION:
UNT021 IN CCTC 5.0
END DESCRIPTION:
XS GIS Cut Line= 2
      3497327.35     10631656.23      3496264.84      10631135.4
#Sta/Elev= 30
  4259.2  448.18  4661.8   440.5  4746.7  437.61  4768.2  438.88  4770.4  438.94
  4852.4  438.52  4874.9  436.29  4880.5  437.41  4919.9  436.54  4958.3  438.18
  4964.9  437.94  4970.4  434.17  4987.4  432.02  4999.8  427.87  5002.6  427.37
  5005.8  427.87  5009.9  432.36  5032.4  434.56  5037.9  433.35  5054.9  434.75
  5060.4   432.9  5099.8  435.38  5105.4  436.67  5127.9  436.81  5144.8  439.06
  5172.9  439.28  5203.3  442.18  5255.5  444.58    5337   447.9  5442.5  448.78
#Mann= 7 ,-1 , 0
  4259.2     .05       0  4661.8     .16       0  4768.2     .05       0
  4770.4     .16       0  4999.8     .07       0  5005.8     .16       0
  5255.5     .05       0
Bank Sta=4970.4,5032.4
XS Rating Curve= 0 ,0
Exp/Cntr=0.3,0.1

Type RM Length L Ch R = 1 ,3200    ,797,797,797
BEGIN DESCRIPTION:
UNT021 IN CCTC 4.0
END DESCRIPTION:
XS GIS Cut Line= 3
      3497499.59     10631610.16      3496749.61     10630810.19
      3496399.63     10630510.21
#Sta/Elev= 30
  3957.2  449.87  4197.7  447.79  4303.7  443.62  4560.1  437.28  4579.7  436.94
  4664.7  435.57  4742.4  436.11    4866  432.19  4940.7  431.84    4969  433.72
  4975.8   433.3  4983.2  430.83    4990  425.14  4994.3  424.96  4997.1  424.46
  5000.3  424.96  5011.5  429.76  5032.5  433.98  5039.8  436.66  5046.7  436.41
  5050.3  438.21  5060.9  438.95  5153.1  443.77  5173.9  443.06  5210.9  445.01
    5231   446.4  5323.3  447.52  5450.5  446.49  5500.6  448.74  5514.7   451.1
#Mann= 9 ,-1 , 0
  3957.2     .05       0  4560.1     .16       0  4579.7     .05       0
    4866     .16       0  4994.3     .07       0  5000.3     .16       0
  5210.9     .05       0  5323.3     .16       0  5500.6     .05       0
Bank Sta=4969,5032.5
XS Rating Curve= 0 ,0
Exp/Cntr=0.3,0.1

Type RM Length L Ch R = 1 ,2403    ,134,134,134
BEGIN DESCRIPTION:
UNT021 IN CCTC 3.0
END DESCRIPTION:
XS GIS Cut Line= 3
      3497497.35     10631136.08      3497315.05     10630315.74
      3496823.76     10630307.95
#Sta/Elev= 30
  4360.1   442.6  4433.8  441.27  4450.9  441.26  4535.1  439.82  4837.7  435.17
  4940.5  434.23  4968.7  434.55  4973.8  428.72  4977.8  424.06  4980.5  423.56
  4983.8  424.06  5011.5  424.48  5022.5  427.06  5060.9  424.81    5073  429.82
  5109.6  433.48  5114.7  431.88  5144.7  433.95  5158.2  431.32  5200.5  433.71
  5206.6  430.86  5225.9  430.26  5245.9  434.45  5275.9  435.45  5345.9  437.31
  5365.9   435.6  5395.9  439.97  5465.9  442.55  5595.9  446.09  5691.8  446.02
#Mann= 9 ,-1 , 0
  4360.1      .1       0  4433.8     .08       0  4450.9     .05       0
  4535.1     .08       0  4837.7     .05       0  4940.5     .08       0
  4977.8     .07       0  4983.8     .08       0  5206.6     .05       0
Bank Sta=4973.8,5022.5
XS Rating Curve= 0 ,0
Exp/Cntr=0.3,0.1

Type RM Length L Ch R = 1 ,2269    ,451,451,451
BEGIN DESCRIPTION:
UNT021 IN CCTC 2.0
END DESCRIPTION:
XS GIS Cut Line= 3
      3497575.46       10631110.      3497385.36     10630201.16
      3496848.87     10630190.74
#Sta/Elev= 30
  4269.5  445.27    4275  442.69  4312.9   443.4  4368.9  442.99    4374   440.6
  4463.4   439.6  4483.9  440.88  4518.8  437.76    4717  434.98  4958.2   432.9
  4974.2  428.13  4984.5   424.6  5005.2   423.9  5007.9   423.4  5011.2   423.9
  5015.1  426.05  5029.5  425.86    5053  425.68  5058.1  429.38  5087.2  432.24
  5108.1  434.09    5198  433.78  5233.8  437.52  5269.9  437.28  5313.8  431.29
  5323.8  431.71  5333.8  434.64  5383.8  436.73  5573.8  442.59  5734.6  444.86
#Mann= 9 ,-1 , 0
  4269.5     .05       0    4275      .1       0  4312.9     .08       0
    4717     .05       0  5005.2    .035       0  5011.2     .05       0
  5029.5     .16       0  5087.2     .08       0  5269.9     .05       0
Bank Sta=4974.2,5015.1
XS Rating Curve= 0 ,0
Exp/Cntr=0.3,0.1

Type RM Length L Ch R = 1 ,1818    ,0,0,0
BEGIN DESCRIPTION:
Mapping XS 970d4e5c
END DESCRIPTION:
XS GIS Cut Line= 3
      3497791.61     10630547.51      3497666.61     10630081.37
       3497043.1     10629980.05
#Sta/Elev= 30
  4667.8  440.11  4716.8  436.06  4852.9  433.43  4882.4  430.61  4892.9  432.63
  4922.6  431.38  4944.6  429.34  4962.6  424.69  4967.8   428.9  4975.6  428.61
  4985.2  421.03  4993.3  419.19  4996.1  418.69  4999.3  419.19  5002.6  421.42
  5007.8  420.71    5017   428.1  5027.4  431.51  5140.5  430.48  5268.9  432.33
  5299.3  429.03    5309  432.05  5319.6  432.56  5471.6  434.27  5501.1   436.8
  5552.6   436.9    5583  433.15  5600.7  432.99  5621.9  434.99  5782.1  438.08
#Mann= 7 ,-1 , 0
  4667.8     .05       0  4985.2     .16       0  4993.3     .07       0
  4999.3     .16       0  5140.5     .05       0  5501.1     .08       0
  5600.7     .05       0
Bank Sta=4975.6,5017
XS Rating Curve= 0 ,0
Exp/Cntr=0.3,0.1

Chan Stop Cuts=-1
Use User Specified Reach Order=0
Composite Channel Slope=5