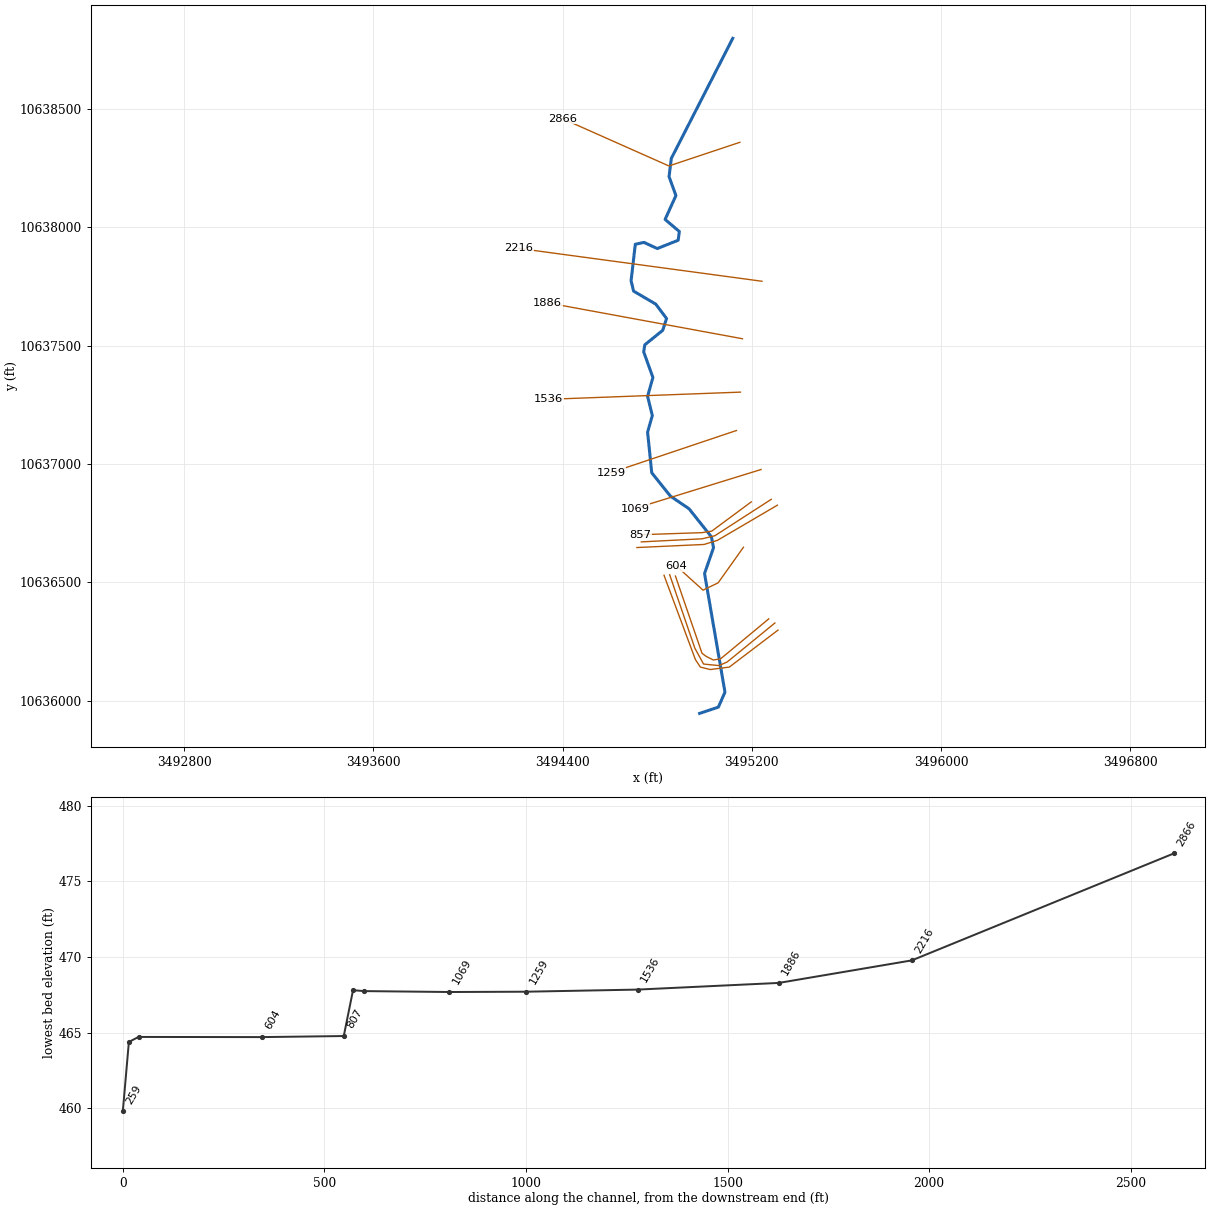
--- UNT022 IN CCTC.prj (project) ---

Proj Title=UNT022 IN CCTC Base Level Engineering
Current Plan=p01
Default Exp/Contr=0.3,0.1
English Units
Geom File=g01
Flow File=f01
Plan File=p01
BEGIN DESCRIPTION:
UNT022 IN CCTC
END DESCRIPTION:

--- UNT022 IN CCTC.p01 (plan) ---

Plan Title=Multiple Run
Short Identifier=Multiple
Geom File=g01
Flow File=f01
Subcritical Flow
K Sum by GR= 0
Std Step Tol= 0.01
Critical Tol= 0.01
Num of Std Step Trials= 20
Max Error Tol= 0.3
Flow Tol Ratio= 0.001
Split Flow NTrial= 30
Split Flow Tol= 0.02
Split Flow Ratio= 0.02
Log Output Level= 0
Friction Slope Method= 1
Unsteady Friction Slope Method= 2
Unsteady Bridges Friction Slope Method= 1
Parabolic Critical Depth
Global Vel Dist=  1 , 1 , 1
Global Log Level= 0
CheckData=True
Encroach Param= -1, 0, 0, 0
BEGIN DESCRIPTION:
Multiple Run
END DESCRIPTION:

--- UNT022 IN CCTC.f01 (steady flow) ---

Flow Title=Multiple
Number of Profiles=7
Profile Names=10-year,25-year,50-year,1pct_min,100-year,1pct_plu,500-year
River Rch & RM= UNT022 IN CCTC,Reach-1,2866
     365     461     533     452     611     827     799
Boundary for River Rch & Prof#=UNT022 IN CCTC,Reach-1,1
Up Type=0
Dn Type=3
Dn Slope=0.005
Boundary for River Rch & Prof#=UNT022 IN CCTC,Reach-1,2
Up Type=0
Dn Type=3
Dn Slope=0.005
Boundary for River Rch & Prof#=UNT022 IN CCTC,Reach-1,3
Up Type=0
Dn Type=3
Dn Slope=0.005
Boundary for River Rch & Prof#=UNT022 IN CCTC,Reach-1,4
Up Type=0
Dn Type=3
Dn Slope=0.005
Boundary for River Rch & Prof#=UNT022 IN CCTC,Reach-1,5
Up Type=0
Dn Type=3
Dn Slope=0.005
Boundary for River Rch & Prof#=UNT022 IN CCTC,Reach-1,6
Up Type=0
Dn Type=3
Dn Slope=0.005
Boundary for River Rch & Prof#=UNT022 IN CCTC,Reach-1,7
Up Type=0
Dn Type=3
Dn Slope=0.005

--- UNT022 IN CCTC.g01 (geometry) ---

Geom Title=Existing Conditions

River Reach=UNT022 IN CCTC,Reach-1
Reach XY= 30
      3495119.58     10638799.78      3494859.75     10638292.00
      3494850.25     10638215.00      3494879.25     10638135.00
      3494833.50     10638034.00      3494893.75     10637983.00
      3494888.75     10637946.00      3494800.50     10637911.00
      3494744.00     10637937.00      3494707.50     10637929.00
      3494689.75     10637775.00      3494700.25     10637731.00
      3494794.00     10637676.00      3494839.75     10637615.00
      3494823.25     10637565.00      3494747.75     10637504.00
      3494743.00     10637474.00      3494782.00     10637366.00
      3494759.50     10637286.00      3494779.50     10637205.00
      3494759.50     10637135.00      3494777.00     10636963.00
      3494856.25     10636864.00      3494934.50     10636811.00
      3495029.50     10636692.00      3495038.25     10636646.00
      3495000.25     10636537.00      3495086.62     10636035.53
      3495058.84     10635972.16      3494979.45     10635945.64

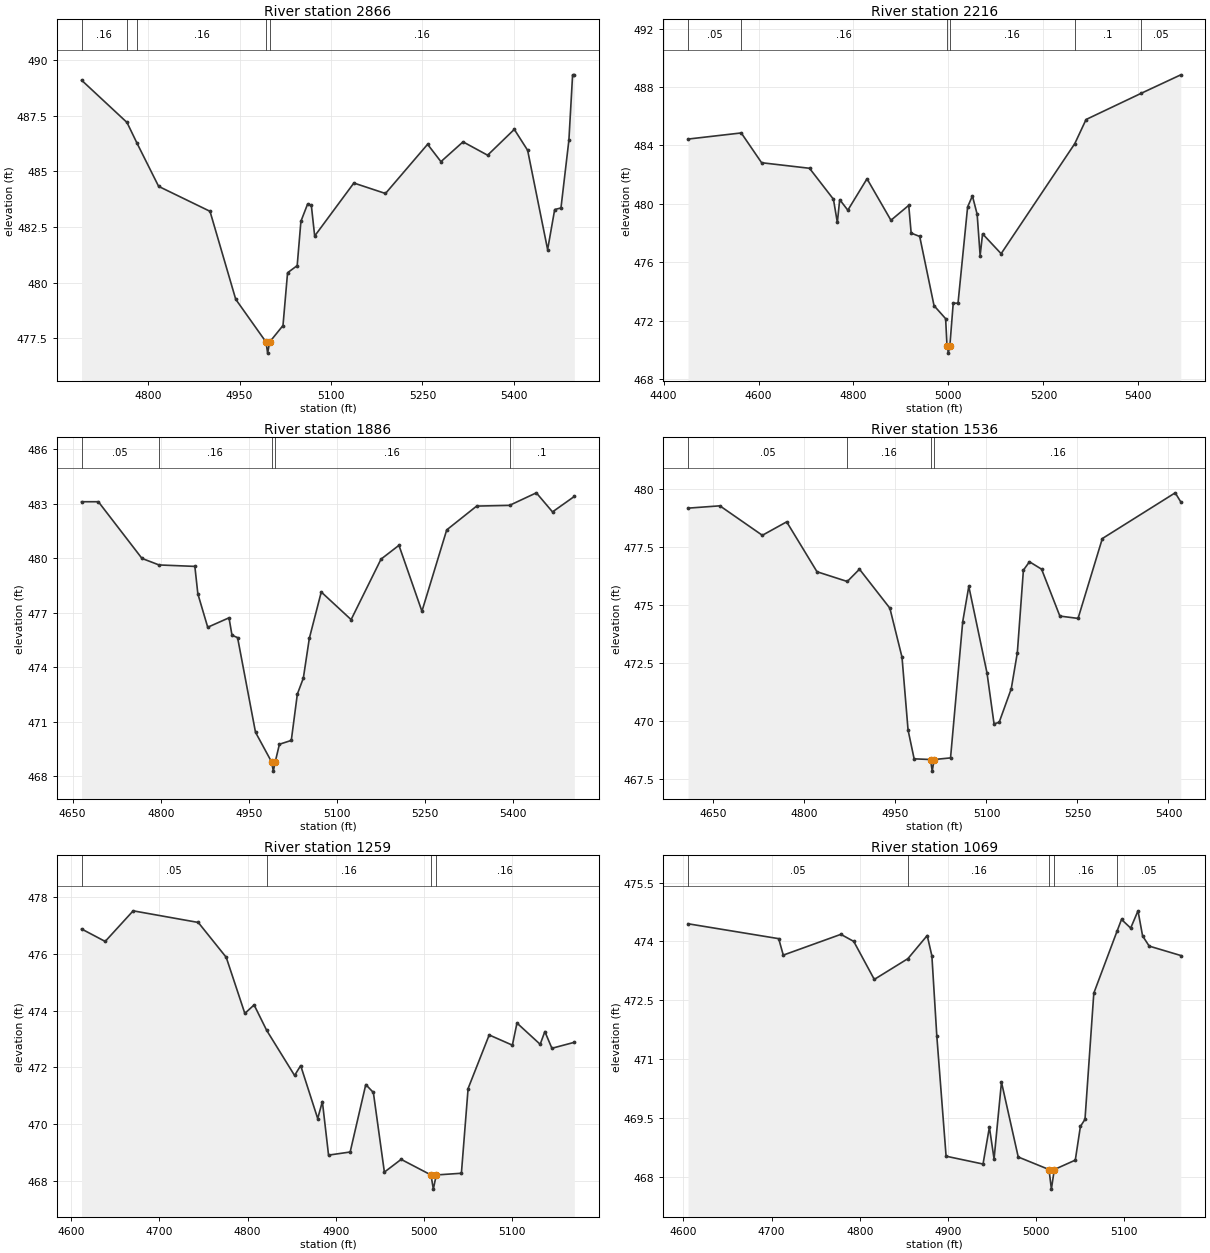
Type RM Length L Ch R = 1,2866,650,650,650
BEGIN DESCRIPTION:
UNT022 IN CCTC 5.0
END DESCRIPTION:
XS GIS Cut Line= 3
      3495149.61     10638360.19      3494849.61     10638260.19
      3494399.59     10638460.20
#Sta/Elev= 30
  4690.6  489.10  4765.2  487.20  4781.6  486.27  4817.1  484.33  4901.4  483.21
  4943.6  479.26  4993.3  477.34  4996.0  476.84  4999.3  477.34  5021.2  478.08
  5028.7  480.45  5044.5  480.77  5050.6  482.76  5061.5  483.53  5067.7  483.48
  5073.2  482.10  5137.5  484.48  5189.4  484.01  5258.5  486.22  5280.4  485.44
  5316.7  486.33  5357.0  485.73  5400.8  486.89  5422.7  485.95  5455.5  481.49
  5467.1  483.29  5477.4  483.36  5490.4  486.40  5496.5  489.34  5499.3  489.34
#Mann=5,-1,0
  4690.6    0.16       0  4765.2    0.05       0  4781.6    0.16       0
  4993.3    0.07       0  4999.3    0.16       0
Bank Sta=4993.3,4999.3
Exp/Cntr=0.3,0.1

Type RM Length L Ch R = 1,2216,330,330,330
BEGIN DESCRIPTION:
UNT022 IN CCTC 4.0
END DESCRIPTION:
XS GIS Cut Line= 2
      3495243.18     10637772.69      3494214.61     10637911.57
#Sta/Elev= 30
  4451.5  484.43  4563.6  484.85  4606.5  482.81  4707.4  482.43  4757.8  480.31
  4766.0  478.72  4771.0  480.28  4788.1  479.56  4828.5  481.71  4878.9  478.87
  4916.4  479.89  4921.5  477.99  4939.5  477.76  4969.7  473.02  4994.1  472.13
  4997.0  470.27  4999.8  469.77  5003.0  470.27  5010.1  473.19  5020.2  473.19
  5040.4  479.78  5050.5  480.54  5060.5  479.28  5066.8  476.45  5071.9  477.94
  5111.0  476.58  5266.2  484.12  5289.9  485.77  5406.4  487.57  5489.4  488.83
#Mann=6,-1,0
  4451.5    0.05       0  4563.6    0.16       0  4997.0    0.07       0
  5003.0    0.16       0  5266.2     0.1       0  5406.4    0.05       0
Bank Sta=4997,5003
Exp/Cntr=0.3,0.1

Type RM Length L Ch R = 1,1886,350,350,350
BEGIN DESCRIPTION:
UNT022 IN CCTC 3.0
END DESCRIPTION:
XS GIS Cut Line= 2
      3495160.75     10637529.63      3494336.12     10637681.53
#Sta/Elev= 30
  4665.3  483.11  4693.9  483.11  4768.1  479.99  4797.1  479.63  4858.1  479.55
  4863.2  478.04  4880.0  476.20  4916.2  476.72  4921.3  475.76  4930.8  475.63
  4961.3  470.42  4988.8  468.78  4991.6  468.28  4994.8  468.78  5002.0  469.76
  5022.2  469.97  5032.5  472.52  5042.7  473.40  5052.9  475.59  5073.2  478.14
  5124.0  476.62  5174.9  479.95  5205.4  480.71  5244.5  477.08  5286.7  481.56
  5337.6  482.87  5393.6  482.91  5439.2  483.60  5466.7  482.55  5503.8  483.40
#Mann=5,-1,0
  4665.3    0.05       0  4797.1    0.16       0  4988.8    0.07       0
  4994.8    0.16       0  5393.6     0.1       0
Bank Sta=4988.8,4994.8
Exp/Cntr=0.3,0.1

Type RM Length L Ch R = 1,1536,277,277,277
BEGIN DESCRIPTION:
UNT022 IN CCTC 2.0
END DESCRIPTION:
XS GIS Cut Line= 2
      3495152.05     10637303.93      3494340.41     10637273.55
#Sta/Elev= 30
  4608.1  479.17  4660.6  479.27  4730.6  478.00  4770.7  478.58  4820.7  476.43
  4870.6  476.01  4890.7  476.54  4940.8  474.86  4960.8  472.75  4970.8  469.61
  4980.8  468.37  5007.8  468.34  5010.6  467.84  5013.8  468.34  5040.8  468.41
  5060.9  474.28  5070.9  475.80  5100.9  472.07  5112.5  469.88  5120.9  469.94
  5140.9  471.39  5150.9  472.94  5160.9  476.50  5170.9  476.86  5190.9  476.54
  5221.0  474.52  5251.0  474.42  5291.0  477.86  5411.1  479.83  5420.3  479.44
#Mann=4,-1,0
  4608.1    0.05       0  4870.6    0.16       0  5007.8    0.07       0
  5013.8    0.16       0
Bank Sta=5007.8,5013.8
Exp/Cntr=0.3,0.1

Type RM Length L Ch R = 1,1259,190,190,190
BEGIN DESCRIPTION:
Mapping XS bcd1df86
END DESCRIPTION:
XS GIS Cut Line= 2
      3495135.02     10637141.61      3494605.52     10636963.66
#Sta/Elev= 30
  4611.7  476.88  4638.5  476.44  4670.2  477.52  4744.0  477.11  4775.7  475.88
  4796.8  473.90  4807.3  474.20  4821.6  473.30  4853.2  471.71  4860.1  472.06
  4879.4  470.19  4884.7  470.79  4891.7  468.90  4916.2  469.01  4933.9  471.39
  4942.5  471.11  4955.0  468.30  4974.0  468.75  5007.8  468.20  5010.5  467.70
  5013.8  468.20  5042.3  468.26  5049.9  471.25  5073.8  473.14  5100.1  472.78
  5105.3  473.56  5131.6  472.81  5136.9  473.26  5144.9  472.67  5170.3  472.88
#Mann=4,-1,0
  4611.7    0.05       0  4821.6    0.16       0  5007.8    0.07       0
  5013.8    0.16       0
Bank Sta=5007.8,5013.8
Exp/Cntr=0.3,0.1

Type RM Length L Ch R = 1,1069,212,212,212
BEGIN DESCRIPTION:
Mapping XS f5779e3b
END DESCRIPTION:
XS GIS Cut Line= 2
      3495239.17     10636976.67      3494705.36     10636811.75
#Sta/Elev= 30
  4605.2  474.45  4708.0  474.07  4713.2  473.65  4778.5  474.18  4793.1  474.00
  4816.4  473.03  4854.5  473.56  4876.4  474.15  4881.7  473.63  4887.3  471.58
  4897.8  468.52  4939.7  468.32  4946.9  469.26  4952.2  468.45  4960.6  470.41
  4979.6  468.50  5014.5  468.18  5017.2  467.68  5020.5  468.18  5044.3  468.42
  5050.1  469.28  5055.3  469.46  5065.3  472.68  5091.8  474.27  5096.7  474.56
  5107.1  474.34  5115.4  474.78  5120.6  474.14  5128.1  473.88  5163.9  473.64
#Mann=5,-1,0
  4605.2    0.05       0  4854.5    0.16       0  5014.5    0.07       0
  5020.5    0.16       0  5091.8    0.05       0
Bank Sta=5014.5,5020.5
Exp/Cntr=0.3,0.1

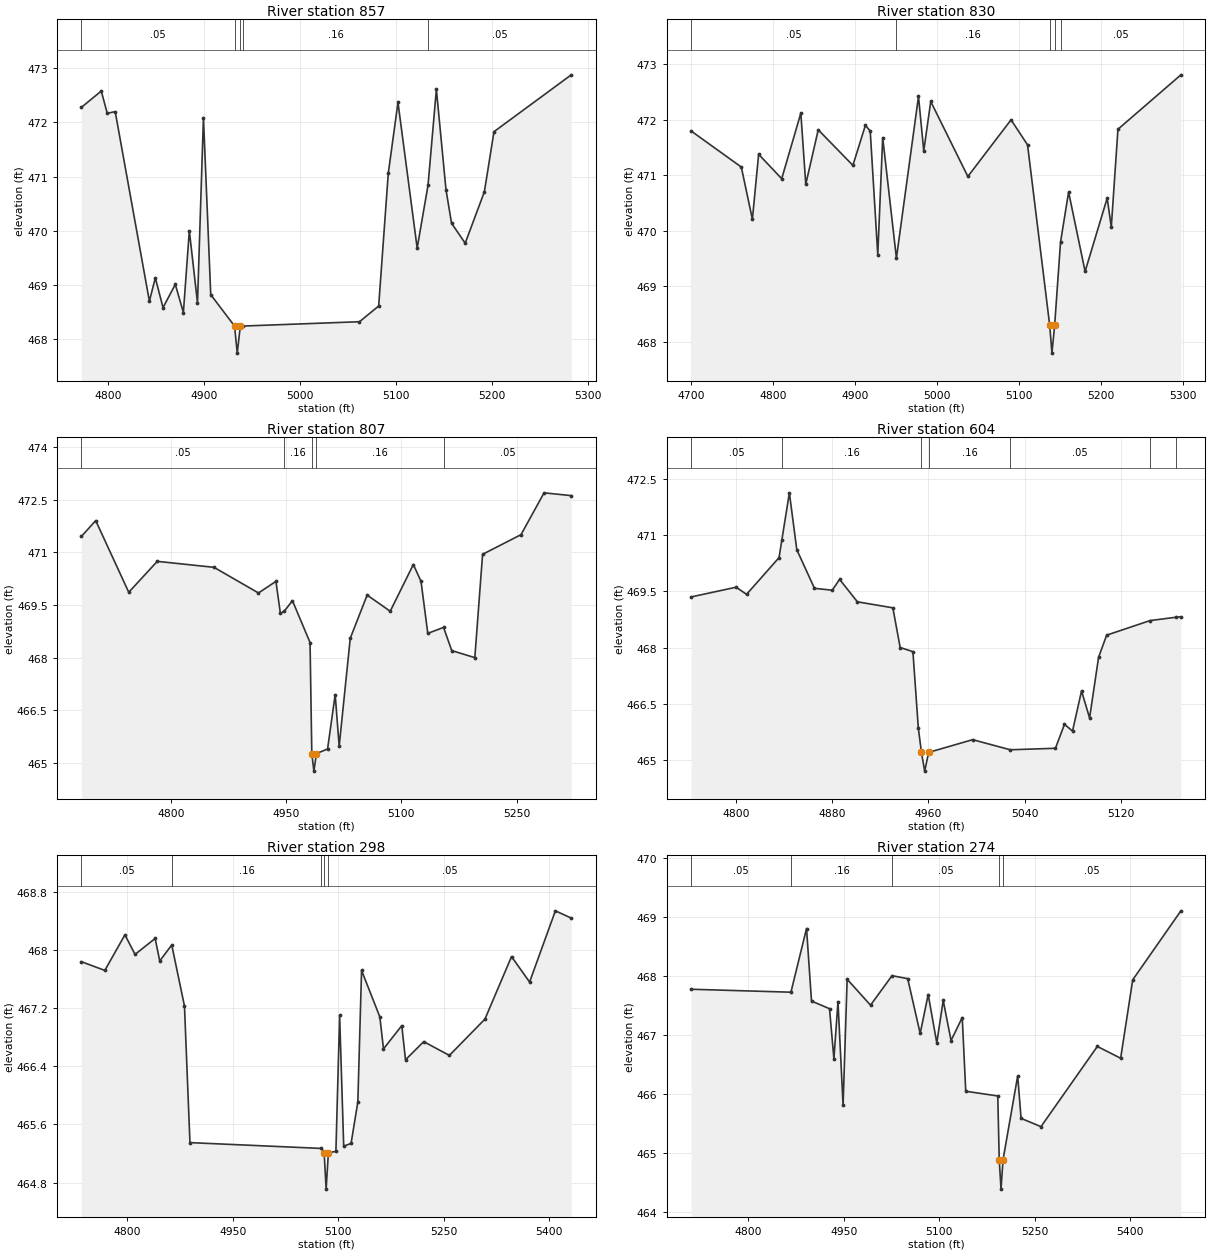
Type RM Length L Ch R = 1,857,27,27,27
BEGIN DESCRIPTION:
Mapping XS 37491b37
END DESCRIPTION:
XS GIS Cut Line= 4
      3495197.91     10636839.93      3495030.84     10636716.25
      3494989.61     10636709.74      3494729.16     10636701.06
#Sta/Elev= 30
  4772.0  472.28  4792.7  472.58  4798.9  472.17  4807.2  472.20  4842.8  468.70
  4849.0  469.13  4857.0  468.58  4869.8  469.01  4878.2  468.49  4884.4  470.00
  4892.9  468.67  4899.1  472.09  4906.7  468.82  4931.5  468.24  4934.3  467.74
  4937.5  468.24  4940.1  468.24  5061.6  468.32  5081.6  468.61  5091.6  471.06
  5101.7  472.37  5121.7  469.68  5133.0  470.84  5141.7  472.61  5151.7  470.76
  5157.5  470.14  5171.7  469.77  5191.7  470.72  5201.7  471.83  5282.2  472.88
#Mann=5,-1,0
  4772.0    0.05       0  4931.5    0.07       0  4937.5    0.05       0
  4940.1    0.16       0  5133.0    0.05       0
Bank Sta=4931.5,4937.5
Exp/Cntr=0.3,0.1

Type RM Length L Ch R = 1,830,23,23,23
BEGIN DESCRIPTION:
Mapping XS 63db6340
END DESCRIPTION:
XS GIS Cut Line= 4
      3495282.35     10636850.71      3495043.86     10636696.72
      3494989.61     10636683.70      3494733.01     10636670.76
#Sta/Elev= 30
  4700.4  471.80  4761.6  471.15  4775.1  470.21  4782.7  471.38  4810.8  470.94
  4834.1  472.12  4840.1  470.84  4855.3  471.82  4897.5  471.18  4912.7  471.90
  4918.6  471.80  4927.8  469.57  4933.8  471.68  4950.5  469.51  4977.4  472.42
  4983.8  471.44  4992.3  472.33  5037.5  470.98  5090.1  472.00  5110.2  471.55
  5137.2  468.30  5139.9  467.80  5143.2  468.30  5150.4  469.80  5160.2  470.70
  5180.3  469.27  5207.2  470.59  5212.2  470.07  5220.3  471.83  5297.0  472.81
#Mann=5,-1,0
  4700.4    0.05       0  4950.5    0.16       0  5137.2    0.07       0
  5143.2    0.16       0  5150.4    0.05       0
Bank Sta=5137.2,5143.2
Exp/Cntr=0.3,0.1

Type RM Length L Ch R = 1,807,203,203,203
BEGIN DESCRIPTION:
Mapping XS 47fd087f
END DESCRIPTION:
XS GIS Cut Line= 4
      3495308.37     10636825.96      3495054.72     10636677.19
      3494998.29     10636659.83      3494714.28     10636646.82
#Sta/Elev= 30
  4683.8  471.45  4702.4  471.90  4745.4  469.86  4782.5  470.74  4856.3  470.57
  4914.2  469.84  4936.9  470.17  4942.7  469.26  4947.7  469.32  4958.4  469.62
  4981.3  468.43  4983.6  465.27  4986.3  464.77  4989.6  465.27  5004.1  465.40
  5014.0  466.95  5019.2  465.48  5033.6  468.55  5055.6  469.78  5085.6  469.32
  5115.7  470.65  5125.7  470.17  5134.5  468.69  5155.0  468.86  5165.7  468.20
  5195.7  468.00  5205.8  470.94  5255.8  471.50  5285.8  472.69  5321.2  472.61
#Mann=5,-1,0
  4683.8    0.05       0  4947.7    0.16       0  4983.6    0.07       0
  4989.6    0.16       0  5155.0    0.05       0
Bank Sta=4983.6,4989.6
Exp/Cntr=0.3,0.1

Type RM Length L Ch R = 1,604,306,306,306
BEGIN DESCRIPTION:
Mapping XS 4add5804
END DESCRIPTION:
XS GIS Cut Line= 4
      3495164.81     10636647.97      3495057.77     10636497.63
      3494993.95     10636466.69      3494881.10     10636568.69
#Sta/Elev= 30
  4762.5  469.35  4800.0  469.61  4808.7  469.42  4835.7  470.40  4838.1  470.88
  4844.3  472.13  4850.5  470.61  4865.2  469.58  4880.0  469.53  4886.1  469.82
  4900.9  469.22  4930.4  469.06  4936.5  468.00  4947.1  467.89  4951.6  465.85
  4954.2  465.20  4956.9  464.70  4960.2  465.20  4996.8  465.54  5028.1  465.27
  5065.7  465.31  5073.2  465.95  5079.9  465.77  5087.4  466.84  5094.1  466.12
  5101.6  467.74  5108.3  468.33  5144.5  468.72  5166.4  468.81  5170.1  468.82
#Mann=7,-1,0
  4762.5    0.05       0  4838.1    0.16       0  4954.2    0.07       0
  4960.2    0.16       0  5028.1    0.05       0  5144.5    0.16       0
  5166.4    0.05       0
Bank Sta=4954.2,4960.2
Exp/Cntr=0.3,0.1

Type RM Length L Ch R = 1,298,24,24,24
BEGIN DESCRIPTION:
Mapping XS bbaabb75
END DESCRIPTION:
XS GIS Cut Line= 6
      3495271.75     10636345.17      3495067.74     10636175.89
      3495037.35     10636171.55      3495006.97     10636186.74
      3494989.61     10636199.76      3494877.17     10636526.28
#Sta/Elev= 30
  4734.9  467.84  4768.2  467.72  4796.8  468.21  4811.2  467.94  4839.8  468.16
  4846.3  467.85  4863.4  468.07  4881.5  467.23  4889.3  465.35  5076.4  465.27
  5080.2  465.21  5083.0  464.71  5086.2  465.21  5096.9  465.23  5102.2  467.10
  5108.0  465.30  5118.5  465.34  5128.1  465.91  5133.4  467.72  5159.4  467.08
  5164.6  466.64  5190.6  466.96  5195.9  466.49  5221.8  466.74  5258.3  466.55
  5308.9  467.05  5346.7  467.91  5372.4  467.56  5409.1  468.54  5431.7  468.44
#Mann=5,-1,0
  4734.9    0.05       0  4863.4    0.16       0  5076.4    0.05       0
  5080.2    0.07       0  5086.2    0.05       0
Bank Sta=5080.2,5086.2
Exp/Cntr=0.3,0.1

Type RM Length L Ch R = 1,274,15,15,15
BEGIN DESCRIPTION:
Mapping XS 49944ca2
END DESCRIPTION:
XS GIS Cut Line= 6
      3495297.75     10636327.78      3495095.95     10636162.87
      3495061.23     10636147.68      3494996.12     10636154.19
      3494959.23     10636221.46      3494852.89     10636531.79
#Sta/Elev= 30
  4710.3  467.77  4867.2  467.72  4891.7  468.80  4899.5  467.57  4927.8  467.44
  4934.7  466.59  4941.1  467.56  4949.1  465.80  4955.5  467.94  4992.2  467.50
  5026.0  468.00  5050.6  467.95  5070.2  467.02  5082.8  467.68  5096.3  466.86
  5106.4  467.58  5118.7  466.90  5136.3  467.29  5141.8  466.04  5192.1  465.96
  5194.4  464.88  5197.2  464.38  5200.4  464.88  5223.4  466.30  5228.7  465.58
  5260.0  465.44  5348.5  466.80  5385.1  466.60  5404.1  467.93  5479.8  469.10
#Mann=5,-1,0
  4710.3    0.05       0  4867.2    0.16       0  5026.0    0.05       0
  5194.4    0.07       0  5200.4    0.05       0
Bank Sta=5194.4,5200.4
Exp/Cntr=0.3,0.1

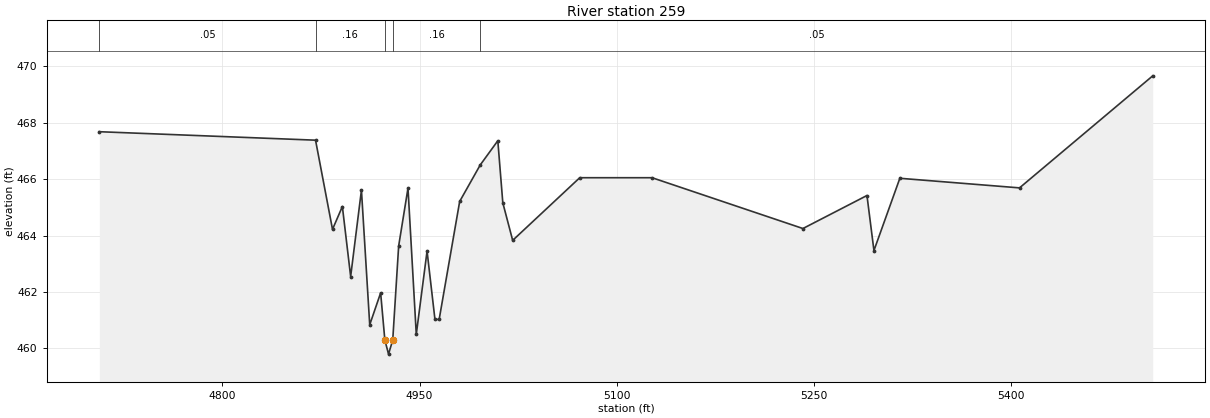
Type RM Length L Ch R = 1,259,0,0,0
BEGIN DESCRIPTION:
UNT022 IN CCTC 1.0
END DESCRIPTION:
XS GIS Cut Line= 6
      3495310.82     10636297.66      3495105.06     10636141.38
      3495024.33     10636130.97      3494982.67     10636141.38
      3494961.83     10636172.63      3494829.01     10636529.43
#Sta/Elev= 30
  4706.5  467.68  4870.9  467.38  4883.8  464.22  4891.3  465.03  4897.6  462.55
  4905.8  465.61  4912.1  460.84  4920.4  461.97  4923.6  460.30  4926.4  459.80
  4929.6  460.30  4934.1  463.63  4941.2  465.68  4947.5  460.50  4955.7  463.45
  4961.7  461.03  4964.9  461.03  4980.5  465.21  4996.1  466.50  5009.5  467.36
  5013.3  465.16  5020.8  463.83  5071.8  466.05  5126.8  466.05  5241.5  464.25
  5290.2  465.42  5295.5  463.47  5315.2  466.03  5406.2  465.69  5507.5  469.66
#Mann=5,-1,0
  4706.5    0.05       0  4870.9    0.16       0  4923.6    0.03       0
  4929.6    0.16       0  4996.1    0.05       0
Bank Sta=4923.6,4929.6
Exp/Cntr=0.3,0.1

Chan Stop Cuts=-1