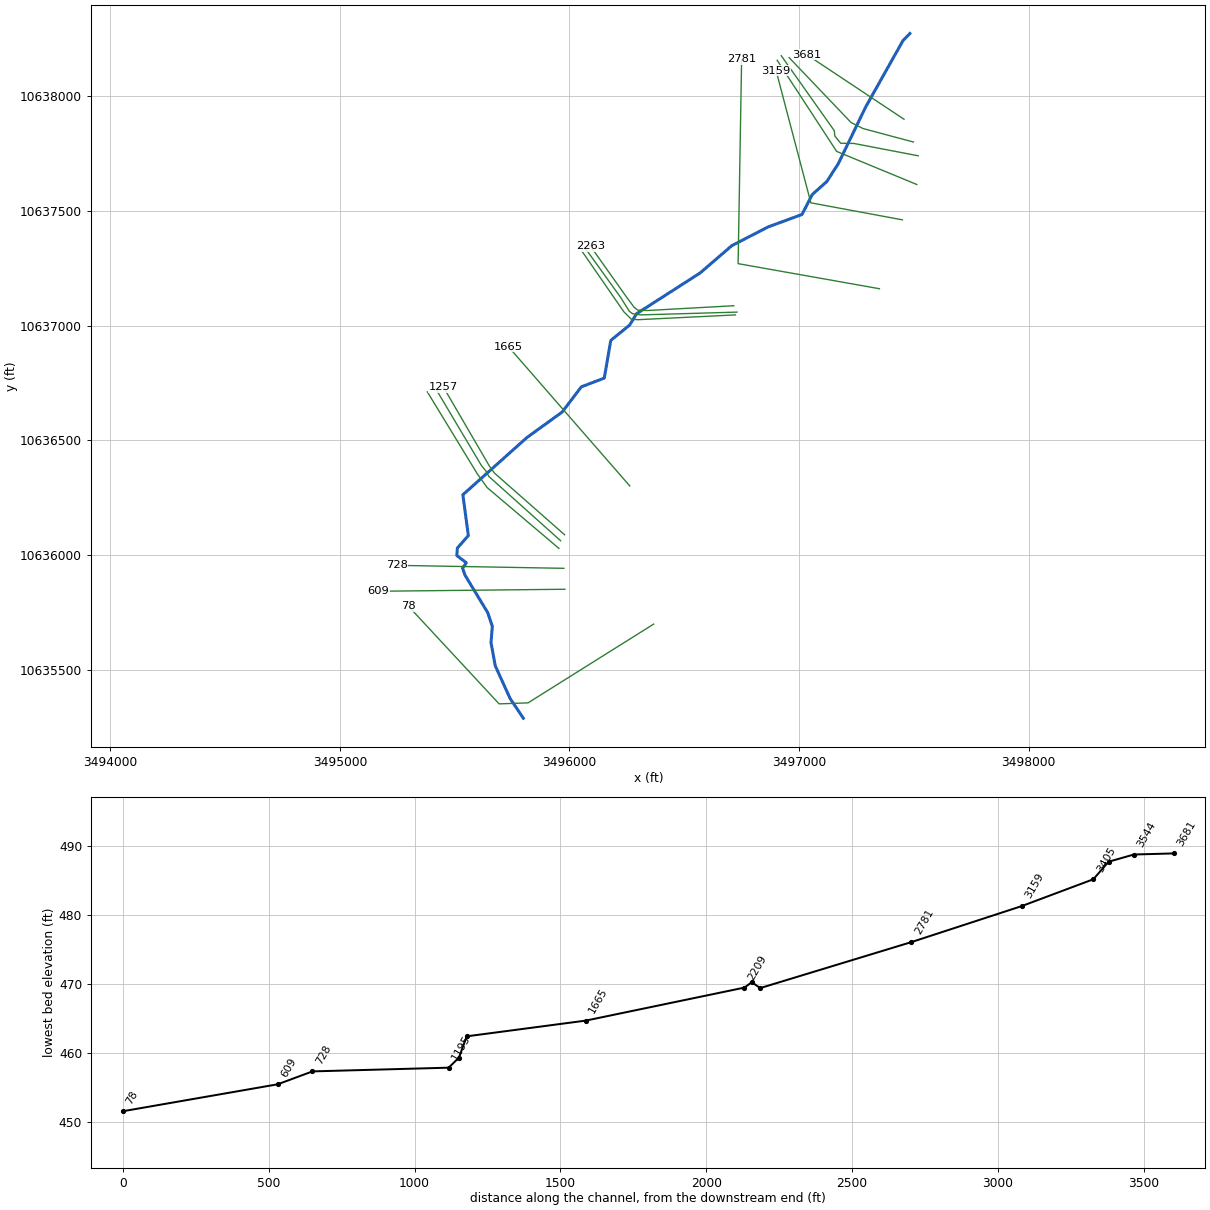
--- UNT023 IN CCTC.prj (project) ---

Proj Title=UNT023 IN CCTC Base Level Engineering
Current Plan=p01
Default Exp/Contr=0.3,0.1
English Units
Geom File=g01
Flow File=f01
Plan File=p01
Y Axis Title=Elevation
X Axis Title(PF)=Main Channel Distance
X Axis Title(XS)=Station
BEGIN DESCRIPTION:
UNT023 IN CCTC
END DESCRIPTION:
DSS Export Rating Curves= 0
DSS Export Rating Curve Sorted= 0
DSS Export Volume Flow Curves= 0
DXF OffsetX= 0
DXF OffsetY= 0
DXF ScaleX= 1
DXF ScaleY= 10

--- UNT023 IN CCTC.p01 (plan) ---

Plan Title=Multiple Run
Short Identifier=Multiple
Geom File=g01
Flow File=f01
Subcritical Flow
K Sum by GR= 0
Std Step Tol= 0.01
Critical Tol= 0.01
Num of Std Step Trials= 20
Max Error Tol= 0.3
Flow Tol Ratio= 0.001
Split Flow NTrial= 30
Split Flow Tol= 0.02
Split Flow Ratio= 0.02
Log Output Level= 0
Friction Slope Method= 1
Unsteady Friction Slope Method= 2
Unsteady Bridges Friction Slope Method= 1
Parabolic Critical Depth
Global Vel Dist=  1 , 1 , 1
Global Log Level= 0
CheckData=True
Encroach Param= -1, 0, 0, 0
BEGIN DESCRIPTION:
Multiple Run
END DESCRIPTION:

--- UNT023 IN CCTC.f01 (steady flow) ---

Flow Title=Multiple
Number of Profiles=7
Profile Names=10-year,25-year,50-year,1pct_min,100-year,1pct_plu,500-year
River Rch & RM= UNT023 IN CCTC,Reach-1,3681
     372     471     546     464     628     849     825
River Rch & RM= UNT023 IN CCTC,Reach-1,78
     470     605     710     610     825    1116    1108
Boundary for River Rch & Prof#=UNT023 IN CCTC,Reach-1,1
Up Type=0
Dn Type=3
Dn Slope=0.005
Boundary for River Rch & Prof#=UNT023 IN CCTC,Reach-1,2
Up Type=0
Dn Type=3
Dn Slope=0.005
Boundary for River Rch & Prof#=UNT023 IN CCTC,Reach-1,3
Up Type=0
Dn Type=3
Dn Slope=0.005
Boundary for River Rch & Prof#=UNT023 IN CCTC,Reach-1,4
Up Type=0
Dn Type=3
Dn Slope=0.005
Boundary for River Rch & Prof#=UNT023 IN CCTC,Reach-1,5
Up Type=0
Dn Type=3
Dn Slope=0.005
Boundary for River Rch & Prof#=UNT023 IN CCTC,Reach-1,6
Up Type=0
Dn Type=3
Dn Slope=0.005
Boundary for River Rch & Prof#=UNT023 IN CCTC,Reach-1,7
Up Type=0
Dn Type=3
Dn Slope=0.005

--- UNT023 IN CCTC.g01 (geometry) ---

Geom Title=Existing Conditions
Program Version=4.10

River Reach=UNT023 IN CCTC  ,Reach-1
Reach XY= 30
      3497482.29     10638271.47      3497452.31     10638240.77
      3497289.58     10637951.16       3497170.8     10637704.98
      3497120.45     10637626.86      3497056.94     10637570.08
      3497012.81     10637483.63      3496864.38     10637428.94
      3496707.11     10637347.86      3496569.09     10637228.94
      3496292.28     10637051.27        3496262.       10637002.
      3496179.75       10636935.       3496151.5       10636771.
      3496051.75       10636733.        3495968.       10636623.
       3495814.5       10636512.      3495535.75       10636263.
       3495559.5       10636085.      3495511.75       10636031.
       3495509.5       10635998.      3495550.75       10635967.
       3495534.5       10635943.       3495545.5       10635912.
      3495643.75       10635750.        3495664.       10635690.
      3495658.25       10635619.      3495676.75       10635518.
      3495741.75       10635375.        3495799.       10635290.

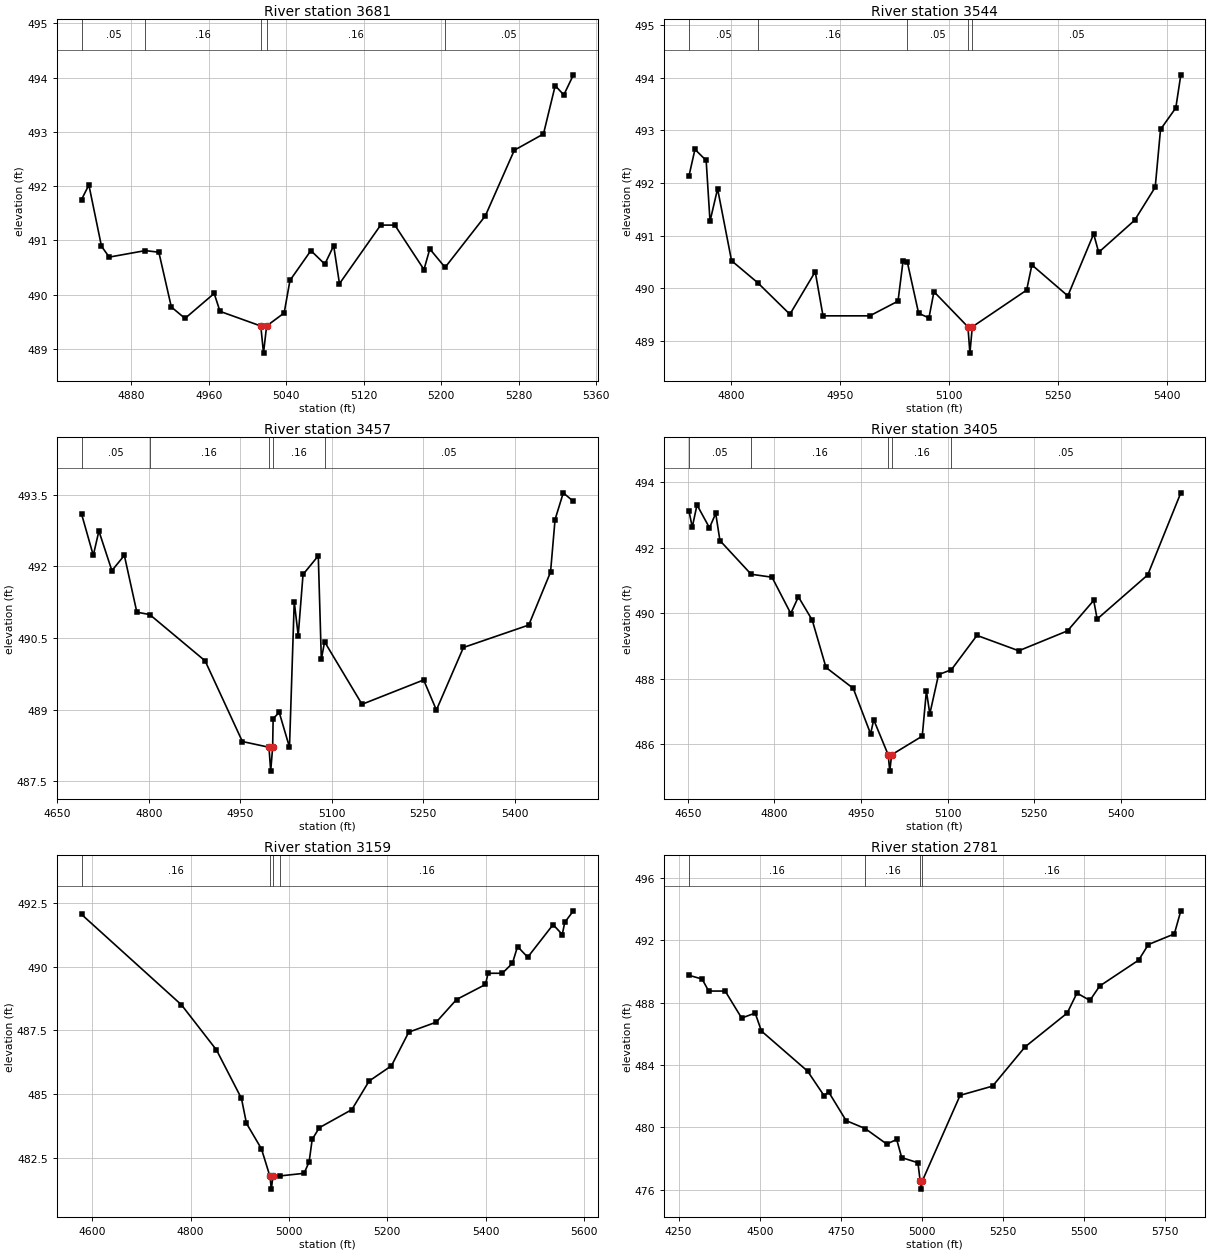
Type RM Length L Ch R = 1 ,3681    ,137,137,137
BEGIN DESCRIPTION:
UNT023 IN CCTC 7.0
END DESCRIPTION:
XS GIS Cut Line= 2
       3497456.8     10637898.25      3497033.92     10638179.01
#Sta/Elev= 30
  4828.7  491.75  4836.3  492.02  4849.3  490.89  4857.3  490.69  4894.6  490.81
  4908.5  490.78  4921.4  489.77  4935.5  489.56  4965.6  490.02  4971.6  489.69
  5013.7  489.42  5016.5  488.92  5019.7  489.42  5037.8  489.66  5043.8  490.26
  5065.4  490.81  5079.8  490.56  5088.9   490.9  5094.9   490.2  5137.4  491.28
    5152  491.28  5182.1  490.46  5188.1  490.84  5203.9   490.5  5245.4  491.45
  5275.3  492.66  5305.4  492.96  5317.5  493.85  5326.4  493.68  5336.3  494.05
#Mann= 5 ,-1 , 0
  4828.7     .05       0  4894.6     .16       0  5013.7     .07       0
  5019.7     .16       0  5203.9     .05       0
Bank Sta=5013.7,5019.7
XS Rating Curve= 0 ,0
Exp/Cntr=0.3,0.1

Type RM Length L Ch R = 1 ,3544    ,87,87,87
BEGIN DESCRIPTION:
Mapping XS 6e98104e
END DESCRIPTION:
XS GIS Cut Line= 4
      3497497.65     10637799.08      3497278.48     10637857.67
       3497226.4     10637883.71      3496956.47      10638166.6
#Sta/Elev= 30
  4742.5  492.13  4750.8  492.64  4766.2  492.43  4771.5  491.27  4781.9  491.89
  4801.1  490.52  4837.1   490.1  4881.3   489.5  4916.1  490.31  4926.8  489.47
  4991.1  489.47  5029.9  489.75  5036.8  490.51  5042.6   490.5  5058.2  489.52
  5072.4  489.43  5079.3  489.93    5126  489.26  5128.7  488.76    5132  489.26
  5206.7  489.96  5213.9  490.44  5263.3  489.85  5298.8  491.03  5305.7  490.68
  5355.1  491.29  5383.4  491.92  5390.7  493.02  5411.7  493.43  5418.6  494.06
#Mann= 5 ,-1 , 0
  4742.5     .05       0  4837.1     .16       0  5042.6     .05       0
    5126     .07       0    5132     .05       0
Bank Sta=5126,5132
XS Rating Curve= 0 ,0
Exp/Cntr=0.3,0.1

Type RM Length L Ch R = 1 ,3457    ,52,52,52
BEGIN DESCRIPTION:
Mapping XS 650abc11
END DESCRIPTION:
XS GIS Cut Line= 6
      3497518.55     10637739.03       3497238.2     10637792.84
      3497180.91     10637793.71      3497155.73     10637824.96
      3497153.13      10637848.4      3496922.22      10638174.8
#Sta/Elev= 30
  4689.7   493.1    4709  492.23  4718.2  492.74  4739.5  491.91  4759.9  492.23
  4780.4  491.04  4801.5  490.99  4892.3  490.02  4953.4  488.33    4997  488.21
  4999.8  487.71    5003  488.21  5003.8  488.81  5013.8  488.94  5030.6  488.21
  5038.4  491.26  5044.9  490.55  5052.8  491.83  5077.8  492.22  5082.8  490.05
  5088.1  490.42  5149.5  489.11  5250.5  489.62  5271.4  488.99  5315.7   490.3
  5422.8  490.77  5458.5  491.88  5465.9  492.98  5479.4  493.54    5496  493.36
#Mann= 5 ,-1 , 0
  4689.7     .05       0  4801.5     .16       0    4997     .07       0
    5003     .16       0  5088.1     .05       0
Bank Sta=4997,5003
XS Rating Curve= 0 ,0
Exp/Cntr=0.3,0.1

Type RM Length L Ch R = 1 ,3405    ,246,246,246
BEGIN DESCRIPTION:
Mapping XS 68ddd7c8
END DESCRIPTION:
XS GIS Cut Line= 3
      3497512.54     10637614.01      3497163.54     10637758.12
      3496904.47     10638154.96
#Sta/Elev= 30
  4652.1  493.13  4657.9  492.63  4666.1  493.31  4687.7  492.61  4698.5  493.05
  4705.8  492.22  4759.8  491.19  4795.9   491.1  4828.4  489.99  4841.6   490.5
  4865.5  489.79  4889.4  488.34  4936.6   487.7  4966.6  486.31    4972  486.74
    4997  485.67  4999.8  485.17    5003  485.67    5056  486.24  5063.2  487.62
  5069.1  486.92  5084.2  488.12  5106.4  488.27  5150.7  489.32  5223.1  488.85
  5307.5  489.46  5352.8  490.39  5358.8  489.82  5446.3  491.17  5503.6  493.68
#Mann= 5 ,-1 , 0
  4652.1     .05       0  4759.8     .16       0    4997     .07       0
    5003     .16       0  5106.4     .05       0
Bank Sta=4997,5003
XS Rating Curve= 0 ,0
Exp/Cntr=0.3,0.1

Type RM Length L Ch R = 1 ,3159    ,378,378,378
BEGIN DESCRIPTION:
UNT023 IN CCTC 6.0
END DESCRIPTION:
XS GIS Cut Line= 3
      3497449.56      10637460.2      3497051.19     10637534.16
      3496899.61     10638110.17
#Sta/Elev= 30
    4578  492.05  4781.4   488.5  4852.6  486.73  4903.4  484.83  4913.6  483.85
  4944.1  482.85  4961.4  481.77  4964.2  481.27  4967.4  481.77  4982.6  481.79
  5030.8  481.89  5041.1  482.34  5047.3  483.22  5061.8  483.68    5128  484.39
  5163.1  485.51  5208.6  486.11  5243.8  487.43  5299.6  487.82    5341  488.71
  5399.9   489.3  5405.1  489.74  5434.1  489.74  5454.7  490.13  5465.1  490.79
  5485.8  490.37  5537.5  491.65  5556.1  491.26  5561.2  491.74  5578.8  492.19
#Mann= 4 ,-1 , 0
    4578     .16       0  4961.4     .07       0  4967.4     .05       0
  4982.6     .16       0
Bank Sta=4961.4,4967.4
XS Rating Curve= 0 ,0
Exp/Cntr=0.3,0.1

Type RM Length L Ch R = 1 ,2781    ,518,518,518
BEGIN DESCRIPTION:
UNT023 IN CCTC 5.0
END DESCRIPTION:
XS GIS Cut Line= 3
       3497349.6     10637160.19      3496734.35      10637269.4
      3496749.61     10638160.21
#Sta/Elev= 30
  4281.8  489.75  4322.4  489.51  4342.7  488.74  4393.5  488.74  4444.3  487.01
    4486  487.33  4505.2  486.18  4647.4  483.61  4698.2  482.04  4712.2  482.28
  4766.2  480.44    4825  479.93  4891.2  478.94  4922.1  479.23  4937.5  478.07
  4987.5  477.74  4994.5  476.55  4997.2  476.05  5000.5  476.55  5117.5  482.06
  5217.5  482.65  5317.5  485.16  5447.5  487.33  5477.5  488.61  5517.5  488.14
  5547.5  489.06  5667.6  490.72  5697.6  491.72  5777.6   492.4  5797.6  493.88
#Mann= 4 ,-1 , 0
  4281.8     .16       0    4825     .16       0  4994.5     .07       0
  5000.5     .16       0
Bank Sta=4994.5,5000.5
XS Rating Curve= 0 ,0
Exp/Cntr=0.3,0.1

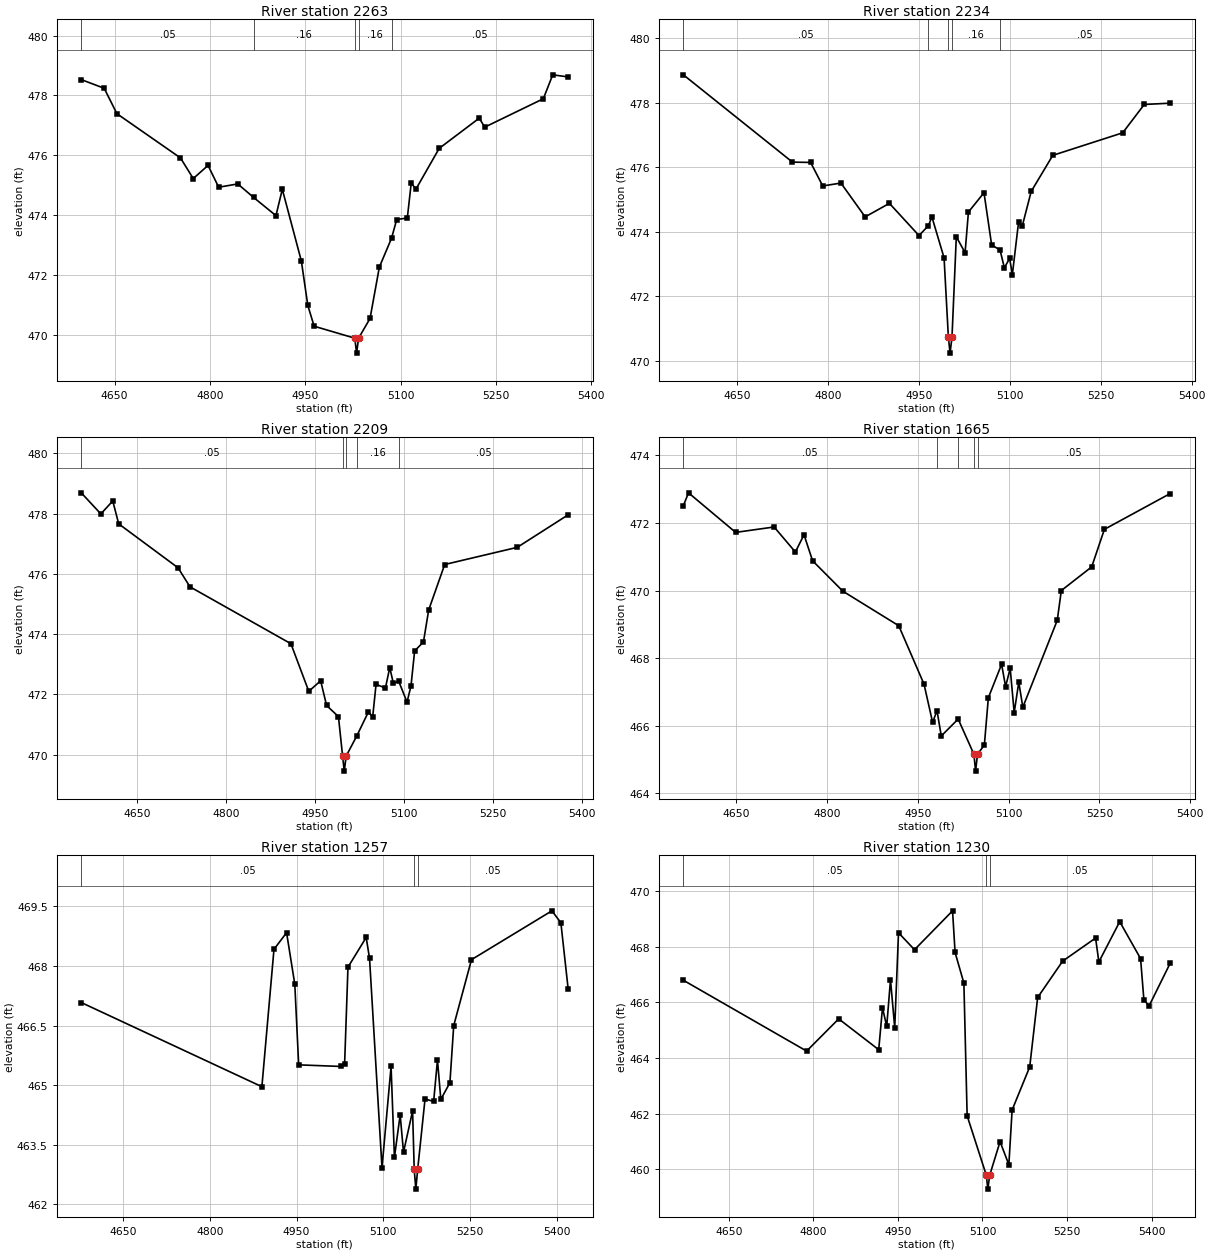
Type RM Length L Ch R = 1 ,2263    ,29,29,29
BEGIN DESCRIPTION:
Mapping XS f26c1b79
END DESCRIPTION:
XS GIS Cut Line= 6
      3496715.62     10637086.12      3496338.89     10637065.28
      3496297.22     10637067.02       3496281.6     10637079.17
      3496246.87     10637126.05      3496091.13     10637345.82
#Sta/Elev= 30
  4597.4  478.53  4633.5  478.24  4653.5  477.39  4753.6  475.91  4773.7  475.22
    4797  475.66  4813.7  474.93  4843.8  475.04  4868.6  474.59  4903.9  473.98
  4913.9  474.86  4943.9  472.46    4954  470.98    4964  470.28    5028  469.88
  5030.8  469.38    5034  469.88    5052  470.54  5066.7  472.26  5085.8  473.22
    5094  473.85  5110.7   473.9  5116.9  475.08  5124.1  474.86  5160.9  476.23
  5223.9  477.24  5232.6  476.94  5324.8  477.89  5339.6  478.69  5363.9  478.62
#Mann= 5 ,-1 , 0
  4597.4     .05       0  4868.6     .16       0    5028     .07       0
    5034     .16       0  5085.8     .05       0
Bank Sta=5028,5034
XS Rating Curve= 0 ,0
Exp/Cntr=0.3,0.1

Type RM Length L Ch R = 1 ,2234    ,25,25,25
BEGIN DESCRIPTION:
Mapping XS d9fee973
END DESCRIPTION:
XS GIS Cut Line= 6
      3496729.51     10637058.34      3496311.11     10637046.19
      3496274.65      10637051.4      3496260.76     10637061.81
      3496222.57     10637122.58       3496071.5     10637332.68
#Sta/Elev= 30
  4561.2  478.87  4741.2  476.16  4771.2  476.15  4791.2  475.42  4821.2  475.51
  4861.2  474.46  4901.2  474.88    4950  473.88  4965.7  474.19  4971.3  474.46
  4991.4  473.19  4998.5  470.73  5001.3  470.23  5004.5  470.73  5011.6  473.84
  5026.1  473.35  5031.6  474.61  5057.3  475.21  5069.9  473.59  5083.8  473.43
  5090.9  472.88  5099.6  473.17  5104.1  472.67  5114.3  474.29  5120.5  474.18
  5135.2  475.25  5170.8  476.37  5286.2  477.07  5321.8  477.95  5364.7  477.99
#Mann= 5 ,-1 , 0
  4561.2     .05       0  4965.7     .16       0  4998.5     .07       0
  5004.5     .16       0  5083.8     .05       0
Bank Sta=4998.5,5004.5
XS Rating Curve= 0 ,0
Exp/Cntr=0.3,0.1

Type RM Length L Ch R = 1 ,2209    ,544,544,544
BEGIN DESCRIPTION:
UNT023 IN CCTC 4.0
END DESCRIPTION:
XS GIS Cut Line= 5
      3496722.61     10637046.19      3496298.96     10637025.35
      3496269.44     10637027.09      3496236.46     10637060.08
       3496054.4     10637323.63
#Sta/Elev= 30
  4556.1  478.69  4589.1  477.99  4609.2  478.42  4619.2  477.66  4719.3   476.2
  4739.3  475.57  4909.5  473.68  4939.6   472.1  4959.6  472.45  4969.6  471.63
  4989.6  471.26  4996.6  469.95  4999.4  469.45  5002.6  469.95  5020.3  470.61
  5040.2  471.42  5047.3  471.25    5053  472.33  5068.8  472.21  5076.1  472.89
  5082.2  472.36  5091.1  472.44  5105.2  471.74  5111.9  472.28    5118  473.44
  5132.9  473.74  5141.7   474.8  5168.7  476.31    5291  476.88  5376.8  477.96
#Mann= 5 ,-1 , 0
  4556.1     .05       0  4996.6    .035       0  5002.6     .05       0
  5020.3     .16       0  5091.1     .05       0
Bank Sta=4996.6,5002.6
XS Rating Curve= 0 ,0
Exp/Cntr=0.3,0.1

Type RM Length L Ch R = 1 ,1665    ,408,408,408
BEGIN DESCRIPTION:
UNT023 IN CCTC 3.0
END DESCRIPTION:
XS GIS Cut Line= 2
      3496262.52     10636301.37      3495733.78     10636908.12
#Sta/Elev= 30
  4562.2  472.51  4570.7  472.89  4648.6  471.72  4712.2  471.88  4747.3  471.14
  4761.6  471.65  4775.8  470.88  4825.9  469.98  4918.2  468.96    4960  467.23
  4974.2   466.1  4981.4  466.45  4988.5   465.7  5016.4   466.2  5042.4  465.16
  5045.2  464.66  5048.4  465.16  5059.7  465.43  5066.3  466.83  5088.2  467.82
  5094.8  467.16  5102.4   467.7    5109  466.39  5116.6  467.29  5123.3  466.55
  5180.2  469.12  5186.9     470  5237.1   470.7  5258.1  471.81    5367  472.87
#Mann= 5 ,-1 , 0
  4562.2     .05       0  4981.4     .16       0  5016.4     .05       0
  5042.4     .07       0  5048.4     .05       0
Bank Sta=5042.4,5048.4
XS Rating Curve= 0 ,0
Exp/Cntr=0.3,0.1

Type RM Length L Ch R = 1 ,1257    ,27,27,27
BEGIN DESCRIPTION:
Mapping XS c57ea27d
END DESCRIPTION:
XS GIS Cut Line= 4
      3495978.73     10636088.74      3495672.76     10636357.82
      3495651.06      10636388.2      3495451.39     10636731.12
#Sta/Elev= 30
  4577.8  467.08    4890  464.96  4910.9  468.42  4932.7  468.84  4946.9  467.54
  4953.6  465.51  5026.6  465.47    5033  465.53  5038.8  467.97  5070.3  468.72
  5076.1  468.19  5097.6  462.92  5113.3  465.47  5119.1  463.18    5129  464.25
  5134.8  463.31  5150.5  464.35  5153.3  462.88  5156.1  462.38  5159.3  462.88
    5172  464.65  5186.9  464.59  5193.5  465.63  5199.3  464.64    5215  465.06
  5221.6   466.5  5252.3  468.16  5391.3  469.39  5406.8  469.09  5419.4  467.42
#Mann= 3 ,-1 , 0
  4577.8     .05       0  5153.3    .035       0  5159.3     .05       0
Bank Sta=5153.3,5159.3
XS Rating Curve= 0 ,0
Exp/Cntr=0.3,0.1

Type RM Length L Ch R = 1 ,1230    ,35,35,35
BEGIN DESCRIPTION:
Mapping XS ff74930f
END DESCRIPTION:
XS GIS Cut Line= 5
      3495961.38      10636062.7      3495648.89     10636342.63
      3495635.87      10636366.5      3495616.34     10636390.37
      3495418.85     10636722.41
#Sta/Elev= 30
  4569.3   466.8    4788  464.25  4844.9  465.41  4915.9   464.3  4922.6  465.81
  4930.1  465.14  4936.8  466.82  4944.3  465.09    4951  468.51  4979.4   467.9
  5046.9   469.3  5051.4   467.8    5067   466.7  5072.8  461.92  5106.8  459.78
  5109.5  459.28  5112.8  459.78  5131.2  460.99  5146.8  460.16  5152.6  462.13
  5183.8  463.68  5197.9  466.18  5242.3  467.49  5300.7  468.32  5306.5  467.46
  5343.5  468.91  5380.5  467.58  5386.4  466.09  5395.7  465.88  5433.2  467.42
#Mann= 3 ,-1 , 0
  4569.3     .05       0  5106.8    .035       0  5112.8     .05       0
Bank Sta=5106.8,5112.8
XS Rating Curve= 0 ,0
Exp/Cntr=0.3,0.1

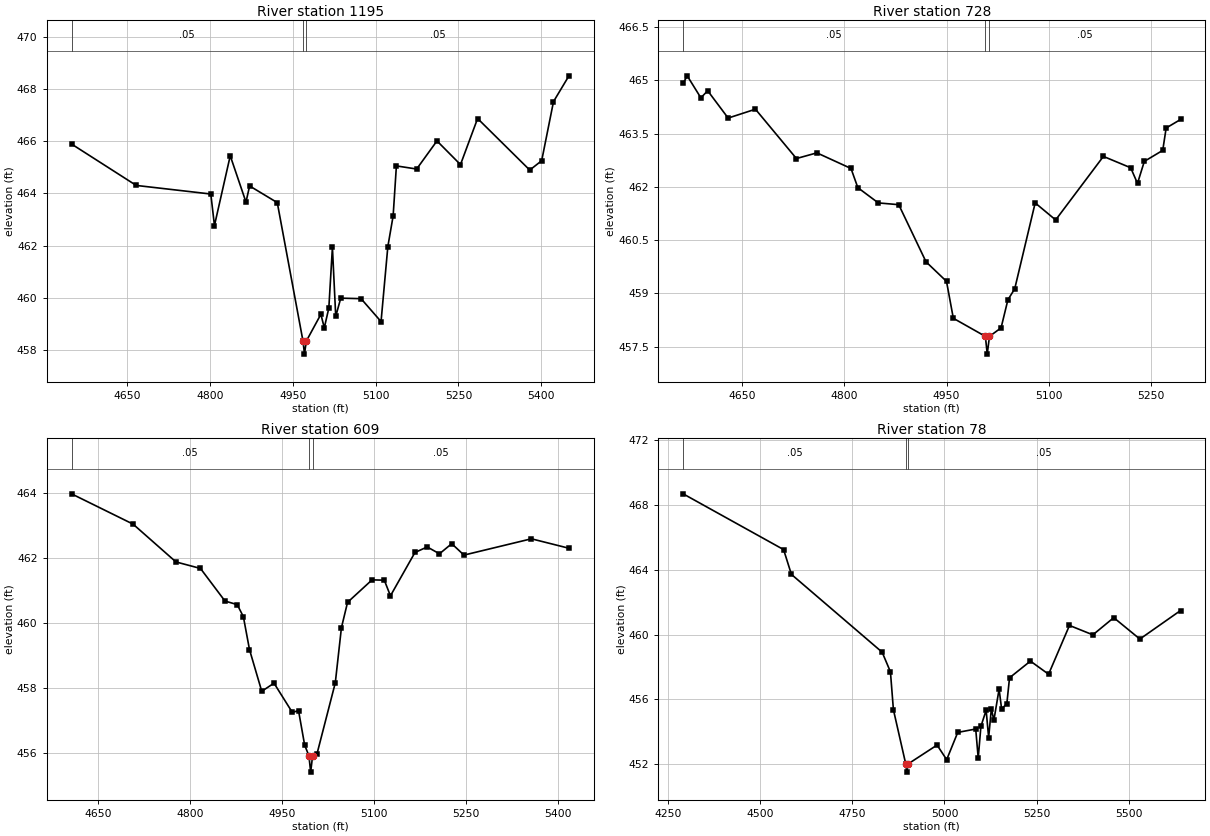
Type RM Length L Ch R = 1 ,1195    ,467,467,467
BEGIN DESCRIPTION:
Mapping XS 6826d456
END DESCRIPTION:
XS GIS Cut Line= 4
      3495953.97     10636029.41      3495641.48     10636294.16
      3495598.07     10636354.93      3495381.06     10636710.84
#Sta/Elev= 30
  4549.2   465.9  4666.4  464.31  4801.5  463.98  4808.1  462.77  4836.7  465.45
  4865.2  463.67  4871.8  464.29  4921.9  463.65  4968.5  458.33  4971.2  457.83
  4974.5  458.33  5000.9  459.36  5007.1  458.84  5015.3   459.6  5021.8  461.93
  5027.8  459.28  5036.9  459.98  5073.7  459.96  5109.9  459.08  5122.2  461.96
  5131.8  463.14  5137.7  465.06  5174.4  464.94  5211.2  466.02  5253.8  465.11
  5284.8  466.88  5379.3   464.9  5400.9  465.26  5422.3  467.53  5450.3  468.52
#Mann= 3 ,-1 , 0
  4549.2     .05       0  4968.5    .035       0  4974.5     .05       0
Bank Sta=4968.5,4974.5
XS Rating Curve= 0 ,0
Exp/Cntr=0.3,0.1

Type RM Length L Ch R = 1 ,728     ,119,119,119
BEGIN DESCRIPTION:
Mapping XS d9e34434
END DESCRIPTION:
XS GIS Cut Line= 2
      3495975.63      10635942.6      3495246.55     10635955.62
#Sta/Elev= 30
  4563.8  464.92  4569.8  465.13  4589.8  464.51  4599.8  464.71  4629.8  463.94
  4669.8  464.19  4729.9   462.8  4759.9  462.96  4809.9  462.52  4819.9  461.98
  4849.9  461.55  4879.9   461.5  4919.9  459.89  4949.9  459.34  4959.9   458.3
  5006.9  457.79  5009.6  457.29  5012.9  457.79  5029.9  458.03  5039.9  458.82
  5049.9  459.13  5079.9  461.55  5109.9  461.07  5179.9  462.86  5219.9  462.54
  5229.9   462.1  5239.9  462.72  5266.9  463.03  5271.9  463.66    5293   463.9
#Mann= 3 ,-1 , 0
  4563.8     .05       0  5006.9     .04       0  5012.9     .05       0
Bank Sta=5006.9,5012.9
XS Rating Curve= 0 ,0
Exp/Cntr=0.3,0.1

Type RM Length L Ch R = 1 ,609     ,531,531,531
BEGIN DESCRIPTION:
UNT023 IN CCTC 1.0
END DESCRIPTION:
XS GIS Cut Line= 2
        3495980.     10635851.45      3495168.35     10635842.77
#Sta/Elev= 30
  4606.9  463.96  4707.3  463.03  4777.3  461.87  4817.3  461.67  4857.3  460.67
  4877.3  460.56  4887.3  460.19  4897.3  459.18  4917.3   457.9  4937.3  458.15
  4967.3  457.25  4977.3  457.31  4987.3  456.25  4994.3  455.92  4997.1  455.42
  5000.3  455.92  5007.3  455.97  5037.3  458.16  5047.3  459.85  5057.3  460.63
  5097.3  461.32  5117.3  461.31  5127.3  460.83  5167.3  462.16  5187.3  462.33
  5207.3  462.12  5227.3  462.43  5247.3  462.08  5357.3  462.58  5418.6  462.29
#Mann= 3 ,-1 , 0
  4606.9     .05       0  4994.3    .035       0  5000.3     .05       0
Bank Sta=4994.3,5000.3
XS Rating Curve= 0 ,0
Exp/Cntr=0.3,0.1

Type RM Length L Ch R = 1 ,78      ,0,0,0
BEGIN DESCRIPTION:
UNT023 IN CCTC 2.0
END DESCRIPTION:
XS GIS Cut Line= 4
      3496366.34     10635699.57      3495819.43     10635356.66
      3495693.56     10635352.32      3495299.76     10635776.42
#Sta/Elev= 30
  4290.6  468.68  4563.3  465.24  4584.5  463.71  4830.8  458.91  4853.3   457.7
  4861.4  455.36  4894.9  452.01  4897.7  451.51  4900.9  452.01  4979.9  453.18
    5006  452.28    5036  453.96  5084.8  454.17  5091.6  452.37  5098.9  454.33
  5113.1  455.33  5119.9  453.64  5127.3  455.42  5134.1  454.71  5148.3  456.63
  5155.1   455.4  5169.3  455.74  5176.6  457.33  5233.3  458.36  5282.6  457.55
  5339.3  460.56  5402.8  459.98  5459.5  461.04  5530.4  459.72  5640.8  461.48
#Mann= 3 ,-1 , 0
  4290.6     .05       0  4894.9    .035       0  4900.9     .05       0
Bank Sta=4894.9,4900.9
XS Rating Curve= 0 ,0
Exp/Cntr=0.3,0.1

Chan Stop Cuts=-1
Use User Specified Reach Order=0
Composite Channel Slope=5