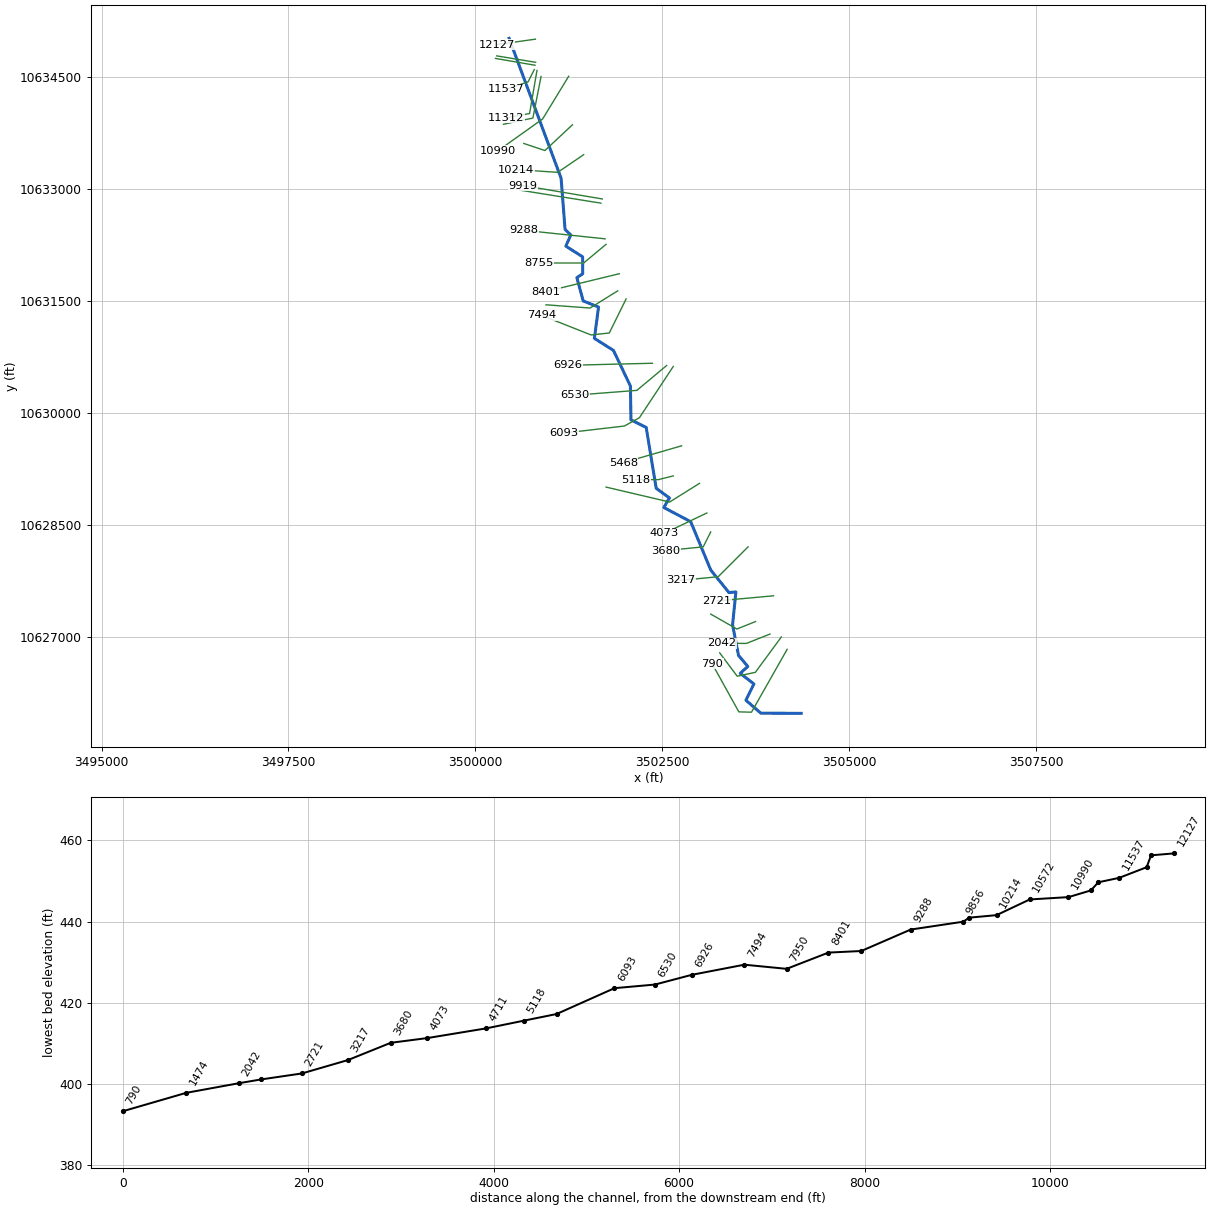
--- UNT024 IN CCTC.prj (project) ---

Proj Title=UNT024 IN CCTC Base Level Engineering
Current Plan=p01
Default Exp/Contr=0.3,0.1
English Units
Geom File=g01
Flow File=f01
Plan File=p01
BEGIN DESCRIPTION:
UNT024 IN CCTC
END DESCRIPTION:

--- UNT024 IN CCTC.p01 (plan) ---

Plan Title=Multiple Run
Short Identifier=Multiple
Geom File=g01
Flow File=f01
Subcritical Flow
K Sum by GR= 0
Std Step Tol= 0.01
Critical Tol= 0.01
Num of Std Step Trials= 20
Max Error Tol= 0.3
Flow Tol Ratio= 0.001
Split Flow NTrial= 30
Split Flow Tol= 0.02
Split Flow Ratio= 0.02
Log Output Level= 0
Friction Slope Method= 1
Unsteady Friction Slope Method= 2
Unsteady Bridges Friction Slope Method= 1
Parabolic Critical Depth
Global Vel Dist=  1 , 1 , 1
Global Log Level= 0
CheckData=True
Encroach Param= -1, 0, 0, 0
BEGIN DESCRIPTION:
Multiple Run
END DESCRIPTION:

--- UNT024 IN CCTC.f01 (steady flow) ---

Flow Title=Multiple
Number of Profiles=7
Profile Names=10-year,25-year,50-year,1pct_min,100-year,1pct_plu,500-year
River Rch & RM= UNT024 IN CCTC,Reach-1,12127
     332     415     477     402     544     735     701
River Rch & RM= UNT024 IN CCTC,Reach-1,10214
    1035    1396    1687    1488    2013    2722    2856
Boundary for River Rch & Prof#=UNT024 IN CCTC,Reach-1,1
Up Type=0
Dn Type=3
Dn Slope=0.005
Boundary for River Rch & Prof#=UNT024 IN CCTC,Reach-1,2
Up Type=0
Dn Type=3
Dn Slope=0.005
Boundary for River Rch & Prof#=UNT024 IN CCTC,Reach-1,3
Up Type=0
Dn Type=3
Dn Slope=0.005
Boundary for River Rch & Prof#=UNT024 IN CCTC,Reach-1,4
Up Type=0
Dn Type=3
Dn Slope=0.005
Boundary for River Rch & Prof#=UNT024 IN CCTC,Reach-1,5
Up Type=0
Dn Type=3
Dn Slope=0.005
Boundary for River Rch & Prof#=UNT024 IN CCTC,Reach-1,6
Up Type=0
Dn Type=3
Dn Slope=0.005
Boundary for River Rch & Prof#=UNT024 IN CCTC,Reach-1,7
Up Type=0
Dn Type=3
Dn Slope=0.005

--- UNT024 IN CCTC.g01 (geometry) ---

Geom Title=Existing Conditions

River Reach=UNT024 IN CCTC,Reach-1
Reach XY= 30
      3500452.28     10635017.77      3501148.00     10633145.00
      3501201.00     10632460.00      3501277.50     10632385.00
      3501211.25     10632236.00      3501436.00     10632093.00
      3501437.25     10631866.00      3501358.75     10631814.00
      3501443.75     10631502.00      3501648.75     10631420.00
      3501593.50     10631001.00      3501848.75     10630840.00
      3502075.25     10630363.00      3502082.50     10629911.00
      3502286.25     10629809.00      3502420.50     10628994.00
      3502597.25     10628865.00      3502522.75     10628737.00
      3502882.00     10628547.00      3503150.00     10627900.00
      3503393.75     10627598.00      3503486.25     10627607.00
      3503442.00     10627166.00      3503522.00     10626756.00
      3503645.75     10626609.00      3503544.25     10626517.00
      3503727.50     10626375.00      3503620.25     10626157.00
      3503819.75     10625984.00      3504360.25     10625981.00

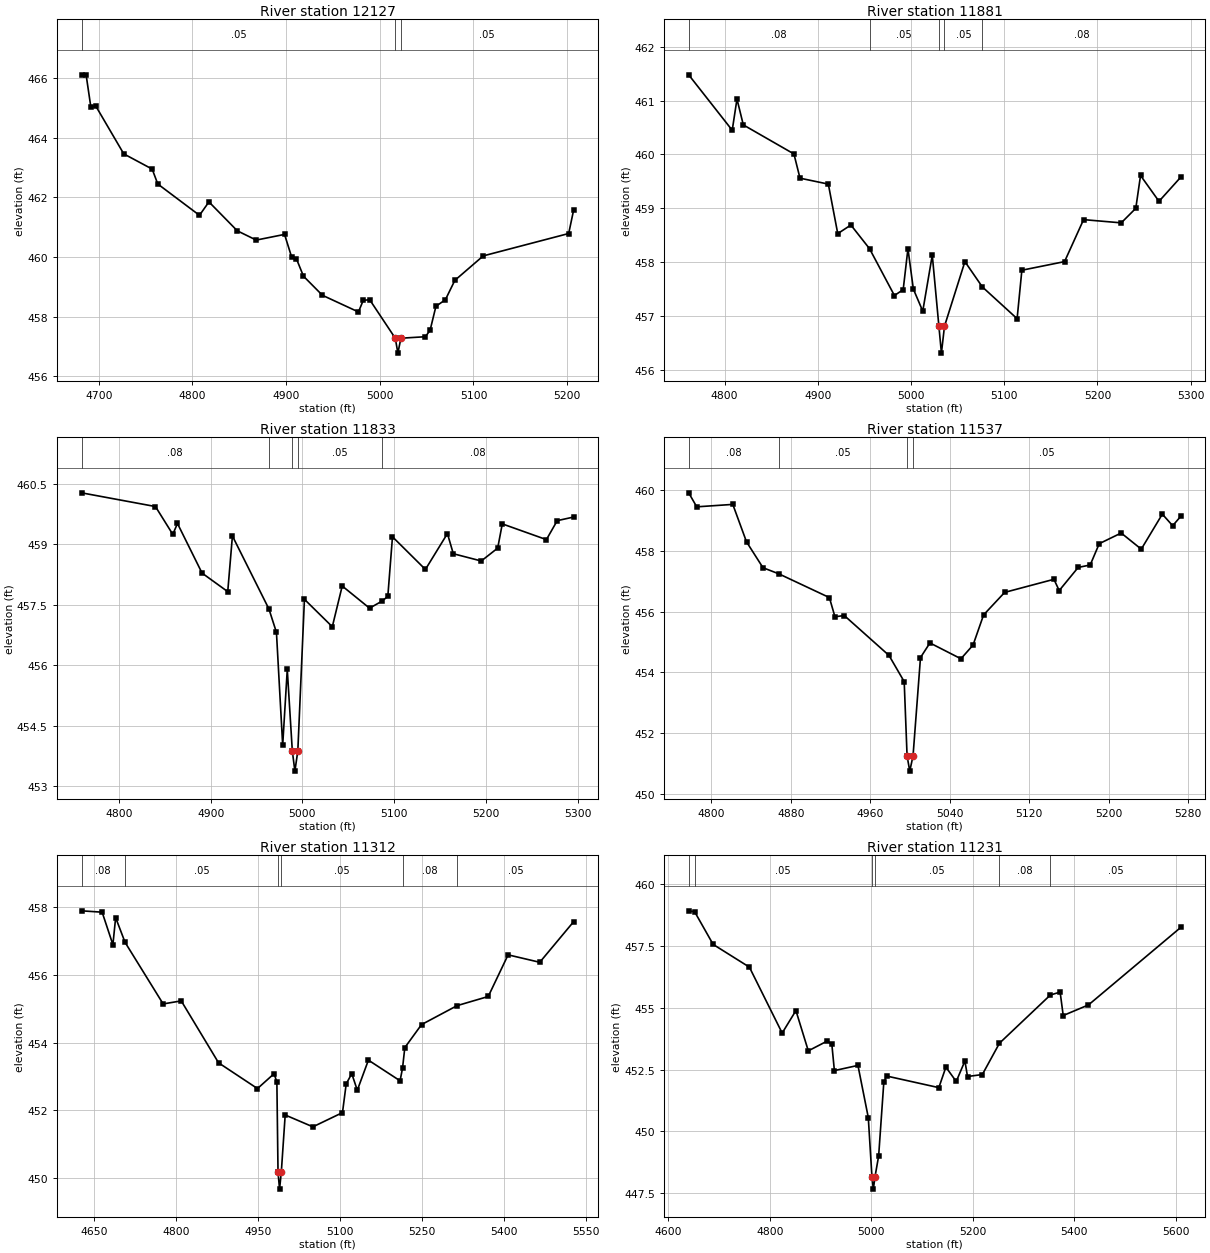
Type RM Length L Ch R = 1,12127,246,246,246
BEGIN DESCRIPTION:
UNT024 IN CCTC 22.0
END DESCRIPTION:
XS GIS Cut Line= 2
      3500804.26     10635006.62      3500284.04     10634933.79
#Sta/Elev= 30
  4681.6  466.11  4686.5  466.11  4691.6  465.02  4696.7  465.07  4726.7  463.46
  4757.0  462.95  4763.0  462.45  4807.5  461.40  4817.6  461.85  4847.9  460.88
  4868.1  460.57  4898.3  460.76  4905.8  460.01  4910.9  459.95  4918.5  459.36
  4938.7  458.72  4977.2  458.16  4982.3  458.55  4989.2  458.57  5016.5  457.28
  5019.3  456.78  5022.5  457.28  5048.7  457.33  5053.7  457.55  5059.9  458.35
  5070.0  458.57  5080.1  459.22  5110.4  460.04  5201.6  460.79  5206.9  461.58
#Mann=3,-1,0
  4681.6    0.05       0  5016.5    0.04       0  5022.5    0.05       0
Bank Sta=5016.5,5022.5
Exp/Cntr=0.3,0.1

Type RM Length L Ch R = 1,11881,48,48,48
BEGIN DESCRIPTION:
Mapping XS 1bc61227
END DESCRIPTION:
XS GIS Cut Line= 2
      3500807.39     10634697.03      3500286.53     10634782.97
#Sta/Elev= 30
  4761.5  461.48  4808.2  460.45  4813.3  461.03  4820.1  460.55  4874.4  460.01
  4880.9  459.56  4911.3  459.45  4921.4  458.53  4935.5  458.69  4955.5  458.25
  4982.2  457.38  4991.6  457.49  4996.7  458.25  5002.5  457.50  5012.6  457.09
  5022.8  458.13  5029.9  456.81  5032.6  456.31  5035.9  456.81  5057.8  458.01
  5076.5  457.54  5113.8  456.95  5118.9  457.85  5164.7  458.01  5185.1  458.79
  5225.5  458.73  5241.1  459.00  5246.2  459.61  5266.0  459.13  5289.4  459.58
#Mann=5,-1,0
  4761.5    0.08       0  4955.5    0.05       0  5029.9    0.04       0
  5035.9    0.05       0  5076.5    0.08       0
Bank Sta=5029.9,5035.9
Exp/Cntr=0.3,0.1

Type RM Length L Ch R = 1,11833,296,296,296
BEGIN DESCRIPTION:
Mapping XS f3d0bc76
END DESCRIPTION:
XS GIS Cut Line= 2
      3500799.06     10634657.65      3500270.36     10634748.81
#Sta/Elev= 30
  4759.2  460.28  4839.8  459.94  4858.7  459.25  4863.8  459.52  4890.6  458.29
  4918.6  457.83  4923.7  459.21  4963.5  457.40  4971.7  456.82  4978.5  454.02
  4983.5  455.90  4989.0  453.88  4991.8  453.38  4995.0  453.88  5002.2  457.64
  5032.6  456.96  5043.4  457.97  5073.2  457.42  5086.4  457.59  5093.1  457.71
  5098.2  459.19  5134.1  458.38  5158.1  459.27  5164.5  458.77  5195.0  458.59
  5212.9  458.91  5217.9  459.51  5266.0  459.12  5277.8  459.59  5295.7  459.68
#Mann=5,-1,0
  4759.2    0.08       0  4963.5    0.05       0  4989.0    0.04       0
  4995.0    0.05       0  5086.4    0.08       0
Bank Sta=4989,4995
Exp/Cntr=0.3,0.1

Type RM Length L Ch R = 1,11537,225,225,225
BEGIN DESCRIPTION:
Mapping XS af0f547f
END DESCRIPTION:
XS GIS Cut Line= 3
      3500789.58     10634599.80      3500706.25     10634435.75
      3500411.98     10634334.19
#Sta/Elev= 30
  4777.3  459.90  4785.4  459.44  4821.7  459.52  4835.5  458.29  4852.1  457.44
  4868.0  457.24  4918.9  456.46  4924.5  455.83  4933.9  455.87  4978.9  454.56
  4994.2  453.70  4997.1  451.26  4999.8  450.76  5003.1  451.26  5010.6  454.49
  5020.1  454.97  5051.3  454.45  5063.5  454.90  5074.1  455.89  5095.3  456.63
  5144.9  457.06  5150.2  456.69  5169.3  457.45  5181.4  457.53  5190.5  458.23
  5212.6  458.58  5232.8  458.05  5254.0  459.20  5264.4  458.82  5272.6  459.13
#Mann=4,-1,0
  4777.3    0.08       0  4868.0    0.05       0  4997.1   0.035       0
  5003.1    0.05       0
Bank Sta=4997.1,5003.1
Exp/Cntr=0.3,0.1

Type RM Length L Ch R = 1,11312,81,81,81
BEGIN DESCRIPTION:
Mapping XS d3a33b64
END DESCRIPTION:
XS GIS Cut Line= 3
      3500825.07     10634587.32      3500726.17     10634011.10
      3500416.04     10633953.41
#Sta/Elev= 30
  4627.6  457.89  4665.3  457.85  4685.0  456.89  4690.0  457.69  4707.2  456.96
  4776.9  455.14  4810.0  455.23  4878.3  453.40  4949.4  452.64  4979.8  453.08
  4984.9  452.83  4987.0  450.17  4989.8  449.67  4993.0  450.17  5000.1  451.86
  5050.8  451.51  5104.9  451.93  5111.7  452.78  5121.9  453.08  5132.0  452.59
  5152.3  453.48  5210.2  452.87  5214.7  453.24  5218.9  453.85  5249.5  454.53
  5314.6  455.09  5371.5  455.36  5407.8  456.59  5465.7  456.37  5527.7  457.57
#Mann=6,-1,0
  4627.6    0.08       0  4707.2    0.05       0  4987.0    0.04       0
  4993.0    0.05       0  5214.7    0.08       0  5314.6    0.05       0
Bank Sta=4987,4993
Exp/Cntr=0.3,0.1

Type RM Length L Ch R = 1,11231,241,241,241
BEGIN DESCRIPTION:
Mapping XS 1b26815c
END DESCRIPTION:
XS GIS Cut Line= 3
      3500879.77     10634507.50      3500770.54     10633950.73
      3500376.94     10633867.46
#Sta/Elev= 30
  4640.2  458.93  4652.0  458.89  4688.4  457.57  4759.8  456.65  4824.4  453.98
  4851.5  454.89  4875.9  453.26  4912.6  453.65  4922.2  453.54  4927.3  452.46
  4973.7  452.67  4994.1  450.56  5001.3  448.16  5004.1  447.66  5007.3  448.16
  5014.5  449.00  5024.7  451.99  5030.2  452.24  5133.1  451.77  5147.0  452.60
  5167.4  452.02  5184.5  452.85  5189.6  452.22  5218.8  452.30  5252.6  453.57
  5352.8  455.52  5372.1  455.64  5378.2  454.69  5428.0  455.12  5609.9  458.26
#Mann=6,-1,0
  4640.2    0.08       0  4652.0    0.05       0  5001.3    0.04       0
  5007.3    0.05       0  5252.6    0.08       0  5352.8    0.05       0
Bank Sta=5001.3,5007.3
Exp/Cntr=0.3,0.1

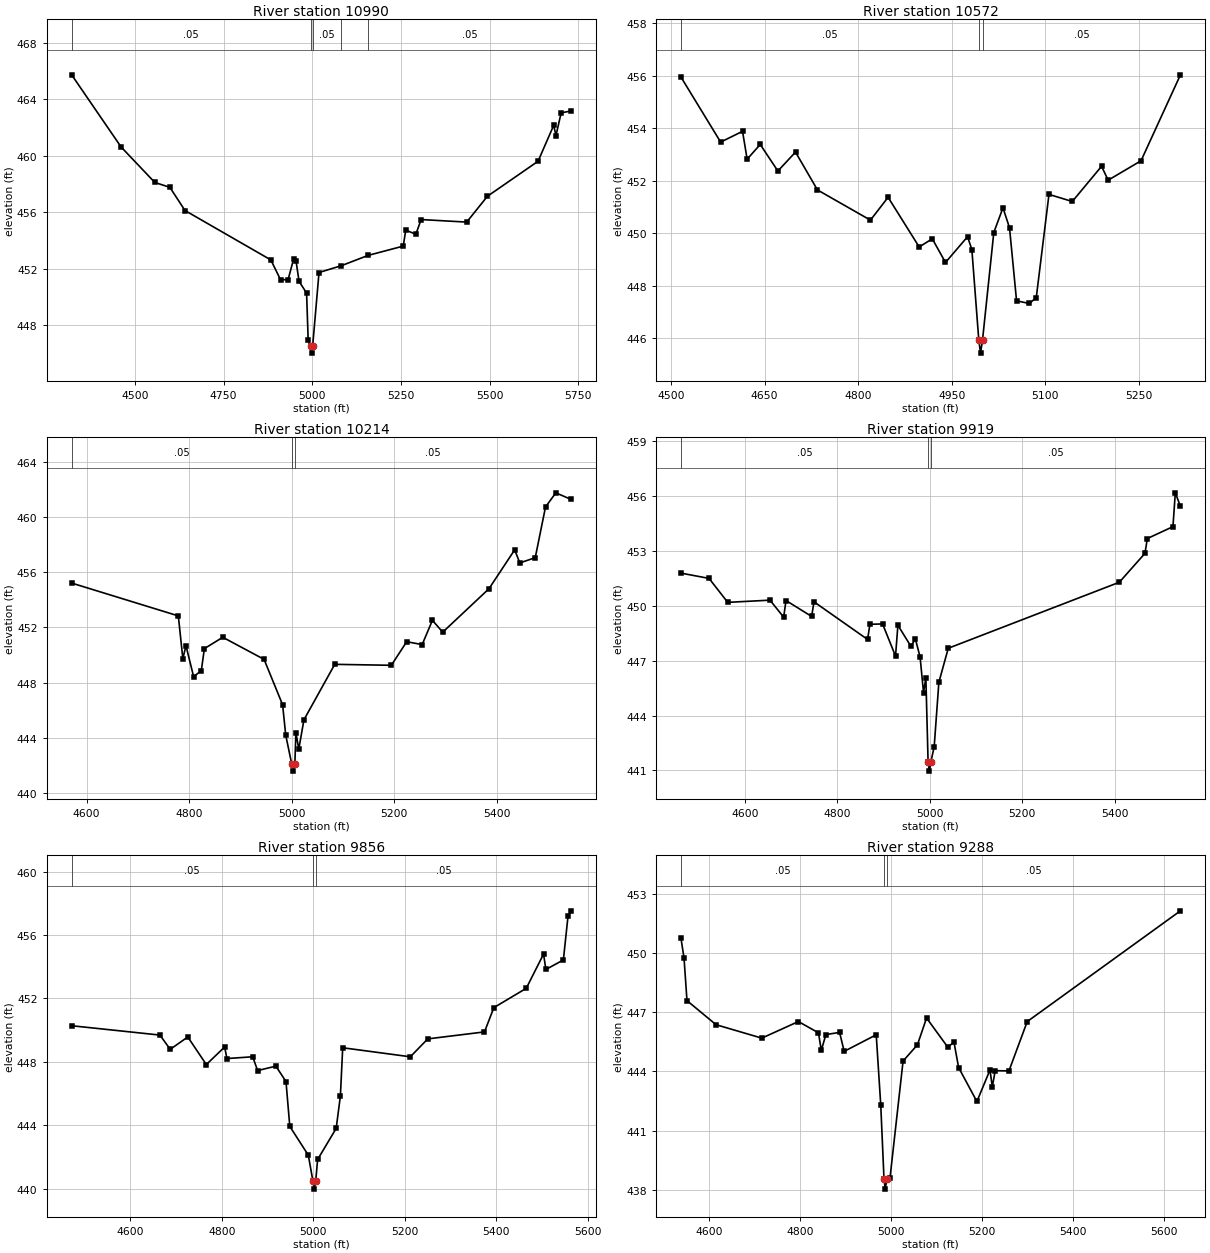
Type RM Length L Ch R = 1,10990,418,418,418
BEGIN DESCRIPTION:
UNT024 IN CCTC 21.0
END DESCRIPTION:
XS GIS Cut Line= 3
      3501249.63     10634510.22      3500900.49     10633937.70
      3500299.62     10633510.20
#Sta/Elev= 30
  4321.9  465.73  4461.3  460.62  4556.2  458.11  4598.8  457.76  4641.4  456.12
  4883.4  452.62  4910.6  451.22  4931.9  451.22  4947.4  452.67  4954.4  452.54
  4962.8  451.11  4984.1  450.27  4988.5  446.98  4995.2  446.52  4998.0  446.02
  5001.2  446.52  5019.1  451.73  5081.8  452.21  5157.3  452.94  5256.5  453.60
  5263.6  454.73  5292.1  454.44  5306.9  455.48  5435.4  455.30  5493.8  457.13
  5636.5  459.61  5680.7  462.16  5686.9  461.42  5701.6  463.04  5729.9  463.17
#Mann=5,-1,0
  4321.9    0.05       0  4995.2   0.035       0  5001.2    0.05       0
  5081.8    0.08       0  5157.3    0.05       0
Bank Sta=4995.2,5001.2
Exp/Cntr=0.3,0.1

Type RM Length L Ch R = 1,10572,358,358,358
BEGIN DESCRIPTION:
UNT024 IN CCTC 20.0
END DESCRIPTION:
XS GIS Cut Line= 3
      3501299.62     10633860.20      3500931.40     10633515.72
      3500649.65     10633610.17
#Sta/Elev= 30
  4515.6  455.95  4579.4  453.47  4614.5  453.88  4621.9  452.82  4642.9  453.38
  4671.2  452.37  4699.5  453.09  4734.7  451.65  4819.7  450.50  4848.0  451.37
  4897.9  449.48  4918.9  449.79  4940.1  448.89  4975.5  449.87  4982.4  449.38
  4993.5  445.94  4996.3  445.44  4999.5  445.94  5017.6  450.03  5032.3  450.97
  5042.8  450.21  5054.1  447.43  5074.5  447.33  5085.7  447.55  5106.1  451.48
  5143.5  451.21  5190.5  452.55  5201.0  452.02  5253.8  452.76  5317.0  456.03
#Mann=3,-1,0
  4515.6    0.05       0  4993.5   0.035       0  4999.5    0.05       0
Bank Sta=4993.5,4999.5
Exp/Cntr=0.3,0.1

Type RM Length L Ch R = 1,10214,295,295,295
BEGIN DESCRIPTION:
UNT024 IN CCTC 19.0
END DESCRIPTION:
XS GIS Cut Line= 3
      3501449.61     10633460.19      3501103.27     10633224.05
      3500549.62     10633260.19
#Sta/Elev= 30
  4570.8  455.21  4778.8  452.83  4787.6  449.73  4793.7  450.67  4808.6  448.43
  4823.6  448.86  4829.6  450.46  4865.5  451.28  4946.0  449.68  4982.1  446.39
  4988.2  444.19  5000.0  442.08  5002.8  441.58  5006.0  442.08  5008.0  444.37
  5013.7  443.18  5023.7  445.30  5083.8  449.32  5194.1  449.25  5224.1  450.96
  5254.2  450.75  5274.2  452.51  5294.3  451.65  5384.5  454.80  5434.6  457.62
  5444.6  456.67  5474.7  457.05  5494.7  460.72  5514.8  461.75  5544.8  461.27
#Mann=3,-1,0
  4570.8    0.05       0  5000.0    0.03       0  5006.0    0.05       0
Bank Sta=5000,5006
Exp/Cntr=0.3,0.1

Type RM Length L Ch R = 1,9919,63,63,63
BEGIN DESCRIPTION:
Mapping XS 7a72d82f
END DESCRIPTION:
XS GIS Cut Line= 2
      3501699.65     10632867.53      3500634.60     10633047.21
#Sta/Elev= 30
  4461.7  451.79  4522.6  451.50  4563.0  450.19  4654.4  450.31  4683.9  449.38
  4689.0  450.29  4744.4  449.42  4749.5  450.22  4865.4  448.16  4870.4  448.99
  4897.8  449.01  4925.8  447.25  4930.9  448.94  4958.7  447.80  4968.8  448.18
  4978.9  447.20  4986.3  445.26  4991.4  446.06  4996.2  441.46  4999.0  440.96
  5002.2  441.46  5009.4  442.30  5019.5  445.82  5039.8  447.68  5409.7  451.29
  5465.1  452.87  5470.2  453.68  5525.6  454.33  5530.7  456.18  5541.8  455.44
#Mann=3,-1,0
  4461.7    0.05       0  4996.2    0.03       0  5002.2    0.05       0
Bank Sta=4996.2,5002.2
Exp/Cntr=0.3,0.1

Type RM Length L Ch R = 1,9856,568,568,568
BEGIN DESCRIPTION:
UNT024 IN CCTC 18.0
END DESCRIPTION:
XS GIS Cut Line= 2
      3501680.12     10632811.54      3500602.70     10632984.39
#Sta/Elev= 30
  4472.2  450.28  4665.1  449.69  4687.5  448.79  4725.9  449.57  4766.4  447.83
  4806.4  448.94  4811.4  448.21  4867.7  448.32  4878.4  447.45  4918.3  447.73
  4940.4  446.76  4948.7  443.93  4989.2  442.11  4999.3  440.47  5002.1  439.97
  5005.3  440.47  5009.5  441.84  5050.0  443.80  5059.2  445.84  5064.3  448.89
  5212.0  448.32  5250.1  449.45  5374.0  449.89  5394.4  451.42  5465.2  452.64
  5503.0  454.80  5508.1  453.83  5546.3  454.43  5556.4  457.18  5563.4  457.53
#Mann=3,-1,0
  4472.2    0.05       0  4999.3    0.04       0  5005.3    0.05       0
Bank Sta=4999.3,5005.3
Exp/Cntr=0.3,0.1

Type RM Length L Ch R = 1,9288,533,533,533
BEGIN DESCRIPTION:
UNT024 IN CCTC 17.0
END DESCRIPTION:
XS GIS Cut Line= 2
      3501736.44     10632333.64      3500644.88     10632448.65
#Sta/Elev= 30
  4538.0  450.77  4544.9  449.74  4551.4  447.58  4615.3  446.36  4715.8  445.68
  4796.2  446.52  4840.3  445.95  4846.5  445.06  4856.6  445.86  4886.7  445.97
  4896.8  445.01  4967.2  445.85  4977.2  442.27  4984.3  438.53  4987.1  438.03
  4990.3  438.53  4997.4  438.58  5026.2  444.52  5057.7  445.34  5077.8  446.70
  5124.2  445.23  5138.1  445.47  5148.2  444.19  5188.4  442.47  5217.2  444.07
  5222.2  443.21  5228.6  444.03  5258.8  444.02  5299.0  446.52  5635.6  452.13
#Mann=3,-1,0
  4538.0    0.05       0  4984.3   0.035       0  4990.3    0.05       0
Bank Sta=4984.3,4990.3
Exp/Cntr=0.3,0.1

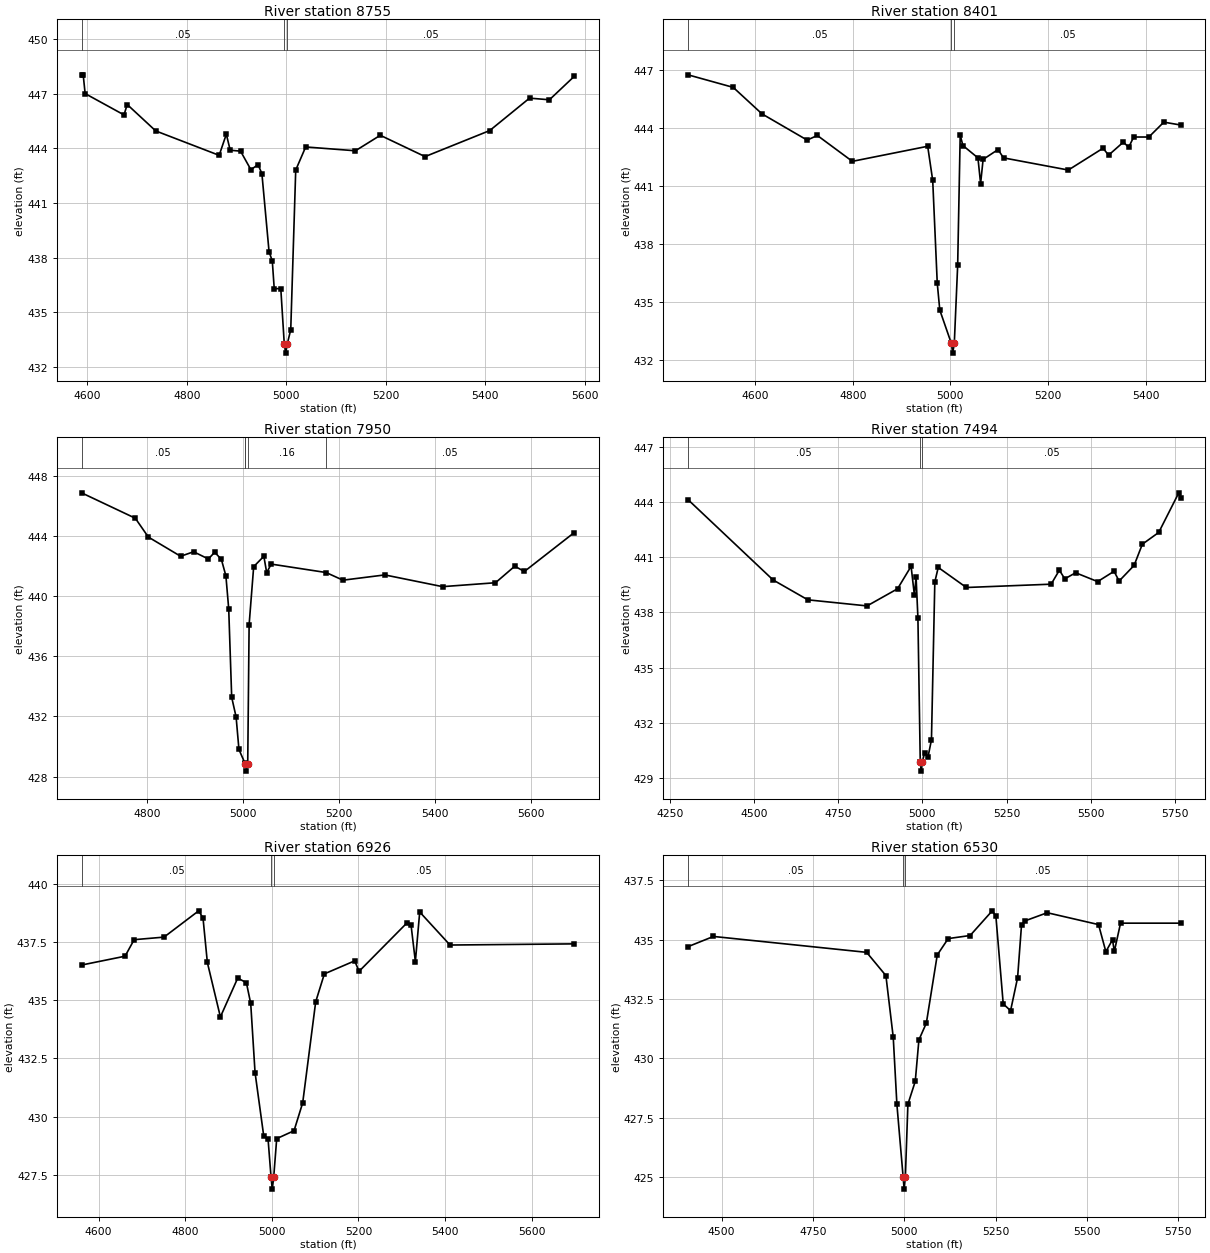
Type RM Length L Ch R = 1,8755,354,354,354
BEGIN DESCRIPTION:
UNT024 IN CCTC 16.0
END DESCRIPTION:
XS GIS Cut Line= 3
      3501749.63     10632260.20      3501449.61     10632010.19
      3500849.64     10632010.19
#Sta/Elev= 30
  4588.6  448.03  4591.9  448.03  4595.8  447.00  4673.9  445.83  4680.4  446.40
  4737.7  444.95  4865.2  443.61  4879.6  444.77  4887.4  443.89  4908.2  443.84
  4929.0  442.82  4943.3  443.10  4951.1  442.61  4965.5  438.32  4972.0  437.81
  4975.9  436.29  4989.1  436.29  4996.1  433.25  4998.9  432.75  5002.1  433.25
  5009.1  434.04  5019.1  442.80  5039.1  444.07  5139.1  443.86  5189.1  444.71
  5279.1  443.54  5409.1  444.97  5489.1  446.75  5529.1  446.66  5579.1  447.95
#Mann=3,-1,0
  4588.6    0.05       0  4996.1    0.03       0  5002.1    0.05       0
Bank Sta=4996.1,5002.1
Exp/Cntr=0.3,0.1

Type RM Length L Ch R = 1,8401,451,451,451
BEGIN DESCRIPTION:
UNT024 IN CCTC 15.0
END DESCRIPTION:
XS GIS Cut Line= 2
      3501926.72     10631866.47      3500945.84     10631628.63
#Sta/Elev= 30
  4462.7  446.77  4555.3  446.12  4614.1  444.75  4706.7  443.39  4727.6  443.63
  4799.3  442.29  4953.6  443.07  4963.9  441.30  4973.2  435.98  4978.4  434.59
  5002.1  432.86  5004.8  432.36  5008.1  432.86  5015.0  436.90  5020.2  443.65
  5025.7  443.11  5056.5  442.47  5062.0  441.14  5067.1  442.39  5097.7  442.90
  5108.9  442.47  5241.7  441.84  5312.8  442.97  5324.1  442.61  5354.6  443.29
  5365.2  443.01  5375.5  443.55  5406.6  443.55  5437.3  444.32  5472.0  444.17
#Mann=3,-1,0
  4462.7    0.05       0  5002.1   0.035       0  5008.1    0.05       0
Bank Sta=5002.1,5008.1
Exp/Cntr=0.3,0.1

Type RM Length L Ch R = 1,7950,456,456,456
BEGIN DESCRIPTION:
UNT024 IN CCTC 14.0
END DESCRIPTION:
XS GIS Cut Line= 3
      3501905.03     10631637.30      3501536.13     10631407.28
      3500945.86     10631450.68
#Sta/Elev= 30
  4664.0  446.87  4776.0  445.18  4803.1  443.93  4870.4  442.65  4897.5  442.95
  4928.2  442.47  4941.4  442.92  4955.3  442.44  4964.7  441.35  4970.6  439.15
  4976.8  433.27  4986.0  431.96  4991.9  429.80  5003.8  428.93  5004.2  428.86
  5007.0  428.36  5010.2  428.86  5013.1  438.10  5022.6  441.96  5043.8  442.65
  5049.7  441.56  5059.1  442.13  5173.4  441.57  5208.6  441.06  5295.8  441.41
  5416.1  440.63  5526.4  440.89  5566.5  441.99  5586.6  441.64  5690.6  444.23
#Mann=5,-1,0
  4664.0    0.05       0  5003.8    0.16       0  5004.2   0.035       0
  5010.2    0.16       0  5173.4    0.05       0
Bank Sta=5004.2,5010.2
Exp/Cntr=0.3,0.1

Type RM Length L Ch R = 1,7494,568,568,568
BEGIN DESCRIPTION:
UNT024 IN CCTC 13.0
END DESCRIPTION:
XS GIS Cut Line= 4
      3502017.91     10631528.83      3501792.21     10631073.08
      3501549.15     10631047.04      3500889.41     10631307.46
#Sta/Elev= 30
  4304.5  444.12  4556.9  439.76  4660.1  438.68  4835.8  438.35  4926.3  439.28
  4966.5  440.50  4976.3  438.93  4981.3  439.91  4986.7  437.72  4993.7  429.88
  4996.5  429.38  4999.7  429.88  5006.8  430.37  5016.8  430.16  5026.9  431.08
  5036.9  439.65  5047.0  440.44  5130.5  439.35  5382.1  439.53  5406.5  440.29
  5422.6  439.82  5454.8  440.15  5520.1  439.67  5568.8  440.23  5583.8  439.70
  5628.3  440.55  5652.7  441.70  5701.4  442.34  5760.9  444.49  5766.8  444.22
#Mann=3,-1,0
  4304.5    0.05       0  4993.7    0.03       0  4999.7    0.05       0
Bank Sta=4993.7,4999.7
Exp/Cntr=0.3,0.1

Type RM Length L Ch R = 1,6926,396,396,396
BEGIN DESCRIPTION:
UNT024 IN CCTC 12.0
END DESCRIPTION:
XS GIS Cut Line= 2
      3502369.97     10630668.05      3501232.81     10630640.32
#Sta/Elev= 30
  4560.7  436.51  4661.1  436.89  4682.1  437.60  4751.1  437.71  4831.1  438.84
  4841.1  438.53  4851.1  436.62  4881.2  434.28  4921.2  435.95  4941.2  435.75
  4951.2  434.86  4961.2  431.89  4981.2  429.17  4991.2  429.04  4998.2  427.38
  5000.9  426.88  5004.2  427.38  5011.2  429.05  5051.2  429.39  5071.2  430.59
  5101.2  434.93  5121.2  436.13  5191.2  436.69  5201.3  436.24  5311.3  438.31
  5321.3  438.23  5331.3  436.66  5341.3  438.79  5411.3  437.37  5698.2  437.42
#Mann=3,-1,0
  4560.7    0.05       0  4998.2    0.03       0  5004.2    0.05       0
Bank Sta=4998.2,5004.2
Exp/Cntr=0.3,0.1

Type RM Length L Ch R = 1,6530,437,437,437
BEGIN DESCRIPTION:
UNT024 IN CCTC 11.0
END DESCRIPTION:
XS GIS Cut Line= 3
      3502560.10     10630638.13      3502161.84     10630305.12
      3501335.26     10630240.97
#Sta/Elev= 30
  4408.3  434.71  4477.9  435.14  4897.0  434.47  4949.7  433.49  4969.8  430.89
  4979.8  428.06  4996.9  424.99  4999.6  424.49  5002.9  424.99  5009.9  428.07
  5030.0  429.03  5040.0  430.78  5060.4  431.49  5090.2  434.36  5120.2  435.05
  5180.2  435.18  5240.6  436.22  5250.6  436.00  5270.7  432.30  5290.8  432.01
  5310.0  433.40  5320.8  435.63  5330.9  435.80  5391.1  436.14  5531.5  435.64
  5551.5  434.50  5569.7  435.00  5574.7  434.51  5591.7  435.70  5756.5  435.70
#Mann=3,-1,0
  4408.3    0.05       0  4996.9    0.03       0  5002.9    0.05       0
Bank Sta=4996.9,5002.9
Exp/Cntr=0.3,0.1

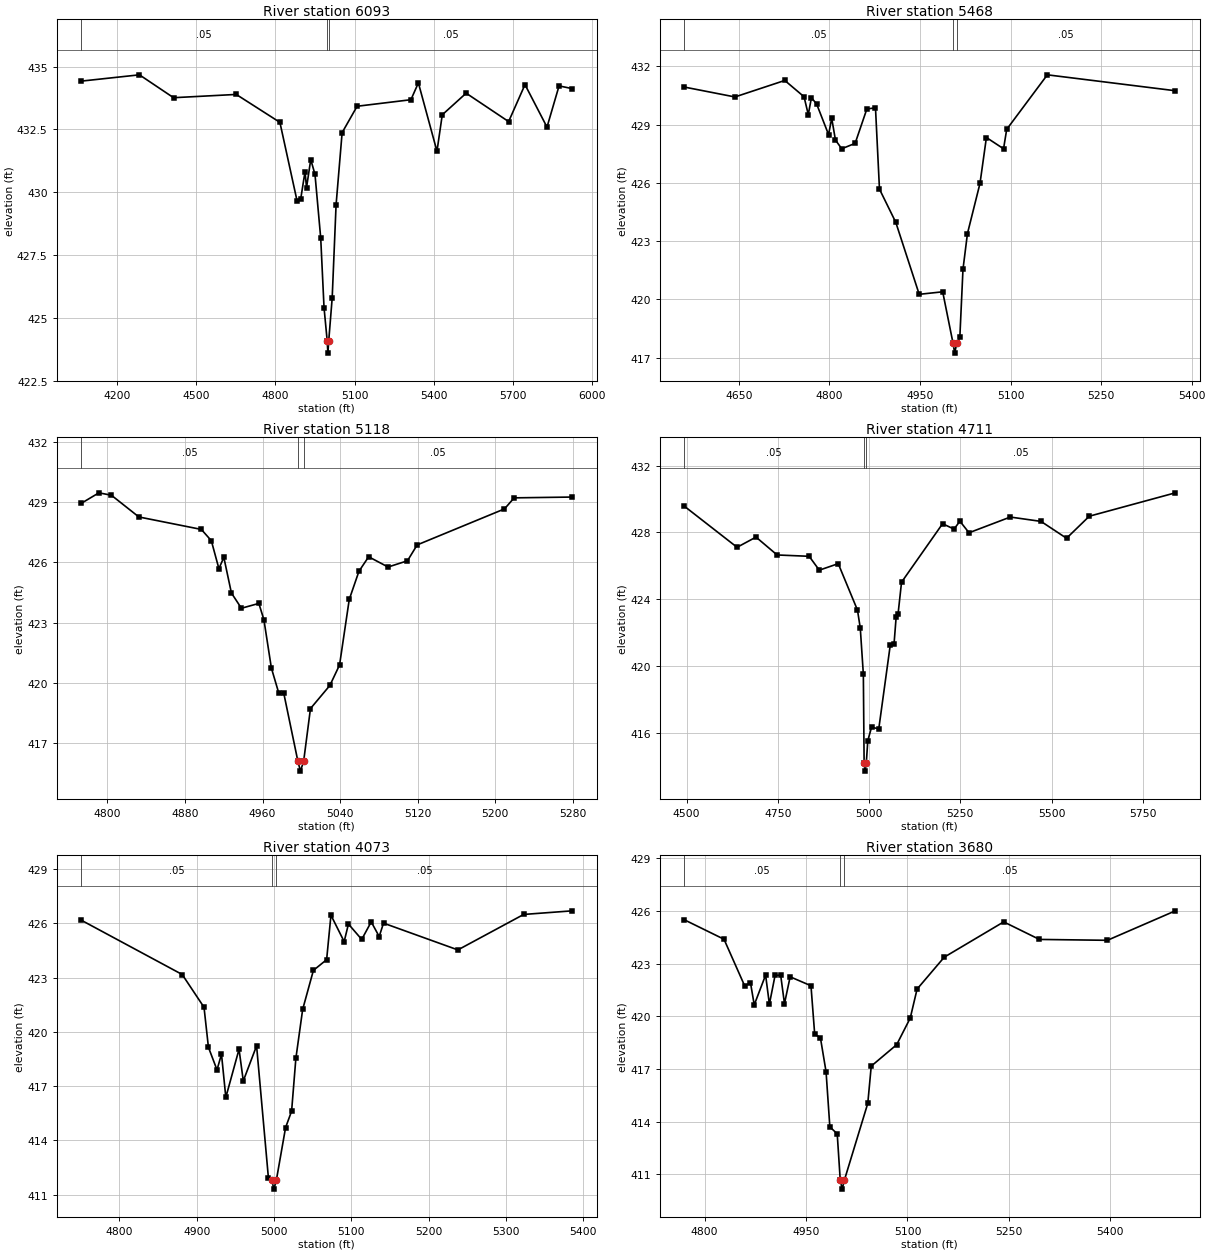
Type RM Length L Ch R = 1,6093,625,625,625
BEGIN DESCRIPTION:
UNT024 IN CCTC 10.0
END DESCRIPTION:
XS GIS Cut Line= 4
      3502648.64     10630625.10      3502196.06     10629939.23
      3501994.99     10629827.77      3501189.46     10629734.03
#Sta/Elev= 30
  4063.6  434.42  4284.0  434.67  4413.4  433.76  4651.2  433.89  4816.8  432.78
  4881.8  429.66  4896.0  429.75  4912.1  430.82  4917.8  430.18  4933.8  431.30
  4949.9  430.71  4971.6  428.18  4984.2  425.41  4996.1  424.10  4998.8  423.60
  5002.1  424.10  5015.1  425.79  5029.9  429.50  5052.8  432.37  5109.7  433.42
  5313.8  433.68  5342.1  434.35  5412.6  431.63  5432.7  433.08  5523.3  433.94
  5684.4  432.81  5746.5  434.28  5830.0  432.59  5875.7  434.23  5926.2  434.12
#Mann=3,-1,0
  4063.6    0.05       0  4996.1    0.03       0  5002.1    0.05       0
Bank Sta=4996.1,5002.1
Exp/Cntr=0.3,0.1

Type RM Length L Ch R = 1,5468,350,350,350
BEGIN DESCRIPTION:
UNT024 IN CCTC 9.0
END DESCRIPTION:
XS GIS Cut Line= 2
      3502760.07     10629562.66      3501978.82     10629336.96
#Sta/Elev= 30
  4559.8  430.94  4643.6  430.43  4726.2  431.28  4758.1  430.44  4765.1  429.52
  4770.3  430.39  4778.9  430.07  4798.7  428.49  4803.9  429.33  4810.1  428.21
  4820.5  427.76  4842.7  428.04  4862.1  429.81  4876.4  429.87  4883.0  425.68
  4910.0  423.97  4948.8  420.26  4987.7  420.39  5004.9  417.73  5007.6  417.23
  5010.9  417.73  5016.1  418.05  5021.3  421.55  5028.7  423.39  5049.5  425.98
  5060.1  428.34  5088.5  427.76  5093.7  428.76  5161.0  431.57  5373.0  430.75
#Mann=3,-1,0
  4559.8    0.05       0  5004.9    0.03       0  5010.9    0.05       0
Bank Sta=5004.9,5010.9
Exp/Cntr=0.3,0.1

Type RM Length L Ch R = 1,5118,407,407,407
BEGIN DESCRIPTION:
UNT024 IN CCTC 8.0
END DESCRIPTION:
XS GIS Cut Line= 3
      3502649.64     10629160.20      3502449.61     10629110.19
      3502149.60     10629110.19
#Sta/Elev= 30
  4773.2  428.93  4791.3  429.45  4804.2  429.33  4832.5  428.25  4896.9  427.63
  4907.2  427.07  4915.0  425.68  4920.1  426.24  4927.9  424.47  4938.2  423.71
  4956.2  423.95  4961.4  423.14  4969.1  420.74  4976.8  419.48  4981.9  419.48
  4996.4  416.11  4999.1  415.61  5002.4  416.11  5009.4  418.72  5029.4  419.87
  5039.4  420.89  5049.4  424.15  5059.4  425.55  5069.4  426.27  5089.4  425.76
  5109.4  426.07  5119.4  426.86  5209.4  428.65  5219.4  429.20  5279.4  429.24
#Mann=3,-1,0
  4773.2    0.05       0  4996.4    0.03       0  5002.4    0.05       0
Bank Sta=4996.4,5002.4
Exp/Cntr=0.3,0.1

Type RM Length L Ch R = 1,4711,638,638,638
BEGIN DESCRIPTION:
UNT024 IN CCTC 7.0
END DESCRIPTION:
XS GIS Cut Line= 3
      3502999.64     10629060.21      3502599.61     10628810.19
      3501749.56     10629010.20
#Sta/Elev= 30
  4494.0  429.57  4638.5  427.11  4690.4  427.72  4748.2  426.65  4836.0  426.57
  4863.7  425.74  4915.6  426.13  4968.3  423.35  4976.0  422.27  4984.4  419.51
  4986.5  414.21  4989.2  413.71  4992.5  414.21  4996.6  415.54  5006.8  416.33
  5026.7  416.25  5058.2  421.27  5068.5  421.34  5074.2  422.92  5079.4  423.10
  5089.0  425.02  5201.4  428.52  5232.8  428.20  5248.9  428.67  5273.9  427.98
  5386.9  428.92  5471.0  428.66  5541.0  427.65  5603.3  428.97  5839.0  430.37
#Mann=3,-1,0
  4494.0    0.05       0  4986.5    0.03       0  4992.5    0.05       0
Bank Sta=4986.5,4992.5
Exp/Cntr=0.3,0.1

Type RM Length L Ch R = 1,4073,393,393,393
BEGIN DESCRIPTION:
UNT024 IN CCTC 6.0
END DESCRIPTION:
XS GIS Cut Line= 2
      3503097.88     10628663.64      3502524.96     10628389.33
#Sta/Elev= 30
  4750.7  426.17  4881.2  423.17  4909.4  421.36  4915.1  419.15  4926.2  417.90
  4932.0  418.77  4937.6  416.38  4954.7  419.04  4960.2  417.29  4977.4  419.23
  4992.7  411.93  4997.0  411.81  4999.8  411.31  5003.0  411.81  5014.9  414.71
  5022.7  415.62  5028.2  418.53  5037.0  421.24  5050.9  423.40  5068.0  423.99
  5073.6  426.45  5090.7  424.99  5096.2  425.96  5113.4  425.11  5125.7  426.08
  5136.0  425.27  5141.6  426.01  5237.8  424.53  5322.9  426.49  5385.9  426.69
#Mann=3,-1,0
  4750.7    0.05       0  4997.0    0.03       0  5003.0    0.05       0
Bank Sta=4997,5003
Exp/Cntr=0.3,0.1

Type RM Length L Ch R = 1,3680,463,463,463
BEGIN DESCRIPTION:
UNT024 IN CCTC 5.0
END DESCRIPTION:
XS GIS Cut Line= 3
      3503149.60     10628410.18      3503049.61     10628210.19
      3502549.60     10628160.19
#Sta/Elev= 30
  4770.0  425.50  4828.7  424.39  4859.4  421.72  4867.8  421.92  4873.4  420.65
  4890.2  422.35  4895.8  420.69  4904.2  422.33  4912.5  422.34  4918.1  420.72
  4926.5  422.25  4957.3  421.74  4962.8  418.97  4971.2  418.79  4979.6  416.84
  4985.2  413.70  4996.1  413.30  5000.6  410.65  5003.4  410.15  5006.6  410.65
  5041.3  415.04  5046.4  417.16  5084.0  418.38  5104.1  419.90  5114.2  421.55
  5154.4  423.37  5242.3  425.38  5295.1  424.38  5395.6  424.33  5496.1  426.01
#Mann=3,-1,0
  4770.0    0.05       0  5000.6    0.03       0  5006.6    0.05       0
Bank Sta=5000.6,5006.6
Exp/Cntr=0.3,0.1

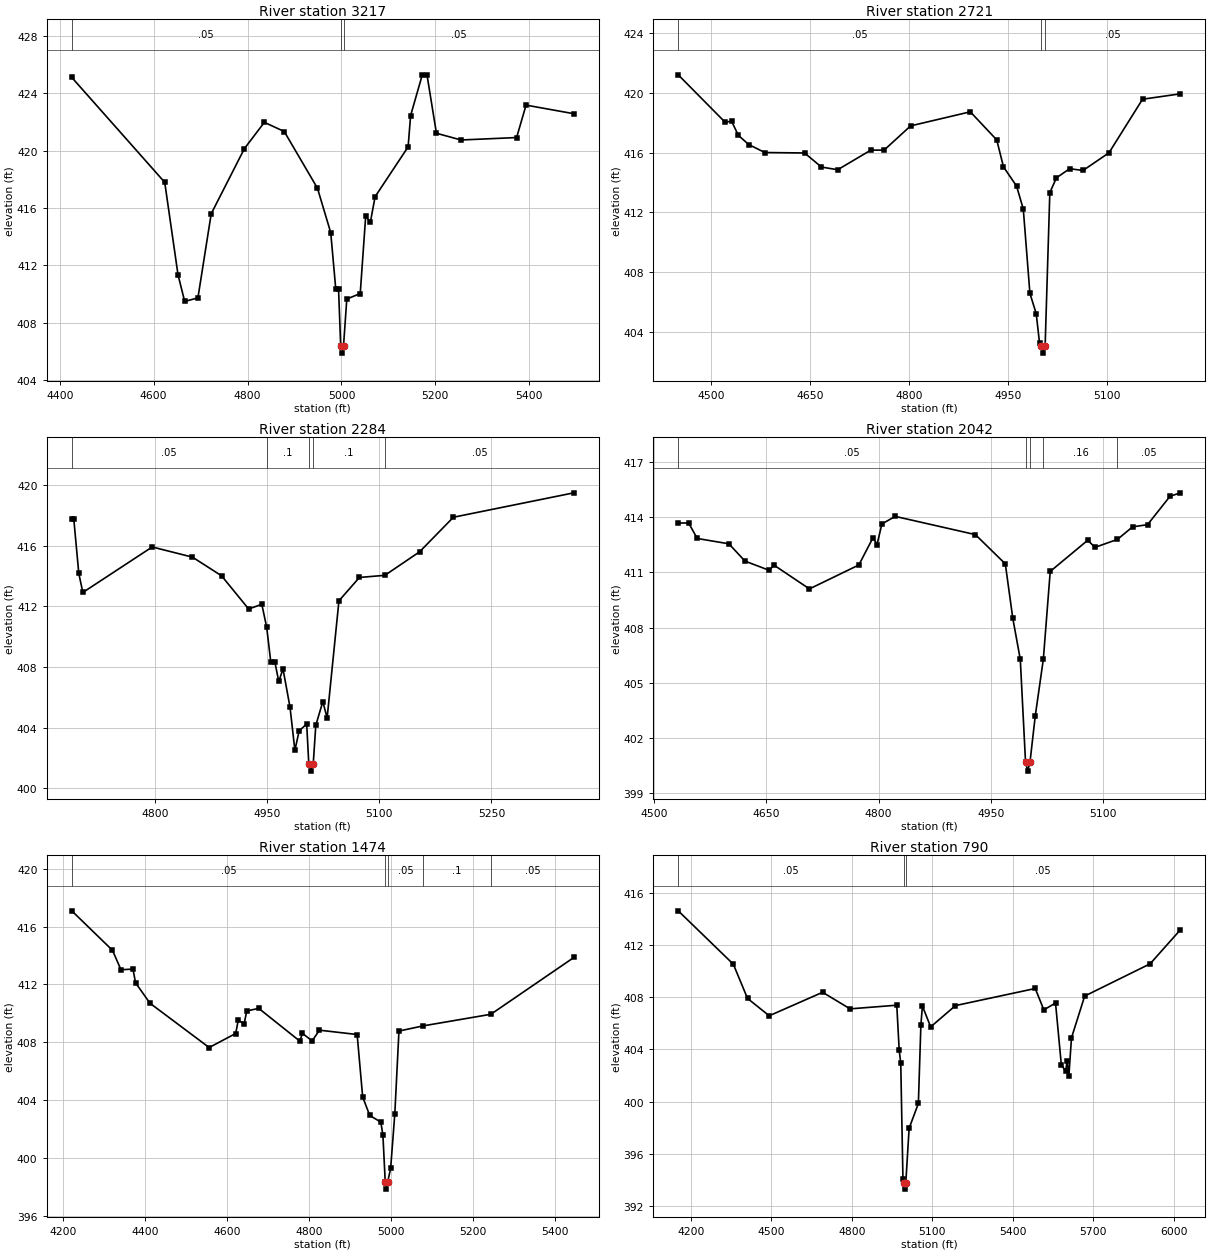
Type RM Length L Ch R = 1,3217,496,496,496
BEGIN DESCRIPTION:
UNT024 IN CCTC 4.0
END DESCRIPTION:
XS GIS Cut Line= 3
      3503649.64     10628210.22      3503249.61     10627810.19
      3502748.26     10627761.86
#Sta/Elev= 30
  4425.6  425.10  4623.6  417.79  4651.9  411.35  4666.1  409.49  4694.3  409.74
  4722.6  415.60  4793.3  420.14  4835.8  421.97  4878.2  421.33  4948.9  417.38
  4977.2  414.28  4987.8  410.39  4993.8  410.39  4998.4  406.39  5001.1  405.89
  5004.4  406.39  5011.4  409.66  5040.0  410.04  5051.6  415.42  5061.7  415.03
  5071.7  416.79  5142.0  420.26  5147.3  422.44  5172.2  425.28  5182.2  425.28
  5202.3  421.21  5254.7  420.74  5373.1  420.91  5393.2  423.17  5495.0  422.57
#Mann=3,-1,0
  4425.6    0.05       0  4998.4   0.035       0  5004.4    0.05       0
Bank Sta=4998.4,5004.4
Exp/Cntr=0.3,0.1

Type RM Length L Ch R = 1,2721,437,437,437
BEGIN DESCRIPTION:
UNT024 IN CCTC 3.0
END DESCRIPTION:
XS GIS Cut Line= 2
      3503990.22     10627554.99      3503232.68     10627485.73
#Sta/Elev= 30
  4449.8  421.19  4520.7  418.03  4530.7  418.09  4540.8  417.15  4556.7  416.53
  4581.0  416.00  4641.2  415.97  4666.8  415.03  4691.4  414.85  4741.6  416.16
  4761.7  416.16  4801.9  417.78  4892.3  418.72  4932.4  416.84  4942.5  415.05
  4962.5  413.75  4972.6  412.22  4982.6  406.60  4992.2  405.23  4997.2  403.28
  4999.7  403.10  5002.5  402.60  5005.7  403.10  5012.8  413.32  5022.8  414.31
  5042.9  414.92  5063.0  414.80  5102.4  415.98  5153.3  419.56  5210.5  419.92
#Mann=3,-1,0
  4449.8    0.05       0  4999.7   0.035       0  5005.7    0.05       0
Bank Sta=4999.7,5005.7
Exp/Cntr=0.3,0.1

Type RM Length L Ch R = 1,2284,242,242,242
BEGIN DESCRIPTION:
UNT024 IN CCTC 2.0
END DESCRIPTION:
XS GIS Cut Line= 3
      3503749.61     10627210.19      3503499.61     10627110.19
      3503149.59     10627310.20
#Sta/Elev= 30
  4688.0  417.77  4690.7  417.77  4697.4  414.18  4702.8  412.92  4795.7  415.92
  4849.6  415.25  4888.6  414.02  4924.9  411.83  4942.5  412.14  4949.0  410.64
  4954.6  408.31  4960.1  408.31  4965.2  407.05  4970.9  407.88  4980.3  405.35
  4986.8  402.51  4992.5  403.79  5002.6  404.25  5005.4  401.64  5008.1  401.14
  5011.4  401.64  5014.8  404.16  5024.2  405.72  5030.0  404.65  5045.8  412.37
  5073.2  413.91  5107.3  414.05  5153.8  415.60  5199.1  417.88  5360.4  419.49
#Mann=5,-1,0
  4688.0    0.05       0  4949.0     0.1       0  5005.4    0.07       0
  5011.4     0.1       0  5107.3    0.05       0
Bank Sta=5005.4,5011.4
Exp/Cntr=0.3,0.1

Type RM Length L Ch R = 1,2042,568,568,568
BEGIN DESCRIPTION:
Mapping XS 6d6fea56
END DESCRIPTION:
XS GIS Cut Line= 3
      3503942.51     10627042.84      3503625.68     10626916.98
      3503295.83     10626921.32
#Sta/Elev= 30
  4532.4  413.68  4546.3  413.68  4557.8  412.84  4600.1  412.55  4621.6  411.61
  4653.9  411.11  4660.4  411.39  4707.7  410.10  4773.7  411.40  4792.6  412.88
  4798.0  412.51  4804.5  413.63  4822.3  414.04  4929.4  413.05  4969.4  411.46
  4979.4  408.50  4989.4  406.27  4996.4  400.70  4999.2  400.20  5002.4  400.70
  5009.4  403.20  5020.2  406.28  5029.4  411.05  5079.4  412.74  5089.4  412.36
  5119.2  412.79  5139.4  413.47  5159.4  413.59  5189.4  415.13  5203.2  415.32
#Mann=5,-1,0
  4532.4    0.05       0  4996.4   0.035       0  5002.4    0.05       0
  5020.2    0.16       0  5119.2    0.05       0
Bank Sta=4996.4,5002.4
Exp/Cntr=0.3,0.1

Type RM Length L Ch R = 1,1474,684,684,684
BEGIN DESCRIPTION:
Mapping XS 3f2b4201
END DESCRIPTION:
XS GIS Cut Line= 4
      3504094.45     10627003.80      3503747.21     10626530.69
      3503504.16     10626478.61      3503269.76     10626791.14
#Sta/Elev= 30
  4220.7  417.09  4320.0  414.36  4340.9  413.01  4370.2  413.06  4376.4  412.11
  4411.9  410.69  4556.2  407.63  4621.0  408.60  4627.2  409.51  4641.8  409.29
  4648.0  410.16  4677.3  410.34  4777.7  408.07  4783.9  408.61  4807.6  408.09
  4825.6  408.83  4917.6  408.53  4931.1  404.21  4948.3  402.93  4975.4  402.47
  4980.5  401.58  4986.2  398.33  4988.9  397.83  4992.2  398.33  4999.4  399.26
  5009.6  403.05  5019.7  408.77  5079.2  409.13  5244.1  409.93  5446.8  413.86
#Mann=5,-1,0
  4220.7    0.05       0  4986.2   0.035       0  4992.2    0.05       0
  5079.2     0.1       0  5244.1    0.05       0
Bank Sta=4986.2,4992.2
Exp/Cntr=0.3,0.1

Type RM Length L Ch R = 1,790,0,0,0
BEGIN DESCRIPTION:
UNT024 IN CCTC 1.0
END DESCRIPTION:
XS GIS Cut Line= 4
      3504172.58     10626838.89      3503695.13     10625996.84
      3503525.86     10626001.18      3503169.95     10626643.55
#Sta/Elev= 30
  4152.7  414.62  4358.1  410.53  4411.0  407.91  4491.8  406.58  4690.9  408.38
  4793.3  407.11  4967.4  407.39  4976.5  403.92  4982.2  402.97  4990.4  394.10
  4995.1  393.80  4997.9  393.30  5001.1  393.80  5013.4  397.96  5047.9  399.86
  5057.3  405.90  5063.0  407.32  5093.8  405.73  5186.2  407.36  5483.6  408.67
  5515.7  407.03  5559.2  407.56  5580.9  402.81  5597.0  402.35  5602.7  403.13
  5609.0  402.00  5618.7  404.89  5667.9  408.09  5911.8  410.56  6024.4  413.16
#Mann=3,-1,0
  4152.7    0.05       0  4995.1   0.035       0  5001.1    0.05       0
Bank Sta=4995.1,5001.1
Exp/Cntr=0.3,0.1

Chan Stop Cuts=-1