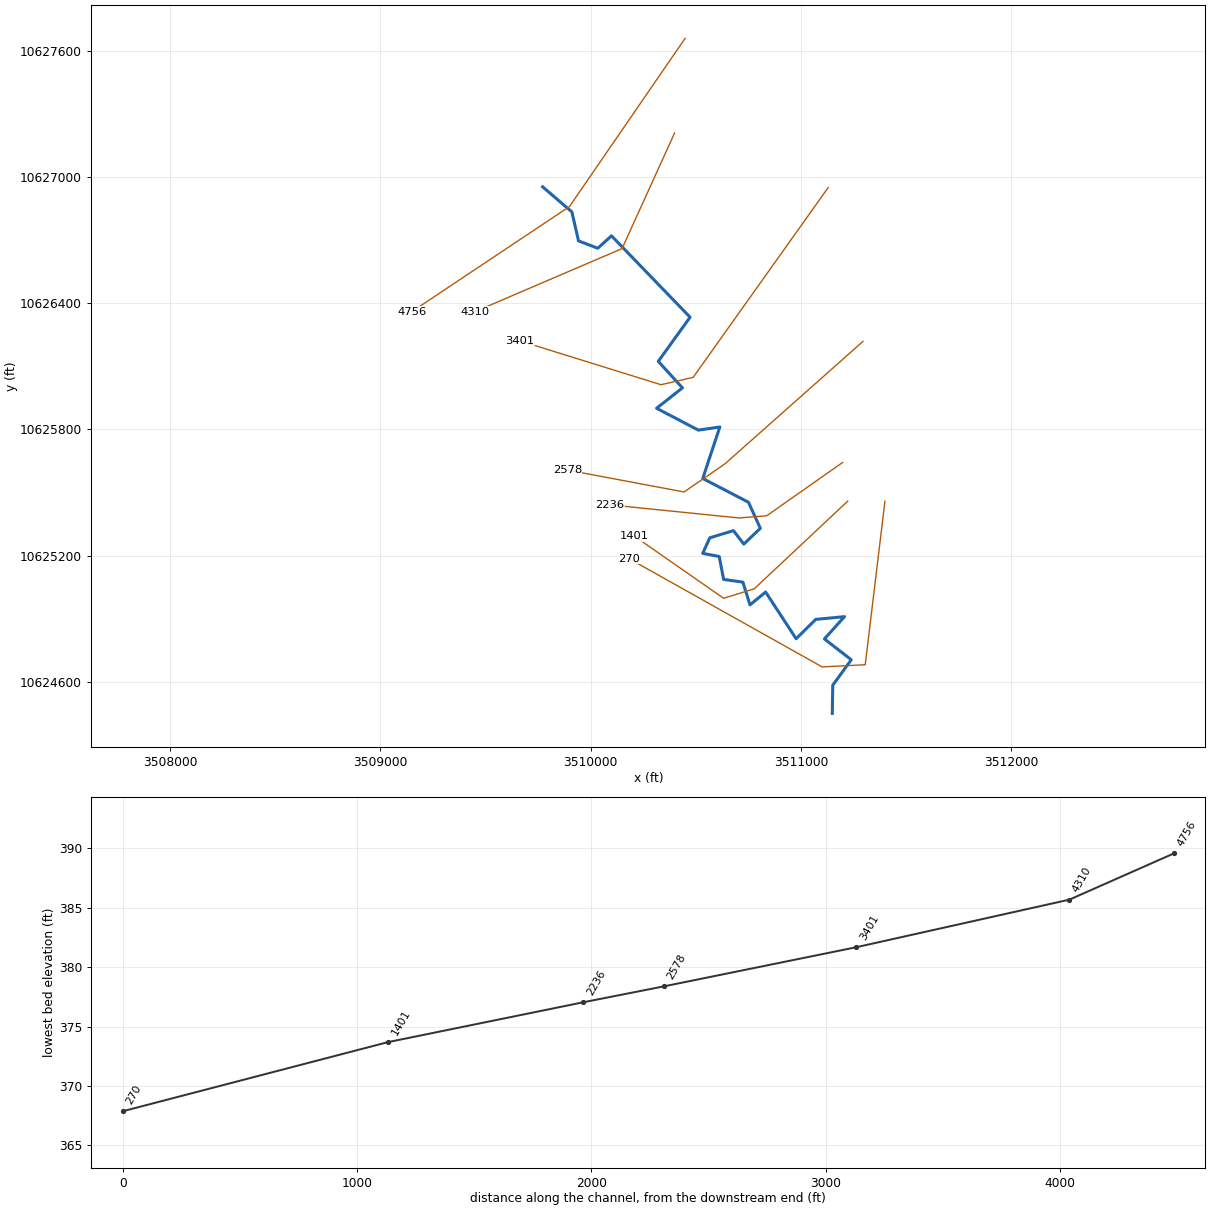
--- UNT025 IN CCTC.prj (project) ---

Proj Title=UNT025 IN CCTC Base Level Engineering
Current Plan=p01
Default Exp/Contr=0.3,0.1
English Units
Geom File=g01
Flow File=f01
Plan File=p01
BEGIN DESCRIPTION:
UNT025 IN CCTC
END DESCRIPTION:

--- UNT025 IN CCTC.p01 (plan) ---

Plan Title=Multiple Run
Short Identifier=Multiple
Geom File=g01
Flow File=f01
Subcritical Flow
K Sum by GR= 0
Std Step Tol= 0.01
Critical Tol= 0.01
Num of Std Step Trials= 20
Max Error Tol= 0.3
Flow Tol Ratio= 0.001
Split Flow NTrial= 30
Split Flow Tol= 0.02
Split Flow Ratio= 0.02
Log Output Level= 0
Friction Slope Method= 1
Unsteady Friction Slope Method= 2
Unsteady Bridges Friction Slope Method= 1
Parabolic Critical Depth
Global Vel Dist=  1 , 1 , 1
Global Log Level= 0
CheckData=True
Encroach Param= -1, 0, 0, 0
BEGIN DESCRIPTION:
Multiple Run
END DESCRIPTION:

--- UNT025 IN CCTC.f01 (steady flow) ---

Flow Title=Multiple
Number of Profiles=7
Profile Names=10-year,25-year,50-year,1pct_min,100-year,1pct_plu,500-year
River Rch & RM= UNT025 IN CCTC,Reach-1,4756
    1340    1835    2242    1997    2701    3653    3909
Boundary for River Rch & Prof#=UNT025 IN CCTC,Reach-1,1
Up Type=0
Dn Type=3
Dn Slope=0.005
Boundary for River Rch & Prof#=UNT025 IN CCTC,Reach-1,2
Up Type=0
Dn Type=3
Dn Slope=0.005
Boundary for River Rch & Prof#=UNT025 IN CCTC,Reach-1,3
Up Type=0
Dn Type=3
Dn Slope=0.005
Boundary for River Rch & Prof#=UNT025 IN CCTC,Reach-1,4
Up Type=0
Dn Type=3
Dn Slope=0.005
Boundary for River Rch & Prof#=UNT025 IN CCTC,Reach-1,5
Up Type=0
Dn Type=3
Dn Slope=0.005
Boundary for River Rch & Prof#=UNT025 IN CCTC,Reach-1,6
Up Type=0
Dn Type=3
Dn Slope=0.005
Boundary for River Rch & Prof#=UNT025 IN CCTC,Reach-1,7
Up Type=0
Dn Type=3
Dn Slope=0.005

--- UNT025 IN CCTC.g01 (geometry) ---

Geom Title=Existing Conditions

River Reach=UNT025 IN CCTC,Reach-1
Reach XY= 30
      3509772.25     10626954.00      3509911.00     10626835.00
      3509942.75     10626697.00      3510034.25     10626662.00
      3510099.50     10626721.00      3510473.25     10626334.00
      3510322.00     10626124.00      3510437.00     10625998.00
      3510314.00     10625901.00      3510512.75     10625797.00
      3510614.75     10625812.00      3510533.50     10625567.00
      3510751.00     10625454.00      3510807.25     10625330.00
      3510728.75     10625255.00      3510679.50     10625319.00
      3510567.25     10625285.00      3510533.25     10625211.00
      3510611.75     10625196.00      3510632.75     10625087.00
      3510724.50     10625074.00      3510758.00     10624966.00
      3510832.50     10625027.00      3510977.50     10624805.00
      3511071.00     10624897.00      3511207.75     10624910.00
      3511112.00     10624804.00      3511239.75     10624705.00
      3511151.75     10624584.00      3511149.50     10624450.00

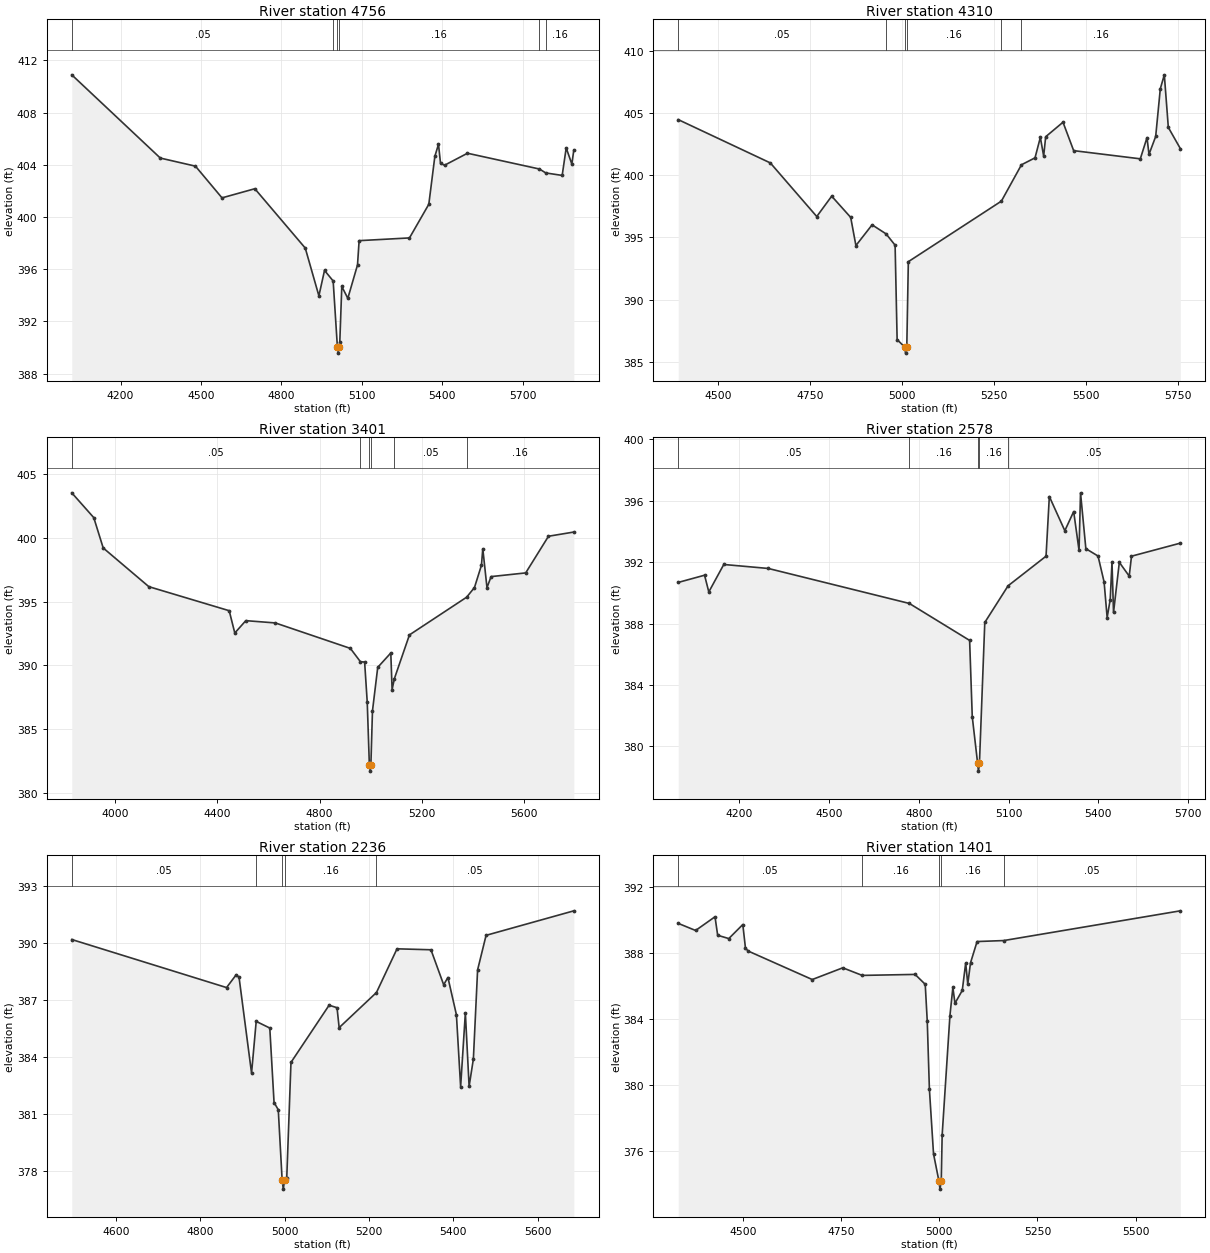
Type RM Length L Ch R = 1,4756,446,446,446
BEGIN DESCRIPTION:
UNT025 IN CCTC 7.0
END DESCRIPTION:
XS GIS Cut Line= 3
      3510449.63     10627660.22      3509899.61     10626860.19
      3509149.65     10626360.21
#Sta/Elev= 30
  4018.0  410.90  4348.2  404.52  4479.2  403.90  4578.2  401.47  4700.6  402.17
  4888.7  397.62  4939.5  393.96  4960.5  395.91  4992.7  395.10  5008.4  390.07
  5011.1  389.57  5014.4  390.07  5017.4  390.39  5024.9  394.68  5047.4  393.77
  5083.5  396.33  5089.5  398.19  5277.3  398.40  5349.4  400.98  5371.9  404.65
  5385.5  405.58  5393.0  404.12  5408.0  403.97  5493.6  404.89  5762.1  403.68
  5785.5  403.38  5846.7  403.19  5861.7  405.30  5882.7  404.06  5890.2  405.15
#Mann=6,-1,0
  4018.0    0.05       0  4992.7    0.16       0  5008.4    0.07       0
  5014.4    0.16       0  5762.1     0.1       0  5785.5    0.16       0
Bank Sta=5008.4,5014.4
Exp/Cntr=0.3,0.1

Type RM Length L Ch R = 1,4310,909,909,909
BEGIN DESCRIPTION:
UNT025 IN CCTC 6.0
END DESCRIPTION:
XS GIS Cut Line= 3
      3510399.62     10627210.20      3510149.61     10626660.19
      3509449.65     10626360.21
#Sta/Elev= 30
  4391.0  404.50  4641.5  401.01  4767.8  396.69  4808.4  398.33  4860.1  396.62
  4874.3  394.35  4918.3  396.02  4956.4  395.29  4980.9  394.38  4986.4  386.77
  5006.7  386.18  5009.4  385.68  5012.7  386.18  5016.9  393.05  5270.0  397.93
  5324.6  400.86  5361.5  401.42  5376.0  403.07  5385.0  401.56  5390.5  403.12
  5437.6  404.29  5466.6  402.00  5647.9  401.34  5666.1  403.05  5671.5  401.70
  5689.7  403.14  5702.3  406.99  5713.2  408.11  5724.1  403.87  5756.7  402.17
#Mann=6,-1,0
  4391.0    0.05       0  4956.4    0.16       0  5006.7    0.07       0
  5012.7    0.16       0  5270.0    0.05       0  5324.6    0.16       0
Bank Sta=5006.7,5012.7
Exp/Cntr=0.3,0.1

Type RM Length L Ch R = 1,3401,823,823,823
BEGIN DESCRIPTION:
UNT025 IN CCTC 4.0
END DESCRIPTION:
XS GIS Cut Line= 4
      3511129.99     10626950.45      3510487.63     10626047.68
      3510334.86     10626012.95      3509664.75     10626221.28
#Sta/Elev= 30
  3829.6  403.54  3915.8  401.59  3952.7  399.21  4131.4  396.17  4446.2  394.28
  4468.1  392.53  4511.3  393.50  4626.9  393.32  4920.8  391.32  4960.3  390.27
  4976.6  390.25  4986.8  387.10  4995.1  382.18  4997.8  381.68  5001.1  382.18
  5007.3  386.41  5027.9  389.83  5079.1  390.96  5084.2  388.09  5093.2  388.95
  5152.1  392.38  5376.0  395.34  5406.8  396.10  5434.1  397.85  5439.4  399.15
  5455.8  396.09  5471.9  396.96  5607.4  397.25  5696.7  400.13  5796.0  400.46
#Mann=6,-1,0
  3829.6    0.05       0  4960.3    0.16       0  4995.1    0.07       0
  5001.1    0.16       0  5093.2    0.05       0  5376.0    0.16       0
Bank Sta=4995.1,5001.1
Exp/Cntr=0.3,0.1

Type RM Length L Ch R = 1,2578,342,342,342
BEGIN DESCRIPTION:
Mapping XS eaf58de7
END DESCRIPTION:
XS GIS Cut Line= 4
      3511295.44     10626219.07      3510640.09     10625637.50
      3510444.78     10625502.95      3509889.22     10625607.12
#Sta/Elev= 30
  3995.8  390.68  4083.8  391.15  4098.0  390.06  4148.1  391.85  4297.0  391.59
  4768.4  389.31  4970.0  386.90  4978.8  381.93  4996.8  378.88  4999.5  378.38
  5002.8  378.88  5020.7  388.07  5098.6  390.46  5225.5  392.39  5236.5  396.28
  5288.3  394.05  5317.9  395.30  5335.8  392.77  5340.8  396.52  5358.6  392.88
  5399.3  392.40  5419.6  390.71  5429.8  388.39  5440.0  389.56  5446.0  391.99
  5451.1  388.72  5470.5  391.99  5503.6  391.09  5511.2  392.39  5674.4  393.24
#Mann=5,-1,0
  3995.8    0.05       0  4768.4    0.16       0  4996.8    0.07       0
  5002.8    0.16       0  5098.6    0.05       0
Bank Sta=4996.8,5002.8
Exp/Cntr=0.3,0.1

Type RM Length L Ch R = 1,2236,835,835,835
BEGIN DESCRIPTION:
UNT025 IN CCTC 3.0
END DESCRIPTION:
XS GIS Cut Line= 4
      3511198.57     10625643.16      3510837.46     10625389.69
      3510705.52     10625379.27      3510092.82     10625441.58
#Sta/Elev= 30
  4495.9  390.19  4862.6  387.66  4885.6  388.34  4892.2  388.20  4921.8  383.16
  4932.8  385.88  4965.0  385.53  4975.1  381.61  4985.1  381.23  4994.2  377.55
  4997.0  377.05  5000.2  377.55  5005.2  377.65  5015.2  383.72  5105.5  386.73
  5124.3  386.60  5129.3  385.55  5217.7  387.40  5266.4  389.70  5346.8  389.65
  5376.9  387.81  5387.0  388.19  5407.1  386.23  5417.1  382.44  5428.3  386.33
  5437.2  382.46  5447.3  383.90  5457.3  388.59  5477.4  390.41  5685.3  391.70
#Mann=5,-1,0
  4495.9    0.05       0  4932.8    0.16       0  4994.2    0.07       0
  5000.2    0.16       0  5217.7    0.05       0
Bank Sta=4994.2,5000.2
Exp/Cntr=0.3,0.1

Type RM Length L Ch R = 1,1401,1131,1131,1131
BEGIN DESCRIPTION:
UNT025 IN CCTC 2.0
END DESCRIPTION:
XS GIS Cut Line= 4
      3511222.89     10625459.14      3510778.43     10625042.47
      3510632.60     10624997.33      3510208.97     10625292.48
#Sta/Elev= 30
  4335.5  389.78  4379.7  389.35  4429.1  390.18  4435.9  389.06  4464.2  388.86
  4499.9  389.71  4506.7  388.27  4514.0  388.10  4676.7  386.38  4754.4  387.09
  4803.9  386.63  4938.5  386.69  4964.3  386.09  4969.5  383.84  4974.9  379.75
  4985.4  375.83  4999.1  374.19  5001.9  373.69  5005.1  374.19  5007.4  376.97
  5027.2  384.20  5034.7  385.90  5040.0  384.94  5058.6  385.72  5067.3  387.38
  5072.6  386.11  5079.6  387.39  5096.3  388.68  5164.2  388.74  5613.7  390.54
#Mann=5,-1,0
  4335.5    0.05       0  4803.9    0.16       0  4999.1    0.07       0
  5005.1    0.16       0  5164.2    0.05       0
Bank Sta=4999.1,5005.1
Exp/Cntr=0.3,0.1

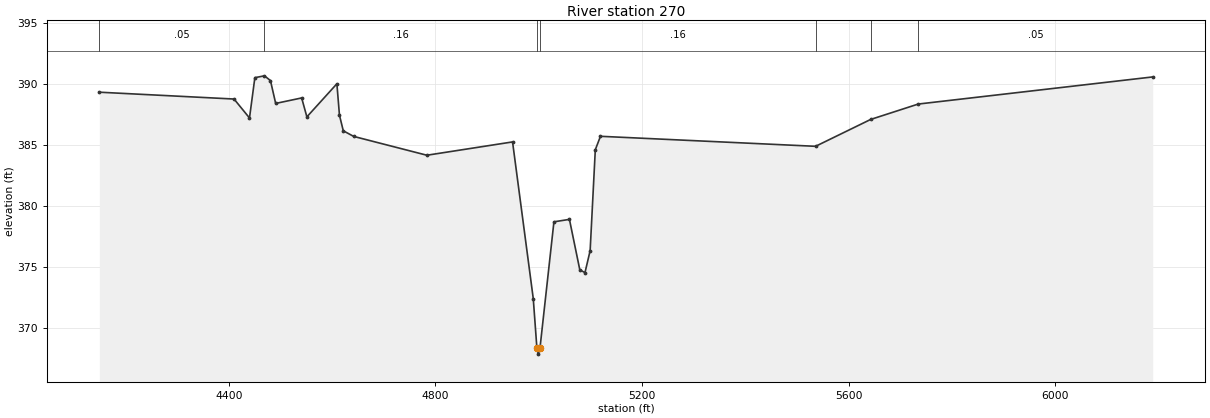
Type RM Length L Ch R = 1,270,0,0,0
BEGIN DESCRIPTION:
UNT025 IN CCTC 1.0
END DESCRIPTION:
XS GIS Cut Line= 4
      3511399.96     10625459.11      3511306.21     10624681.36
      3511101.35     10624670.94      3510184.68     10625184.83
#Sta/Elev= 30
  4149.2  389.32  4410.0  388.76  4439.9  387.21  4450.3  390.51  4468.9  390.66
  4480.5  390.27  4490.6  388.40  4540.9  388.85  4551.0  387.30  4609.1  390.01
  4614.1  387.43  4621.5  386.16  4641.7  385.70  4783.3  384.16  4949.2  385.25
  4989.3  372.42  4996.3  368.38  4999.0  367.88  5002.3  368.38  5029.3  378.71
  5059.3  378.91  5079.4  374.78  5089.4  374.55  5099.4  376.35  5109.4  384.61
  5119.4  385.71  5535.8  384.89  5642.5  387.09  5734.6  388.35  6188.6  390.57
#Mann=7,-1,0
  4149.2    0.05       0  4468.9    0.16       0  4996.3    0.07       0
  5002.3    0.16       0  5535.8    0.05       0  5642.5    0.16       0
  5734.6    0.05       0
Bank Sta=4996.3,5002.3
Exp/Cntr=0.3,0.1

Chan Stop Cuts=-1