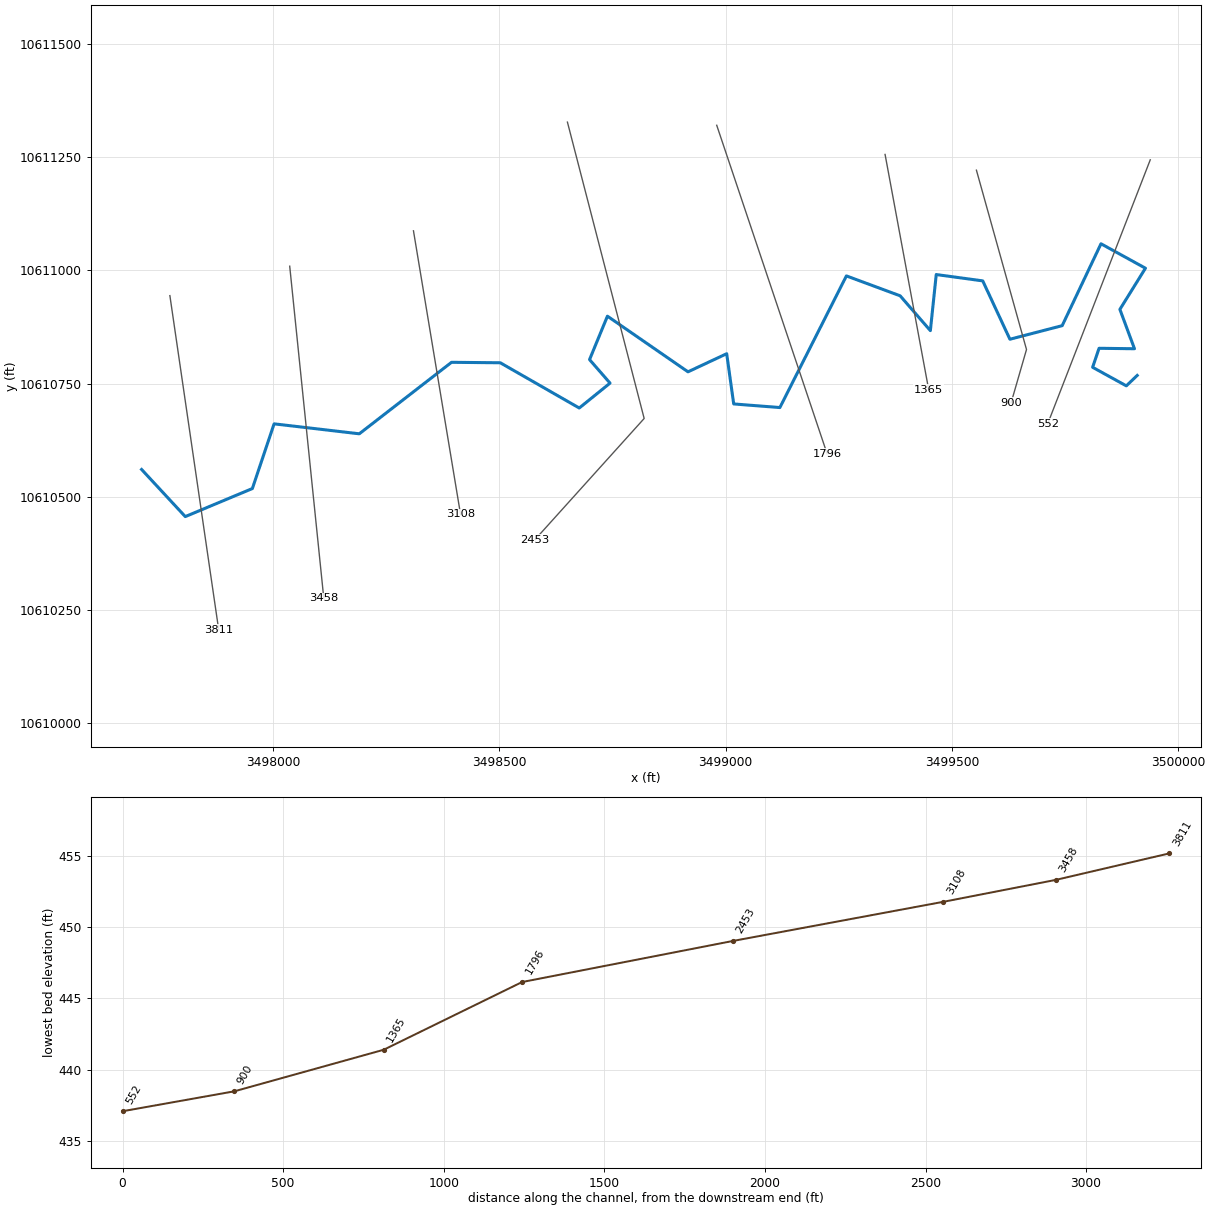
--- UNT028 IN CCTC.prj (project) ---

Proj Title=UNT028 IN CCTC Base Level Engineering
Current Plan=p01
Default Exp/Contr=0.3,0.1
English Units
Geom File=g01
Flow File=f01
Plan File=p01
Y Axis Title=Elevation
X Axis Title(PF)=Main Channel Distance
X Axis Title(XS)=Station
BEGIN DESCRIPTION:
UNT028 IN CCTC
END DESCRIPTION:
DSS Export Rating Curves= 0
DSS Export Rating Curve Sorted= 0
DSS Export Volume Flow Curves= 0
DXF OffsetX= 0
DXF OffsetY= 0
DXF ScaleX= 1
DXF ScaleY= 10

--- UNT028 IN CCTC.p01 (plan) ---

Plan Title=Multiple Run
Short Identifier=Multiple
Geom File=g01
Flow File=f01
Subcritical Flow
K Sum by GR= 0
Std Step Tol= 0.01
Critical Tol= 0.01
Num of Std Step Trials= 20
Max Error Tol= 0.3
Flow Tol Ratio= 0.001
Split Flow NTrial= 30
Split Flow Tol= 0.02
Split Flow Ratio= 0.02
Log Output Level= 0
Friction Slope Method= 1
Unsteady Friction Slope Method= 2
Unsteady Bridges Friction Slope Method= 1
Parabolic Critical Depth
Global Vel Dist=  1 , 1 , 1
Global Log Level= 0
CheckData=True
Encroach Param= -1, 0, 0, 0
BEGIN DESCRIPTION:
Multiple Run
END DESCRIPTION:

--- UNT028 IN CCTC.f01 (steady flow) ---

Flow Title=Multiple
Number of Profiles=7
Profile Names=10-year,25-year,50-year,1pct_min,100-year,1pct_plu,500-year
River Rch & RM= UNT028 IN CCTC,Reach-1,3811
     900    1207    1454    1279    1730    2340    2441
Boundary for River Rch & Prof#=UNT028 IN CCTC,Reach-1,1
Up Type=0
Dn Type=3
Dn Slope=0.005
Boundary for River Rch & Prof#=UNT028 IN CCTC,Reach-1,2
Up Type=0
Dn Type=3
Dn Slope=0.005
Boundary for River Rch & Prof#=UNT028 IN CCTC,Reach-1,3
Up Type=0
Dn Type=3
Dn Slope=0.005
Boundary for River Rch & Prof#=UNT028 IN CCTC,Reach-1,4
Up Type=0
Dn Type=3
Dn Slope=0.005
Boundary for River Rch & Prof#=UNT028 IN CCTC,Reach-1,5
Up Type=0
Dn Type=3
Dn Slope=0.005
Boundary for River Rch & Prof#=UNT028 IN CCTC,Reach-1,6
Up Type=0
Dn Type=3
Dn Slope=0.005
Boundary for River Rch & Prof#=UNT028 IN CCTC,Reach-1,7
Up Type=0
Dn Type=3
Dn Slope=0.005

--- UNT028 IN CCTC.g01 (geometry) ---

Geom Title=Existing Conditions
Program Version=4.10

River Reach=UNT028 IN CCTC  ,Reach-1
Reach XY= 30
      3497709.76     10610560.19      3497806.25       10610456.
       3497954.5       10610518.       3498002.5       10610661.
      3498190.75       10610639.       3498394.5       10610797.
      3498502.25       10610796.      3498676.75       10610696.
      3498744.75       10610751.       3498699.5       10610803.
        3498739.       10610899.        3498917.       10610776.
       3499002.5       10610816.        3499018.       10610705.
        3499120.       10610697.        3499267.       10610988.
      3499385.75       10610944.       3499452.5       10610867.
       3499465.5       10610991.      3499568.25       10610977.
      3499628.25       10610848.      3499743.75       10610878.
       3499829.5       10611059.      3499927.75       10611005.
      3499871.25       10610914.       3499903.5       10610827.
      3499825.25       10610828.        3499811.       10610786.
       3499885.5       10610745.       3499909.5       10610768.

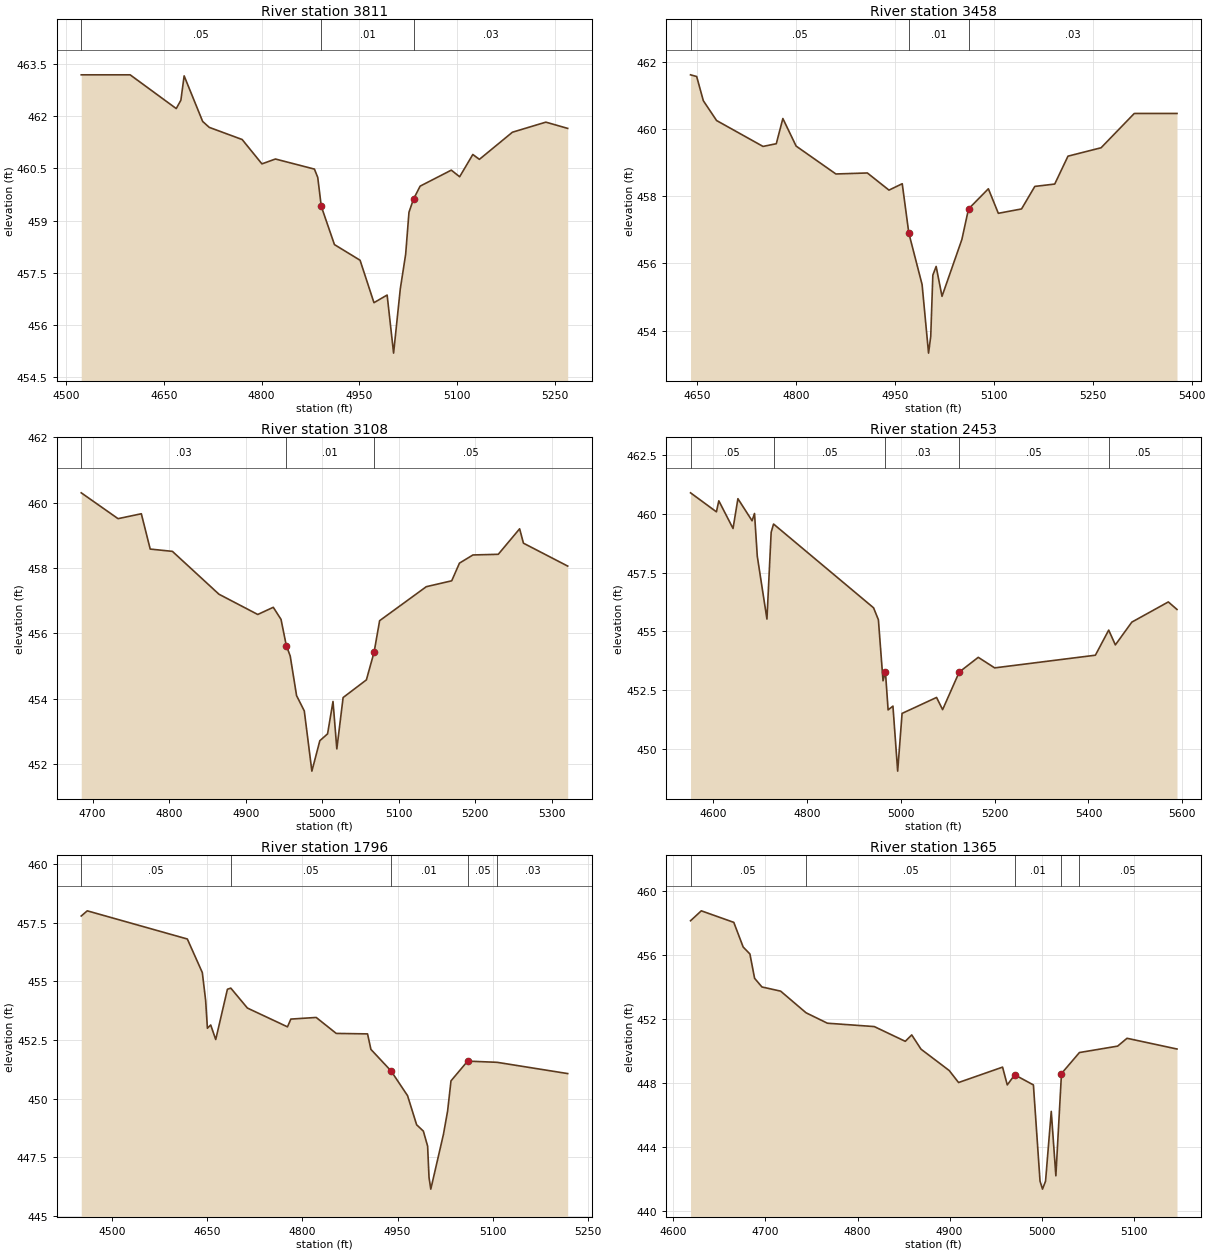
Type RM Length L Ch R = 1 ,3811    ,353,353,353
BEGIN DESCRIPTION:
UNT028 IN CCTC 1.0
END DESCRIPTION:
XS GIS Cut Line= 2
      3497772.25      10610944.4      3497880.06     10610206.23
#Sta/Elev= 30
  4523.3  463.19  4598.3  463.19    4669  462.22  4676.1  462.46  4681.1  463.16
  4709.5  461.85  4719.6  461.68  4770.1  461.33  4800.4  460.63  4821.1  460.77
  4880.9  460.48    4886  460.24  4891.4  459.41  4911.6  458.31  4950.9  457.86
  4972.2  456.64  4992.4  456.86  5002.3  455.19  5012.6  457.04  5020.8  458.03
  5025.9  459.24  5032.9  459.62    5043  459.99  5090.8  460.45  5103.6  460.26
  5123.8   460.9  5133.9  460.76  5184.5  461.54  5235.8  461.83  5269.3  461.65
#Mann= 3 , 0 , 0
  4523.3     .05       0  4891.4     .01       0  5032.9     .03       0
Bank Sta=4891.4,5032.9
XS Rating Curve= 0 ,0
Exp/Cntr=0.3,0.1

Type RM Length L Ch R = 1 ,3458    ,350,350,350
BEGIN DESCRIPTION:
Mapping XS 16fd9079
END DESCRIPTION:
XS GIS Cut Line= 2
      3498037.01     10611009.48      3498112.26     10610275.73
#Sta/Elev= 30
  4640.2  461.61  4649.5  461.56  4659.6  460.84  4679.7  460.25  4750.1  459.48
  4770.2  459.56  4780.2  460.31  4800.3  459.49  4860.6  458.66  4908.3  458.69
  4941.1  458.18  4961.2  458.37  4971.2   456.9  4991.3  455.37  5001.1  453.33
  5004.4  453.83  5007.6  455.65  5012.6  455.91  5021.5  455.02  5051.6  456.71
  5061.7  457.62  5091.8  458.22  5106.9  457.49  5142.1  457.62  5162.2  458.29
  5192.4  458.36  5212.5  459.19  5262.7  459.44    5313  460.46  5377.8  460.46
#Mann= 3 , 0 , 0
  4640.2     .05       0  4971.2     .01       0  5061.7     .03       0
Bank Sta=4971.2,5061.7
XS Rating Curve= 0 ,0
Exp/Cntr=0.3,0.1

Type RM Length L Ch R = 1 ,3108    ,655,655,655
BEGIN DESCRIPTION:
Mapping XS c3d5406f
END DESCRIPTION:
XS GIS Cut Line= 2
      3498310.44     10611087.66      3498414.49     10610460.73
#Sta/Elev= 30
  4685.2   460.3  4733.3  459.51  4763.7  459.66  4775.3  458.58  4804.3  458.51
  4865.1   457.2  4915.8  456.58  4936.1   456.8  4946.2  456.43  4953.1  455.63
  4958.2  455.31  4966.5   454.1  4976.6  453.63  4986.5  451.79  4996.9  452.72
    5007  452.93  5014.1  453.92  5019.1  452.47  5027.3  454.04  5057.7  454.58
  5067.8  455.43    5075  456.39    5136  457.43  5169.2  457.61  5179.3  458.15
  5196.9   458.4    5230  458.42  5257.9   459.2  5262.9  458.76  5320.7  458.06
#Mann= 3 , 0 , 0
  4685.2     .03       0  4953.1     .01       0  5067.8     .05       0
Bank Sta=4953.1,5067.8
XS Rating Curve= 0 ,0
Exp/Cntr=0.3,0.1

Type RM Length L Ch R = 1 ,2453    ,657,657,657
BEGIN DESCRIPTION:
Mapping XS 25f047d7
END DESCRIPTION:
XS GIS Cut Line= 3
       3498650.6     10611327.92      3498820.16     10610672.84
      3498578.89     10610405.08
#Sta/Elev= 30
  4551.6   460.9  4606.8  460.09  4611.9  460.56  4642.2  459.38  4652.6  460.65
  4682.8  459.71    4688  460.02  4693.9   458.2  4714.5  455.52  4723.5  459.22
  4728.6  459.57  4941.8     456  4952.1  455.49    4962  452.89  4967.1  453.27
  4972.8  451.65  4983.1  451.81  4993.2  449.04  5002.6   451.5  5076.1  452.18
    5089  451.66  5124.4  453.26    5165  453.89    5200  453.44  5414.7  453.98
  5443.1  455.05  5457.3  454.42  5492.4  455.39  5570.2  456.25  5588.7  455.93
#Mann= 5 ,-1 , 0
  4551.6     .05       0  4728.6     .05       0  4967.1     .03       0
  5124.4     .05       0  5443.1     .05       0
Bank Sta=4967.1,5124.4
XS Rating Curve= 0 ,0
Exp/Cntr=0.3,0.1

Type RM Length L Ch R = 1 ,1796    ,431,431,431
BEGIN DESCRIPTION:
Mapping XS 02208492
END DESCRIPTION:
XS GIS Cut Line= 2
      3498980.48     10611320.93      3499224.42      10610594.7
#Sta/Elev= 30
  4451.8  457.78  4461.3     458  4618.9   456.8  4642.5  455.37  4647.7  454.19
  4650.5     453  4655.7  453.14  4663.6  452.52    4682  454.66  4687.3  454.71
  4713.5  453.86  4776.6  453.06  4781.9  453.39  4821.8  453.46  4853.4  452.78
  4902.7  452.76    4908   452.1  4939.5  451.19  4965.7  450.13    4980  448.89
  4990.6  448.62  4997.3  447.98  4999.5  446.65  5002.3  446.15  5022.2  448.48
  5028.8  449.48  5034.1  450.76  5060.3   451.6  5106.6  451.55  5217.9  451.07
#Mann= 5 ,-1 , 0
  4451.8     .05       0  4687.3     .05       0  4939.5     .01       0
  5060.3     .05       0  5106.6     .03       0
Bank Sta=4939.5,5060.3
XS Rating Curve= 0 ,0
Exp/Cntr=0.3,0.1

Type RM Length L Ch R = 1 ,1365    ,465,465,465
BEGIN DESCRIPTION:
Mapping XS 736b6382
END DESCRIPTION:
XS GIS Cut Line= 2
      3499352.45     10611256.44      3499448.76     10610736.79
#Sta/Elev= 30
  4618.6  458.13  4630.3  458.75  4665.6  458.03  4675.8  456.49  4683.1  456.06
  4688.2  454.54  4696.2     454  4716.5  453.74  4744.1  452.39  4767.3  451.74
  4818.2  451.53  4851.9  450.61  4858.9  451.01    4869  450.12  4899.6  448.79
  4909.8  448.04  4957.6     449  4962.7  447.89  4970.8  448.52  4991.1  447.89
  4998.3  441.89    5001  441.39  5004.3  441.89  5010.5  446.24  5015.5  442.22
  5021.6   448.6  5041.1  449.91  5082.6  450.31  5092.8   450.8  5147.1  450.13
#Mann= 5 ,-1 , 0
  4618.6     .05       0  4744.1     .05       0  4970.8     .01       0
  5021.6     .03       0  5041.1     .05       0
Bank Sta=4970.8,5021.6
XS Rating Curve= 0 ,0
Exp/Cntr=0.3,0.1

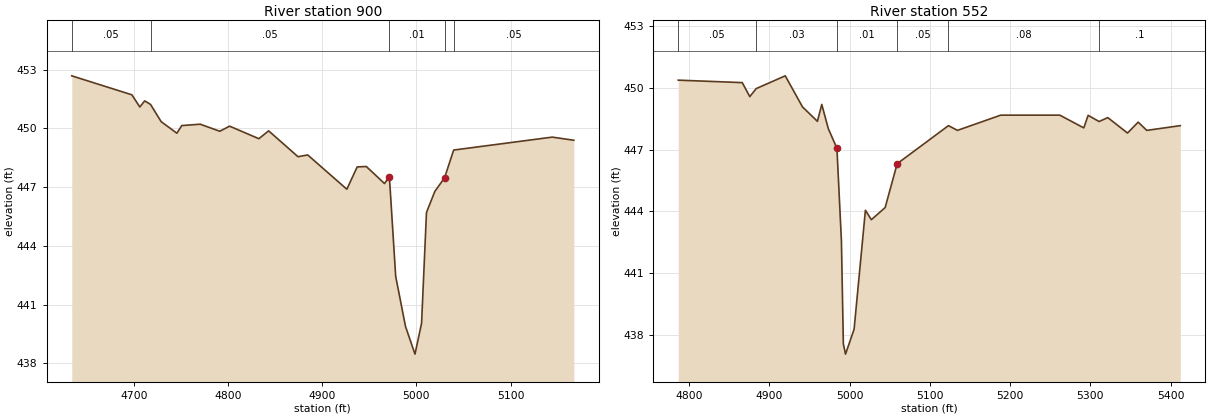
Type RM Length L Ch R = 1 ,900     ,348,348,348
BEGIN DESCRIPTION:
Mapping XS 499403de
END DESCRIPTION:
XS GIS Cut Line= 3
      3499554.27      10611221.7      3499664.92      10610825.3
      3499631.07     10610708.14
#Sta/Elev= 30
  4633.8  452.68  4697.7  451.71  4706.1  451.09  4711.3   451.4  4717.5  451.22
  4728.8  450.34  4745.5  449.75  4750.7  450.14  4770.3  450.21  4791.1  449.85
  4801.5  450.11  4832.6  449.47    4843  449.87  4874.2  448.55  4884.5  448.64
  4926.1  446.89  4937.1  448.03  4946.8  448.05  4966.1  447.18  4971.3  447.53
    4978  442.44  4988.4  439.89  4998.5  438.47  5005.5  440.05  5010.7   445.7
  5019.6  446.78  5029.9  447.47  5039.6  448.89  5144.4  449.55  5167.3  449.39
#Mann= 5 ,-1 , 0
  4633.8     .05       0  4717.5     .05       0  4971.3     .01       0
  5029.9     .03       0  5039.6     .05       0
Bank Sta=4971.3,5029.9
XS Rating Curve= 0 ,0
Exp/Cntr=0.3,0.1

Type RM Length L Ch R = 1 ,552     ,0,0,0
BEGIN DESCRIPTION:
UNT028 IN CCTC 2.0
END DESCRIPTION:
XS GIS Cut Line= 2
      3499938.35     10611244.56      3499711.78     10610661.22
#Sta/Elev= 30
  4786.3  450.38  4866.1  450.26  4875.5  449.58  4883.5  449.97  4919.7  450.59
  4941.2  449.08  4959.8  448.38  4965.2   449.2  4973.4  448.02  4984.1  447.07
  4989.7  442.58  4992.1  437.57  4994.8  437.07  5005.5  438.28  5019.6  444.06
    5027   443.6  5044.2  444.19  5059.2  446.32  5123.1  448.17  5134.3  447.94
  5188.3  448.68  5261.9  448.68  5291.8  448.06  5297.2  448.67  5310.9  448.37
  5321.7  448.56  5346.3  447.81  5359.6  448.34  5370.3  447.94  5412.1  448.17
#Mann= 6 ,-1 , 0
  4786.3     .05       0  4883.5     .03       0  4984.1     .01       0
  5059.2     .05       0  5123.1     .08       0  5310.9      .1       0
Bank Sta=4984.1,5059.2
XS Rating Curve= 0 ,0
Exp/Cntr=0.3,0.1

Chan Stop Cuts=-1
Use User Specified Reach Order=0
Composite Channel Slope=5