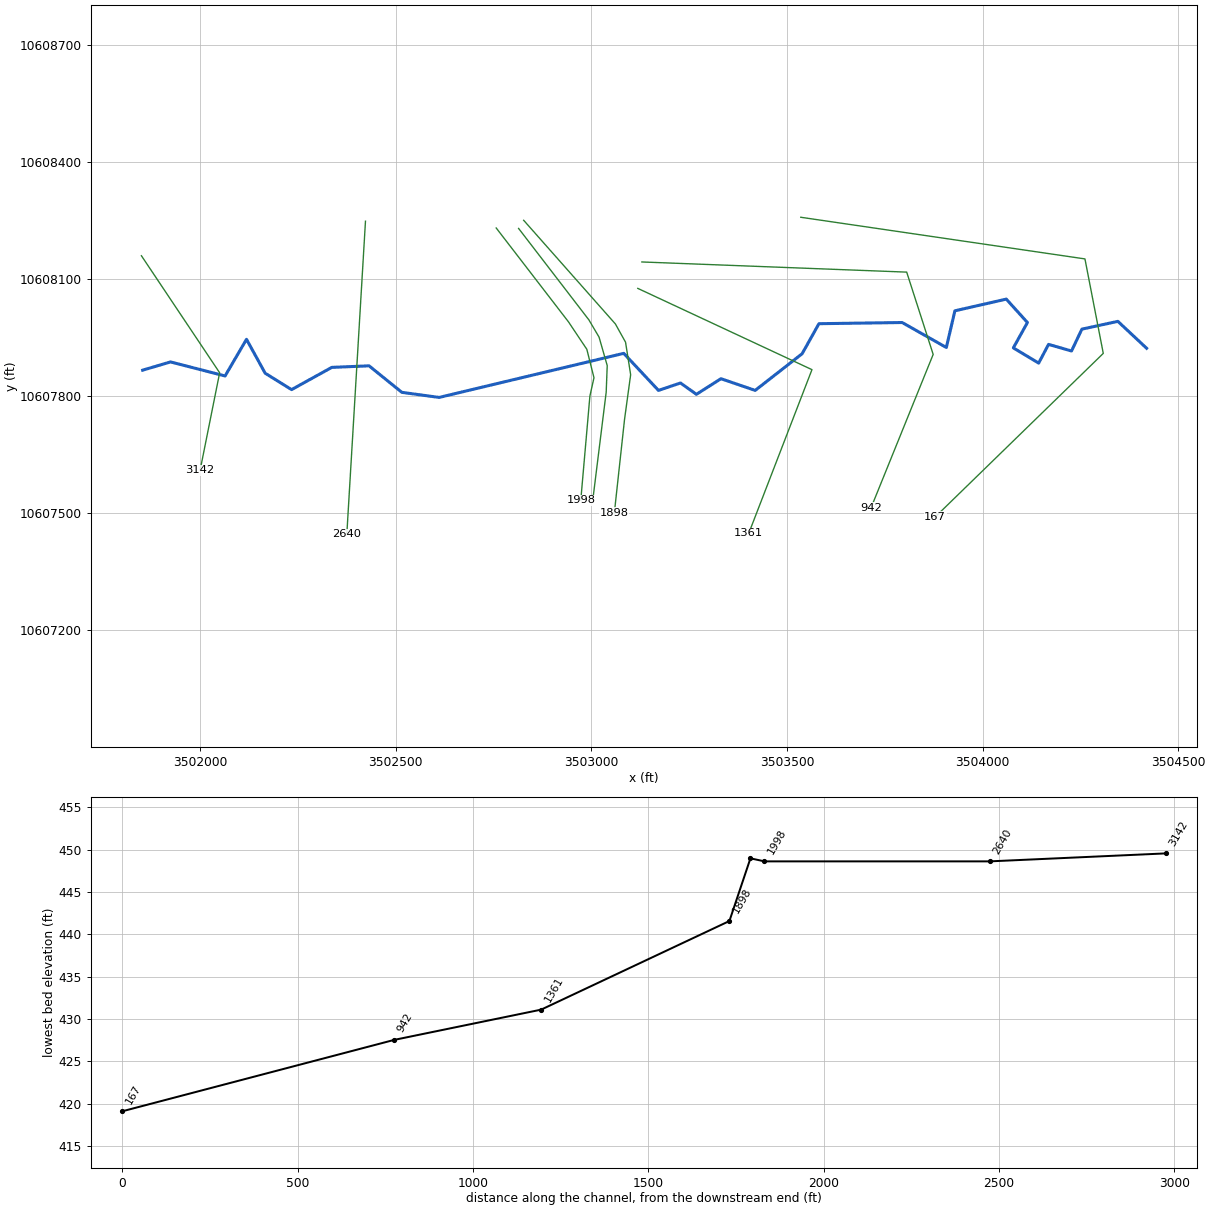
--- UNT029 IN CCTC.prj (project) ---

Proj Title=UNT029 IN CCTC Base Level Engineering
Current Plan=p01
Default Exp/Contr=0.3,0.1
English Units
Geom File=g01
Flow File=f01
Plan File=p01
BEGIN DESCRIPTION:
UNT029 IN CCTC
END DESCRIPTION:

--- UNT029 IN CCTC.p01 (plan) ---

Plan Title=Multiple Run
Short Identifier=Multiple
Geom File=g01
Flow File=f01
Subcritical Flow
K Sum by GR= 0
Std Step Tol= 0.01
Critical Tol= 0.01
Num of Std Step Trials= 20
Max Error Tol= 0.3
Flow Tol Ratio= 0.001
Split Flow NTrial= 30
Split Flow Tol= 0.02
Split Flow Ratio= 0.02
Log Output Level= 0
Friction Slope Method= 1
Unsteady Friction Slope Method= 2
Unsteady Bridges Friction Slope Method= 1
Parabolic Critical Depth
Global Vel Dist=  1 , 1 , 1
Global Log Level= 0
CheckData=True
Encroach Param= -1, 0, 0, 0
BEGIN DESCRIPTION:
Multiple Run
END DESCRIPTION:

--- UNT029 IN CCTC.f01 (steady flow) ---

Flow Title=Multiple
Number of Profiles=7
Profile Names=10-year,25-year,50-year,1pct_min,100-year,1pct_plu,500-year
River Rch & RM= UNT029 IN CCTC,Reach-1,3142
     627     826     985     859    1162    1571    1610
Boundary for River Rch & Prof#=UNT029 IN CCTC,Reach-1,1
Up Type=0
Dn Type=3
Dn Slope=0.005
Boundary for River Rch & Prof#=UNT029 IN CCTC,Reach-1,2
Up Type=0
Dn Type=3
Dn Slope=0.005
Boundary for River Rch & Prof#=UNT029 IN CCTC,Reach-1,3
Up Type=0
Dn Type=3
Dn Slope=0.005
Boundary for River Rch & Prof#=UNT029 IN CCTC,Reach-1,4
Up Type=0
Dn Type=3
Dn Slope=0.005
Boundary for River Rch & Prof#=UNT029 IN CCTC,Reach-1,5
Up Type=0
Dn Type=3
Dn Slope=0.005
Boundary for River Rch & Prof#=UNT029 IN CCTC,Reach-1,6
Up Type=0
Dn Type=3
Dn Slope=0.005
Boundary for River Rch & Prof#=UNT029 IN CCTC,Reach-1,7
Up Type=0
Dn Type=3
Dn Slope=0.005

--- UNT029 IN CCTC.g01 (geometry) ---

Geom Title=Existing Conditions

River Reach=UNT029 IN CCTC,Reach-1
Reach XY= 30
      3501852.85     10607866.89      3501924.00     10607888.00
      3502063.50     10607852.00      3502118.25     10607946.00
      3502166.00     10607859.00      3502233.50     10607817.00
      3502336.25     10607874.00      3502431.50     10607878.00
      3502515.50     10607810.00      3502610.75     10607797.00
      3503082.75     10607910.00      3503171.50     10607815.00
      3503227.75     10607834.00      3503268.50     10607805.00
      3503331.25     10607845.00      3503418.75     10607815.00
      3503538.75     10607909.00      3503581.75     10607986.00
      3503794.50     10607989.00      3503907.50     10607925.00
      3503929.25     10608019.00      3504060.75     10608049.00
      3504114.75     10607989.00      3504078.75     10607924.00
      3504143.50     10607885.00      3504168.75     10607933.00
      3504227.50     10607916.00      3504254.00     10607972.00
      3504346.00     10607992.00      3504419.50     10607923.00

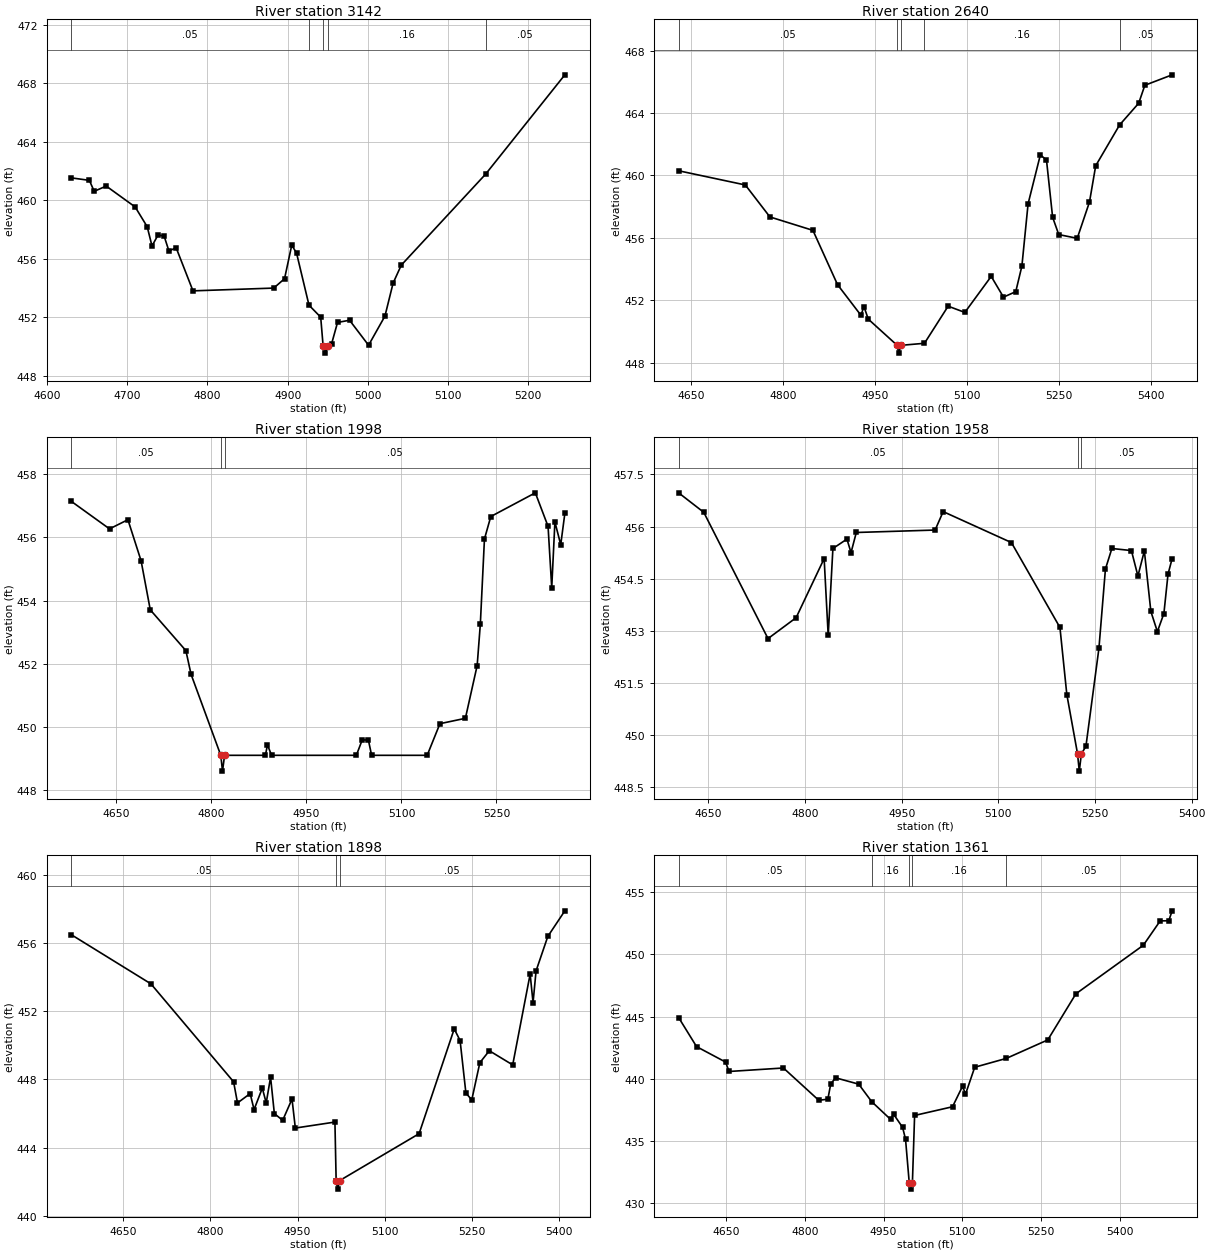
Type RM Length L Ch R = 1,3142,502,502,502
BEGIN DESCRIPTION:
UNT029 IN CCTC 3.0
END DESCRIPTION:
XS GIS Cut Line= 3
      3501849.62     10608160.17      3502049.61     10607860.19
      3501999.61     10607610.17
#Sta/Elev= 30
  4630.2  461.54  4652.7  461.37  4658.7  460.62  4673.7  460.98  4709.8  459.55
  4724.8  458.20  4730.8  456.88  4738.3  457.63  4745.9  457.56  4751.9  456.54
  4760.9  456.76  4781.9  453.81  4882.6  454.00  4896.1  454.64  4905.1  456.94
  4911.1  456.39  4926.6  452.83  4941.2  452.01  4944.2  450.05  4946.9  449.55
  4950.2  450.05  4954.7  450.17  4962.2  451.65  4977.2  451.80  5000.9  450.09
  5021.3  452.08  5031.5  454.34  5041.7  455.57  5146.8  461.79  5245.7  468.59
#Mann=5,-1,0
  4630.2    0.05       0  4926.6    0.16       0  4944.2    0.07       0
  4950.2    0.16       0  5146.8    0.05       0
Bank Sta=4944.2,4950.2
Exp/Cntr=0.3,0.1

Type RM Length L Ch R = 1,2640,642,642,642
BEGIN DESCRIPTION:
UNT029 IN CCTC 2.0
END DESCRIPTION:
XS GIS Cut Line= 2
      3502422.42     10608248.74      3502374.68     10607445.76
#Sta/Elev= 30
  4629.8  460.30  4738.5  459.39  4778.6  457.34  4848.7  456.48  4888.8  453.00
  4926.9  451.04  4931.9  451.59  4938.9  450.79  4986.0  449.11  4988.7  448.61
  4992.0  449.11  5030.5  449.24  5069.1  451.62  5096.3  451.22  5139.3  453.53
  5159.3  452.20  5179.3  452.55  5189.3  454.19  5199.4  458.18  5219.4  461.32
  5229.4  460.99  5239.4  457.32  5249.4  456.21  5279.5  455.97  5299.5  458.30
  5309.6  460.62  5348.6  463.24  5379.7  464.63  5389.7  465.78  5434.2  466.45
#Mann=5,-1,0
  4629.8    0.05       0  4986.0   0.035       0  4992.0    0.05       0
  5030.5    0.16       0  5348.6    0.05       0
Bank Sta=4986,4992
Exp/Cntr=0.3,0.1

Type RM Length L Ch R = 1,1998,40,40,40
BEGIN DESCRIPTION:
Mapping XS 4d1252f4
END DESCRIPTION:
XS GIS Cut Line= 6
      3502756.63     10608231.36      3502941.50     10607990.61
      3502988.37     10607920.30      3503006.60     10607847.38
      3502996.18     10607800.50      3502972.88     10607533.75
#Sta/Elev= 30
  4578.9  457.14  4639.2  456.27  4668.2  456.56  4689.0  455.26  4703.5  453.71
  4759.7  452.42  4767.9  451.67  4814.8  449.11  4817.5  448.61  4820.8  449.11
  4885.2  449.11  4888.5  449.44  4895.0  449.11  5028.8  449.11  5038.1  449.60
  5047.8  449.59  5052.9  449.11  5140.6  449.11  5160.7  450.11  5200.9  450.28
  5219.5  451.95  5224.5  453.26  5231.0  455.95  5241.0  456.66  5311.3  457.41
  5331.4  456.35  5337.2  454.41  5342.2  456.49  5351.4  455.77  5357.9  456.76
#Mann=3,-1,0
  4578.9    0.05       0  4814.8   0.035       0  4820.8    0.05       0
Bank Sta=4814.8,4820.8
Exp/Cntr=0.3,0.1

Type RM Length L Ch R = 1,1958,60,60,60
BEGIN DESCRIPTION:
Mapping XS d445a4b0
END DESCRIPTION:
XS GIS Cut Line= 6
      3502813.92     10608230.15      3502993.58     10607995.82
      3503019.62     10607951.55      3503040.46     10607878.63
      3503037.85     10607810.92      3503003.99     10607537.44
#Sta/Elev= 30
  4603.9  456.97  4642.9  456.41  4742.6  452.78  4786.2  453.38  4829.7  455.08
  4836.0  452.87  4843.3  455.37  4865.1  455.64  4871.4  455.25  4879.6  455.83
  5001.9  455.90  5014.4  456.43  5120.3  455.54  5195.6  453.10  5206.3  451.17
  5222.9  449.47  5225.6  448.97  5228.9  449.47  5235.9  449.68  5256.1  452.50
  5266.2  454.78  5276.2  455.37  5306.5  455.31  5316.6  454.58  5326.6  455.30
  5336.7  453.56  5346.8  452.98  5356.9  453.50  5363.3  454.63  5369.7  455.08
#Mann=3,-1,0
  4603.9    0.05       0  5222.9   0.035       0  5228.9    0.05       0
Bank Sta=5222.9,5228.9
Exp/Cntr=0.3,0.1

Type RM Length L Ch R = 1,1898,537,537,537
BEGIN DESCRIPTION:
Mapping XS 2b74dfce
END DESCRIPTION:
XS GIS Cut Line= 6
      3502826.88     10608251.06      3503061.29     10607985.40
      3503087.33     10607938.53      3503100.35     10607855.19
      3503084.73     10607740.61      3503058.68     10607501.02
#Sta/Elev= 30
  4560.9  456.48  4697.8  453.60  4840.0  447.86  4846.7  446.62  4868.5  447.17
  4875.2  446.23  4889.4  447.49  4896.1  446.62  4903.6  448.13  4910.1  446.00
  4924.4  445.60  4940.5  446.85  4946.2  445.15  5014.3  445.50  5016.4  442.07
  5019.1  441.57  5022.4  442.07  5159.1  444.82  5219.5  450.96  5229.6  450.28
  5239.6  447.20  5249.7  446.80  5263.6  448.98  5279.9  449.68  5320.1  448.85
  5350.1  454.17  5355.1  452.50  5360.3  454.36  5380.5  456.38  5409.8  457.88
#Mann=3,-1,0
  4560.9    0.05       0  5016.4   0.035       0  5022.4    0.05       0
Bank Sta=5016.4,5022.4
Exp/Cntr=0.3,0.1

Type RM Length L Ch R = 1,1361,419,419,419
BEGIN DESCRIPTION:
Mapping XS 326638ee
END DESCRIPTION:
XS GIS Cut Line= 3
      3503118.62     10608076.53      3503563.89     10607868.21
      3503402.43     10607448.92
#Sta/Elev= 30
  4559.2  444.92  4593.4  442.58  4648.6  441.34  4655.4  440.58  4759.0  440.86
  4826.4  438.26  4843.7  438.35  4849.2  439.58  4858.4  440.07  4902.5  439.56
  4927.3  438.15  4963.4  436.72  4968.9  437.15  4986.2  436.08  4991.8  435.13
  4998.9  431.61  5001.7  431.11  5004.9  431.61  5009.1  437.04  5081.4  437.74
  5100.7  439.41  5106.0  438.73  5123.7  440.92  5183.8  441.63  5263.0  443.12
  5316.6  446.83  5445.2  450.74  5477.3  452.70  5493.7  452.71  5500.1  453.51
#Mann=5,-1,0
  4559.2    0.05       0  4927.3    0.16       0  4998.9    0.07       0
  5004.9    0.16       0  5183.8    0.05       0
Bank Sta=4998.9,5004.9
Exp/Cntr=0.3,0.1

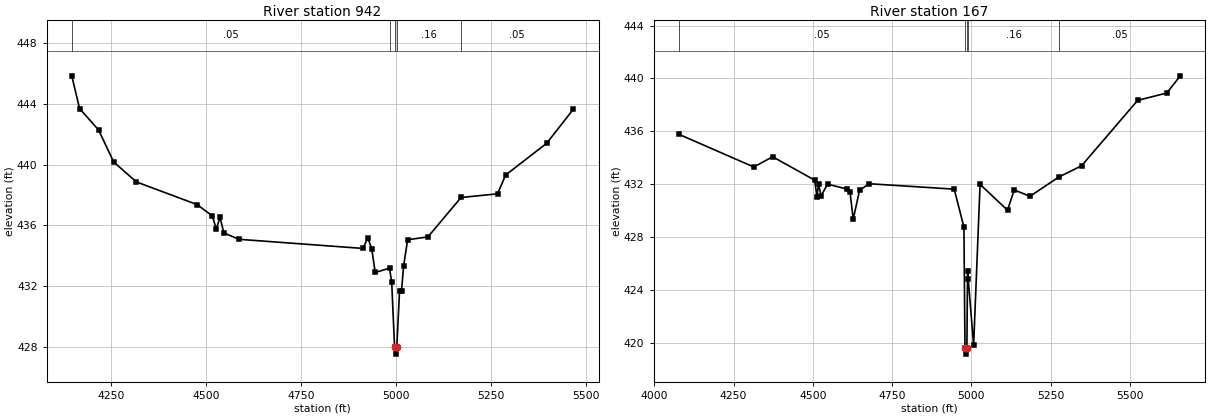
Type RM Length L Ch R = 1,942,775,775,775
BEGIN DESCRIPTION:
Mapping XS 0ceaddb3
END DESCRIPTION:
XS GIS Cut Line= 4
      3503129.01     10608144.25      3503806.08     10608118.21
      3503873.79     10607907.28      3503715.16     10607514.61
#Sta/Elev= 30
  4145.3  445.84  4165.9  443.69  4216.0  442.28  4256.0  440.17  4316.0  438.86
  4476.1  437.37  4516.2  436.62  4526.2  435.76  4536.2  436.54  4546.2  435.51
  4586.2  435.09  4913.1  434.49  4925.8  435.18  4936.3  434.46  4945.3  432.91
  4983.0  433.19  4988.8  432.27  4996.3  428.04  4999.1  427.54  5002.3  428.04
  5009.5  431.71  5014.7  431.71  5020.3  433.36  5030.8  435.06  5084.4  435.25
  5171.6  437.84  5267.8  438.08  5289.3  439.32  5397.2  441.40  5467.9  443.65
#Mann=5,-1,0
  4145.3    0.05       0  4983.0    0.16       0  4996.3    0.07       0
  5002.3    0.16       0  5171.6    0.05       0
Bank Sta=4996.3,5002.3
Exp/Cntr=0.3,0.1

Type RM Length L Ch R = 1,167,0,0,0
BEGIN DESCRIPTION:
UNT029 IN CCTC 1.0
END DESCRIPTION:
XS GIS Cut Line= 4
      3503535.29     10608258.83      3504261.81     10608152.07
      3504308.68     10607909.88      3503878.96     10607490.58
#Sta/Elev= 30
  4077.1  435.77  4313.9  433.29  4373.4  434.06  4506.0  432.29  4512.9  431.04
  4518.0  431.99  4526.2  431.10  4546.4  431.99  4607.0  431.62  4617.2  431.41
  4627.3  429.33  4647.4  431.53  4677.8  432.02  4945.7  431.61  4976.3  428.74
  4979.7  419.62  4982.5  419.12  4985.7  419.62  4987.8  425.43  4989.8  424.84
  5006.9  419.78  5027.2  431.97  5113.7  430.02  5135.0  431.55  5184.5  431.07
  5275.6  432.53  5347.2  433.38  5523.9  438.33  5615.8  438.89  5658.5  440.19
#Mann=5,-1,0
  4077.1    0.05       0  4979.7    0.07       0  4985.7    0.05       0
  4989.8    0.16       0  5275.6    0.05       0
Bank Sta=4979.7,4985.7
Exp/Cntr=0.3,0.1

Chan Stop Cuts=-1