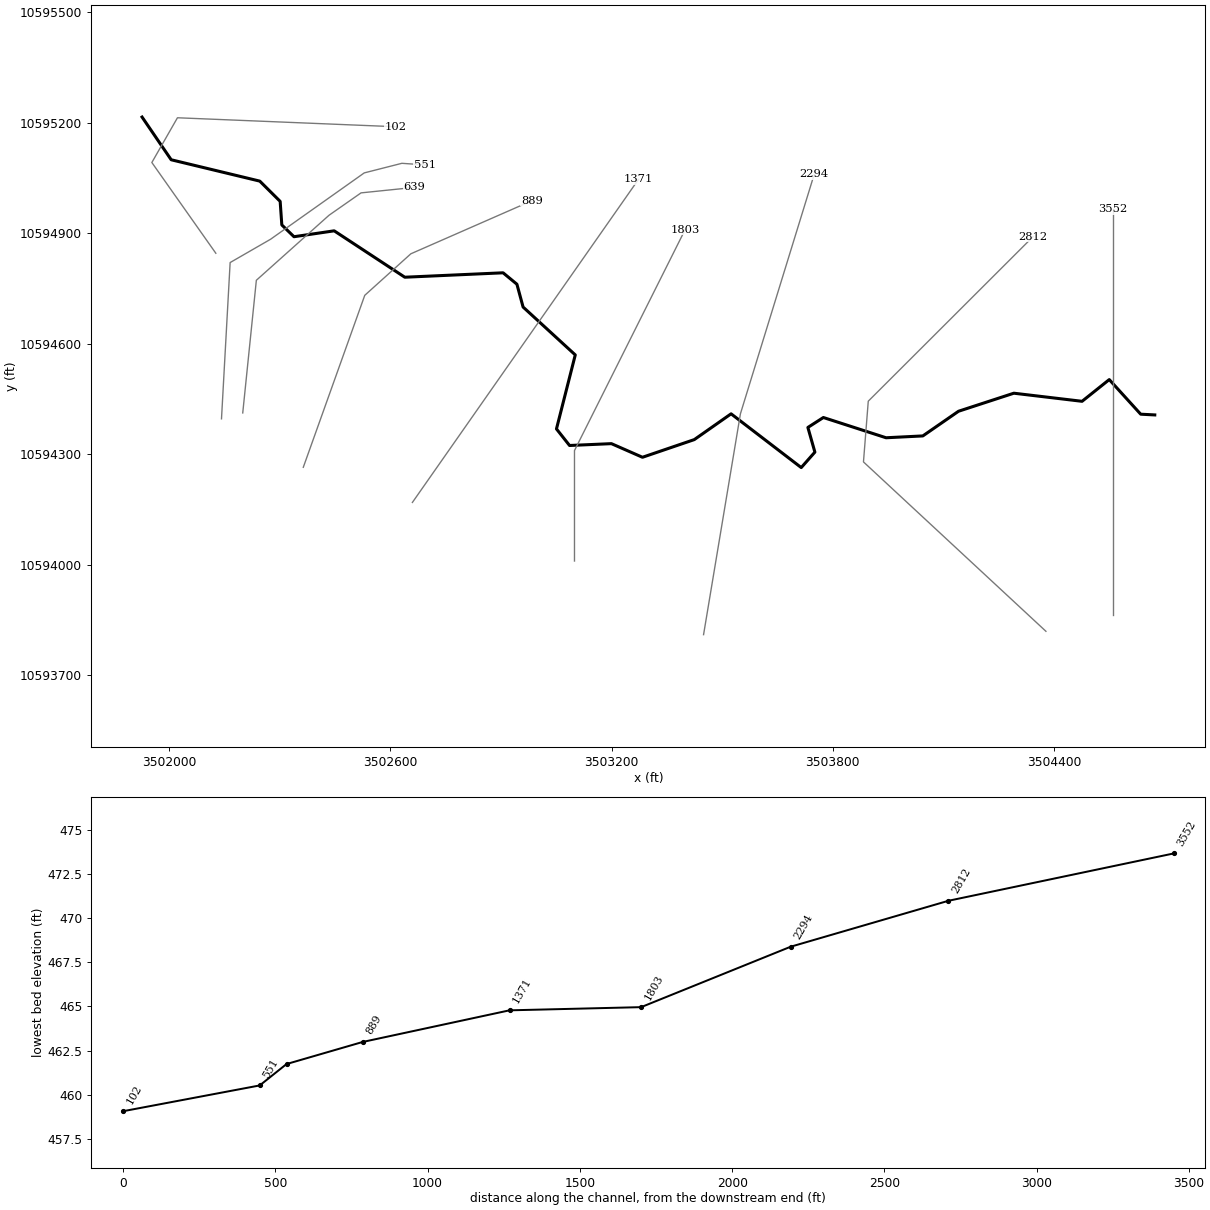
--- UNT033 IN CCTC.prj (project) ---

Proj Title=UNT033 IN CCTC Base Level Engineering
Current Plan=p01
Default Exp/Contr=0.3,0.1
English Units
Geom File=g01
Flow File=f01
Plan File=p01
Y Axis Title=Elevation
X Axis Title(PF)=Main Channel Distance
X Axis Title(XS)=Station
BEGIN DESCRIPTION:
UNT033 IN CCTC
END DESCRIPTION:
DSS Export Rating Curves= 0
DSS Export Rating Curve Sorted= 0
DSS Export Volume Flow Curves= 0
DXF OffsetX= 0
DXF OffsetY= 0
DXF ScaleX= 1
DXF ScaleY= 10

--- UNT033 IN CCTC.p01 (plan) ---

Plan Title=Multiple Run
Short Identifier=Multiple
Geom File=g01
Flow File=f01
Subcritical Flow
K Sum by GR= 0
Std Step Tol= 0.01
Critical Tol= 0.01
Num of Std Step Trials= 20
Max Error Tol= 0.3
Flow Tol Ratio= 0.001
Split Flow NTrial= 30
Split Flow Tol= 0.02
Split Flow Ratio= 0.02
Log Output Level= 0
Friction Slope Method= 1
Unsteady Friction Slope Method= 2
Unsteady Bridges Friction Slope Method= 1
Parabolic Critical Depth
Global Vel Dist=  1 , 1 , 1
Global Log Level= 0
CheckData=True
Encroach Param= -1, 0, 0, 0
BEGIN DESCRIPTION:
Multiple Run
END DESCRIPTION:

--- UNT033 IN CCTC.f01 (steady flow) ---

Flow Title=Multiple
Number of Profiles=7
Profile Names=10-year,25-year,50-year,1pct_min,100-year,1pct_plu,500-year
River Rch & RM= UNT033 IN CCTC,Reach-1,3552
    1076    1469    1791    1595    2157    2918    3120
Boundary for River Rch & Prof#=UNT033 IN CCTC,Reach-1,1
Up Type=0
Dn Type=3
Dn Slope=0.005
Boundary for River Rch & Prof#=UNT033 IN CCTC,Reach-1,2
Up Type=0
Dn Type=3
Dn Slope=0.005
Boundary for River Rch & Prof#=UNT033 IN CCTC,Reach-1,3
Up Type=0
Dn Type=3
Dn Slope=0.005
Boundary for River Rch & Prof#=UNT033 IN CCTC,Reach-1,4
Up Type=0
Dn Type=3
Dn Slope=0.005
Boundary for River Rch & Prof#=UNT033 IN CCTC,Reach-1,5
Up Type=0
Dn Type=3
Dn Slope=0.005
Boundary for River Rch & Prof#=UNT033 IN CCTC,Reach-1,6
Up Type=0
Dn Type=3
Dn Slope=0.005
Boundary for River Rch & Prof#=UNT033 IN CCTC,Reach-1,7
Up Type=0
Dn Type=3
Dn Slope=0.005

--- UNT033 IN CCTC.g01 (geometry) ---

Geom Title=Existing Conditions

River Reach=UNT033 IN CCTC,Reach-1
Reach XY= 30
      3504673.18     10594407.00      3504635.00     10594409.00
      3504549.75     10594503.00      3504476.00     10594444.00
      3504291.00     10594466.00      3504141.00     10594417.00
      3504044.25     10594350.00      3503944.50     10594345.00
      3503774.50     10594400.00      3503732.50     10594373.00
      3503751.50     10594306.00      3503714.50     10594264.00
      3503524.25     10594410.00      3503424.50     10594340.00
      3503284.00     10594292.00      3503199.75     10594329.00
      3503086.25     10594324.00      3503050.75     10594369.00
      3503101.75     10594570.00      3502960.25     10594700.00
      3502943.50     10594762.00      3502906.00     10594793.00
      3502639.50     10594781.00      3502448.00     10594907.00
      3502339.00     10594891.00      3502306.00     10594923.00
      3502301.50     10594987.00      3502246.25     10595042.00
      3502006.00     10595100.00      3501927.00     10595216.00

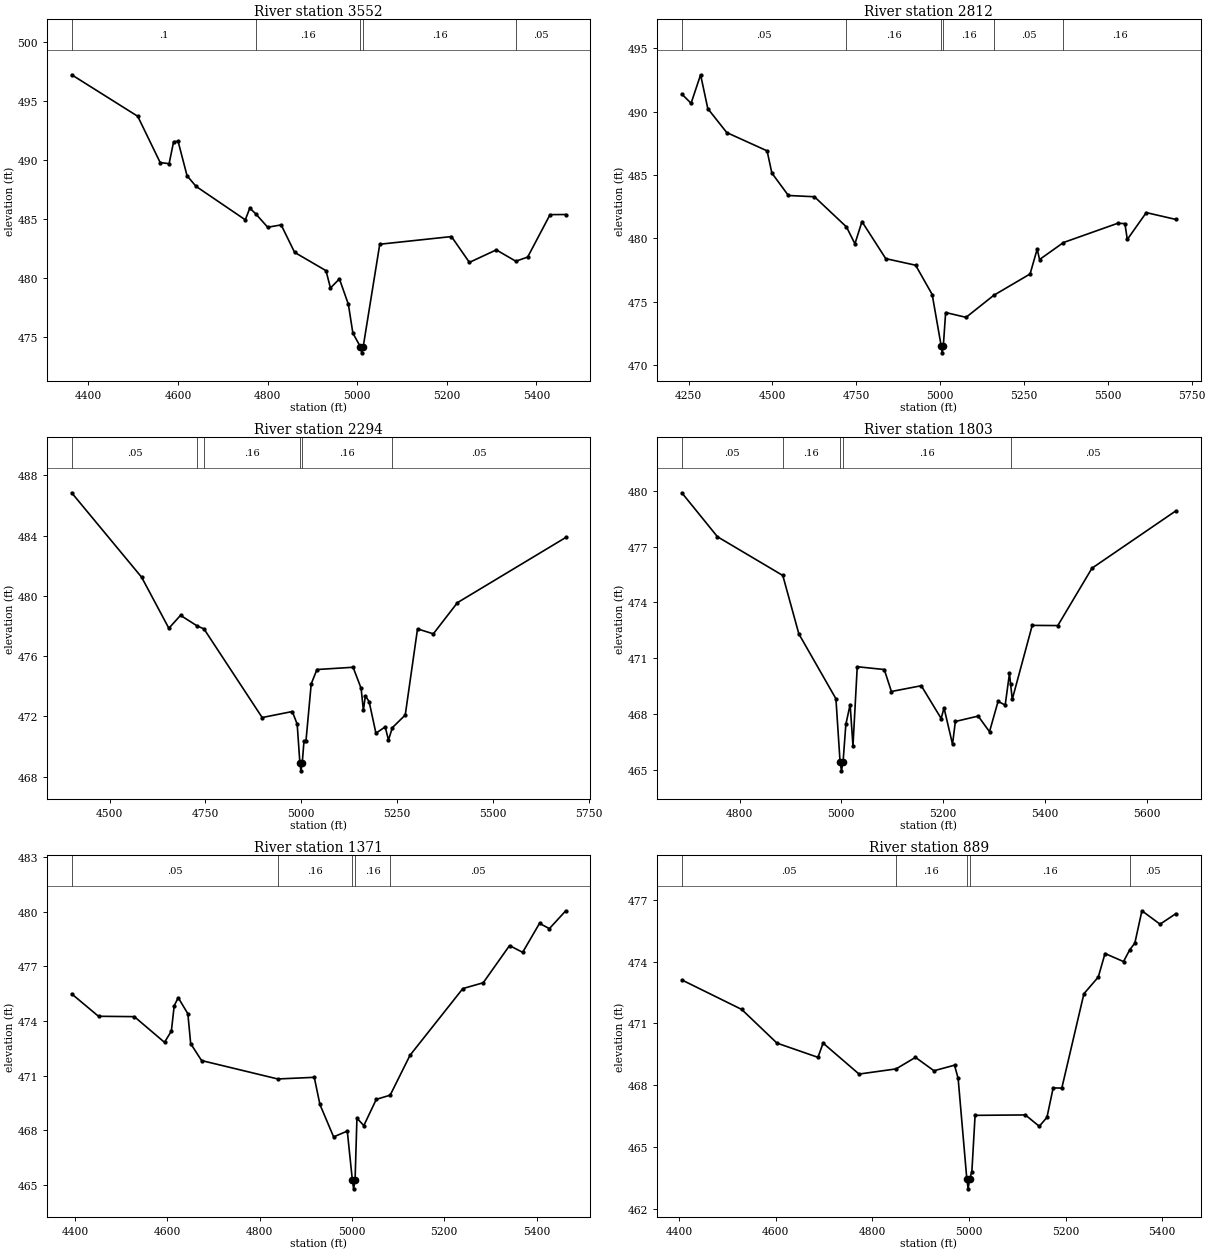
Type RM Length L Ch R = 1,3552,740,740,740
BEGIN DESCRIPTION:
UNT033 IN CCTC 6.0
END DESCRIPTION:
XS GIS Cut Line= 2
      3504560.33     10593862.76      3504560.33     10594965.16
#Sta/Elev= 30
  4363.0  497.24  4510.4  493.72  4560.4  489.80  4580.4  489.70  4590.4  491.56
  4600.4  491.60  4620.4  488.68  4640.4  487.78  4750.4  484.94  4760.4  485.93
  4773.4  485.46  4800.4  484.31  4830.4  484.51  4860.4  482.18  4930.4  480.63
  4940.4  479.16  4960.4  479.93  4980.4  477.77  4990.4  475.33  5007.4  474.16
  5010.2  473.66  5013.4  474.16  5050.4  482.87  5210.4  483.52  5250.4  481.33
  5310.4  482.39  5354.0  481.43  5380.4  481.78  5430.4  485.38  5465.4  485.39
#Mann=5,-1,0
  4363.0     0.1       0  4773.4    0.16       0  5007.4    0.07       0
  5013.4    0.16       0  5354.0    0.05       0
Bank Sta=5007.4,5013.4
Exp/Cntr=0.3,0.1

Type RM Length L Ch R = 1,2812,518,518,518
BEGIN DESCRIPTION:
UNT033 IN CCTC 5.0
END DESCRIPTION:
XS GIS Cut Line= 4
      3504378.01     10593819.34      3503883.24     10594279.39
      3503896.26     10594444.32      3504343.34     10594891.39
#Sta/Elev= 30
  4229.7  491.39  4257.3  490.66  4285.7  492.91  4307.2  490.24  4363.8  488.35
  4484.0  486.91  4498.2  485.16  4547.5  483.39  4625.2  483.29  4720.7  480.91
  4745.9  479.58  4766.9  481.33  4837.8  478.41  4926.9  477.89  4976.3  475.58
  5003.4  471.48  5006.2  470.98  5009.4  471.48  5016.4  474.16  5077.3  473.78
  5160.1  475.52  5268.2  477.20  5289.4  479.16  5296.5  478.34  5367.8  479.68
  5529.8  481.20  5551.0  481.17  5558.1  479.92  5614.7  482.04  5703.0  481.50
#Mann=6,-1,0
  4229.7    0.05       0  4720.7    0.16       0  5003.4    0.07       0
  5009.4    0.16       0  5160.1    0.05       0  5367.8    0.16       0
Bank Sta=5003.4,5009.4
Exp/Cntr=0.3,0.1

Type RM Length L Ch R = 1,2294,491,491,491
BEGIN DESCRIPTION:
UNT033 IN CCTC 4.0
END DESCRIPTION:
XS GIS Cut Line= 3
      3503449.62     10593810.24      3503549.61     10594410.19
      3503749.61     10595060.19
#Sta/Elev= 30
  4401.1  486.85  4583.5  481.24  4654.5  477.85  4684.9  478.71  4728.6  478.00
  4746.0  477.81  4897.8  471.92  4976.4  472.32  4989.1  471.48  4996.2  468.88
  4998.9  468.38  5002.2  468.88  5006.8  470.33  5011.9  470.33  5025.7  474.16
  5040.7  475.11  5134.9  475.26  5155.8  473.86  5161.7  472.41  5166.9  473.36
  5176.7  472.98  5194.4  470.88  5218.6  471.30  5227.1  470.43  5237.4  471.25
  5270.9  472.09  5302.9  477.81  5344.1  477.48  5406.9  479.55  5689.4  483.88
#Mann=6,-1,0
  4401.1    0.05       0  4728.6     0.1       0  4746.0    0.16       0
  4996.2    0.07       0  5002.2    0.16       0  5237.4    0.05       0
Bank Sta=4996.2,5002.2
Exp/Cntr=0.3,0.1

Type RM Length L Ch R = 1,1803,432,432,432
BEGIN DESCRIPTION:
UNT033 IN CCTC 3.0
END DESCRIPTION:
XS GIS Cut Line= 3
      3503099.61     10594010.23      3503099.61     10594310.19
      3503399.62     10594910.21
#Sta/Elev= 30
  4686.6  479.89  4756.6  477.53  4885.0  475.45  4916.6  472.31  4989.4  468.83
  4997.5  465.46  5000.3  464.96  5003.5  465.46  5008.9  467.45  5017.3  468.52
  5022.9  466.30  5031.3  470.55  5084.4  470.40  5098.4  469.22  5157.1  469.53
  5196.2  467.77  5201.8  468.34  5218.5  466.39  5224.1  467.61  5268.9  467.90
  5291.2  467.06  5308.0  468.69  5322.0  468.49  5330.4  470.19  5332.6  469.63
  5335.9  468.80  5375.1  472.77  5425.4  472.76  5492.5  475.84  5657.4  478.92
#Mann=5,-1,0
  4686.6    0.05       0  4885.0    0.16       0  4997.5    0.07       0
  5003.5    0.16       0  5332.6    0.05       0
Bank Sta=4997.5,5003.5
Exp/Cntr=0.3,0.1

Type RM Length L Ch R = 1,1371,482,482,482
BEGIN DESCRIPTION:
UNT033 IN CCTC 2.0
END DESCRIPTION:
XS GIS Cut Line= 2
      3502660.08     10594169.33      3503273.19     10595046.74
#Sta/Elev= 30
  4392.8  475.48  4450.9  474.25  4528.5  474.23  4593.9  472.82  4608.8  473.44
  4614.9  474.83  4623.6  475.27  4644.5  474.39  4650.6  472.75  4674.2  471.82
  4839.3  470.81  4918.4  470.90  4930.6  469.41  4960.3  467.63  4989.9  467.95
  5000.8  465.28  5003.6  464.78  5006.8  465.28  5010.8  468.66  5025.7  468.25
  5052.7  469.69  5082.8  469.92  5125.8  472.11  5240.2  475.77  5284.4  476.09
  5341.4  478.13  5369.8  477.76  5406.4  479.35  5427.7  479.06  5463.2  480.04
#Mann=5,-1,0
  4392.8    0.05       0  4839.3    0.16       0  5000.8    0.07       0
  5006.8    0.16       0  5082.8    0.05       0
Bank Sta=5000.8,5006.8
Exp/Cntr=0.3,0.1

Type RM Length L Ch R = 1,889,250,250,250
BEGIN DESCRIPTION:
Mapping XS 261a4373
END DESCRIPTION:
XS GIS Cut Line= 4
      3502364.21     10594264.76      3502530.88     10594731.78
      3502655.88     10594844.63      3502983.97     10594988.71
#Sta/Elev= 30
  4405.5  473.11  4529.5  471.68  4602.4  470.05  4687.3  469.36  4697.9  470.05
  4772.3  468.55  4849.0  468.80  4889.1  469.36  4927.4  468.71  4969.9  468.98
  4977.4  468.34  4995.3  463.49  4998.1  462.99  5001.3  463.49  5005.8  463.81
  5012.5  466.55  5116.5  466.57  5145.3  466.02  5161.2  466.45  5174.1  467.88
  5192.0  467.87  5237.7  472.44  5267.5  473.25  5281.4  474.39  5319.7  474.00
  5332.8  474.58  5343.1  474.89  5357.8  476.46  5395.3  475.81  5428.1  476.32
#Mann=5,-1,0
  4405.5    0.05       0  4849.0    0.16       0  4995.3    0.07       0
  5001.3    0.16       0  5332.8    0.05       0
Bank Sta=4995.3,5001.3
Exp/Cntr=0.3,0.1

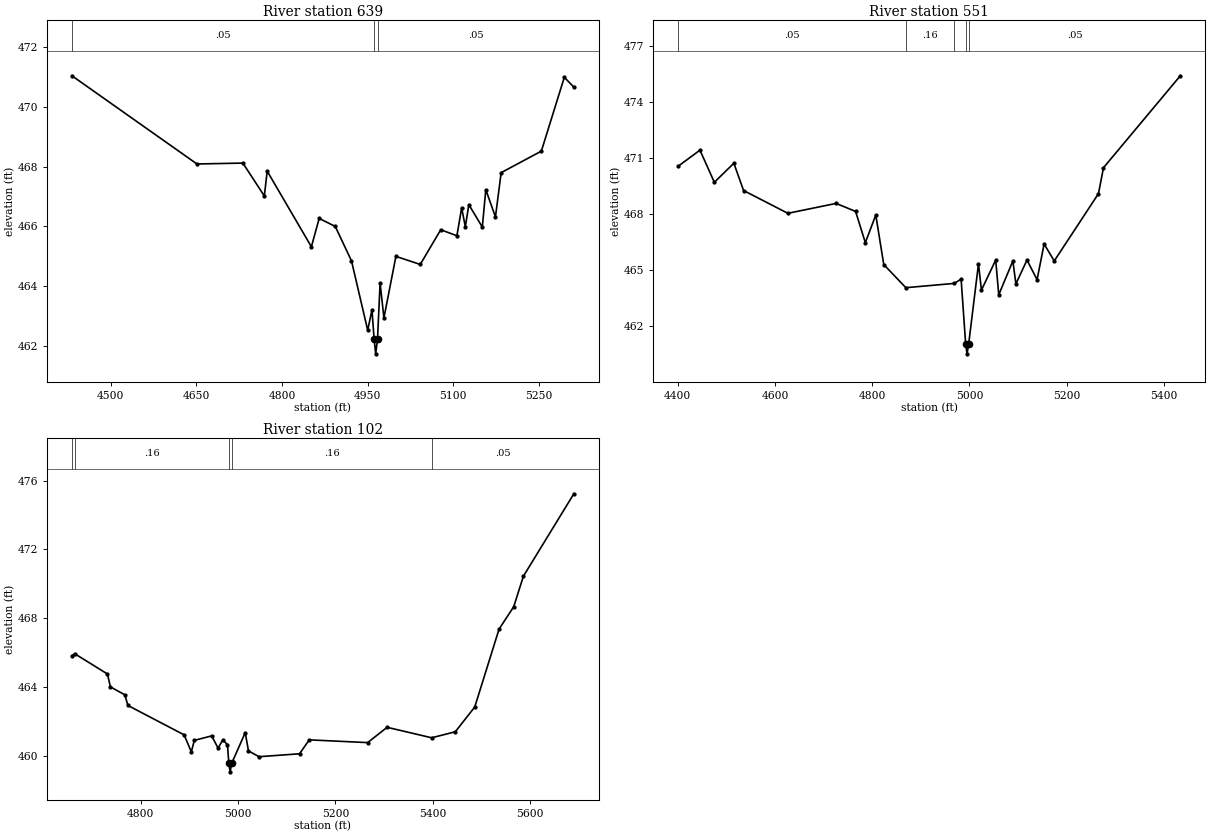
Type RM Length L Ch R = 1,639,88,88,88
BEGIN DESCRIPTION:
Mapping XS 7eebd54a
END DESCRIPTION:
XS GIS Cut Line= 5
      3502200.04     10594412.43      3502236.93     10594772.67
      3502434.03     10594949.30      3502520.84     10595010.07
      3502666.22     10595025.03
#Sta/Elev= 30
  4432.2  471.04  4651.1  468.09  4731.5  468.12  4769.1  467.02  4774.1  467.85
  4851.5  465.32  4865.1  466.27  4893.3  466.00  4921.7  464.85  4950.1  462.53
  4957.6  463.21  4961.3  462.24  4964.1  461.74  4967.3  462.24  4971.8  464.11
  4978.5  462.94  4999.5  465.00  5042.1  464.73  5078.0  465.89  5106.3  465.69
  5114.6  466.62  5121.1  465.99  5127.2  466.73  5150.8  465.98  5156.9  467.23
  5173.8  466.32  5183.8  467.80  5254.2  468.52  5294.4  470.99  5311.1  470.66
#Mann=3,-1,0
  4432.2    0.05       0  4961.3    0.04       0  4967.3    0.05       0
Bank Sta=4961.3,4967.3
Exp/Cntr=0.3,0.1

Type RM Length L Ch R = 1,551,449,449,449
BEGIN DESCRIPTION:
Mapping XS c8d9f8ee
END DESCRIPTION:
XS GIS Cut Line= 6
      3502142.42     10594396.37      3502165.86     10594820.84
      3502275.61     10594884.20      3502529.52     10595064.32
      3502631.52     10595090.36      3502694.47     10595086.02
#Sta/Elev= 30
  4401.5  470.58  4445.8  471.43  4475.4  469.71  4515.5  470.73  4535.5  469.27
  4626.6  468.05  4725.8  468.58  4765.9  468.15  4785.9  466.48  4807.4  467.96
  4823.8  465.31  4869.2  464.07  4969.1  464.30  4982.9  464.53  4992.3  461.03
  4995.1  460.53  4998.3  461.03  5018.6  465.34  5024.7  463.94  5054.0  465.55
  5060.3  463.69  5089.3  465.50  5095.6  464.27  5118.3  465.55  5139.1  464.50
  5153.6  466.41  5174.4  465.50  5265.3  469.10  5275.7  470.49  5433.7  475.41
#Mann=5,-1,0
  4401.5    0.05       0  4869.2    0.16       0  4969.1    0.05       0
  4992.3    0.04       0  4998.3    0.05       0
Bank Sta=4992.3,4998.3
Exp/Cntr=0.3,0.1

Type RM Length L Ch R = 1,102,0,0,0
BEGIN DESCRIPTION:
UNT033 IN CCTC 1.0
END DESCRIPTION:
XS GIS Cut Line= 4
      3502127.05     10594846.07      3501953.56     10595092.53
      3502023.01     10595214.06      3502613.24     10595189.76
#Sta/Elev= 30
  4658.4  465.82  4664.0  465.94  4731.4  464.76  4737.5  464.01  4767.1  463.55
  4773.5  462.93  4889.1  461.22  4903.9  460.23  4910.0  460.90  4945.7  461.16
  4958.9  460.45  4968.6  460.93  4978.2  460.65  4981.0  459.57  4983.7  459.07
  4987.0  459.57  5014.7  461.35  5021.4  460.29  5043.0  459.95  5126.4  460.12
  5146.4  460.93  5266.5  460.77  5306.5  461.66  5398.1  461.05  5446.7  461.40
  5486.7  462.84  5536.7  467.37  5566.8  468.67  5586.8  470.45  5690.5  475.24
#Mann=5,-1,0
  4658.4    0.05       0  4664.0    0.16       0  4981.0    0.07       0
  4987.0    0.16       0  5398.1    0.05       0
Bank Sta=4981,4987
Exp/Cntr=0.3,0.1

Chan Stop Cuts=-1