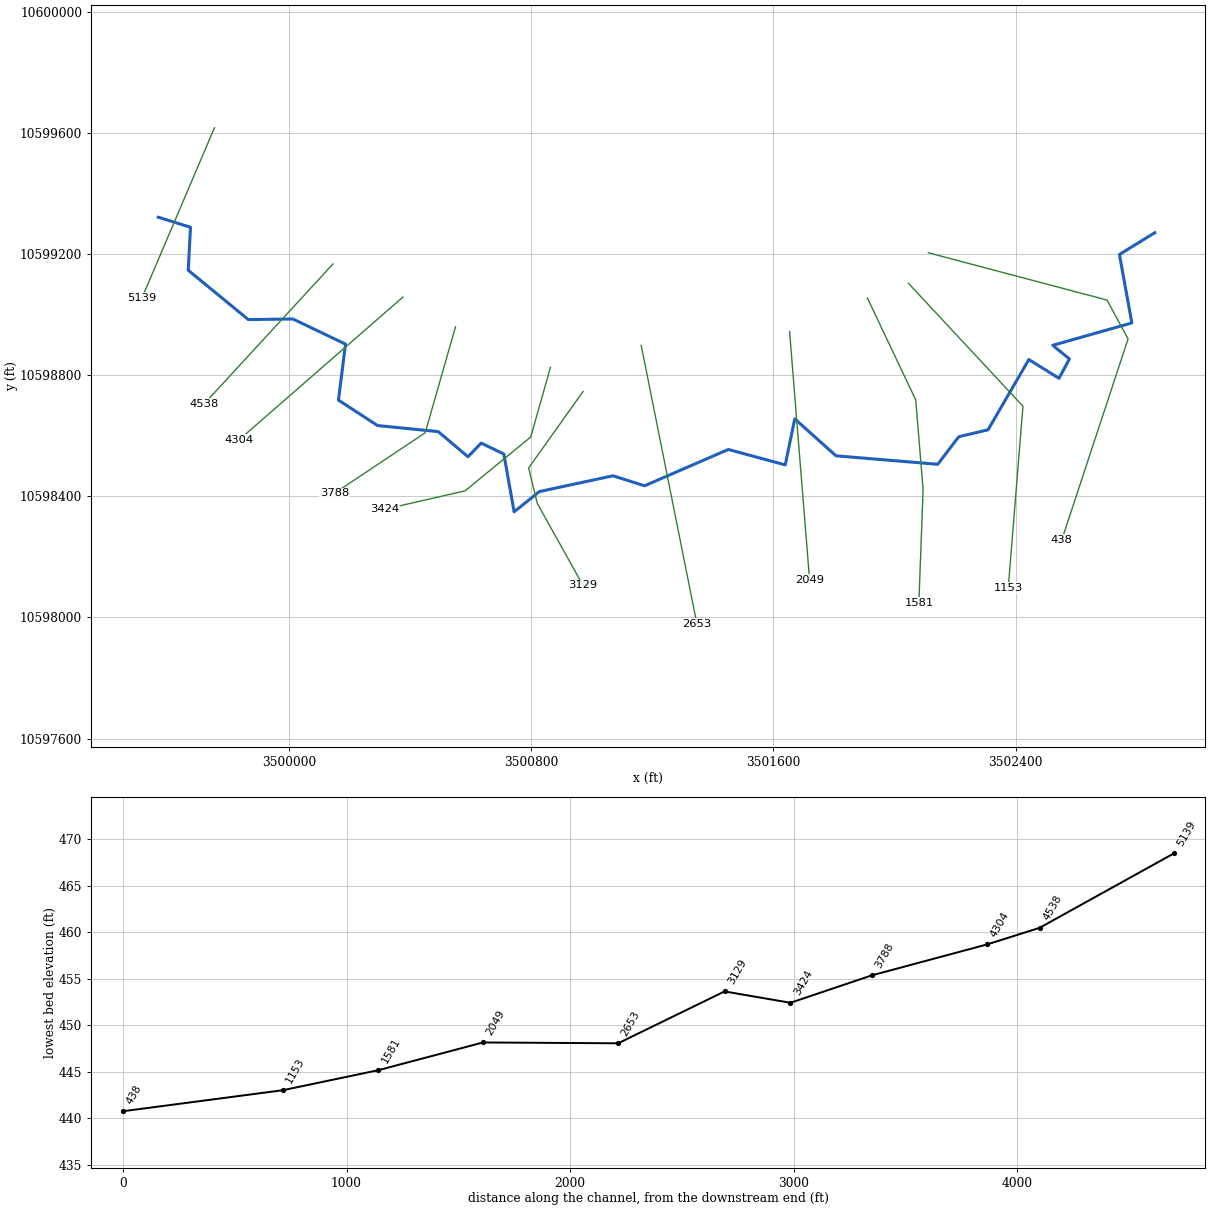
--- UNT034 IN CCTC.prj (project) ---

Proj Title=UNT034 IN CCTC Base Level Engineering
Current Plan=p01
Default Exp/Contr=0.3,0.1
English Units
Geom File=g01
Flow File=f01
Plan File=p01
BEGIN DESCRIPTION:
UNT034 IN CCTC
END DESCRIPTION:

--- UNT034 IN CCTC.p01 (plan) ---

Plan Title=Multiple Run
Short Identifier=Multiple
Geom File=g01
Flow File=f01
Subcritical Flow
K Sum by GR= 0
Std Step Tol= 0.01
Critical Tol= 0.01
Num of Std Step Trials= 20
Max Error Tol= 0.3
Flow Tol Ratio= 0.001
Split Flow NTrial= 30
Split Flow Tol= 0.02
Split Flow Ratio= 0.02
Log Output Level= 0
Friction Slope Method= 1
Unsteady Friction Slope Method= 2
Unsteady Bridges Friction Slope Method= 1
Parabolic Critical Depth
Global Vel Dist=  1 , 1 , 1
Global Log Level= 0
CheckData=True
Encroach Param= -1, 0, 0, 0
BEGIN DESCRIPTION:
Multiple Run
END DESCRIPTION:

--- UNT034 IN CCTC.f01 (steady flow) ---

Flow Title=Multiple
Number of Profiles=7
Profile Names=10-year,25-year,50-year,1pct_min,100-year,1pct_plu,500-year
River Rch & RM= UNT034 IN CCTC,Reach-1,5139
     761    1019    1227    1082    1463    1979    2069
River Rch & RM= UNT034 IN CCTC,Reach-1,3129
    1364    1892    2331    2097    2836    3835    4185
Boundary for River Rch & Prof#=UNT034 IN CCTC,Reach-1,1
Up Type=0
Dn Type=3
Dn Slope=0.005
Boundary for River Rch & Prof#=UNT034 IN CCTC,Reach-1,2
Up Type=0
Dn Type=3
Dn Slope=0.005
Boundary for River Rch & Prof#=UNT034 IN CCTC,Reach-1,3
Up Type=0
Dn Type=3
Dn Slope=0.005
Boundary for River Rch & Prof#=UNT034 IN CCTC,Reach-1,4
Up Type=0
Dn Type=3
Dn Slope=0.005
Boundary for River Rch & Prof#=UNT034 IN CCTC,Reach-1,5
Up Type=0
Dn Type=3
Dn Slope=0.005
Boundary for River Rch & Prof#=UNT034 IN CCTC,Reach-1,6
Up Type=0
Dn Type=3
Dn Slope=0.005
Boundary for River Rch & Prof#=UNT034 IN CCTC,Reach-1,7
Up Type=0
Dn Type=3
Dn Slope=0.005

--- UNT034 IN CCTC.g01 (geometry) ---

Geom Title=Existing Conditions

River Reach=UNT034 IN CCTC,Reach-1
Reach XY= 30
      3499567.96     10599322.06      3499674.25     10599289.00
      3499666.75     10599147.00      3499865.25     10598984.00
      3500012.50     10598986.00      3500186.25     10598903.00
      3500163.00     10598718.00      3500292.00     10598634.00
      3500492.50     10598614.00      3500590.75     10598531.00
      3500634.50     10598576.00      3500709.25     10598540.00
      3500743.25     10598349.00      3500826.75     10598416.00
      3501069.75     10598468.00      3501174.25     10598435.00
      3501450.75     10598555.00      3501638.75     10598504.00
      3501670.25     10598656.00      3501806.50     10598534.00
      3502142.50     10598506.00      3502212.00     10598597.00
      3502308.75     10598620.00      3502443.50     10598852.00
      3502543.25     10598790.00      3502577.50     10598854.00
      3502522.50     10598899.00      3502783.75     10598973.00
      3502742.75     10599199.00      3502859.50     10599271.00

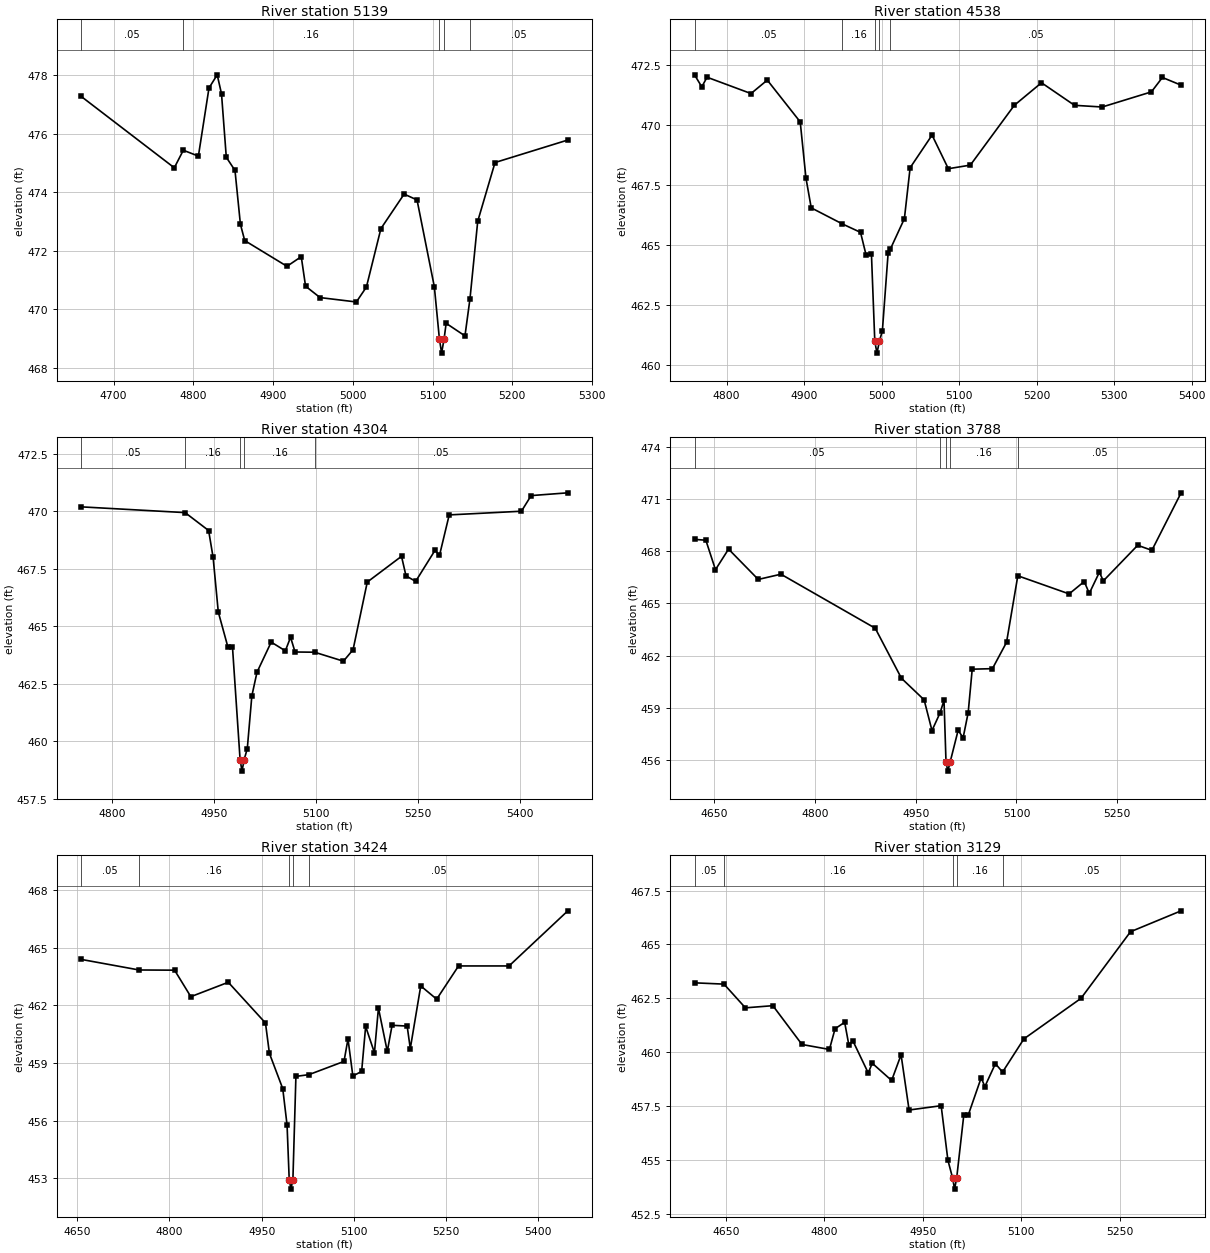
Type RM Length L Ch R = 1,5139,601,601,601
BEGIN DESCRIPTION:
UNT034 IN CCTC 8.0
END DESCRIPTION:
XS GIS Cut Line= 2
      3499753.32     10599617.58      3499514.21     10599056.18
#Sta/Elev= 30
  4659.5  477.28  4776.2  474.84  4787.5  475.44  4806.4  475.24  4819.7  477.57
  4830.0  478.02  4835.4  477.37  4841.4  475.20  4852.3  474.75  4859.1  472.91
  4864.5  472.35  4917.5  471.47  4935.4  471.80  4940.8  470.79  4959.0  470.40
  5004.5  470.25  5017.1  470.76  5035.3  472.76  5064.4  473.94  5080.6  473.74
  5102.3  470.77  5108.6  469.00  5111.4  468.50  5114.6  469.00  5117.1  469.52
  5140.7  469.09  5147.0  470.36  5156.7  473.01  5178.4  475.02  5269.7  475.79
#Mann=5,-1,0
  4659.5    0.05       0  4787.5    0.16       0  5108.6    0.07       0
  5114.6    0.16       0  5147.0    0.05       0
Bank Sta=5108.6,5114.6
Exp/Cntr=0.3,0.1

Type RM Length L Ch R = 1,4538,234,234,234
BEGIN DESCRIPTION:
Mapping XS ba8ff8e8
END DESCRIPTION:
XS GIS Cut Line= 2
      3500144.96     10599167.75      3499719.64     10598705.98
#Sta/Elev= 30
  4758.7  472.08  4768.1  471.58  4774.9  471.98  4831.6  471.30  4852.6  471.86
  4895.1  470.12  4902.5  467.78  4909.3  466.54  4949.5  465.87  4972.9  465.52
  4980.2  464.56  4987.0  464.61  4991.3  460.99  4994.1  460.49  4997.3  460.99
  5001.1  461.42  5008.5  464.65  5011.5  464.83  5029.5  466.09  5036.9  468.21
  5065.2  469.57  5086.2  468.17  5114.6  468.32  5171.3  470.81  5206.4  471.75
  5249.0  470.81  5284.7  470.74  5348.2  471.37  5362.4  471.97  5386.5  471.65
#Mann=5,-1,0
  4758.7    0.05       0  4949.5    0.16       0  4991.3    0.07       0
  4997.3    0.16       0  5011.5    0.05       0
Bank Sta=4991.3,4997.3
Exp/Cntr=0.3,0.1

Type RM Length L Ch R = 1,4304,516,516,516
BEGIN DESCRIPTION:
UNT034 IN CCTC 7.0
END DESCRIPTION:
XS GIS Cut Line= 2
      3500375.90     10599058.40      3499835.93     10598587.89
#Sta/Elev= 30
  4754.5  470.20  4907.4  469.95  4942.0  469.17  4948.6  468.00  4956.2  465.63
  4970.5  464.09  4977.1  464.11  4988.3  459.21  4991.1  458.71  4994.3  459.21
  4998.9  459.69  5005.6  461.98  5013.2  463.01  5034.1  464.32  5054.9  463.94
  5062.6  464.53  5069.2  463.89  5098.0  463.88  5140.4  463.49  5154.6  463.99
  5175.5  466.93  5225.9  468.05  5232.5  467.20  5246.7  466.96  5275.2  468.31
  5281.8  468.09  5296.1  469.85  5402.4  470.01  5416.7  470.69  5470.7  470.81
#Mann=5,-1,0
  4754.5    0.05       0  4907.4    0.16       0  4988.3    0.07       0
  4994.3    0.16       0  5098.0    0.05       0
Bank Sta=4988.3,4994.3
Exp/Cntr=0.3,0.1

Type RM Length L Ch R = 1,3788,364,364,364
BEGIN DESCRIPTION:
UNT034 IN CCTC 6.0
END DESCRIPTION:
XS GIS Cut Line= 3
      3500549.60     10598960.15      3500449.61     10598610.19
      3500149.63     10598410.20
#Sta/Elev= 30
  4620.6  468.68  4637.5  468.63  4651.8  466.94  4671.3  468.12  4715.5  466.38
  4749.3  466.68  4889.7  463.58  4928.7  460.71  4962.5  459.47  4974.2  457.71
  4986.2  458.72  4992.1  459.44  4995.1  455.88  4997.8  455.38  5001.1  455.88
  5013.1  457.72  5020.6  457.30  5028.1  458.74  5034.1  461.23  5064.2  461.26
  5085.2  462.77  5102.0  466.59  5178.4  465.55  5200.9  466.26  5208.4  465.58
  5223.4  466.79  5229.4  466.30  5280.5  468.34  5301.6  468.05  5345.1  471.35
#Mann=5,-1,0
  4620.6    0.05       0  4986.2    0.16       0  4995.1    0.07       0
  5001.1    0.16       0  5102.0    0.05       0
Bank Sta=4995.1,5001.1
Exp/Cntr=0.3,0.1

Type RM Length L Ch R = 1,3424,295,295,295
BEGIN DESCRIPTION:
UNT034 IN CCTC 5.0
END DESCRIPTION:
XS GIS Cut Line= 4
      3500863.27     10598826.25      3500798.17     10598596.23
      3500581.15     10598418.28      3500316.43     10598357.53
#Sta/Elev= 30
  4656.5  464.39  4750.6  463.84  4808.3  463.83  4834.7  462.45  4895.6  463.20
  4956.1  461.08  4962.5  459.50  4984.2  457.66  4991.2  455.77  4994.7  452.93
  4997.5  452.43  5000.7  452.93  5005.6  458.30  5026.7  458.39  5083.8  459.08
  5090.3  460.25  5098.2  458.32  5112.5  458.56  5119.0  460.90  5133.3  459.53
  5139.8  461.86  5154.2  459.60  5162.0  460.96  5186.5  460.92  5191.6  459.75
  5208.6  463.01  5234.5  462.32  5270.1  464.05  5352.2  464.05  5447.8  466.92
#Mann=5,-1,0
  4656.5    0.05       0  4750.6    0.16       0  4994.7    0.07       0
  5000.7    0.16       0  5026.7    0.05       0
Bank Sta=4994.7,5000.7
Exp/Cntr=0.3,0.1

Type RM Length L Ch R = 1,3129,476,476,476
BEGIN DESCRIPTION:
UNT034 IN CCTC 4.0
END DESCRIPTION:
XS GIS Cut Line= 4
      3500970.93     10598746.44      3500791.22     10598493.80
      3500819.87     10598376.62      3500970.92     10598105.76
#Sta/Elev= 30
  4602.3  463.22  4647.2  463.16  4679.8  462.06  4721.6  462.16  4765.9  460.36
  4807.7  460.13  4816.3  461.09  4830.9  461.39  4837.2  460.35  4843.4  460.53
  4866.8  459.04  4872.9  459.49  4902.4  458.69  4916.8  459.88  4929.0  457.32
  4977.8  457.52  4988.1  454.99  4995.4  454.15  4998.2  453.65  5001.4  454.15
  5012.3  457.09  5019.0  457.08  5038.7  458.81  5044.4  458.41  5060.4  459.47
  5071.3  459.08  5103.8  460.62  5190.7  462.50  5266.1  465.59  5343.1  466.56
#Mann=5,-1,0
  4602.3    0.05       0  4647.2    0.16       0  4995.4    0.07       0
  5001.4    0.16       0  5071.3    0.05       0
Bank Sta=4995.4,5001.4
Exp/Cntr=0.3,0.1

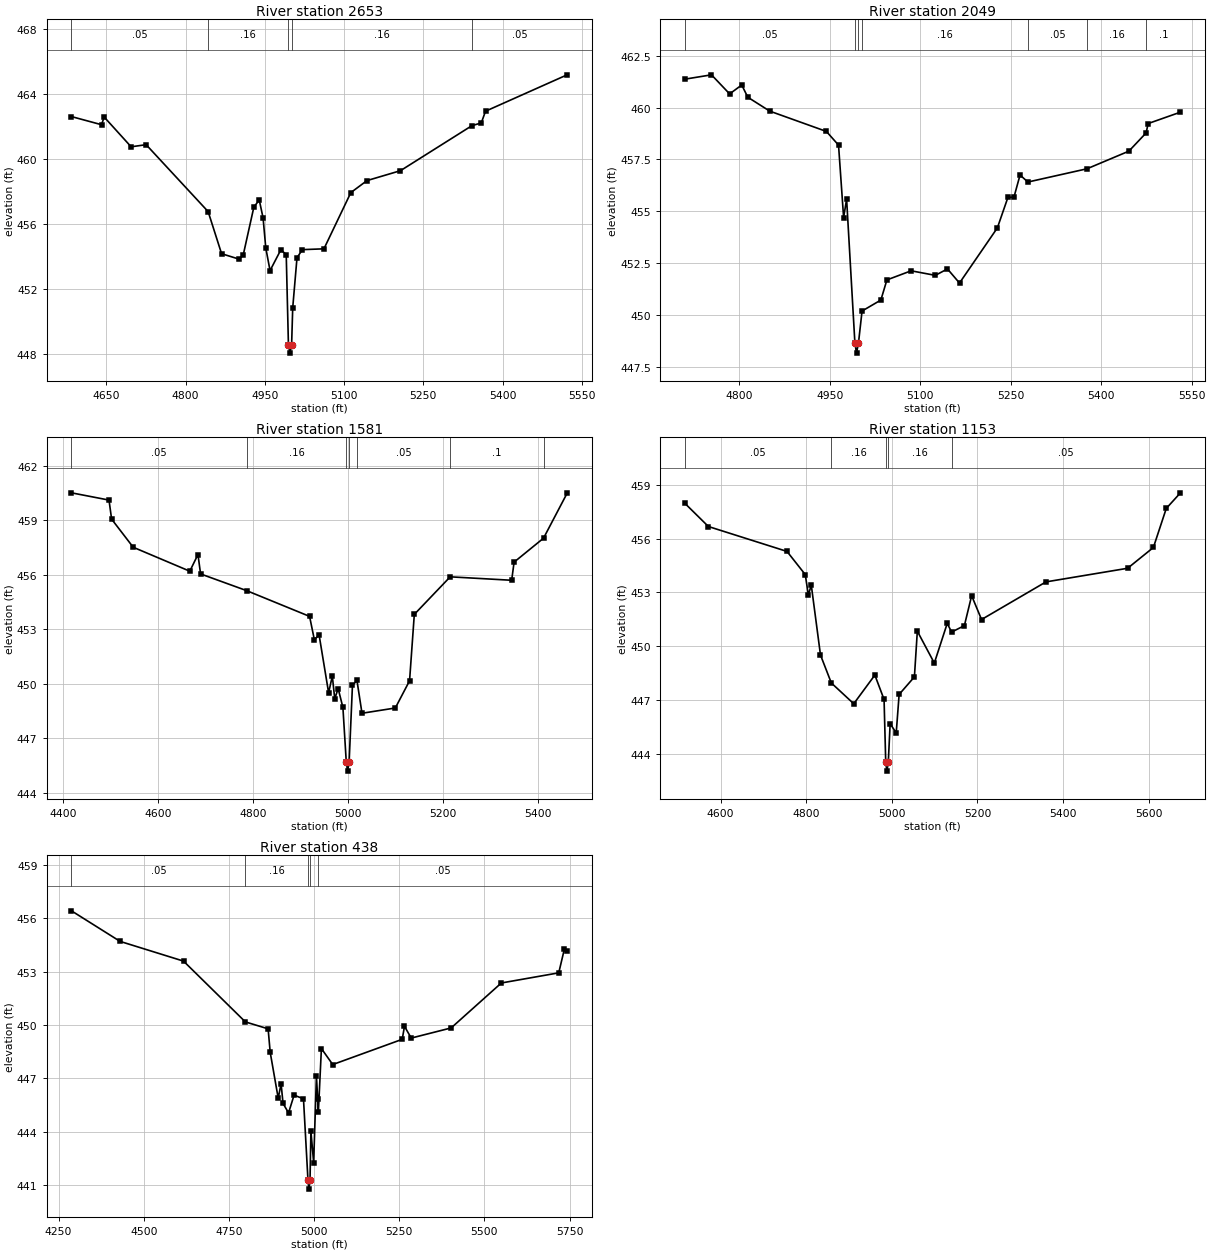
Type RM Length L Ch R = 1,2653,604,604,604
BEGIN DESCRIPTION:
UNT034 IN CCTC 3.0
END DESCRIPTION:
XS GIS Cut Line= 2
      3501163.03     10598898.87      3501347.07     10597978.69
#Sta/Elev= 30
  4583.9  462.63  4640.8  462.13  4645.9  462.60  4696.9  460.77  4725.3  460.90
  4842.7  456.78  4868.1  454.19  4900.8  453.86  4908.9  454.08  4929.3  457.07
  4939.5  457.49  4946.7  456.39  4951.8  454.54  4959.9  453.15  4980.3  454.43
  4990.5  454.14  4994.7  448.57  4997.5  448.07  5000.7  448.57  5002.8  450.86
  5010.9  453.94  5021.1  454.44  5061.9  454.49  5112.8  457.95  5143.4  458.69
  5206.8  459.30  5342.0  462.07  5359.8  462.24  5367.8  462.96  5522.3  465.20
#Mann=5,-1,0
  4583.9    0.05       0  4842.7    0.16       0  4994.7    0.07       0
  5000.7    0.16       0  5342.0    0.05       0
Bank Sta=4994.7,5000.7
Exp/Cntr=0.3,0.1

Type RM Length L Ch R = 1,2049,468,468,468
BEGIN DESCRIPTION:
UNT034 IN CCTC 2.0
END DESCRIPTION:
XS GIS Cut Line= 2
      3501653.20     10598944.35      3501719.16     10598125.00
#Sta/Elev= 30
  4709.5  461.37  4753.8  461.58  4783.9  460.66  4804.0  461.09  4814.0  460.50
  4850.4  459.83  4944.4  458.85  4964.5  458.19  4972.9  454.70  4977.9  455.58
  4991.6  448.66  4994.3  448.16  4997.6  448.66  5003.5  450.19  5034.7  450.72
  5044.7  451.69  5084.9  452.13  5125.0  451.91  5145.1  452.22  5165.1  451.54
  5227.9  454.20  5245.4  455.67  5255.4  455.68  5265.5  456.75  5278.5  456.41
  5376.6  457.05  5446.0  457.90  5474.6  458.78  5477.9  459.23  5531.5  459.78
#Mann=7,-1,0
  4709.5    0.05       0  4991.6   0.035       0  4997.6    0.05       0
  5003.5    0.16       0  5278.5    0.05       0  5376.6    0.16       0
  5474.6     0.1       0
Bank Sta=4991.6,4997.6
Exp/Cntr=0.3,0.1

Type RM Length L Ch R = 1,1581,428,428,428
BEGIN DESCRIPTION:
Mapping XS 5365b5df
END DESCRIPTION:
XS GIS Cut Line= 4
      3501910.16     10599055.41      3502069.87     10598718.63
      3502094.17     10598423.49      3502080.29     10598048.52
#Sta/Elev= 30
  4417.4  460.52  4496.5  460.12  4502.0  459.07  4547.5  457.52  4666.7  456.20
  4683.9  457.12  4689.4  456.05  4786.3  455.13  4919.0  453.71  4929.0  452.43
  4939.1  452.68  4959.1  449.50  4966.9  450.42  4972.0  449.17  4979.2  449.73
  4989.2  448.69  4996.3  445.68  4999.0  445.18  5002.3  445.68  5009.3  449.90
  5018.8  450.18  5029.4  448.37  5099.6  448.66  5129.6  450.16  5139.6  453.82
  5215.2  455.89  5344.7  455.70  5349.8  456.70  5411.8  458.02  5461.5  460.50
#Mann=7,-1,0
  4417.4    0.05       0  4786.3    0.16       0  4996.3    0.07       0
  5002.3    0.16       0  5018.8    0.05       0  5215.2     0.1       0
  5411.8    0.05       0
Bank Sta=4996.3,5002.3
Exp/Cntr=0.3,0.1

Type RM Length L Ch R = 1,1153,715,715,715
BEGIN DESCRIPTION:
Mapping XS f13f49bb
END DESCRIPTION:
XS GIS Cut Line= 3
      3502045.59     10599104.02      3502424.03     10598697.80
      3502375.43     10598097.15
#Sta/Elev= 30
  4516.5  457.97  4571.7  456.67  4755.3  455.28  4797.9  453.99  4805.2  452.85
  4812.0  453.40  4833.5  449.50  4858.8  447.94  4911.2  446.78  4960.5  448.38
  4982.0  447.02  4985.9  443.52  4988.6  443.02  4991.9  443.52  4996.2  445.67
  5010.4  445.15  5017.2  447.30  5052.9  448.28  5059.7  450.83  5099.4  449.05
  5129.5  451.26  5139.9  450.78  5169.6  451.14  5186.6  452.81  5209.7  451.48
  5360.2  453.58  5550.9  454.34  5611.1  455.50  5641.2  457.68  5674.3  458.55
#Mann=5,-1,0
  4516.5    0.05       0  4858.8    0.16       0  4985.9    0.07       0
  4991.9    0.16       0  5139.9    0.05       0
Bank Sta=4985.9,4991.9
Exp/Cntr=0.3,0.1

Type RM Length L Ch R = 1,438,0,0,0
BEGIN DESCRIPTION:
UNT034 IN CCTC 1.0
END DESCRIPTION:
XS GIS Cut Line= 4
      3502111.54     10599204.74      3502701.81     10599048.49
      3502771.26     10598920.02      3502552.50     10598256.81
#Sta/Elev= 30
  4287.9  456.42  4430.7  454.70  4616.9  453.59  4798.4  450.17  4865.2  449.78
  4871.3  448.46  4894.8  445.88  4903.3  446.69  4909.0  445.58  4925.2  445.05
  4941.4  446.05  4969.0  445.84  4982.2  441.26  4984.9  440.76  4988.2  441.26
  4990.8  444.02  4998.9  442.25  5007.0  447.13  5010.7  445.81  5012.7  445.10
  5021.6  448.67  5054.9  447.77  5258.8  449.19  5265.5  449.92  5285.3  449.26
  5402.4  449.83  5549.8  452.36  5718.3  452.93  5735.1  454.29  5742.9  454.16
#Mann=5,-1,0
  4287.9    0.05       0  4798.4    0.16       0  4982.2    0.07       0
  4988.2    0.16       0  5010.7    0.05       0
Bank Sta=4982.2,4988.2
Exp/Cntr=0.3,0.1

Chan Stop Cuts=-1