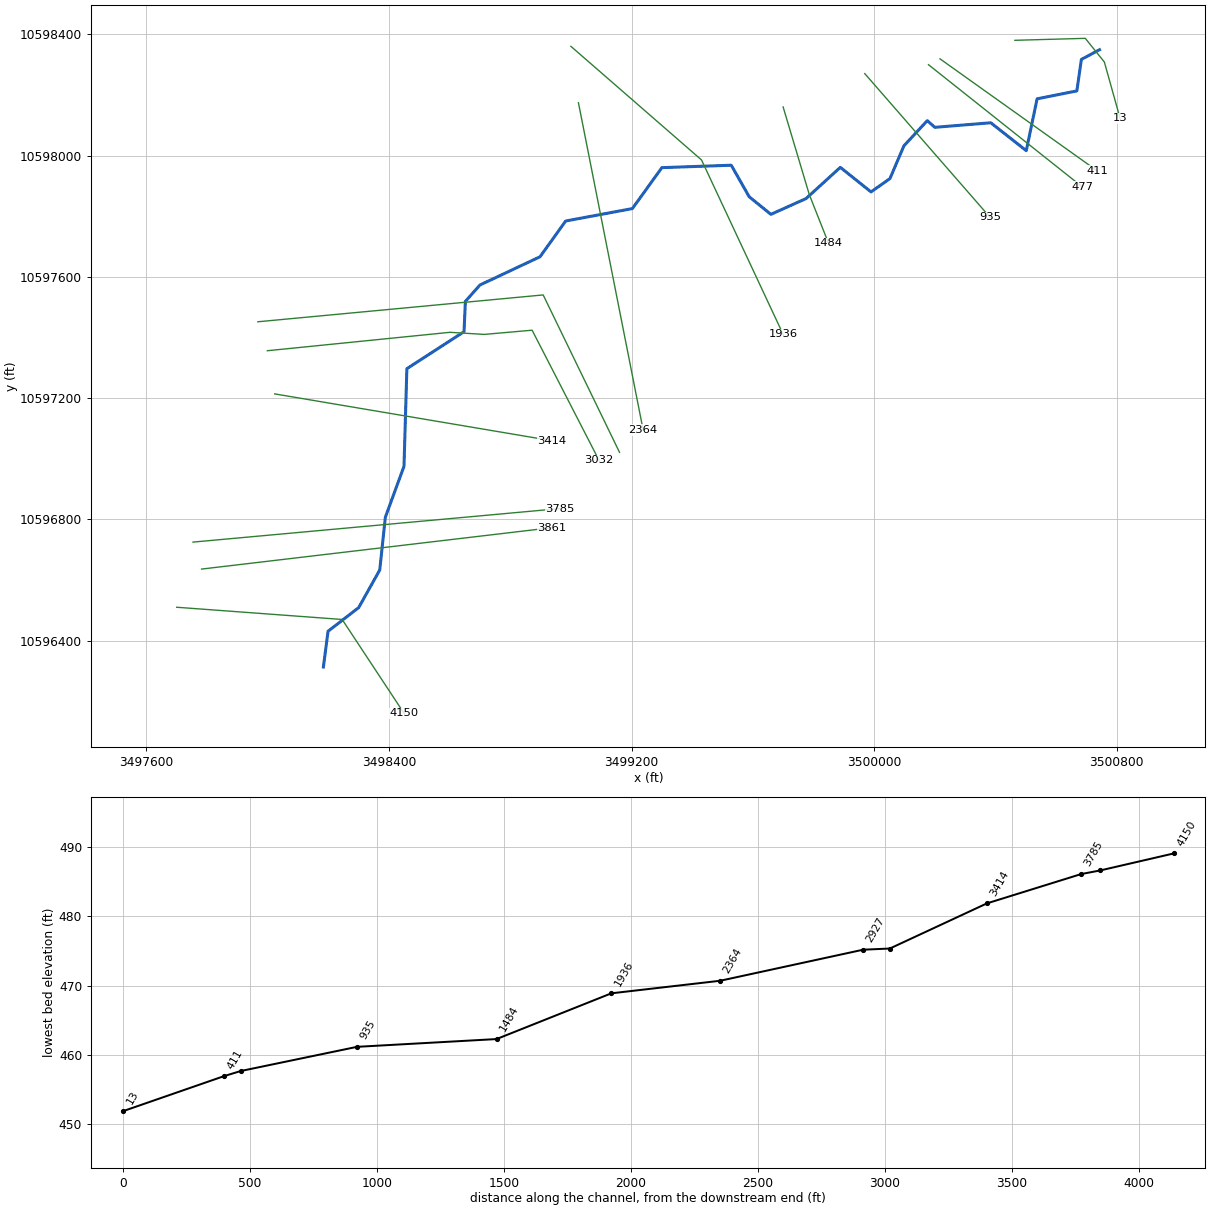
--- UNT035 IN CCTC.prj (project) ---

Proj Title=UNT035 IN CCTC Base Level Engineering
Current Plan=p01
Default Exp/Contr=0.3,0.1
English Units
Geom File=g01
Flow File=f01
Plan File=p01
Y Axis Title=Elevation
X Axis Title(PF)=Main Channel Distance
X Axis Title(XS)=Station
BEGIN DESCRIPTION:
UNT035 IN CCTC
END DESCRIPTION:
DSS Export Rating Curves= 0
DSS Export Rating Curve Sorted= 0
DSS Export Volume Flow Curves= 0
DXF OffsetX= 0
DXF OffsetY= 0
DXF ScaleX= 1
DXF ScaleY= 10

--- UNT035 IN CCTC.p01 (plan) ---

Plan Title=Multiple Run
Short Identifier=Multiple
Geom File=g01
Flow File=f01
Subcritical Flow
K Sum by GR= 0
Std Step Tol= 0.01
Critical Tol= 0.01
Num of Std Step Trials= 20
Max Error Tol= 0.3
Flow Tol Ratio= 0.001
Split Flow NTrial= 30
Split Flow Tol= 0.02
Split Flow Ratio= 0.02
Log Output Level= 0
Friction Slope Method= 1
Unsteady Friction Slope Method= 2
Unsteady Bridges Friction Slope Method= 1
Parabolic Critical Depth
Global Vel Dist=  1 , 1 , 1
Global Log Level= 0
CheckData=True
Encroach Param= -1, 0, 0, 0
BEGIN DESCRIPTION:
Multiple Run
END DESCRIPTION:

--- UNT035 IN CCTC.f01 (steady flow) ---

Flow Title=Multiple
Number of Profiles=7
Profile Names=10-year,25-year,50-year,1pct_min,100-year,1pct_plu,500-year
River Rch & RM= UNT035 IN CCTC,Reach-1,4150
     493     637     749     645     872    1180    1177
Boundary for River Rch & Prof#=UNT035 IN CCTC,Reach-1,1
Up Type=0
Dn Type=3
Dn Slope=0.005
Boundary for River Rch & Prof#=UNT035 IN CCTC,Reach-1,2
Up Type=0
Dn Type=3
Dn Slope=0.005
Boundary for River Rch & Prof#=UNT035 IN CCTC,Reach-1,3
Up Type=0
Dn Type=3
Dn Slope=0.005
Boundary for River Rch & Prof#=UNT035 IN CCTC,Reach-1,4
Up Type=0
Dn Type=3
Dn Slope=0.005
Boundary for River Rch & Prof#=UNT035 IN CCTC,Reach-1,5
Up Type=0
Dn Type=3
Dn Slope=0.005
Boundary for River Rch & Prof#=UNT035 IN CCTC,Reach-1,6
Up Type=0
Dn Type=3
Dn Slope=0.005
Boundary for River Rch & Prof#=UNT035 IN CCTC,Reach-1,7
Up Type=0
Dn Type=3
Dn Slope=0.005

--- UNT035 IN CCTC.g01 (geometry) ---

Geom Title=Existing Conditions

River Reach=UNT035 IN CCTC,Reach-1
Reach XY= 30
      3498183.40     10596312.98      3498198.75     10596431.00
      3498299.75     10596509.00      3498369.25     10596633.00
      3498387.75     10596807.00      3498449.25     10596975.00
      3498458.75     10597297.00      3498647.25     10597419.00
      3498651.75     10597519.00      3498699.75     10597573.00
      3498897.75     10597666.00      3498982.50     10597784.00
      3499202.50     10597825.00      3499299.75     10597960.00
      3499528.50     10597968.00      3499587.75     10597864.00
      3499659.25     10597806.00      3499775.25     10597858.00
      3499888.25     10597961.00      3499989.50     10597880.00
      3500052.00     10597924.00      3500098.00     10598032.00
      3500175.00     10598115.00      3500200.00     10598093.00
      3500384.50     10598108.00      3500501.50     10598016.00
      3500537.25     10598187.00      3500668.25     10598213.00
      3500683.25     10598317.00      3500743.25     10598349.00

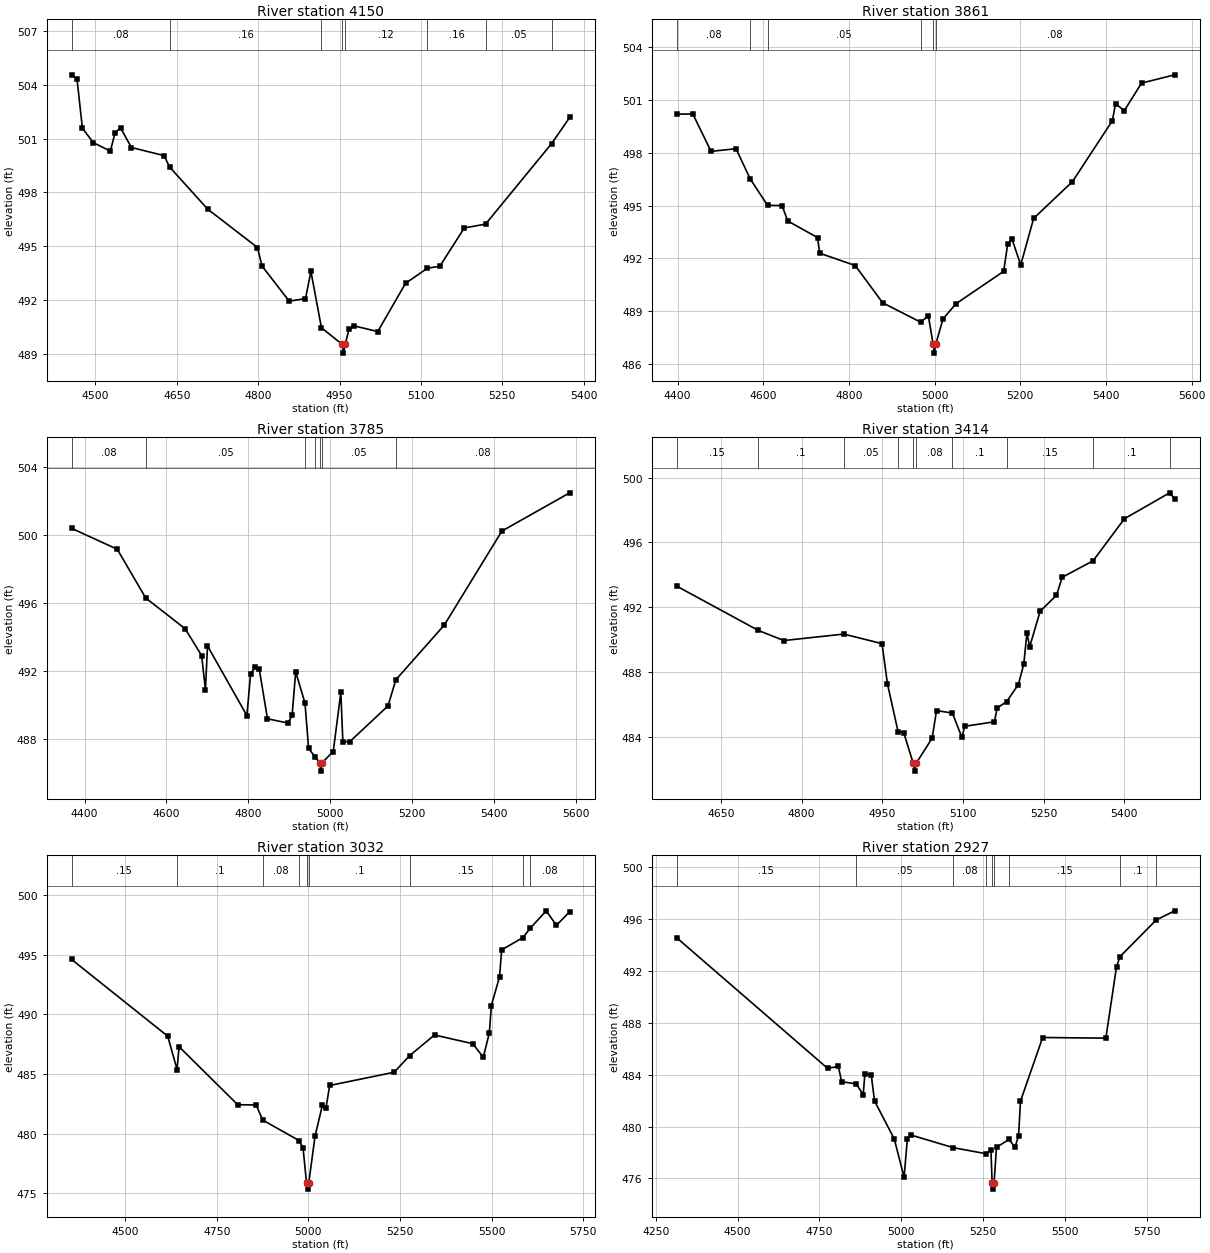
Type RM Length L Ch R = 1,4150,289,289,289
BEGIN DESCRIPTION:
UNT035 IN CCTC 8.0
END DESCRIPTION:
XS GIS Cut Line= 3
      3497699.62     10596510.19      3498245.32     10596469.89
      3498449.61     10596160.19
#Sta/Elev= 30
  4456.1  504.54  4466.1  504.31  4476.1  501.57  4496.2  500.77  4527.6  500.30
  4536.3  501.32  4546.3  501.60  4566.4  500.50  4626.6  500.05  4636.7  499.42
  4706.8  497.08  4798.8  494.94  4807.0  493.92  4857.2  491.96  4887.3  492.10
  4897.3  493.61  4916.7  490.48  4954.5  489.57  4957.2  489.07  4960.5  489.57
  4967.5  490.39  4977.5  490.58  5020.5  490.27  5071.7  492.95  5112.0  493.79
  5134.9  493.90  5180.1  496.03  5219.2  496.24  5341.0  500.72  5374.3  502.17
#Mann=8,-1,0
  4456.1    0.08       0  4636.7    0.16       0  4916.7    0.12       0
  4954.5    0.07       0  4960.5    0.12       0  5112.0    0.16       0
  5219.2    0.05       0  5341.0     0.1       0
Bank Sta=4954.5,4960.5
Exp/Cntr=0.3,0.1

Type RM Length L Ch R = 1,3861,76,76,76
BEGIN DESCRIPTION:
Mapping XS 3076eb29
END DESCRIPTION:
XS GIS Cut Line= 2
      3497781.66     10596636.08      3498936.42     10596772.57
#Sta/Elev= 30
  4397.5  500.21  4435.7  500.21  4478.1  498.09  4536.4  498.24  4569.4  496.53
  4610.0  495.02  4643.8  495.01  4657.2  494.13  4726.7  493.19  4731.7  492.30
  4814.6  491.60  4878.8  489.48  4967.5  488.38  4985.4  488.74  4996.6  487.12
  4999.4  486.62  5002.6  487.12  5019.7  488.57  5050.0  489.43  5161.2  491.27
  5170.8  492.85  5180.9  493.09  5201.0  491.63  5231.2  494.28  5321.8  496.37
  5414.9  499.83  5422.5  500.80  5442.7  500.40  5483.0  501.97  5560.3  502.44
#Mann=6,-1,0
  4397.5    0.08       0  4569.4    0.16       0  4610.0    0.05       0
  4967.5    0.08       0  4996.6    0.07       0  5002.6    0.08       0
Bank Sta=4996.6,5002.6
Exp/Cntr=0.3,0.1

Type RM Length L Ch R = 1,3785,371,371,371
BEGIN DESCRIPTION:
UNT035 IN CCTC 7.0
END DESCRIPTION:
XS GIS Cut Line= 2
      3497753.43     10596725.05      3498964.39     10596835.73
#Sta/Elev= 30
  4368.3  500.38  4479.8  499.15  4549.3  496.28  4645.6  494.47  4685.8  492.89
  4695.1  490.88  4700.1  493.46  4796.3  489.36  4805.3  491.80  4816.3  492.22
  4826.4  492.11  4846.5  489.17  4896.7  488.92  4906.7  489.37  4915.4  491.93
  4938.1  490.10  4946.9  487.44  4962.1  486.94  4974.0  486.59  4976.8  486.09
  4980.0  486.59  5007.1  487.24  5025.6  490.72  5030.6  487.83  5047.3  487.82
  5140.8  489.93  5160.0  491.47  5278.3  494.69  5418.8  500.22  5584.3  502.47
#Mann=7,-1,0
  4368.3    0.08       0  4549.3    0.05       0  4938.1     0.1       0
  4962.1    0.05       0  4974.0    0.04       0  4980.0    0.05       0
  5160.0    0.08       0
Bank Sta=4974,4980
Exp/Cntr=0.3,0.1

Type RM Length L Ch R = 1,3414,382,382,382
BEGIN DESCRIPTION:
UNT035 IN CCTC 6.0
END DESCRIPTION:
XS GIS Cut Line= 2
      3498022.83     10597213.84      3498936.20     10597059.59
#Sta/Elev= 30
  4567.4  493.30  4719.3  490.56  4767.0  489.93  4878.4  490.33  4949.5  489.74
  4959.7  487.25  4979.4  484.30  4990.1  484.23  5007.4  482.36  5010.1  481.86
  5013.4  482.36  5042.8  483.90  5050.9  485.60  5080.4  485.45  5098.2  483.94
  5103.2  484.63  5158.6  484.91  5163.7  485.76  5181.4  486.16  5203.1  487.21
  5213.2  488.48  5219.1  490.42  5224.1  489.54  5243.6  491.74  5274.0  492.73
  5284.6  493.84  5342.1  494.86  5400.4  497.46  5484.4  499.06  5493.7  498.69
#Mann=10,-1,0
  4567.4    0.15       0  4719.3     0.1       0  4878.4    0.05       0
  4979.4    0.08       0  5007.4    0.07       0  5013.4    0.08       0
  5080.4     0.1       0  5181.4    0.15       0  5342.1     0.1       0
  5484.4    0.08       0
Bank Sta=5007.4,5013.4
Exp/Cntr=0.3,0.1

Type RM Length L Ch R = 1,3032,105,105,105
BEGIN DESCRIPTION:
Mapping XS b0c6d58a
END DESCRIPTION:
XS GIS Cut Line= 5
      3497998.52     10597356.19      3498600.99     10597416.96
      3498713.84     10597410.01      3498871.82     10597423.90
      3499092.28     10596995.14
#Sta/Elev= 30
  4354.0  494.59  4616.4  488.16  4641.9  485.36  4647.3  487.28  4807.4  482.42
  4857.6  482.40  4875.7  481.13  4974.7  479.42  4985.7  478.80  4995.2  475.85
  4998.0  475.35  5001.2  475.85  5018.3  479.77  5038.3  482.36  5048.3  482.16
  5058.3  484.03  5234.2  485.14  5276.9  486.54  5344.4  488.26  5449.0  487.53
  5477.5  486.39  5494.0  488.43  5499.6  490.73  5521.8  493.13  5527.7  495.39
  5585.6  496.42  5606.1  497.22  5649.3  498.66  5677.1  497.44  5713.3  498.59
#Mann=9,-1,0
  4354.0    0.15       0  4641.9     0.1       0  4875.7    0.08       0
  4974.7     0.1       0  4995.2    0.07       0  5001.2     0.1       0
  5276.9    0.15       0  5585.6     0.1       0  5606.1    0.08       0
Bank Sta=4995.2,5001.2
Exp/Cntr=0.3,0.1

Type RM Length L Ch R = 1,2927,563,563,563
BEGIN DESCRIPTION:
UNT035 IN CCTC 5.0
END DESCRIPTION:
XS GIS Cut Line= 3
      3497967.28     10597451.68      3498908.28     10597540.22
      3499160.03     10597021.10
#Sta/Elev= 30
  4313.4  494.54  4775.3  484.47  4807.9  484.63  4817.9  483.45  4862.3  483.28
  4883.9  482.46  4888.9  484.03  4908.3  484.00  4918.4  481.97  4978.7  479.05
  5008.8  476.10  5018.8  479.06  5028.9  479.35  5159.3  478.37  5258.3  477.91
  5274.2  478.19  5277.8  475.68  5280.6  475.18  5283.8  475.68  5291.2  478.40
  5329.7  479.01  5347.5  478.39  5358.6  479.28  5364.5  481.95  5432.2  486.85
  5625.3  486.80  5657.9  492.29  5668.4  493.07  5779.0  495.89  5835.5  496.60
#Mann=9,-1,0
  4313.4    0.15       0  4862.3    0.05       0  5159.3    0.08       0
  5258.3     0.1       0  5277.8    0.04       0  5283.8     0.1       0
  5329.7    0.15       0  5668.4     0.1       0  5779.0    0.08       0
Bank Sta=5277.8,5283.8
Exp/Cntr=0.3,0.1

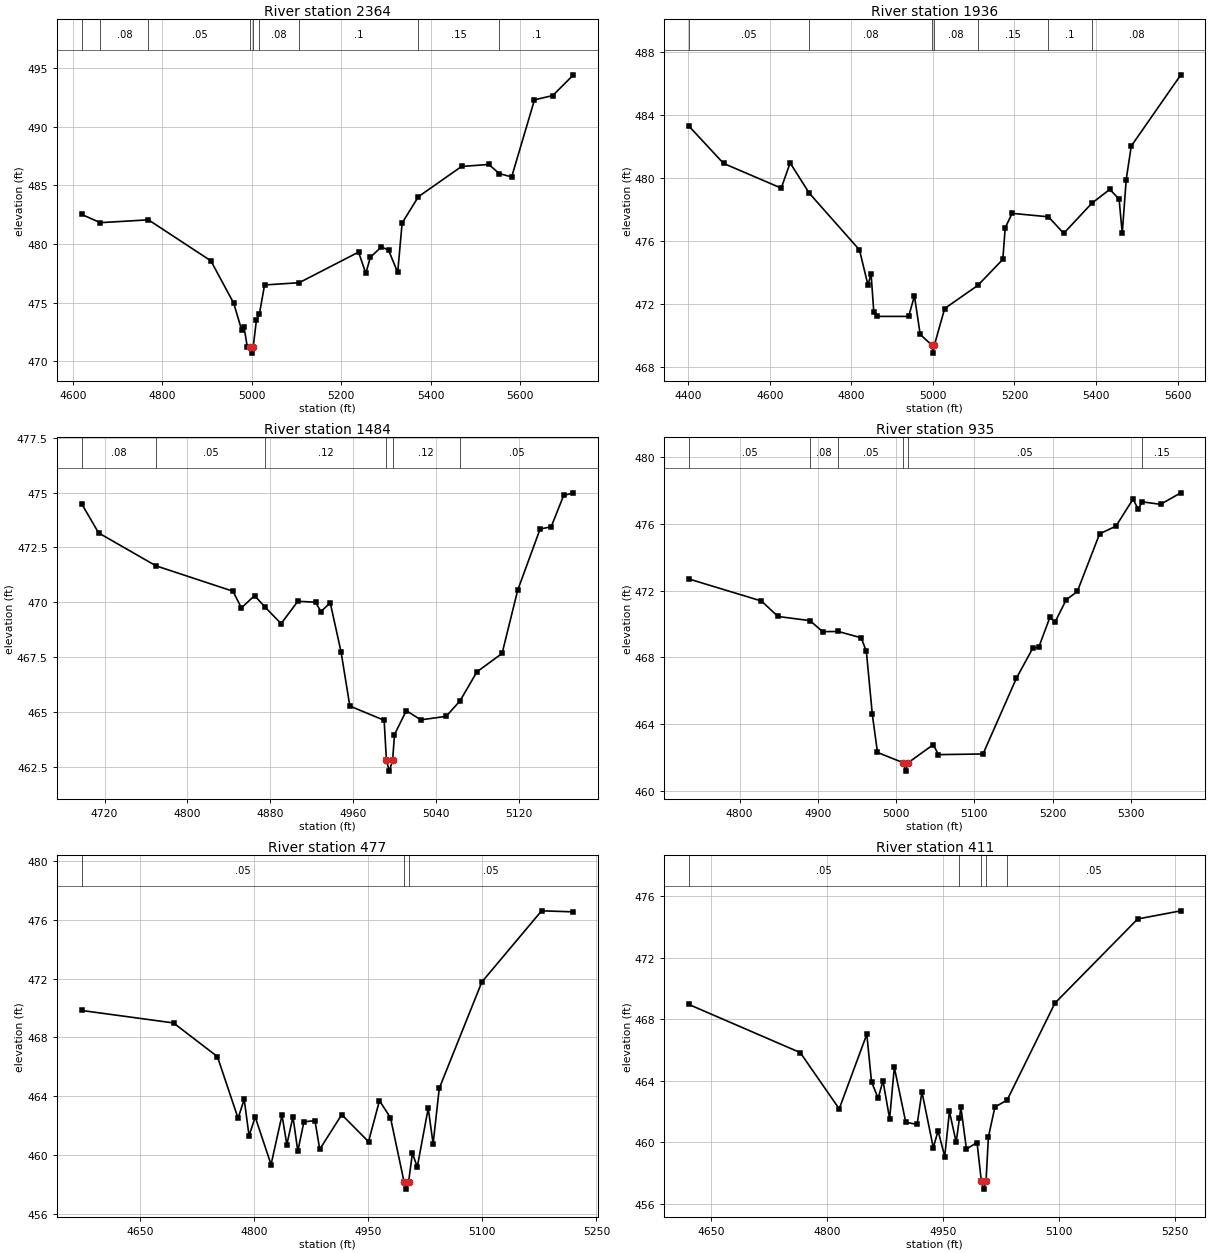
Type RM Length L Ch R = 1,2364,428,428,428
BEGIN DESCRIPTION:
UNT035 IN CCTC 4.0
END DESCRIPTION:
XS GIS Cut Line= 2
      3499024.60     10598173.90      3499238.03     10597094.60
#Sta/Elev= 30
  4619.5  482.53  4661.4  481.82  4769.2  482.06  4908.7  478.57  4959.7  474.97
  4977.7  472.66  4982.8  472.94  4990.3  471.22  4997.4  471.20  5000.2  470.70
  5003.4  471.20  5010.6  473.51  5017.1  474.00  5028.9  476.51  5106.2  476.70
  5239.1  479.31  5255.3  477.50  5265.5  478.87  5290.3  479.76  5306.3  479.46
  5326.6  477.58  5336.5  481.79  5372.8  484.03  5469.4  486.61  5530.5  486.78
  5553.8  486.00  5581.5  485.72  5632.5  492.29  5673.2  492.65  5719.7  494.42
#Mann=9,-1,0
  4619.5    0.05       0  4661.4    0.08       0  4769.2    0.05       0
  4997.4    0.04       0  5003.4    0.05       0  5017.1    0.08       0
  5106.2     0.1       0  5372.8    0.15       0  5553.8     0.1       0
Bank Sta=4997.4,5003.4
Exp/Cntr=0.3,0.1

Type RM Length L Ch R = 1,1936,452,452,452
BEGIN DESCRIPTION:
UNT035 IN CCTC 3.0
END DESCRIPTION:
XS GIS Cut Line= 3
      3498999.59     10598360.20      3499430.56     10597985.34
      3499699.63     10597410.15
#Sta/Elev= 30
  4401.8  483.30  4486.8  480.93  4628.3  479.36  4650.1  480.96  4697.0  479.04
  4820.1  475.44  4840.9  473.22  4848.6  473.91  4855.2  471.51  4862.8  471.22
  4940.7  471.22  4954.9  472.52  4969.0  470.08  4997.7  469.39  5000.4  468.89
  5003.7  469.39  5029.0  471.72  5110.4  473.19  5171.6  474.84  5177.4  476.84
  5194.4  477.76  5283.5  477.54  5320.9  476.49  5389.8  478.40  5433.9  479.28
  5456.7  478.66  5464.4  476.49  5474.1  479.90  5486.5  482.03  5608.0  486.55
#Mann=7,-1,0
  4401.8    0.05       0  4697.0    0.08       0  4997.7    0.07       0
  5003.7    0.08       0  5110.4    0.15       0  5283.5     0.1       0
  5389.8    0.08       0
Bank Sta=4997.7,5003.7
Exp/Cntr=0.3,0.1

Type RM Length L Ch R = 1,1484,549,549,549
BEGIN DESCRIPTION:
UNT035 IN CCTC 2.0
END DESCRIPTION:
XS GIS Cut Line= 3
      3499699.62     10598160.16      3499786.03     10597870.75
      3499849.60     10597710.21
#Sta/Elev= 30
  4697.8  474.50  4714.3  473.16  4769.6  471.66  4843.9  470.50  4852.1  469.74
  4864.8  470.30  4874.6  469.79  4890.4  469.02  4906.5  470.04  4923.6  470.00
  4928.8  469.57  4937.8  469.97  4948.2  467.74  4956.7  465.26  4989.8  464.61
  4992.0  462.79  4994.8  462.29  4998.0  462.79  4999.8  463.96  5011.2  465.05
  5025.2  464.63  5049.6  464.79  5063.1  465.50  5079.3  466.82  5103.6  467.66
  5118.7  470.55  5140.3  473.34  5151.0  473.44  5163.0  474.87  5172.5  474.99
#Mann=6,-1,0
  4697.8    0.08       0  4769.6    0.05       0  4874.6    0.12       0
  4992.0    0.07       0  4998.0    0.12       0  5063.1    0.05       0
Bank Sta=4992,4998
Exp/Cntr=0.3,0.1

Type RM Length L Ch R = 1,935,458,458,458
BEGIN DESCRIPTION:
Mapping XS 50f752d7
END DESCRIPTION:
XS GIS Cut Line= 2
      3499968.89     10598270.10      3500382.09     10597796.13
#Sta/Elev= 30
  4735.1  472.70  4827.8  471.38  4849.0  470.45  4890.0  470.20  4906.0  469.54
  4926.0  469.55  4955.4  469.17  4962.0  468.35  4969.6  464.57  4976.2  462.29
  5009.3  461.67  5012.1  461.17  5015.3  461.67  5047.5  462.76  5054.1  462.16
  5111.1  462.20  5153.8  466.75  5174.7  468.55  5182.3  468.60  5196.5  470.39
  5203.1  470.11  5217.4  471.45  5231.6  471.95  5260.1  475.41  5281.0  475.87
  5302.8  477.49  5309.5  476.89  5314.5  477.33  5338.0  477.18  5363.9  477.87
#Mann=6,-1,0
  4735.1    0.05       0  4890.0    0.08       0  4926.0    0.05       0
  5009.3   0.035       0  5015.3    0.05       0  5314.5    0.15       0
Bank Sta=5009.3,5015.3
Exp/Cntr=0.3,0.1

Type RM Length L Ch R = 1,477,66,66,66
BEGIN DESCRIPTION:
Mapping XS ce98eefa
END DESCRIPTION:
XS GIS Cut Line= 2
      3500178.96     10598299.61      3500685.22     10597897.38
#Sta/Elev= 30
  4573.3  469.84  4694.2  468.99  4751.9  466.70  4779.1  462.50  4787.1  463.80
  4793.5  461.31  4801.6  462.59  4822.4  459.35  4836.8  462.71  4843.2  460.71
  4851.2  462.61  4857.6  460.26  4865.6  462.26  4880.1  462.34  4886.4  460.39
  4915.3  462.75  4950.5  460.91  4964.9  463.70  4979.4  462.54  4997.2  458.18
  4999.9  457.68  5003.2  458.18  5008.2  460.12  5014.6  459.19  5029.0  463.19
  5035.4  460.76  5043.5  464.54  5099.5  471.78  5178.0  476.62  5219.9  476.55
#Mann=3,-1,0
  4573.3    0.05       0  4997.2   0.035       0  5003.2    0.05       0
Bank Sta=4997.2,5003.2
Exp/Cntr=0.3,0.1

Type RM Length L Ch R = 1,411,398,398,398
BEGIN DESCRIPTION:
Mapping XS 4dcfb55f
END DESCRIPTION:
XS GIS Cut Line= 2
      3500217.13     10598318.73      3500735.45     10597949.49
#Sta/Elev= 30
  4621.0  468.95  4765.1  465.82  4815.5  462.16  4851.2  467.01  4857.3  463.92
  4865.9  462.85  4872.1  463.99  4880.7  461.52  4886.8  464.86  4901.6  461.29
  4916.3  461.15  4922.5  463.27  4937.2  459.64  4943.4  460.73  4952.0  459.06
  4958.1  461.99  4966.8  459.99  4971.0  461.55  4972.9  462.26  4980.1  459.55
  4993.8  459.97  4999.4  457.44  5002.2  456.94  5005.4  457.44  5008.5  460.33
  5016.9  462.28  5032.7  462.73  5094.6  469.04  5201.6  474.51  5257.4  475.04
#Mann=5,-1,0
  4621.0    0.05       0  4971.0    0.16       0  4999.4    0.07       0
  5005.4    0.16       0  5032.7    0.05       0
Bank Sta=4999.4,5005.4
Exp/Cntr=0.3,0.1

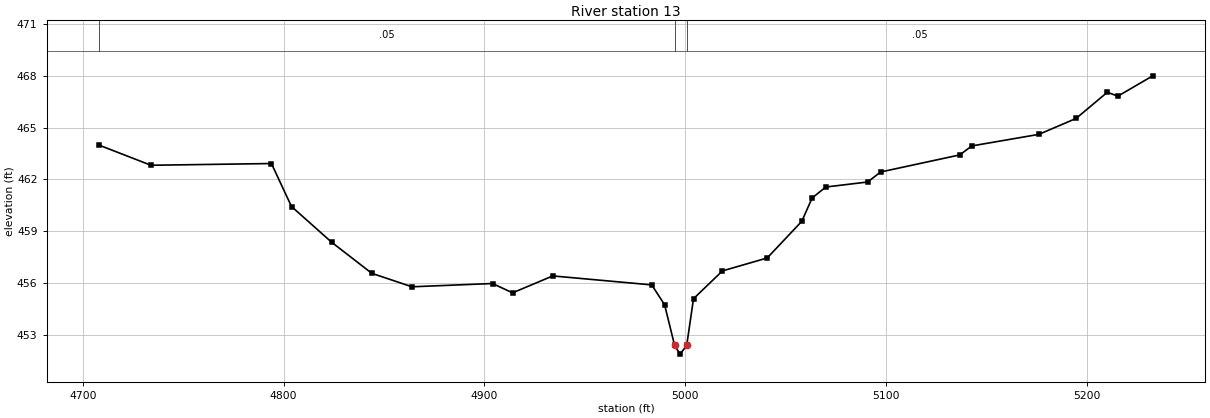
Type RM Length L Ch R = 1,13,0,0,0
BEGIN DESCRIPTION:
UNT035 IN CCTC 1.0
END DESCRIPTION:
XS GIS Cut Line= 4
      3500463.92     10598379.96      3500696.13     10598386.47
      3500759.06     10598308.34      3500810.67     10598123.43
#Sta/Elev= 30
  4708.2  463.98  4733.9  462.82  4793.9  462.92  4803.9  460.43  4823.9  458.36
  4843.9  456.56  4863.9  455.78  4904.0  455.97  4914.0  455.43  4934.0  456.41
  4983.3  455.89  4989.7  454.74  4994.7  452.38  4997.4  451.88  5000.7  452.38
  5004.1  455.09  5018.5  456.70  5040.8  457.45  5058.0  459.57  5063.2  460.93
  5070.0  461.56  5090.8  461.85  5097.3  462.43  5136.7  463.42  5142.7  463.94
  5176.1  464.61  5194.6  465.53  5210.2  467.05  5215.4  466.82  5232.8  468.00
#Mann=3,-1,0
  4708.2    0.05       0  4994.7   0.035       0  5000.7    0.05       0
Bank Sta=4994.7,5000.7
Exp/Cntr=0.3,0.1

Chan Stop Cuts=-1