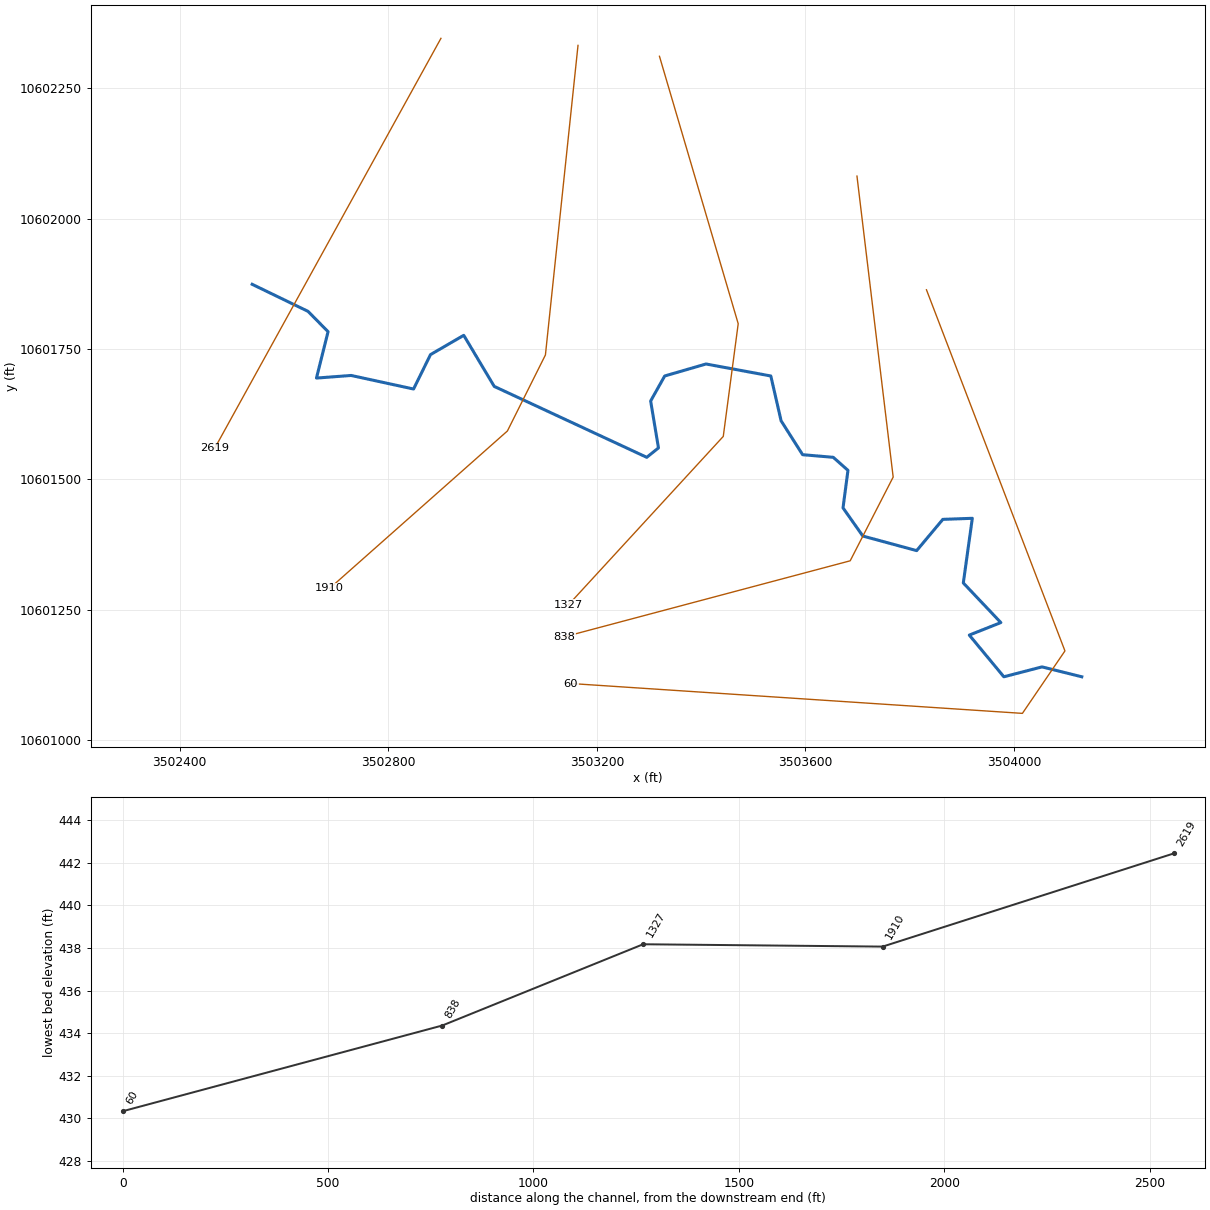
--- UNT037 IN CCTC.prj (project) ---

Proj Title=UNT037 IN CCTC Base Level Engineering
Current Plan=p01
Default Exp/Contr=0.3,0.1
English Units
Geom File=g01
Flow File=f01
Plan File=p01
Y Axis Title=Elevation
X Axis Title(PF)=Main Channel Distance
X Axis Title(XS)=Station
BEGIN DESCRIPTION:
UNT037 IN CCTC
END DESCRIPTION:
DSS Export Rating Curves= 0
DSS Export Rating Curve Sorted= 0
DSS Export Volume Flow Curves= 0
DXF OffsetX= 0
DXF OffsetY= 0
DXF ScaleX= 1
DXF ScaleY= 10

--- UNT037 IN CCTC.p01 (plan) ---

Plan Title=Multiple Run
Short Identifier=Multiple
Geom File=g01
Flow File=f01
Subcritical Flow
K Sum by GR= 0
Std Step Tol= 0.01
Critical Tol= 0.01
Num of Std Step Trials= 20
Max Error Tol= 0.3
Flow Tol Ratio= 0.001
Split Flow NTrial= 30
Split Flow Tol= 0.02
Split Flow Ratio= 0.02
Log Output Level= 0
Friction Slope Method= 1
Unsteady Friction Slope Method= 2
Unsteady Bridges Friction Slope Method= 1
Parabolic Critical Depth
Global Vel Dist=  1 , 1 , 1
Global Log Level= 0
CheckData=True
Encroach Param= -1, 0, 0, 0
BEGIN DESCRIPTION:
Multiple Run
END DESCRIPTION:

--- UNT037 IN CCTC.f01 (steady flow) ---

Flow Title=Multiple
Number of Profiles=7
Profile Names=10-year,25-year,50-year,1pct_min,100-year,1pct_plu,500-year
River Rch & RM= UNT037 IN CCTC,Reach-1,2619
    1077    1461    1774    1572    2125    2874    3042
River Rch & RM= UNT037 IN CCTC,Reach-1,60
    3419    4926    6223    5717    7732   10456   11914
Boundary for River Rch & Prof#=UNT037 IN CCTC,Reach-1,1
Up Type=0
Dn Type=3
Dn Slope=0.005
Boundary for River Rch & Prof#=UNT037 IN CCTC,Reach-1,2
Up Type=0
Dn Type=3
Dn Slope=0.005
Boundary for River Rch & Prof#=UNT037 IN CCTC,Reach-1,3
Up Type=0
Dn Type=3
Dn Slope=0.005
Boundary for River Rch & Prof#=UNT037 IN CCTC,Reach-1,4
Up Type=0
Dn Type=3
Dn Slope=0.005
Boundary for River Rch & Prof#=UNT037 IN CCTC,Reach-1,5
Up Type=0
Dn Type=3
Dn Slope=0.005
Boundary for River Rch & Prof#=UNT037 IN CCTC,Reach-1,6
Up Type=0
Dn Type=3
Dn Slope=0.005
Boundary for River Rch & Prof#=UNT037 IN CCTC,Reach-1,7
Up Type=0
Dn Type=3
Dn Slope=0.005

--- UNT037 IN CCTC.g01 (geometry) ---

Geom Title=Existing Conditions

River Reach=UNT037 IN CCTC,Reach-1
Reach XY= 30
      3502538.89     10601873.86      3502646.00     10601822.00
      3502684.50     10601783.00      3502662.25     10601694.00
      3502728.75     10601699.00      3502848.50     10601673.00
      3502881.00     10601739.00      3502944.75     10601776.00
      3503003.25     10601678.00      3503295.75     10601542.00
      3503318.25     10601560.00      3503303.25     10601650.00
      3503330.25     10601698.00      3503409.50     10601721.00
      3503533.75     10601698.00      3503553.50     10601612.00
      3503594.75     10601547.00      3503653.50     10601542.00
      3503681.75     10601517.00      3503672.25     10601445.00
      3503710.25     10601391.00      3503813.50     10601363.00
      3503863.75     10601423.00      3503920.25     10601425.00
      3503903.00     10601301.00      3503975.00     10601225.00
      3503914.50     10601201.00      3503980.75     10601121.00
      3504054.00     10601140.00      3504130.25     10601121.00

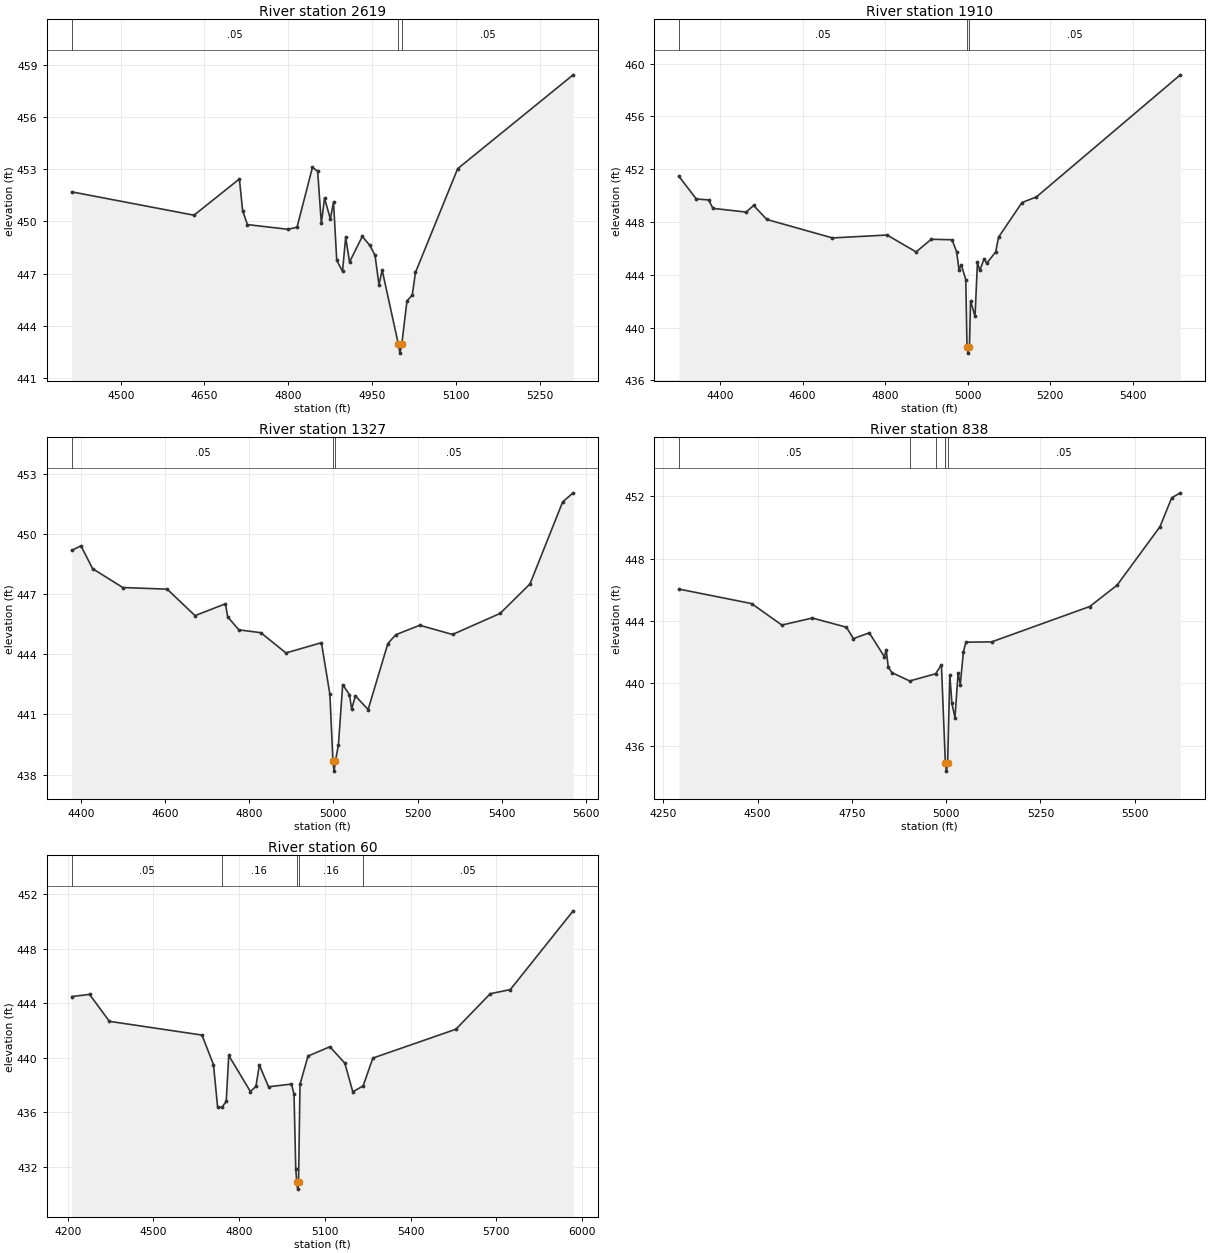
Type RM Length L Ch R = 1,2619,709,709,709
BEGIN DESCRIPTION:
UNT037 IN CCTC 2.0
END DESCRIPTION:
XS GIS Cut Line= 2
      3502901.00     10602345.66      3502467.23     10601559.60
#Sta/Elev= 30
  4412.3  451.69  4631.2  450.35  4712.5  452.43  4718.3  450.60  4726.9  449.81
  4799.6  449.54  4815.7  449.66  4843.2  453.09  4852.6  452.88  4859.2  449.88
  4864.9  451.33  4875.3  450.14  4881.0  451.10  4886.8  447.75  4897.1  447.13
  4902.8  449.09  4909.7  447.66  4932.5  449.13  4946.3  448.61  4955.4  448.04
  4962.4  446.35  4968.1  447.20  4997.2  442.93  4999.9  442.43  5003.2  442.93
  5012.5  445.43  5022.0  445.76  5027.7  447.06  5103.3  453.02  5310.1  458.41
#Mann=3,-1,0
  4412.3    0.05       0  4997.2   0.035       0  5003.2    0.05       0
Bank Sta=4997.2,5003.2
Exp/Cntr=0.3,0.1

Type RM Length L Ch R = 1,1910,583,583,583
BEGIN DESCRIPTION:
Mapping XS bf84f5d1
END DESCRIPTION:
XS GIS Cut Line= 4
      3503163.92     10602332.13      3503101.42     10601738.33
      3503028.50     10601592.50      3502687.35     10601290.41
#Sta/Elev= 30
  4300.0  451.46  4342.2  449.74  4372.3  449.67  4382.4  449.03  4462.8  448.75
  4481.2  449.25  4513.1  448.19  4672.3  446.79  4804.7  447.01  4875.1  445.73
  4912.0  446.69  4962.3  446.65  4973.3  445.75  4979.1  444.38  4984.7  444.75
  4995.6  443.63  4998.5  438.56  5001.2  438.06  5004.5  438.56  5007.1  442.02
  5018.0  440.85  5023.8  444.93  5029.4  444.33  5040.3  445.22  5046.2  444.86
  5068.2  445.74  5074.9  446.84  5131.8  449.47  5166.9  449.90  5515.8  459.15
#Mann=3,-1,0
  4300.0    0.05       0  4998.5   0.035       0  5004.5    0.05       0
Bank Sta=4998.5,5004.5
Exp/Cntr=0.3,0.1

Type RM Length L Ch R = 1,1327,489,489,489
BEGIN DESCRIPTION:
Mapping XS c88ec769
END DESCRIPTION:
XS GIS Cut Line= 4
      3503320.17     10602311.23      3503471.21     10601798.23
      3503442.56     10601582.08      3503145.66     10601259.13
#Sta/Elev= 30
  4378.3  449.17  4400.2  449.40  4427.9  448.26  4499.7  447.32  4605.0  447.24
  4671.3  445.92  4743.6  446.51  4748.8  445.86  4775.5  445.21  4827.6  445.07
  4887.3  444.06  4971.6  444.57  4991.8  441.99  4998.9  438.67  5001.6  438.17
  5004.9  438.67  5012.0  439.48  5022.1  442.48  5038.3  441.98  5043.4  441.26
  5052.3  441.92  5082.6  441.24  5129.5  444.53  5148.5  444.97  5205.2  445.44
  5283.1  444.98  5396.3  446.03  5467.2  447.50  5544.9  451.59  5569.8  452.04
#Mann=3,-1,0
  4378.3    0.05       0  4998.9   0.035       0  5004.9    0.05       0
Bank Sta=4998.9,5004.9
Exp/Cntr=0.3,0.1

Type RM Length L Ch R = 1,838,778,778,778
BEGIN DESCRIPTION:
Mapping XS 32f03fa4
END DESCRIPTION:
XS GIS Cut Line= 4
      3503699.01     10602081.35      3503768.46     10601504.08
      3503686.00     10601343.49      3503137.52     10601197.64
#Sta/Elev= 30
  4291.4  446.05  4483.9  445.12  4564.5  443.74  4645.1  444.19  4735.7  443.60
  4753.9  442.87  4796.2  443.24  4836.0  441.71  4841.0  442.15  4846.5  441.03
  4856.6  440.68  4903.3  440.15  4971.9  440.61  4987.4  441.19  4997.9  434.86
  5000.6  434.36  5003.9  434.86  5009.6  440.55  5015.2  438.72  5023.3  437.79
  5031.7  440.67  5037.4  439.92  5045.8  442.04  5052.4  442.64  5120.7  442.66
  5380.7  444.93  5453.2  446.30  5567.0  450.06  5598.0  451.91  5620.9  452.23
#Mann=5,-1,0
  4291.4    0.05       0  4903.3    0.16       0  4971.9    0.05       0
  4997.9   0.035       0  5003.9    0.05       0
Bank Sta=4997.9,5003.9
Exp/Cntr=0.3,0.1

Type RM Length L Ch R = 1,60,0,0,0
BEGIN DESCRIPTION:
UNT037 IN CCTC 1.0
END DESCRIPTION:
XS GIS Cut Line= 4
      3503832.31     10601863.36      3504097.95     10601170.62
      3504016.35     10601050.83      3503150.01     10601108.12
#Sta/Elev= 30
  4214.1  444.49  4276.4  444.65  4346.0  442.67  4670.0  441.66  4710.2  439.49
  4724.7  436.37  4739.3  436.34  4754.8  436.78  4763.7  440.16  4839.5  437.51
  4858.8  437.89  4870.8  439.46  4902.9  437.86  4983.3  438.06  4992.1  437.32
  4998.2  431.85  5001.9  430.84  5004.7  430.34  5007.9  430.84  5013.1  438.04
  5041.2  440.12  5117.7  440.80  5169.9  439.60  5197.9  437.49  5234.1  437.93
  5268.1  439.97  5558.7  442.09  5679.0  444.70  5749.1  445.00  5969.2  450.79
#Mann=5,-1,0
  4214.1    0.05       0  4739.3    0.16       0  5001.9    0.07       0
  5007.9    0.16       0  5234.1    0.05       0
Bank Sta=5001.9,5007.9
Exp/Cntr=0.3,0.1

Chan Stop Cuts=-1