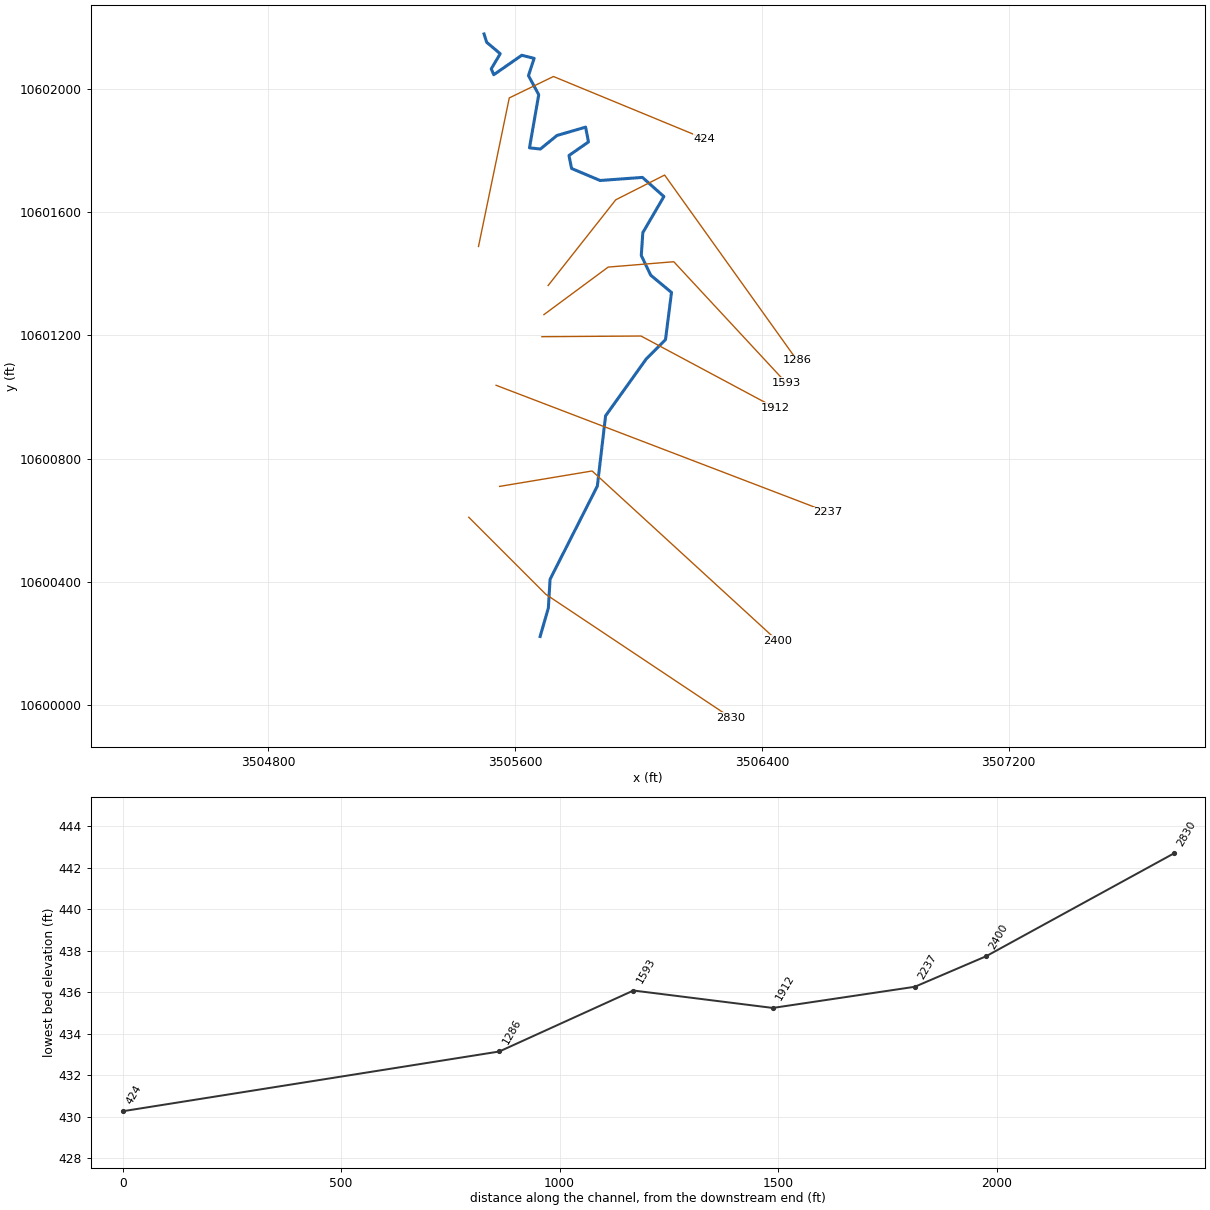
--- UNT038 IN CCTC.prj (project) ---

Proj Title=UNT038 IN CCTC Base Level Engineering
Current Plan=p01
Default Exp/Contr=0.3,0.1
English Units
Geom File=g01
Flow File=f01
Plan File=p01
Y Axis Title=Elevation
X Axis Title(PF)=Main Channel Distance
X Axis Title(XS)=Station
BEGIN DESCRIPTION:
UNT038 IN CCTC
END DESCRIPTION:
DSS Export Rating Curves= 0
DSS Export Rating Curve Sorted= 0
DSS Export Volume Flow Curves= 0
DXF OffsetX= 0
DXF OffsetY= 0
DXF ScaleX= 1
DXF ScaleY= 10

--- UNT038 IN CCTC.p01 (plan) ---

Plan Title=Multiple Run
Short Identifier=Multiple
Geom File=g01
Flow File=f01
Subcritical Flow
K Sum by GR= 0
Std Step Tol= 0.01
Critical Tol= 0.01
Num of Std Step Trials= 20
Max Error Tol= 0.3
Flow Tol Ratio= 0.001
Split Flow NTrial= 30
Split Flow Tol= 0.02
Split Flow Ratio= 0.02
Log Output Level= 0
Friction Slope Method= 1
Unsteady Friction Slope Method= 2
Unsteady Bridges Friction Slope Method= 1
Parabolic Critical Depth
Global Vel Dist=  1 , 1 , 1
Global Log Level= 0
CheckData=True
Encroach Param= -1, 0, 0, 0
BEGIN DESCRIPTION:
Multiple Run
END DESCRIPTION:

--- UNT038 IN CCTC.f01 (steady flow) ---

Flow Title=Multiple
Number of Profiles=7
Profile Names=10-year,25-year,50-year,1pct_min,100-year,1pct_plu,500-year
River Rch & RM= UNT038 IN CCTC,Reach-1,2830
     937    1273    1549    1379    1865    2522    2690
Boundary for River Rch & Prof#=UNT038 IN CCTC,Reach-1,1
Up Type=0
Dn Type=3
Dn Slope=0.005
Boundary for River Rch & Prof#=UNT038 IN CCTC,Reach-1,2
Up Type=0
Dn Type=3
Dn Slope=0.005
Boundary for River Rch & Prof#=UNT038 IN CCTC,Reach-1,3
Up Type=0
Dn Type=3
Dn Slope=0.005
Boundary for River Rch & Prof#=UNT038 IN CCTC,Reach-1,4
Up Type=0
Dn Type=3
Dn Slope=0.005
Boundary for River Rch & Prof#=UNT038 IN CCTC,Reach-1,5
Up Type=0
Dn Type=3
Dn Slope=0.005
Boundary for River Rch & Prof#=UNT038 IN CCTC,Reach-1,6
Up Type=0
Dn Type=3
Dn Slope=0.005
Boundary for River Rch & Prof#=UNT038 IN CCTC,Reach-1,7
Up Type=0
Dn Type=3
Dn Slope=0.005

--- UNT038 IN CCTC.g01 (geometry) ---

Geom Title=Existing Conditions

River Reach=UNT038 IN CCTC,Reach-1
Reach XY= 30
      3505681.01     10600223.64      3505707.75     10600316.00
      3505713.25     10600409.00      3505866.50     10600711.00
      3505893.25     10600939.00      3506024.75     10601123.00
      3506087.50     10601186.00      3506107.00     10601339.00
      3506039.50     10601395.00      3506009.00     10601459.00
      3506014.00     10601533.00      3506082.25     10601650.00
      3506012.75     10601712.00      3505875.50     10601702.00
      3505783.00     10601741.00      3505774.50     10601783.00
      3505837.75     10601827.00      3505828.50     10601875.00
      3505735.75     10601848.00      3505681.75     10601804.00
      3505646.50     10601808.00      3505676.50     10601980.00
      3505643.25     10602042.00      3505661.50     10602098.00
      3505621.50     10602108.00      3505530.75     10602045.00
      3505522.50     10602064.00      3505551.75     10602113.00
      3505507.75     10602150.00      3505499.25     10602177.00

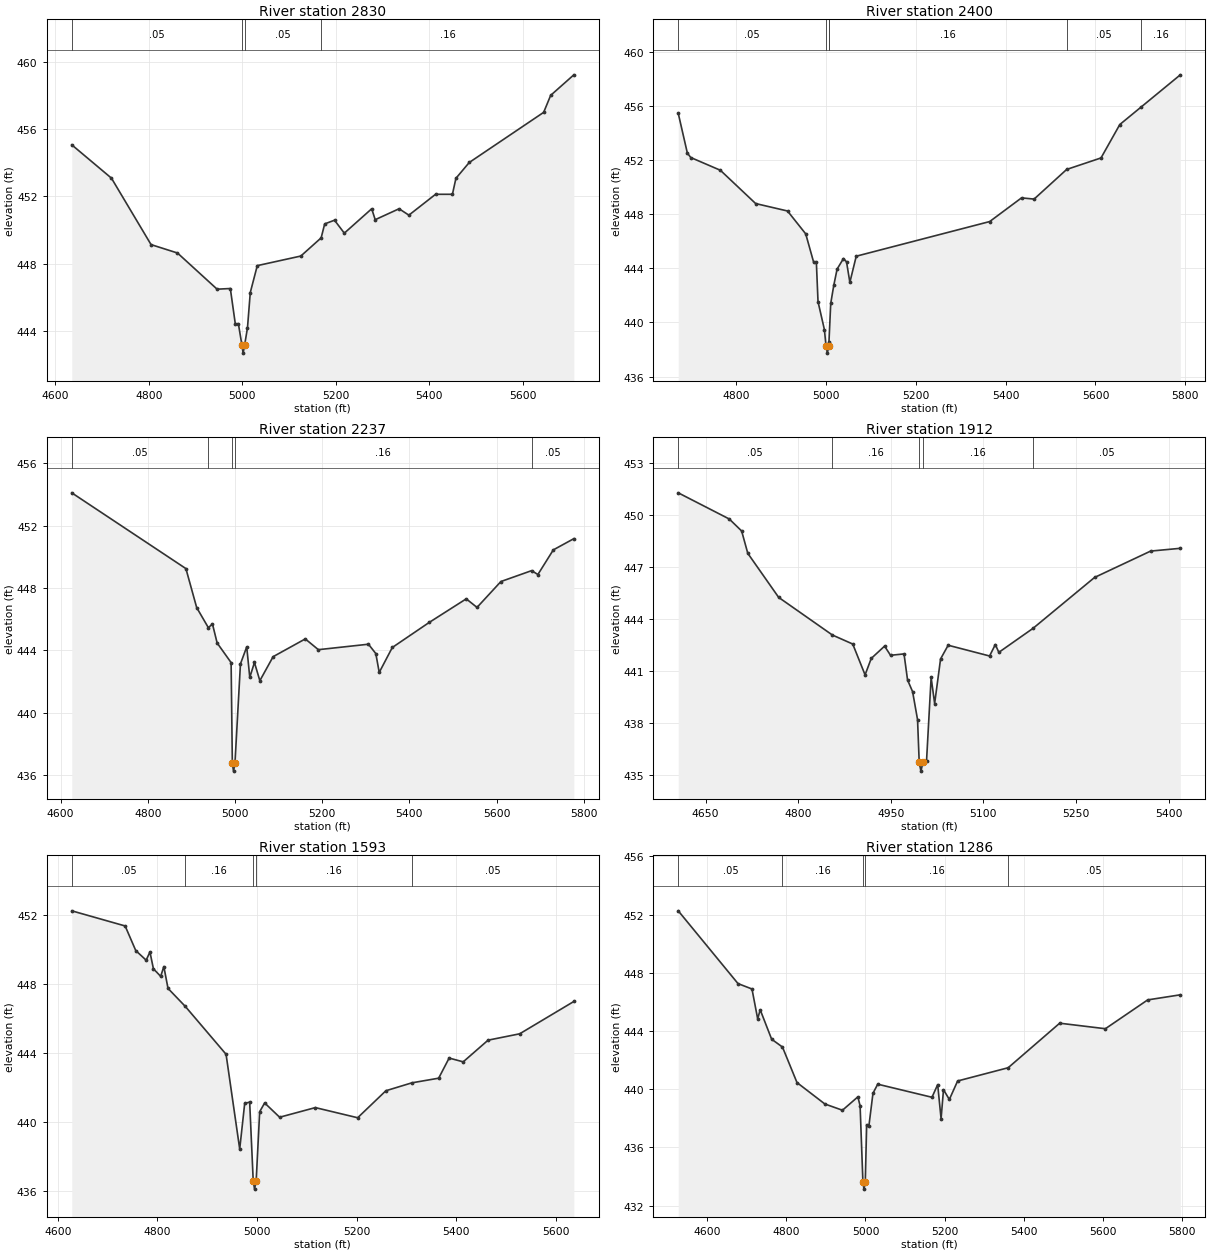
Type RM Length L Ch R = 1,2830,430,430,430
BEGIN DESCRIPTION:
UNT038 IN CCTC 5.0
END DESCRIPTION:
XS GIS Cut Line= 3
      3505449.60     10600610.20      3505699.61     10600360.19
      3506299.62     10599960.18
#Sta/Elev= 30
  4635.2  455.07  4720.1  453.09  4804.9  449.14  4861.5  448.64  4946.3  446.49
  4974.6  446.53  4985.2  444.44  4991.8  444.44  4999.3  443.19  5002.0  442.69
  5005.3  443.19  5011.3  444.19  5017.3  446.29  5032.3  447.89  5125.5  448.46
  5169.0  449.54  5176.6  450.37  5197.6  450.59  5218.6  449.82  5277.2  451.27
  5284.7  450.62  5335.8  451.27  5356.8  450.89  5413.9  452.13  5450.0  452.13
  5457.5  453.08  5486.0  454.02  5645.3  457.00  5660.3  458.01  5709.9  459.23
#Mann=4,-1,0
  4635.2    0.05       0  4999.3    0.03       0  5005.3    0.05       0
  5169.0    0.16       0
Bank Sta=4999.3,5005.3
Exp/Cntr=0.3,0.1

Type RM Length L Ch R = 1,2400,163,163,163
BEGIN DESCRIPTION:
UNT038 IN CCTC 4.0
END DESCRIPTION:
XS GIS Cut Line= 3
      3505549.57     10600710.18      3505849.61     10600760.19
      3506449.59     10600210.20
#Sta/Elev= 30
  4670.8  455.45  4691.1  452.51  4698.7  452.18  4764.6  451.24  4843.2  448.78
  4914.2  448.23  4954.7  446.54  4972.4  444.44  4978.4  444.44  4982.1  441.53
  4996.3  439.47  5000.0  438.23  5002.8  437.73  5006.0  438.23  5006.4  438.52
  5010.4  441.40  5017.2  442.74  5024.6  443.94  5038.8  444.72  5045.6  444.47
  5053.0  442.96  5067.2  444.89  5364.4  447.45  5435.3  449.20  5463.3  449.11
  5535.8  451.30  5612.3  452.15  5654.2  454.62  5701.6  455.91  5788.9  458.29
#Mann=6,-1,0
  4670.8    0.05       0  5000.0    0.03       0  5006.0    0.05       0
  5006.4    0.16       0  5535.8    0.05       0  5701.6    0.16       0
Bank Sta=5000,5006
Exp/Cntr=0.3,0.1

Type RM Length L Ch R = 1,2237,325,325,325
BEGIN DESCRIPTION:
Mapping XS c97d3d31
END DESCRIPTION:
XS GIS Cut Line= 2
      3505538.25     10601038.02      3506613.83     10600626.54
#Sta/Elev= 30
  4625.6  454.11  4887.4  449.25  4912.1  446.75  4938.9  445.46  4948.3  445.70
  4959.0  444.48  4991.1  443.22  4993.9  436.76  4996.6  436.26  4999.9  436.76
  5012.5  443.14  5026.9  444.23  5033.9  442.27  5044.6  443.23  5057.0  442.06
  5087.4  443.60  5161.2  444.74  5191.2  444.05  5306.1  444.40  5323.0  443.80
  5330.8  442.59  5360.8  444.19  5445.6  445.80  5530.4  447.31  5555.1  446.76
  5609.9  448.42  5680.4  449.12  5694.7  448.87  5730.1  450.45  5777.2  451.17
#Mann=5,-1,0
  4625.6    0.05       0  4938.9    0.16       0  4993.9    0.07       0
  4999.9    0.16       0  5680.4    0.05       0
Bank Sta=4993.9,4999.9
Exp/Cntr=0.3,0.1

Type RM Length L Ch R = 1,1912,319,319,319
BEGIN DESCRIPTION:
Mapping XS 2cc10f0f
END DESCRIPTION:
XS GIS Cut Line= 3
      3505686.88     10601195.56      3506008.05     10601197.73
      3506442.06     10600965.53
#Sta/Elev= 30
  4605.7  451.29  4688.4  449.78  4708.4  449.09  4718.4  447.80  4768.4  445.26
  4855.4  443.09  4888.4  442.57  4908.4  440.79  4918.4  441.74  4940.0  442.45
  4949.6  441.92  4971.5  442.00  4977.2  440.50  4985.4  439.82  4993.4  438.21
  4996.1  435.74  4998.9  435.24  5002.1  435.74  5008.0  435.85  5015.4  440.64
  5021.1  439.14  5030.7  441.71  5043.0  442.50  5110.1  441.88  5119.4  442.54
  5125.1  442.09  5180.7  443.48  5280.2  446.41  5371.0  447.93  5419.1  448.09
#Mann=5,-1,0
  4605.7    0.05       0  4855.4    0.16       0  4996.1    0.07       0
  5002.1    0.16       0  5180.7    0.05       0
Bank Sta=4996.1,5002.1
Exp/Cntr=0.3,0.1

Type RM Length L Ch R = 1,1593,307,307,307
BEGIN DESCRIPTION:
UNT038 IN CCTC 3.0
END DESCRIPTION:
XS GIS Cut Line= 4
      3505693.39     10601267.17      3505901.71     10601421.25
      3506114.39     10601438.61      3506478.96     10601045.82
#Sta/Elev= 30
  4628.1  452.26  4735.3  451.38  4756.6  449.95  4777.5  449.39  4785.1  449.87
  4792.1  448.89  4806.7  448.45  4813.0  449.02  4821.4  447.75  4856.2  446.70
  4938.0  443.92  4965.4  438.41  4975.4  441.06  4985.4  441.14  4992.5  436.58
  4995.2  436.08  4998.5  436.58  5005.5  440.58  5015.5  441.09  5045.6  440.26
  5117.3  440.82  5202.3  440.23  5259.0  441.80  5311.2  442.26  5365.0  442.53
  5386.0  443.70  5414.3  443.48  5464.2  444.74  5527.7  445.11  5636.5  446.99
#Mann=5,-1,0
  4628.1    0.05       0  4856.2    0.16       0  4992.5    0.07       0
  4998.5    0.16       0  5311.2    0.05       0
Bank Sta=4992.5,4998.5
Exp/Cntr=0.3,0.1

Type RM Length L Ch R = 1,1286,862,862,862
BEGIN DESCRIPTION:
UNT038 IN CCTC 2.0
END DESCRIPTION:
XS GIS Cut Line= 4
      3505707.03     10601361.59      3505926.20     10601639.35
      3506084.62     10601719.65      3506513.69     10601119.60
#Sta/Elev= 30
  4526.8  452.26  4677.9  447.26  4713.2  446.89  4727.6  444.84  4734.0  445.46
  4762.9  443.44  4790.3  442.90  4827.0  440.46  4897.4  438.99  4941.9  438.56
  4980.9  439.48  4986.5  438.86  4993.6  433.64  4996.3  433.14  4999.6  433.64
  5003.1  437.57  5008.7  437.47  5019.0  439.72  5031.0  440.35  5168.2  439.45
  5182.6  440.32  5191.2  437.98  5197.3  439.97  5212.1  439.30  5233.0  440.57
  5360.8  441.48  5491.0  444.54  5606.5  444.16  5713.4  446.14  5795.9  446.49
#Mann=5,-1,0
  4526.8    0.05       0  4790.3    0.16       0  4993.6    0.07       0
  4999.6    0.16       0  5360.8    0.05       0
Bank Sta=4993.6,4999.6
Exp/Cntr=0.3,0.1

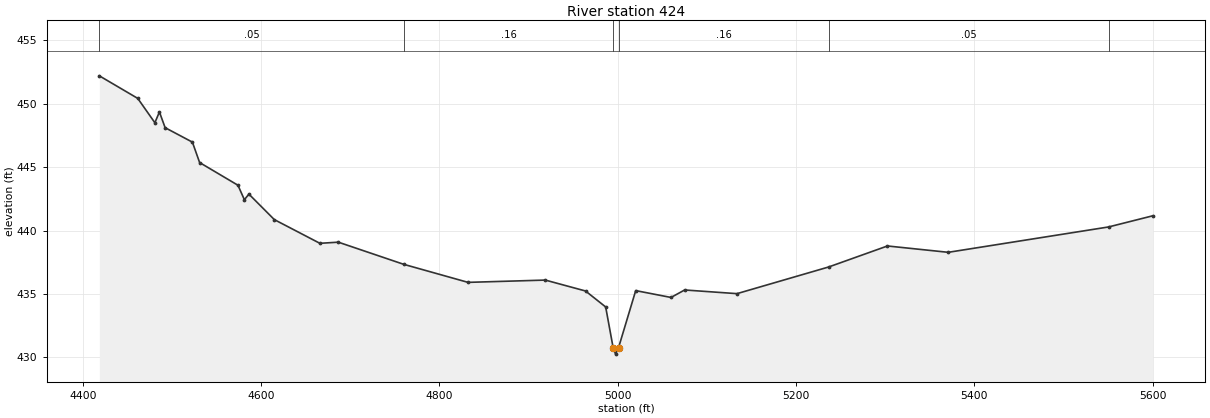
Type RM Length L Ch R = 1,424,0,0,0
BEGIN DESCRIPTION:
UNT038 IN CCTC 1.0
END DESCRIPTION:
XS GIS Cut Line= 4
      3505481.17     10601487.96      3505580.99     10601969.71
      3505724.22     10602039.16      3506214.69     10601836.89
#Sta/Elev= 30
  4418.5  452.21  4461.6  450.43  4480.8  448.51  4485.9  449.36  4492.3  448.12
  4522.9  446.98  4531.0  445.37  4574.0  443.58  4581.2  442.44  4586.3  442.88
  4614.8  440.87  4665.9  439.00  4686.6  439.09  4760.1  437.34  4832.1  435.92
  4918.8  436.10  4963.9  435.24  4986.5  433.98  4994.9  430.76  4997.6  430.26
  5000.9  430.76  5020.2  435.27  5059.8  434.73  5075.1  435.32  5133.8  435.03
  5236.5  437.13  5302.6  438.79  5370.8  438.29  5550.6  440.29  5600.2  441.17
#Mann=6,-1,0
  4418.5    0.05       0  4760.1    0.16       0  4994.9    0.07       0
  5000.9    0.16       0  5236.5    0.05       0  5550.6    0.16       0
Bank Sta=4994.9,5000.9
Exp/Cntr=0.3,0.1

Chan Stop Cuts=-1