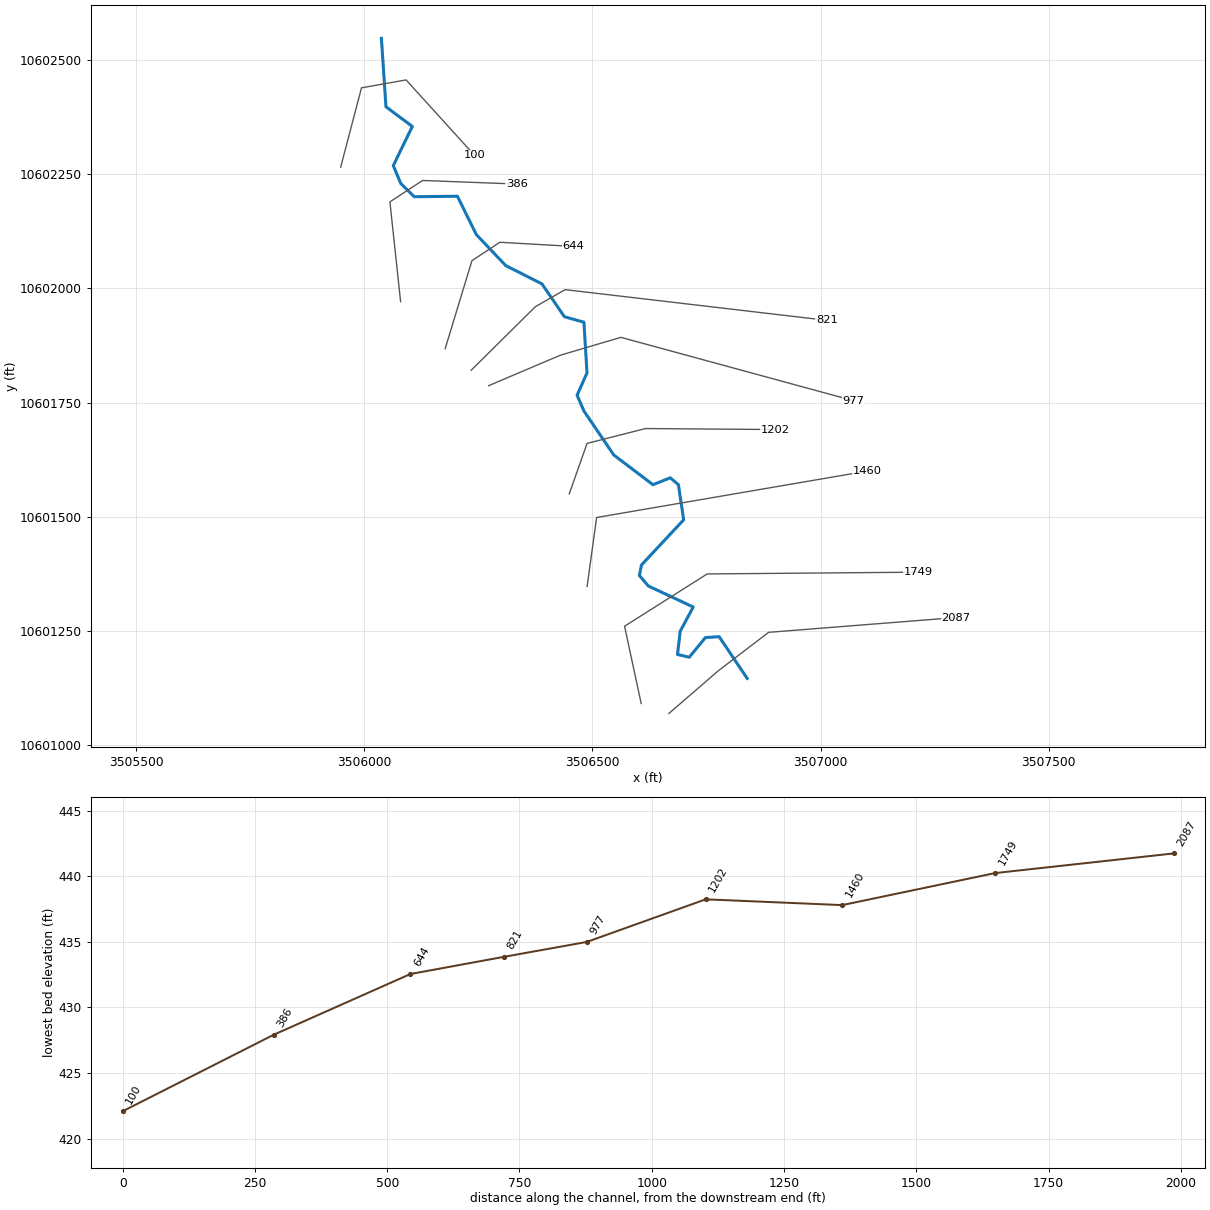
--- UNT039 IN CCTC.prj (project) ---

Proj Title=UNT039 IN CCTC Base Level Engineering
Current Plan=p01
Default Exp/Contr=0.3,0.1
English Units
Geom File=g01
Flow File=f01
Plan File=p01
Y Axis Title=Elevation
X Axis Title(PF)=Main Channel Distance
X Axis Title(XS)=Station
BEGIN DESCRIPTION:
UNT039 IN CCTC
END DESCRIPTION:
DSS Export Rating Curves= 0
DSS Export Rating Curve Sorted= 0
DSS Export Volume Flow Curves= 0
DXF OffsetX= 0
DXF OffsetY= 0
DXF ScaleX= 1
DXF ScaleY= 10

--- UNT039 IN CCTC.p01 (plan) ---

Plan Title=Multiple Run
Short Identifier=Multiple
Geom File=g01
Flow File=f01
Subcritical Flow
K Sum by GR= 0
Std Step Tol= 0.01
Critical Tol= 0.01
Num of Std Step Trials= 20
Max Error Tol= 0.3
Flow Tol Ratio= 0.001
Split Flow NTrial= 30
Split Flow Tol= 0.02
Split Flow Ratio= 0.02
Log Output Level= 0
Friction Slope Method= 1
Unsteady Friction Slope Method= 2
Unsteady Bridges Friction Slope Method= 1
Parabolic Critical Depth
Global Vel Dist=  1 , 1 , 1
Global Log Level= 0
CheckData=True
Encroach Param= -1, 0, 0, 0
BEGIN DESCRIPTION:
Multiple Run
END DESCRIPTION:

--- UNT039 IN CCTC.f01 (steady flow) ---

Flow Title=Multiple
Number of Profiles=7
Profile Names=10-year,25-year,50-year,1pct_min,100-year,1pct_plu,500-year
River Rch & RM= UNT039 IN CCTC,Reach-1,2087
     387     495     579     498     673     910     902
Boundary for River Rch & Prof#=UNT039 IN CCTC,Reach-1,1
Up Type=0
Dn Type=3
Dn Slope=0.005
Boundary for River Rch & Prof#=UNT039 IN CCTC,Reach-1,2
Up Type=0
Dn Type=3
Dn Slope=0.005
Boundary for River Rch & Prof#=UNT039 IN CCTC,Reach-1,3
Up Type=0
Dn Type=3
Dn Slope=0.005
Boundary for River Rch & Prof#=UNT039 IN CCTC,Reach-1,4
Up Type=0
Dn Type=3
Dn Slope=0.005
Boundary for River Rch & Prof#=UNT039 IN CCTC,Reach-1,5
Up Type=0
Dn Type=3
Dn Slope=0.005
Boundary for River Rch & Prof#=UNT039 IN CCTC,Reach-1,6
Up Type=0
Dn Type=3
Dn Slope=0.005
Boundary for River Rch & Prof#=UNT039 IN CCTC,Reach-1,7
Up Type=0
Dn Type=3
Dn Slope=0.005

--- UNT039 IN CCTC.g01 (geometry) ---

Geom Title=Existing Conditions
Program Version=4.10

River Reach=UNT039 IN CCTC  ,Reach-1
Reach XY= 30
      3506839.28     10601145.46      3506777.75       10601237.
      3506747.75       10601235.      3506712.25       10601192.
       3506686.5       10601198.       3506692.5       10601249.
        3506721.       10601302.      3506622.75       10601348.
        3506603.       10601371.       3506607.5       10601394.
        3506700.       10601493.       3506688.5       10601570.
      3506670.75       10601585.      3506632.75       10601570.
        3506547.       10601635.      3506481.75       10601731.
       3506466.5       10601766.      3506488.25       10601815.
       3506481.5       10601926.      3506438.75       10601938.
       3506389.5       10602010.      3506310.25       10602050.
      3506245.75       10602118.      3506204.25       10602202.
       3506109.5       10602201.      3506080.25       10602230.
      3506063.75       10602269.       3506105.5       10602355.
      3506047.75       10602398.      3506037.75       10602548.

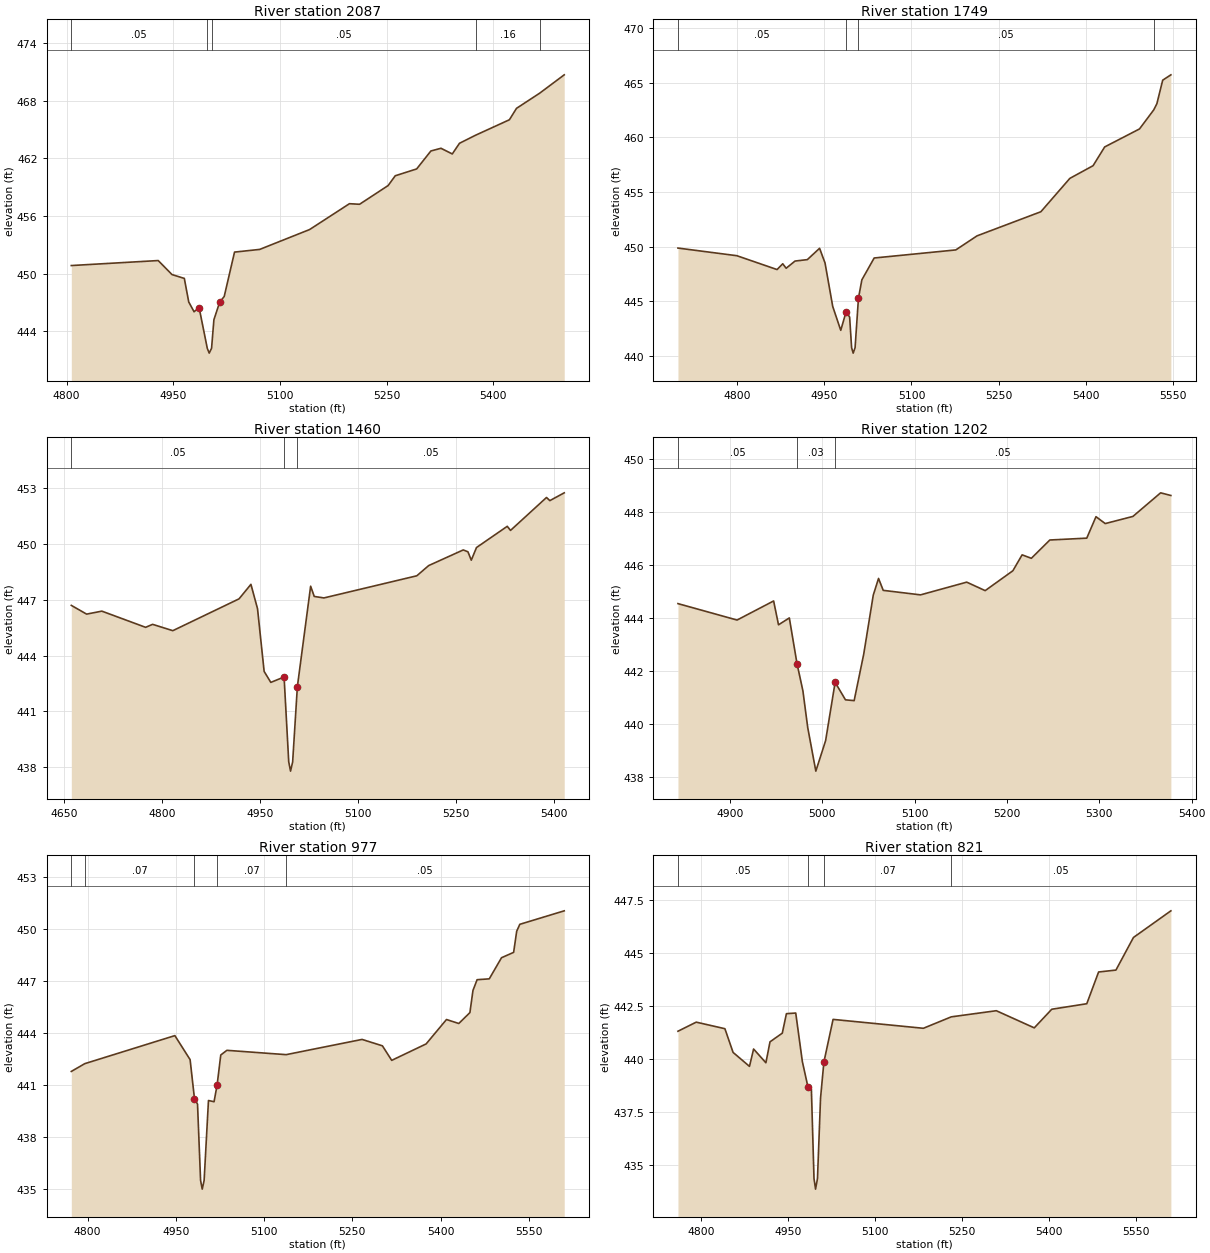
Type RM Length L Ch R = 1 ,2087    ,338,338,338
BEGIN DESCRIPTION:
UNT039 IN CCTC 2.0
END DESCRIPTION:
XS GIS Cut Line= 4
      3506667.91     10601068.94       3506775.4     10601161.86
      3506886.08     10601246.49      3507296.49     10601278.89
#Sta/Elev= 30
  4806.7  450.85  4928.9  451.37  4948.3  449.91  4965.6  449.51  4971.8  447.06
  4979.3  446.04  4986.4  446.47  4997.9  442.23  5000.6  441.73  5003.9  442.23
  5007.2  445.21  5015.4  447.05  5021.7  447.63  5036.2  452.25  5071.6  452.53
  5141.8   454.6  5197.8  457.29    5212  457.23  5252.2  459.18  5262.2   460.2
  5292.3  460.91  5312.3  462.78  5326.5  463.06  5342.4  462.47  5352.5  463.58
  5375.1  464.42  5422.7  466.03  5432.7  467.22  5465.3   468.8  5499.8  470.71
#Mann= 5 ,-1 , 0
  4806.7     .05       0  4997.9     .03       0  5003.9     .05       0
  5375.1     .16       0  5465.3     .05       0
Bank Sta=4986.4,5015.4
XS Rating Curve= 0 ,0
Exp/Cntr=0.3,0.1

Type RM Length L Ch R = 1 ,1749    ,289,289,289
BEGIN DESCRIPTION:
Mapping XS bc652a09
END DESCRIPTION:
XS GIS Cut Line= 4
      3506606.98     10601090.56      3506570.51     10601259.85
       3506751.5     10601374.43      3507213.71     10601378.33
#Sta/Elev= 30
  4697.5  449.86    4799  449.16  4868.3  447.89  4878.1  448.42    4884  448.01
  4899.3  448.67  4920.5   448.8  4941.6  449.84    4951  448.49  4964.3   444.5
  4978.1  442.32  4987.4  444.04  4993.4  443.53  4996.8  440.73  4999.5  440.23
  5002.8  440.73  5008.6  445.27  5014.5  446.95  5035.7  448.95  5176.4  449.69
    5213  450.98    5323  453.19    5373  456.25    5413  457.41    5433  459.13
    5493  460.78  5517.6  462.53    5523   463.1    5533  465.25  5547.1  465.74
#Mann= 4 ,-1 , 0
  4697.5     .05       0  4987.4     .03       0  5008.6     .05       0
  5517.6     .16       0
Bank Sta=4987.4,5008.6
XS Rating Curve= 0 ,0
Exp/Cntr=0.3,0.1

Type RM Length L Ch R = 1 ,1460    ,258,258,258
BEGIN DESCRIPTION:
Mapping XS 122d4cc8
END DESCRIPTION:
XS GIS Cut Line= 3
      3506488.48     10601347.05      3506509.32     10601498.13
      3507101.76     10601599.69
#Sta/Elev= 30
  4661.4   446.7  4684.8  446.23  4708.1  446.39    4775  445.52  4785.7  445.68
  4816.6  445.34  4917.8  447.05    4936  447.83  4946.1  446.52  4956.2  443.15
  4966.4  442.56  4986.7  442.85  4993.8  438.29  4996.6  437.79  4999.8  438.29
    5007  442.33  5027.3  447.73  5032.8  447.18  5047.6   447.1  5189.6  448.29
  5207.8  448.84  5260.6  449.68  5267.8  449.58  5272.9  449.13  5280.9  449.81
  5327.9  450.95  5332.9  450.73  5387.9   452.5    5393  452.33    5415  452.75
#Mann= 3 , 0 , 0
  4661.4     .05       0  4986.7     .03       0    5007     .05       0
Bank Sta=4986.7,5007
XS Rating Curve= 0 ,0
Exp/Cntr=0.3,0.1

Type RM Length L Ch R = 1 ,1202    ,225,225,225
BEGIN DESCRIPTION:
Mapping XS 38ca70a8
END DESCRIPTION:
XS GIS Cut Line= 4
      3506449.32      10601549.8      3506488.38     10601660.46
      3506616.42     10601693.01      3506900.75     10601690.84
#Sta/Elev= 30
  4843.7  444.55  4907.7  443.93  4947.3  444.65  4952.6  443.75  4964.3  444.01
  4972.6  442.29    4979  441.26  4984.2  439.88    4993  438.23  5003.6  439.38
  5013.9  441.58  5025.1  440.92  5034.5  440.89  5044.9  442.65  5055.2  444.87
  5060.9   445.5    5066  445.05  5106.4  444.88  5156.4  445.36  5176.4  445.04
  5206.4  445.79  5216.4  446.39  5226.4  446.26  5246.4  446.95  5286.4  447.02
  5296.4  447.83  5306.4  447.57  5336.4  447.84  5366.4  448.73  5377.5  448.63
#Mann= 3 ,-1 , 0
  4843.7     .05       0  4972.6     .03       0  5013.9     .05       0
Bank Sta=4972.6,5013.9
XS Rating Curve= 0 ,0
Exp/Cntr=0.3,0.1

Type RM Length L Ch R = 1 ,977     ,156,156,156
BEGIN DESCRIPTION:
Mapping XS cb46e22b
END DESCRIPTION:
XS GIS Cut Line= 4
      3506272.61     10601786.91       3506430.1     10601853.76
      3506562.48     10601892.83      3507072.49     10601753.93
#Sta/Elev= 30
  4772.4  441.78  4795.3  442.23  4948.4  443.85  4974.3  442.46  4981.7  440.21
  4986.9  439.89  4992.1  435.48  4994.9  434.98  4998.1  435.48  5005.5   440.1
    5015  440.03  5020.2     441  5026.4  442.73  5036.8     443  5137.5  442.75
  5266.5  443.63  5301.1  443.26  5316.9  442.42  5375.4  443.37    5410  444.78
  5430.9  444.55  5449.8  445.18    5455  446.46    5462  447.08  5482.7  447.13
  5503.5  448.35  5524.1  448.66  5529.3  449.88  5534.6  450.28  5610.1  451.06
#Mann= 5 ,-1 , 0
  4772.4     .05       0  4795.3     .07       0  4981.7     .05       0
  5020.2     .07       0  5137.5     .05       0
Bank Sta=4981.7,5020.2
XS Rating Curve= 0 ,0
Exp/Cntr=0.3,0.1

Type RM Length L Ch R = 1 ,821     ,177,177,177
BEGIN DESCRIPTION:
Mapping XS aec659ff
END DESCRIPTION:
XS GIS Cut Line= 4
      3506234.45     10601820.77       3506375.2     10601960.03
       3506440.3     10601997.35      3507013.73     10601930.12
#Sta/Elev= 30
  4759.5  441.31    4791  441.74  4840.5  441.43  4854.6  440.31  4882.9  439.65
    4890  440.47  4911.2  439.82  4918.3  440.81  4939.5  441.22  4946.6  442.14
  4962.7  442.17  4974.1  439.88  4983.9  438.66  4989.7  438.57  4994.2  434.35
  4996.9  433.85  5000.2  434.35  5005.5  438.16  5011.3  439.86  5027.1  441.87
  5182.9  441.45    5231  441.99  5308.7  442.28  5374.2  441.47  5404.4  442.35
  5464.8  442.61  5485.2  444.11  5515.1   444.2  5545.3  445.74  5609.9     447
#Mann= 4 ,-1 , 0
  4759.5     .05       0  4983.9     .03       0  5011.3     .07       0
    5231     .05       0
Bank Sta=4983.9,5011.3
XS Rating Curve= 0 ,0
Exp/Cntr=0.3,0.1

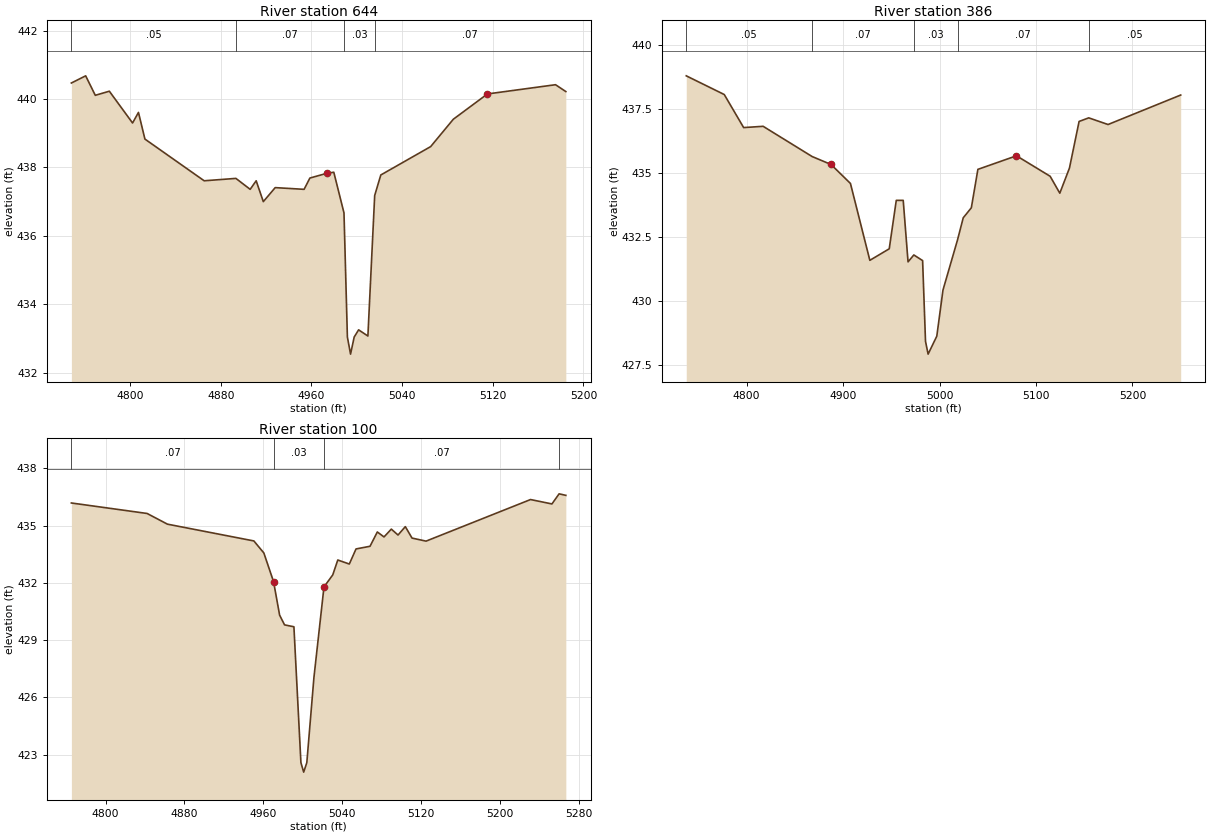
Type RM Length L Ch R = 1 ,644     ,258,258,258
BEGIN DESCRIPTION:
Mapping XS 979901a5
END DESCRIPTION:
XS GIS Cut Line= 4
       3506177.5      10601868.1      3506236.09     10602060.79
      3506297.29     10602101.16      3506458.72     10602092.05
#Sta/Elev= 30
  4748.1  440.47  4760.7  440.68  4769.2  440.11  4781.6  440.23  4802.1   439.3
  4807.3  439.61    4813  438.83  4865.3  437.61  4893.3  437.68  4905.9  437.36
  4911.2  437.61  4917.5     437    4928  437.41  4953.5  437.36  4958.6  437.69
  4973.7  437.83  4979.7  437.86  4988.7  436.67  4991.7  433.04  4994.5  432.54
  4997.7  433.04  5001.6  433.25  5009.8  433.07  5015.8  437.18  5021.2  437.78
  5065.2  438.61  5085.2  439.41  5115.3  440.15  5175.4  440.42  5184.5  440.22
#Mann= 4 ,-1 , 0
  4748.1     .05       0  4893.3     .07       0  4988.7     .03       0
  5015.8     .07       0
Bank Sta=4973.7,5115.3
XS Rating Curve= 0 ,0
Exp/Cntr=0.3,0.1

Type RM Length L Ch R = 1 ,386     ,286,286,286
BEGIN DESCRIPTION:
Mapping XS 402bd401
END DESCRIPTION:
XS GIS Cut Line= 4
      3506079.84     10601970.98      3506056.41      10602189.7
      3506128.02     10602236.58      3506334.81     10602228.77
#Sta/Elev= 30
  4737.5  438.78  4776.9  438.05    4797  436.76  4817.2  436.81    4868  435.63
  4887.6  435.32  4907.7  434.58  4927.8  431.58  4947.9  432.03  4955.2  433.92
  4962.4  433.92  4967.4  431.52  4973.4  431.79  4982.5  431.57  4985.5  428.42
  4988.2  427.92  4997.2  428.62  5003.6  430.42  5018.7  432.38  5024.6  433.24
    5033  433.63  5039.8  435.13  5079.8  435.66  5114.7  434.86  5124.7   434.2
  5134.7  435.18  5144.7     437  5154.7  437.14  5174.7  436.88    5250  438.03
#Mann= 5 ,-1 , 0
  4737.5     .05       0    4868     .07       0  4973.4     .03       0
  5018.7     .07       0  5154.7     .05       0
Bank Sta=4887.6,5079.8
XS Rating Curve= 0 ,0
Exp/Cntr=0.3,0.1

Type RM Length L Ch R = 1 ,100     ,0,0,0
BEGIN DESCRIPTION:
UNT039 IN CCTC 1.0
END DESCRIPTION:
XS GIS Cut Line= 4
      3505948.57     10602265.89      3505994.15     10602439.53
      3506091.81     10602456.89      3506241.56     10602291.94
#Sta/Elev= 30
  4765.3  436.19  4842.1  435.64  4862.7  435.08  4950.4   434.2  4960.5  433.57
 4970.34  432.07  4976.5  430.31  4981.5   429.8    4991   429.7  4998.1  422.58
  5000.9  422.08  5004.1  422.58  5011.3  427.04  5021.5  431.79  5030.4  432.42
  5035.5   433.2  5047.2  432.99    5054  433.78  5068.2  433.92  5075.6  434.67
  5082.4  434.41  5089.8  434.82  5096.6  434.51    5104  434.95  5110.8  434.35
    5125  434.19    5231  436.37  5252.7  436.14    5260  436.67  5266.8  436.59
#Mann= 4 ,-1 , 0
  4765.3     .07       0 4970.34     .03       0  5021.5     .07       0
    5260     .05       0
Bank Sta=4970.34,5021.5
XS Rating Curve= 0 ,0
Exp/Cntr=0.3,0.1

Chan Stop Cuts=-1
Use User Specified Reach Order=0
Composite Channel Slope=5