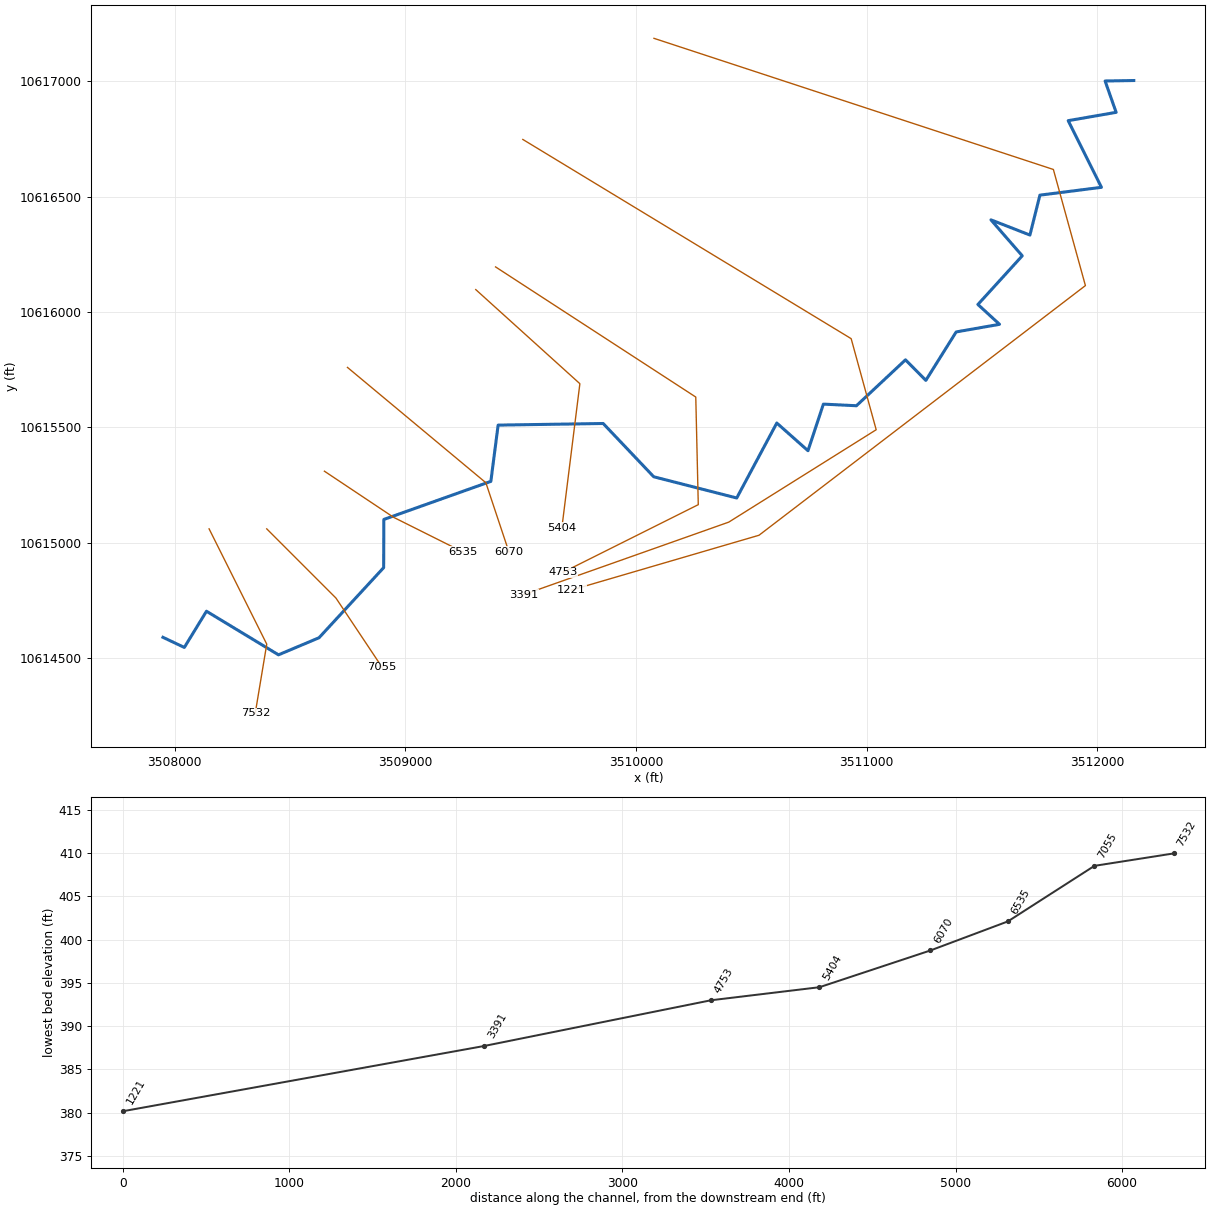
--- UNT043 IN CCTC.prj (project) ---

Proj Title=UNT043 IN CCTC Base Level Engineering
Current Plan=p01
Default Exp/Contr=0.3,0.1
English Units
Geom File=g01
Flow File=f01
Plan File=p01
Y Axis Title=Elevation
X Axis Title(PF)=Main Channel Distance
X Axis Title(XS)=Station
BEGIN DESCRIPTION:
UNT043 IN CCTC
END DESCRIPTION:
DSS Export Rating Curves= 0
DSS Export Rating Curve Sorted= 0
DSS Export Volume Flow Curves= 0
DXF OffsetX= 0
DXF OffsetY= 0
DXF ScaleX= 1
DXF ScaleY= 10

--- UNT043 IN CCTC.p01 (plan) ---

Plan Title=Multiple Run
Short Identifier=Multiple
Geom File=g01
Flow File=f01
Subcritical Flow
K Sum by GR= 0
Std Step Tol= 0.01
Critical Tol= 0.01
Num of Std Step Trials= 20
Max Error Tol= 0.3
Flow Tol Ratio= 0.001
Split Flow NTrial= 30
Split Flow Tol= 0.02
Split Flow Ratio= 0.02
Log Output Level= 0
Friction Slope Method= 1
Unsteady Friction Slope Method= 2
Unsteady Bridges Friction Slope Method= 1
Parabolic Critical Depth
Global Vel Dist=  1 , 1 , 1
Global Log Level= 0
CheckData=True
Encroach Param= -1, 0, 0, 0
BEGIN DESCRIPTION:
Multiple Run
END DESCRIPTION:

--- UNT043 IN CCTC.f01 (steady flow) ---

Flow Title=Multiple
Number of Profiles=7
Profile Names=10-year,25-year,50-year,1pct_min,100-year,1pct_plu,500-year
River Rch & RM= UNT043 IN CCTC,Reach-1,7532
    1078    1460    1771    1568    2121    2868    3030
Boundary for River Rch & Prof#=UNT043 IN CCTC,Reach-1,1
Up Type=0
Dn Type=3
Dn Slope=0.005
Boundary for River Rch & Prof#=UNT043 IN CCTC,Reach-1,2
Up Type=0
Dn Type=3
Dn Slope=0.005
Boundary for River Rch & Prof#=UNT043 IN CCTC,Reach-1,3
Up Type=0
Dn Type=3
Dn Slope=0.005
Boundary for River Rch & Prof#=UNT043 IN CCTC,Reach-1,4
Up Type=0
Dn Type=3
Dn Slope=0.005
Boundary for River Rch & Prof#=UNT043 IN CCTC,Reach-1,5
Up Type=0
Dn Type=3
Dn Slope=0.005
Boundary for River Rch & Prof#=UNT043 IN CCTC,Reach-1,6
Up Type=0
Dn Type=3
Dn Slope=0.005
Boundary for River Rch & Prof#=UNT043 IN CCTC,Reach-1,7
Up Type=0
Dn Type=3
Dn Slope=0.005

--- UNT043 IN CCTC.g01 (geometry) ---

Geom Title=Existing Conditions

River Reach=UNT043 IN CCTC,Reach-1
Reach XY= 30
      3507949.50     10614590.00      3508042.25     10614546.00
      3508138.25     10614703.00      3508450.50     10614514.00
      3508626.25     10614588.00      3508906.50     10614892.00
      3508907.25     10615101.00      3509371.25     10615266.00
      3509402.75     10615510.00      3509858.25     10615517.00
      3510077.50     10615286.00      3510437.25     10615194.00
      3510611.00     10615519.00      3510746.25     10615399.00
      3510813.00     10615601.00      3510956.25     10615594.00
      3511169.00     10615793.00      3511257.25     10615704.00
      3511388.75     10615914.00      3511576.75     10615947.00
      3511483.00     10616033.00      3511675.25     10616244.00
      3511539.50     10616400.00      3511708.50     10616334.00
      3511751.75     10616507.00      3512018.50     10616541.00
      3511874.50     10616830.00      3512082.25     10616866.00
      3512034.50     10617002.00      3512158.75     10617004.00

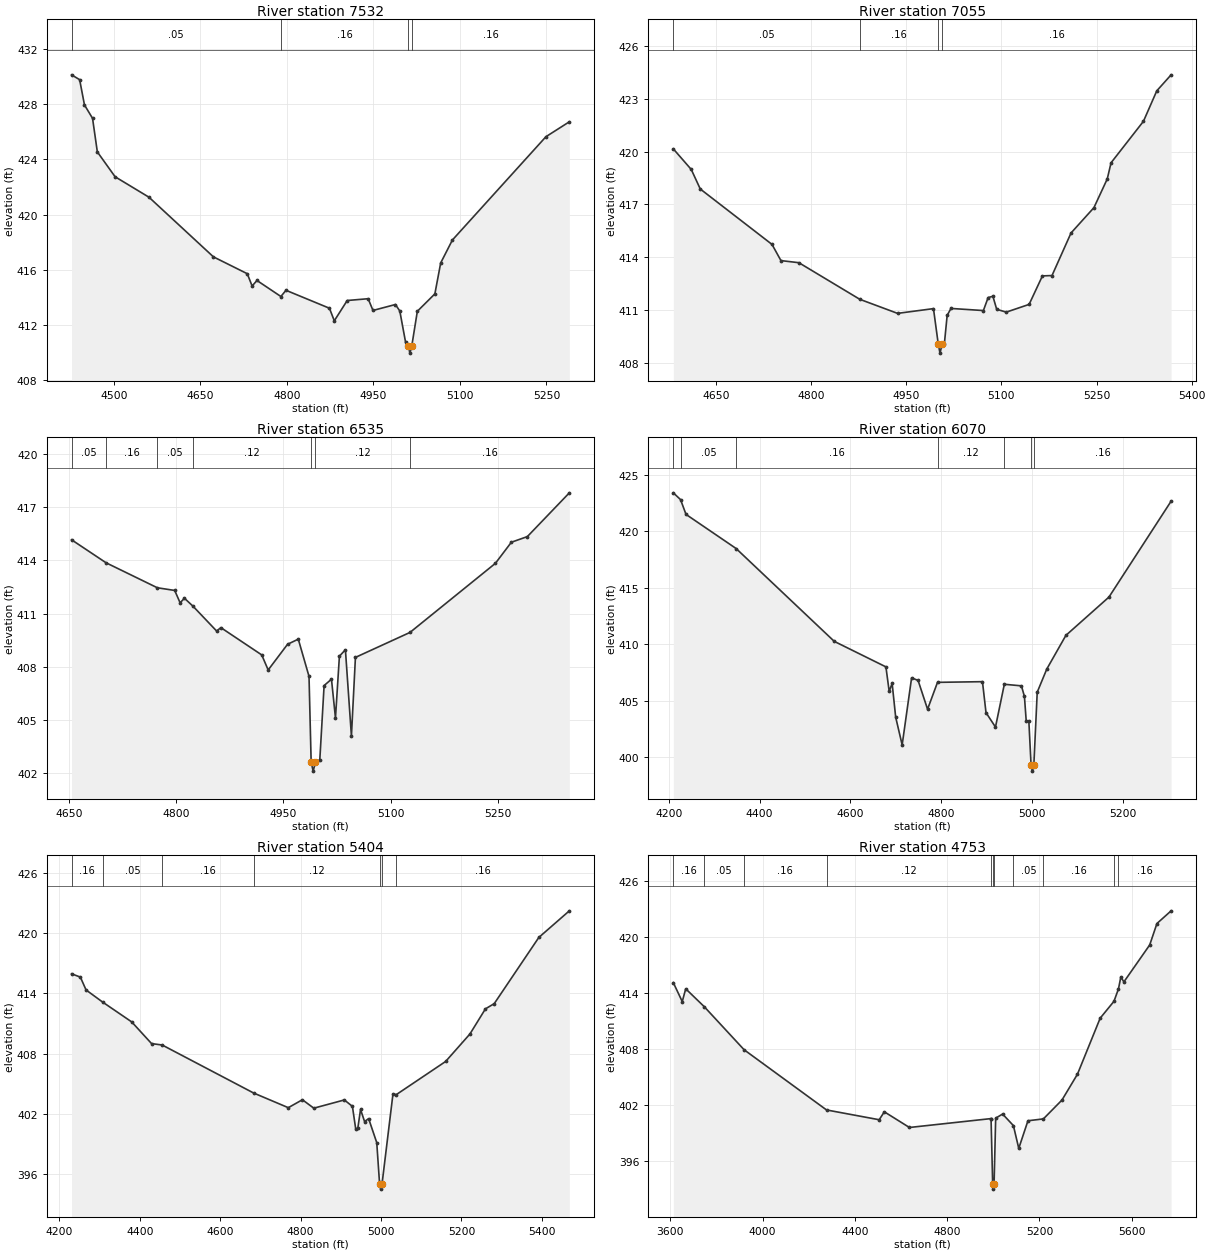
Type RM Length L Ch R = 1,7532,477,477,477
BEGIN DESCRIPTION:
UNT043 IN CCTC 6.0
END DESCRIPTION:
XS GIS Cut Line= 3
      3508149.60     10615060.20      3508399.61     10614560.19
      3508349.60     10614260.16
#Sta/Elev= 30
  4426.5  430.13  4440.5  429.78  4448.9  427.95  4462.9  426.98  4471.2  424.55
  4502.0  422.75  4560.7  421.27  4672.5  416.95  4731.2  415.73  4739.6  414.84
  4748.0  415.24  4789.5  414.08  4798.3  414.53  4873.7  413.23  4882.1  412.32
  4904.5  413.79  4940.8  413.92  4949.2  413.07  4988.1  413.50  4995.7  413.03
  5005.8  410.75  5010.4  410.48  5013.2  409.98  5016.4  410.48  5026.1  413.01
  5056.5  414.27  5066.6  416.51  5086.9  418.17  5249.1  425.65  5289.7  426.73
#Mann=4,-1,0
  4426.5    0.05       0  4789.5    0.16       0  5010.4    0.07       0
  5016.4    0.16       0
Bank Sta=5010.4,5016.4
Exp/Cntr=0.3,0.1

Type RM Length L Ch R = 1,7055,520,520,520
BEGIN DESCRIPTION:
UNT043 IN CCTC 5.0
END DESCRIPTION:
XS GIS Cut Line= 3
      3508399.58     10615060.21      3508699.61     10614760.19
      3508899.63     10614460.15
#Sta/Elev= 30
  4582.7  420.15  4611.0  418.98  4625.2  417.87  4738.3  414.72  4752.4  413.80
  4780.7  413.68  4876.7  411.60  4936.3  410.80  4992.9  411.07  5000.5  409.04
  5003.2  408.54  5006.5  409.04  5010.0  409.04  5014.5  410.69  5020.5  411.08
  5071.6  410.96  5079.1  411.70  5086.6  411.77  5092.6  411.03  5107.7  410.87
  5143.7  411.31  5164.7  412.93  5179.8  412.95  5209.8  415.37  5245.9  416.81
  5266.9  418.44  5272.9  419.36  5324.0  421.72  5345.0  423.45  5367.6  424.36
#Mann=4,-1,0
  4582.7    0.05       0  4876.7    0.16       0  5000.5    0.07       0
  5006.5    0.16       0
Bank Sta=5000.5,5006.5
Exp/Cntr=0.3,0.1

Type RM Length L Ch R = 1,6535,465,465,465
BEGIN DESCRIPTION:
UNT043 IN CCTC 4.0
END DESCRIPTION:
XS GIS Cut Line= 3
      3508649.59     10615310.20      3508949.61     10615110.19
      3509249.62     10614960.18
#Sta/Elev= 30
  4653.9  415.17  4702.2  413.87  4773.9  412.46  4798.1  412.31  4805.7  411.61
  4811.7  411.87  4823.7  411.42  4856.7  410.02  4862.7  410.21  4919.8  408.67
  4928.8  407.82  4955.9  409.27  4970.9  409.56  4985.9  407.46  4988.9  402.61
  4991.7  402.11  4994.9  402.61  5001.0  402.75  5007.0  406.94  5017.3  407.30
  5022.9  405.11  5028.4  408.60  5036.8  408.96  5045.2  404.09  5050.8  408.53
  5127.1  409.94  5246.5  413.84  5268.8  415.03  5291.2  415.35  5349.9  417.82
#Mann=7,-1,0
  4653.9    0.05       0  4702.2    0.16       0  4773.9    0.05       0
  4823.7    0.12       0  4988.9    0.07       0  4994.9    0.12       0
  5127.1    0.16       0
Bank Sta=4988.9,4994.9
Exp/Cntr=0.3,0.1

Type RM Length L Ch R = 1,6070,666,666,666
BEGIN DESCRIPTION:
UNT043 IN CCTC 3.0
END DESCRIPTION:
XS GIS Cut Line= 3
      3508749.62     10615760.18      3509349.61     10615260.19
      3509449.60     10614960.23
#Sta/Elev= 30
  4209.8  423.39  4225.7  422.79  4237.8  421.48  4348.2  418.46  4564.5  410.24
  4678.4  407.98  4685.6  405.81  4692.1  406.52  4699.9  403.53  4714.2  401.07
  4735.0  407.01  4749.3  406.78  4770.2  404.23  4792.1  406.61  4891.2  406.67
  4899.0  403.93  4919.9  402.65  4939.4  406.44  4977.1  406.30  4983.7  405.36
  4987.6  403.21  4993.4  403.21  4998.4  399.25  5001.1  398.75  5004.4  399.25
  5011.9  405.74  5033.0  407.79  5075.1  410.77  5170.0  414.16  5307.0  422.65
#Mann=7,-1,0
  4209.8    0.16       0  4225.7    0.05       0  4348.2    0.16       0
  4792.1    0.12       0  4939.4    0.16       0  4998.4    0.07       0
  5004.4    0.16       0
Bank Sta=4998.4,5004.4
Exp/Cntr=0.3,0.1

Type RM Length L Ch R = 1,5404,651,651,651
BEGIN DESCRIPTION:
Mapping XS eac9d405
END DESCRIPTION:
XS GIS Cut Line= 3
      3509305.83     10616097.54      3509757.22     10615689.56
      3509679.14     10615064.86
#Sta/Elev= 30
  4230.5  415.94  4252.4  415.61  4266.6  414.33  4307.6  413.13  4380.1  411.15
  4429.5  408.99  4455.9  408.85  4683.3  404.07  4769.5  402.61  4804.6  403.40
  4833.0  402.56  4908.9  403.38  4929.0  402.74  4937.3  400.46  4942.4  400.56
  4949.2  402.43  4959.2  401.23  4969.3  401.52  4989.5  399.13  4996.6  395.00
  4999.3  394.50  5002.6  395.00  5029.8  403.96  5038.5  403.92  5160.8  407.21
  5221.3  409.95  5259.8  412.45  5281.7  412.97  5392.6  419.56  5468.5  422.21
#Mann=7,-1,0
  4230.5    0.16       0  4307.6    0.05       0  4455.9    0.16       0
  4683.3    0.12       0  4996.6    0.07       0  5002.6    0.12       0
  5038.5    0.16       0
Bank Sta=4996.6,5002.6
Exp/Cntr=0.3,0.1

Type RM Length L Ch R = 1,4753,1362,1362,1362
BEGIN DESCRIPTION:
UNT043 IN CCTC 2.0
END DESCRIPTION:
XS GIS Cut Line= 4
      3509391.66     10616195.91      3510259.73     10615631.67
      3510270.58     10615165.09      3509684.67     10614872.13
#Sta/Elev= 30
  3613.5  415.13  3652.2  413.10  3667.3  414.47  3747.6  412.55  3920.4  407.93
  4277.4  401.48  4505.6  400.43  4527.9  401.28  4636.6  399.60  4989.2  400.55
  4990.4  400.52  4997.4  393.49  5000.2  392.99  5003.4  393.49  5010.4  400.60
  5040.4  401.04  5087.2  399.80  5110.4  397.36  5150.2  400.32  5217.1  400.52
  5297.6  402.54  5364.7  405.31  5463.2  411.32  5523.0  413.13  5542.5  414.46
  5552.7  415.74  5566.0  415.21  5677.8  419.17  5709.2  421.47  5770.6  422.83
#Mann=11,-1,0
  3613.5    0.16       0  3747.6    0.05       0  3920.4    0.16       0
  4277.4    0.12       0  4989.2    0.16       0  4997.4    0.07       0
  5003.4    0.16       0  5087.2    0.05       0  5217.1    0.16       0
  5523.0    0.05       0  5542.5    0.16       0
Bank Sta=4997.4,5003.4
Exp/Cntr=0.3,0.1

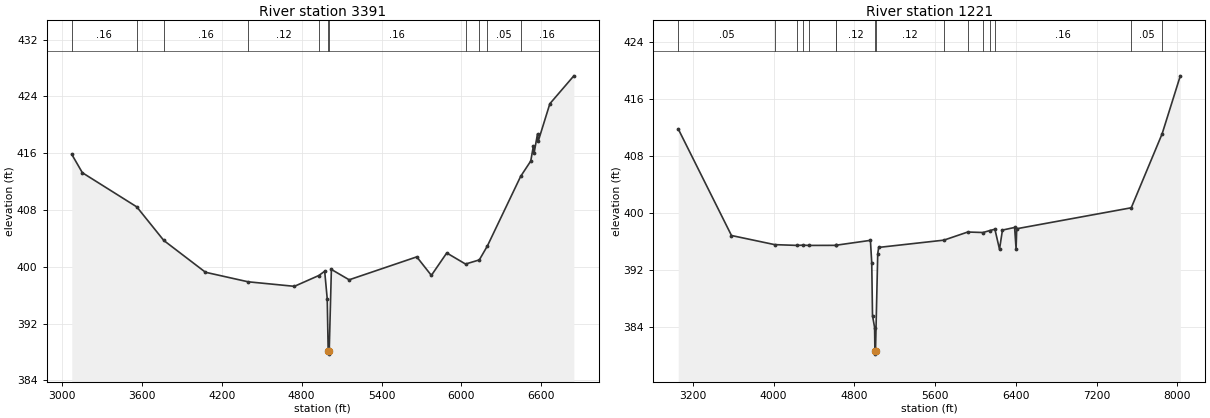
Type RM Length L Ch R = 1,3391,2170,2170,2170
BEGIN DESCRIPTION:
Mapping XS 11729d3e
END DESCRIPTION:
XS GIS Cut Line= 5
      3509509.85     10616748.57      3510933.44     10615884.87
      3511041.95     10615489.90      3510402.77     10615089.37
      3509514.49     10614775.22
#Sta/Elev= 30
  3073.2  415.84  3152.9  413.25  3561.5  408.44  3764.5  403.71  4077.6  399.23
  4397.2  397.89  4745.5  397.25  4928.4  398.77  4972.9  399.37  4992.0  395.49
  4999.1  388.20  5001.8  387.70  5005.1  388.20  5007.3  388.43  5023.2  399.63
  5156.7  398.17  5664.6  401.40  5774.2  398.79  5889.7  401.95  6030.8  400.39
  6134.3  400.97  6195.6  402.96  6444.7  412.73  6520.8  414.90  6540.6  417.03
  6545.9  416.03  6571.5  418.72  6576.8  417.69  6664.2  422.97  6844.4  426.90
#Mann=11,-1,0
  3073.2    0.16       0  3561.5    0.05       0  3764.5    0.16       0
  4397.2    0.12       0  4928.4    0.16       0  4999.1    0.07       0
  5005.1    0.16       0  6030.8    0.05       0  6134.3    0.16       0
  6195.6    0.05       0  6444.7    0.16       0
Bank Sta=4999.1,5005.1
Exp/Cntr=0.3,0.1

Type RM Length L Ch R = 1,1221,0,0,0
BEGIN DESCRIPTION:
UNT043 IN CCTC 1.0
END DESCRIPTION:
XS GIS Cut Line= 5
      3510078.44     10617186.94      3511810.17     10616618.38
      3511949.06     10616114.90      3510533.87     10615032.45
      3509720.78     10614794.70
#Sta/Elev= 30
  3055.4  411.74  3582.9  396.79  4010.7  395.51  4236.4  395.40  4291.2  395.44
  4346.1  395.40  4614.4  395.41  4620.4  395.43  4959.2  396.11  4972.4  392.96
  4979.9  385.56  5000.7  383.88  5003.7  380.65  5006.5  380.15  5009.7  380.65
  5031.8  394.25  5041.1  395.12  5687.3  396.14  5923.7  397.28  6074.8  397.21
  6143.3  397.49  6192.4  397.67  6238.1  394.86  6267.2  397.55  6387.7  397.92
  6402.3  394.91  6408.5  397.74  7543.3  400.68  7848.9  411.05  8029.2  419.19
#Mann=16,-1,0
  3055.4    0.05       0  4010.7    0.16       0  4236.4    0.05       0
  4291.2    0.16       0  4346.1    0.12       0  4614.4    0.16       0
  4620.4    0.12       0  5003.7    0.07       0  5009.7    0.12       0
  5687.3    0.16       0  5923.7    0.12       0  6074.8    0.16       0
  6143.3    0.12       0  6192.4    0.16       0  7543.3    0.05       0
  7848.9    0.16       0
Bank Sta=5003.7,5009.7
Exp/Cntr=0.3,0.1

Chan Stop Cuts=-1