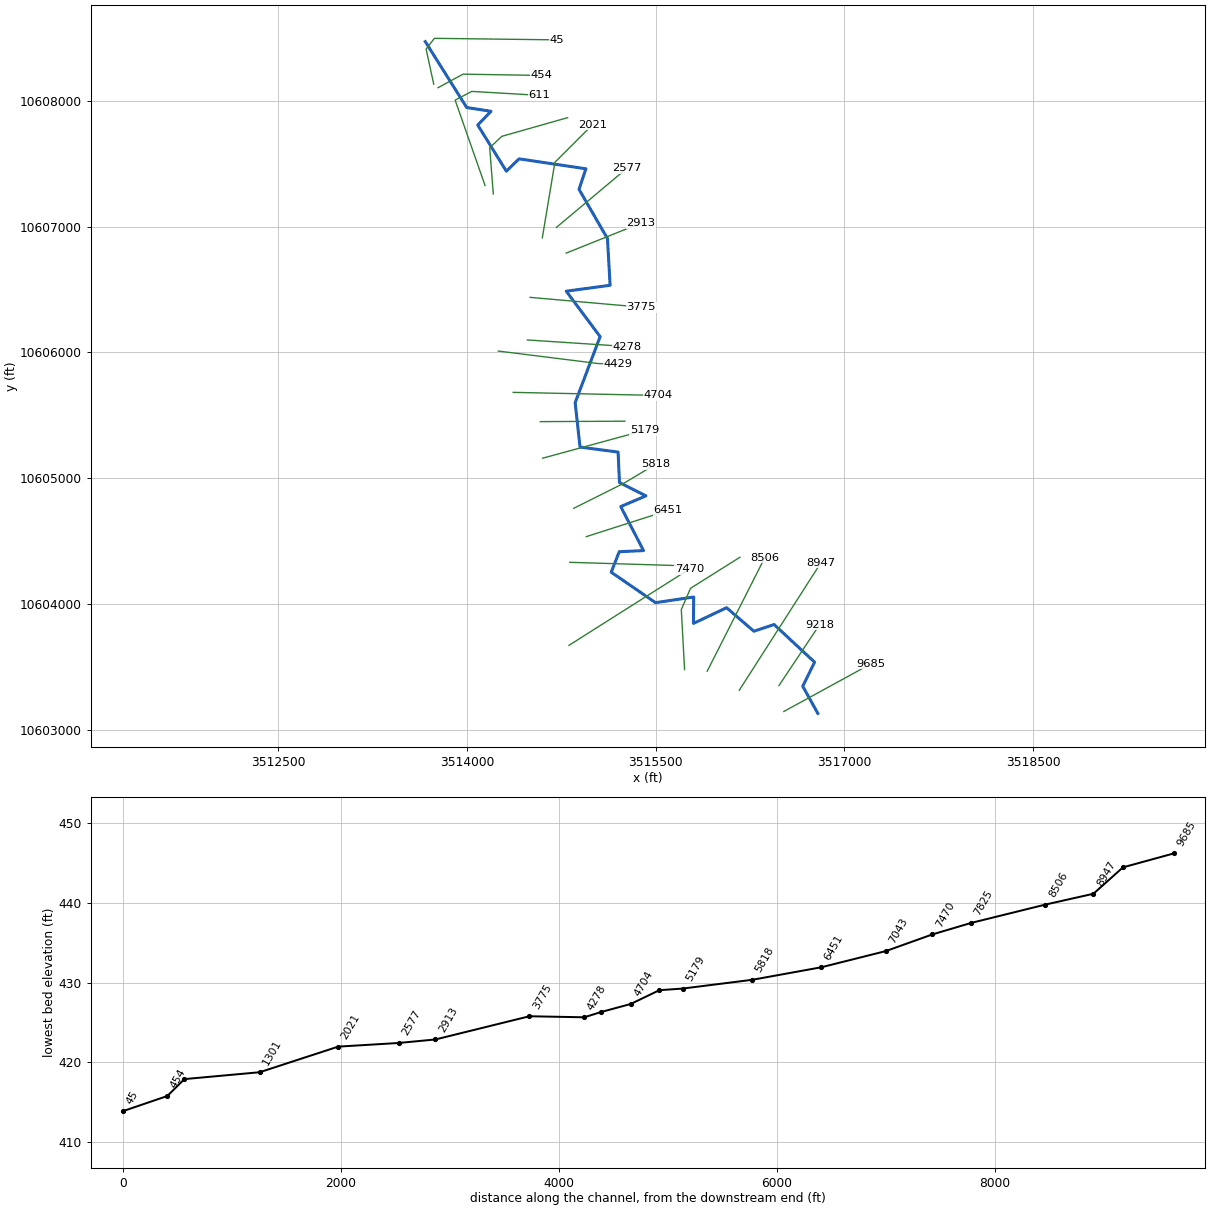
--- UNT044 IN CCTC.prj (project) ---

Proj Title=UNT044 IN CCTC Base Level Engineering
Current Plan=p01
Default Exp/Contr=0.3,0.1
English Units
Geom File=g01
Flow File=f01
Plan File=p01
Y Axis Title=Elevation
X Axis Title(PF)=Main Channel Distance
X Axis Title(XS)=Station
BEGIN DESCRIPTION:
UNT044 IN CCTC
END DESCRIPTION:
DSS Export Rating Curves= 0
DSS Export Rating Curve Sorted= 0
DSS Export Volume Flow Curves= 0
DXF OffsetX= 0
DXF OffsetY= 0
DXF ScaleX= 1
DXF ScaleY= 10

--- UNT044 IN CCTC.p01 (plan) ---

Plan Title=Multiple Run
Short Identifier=Multiple
Geom File=g01
Flow File=f01
Subcritical Flow
K Sum by GR= 0
Std Step Tol= 0.01
Critical Tol= 0.01
Num of Std Step Trials= 20
Max Error Tol= 0.3
Flow Tol Ratio= 0.001
Split Flow NTrial= 30
Split Flow Tol= 0.02
Split Flow Ratio= 0.02
Log Output Level= 0
Friction Slope Method= 1
Unsteady Friction Slope Method= 2
Unsteady Bridges Friction Slope Method= 1
Parabolic Critical Depth
Global Vel Dist=  1 , 1 , 1
Global Log Level= 0
CheckData=True
Encroach Param= -1, 0, 0, 0
BEGIN DESCRIPTION:
Multiple Run
END DESCRIPTION:

--- UNT044 IN CCTC.f01 (steady flow) ---

Flow Title=Multiple
Number of Profiles=7
Profile Names=10-year,25-year,50-year,1pct_min,100-year,1pct_plu,500-year
River Rch & RM= UNT044 IN CCTC,Reach-1,9685
    2054    2890    3594    3255    4402    5953    6591
Boundary for River Rch & Prof#=UNT044 IN CCTC,Reach-1,1
Up Type=0
Dn Type=3
Dn Slope=0.005
Boundary for River Rch & Prof#=UNT044 IN CCTC,Reach-1,2
Up Type=0
Dn Type=3
Dn Slope=0.005
Boundary for River Rch & Prof#=UNT044 IN CCTC,Reach-1,3
Up Type=0
Dn Type=3
Dn Slope=0.005
Boundary for River Rch & Prof#=UNT044 IN CCTC,Reach-1,4
Up Type=0
Dn Type=3
Dn Slope=0.005
Boundary for River Rch & Prof#=UNT044 IN CCTC,Reach-1,5
Up Type=0
Dn Type=3
Dn Slope=0.005
Boundary for River Rch & Prof#=UNT044 IN CCTC,Reach-1,6
Up Type=0
Dn Type=3
Dn Slope=0.005
Boundary for River Rch & Prof#=UNT044 IN CCTC,Reach-1,7
Up Type=0
Dn Type=3
Dn Slope=0.005

--- UNT044 IN CCTC.g01 (geometry) ---

Geom Title=Existing Conditions

River Reach=UNT044 IN CCTC,Reach-1
Reach XY= 30
      3516789.50     10603130.00      3516669.75     10603346.00
      3516764.00     10603537.00      3516442.50     10603836.00
      3516281.25     10603783.00      3516064.25     10603970.00
      3515801.00     10603845.00      3515802.75     10604055.00
      3515499.50     10604010.00      3515147.50     10604252.00
      3515211.00     10604415.00      3515404.25     10604424.00
      3515223.00     10604774.00      3515423.50     10604859.00
      3515213.00     10604965.00      3515202.00     10605207.00
      3514899.25     10605247.00      3514860.75     10605600.00
      3515059.25     10606125.00      3514789.75     10606486.00
      3515138.50     10606533.00      3515117.50     10606904.00
      3514891.25     10607296.00      3514946.00     10607459.00
      3514415.00     10607538.00      3514313.75     10607440.00
      3514086.25     10607807.00      3514192.25     10607916.00
      3513998.50     10607946.00      3513669.50     10608470.00

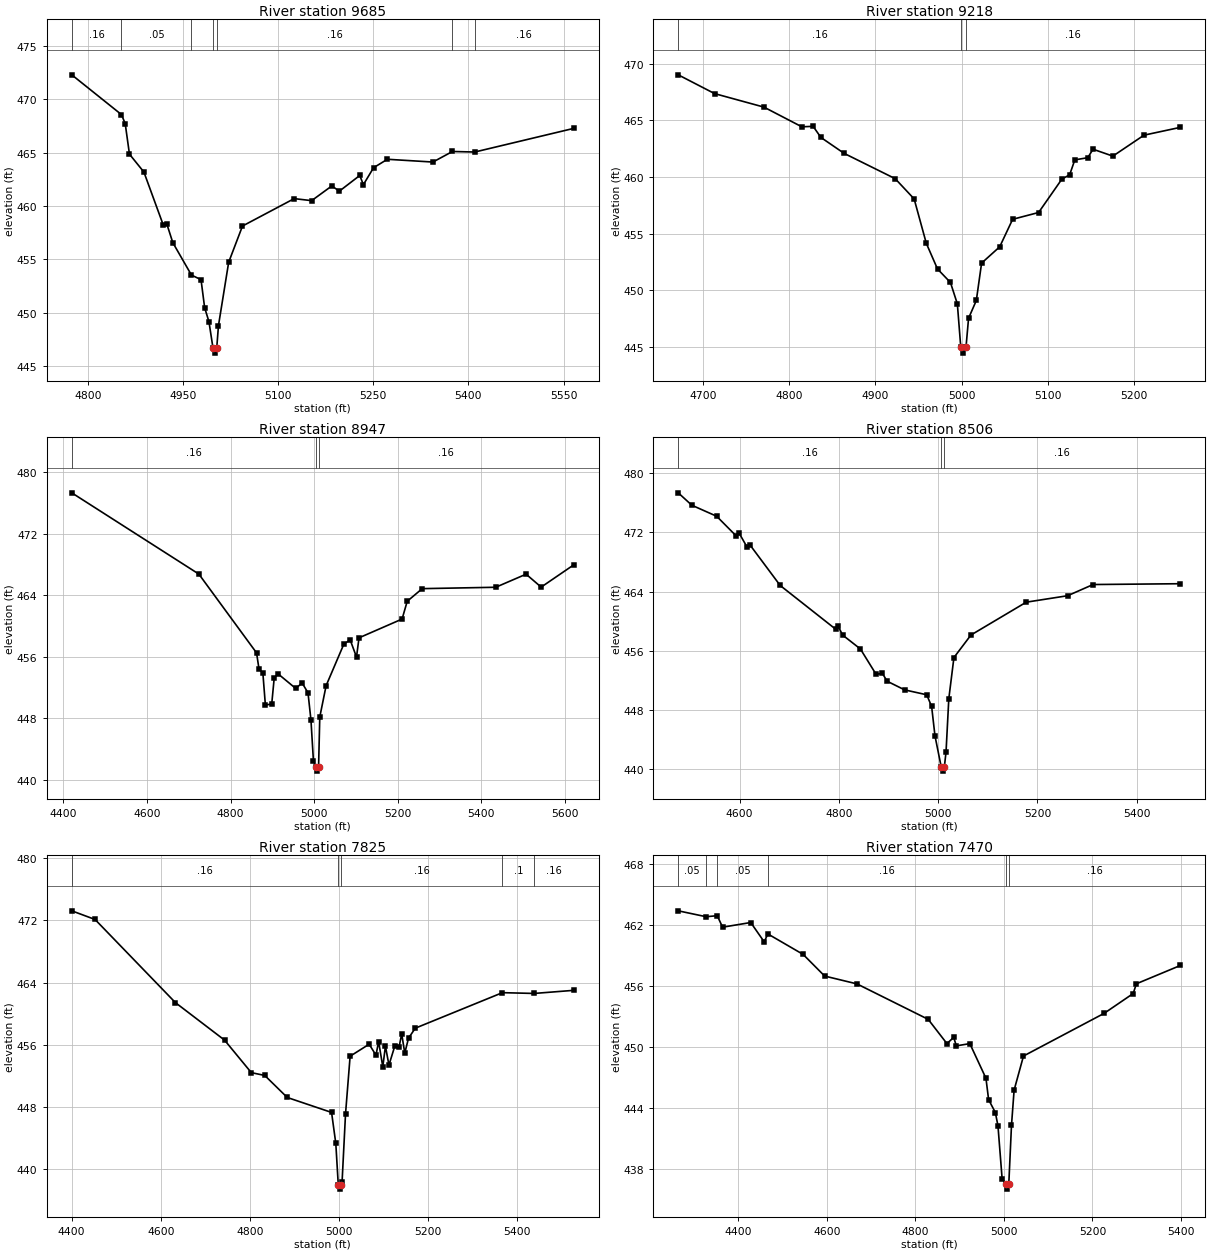
Type RM Length L Ch R = 1,9685,467,467,467
BEGIN DESCRIPTION:
UNT044 IN CCTC 19.0
END DESCRIPTION:
XS GIS Cut Line= 2
      3516519.74     10603145.19      3517214.63     10603525.17
#Sta/Elev= 30
  4774.3  472.29  4852.7  468.56  4858.6  467.71  4865.3  464.85  4888.1  463.17
  4918.4  458.24  4924.1  458.33  4933.7  456.55  4963.1  453.51  4978.2  453.08
  4983.9  450.45  4990.7  449.14  4997.0  446.69  4999.7  446.19  5003.0  446.69
  5005.7  448.77  5021.8  454.71  5043.6  458.11  5125.2  460.68  5152.7  460.49
  5184.5  461.87  5196.4  461.38  5228.6  462.85  5234.3  461.99  5250.4  463.58
  5272.2  464.37  5344.0  464.11  5374.8  465.10  5410.0  465.05  5566.3  467.27
#Mann=7,-1,0
  4774.3    0.16       0  4852.7    0.05       0  4963.1    0.16       0
  4997.0    0.07       0  5003.0    0.16       0  5374.8    0.05       0
  5410.0    0.16       0
Bank Sta=4997,5003
Exp/Cntr=0.3,0.1

Type RM Length L Ch R = 1,9218,271,271,271
BEGIN DESCRIPTION:
UNT044 IN CCTC 18.0
END DESCRIPTION:
XS GIS Cut Line= 2
      3516480.66     10603350.92      3516803.55     10603835.25
#Sta/Elev= 30
  4671.3  469.02  4713.5  467.36  4770.6  466.17  4814.6  464.43  4827.7  464.47
  4836.7  463.49  4863.7  462.08  4922.8  459.85  4944.8  458.06  4958.9  454.14
  4971.9  451.87  4986.9  450.68  4994.9  448.79  4998.9  444.94  5001.7  444.44
  5004.9  444.94  5007.9  447.52  5016.9  449.09  5023.0  452.39  5044.0  453.83
  5059.0  456.26  5089.1  456.86  5116.1  459.81  5125.1  460.19  5131.1  461.51
  5146.1  461.70  5152.2  462.45  5175.2  461.84  5211.3  463.69  5253.4  464.38
#Mann=3,-1,0
  4671.3    0.16       0  4998.9    0.07       0  5004.9    0.16       0
Bank Sta=4998.9,5004.9
Exp/Cntr=0.3,0.1

Type RM Length L Ch R = 1,8947,441,441,441
BEGIN DESCRIPTION:
UNT044 IN CCTC 17.0
END DESCRIPTION:
XS GIS Cut Line= 2
      3516165.40     10603313.96      3516813.25     10604326.07
#Sta/Elev= 30
  4420.0  477.29  4724.2  466.73  4862.2  456.50  4868.2  454.39  4877.4  453.87
  4883.4  449.71  4898.6  449.86  4904.5  453.22  4913.8  453.77  4956.1  451.87
  4971.3  452.59  4985.4  451.31  4992.5  447.76  4998.4  442.47  5004.7  441.63
  5007.4  441.13  5010.7  441.63  5013.6  448.16  5028.8  452.24  5071.1  457.62
  5086.3  458.19  5101.5  455.95  5107.5  458.45  5210.6  460.89  5222.9  463.20
  5258.8  464.84  5434.7  465.02  5507.4  466.72  5543.5  465.04  5621.7  467.94
#Mann=3,-1,0
  4420.0    0.16       0  5004.7    0.07       0  5010.7    0.16       0
Bank Sta=5004.7,5010.7
Exp/Cntr=0.3,0.1

Type RM Length L Ch R = 1,8506,681,681,681
BEGIN DESCRIPTION:
UNT044 IN CCTC 16.0
END DESCRIPTION:
XS GIS Cut Line= 2
      3515910.17     10603464.97      3516367.63     10604366.89
#Sta/Elev= 30
  4476.5  477.31  4503.8  475.64  4553.9  474.15  4592.9  471.52  4598.5  471.95
  4615.1  469.99  4620.7  470.31  4681.9  464.81  4793.3  458.93  4798.9  459.29
  4807.5  458.13  4843.4  456.25  4874.8  452.85  4887.9  452.94  4897.2  451.90
  4932.5  450.73  4977.0  450.07  4986.9  448.49  4993.6  444.54  5006.4  440.27
  5009.1  439.77  5012.4  440.27  5015.9  442.34  5021.5  449.54  5031.8  455.09
  5066.1  458.13  5177.5  462.56  5260.8  463.43  5312.1  464.94  5487.8  465.05
#Mann=3,-1,0
  4476.5    0.16       0  5006.4    0.07       0  5012.4    0.16       0
Bank Sta=5006.4,5012.4
Exp/Cntr=0.3,0.1

Type RM Length L Ch R = 1,7825,355,355,355
BEGIN DESCRIPTION:
UNT044 IN CCTC 15.0
END DESCRIPTION:
XS GIS Cut Line= 4
      3515730.51     10603478.08      3515704.47     10603954.60
      3515777.38     10604123.87      3516170.60     10604371.26
#Sta/Elev= 30
  4400.5  473.21  4452.7  472.10  4633.0  461.42  4743.1  456.61  4803.2  452.43
  4833.3  452.07  4883.8  449.24  4983.2  447.32  4992.7  443.33  4998.3  437.97
  5001.1  437.47  5004.3  437.97  5006.8  438.42  5014.5  447.13  5024.8  454.54
  5067.5  456.08  5082.8  454.67  5088.7  456.42  5098.1  453.18  5104.0  455.83
  5111.9  453.40  5125.2  455.88  5134.6  455.74  5140.5  457.40  5147.4  454.94
  5155.8  456.86  5171.0  458.14  5366.4  462.70  5437.6  462.60  5526.6  463.00
#Mann=5,-1,0
  4400.5    0.16       0  4998.3    0.07       0  5004.3    0.16       0
  5366.4     0.1       0  5437.6    0.16       0
Bank Sta=4998.3,5004.3
Exp/Cntr=0.3,0.1

Type RM Length L Ch R = 1,7470,427,427,427
BEGIN DESCRIPTION:
UNT044 IN CCTC 14.0
END DESCRIPTION:
XS GIS Cut Line= 2
      3514811.22     10603670.73      3515769.58     10604277.52
#Sta/Elev= 30
  4264.3  463.42  4327.3  462.84  4352.4  462.94  4364.5  461.81  4428.1  462.27
  4458.6  460.36  4466.6  461.15  4546.5  459.13  4595.1  457.00  4668.0  456.23
  4829.0  452.74  4871.4  450.35  4886.6  450.97  4892.6  450.13  4923.1  450.35
  4959.5  446.94  4965.5  444.84  4980.7  443.57  4986.6  442.28  4996.0  437.06
  5005.1  436.53  5007.8  436.03  5011.1  436.53  5017.2  442.32  5023.1  445.77
  5044.3  449.13  5226.5  453.33  5292.1  455.28  5299.4  456.24  5398.6  458.04
#Mann=6,-1,0
  4264.3    0.05       0  4327.3    0.08       0  4352.4    0.05       0
  4466.6    0.16       0  5005.1    0.07       0  5011.1    0.16       0
Bank Sta=5005.1,5011.1
Exp/Cntr=0.3,0.1

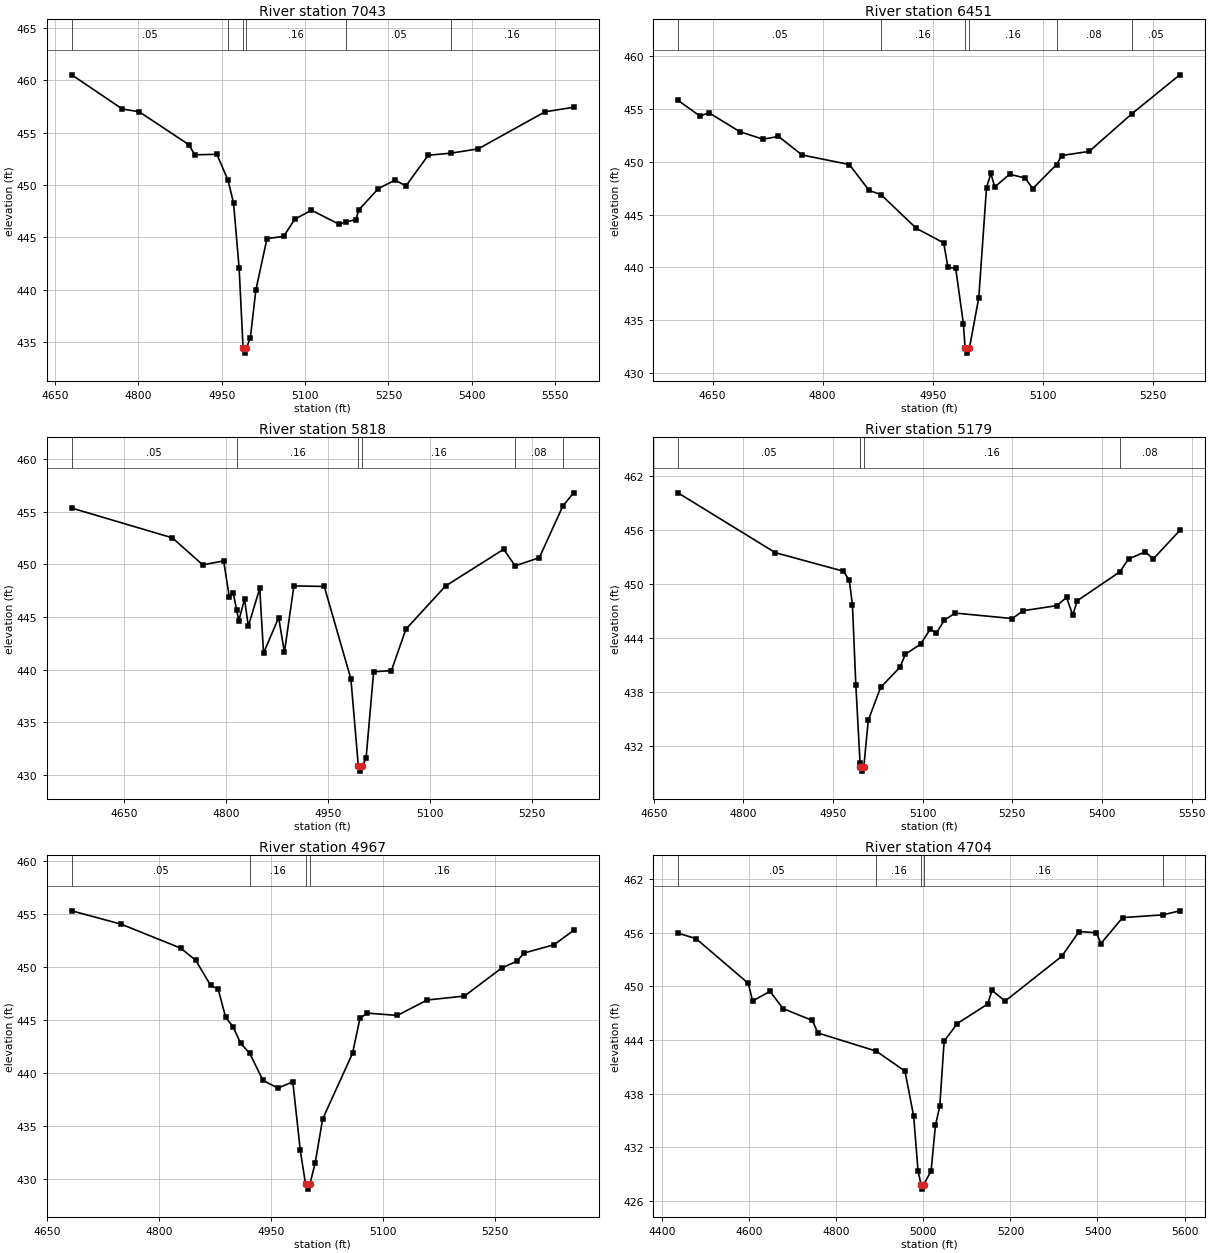
Type RM Length L Ch R = 1,7043,592,592,592
BEGIN DESCRIPTION:
UNT044 IN CCTC 13.0
END DESCRIPTION:
XS GIS Cut Line= 2
      3514818.60     10604330.82      3515720.98     10604303.48
#Sta/Elev= 30
  4680.2  460.52  4771.3  457.25  4801.3  457.00  4891.3  453.83  4901.3  452.88
  4941.3  452.93  4961.3  450.45  4971.3  448.26  4981.3  442.05  4988.4  434.44
  4991.1  433.94  4994.4  434.44  5001.4  435.38  5011.4  439.96  5031.4  444.88
  5061.4  445.09  5081.4  446.73  5111.4  447.59  5161.4  446.24  5172.9  446.47
  5191.4  446.68  5196.4  447.61  5231.5  449.64  5261.5  450.46  5281.5  449.92
  5321.5  452.84  5362.5  453.04  5411.5  453.45  5531.6  456.99  5583.0  457.42
#Mann=6,-1,0
  4680.2    0.05       0  4961.3    0.16       0  4988.4    0.07       0
  4994.4    0.16       0  5172.9    0.05       0  5362.5    0.16       0
Bank Sta=4988.4,4994.4
Exp/Cntr=0.3,0.1

Type RM Length L Ch R = 1,6451,633,633,633
BEGIN DESCRIPTION:
UNT044 IN CCTC 12.0
END DESCRIPTION:
XS GIS Cut Line= 2
      3514949.29     10604535.04      3515600.37     10604743.39
#Sta/Elev= 30
  4602.9  455.78  4632.8  454.30  4645.2  454.60  4687.2  452.82  4718.7  452.11
  4739.8  452.37  4772.0  450.62  4836.3  449.72  4863.2  447.28  4879.6  446.87
  4927.5  443.70  4964.9  442.32  4970.7  440.00  4981.2  439.94  4991.7  434.69
  4994.0  432.41  4996.8  431.91  5000.0  432.41  5012.7  437.15  5023.2  447.54
  5029.2  448.88  5034.4  447.60  5054.7  448.80  5075.7  448.45  5086.2  447.45
  5118.7  449.72  5125.7  450.57  5163.1  450.96  5221.3  454.52  5286.5  458.19
#Mann=6,-1,0
  4602.9    0.05       0  4879.6    0.16       0  4994.0    0.07       0
  5000.0    0.16       0  5118.7    0.08       0  5221.3    0.05       0
Bank Sta=4994,5000
Exp/Cntr=0.3,0.1

Type RM Length L Ch R = 1,5818,639,639,639
BEGIN DESCRIPTION:
UNT044 IN CCTC 11.0
END DESCRIPTION:
XS GIS Cut Line= 3
      3514849.63     10604760.20      3515249.61     10604960.19
      3515499.57     10605110.17
#Sta/Elev= 30
  4572.6  455.35  4720.7  452.52  4765.4  449.95  4796.2  450.33  4804.6  446.85
  4810.2  447.31  4815.2  445.70  4818.5  444.63  4826.9  446.70  4832.5  444.12
  4849.3  447.71  4854.9  441.56  4877.2  444.94  4885.6  441.63  4899.6  447.95
  4944.3  447.90  4983.5  439.10  4994.4  430.84  4997.2  430.34  5000.4  430.84
  5005.8  431.55  5017.0  439.79  5043.1  439.89  5064.5  443.84  5122.8  447.94
  5208.3  451.43  5225.2  449.86  5260.8  450.63  5295.6  455.56  5311.3  456.80
#Mann=6,-1,0
  4572.6    0.05       0  4815.2    0.16       0  4994.4    0.07       0
  5000.4    0.16       0  5225.2    0.08       0  5295.6    0.05       0
Bank Sta=4994.4,5000.4
Exp/Cntr=0.3,0.1

Type RM Length L Ch R = 1,5179,212,212,212
BEGIN DESCRIPTION:
UNT044 IN CCTC 10.0
END DESCRIPTION:
XS GIS Cut Line= 2
      3514602.52     10605158.38      3515412.41     10605379.74
#Sta/Elev= 30
  4690.6  460.12  4853.5  453.48  4967.5  451.42  4977.3  450.40  4982.5  447.68
  4988.2  438.78  4995.3  430.11  4995.6  429.74  4998.3  429.24  5001.6  429.74
  5009.0  434.89  5029.7  438.53  5061.9  440.76  5071.2  442.22  5096.4  443.32
  5112.6  444.98  5123.0  444.56  5136.1  445.97  5154.1  446.78  5250.0  446.17
  5268.1  447.04  5324.2  447.60  5340.7  448.51  5351.1  446.56  5358.7  448.15
  5429.7  451.34  5444.4  452.78  5472.6  453.57  5485.8  452.78  5530.2  455.95
#Mann=5,-1,0
  4690.6    0.05       0  4995.3    0.16       0  4995.6    0.07       0
  5001.6    0.16       0  5429.7    0.08       0
Bank Sta=4995.6,5001.6
Exp/Cntr=0.3,0.1

Type RM Length L Ch R = 1,4967,263,263,263
BEGIN DESCRIPTION:
UNT044 IN CCTC 9.0
END DESCRIPTION:
XS GIS Cut Line= 2
      3514583.44     10605449.11      3515255.83     10605452.58
#Sta/Elev= 30
  4682.8  455.32  4749.0  454.06  4829.0  451.79  4849.0  450.64  4869.0  448.27
  4879.0  447.92  4889.0  445.27  4899.0  444.36  4909.0  442.82  4921.3  441.86
  4939.0  439.31  4959.0  438.58  4979.0  439.17  4989.0  432.70  4996.0  429.54
  4998.7  429.04  5002.0  429.54  5009.0  431.53  5019.0  435.67  5059.0  441.86
  5069.0  445.18  5079.0  445.66  5119.0  445.44  5159.0  446.90  5209.0  447.27
  5259.0  449.93  5279.0  450.55  5289.0  451.34  5329.0  452.12  5355.2  453.47
#Mann=4,-1,0
  4682.8    0.05       0  4921.3    0.16       0  4996.0    0.07       0
  5002.0    0.16       0
Bank Sta=4996,5002
Exp/Cntr=0.3,0.1

Type RM Length L Ch R = 1,4704,275,275,275
BEGIN DESCRIPTION:
Mapping XS 2c4f0788
END DESCRIPTION:
XS GIS Cut Line= 2
      3514368.13     10605681.75      3515520.97     10605657.44
#Sta/Elev= 30
  4436.0  455.95  4477.5  455.34  4597.5  450.34  4607.5  448.36  4647.5  449.44
  4677.5  447.51  4744.9  446.18  4757.6  444.78  4891.7  442.75  4957.6  440.51
  4977.6  435.48  4987.6  429.37  4994.6  427.81  4997.4  427.31  5000.6  427.81
  5017.6  429.34  5027.6  434.43  5037.6  436.60  5047.6  443.86  5077.6  445.83
  5147.6  448.02  5157.6  449.55  5187.6  448.35  5317.7  453.35  5357.7  456.13
  5397.7  456.00  5407.7  454.78  5457.7  457.69  5550.3  458.00  5589.1  458.45
#Mann=5,-1,0
  4436.0    0.05       0  4891.7    0.16       0  4994.6    0.07       0
  5000.6    0.16       0  5550.3    0.05       0
Bank Sta=4994.6,5000.6
Exp/Cntr=0.3,0.1

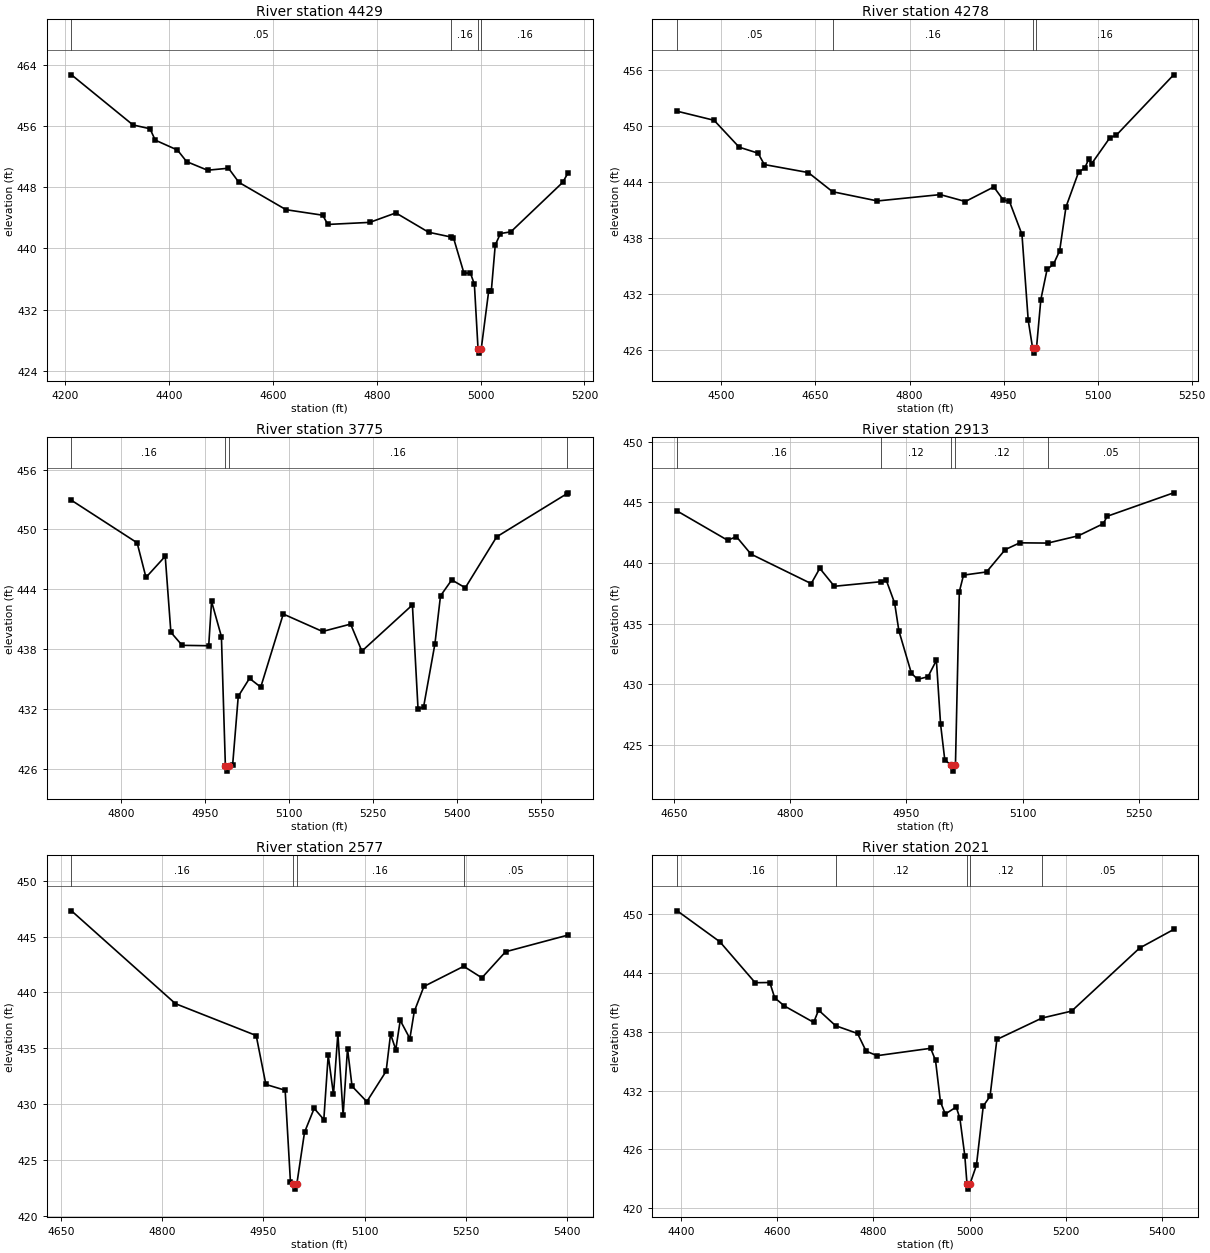
Type RM Length L Ch R = 1,4429,151,151,151
BEGIN DESCRIPTION:
UNT044 IN CCTC 8.0
END DESCRIPTION:
XS GIS Cut Line= 3
      3514249.59     10606010.19      3515049.61     10605910.19
      3515199.57     10605910.19
#Sta/Elev= 30
  4211.9  462.73  4330.3  456.17  4363.1  455.67  4373.2  454.18  4416.0  452.88
  4433.6  451.37  4473.9  450.24  4514.3  450.50  4534.4  448.65  4625.1  445.07
  4695.7  444.35  4705.7  443.14  4786.4  443.41  4836.7  444.65  4899.7  442.12
  4942.4  441.50  4947.6  441.40  4967.8  436.77  4980.3  436.77  4987.9  435.32
  4995.0  426.79  4997.7  426.29  5001.0  426.79  5015.6  434.48  5020.6  434.48
  5028.1  440.44  5038.1  441.95  5058.1  442.17  5158.1  448.65  5168.1  449.87
#Mann=4,-1,0
  4211.9    0.05       0  4942.4    0.16       0  4995.0    0.07       0
  5001.0    0.16       0
Bank Sta=4995,5001
Exp/Cntr=0.3,0.1

Type RM Length L Ch R = 1,4278,503,503,503
BEGIN DESCRIPTION:
UNT044 IN CCTC 7.0
END DESCRIPTION:
XS GIS Cut Line= 2
      3514480.98     10606098.42      3515270.97     10606046.33
#Sta/Elev= 30
  4429.5  451.55  4488.3  450.58  4528.3  447.70  4558.4  447.06  4568.4  445.84
  4638.6  444.98  4677.2  442.93  4748.8  441.94  4849.0  442.62  4889.1  441.88
  4934.4  443.44  4949.3  442.06  4959.3  441.90  4979.3  438.35  4989.3  429.14
  4996.4  426.14  4999.1  425.64  5002.4  426.14  5009.4  431.38  5019.4  434.62
  5029.4  435.14  5039.4  436.60  5049.5  441.30  5069.5  445.01  5079.5  445.48
  5085.6  446.39  5090.6  445.95  5119.6  448.72  5129.6  448.97  5221.2  455.45
#Mann=4,-1,0
  4429.5    0.05       0  4677.2    0.16       0  4996.4    0.07       0
  5002.4    0.16       0
Bank Sta=4996.4,5002.4
Exp/Cntr=0.3,0.1

Type RM Length L Ch R = 1,3775,862,862,862
BEGIN DESCRIPTION:
UNT044 IN CCTC 6.0
END DESCRIPTION:
XS GIS Cut Line= 2
      3514502.72     10606436.96      3515386.38     10606358.99
#Sta/Elev= 30
  4711.5  452.92  4828.8  448.66  4844.6  445.19  4879.0  447.31  4889.1  439.69
  4909.2  438.38  4956.7  438.34  4961.8  442.78  4979.4  439.26  4986.5  426.27
  4989.2  425.77  4992.5  426.27  4999.5  426.41  5009.5  433.27  5029.6  435.07
  5049.7  434.19  5089.9  441.52  5160.1  439.77  5210.3  440.51  5230.4  437.80
  5320.7  442.43  5330.8  431.95  5340.8  432.24  5360.9  438.52  5370.9  443.34
  5391.0  444.94  5415.2  444.15  5471.3  449.26  5597.0  453.59  5598.6  453.67
#Mann=4,-1,0
  4711.5    0.16       0  4986.5    0.07       0  4992.5    0.16       0
  5597.0    0.05       0
Bank Sta=4986.5,4992.5
Exp/Cntr=0.3,0.1

Type RM Length L Ch R = 1,2913,336,336,336
BEGIN DESCRIPTION:
UNT044 IN CCTC 5.0
END DESCRIPTION:
XS GIS Cut Line= 2
      3514789.19     10606788.54      3515383.76     10607027.23
#Sta/Elev= 30
  4654.3  444.29  4719.4  441.88  4730.7  442.18  4749.5  440.74  4827.2  438.31
  4838.3  439.57  4857.1  438.09  4917.7  438.47  4924.1  438.59  4934.9  436.71
  4940.4  434.42  4956.5  430.93  4964.6  430.42  4978.0  430.64  4988.8  431.99
  4994.2  426.73  4999.6  423.80  5007.4  423.36  5010.1  422.86  5013.4  423.36
  5018.4  437.64  5023.8  439.01  5053.5  439.27  5077.6  441.11  5096.4  441.67
  5132.6  441.65  5172.0  442.25  5204.0  443.24  5209.3  443.86  5295.0  445.79
#Mann=5,-1,0
  4654.3    0.16       0  4917.7    0.12       0  5007.4    0.07       0
  5013.4    0.12       0  5132.6    0.05       0
Bank Sta=5007.4,5013.4
Exp/Cntr=0.3,0.1

Type RM Length L Ch R = 1,2577,556,556,556
BEGIN DESCRIPTION:
UNT044 IN CCTC 4.0
END DESCRIPTION:
XS GIS Cut Line= 2
      3514711.04     10606992.52      3515274.72     10607465.15
#Sta/Elev= 30
  4665.5  447.30  4819.5  439.00  4939.2  436.15  4953.5  431.78  4982.1  431.26
  4989.9  423.10  4993.5  422.92  4996.2  422.42  4999.5  422.92  5010.8  427.50
  5025.1  429.64  5039.4  428.64  5045.9  434.40  5053.7  430.88  5060.2  436.33
  5068.0  429.03  5074.5  434.99  5081.2  431.62  5103.1  430.24  5131.7  432.96
  5138.3  436.28  5146.0  434.89  5152.6  437.51  5166.9  435.88  5173.4  438.30
  5187.7  440.54  5246.7  442.34  5273.6  441.31  5308.7  443.64  5401.1  445.13
#Mann=4,-1,0
  4665.5    0.16       0  4993.5    0.07       0  4999.5    0.16       0
  5246.7    0.05       0
Bank Sta=4993.5,4999.5
Exp/Cntr=0.3,0.1

Type RM Length L Ch R = 1,2021,720,720,720
BEGIN DESCRIPTION:
UNT044 IN CCTC 3.0
END DESCRIPTION:
XS GIS Cut Line= 3
      3514599.61     10606910.17      3514699.61     10607510.19
      3514999.64     10607810.22
#Sta/Elev= 30
  4391.9  450.30  4480.6  447.15  4554.1  442.98  4584.5  443.00  4594.7  441.44
  4614.9  440.61  4675.8  438.94  4685.9  440.19  4721.4  438.60  4767.0  437.81
  4784.8  436.01  4807.6  435.55  4919.1  436.30  4929.2  435.07  4939.4  430.85
  4949.5  429.61  4972.3  430.32  4979.9  429.16  4990.1  425.36  4994.7  422.46
  4997.4  421.96  5000.7  422.46  5014.3  424.39  5028.5  430.42  5042.6  431.42
  5056.8  437.20  5150.6  439.38  5212.3  440.09  5353.7  446.51  5424.5  448.40
#Mann=5,-1,0
  4391.9    0.16       0  4721.4    0.12       0  4994.7    0.07       0
  5000.7    0.12       0  5150.6    0.05       0
Bank Sta=4994.7,5000.7
Exp/Cntr=0.3,0.1

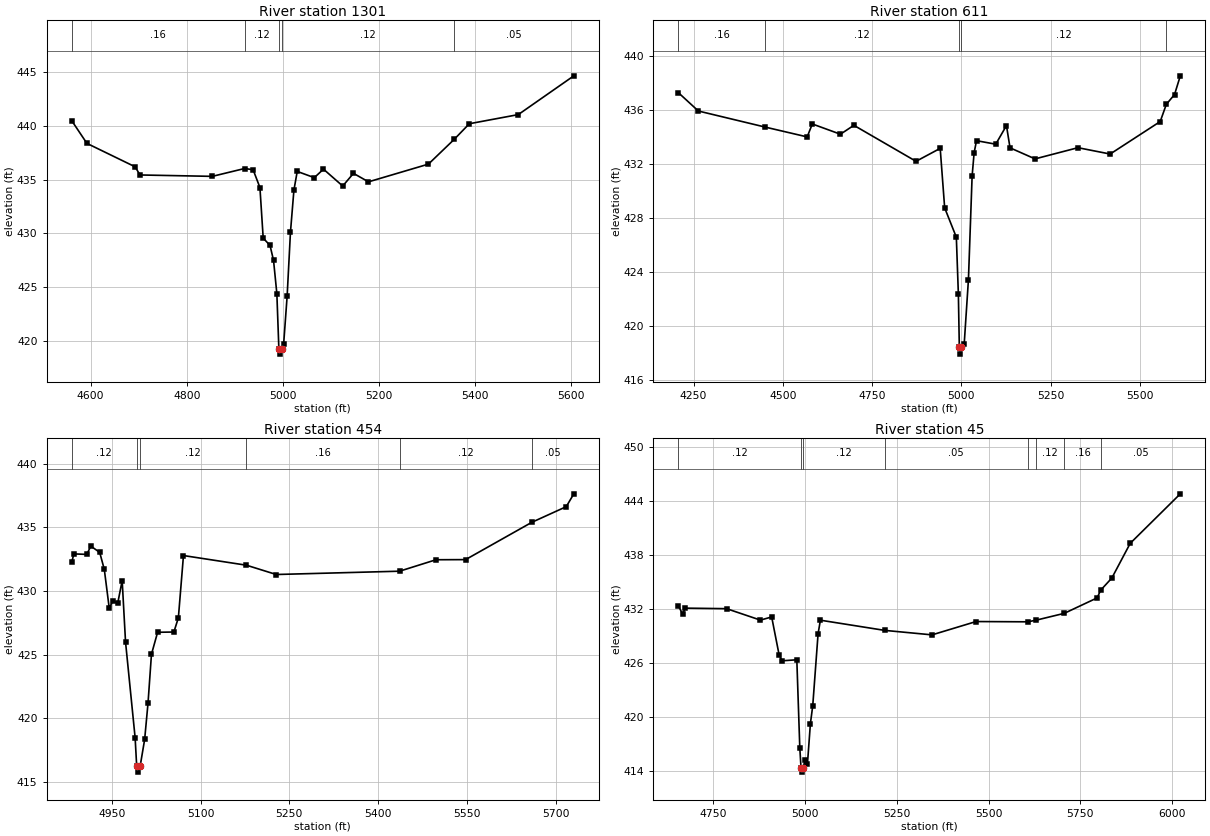
Type RM Length L Ch R = 1,1301,690,690,690
BEGIN DESCRIPTION:
UNT044 IN CCTC 2.0
END DESCRIPTION:
XS GIS Cut Line= 4
      3514210.12     10607258.75      3514181.47     10607625.96
      3514277.83     10607717.11      3514800.65     10607865.37
#Sta/Elev= 30
  4560.8  440.48  4592.3  438.37  4692.6  436.19  4702.7  435.43  4853.1  435.30
  4920.2  436.03  4938.0  435.92  4952.2  434.26  4959.0  429.55  4973.2  428.87
  4980.5  427.48  4987.4  424.39  4991.6  419.25  4994.4  418.75  4997.6  419.25
  5001.5  419.67  5008.8  424.15  5015.7  430.10  5022.9  434.02  5029.8  435.76
  5065.3  435.18  5084.4  435.97  5124.4  434.40  5146.8  435.58  5178.0  434.79
  5302.7  436.44  5356.2  438.74  5387.8  440.20  5489.6  441.05  5605.2  444.66
#Mann=5,-1,0
  4560.8    0.16       0  4920.2    0.12       0  4991.6    0.07       0
  4997.6    0.12       0  5356.2    0.05       0
Bank Sta=4991.6,4997.6
Exp/Cntr=0.3,0.1

Type RM Length L Ch R = 1,611,157,157,157
BEGIN DESCRIPTION:
Mapping XS 4dd8c0be
END DESCRIPTION:
XS GIS Cut Line= 4
      3514144.60     10607325.84      3513906.75     10608004.68
      3514038.69     10608074.12      3514575.79     10608042.93
#Sta/Elev= 30
  4207.2  437.29  4263.6  435.92  4450.5  434.73  4568.4  434.00  4582.7  434.96
  4661.5  434.20  4699.2  434.86  4873.3  432.19  4941.0  433.15  4953.5  428.74
  4986.2  426.56  4991.9  422.34  4994.6  418.39  4997.3  417.89  5000.6  418.39
  5008.3  418.67  5020.1  423.42  5030.4  431.09  5036.0  432.82  5042.7  433.72
  5096.6  433.46  5126.6  434.84  5136.6  433.19  5206.7  432.37  5326.9  433.20
  5417.1  432.73  5557.3  435.14  5574.5  436.42  5597.4  437.14  5613.6  438.53
#Mann=5,-1,0
  4207.2    0.16       0  4450.5    0.12       0  4994.6    0.07       0
  5000.6    0.12       0  5574.5    0.05       0
Bank Sta=4994.6,5000.6
Exp/Cntr=0.3,0.1

Type RM Length L Ch R = 1,454,409,409,409
BEGIN DESCRIPTION:
Mapping XS 15332f08
END DESCRIPTION:
XS GIS Cut Line= 3
      3513771.32     10608103.63      3513969.25     10608211.27
      3514592.56     10608200.86
#Sta/Elev= 30
  4882.2  432.27  4885.7  432.92  4907.6  432.88  4914.4  433.53  4929.4  433.04
  4937.2  431.70  4945.6  428.63  4951.2  429.21  4959.9  429.05  4967.4  430.82
  4973.1  425.99  4989.3  418.47  4991.9  416.27  4994.7  415.77  4997.9  416.27
  5005.4  418.34  5011.1  421.20  5016.9  425.03  5027.3  426.76  5054.8  426.78
  5062.4  427.90  5071.0  432.79  5177.5  432.03  5227.9  431.30  5436.3  431.56
  5497.9  432.46  5547.9  432.47  5659.8  435.40  5718.0  436.63  5730.9  437.64
#Mann=6,-1,0
  4882.2    0.12       0  4991.9    0.07       0  4997.9    0.12       0
  5177.5    0.16       0  5436.3    0.12       0  5659.8    0.05       0
Bank Sta=4991.9,4997.9
Exp/Cntr=0.3,0.1

Type RM Length L Ch R = 1,45,0,0,0
BEGIN DESCRIPTION:
UNT044 IN CCTC 1.0
END DESCRIPTION:
XS GIS Cut Line= 4
      3513736.60     10608131.43      3513675.84     10608410.93
      3513741.82     10608495.99      3514716.07     10608483.86
#Sta/Elev= 30
  4654.5  432.37  4666.2  431.43  4673.7  432.08  4786.3  432.02  4878.4  430.75
  4909.1  431.10  4929.5  426.86  4937.6  426.23  4977.6  426.34  4985.7  416.59
  4989.0  414.36  4991.7  413.86  4995.0  414.36  5000.2  415.25  5006.5  414.74
  5014.6  419.25  5021.0  421.24  5035.5  429.22  5041.8  430.74  5216.8  429.61
  5346.0  429.11  5466.0  430.59  5607.2  430.56  5630.3  430.75  5706.2  431.50
  5796.0  433.22  5805.2  434.06  5836.0  435.43  5886.0  439.28  6022.5  444.78
#Mann=8,-1,0
  4654.5    0.12       0  4989.0    0.07       0  4995.0    0.12       0
  5216.8    0.05       0  5607.2    0.16       0  5630.3    0.12       0
  5706.2    0.16       0  5805.2    0.05       0
Bank Sta=4989,4995
Exp/Cntr=0.3,0.1

Chan Stop Cuts=-1