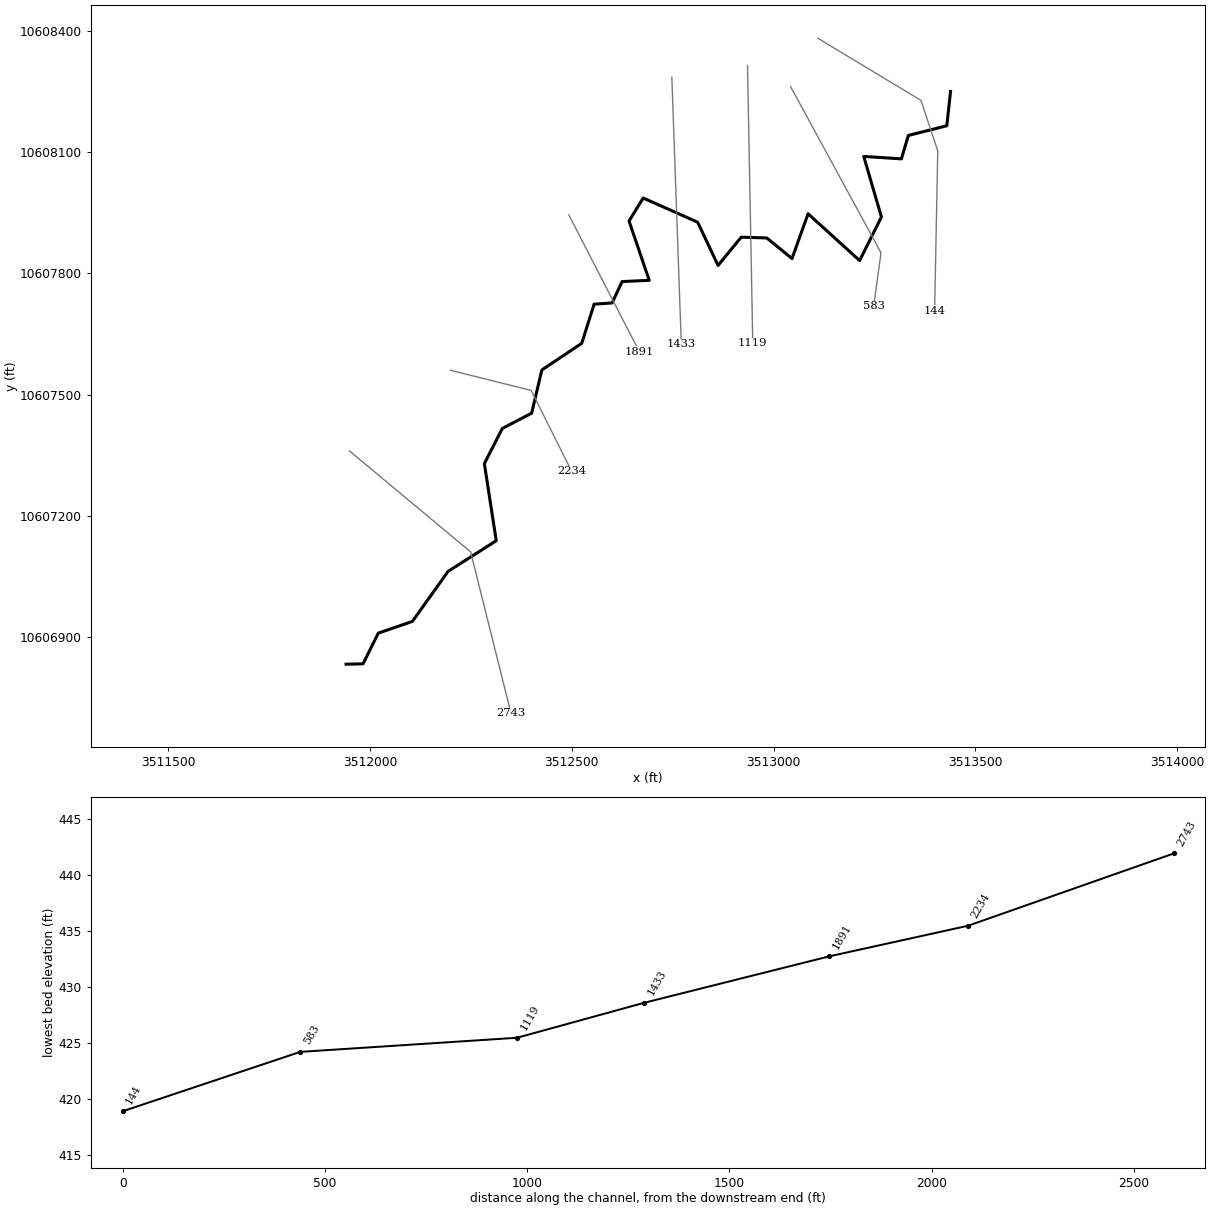
--- UNT046 IN CCTC.prj (project) ---

Proj Title=UNT046 IN CCTC Base Level Engineering
Current Plan=p01
Default Exp/Contr=0.3,0.1
English Units
Geom File=g01
Flow File=f01
Plan File=p01
BEGIN DESCRIPTION:
UNT046 IN CCTC
END DESCRIPTION:

--- UNT046 IN CCTC.p01 (plan) ---

Plan Title=Multiple Run
Short Identifier=Multiple
Geom File=g01
Flow File=f01
Subcritical Flow
K Sum by GR= 0
Std Step Tol= 0.01
Critical Tol= 0.01
Num of Std Step Trials= 20
Max Error Tol= 0.3
Flow Tol Ratio= 0.001
Split Flow NTrial= 30
Split Flow Tol= 0.02
Split Flow Ratio= 0.02
Log Output Level= 0
Friction Slope Method= 1
Unsteady Friction Slope Method= 2
Unsteady Bridges Friction Slope Method= 1
Parabolic Critical Depth
Global Vel Dist=  1 , 1 , 1
Global Log Level= 0
CheckData=True
Encroach Param= -1, 0, 0, 0
BEGIN DESCRIPTION:
Multiple Run
END DESCRIPTION:

--- UNT046 IN CCTC.f01 (steady flow) ---

Flow Title=Multiple
Number of Profiles=7
Profile Names=10-year,25-year,50-year,1pct_min,100-year,1pct_plu,500-year
River Rch & RM= UNT046 IN CCTC,Reach-1,2743
     383     487     567     483     654     884     864
Boundary for River Rch & Prof#=UNT046 IN CCTC,Reach-1,1
Up Type=0
Dn Type=3
Dn Slope=0.005
Boundary for River Rch & Prof#=UNT046 IN CCTC,Reach-1,2
Up Type=0
Dn Type=3
Dn Slope=0.005
Boundary for River Rch & Prof#=UNT046 IN CCTC,Reach-1,3
Up Type=0
Dn Type=3
Dn Slope=0.005
Boundary for River Rch & Prof#=UNT046 IN CCTC,Reach-1,4
Up Type=0
Dn Type=3
Dn Slope=0.005
Boundary for River Rch & Prof#=UNT046 IN CCTC,Reach-1,5
Up Type=0
Dn Type=3
Dn Slope=0.005
Boundary for River Rch & Prof#=UNT046 IN CCTC,Reach-1,6
Up Type=0
Dn Type=3
Dn Slope=0.005
Boundary for River Rch & Prof#=UNT046 IN CCTC,Reach-1,7
Up Type=0
Dn Type=3
Dn Slope=0.005

--- UNT046 IN CCTC.g01 (geometry) ---

Geom Title=Existing Conditions

River Reach=UNT046 IN CCTC,Reach-1
Reach XY= 30
      3511940.85     10606831.95      3511983.00     10606833.00
      3512020.75     10606909.00      3512105.25     10606938.00
      3512193.75     10607062.00      3512313.00     10607138.00
      3512283.50     10607329.00      3512328.00     10607416.00
      3512400.75     10607454.00      3512426.00     10607561.00
      3512524.75     10607627.00      3512555.50     10607724.00
      3512600.00     10607727.00      3512624.75     10607780.00
      3512692.00     10607783.00      3512642.00     10607930.00
      3512677.00     10607987.00      3512812.00     10607927.00
      3512862.50     10607820.00      3512920.00     10607890.00
      3512983.25     10607888.00      3513045.75     10607837.00
      3513085.50     10607948.00      3513213.25     10607832.00
      3513267.25     10607940.00      3513223.50     10608090.00
      3513316.75     10608084.00      3513334.00     10608142.00
      3513429.25     10608166.00      3513438.50     10608251.00

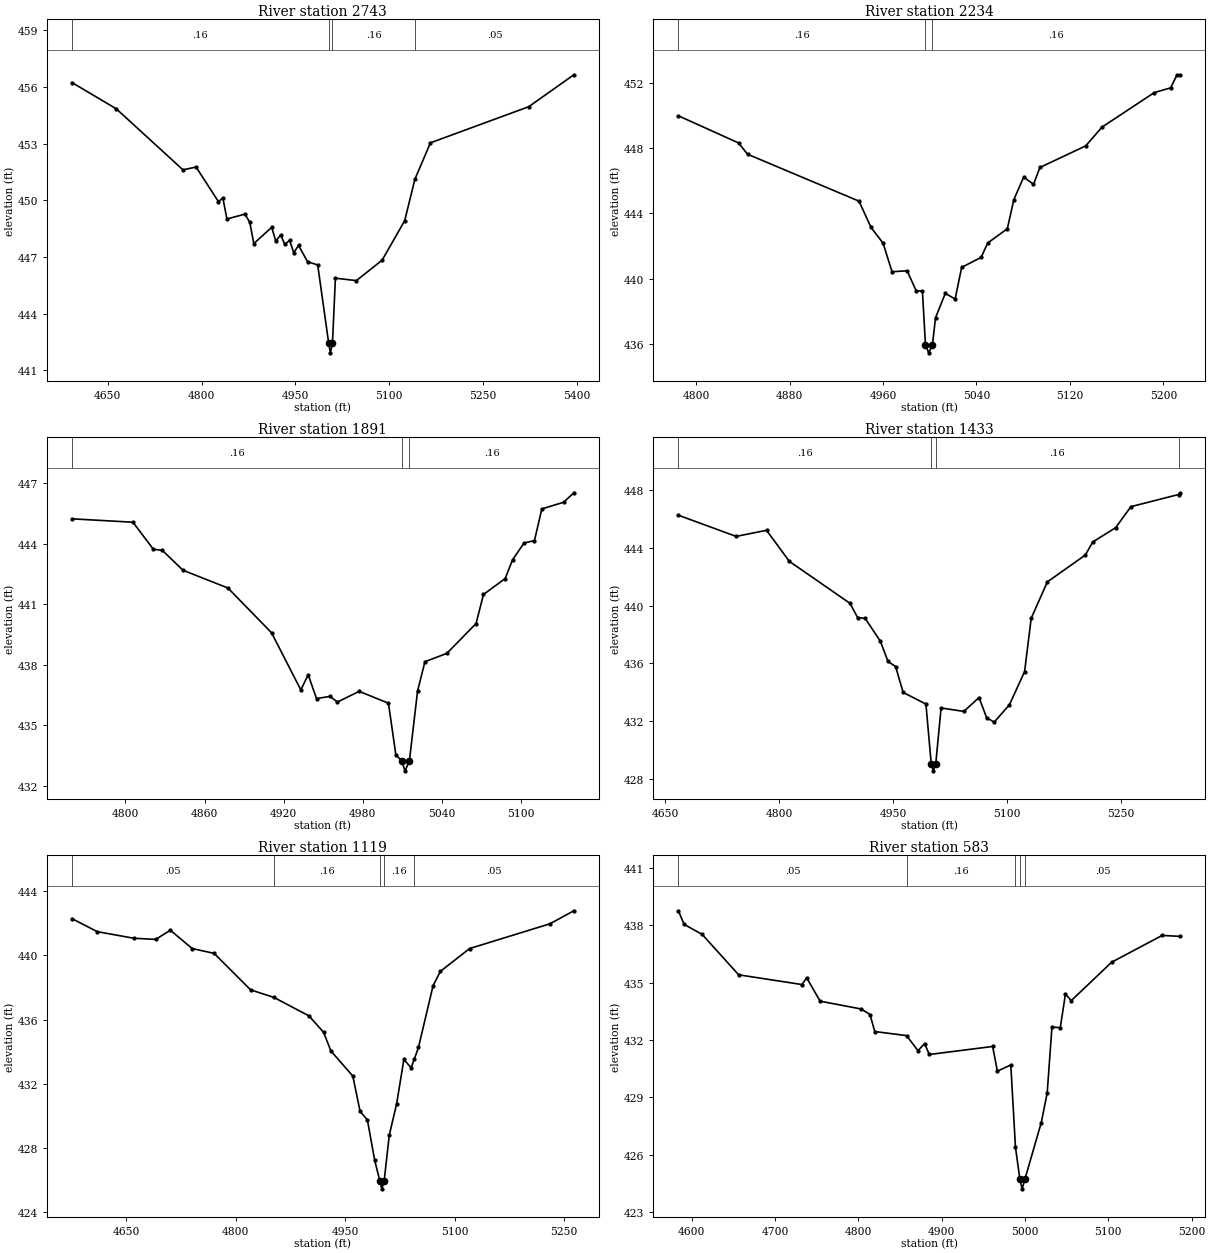
Type RM Length L Ch R = 1,2743,509,509,509
BEGIN DESCRIPTION:
UNT046 IN CCTC 5.0
END DESCRIPTION:
XS GIS Cut Line= 3
      3511949.63     10607360.17      3512249.61     10607110.19
      3512349.61     10606710.18
#Sta/Elev= 30
  4592.7  456.23  4663.6  454.84  4770.3  451.61  4791.2  451.76  4827.0  449.93
  4834.1  450.12  4840.6  449.01  4869.3  449.27  4877.1  448.84  4883.6  447.71
  4912.2  448.57  4918.7  447.84  4926.6  448.17  4933.1  447.67  4940.9  447.88
  4947.4  447.23  4955.2  447.61  4969.5  446.75  4985.8  446.58  5003.4  442.43
  5006.1  441.93  5009.4  442.43  5014.1  445.88  5047.6  445.75  5088.8  446.83
  5124.9  448.92  5141.3  451.12  5166.1  453.04  5323.3  454.95  5395.5  456.64
#Mann=4,-1,0
  4592.7    0.16       0  5003.4    0.07       0  5009.4    0.16       0
  5141.3    0.05       0
Bank Sta=5003.4,5009.4
Exp/Cntr=0.3,0.1

Type RM Length L Ch R = 1,2234,343,343,343
BEGIN DESCRIPTION:
UNT046 IN CCTC 4.0
END DESCRIPTION:
XS GIS Cut Line= 3
      3512199.63     10607560.18      3512399.61     10607510.19
      3512499.59     10607310.22
#Sta/Elev= 30
  4784.8  449.97  4836.3  448.31  4844.0  447.62  4939.4  444.75  4949.7  443.14
  4960.0  442.18  4967.7  440.43  4980.6  440.49  4988.4  439.26  4993.7  439.26
  4996.3  435.97  4999.1  435.47  5002.3  435.97  5004.9  437.61  5013.3  439.11
  5021.7  438.76  5027.3  440.70  5044.0  441.31  5049.6  442.19  5066.4  443.06
  5072.0  444.85  5080.4  446.22  5088.8  445.78  5094.3  446.81  5133.5  448.13
  5147.5  449.28  5192.2  451.39  5206.2  451.68  5211.7  452.48  5214.5  452.48
#Mann=3,-1,0
  4784.8    0.16       0  4996.3    0.07       0  5002.3    0.16       0
Bank Sta=4996.3,5002.3
Exp/Cntr=0.3,0.1

Type RM Length L Ch R = 1,1891,458,458,458
BEGIN DESCRIPTION:
Mapping XS 1f32cfd2
END DESCRIPTION:
XS GIS Cut Line= 2
      3512492.78     10607945.16      3512667.28     10607606.58
#Sta/Elev= 30
  4759.4  445.23  4805.7  445.06  4821.2  443.72  4827.9  443.67  4843.7  442.68
  4877.8  441.80  4910.9  439.58  4933.1  436.75  4938.7  437.50  4945.0  436.32
  4955.2  436.43  4960.9  436.15  4977.4  436.68  4999.6  436.09  5005.2  433.54
  5009.5  433.24  5012.2  432.74  5015.5  433.24  5021.7  436.70  5027.3  438.15
  5043.9  438.56  5066.1  440.04  5071.7  441.48  5088.2  442.27  5093.8  443.20
  5102.5  444.03  5110.4  444.15  5116.0  445.72  5132.5  446.05  5140.3  446.52
#Mann=3,-1,0
  4759.4    0.16       0  5009.5    0.07       0  5015.5    0.16       0
Bank Sta=5009.5,5015.5
Exp/Cntr=0.3,0.1

Type RM Length L Ch R = 1,1433,314,314,314
BEGIN DESCRIPTION:
UNT046 IN CCTC 3.0
END DESCRIPTION:
XS GIS Cut Line= 2
      3512748.01     10608286.27      3512771.44     10607624.98
#Sta/Elev= 30
  4667.1  446.23  4743.2  444.77  4783.3  445.19  4813.3  443.05  4893.3  440.15
  4903.3  439.17  4913.3  439.11  4933.3  437.54  4943.4  436.14  4953.4  435.79
  4963.4  434.00  4993.4  433.20  5000.4  429.09  5003.1  428.59  5006.4  429.09
  5013.4  432.93  5043.4  432.69  5063.4  433.65  5073.4  432.26  5083.4  431.95
  5103.5  433.15  5123.5  435.44  5132.2  439.12  5153.5  441.63  5203.5  443.48
  5213.5  444.39  5243.5  445.37  5263.6  446.82  5326.4  447.66  5328.8  447.78
#Mann=4,-1,0
  4667.1    0.16       0  5000.4    0.07       0  5006.4    0.16       0
  5326.4    0.05       0
Bank Sta=5000.4,5006.4
Exp/Cntr=0.3,0.1

Type RM Length L Ch R = 1,1119,536,536,536
BEGIN DESCRIPTION:
UNT046 IN CCTC 2.0
END DESCRIPTION:
XS GIS Cut Line= 2
      3512935.51     10608314.95      3512948.53     10607627.37
#Sta/Elev= 30
  4575.5  442.28  4610.3  441.47  4660.3  441.06  4690.3  440.99  4710.3  441.56
  4740.3  440.42  4770.3  440.12  4820.3  437.85  4852.2  437.38  4900.3  436.23
  4920.3  435.21  4930.3  434.05  4960.3  432.49  4970.3  430.29  4980.3  429.76
  4990.3  427.25  4997.3  425.97  5000.1  425.47  5003.3  425.97  5010.3  428.81
  5020.3  430.74  5030.3  433.52  5040.3  433.00  5044.8  433.57  5050.3  434.27
  5070.3  438.11  5080.3  439.00  5120.4  440.42  5230.4  441.96  5263.2  442.77
#Mann=5,-1,0
  4575.5    0.05       0  4852.2    0.16       0  4997.3    0.07       0
  5003.3    0.16       0  5044.8    0.05       0
Bank Sta=4997.3,5003.3
Exp/Cntr=0.3,0.1

Type RM Length L Ch R = 1,583,439,439,439
BEGIN DESCRIPTION:
Mapping XS 7687b66c
END DESCRIPTION:
XS GIS Cut Line= 3
      3513042.29     10608262.81      3513266.24     10607851.37
      3513248.01     10607718.56
#Sta/Elev= 30
  4583.9  438.76  4590.7  438.05  4612.5  437.52  4656.2  435.41  4732.2  434.90
  4737.9  435.25  4754.0  434.03  4803.4  433.62  4813.9  433.33  4819.6  432.44
  4857.7  432.23  4871.5  431.44  4879.4  431.81  4885.1  431.24  4961.1  431.66
  4966.8  430.37  4982.9  430.69  4988.5  426.39  4993.8  424.71  4996.5  424.21
  4999.8  424.71  5019.5  427.68  5026.6  429.23  5032.3  432.68  5042.3  432.64
  5048.5  434.40  5055.5  434.06  5104.0  436.07  5164.6  437.47  5186.4  437.42
#Mann=5,-1,0
  4583.9    0.05       0  4857.7    0.16       0  4988.5    0.05       0
  4993.8    0.03       0  4999.8    0.05       0
Bank Sta=4993.8,4999.8
Exp/Cntr=0.3,0.1

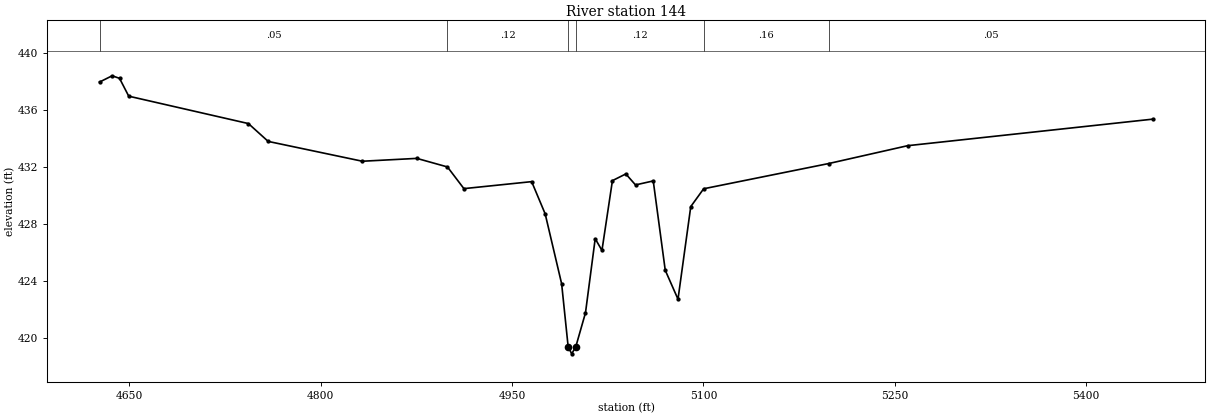
Type RM Length L Ch R = 1,144,0,0,0
BEGIN DESCRIPTION:
UNT046 IN CCTC 1.0
END DESCRIPTION:
XS GIS Cut Line= 4
      3513110.03     10608382.59      3513365.19     10608228.97
      3513406.86     10608103.97      3513399.05     10607708.15
#Sta/Elev= 30
  4626.7  437.96  4636.6  438.40  4642.4  438.22  4649.6  436.97  4743.4  435.05
  4758.9  433.80  4832.7  432.41  4875.4  432.61  4899.4  432.01  4912.3  430.49
  4965.4  430.98  4976.0  428.72  4988.9  423.82  4994.0  419.41  4996.8  418.91
  5000.0  419.41  5007.6  421.79  5015.2  426.98  5020.5  426.16  5028.7  431.05
  5039.2  431.52  5046.8  430.75  5060.7  431.03  5070.1  424.77  5080.1  422.74
  5090.1  429.23  5100.2  430.48  5198.3  432.25  5260.1  433.50  5452.2  435.36
#Mann=6,-1,0
  4626.7    0.05       0  4899.4    0.12       0  4994.0    0.07       0
  5000.0    0.12       0  5100.2    0.16       0  5198.3    0.05       0
Bank Sta=4994,5000
Exp/Cntr=0.3,0.1

Chan Stop Cuts=-1