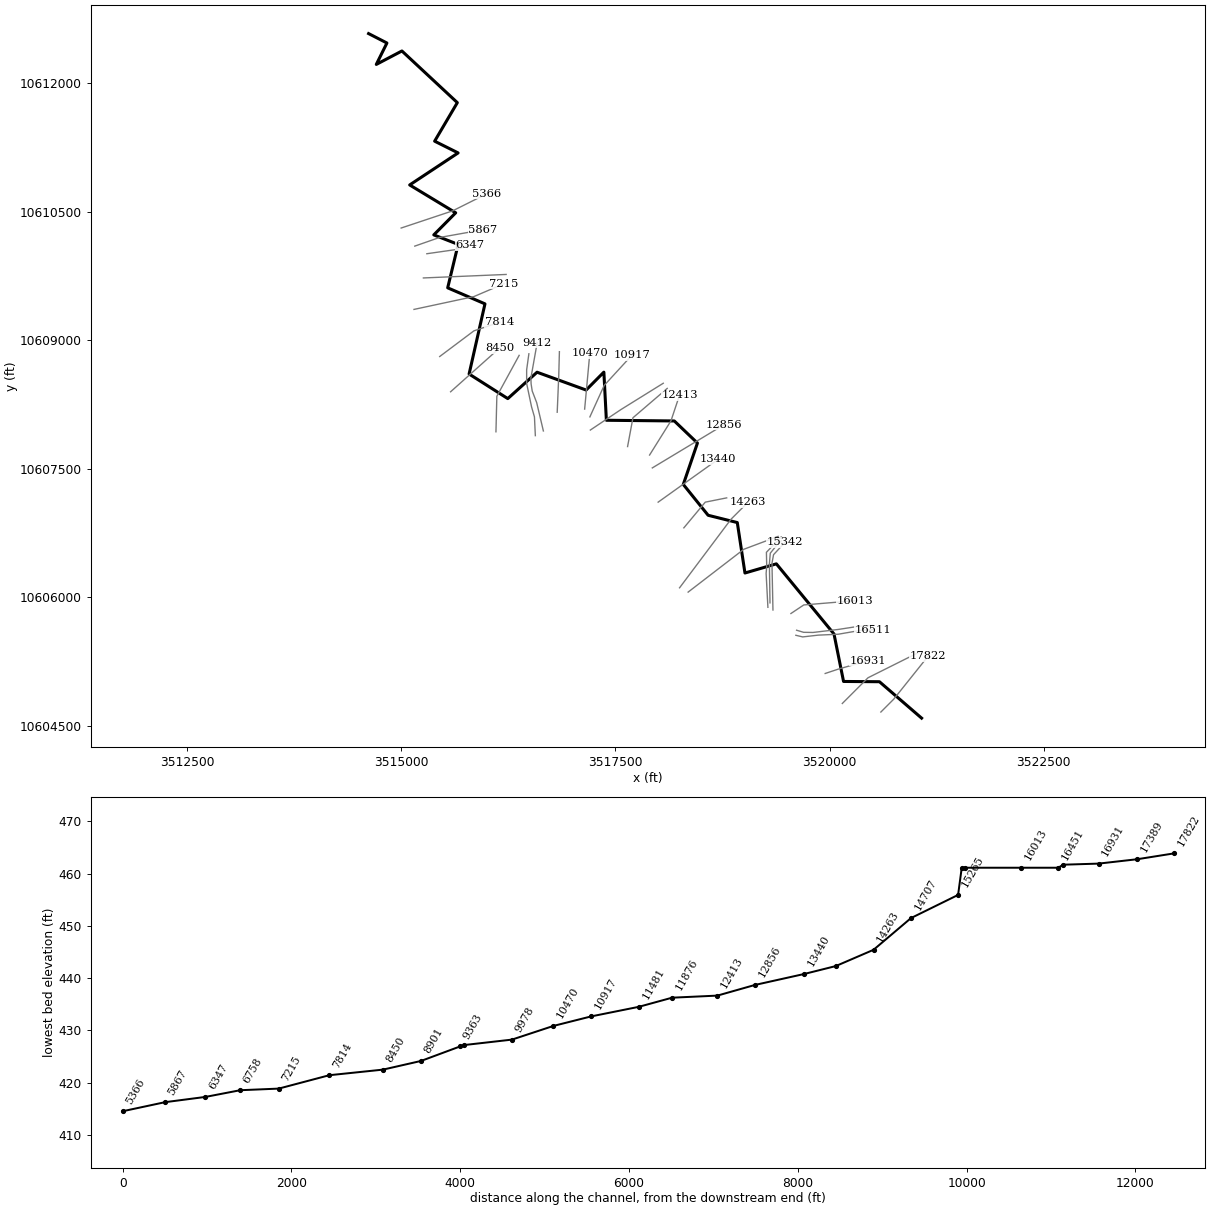
--- UNT047 IN CCTC.prj (project) ---

Proj Title=UNT047 IN CCTC Base Level Engineering
Current Plan=p01
Default Exp/Contr=0.3,0.1
English Units
Geom File=g01
Flow File=f01
Plan File=p01
Y Axis Title=Elevation
X Axis Title(PF)=Main Channel Distance
X Axis Title(XS)=Station
BEGIN DESCRIPTION:
UNT047 IN CCTC
END DESCRIPTION:
DSS Export Rating Curves= 0
DSS Export Rating Curve Sorted= 0
DSS Export Volume Flow Curves= 0
DXF OffsetX= 0
DXF OffsetY= 0
DXF ScaleX= 1
DXF ScaleY= 10

--- UNT047 IN CCTC.p01 (plan) ---

Plan Title=Multiple Run
Short Identifier=Multiple
Geom File=g01
Flow File=f01
Subcritical Flow
K Sum by GR= 0
Std Step Tol= 0.01
Critical Tol= 0.01
Num of Std Step Trials= 20
Max Error Tol= 0.3
Flow Tol Ratio= 0.001
Split Flow NTrial= 30
Split Flow Tol= 0.02
Split Flow Ratio= 0.02
Log Output Level= 0
Friction Slope Method= 1
Unsteady Friction Slope Method= 2
Unsteady Bridges Friction Slope Method= 1
Parabolic Critical Depth
Global Vel Dist=  1 , 1 , 1
Global Log Level= 0
CheckData=True
Encroach Param= -1, 0, 0, 0
BEGIN DESCRIPTION:
Multiple Run
END DESCRIPTION:

--- UNT047 IN CCTC.f01 (steady flow) ---

Flow Title=Multiple
Number of Profiles=7
Profile Names=10-year,25-year,50-year,1pct_min,100-year,1pct_plu,500-year
River Rch & RM= UNT047 IN CCTC,Reach-1,17822
    1093    1481    1796    1589    2149    2907    3069
River Rch & RM= UNT047 IN CCTC,Reach-1,15307
    1783    2480    3060    2751    3721    5032    5487
River Rch & RM= UNT047 IN CCTC,Reach-1,6347
    2076    2908    3605    3253    4399    5950    6538
Boundary for River Rch & Prof#=UNT047 IN CCTC,Reach-1,1
Up Type=0
Dn Type=3
Dn Slope=0.005
Boundary for River Rch & Prof#=UNT047 IN CCTC,Reach-1,2
Up Type=0
Dn Type=3
Dn Slope=0.005
Boundary for River Rch & Prof#=UNT047 IN CCTC,Reach-1,3
Up Type=0
Dn Type=3
Dn Slope=0.005
Boundary for River Rch & Prof#=UNT047 IN CCTC,Reach-1,4
Up Type=0
Dn Type=3
Dn Slope=0.005
Boundary for River Rch & Prof#=UNT047 IN CCTC,Reach-1,5
Up Type=0
Dn Type=3
Dn Slope=0.005
Boundary for River Rch & Prof#=UNT047 IN CCTC,Reach-1,6
Up Type=0
Dn Type=3
Dn Slope=0.005
Boundary for River Rch & Prof#=UNT047 IN CCTC,Reach-1,7
Up Type=0
Dn Type=3
Dn Slope=0.005

--- UNT047 IN CCTC.g01 (geometry) ---

Geom Title=Existing Conditions

River Reach=UNT047 IN CCTC,Reach-1
Reach XY= 30
      3521075.00     10604589.00      3520582.75     10605014.00
      3520164.00     10605017.00      3520052.50     10605571.00
      3519379.50     10606390.00      3519013.00     10606283.00
      3518923.50     10606872.00      3518583.00     10606957.00
      3518293.25     10607317.00      3518458.25     10607800.00
      3518188.25     10608058.00      3517395.25     10608066.00
      3517366.00     10608628.00      3517158.75     10608419.00
      3516586.00     10608627.00      3516244.50     10608319.00
      3515792.75     10608606.00      3515978.00     10609425.00
      3515542.75     10609612.00      3515665.00     10610119.00
      3515380.50     10610230.00      3515636.25     10610488.00
      3515099.00     10610813.00      3515664.50     10611187.00
      3515390.50     10611324.00      3515655.50     10611774.00
      3515008.50     10612377.00      3514709.50     10612220.00
      3514833.50     10612470.00      3514619.50     10612580.00

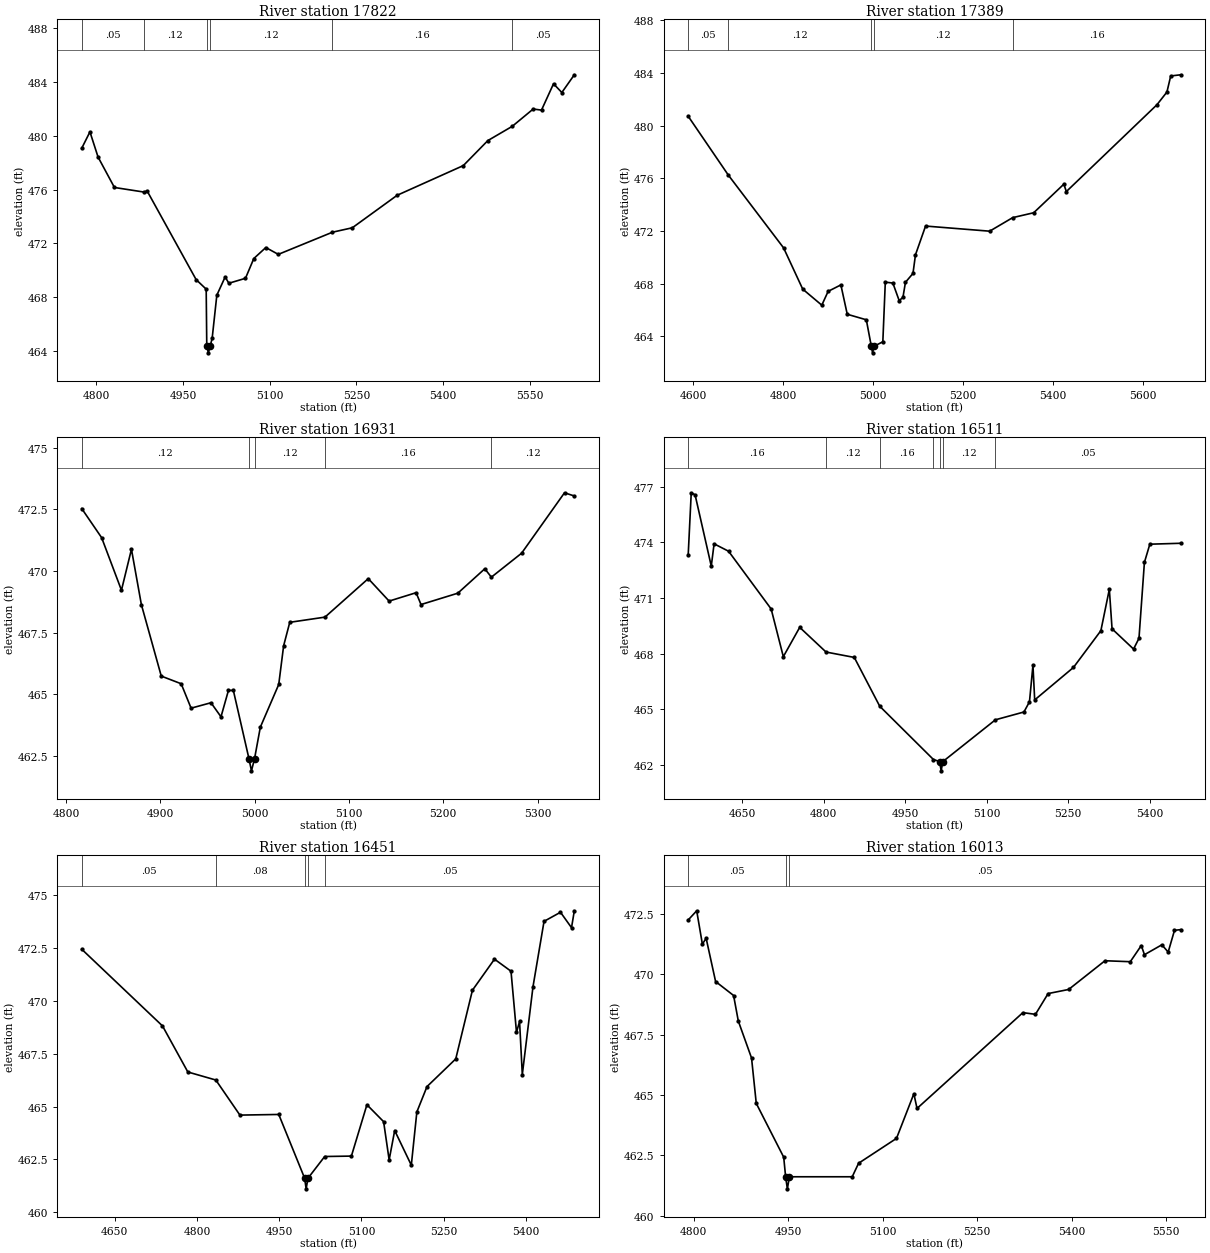
Type RM Length L Ch R = 1,17822,433,433,433
BEGIN DESCRIPTION:
UNT047 IN CCTC 35.0
END DESCRIPTION:
XS GIS Cut Line= 3
      3520599.57     10604660.15      3520749.61     10604810.19
      3521149.61     10605310.19
#Sta/Elev= 30
  4774.7  479.08  4788.9  480.30  4803.0  478.42  4831.3  476.16  4882.3  475.82
  4887.9  475.90  4972.7  469.30  4990.1  468.59  4991.1  464.35  4993.8  463.85
  4997.1  464.35  5000.5  464.96  5008.5  468.14  5022.9  469.50  5029.3  469.03
  5058.1  469.40  5072.5  470.87  5093.3  471.69  5114.9  471.18  5208.6  472.83
  5243.0  473.16  5320.6  475.58  5435.1  477.79  5477.5  479.65  5519.7  480.71
  5556.0  482.00  5570.4  481.92  5591.2  483.88  5605.6  483.23  5627.2  484.55
#Mann=6,-1,0
  4774.7    0.05       0  4882.3    0.12       0  4991.1    0.07       0
  4997.1    0.12       0  5208.6    0.16       0  5519.7    0.05       0
Bank Sta=4991.1,4997.1
Exp/Cntr=0.3,0.1

Type RM Length L Ch R = 1,17389,458,458,458
BEGIN DESCRIPTION:
UNT047 IN CCTC 34.0
END DESCRIPTION:
XS GIS Cut Line= 3
      3520149.61     10604760.19      3520449.61     10605060.19
      3521049.62     10605360.19
#Sta/Elev= 30
  4589.5  480.71  4678.7  476.24  4801.6  470.71  4844.1  467.58  4886.5  466.36
  4900.6  467.41  4928.9  467.90  4943.1  465.67  4985.5  465.25  4996.6  463.24
  4999.4  462.74  5002.6  463.24  5022.2  463.58  5027.7  468.11  5044.5  468.04
  5058.5  466.71  5066.9  466.95  5072.5  468.10  5089.2  468.77  5094.8  470.19
  5117.2  472.37  5259.7  471.98  5310.9  473.01  5357.6  473.38  5424.6  475.55
  5430.2  474.99  5631.5  481.58  5653.8  482.55  5662.2  483.77  5684.6  483.86
#Mann=5,-1,0
  4589.5    0.05       0  4678.7    0.12       0  4996.6    0.07       0
  5002.6    0.12       0  5310.9    0.16       0
Bank Sta=4996.6,5002.6
Exp/Cntr=0.3,0.1

Type RM Length L Ch R = 1,16931,420,420,420
BEGIN DESCRIPTION:
UNT047 IN CCTC 33.0
END DESCRIPTION:
XS GIS Cut Line= 3
      3519949.63     10605110.19      3520099.61     10605160.19
      3520449.61     10605260.19
#Sta/Elev= 30
  4816.8  472.53  4837.9  471.35  4858.9  469.22  4869.5  470.88  4880.0  468.64
  4901.1  465.74  4922.2  465.43  4932.7  464.44  4953.8  464.66  4964.4  464.09
  4972.3  465.16  4977.5  465.16  4994.0  462.40  4996.7  461.90  5000.0  462.40
  5006.1  463.67  5025.6  465.40  5030.8  466.97  5037.3  467.92  5074.6  468.13
  5120.5  469.69  5142.6  468.78  5171.2  469.12  5176.4  468.64  5215.4  469.10
  5244.0  470.09  5251.0  469.75  5283.0  470.72  5328.5  473.17  5338.9  473.04
#Mann=5,-1,0
  4816.8    0.12       0  4994.0    0.07       0  5000.0    0.12       0
  5074.6    0.16       0  5251.0    0.12       0
Bank Sta=4994,5000
Exp/Cntr=0.3,0.1

Type RM Length L Ch R = 1,16511,60,60,60
BEGIN DESCRIPTION:
Mapping XS bda591b3
END DESCRIPTION:
XS GIS Cut Line= 6
      3519607.24     10605556.03      3519687.13     10605536.93
      3519867.68     10605557.76      3520100.32     10605568.18
      3520372.89     10605615.05      3520506.50     10605621.90
#Sta/Elev= 30
  4550.2  473.32  4555.8  476.67  4562.9  476.56  4592.7  472.72  4597.9  473.92
  4624.6  473.52  4703.0  470.41  4725.4  467.84  4755.6  469.42  4804.1  468.09
  4856.1  467.80  4903.0  465.17  5001.9  462.30  5013.3  462.19  5016.1  461.69
  5019.3  462.19  5116.1  464.44  5168.6  464.86  5178.8  465.41  5185.2  467.38
  5188.4  465.51  5259.8  467.26  5310.3  469.24  5325.9  471.47  5330.9  469.34
  5370.5  468.25  5380.5  468.83  5390.5  472.92  5400.5  473.90  5457.5  473.95
#Mann=7,-1,0
  4550.2    0.16       0  4804.1    0.12       0  4903.0    0.16       0
  5001.9    0.12       0  5013.3    0.07       0  5019.3    0.12       0
  5116.1    0.05       0
Bank Sta=5013.3,5019.3
Exp/Cntr=0.3,0.1

Type RM Length L Ch R = 1,16451,438,438,438
BEGIN DESCRIPTION:
UNT047 IN CCTC 32.0
END DESCRIPTION:
XS GIS Cut Line= 6
      3519615.96     10605615.05      3519697.54     10605590.75
      3519806.92     10605589.01      3520098.59     10605623.73
      3520336.43     10605660.19      3520504.71     10605672.33
#Sta/Elev= 30
  4590.1  472.45  4737.3  468.82  4783.5  466.64  4834.5  466.26  4878.4  464.60
  4949.2  464.63  4996.4  461.61  4999.1  461.11  5002.4  461.61  5032.9  462.64
  5081.6  462.66  5109.9  465.09  5140.3  464.29  5150.4  462.48  5160.5  463.87
  5190.8  462.23  5200.9  464.75  5219.4  465.95  5271.8  467.26  5302.2  470.51
  5342.4  471.98  5372.5  471.41  5382.5  468.52  5388.1  469.03  5393.1  466.52
  5412.6  470.68  5432.7  473.77  5462.7  474.20  5482.8  473.47  5487.9  474.27
#Mann=5,-1,0
  4590.1    0.05       0  4834.5    0.08       0  4996.4    0.07       0
  5002.4    0.08       0  5032.9    0.05       0
Bank Sta=4996.4,5002.4
Exp/Cntr=0.3,0.1

Type RM Length L Ch R = 1,16013,671,671,671
BEGIN DESCRIPTION:
UNT047 IN CCTC 31.0
END DESCRIPTION:
XS GIS Cut Line= 3
      3519549.63     10605810.20      3519699.61     10605910.19
      3520299.57     10605960.19
#Sta/Elev= 30
  4791.2  472.25  4804.7  472.63  4813.7  471.25  4819.7  471.49  4834.7  469.70
  4863.3  469.12  4870.8  468.06  4891.8  466.53  4899.3  464.65  4942.9  462.42
  4945.9  461.61  4948.7  461.11  4951.9  461.61  5051.7  461.61  5061.8  462.17
  5122.0  463.20  5149.6  465.05  5154.6  464.44  5322.7  468.41  5342.7  468.34
  5362.8  469.20  5395.4  469.37  5453.1  470.56  5493.3  470.52  5510.8  471.19
  5515.8  470.81  5543.4  471.22  5553.5  470.92  5563.5  471.82  5573.5  471.85
#Mann=3,-1,0
  4791.2    0.05       0  4945.9    0.03       0  4951.9    0.05       0
Bank Sta=4945.9,4951.9
Exp/Cntr=0.3,0.1

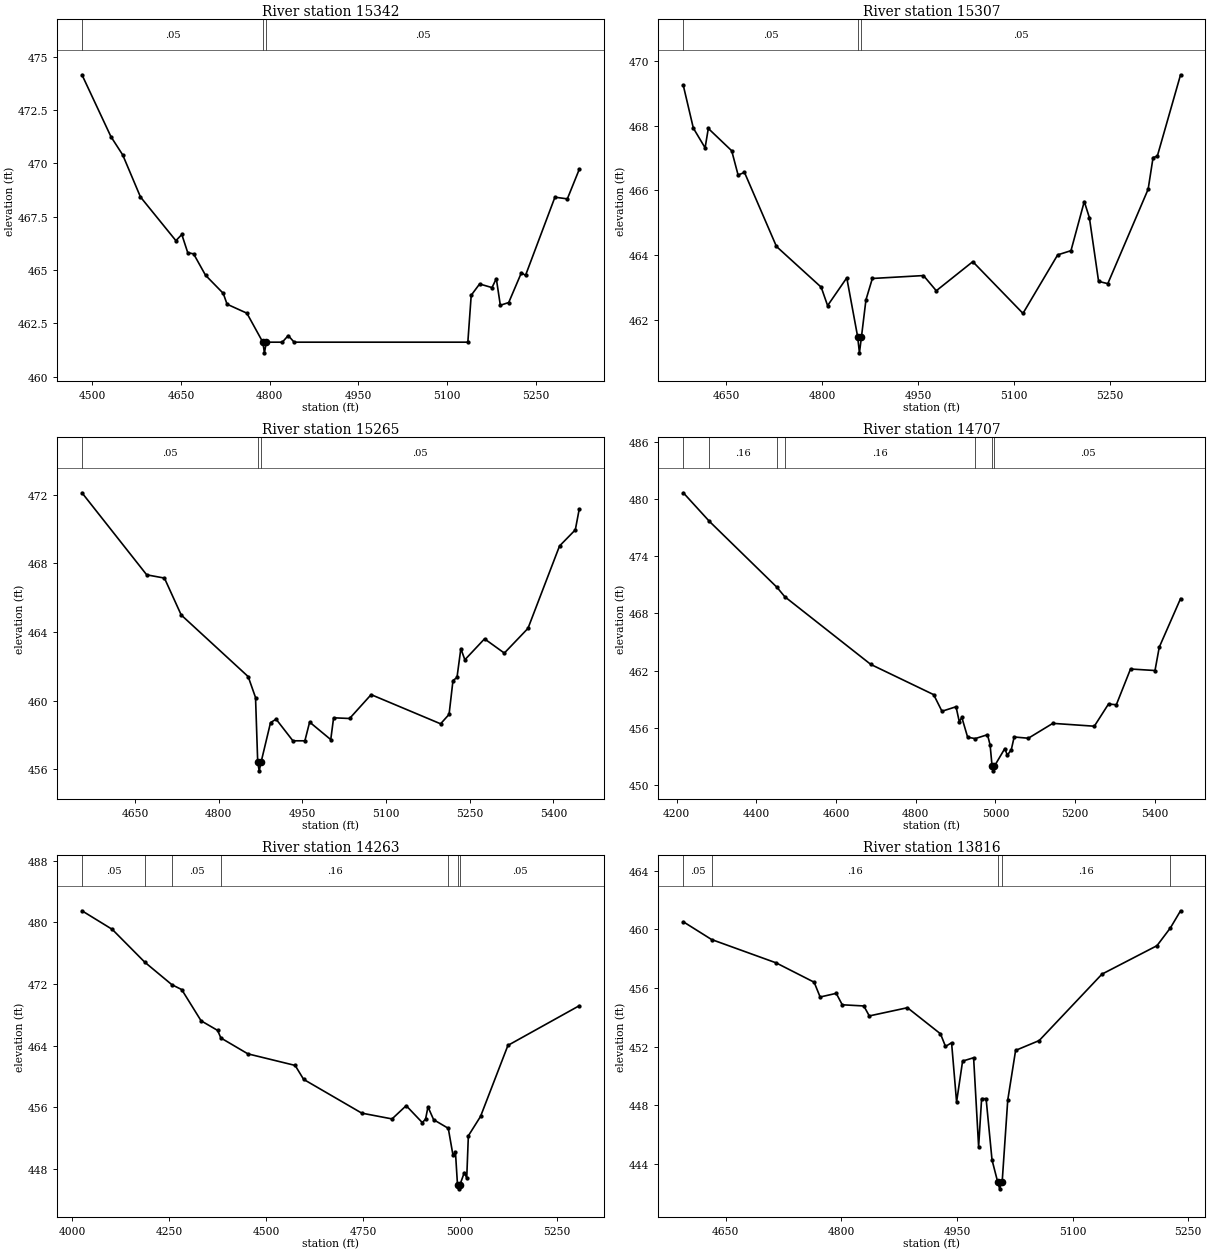
Type RM Length L Ch R = 1,15342,35,35,35
BEGIN DESCRIPTION:
UNT047 IN CCTC 30.0
END DESCRIPTION:
XS GIS Cut Line= 5
      3519339.91     10605851.18      3519329.49     10606337.27
      3519329.49     10606403.25      3519346.85     10606497.00
      3519478.78     10606639.34
#Sta/Elev= 30
  4482.3  474.15  4531.3  471.25  4551.3  470.39  4581.3  468.42  4641.3  466.37
  4651.3  466.66  4661.3  465.81  4671.3  465.75  4691.4  464.75  4721.4  463.90
  4727.9  463.39  4761.4  462.97  4788.4  461.61  4791.1  461.11  4794.4  461.61
  4821.4  461.61  4831.4  461.92  4841.4  461.61  5135.4  461.61  5141.1  463.81
  5155.3  464.34  5176.3  464.17  5183.6  464.59  5190.4  463.34  5204.6  463.47
  5226.1  464.87  5233.0  464.74  5282.8  468.41  5303.8  468.33  5323.9  469.71
#Mann=3,-1,0
  4482.3    0.05       0  4788.4    0.03       0  4794.4    0.05       0
Bank Sta=4788.4,4794.4
Exp/Cntr=0.3,0.1

Type RM Length L Ch R = 1,15307,42,42,42
BEGIN DESCRIPTION:
Mapping XS 5a61bf1c
END DESCRIPTION:
XS GIS Cut Line= 5
      3519305.18     10605934.50      3519298.24     10606389.36
      3519308.66     10606514.36      3519395.46     10606622.00
      3519440.63     10606660.22
#Sta/Elev= 30
  4583.0  469.24  4598.7  467.92  4617.1  467.31  4622.1  467.91  4658.7  467.22
  4668.7  466.47  4678.7  466.55  4728.7  464.26  4798.7  463.00  4808.7  462.43
  4838.7  463.29  4855.7  461.47  4858.5  460.97  4861.7  461.47  4868.7  462.61
  4878.7  463.27  4958.7  463.36  4978.7  462.89  5035.8  463.79  5114.3  462.19
  5168.6  464.00  5189.4  464.13  5210.2  465.65  5218.2  465.15  5232.6  463.18
  5247.0  463.11  5310.1  466.03  5317.8  467.01  5324.4  467.05  5360.8  469.57
#Mann=3,-1,0
  4583.0    0.05       0  4855.7   0.035       0  4861.7    0.05       0
Bank Sta=4855.7,4861.7
Exp/Cntr=0.3,0.1

Type RM Length L Ch R = 1,15265,558,558,558
BEGIN DESCRIPTION:
UNT047 IN CCTC 29.0
END DESCRIPTION:
XS GIS Cut Line= 5
      3519280.88     10605882.45      3519260.04     10606278.25
      3519266.99     10606358.11      3519263.52     10606524.77
      3519435.82     10606703.97
#Sta/Elev= 30
  4554.5  472.11  4670.6  467.33  4702.4  467.14  4732.5  464.99  4852.6  461.40
  4865.8  460.18  4869.7  456.41  4872.4  455.91  4875.7  456.41  4892.7  458.72
  4902.7  458.92  4932.8  457.66  4954.3  457.66  4962.8  458.75  5000.7  457.73
  5005.8  459.00  5034.5  458.96  5073.1  460.35  5197.7  458.65  5212.9  459.20
  5219.9  461.17  5227.1  461.35  5234.0  463.03  5241.2  462.38  5276.5  463.60
  5312.0  462.77  5354.4  464.21  5411.0  469.01  5439.3  469.95  5446.3  471.15
#Mann=3,-1,0
  4554.5    0.05       0  4869.7   0.035       0  4875.7    0.05       0
Bank Sta=4869.7,4875.7
Exp/Cntr=0.3,0.1

Type RM Length L Ch R = 1,14707,444,444,444
BEGIN DESCRIPTION:
UNT047 IN CCTC 28.0
END DESCRIPTION:
XS GIS Cut Line= 3
      3518349.59     10606060.18      3518999.61     10606560.19
      3519399.63     10606710.20
#Sta/Elev= 30
  4216.9  480.64  4282.4  477.64  4452.0  470.72  4471.4  469.74  4687.2  462.64
  4844.9  459.47  4865.7  457.73  4901.0  458.20  4909.2  456.63  4915.5  457.09
  4930.1  455.01  4949.0  454.86  4979.9  455.27  4986.5  454.19  4991.4  451.98
  4994.2  451.48  4997.4  451.98  5023.4  453.82  5029.7  453.11  5039.7  453.71
  5046.8  455.03  5082.4  454.90  5143.8  456.46  5247.9  456.16  5283.5  458.49
  5303.1  458.41  5338.7  462.16  5400.1  462.00  5410.8  464.45  5464.2  469.54
#Mann=7,-1,0
  4216.9    0.05       0  4282.4    0.16       0  4452.0    0.05       0
  4471.4    0.16       0  4949.0    0.05       0  4991.4   0.035       0
  4997.4    0.05       0
Bank Sta=4991.4,4997.4
Exp/Cntr=0.3,0.1

Type RM Length L Ch R = 1,14263,447,447,447
BEGIN DESCRIPTION:
UNT047 IN CCTC 27.0
END DESCRIPTION:
XS GIS Cut Line= 3
      3518249.60     10606110.17      3518849.61     10606910.19
      3519049.63     10607110.21
#Sta/Elev= 30
  4024.8  481.48  4102.9  479.07  4186.9  474.81  4256.8  471.89  4282.1  471.26
  4332.1  467.21  4374.8  465.96  4383.2  464.98  4452.9  462.92  4574.8  461.42
  4596.7  459.61  4746.7  455.23  4824.8  454.48  4861.3  456.20  4902.9  454.00
  4911.3  454.46  4917.5  456.04  4932.1  454.38  4969.9  453.26  4982.1  449.75
  4988.4  450.17  4993.7  445.91  4996.4  445.41  4999.7  445.91  5011.3  447.52
  5017.5  446.82  5021.7  452.29  5053.1  454.80  5123.8  464.02  5307.7  469.16
#Mann=7,-1,0
  4024.8    0.05       0  4186.9    0.16       0  4256.8    0.05       0
  4383.2    0.16       0  4969.9    0.05       0  4993.7   0.035       0
  4999.7    0.05       0
Bank Sta=4993.7,4999.7
Exp/Cntr=0.3,0.1

Type RM Length L Ch R = 1,13816,376,376,376
BEGIN DESCRIPTION:
UNT047 IN CCTC 26.0
END DESCRIPTION:
XS GIS Cut Line= 3
      3518299.64     10606810.22      3518549.61     10607110.19
      3518799.59     10607160.19
#Sta/Elev= 30
  4594.8  460.51  4631.5  459.30  4715.2  457.71  4764.6  456.39  4772.4  455.38
  4793.3  455.63  4801.1  454.85  4829.1  454.77  4836.2  454.09  4885.7  454.65
  4928.6  452.87  4935.1  452.01  4943.0  452.26  4949.5  448.22  4957.3  451.01
  4971.6  451.24  4978.1  445.17  4982.0  448.45  4987.8  448.45  4995.5  444.27
  5002.7  442.80  5005.4  442.30  5008.7  442.80  5015.9  448.35  5026.1  451.74
  5056.7  452.41  5138.2  456.94  5209.6  458.88  5227.1  460.10  5240.2  461.26
#Mann=5,-1,0
  4594.8    0.05       0  4631.5    0.16       0  5002.7    0.07       0
  5008.7    0.16       0  5227.1    0.05       0
Bank Sta=5002.7,5008.7
Exp/Cntr=0.3,0.1

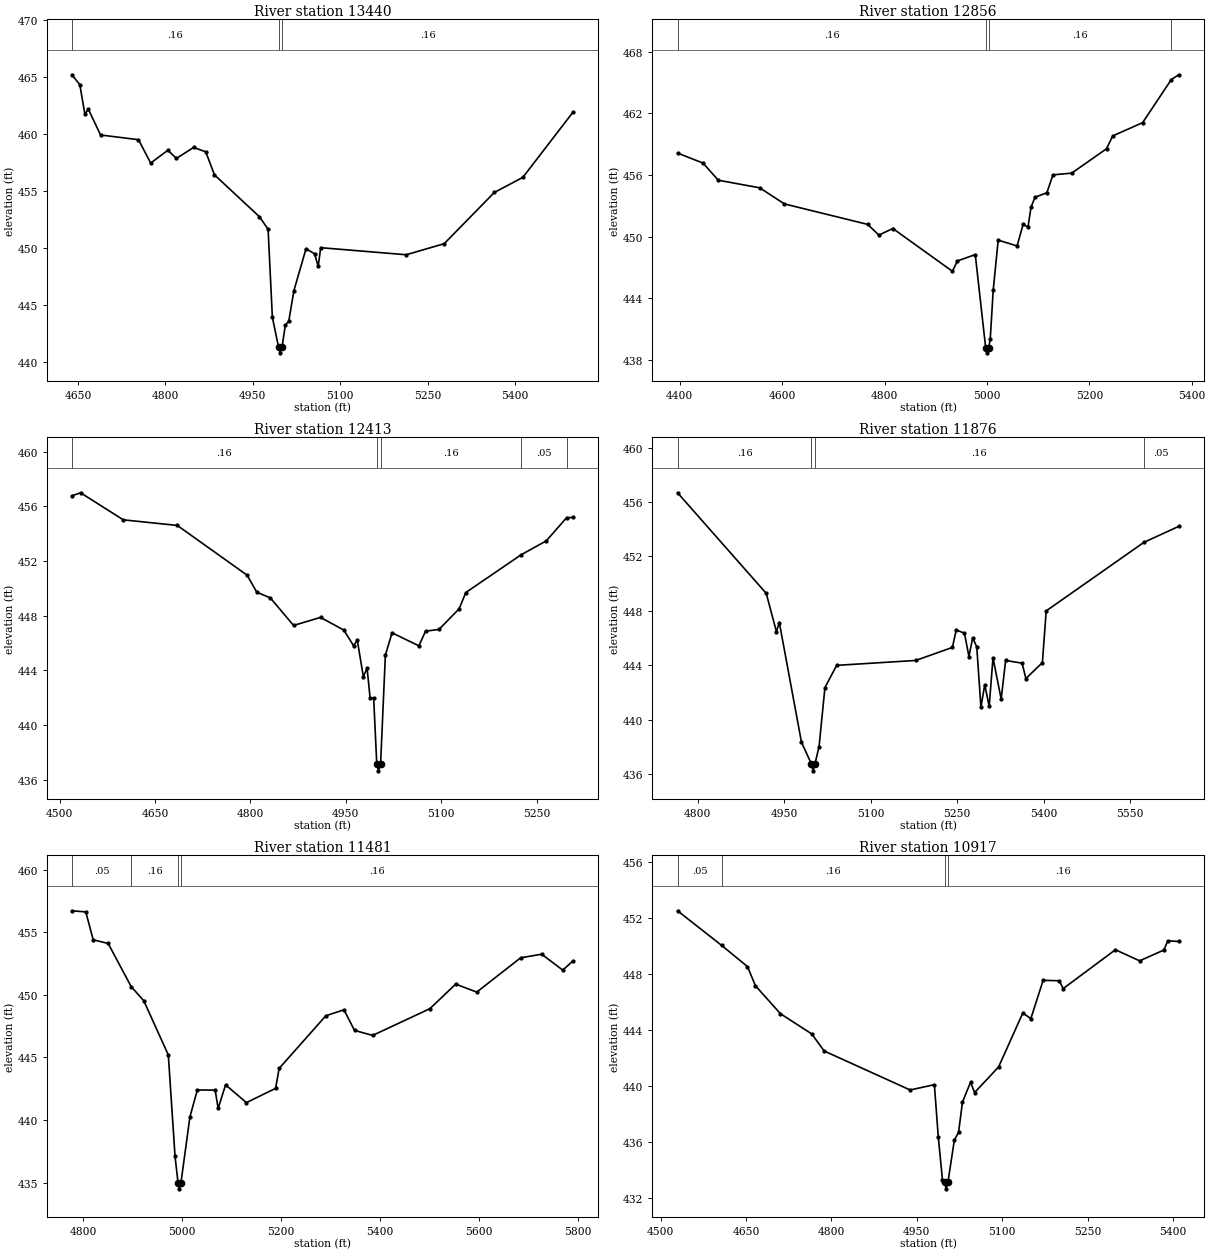
Type RM Length L Ch R = 1,13440,584,584,584
BEGIN DESCRIPTION:
UNT047 IN CCTC 25.0
END DESCRIPTION:
XS GIS Cut Line= 3
      3517999.58     10607110.16      3518349.61     10607360.19
      3518699.63     10607610.20
#Sta/Elev= 30
  4639.5  465.16  4653.1  464.29  4661.7  461.72  4667.8  462.13  4688.7  459.88
  4753.8  459.47  4774.7  457.42  4804.2  458.54  4819.0  457.83  4848.5  458.79
  4869.3  458.40  4884.1  456.39  4961.5  452.71  4976.3  451.61  4983.6  443.90
  4994.2  441.28  4996.9  440.78  5000.2  441.28  5005.8  443.18  5011.9  443.59
  5020.5  446.22  5041.4  449.91  5056.1  449.46  5062.3  448.36  5066.6  450.00
  5213.4  449.38  5278.6  450.35  5364.6  454.84  5413.7  456.17  5499.8  461.89
#Mann=3,-1,0
  4639.5    0.16       0  4994.2    0.07       0  5000.2    0.16       0
Bank Sta=4994.2,5000.2
Exp/Cntr=0.3,0.1

Type RM Length L Ch R = 1,12856,443,443,443
BEGIN DESCRIPTION:
UNT047 IN CCTC 24.0
END DESCRIPTION:
XS GIS Cut Line= 2
      3517931.47     10607509.89      3518770.03     10608015.11
#Sta/Elev= 30
  4395.6  458.12  4445.3  457.15  4475.2  455.48  4556.0  454.74  4604.5  453.17
  4767.0  451.18  4789.0  450.14  4816.2  450.78  4932.7  446.61  4942.1  447.62
  4977.2  448.24  4997.5  439.18  5000.3  438.68  5003.5  439.18  5006.5  440.06
  5012.3  444.81  5022.0  449.65  5058.9  449.08  5070.6  451.18  5080.2  450.91
  5086.1  452.85  5093.9  453.82  5117.1  454.26  5128.9  456.00  5165.7  456.17
  5233.6  458.54  5245.7  459.79  5304.1  461.08  5360.1  465.27  5374.6  465.74
#Mann=4,-1,0
  4395.6    0.16       0  4997.5    0.07       0  5003.5    0.16       0
  5360.1    0.05       0
Bank Sta=4997.5,5003.5
Exp/Cntr=0.3,0.1

Type RM Length L Ch R = 1,12413,537,537,537
BEGIN DESCRIPTION:
UNT047 IN CCTC 23.0
END DESCRIPTION:
XS GIS Cut Line= 3
      3517899.60     10607660.17      3518149.61     10608060.19
      3518249.59     10608360.14
#Sta/Elev= 30
  4519.4  456.78  4533.0  457.00  4600.2  455.02  4685.1  454.61  4794.8  450.97
  4810.1  449.72  4831.3  449.31  4867.9  447.29  4910.3  447.88  4946.9  446.95
  4962.2  445.81  4968.1  446.21  4977.6  443.54  4983.5  444.16  4988.2  441.98
  4993.8  441.98  4998.7  437.15  5001.4  436.65  5004.7  437.15  5012.2  445.11
  5022.7  446.75  5064.9  445.80  5075.4  446.87  5096.5  447.00  5128.2  448.51
  5138.7  449.70  5225.9  452.47  5265.2  453.48  5297.0  455.17  5307.3  455.20
#Mann=5,-1,0
  4519.4    0.16       0  4998.7    0.07       0  5004.7    0.16       0
  5225.9    0.05       0  5297.0    0.16       0
Bank Sta=4998.7,5004.7
Exp/Cntr=0.3,0.1

Type RM Length L Ch R = 1,11876,395,395,395
BEGIN DESCRIPTION:
Mapping XS 960b3623
END DESCRIPTION:
XS GIS Cut Line= 3
      3517642.85     10607759.11      3517705.36     10608095.08
      3518105.26     10608437.80
#Sta/Elev= 30
  4765.4  456.68  4919.1  449.29  4936.7  446.48  4941.8  447.14  4980.1  438.36
  4997.4  436.75  5000.2  436.25  5003.4  436.75  5010.6  438.02  5020.8  442.37
  5041.1  444.00  5178.1  444.36  5241.7  445.32  5248.3  446.60  5262.6  446.36
  5270.3  444.65  5276.9  446.03  5283.9  445.35  5291.1  440.93  5297.7  442.57
  5305.4  440.99  5312.0  444.55  5326.2  441.52  5333.9  444.36  5362.5  444.16
  5369.0  443.03  5397.6  444.20  5404.2  448.00  5573.6  453.04  5633.8  454.21
#Mann=4,-1,0
  4765.4    0.16       0  4997.4    0.07       0  5003.4    0.16       0
  5573.6    0.05       0
Bank Sta=4997.4,5003.4
Exp/Cntr=0.3,0.1

Type RM Length L Ch R = 1,11481,564,564,564
BEGIN DESCRIPTION:
UNT047 IN CCTC 22.0
END DESCRIPTION:
XS GIS Cut Line= 3
      3517207.94     10607951.84      3517564.98     10608190.87
      3518059.33     10608498.10
#Sta/Elev= 30
  4777.7  456.72  4805.7  456.63  4820.7  454.40  4850.8  454.11  4897.4  450.66
  4922.8  449.53  4972.3  445.20  4985.9  437.09  4991.9  435.00  4994.6  434.50
  4997.9  435.00  5015.9  440.25  5030.9  442.40  5066.9  442.39  5072.9  440.92
  5087.9  442.81  5130.0  441.39  5188.9  442.53  5196.0  444.12  5290.3  448.33
  5326.9  448.81  5348.2  447.16  5384.8  446.76  5500.5  448.90  5552.5  450.86
  5595.0  450.22  5683.5  452.96  5726.0  453.25  5768.5  451.98  5789.4  452.71
#Mann=4,-1,0
  4777.7    0.05       0  4897.4    0.16       0  4991.9    0.07       0
  4997.9    0.16       0
Bank Sta=4991.9,4997.9
Exp/Cntr=0.3,0.1

Type RM Length L Ch R = 1,10917,447,447,447
BEGIN DESCRIPTION:
UNT047 IN CCTC 21.0
END DESCRIPTION:
XS GIS Cut Line= 3
      3517202.77     10608105.54      3517369.42     10608472.69
      3517692.37     10608824.28
#Sta/Elev= 30
  4529.6  452.50  4607.1  450.03  4652.5  448.52  4666.5  447.15  4710.4  445.16
  4765.3  443.72  4787.3  442.50  4938.3  439.72  4980.9  440.10  4987.7  436.39
  4995.1  433.32  4998.8  433.17  5001.6  432.67  5004.8  433.17  5016.0  436.15
  5023.4  436.70  5030.2  438.85  5044.4  440.27  5051.6  439.54  5093.7  441.36
  5136.3  445.21  5150.4  444.81  5172.0  447.54  5200.4  447.51  5207.2  446.95
  5299.0  449.72  5341.6  448.93  5384.1  449.70  5391.1  450.36  5410.2  450.31
#Mann=4,-1,0
  4529.6    0.05       0  4607.1    0.16       0  4998.8    0.07       0
  5004.8    0.16       0
Bank Sta=4998.8,5004.8
Exp/Cntr=0.3,0.1

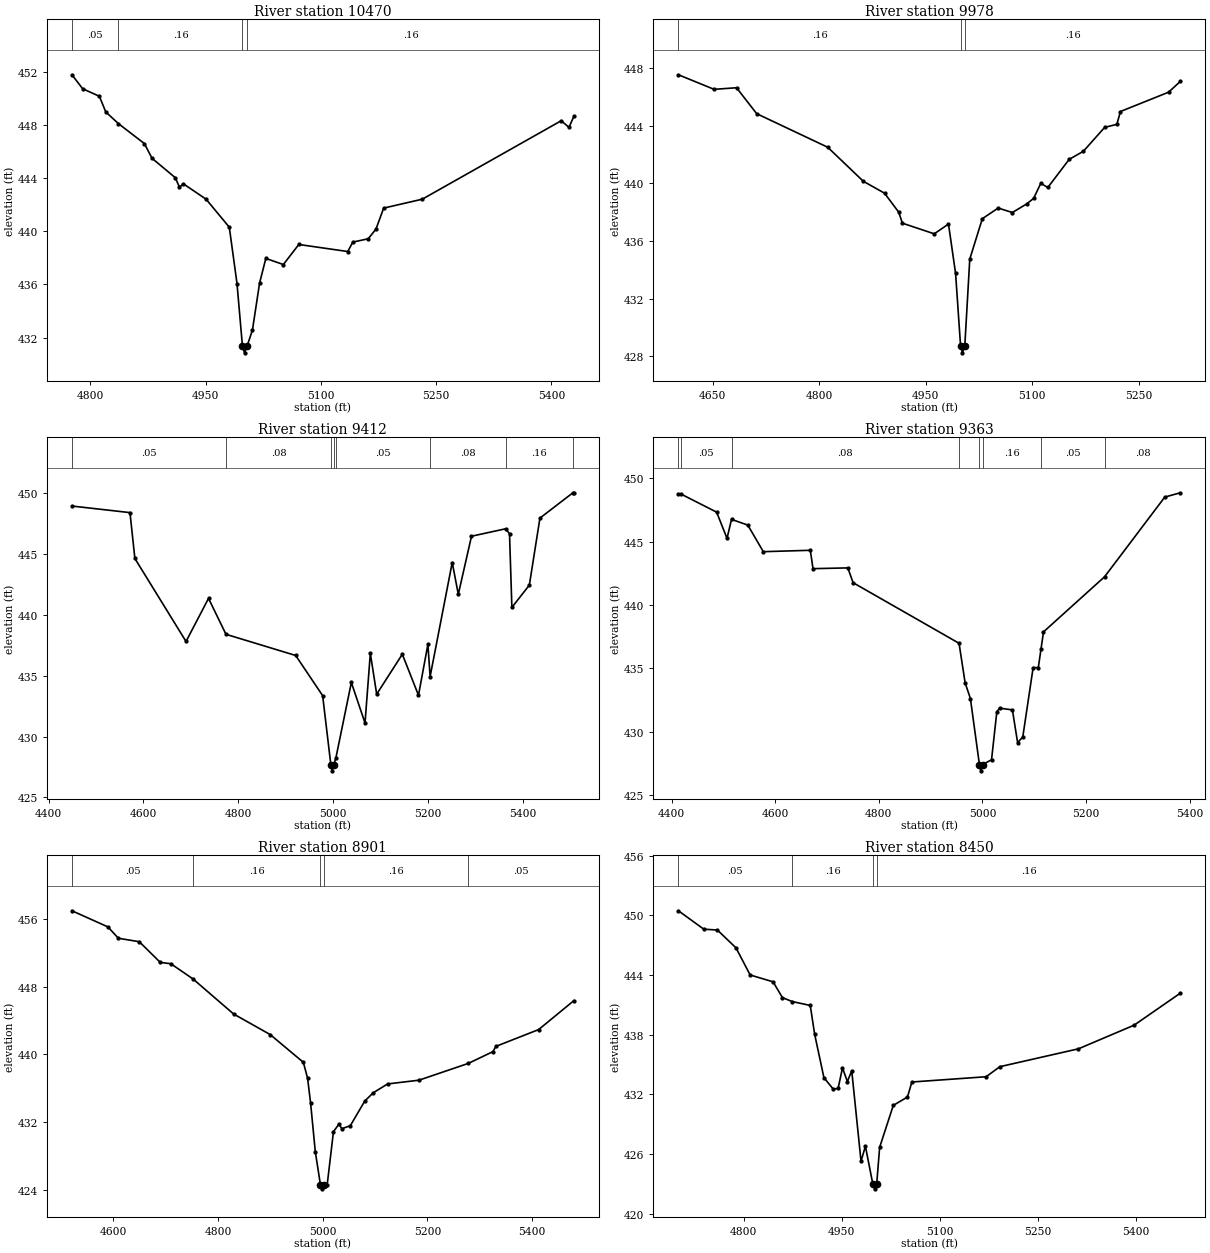
Type RM Length L Ch R = 1,10470,492,492,492
BEGIN DESCRIPTION:
UNT047 IN CCTC 20.0
END DESCRIPTION:
XS GIS Cut Line= 3
      3517141.61     10608196.39      3517164.97     10608447.46
      3517201.73     10608846.52
#Sta/Elev= 30
  4776.2  451.79  4790.1  450.74  4811.9  450.17  4820.2  448.99  4836.7  448.11
  4870.4  446.61  4880.4  445.50  4910.6  444.04  4916.1  443.32  4921.1  443.58
  4950.7  442.42  4980.9  440.31  4990.9  436.07  4998.0  431.35  5000.7  430.85
  5004.0  431.35  5011.0  432.57  5020.3  436.11  5028.4  437.96  5051.2  437.50
  5071.3  439.01  5135.0  438.48  5141.6  439.19  5161.6  439.44  5171.7  440.17
  5181.7  441.75  5231.9  442.42  5412.7  448.33  5422.7  447.83  5429.1  448.65
#Mann=4,-1,0
  4776.2    0.05       0  4836.7    0.16       0  4998.0    0.07       0
  5004.0    0.16       0
Bank Sta=4998,5004
Exp/Cntr=0.3,0.1

Type RM Length L Ch R = 1,9978,566,566,566
BEGIN DESCRIPTION:
UNT047 IN CCTC 19.0
END DESCRIPTION:
XS GIS Cut Line= 3
      3516821.30     10608159.96      3516839.47     10608590.64
      3516846.98     10608866.78
#Sta/Elev= 30
  4601.5  447.53  4651.8  446.52  4683.4  446.63  4711.8  444.83  4811.9  442.50
  4862.0  440.14  4892.0  439.31  4912.0  437.99  4917.1  437.23  4962.0  436.49
  4982.1  437.17  4992.1  433.74  4999.1  428.73  5001.8  428.23  5005.1  428.73
  5012.1  434.74  5029.8  437.54  5052.1  438.28  5072.1  437.97  5092.1  438.56
  5102.1  438.95  5112.1  439.99  5122.1  439.71  5152.2  441.66  5172.2  442.22
  5202.2  443.88  5219.4  444.09  5224.4  444.98  5292.2  446.32  5308.8  447.07
#Mann=3,-1,0
  4601.5    0.16       0  4999.1    0.07       0  5005.1    0.16       0
Bank Sta=4999.1,5005.1
Exp/Cntr=0.3,0.1

Type RM Length L Ch R = 1,9412,49,49,49
BEGIN DESCRIPTION:
UNT047 IN CCTC 18.0
END DESCRIPTION:
XS GIS Cut Line= 6
      3516659.85     10607941.17      3516581.72     10608271.92
      3516529.63     10608407.34      3516516.61     10608490.67
      3516514.01     10608558.38      3516587.69     10608972.54
#Sta/Elev= 30
  4449.4  448.95  4571.7  448.41  4582.0  444.64  4689.8  437.82  4737.2  441.36
  4774.0  438.41  4920.9  436.67  4977.7  433.37  4995.0  427.69  4997.7  427.19
  5001.0  427.69  5005.4  428.21  5038.2  434.45  5067.0  431.12  5078.2  436.85
  5091.6  433.49  5145.6  436.77  5179.7  433.40  5199.5  437.58  5204.2  434.94
  5250.8  444.31  5263.6  441.70  5291.4  446.47  5363.2  447.08  5371.5  446.68
  5376.5  440.62  5413.3  442.45  5435.6  447.96  5505.1  450.04  5507.1  450.04
#Mann=8,-1,0
  4449.4    0.05       0  4774.0    0.08       0  4995.0    0.07       0
  5001.0    0.08       0  5005.4    0.05       0  5204.2    0.08       0
  5363.2    0.16       0  5505.1    0.08       0
Bank Sta=4995,5001
Exp/Cntr=0.3,0.1

Type RM Length L Ch R = 1,9363,462,462,462
BEGIN DESCRIPTION:
UNT047 IN CCTC 17.0
END DESCRIPTION:
XS GIS Cut Line= 6
      3516566.09     10607886.47      3516555.68     10608105.26
      3516521.82     10608222.44      3516464.53     10608495.88
      3516464.53     10608654.74      3516490.58     10608842.27
#Sta/Elev= 30
  4413.1  448.79  4417.6  448.78  4486.9  447.34  4506.9  445.27  4515.6  446.77
  4547.0  446.32  4577.0  444.22  4667.7  444.33  4672.9  442.88  4740.1  442.94
  4750.3  441.77  4954.8  436.99  4966.5  433.87  4976.7  432.63  4994.1  427.42
  4996.8  426.92  5000.1  427.42  5017.5  427.79  5027.7  431.58  5033.0  431.87
  5057.8  431.73  5067.8  429.15  5077.8  429.59  5097.8  435.07  5107.8  435.07
  5112.9  436.51  5117.8  437.89  5235.7  442.24  5351.9  448.53  5381.9  448.87
#Mann=8,-1,0
  4413.1    0.08       0  4417.6    0.05       0  4515.6    0.08       0
  4954.8    0.16       0  4994.1    0.07       0  5000.1    0.16       0
  5112.9    0.05       0  5235.7    0.08       0
Bank Sta=4994.1,5000.1
Exp/Cntr=0.3,0.1

Type RM Length L Ch R = 1,8901,451,451,451
BEGIN DESCRIPTION:
UNT047 IN CCTC 16.0
END DESCRIPTION:
XS GIS Cut Line= 3
      3516106.22     10607931.48      3516116.64     10608346.43
      3516377.05     10608823.85
#Sta/Elev= 30
  4520.9  456.94  4589.6  455.04  4609.6  453.70  4649.6  453.29  4689.7  450.85
  4709.7  450.70  4752.2  448.90  4829.7  444.77  4899.7  442.34  4963.0  439.07
  4971.1  437.19  4976.8  434.29  4985.8  428.54  4995.6  424.65  4998.4  424.15
  5001.6  424.65  5008.6  424.66  5020.5  430.89  5030.9  431.78  5036.6  431.24
  5052.8  431.60  5080.3  434.50  5096.4  435.47  5123.9  436.52  5183.7  436.96
  5278.1  438.94  5325.2  440.33  5330.9  440.95  5412.5  442.93  5479.8  446.34
#Mann=5,-1,0
  4520.9    0.05       0  4752.2    0.16       0  4995.6    0.07       0
  5001.6    0.16       0  5278.1    0.05       0
Bank Sta=4995.6,5001.6
Exp/Cntr=0.3,0.1

Type RM Length L Ch R = 1,8450,636,636,636
BEGIN DESCRIPTION:
UNT047 IN CCTC 15.0
END DESCRIPTION:
XS GIS Cut Line= 2
      3515576.68     10608398.48      3516149.63     10608910.21
#Sta/Elev= 30
  4700.0  450.47  4738.8  448.62  4759.7  448.53  4788.1  446.74  4809.8  444.01
  4844.9  443.32  4859.2  441.73  4874.1  441.34  4901.8  440.94  4908.5  438.05
  4922.7  433.68  4936.9  432.53  4944.4  432.59  4951.1  434.66  4958.6  433.29
  4965.3  434.36  4979.5  425.26  4986.2  426.78  4997.5  422.99  5000.2  422.49
  5003.5  422.99  5008.0  426.67  5028.9  430.89  5050.6  431.73  5057.3  433.24
  5171.0  433.77  5191.9  434.78  5312.3  436.58  5397.5  438.96  5468.2  442.18
#Mann=4,-1,0
  4700.0    0.05       0  4874.1    0.16       0  4997.5    0.07       0
  5003.5    0.16       0
Bank Sta=4997.5,5003.5
Exp/Cntr=0.3,0.1

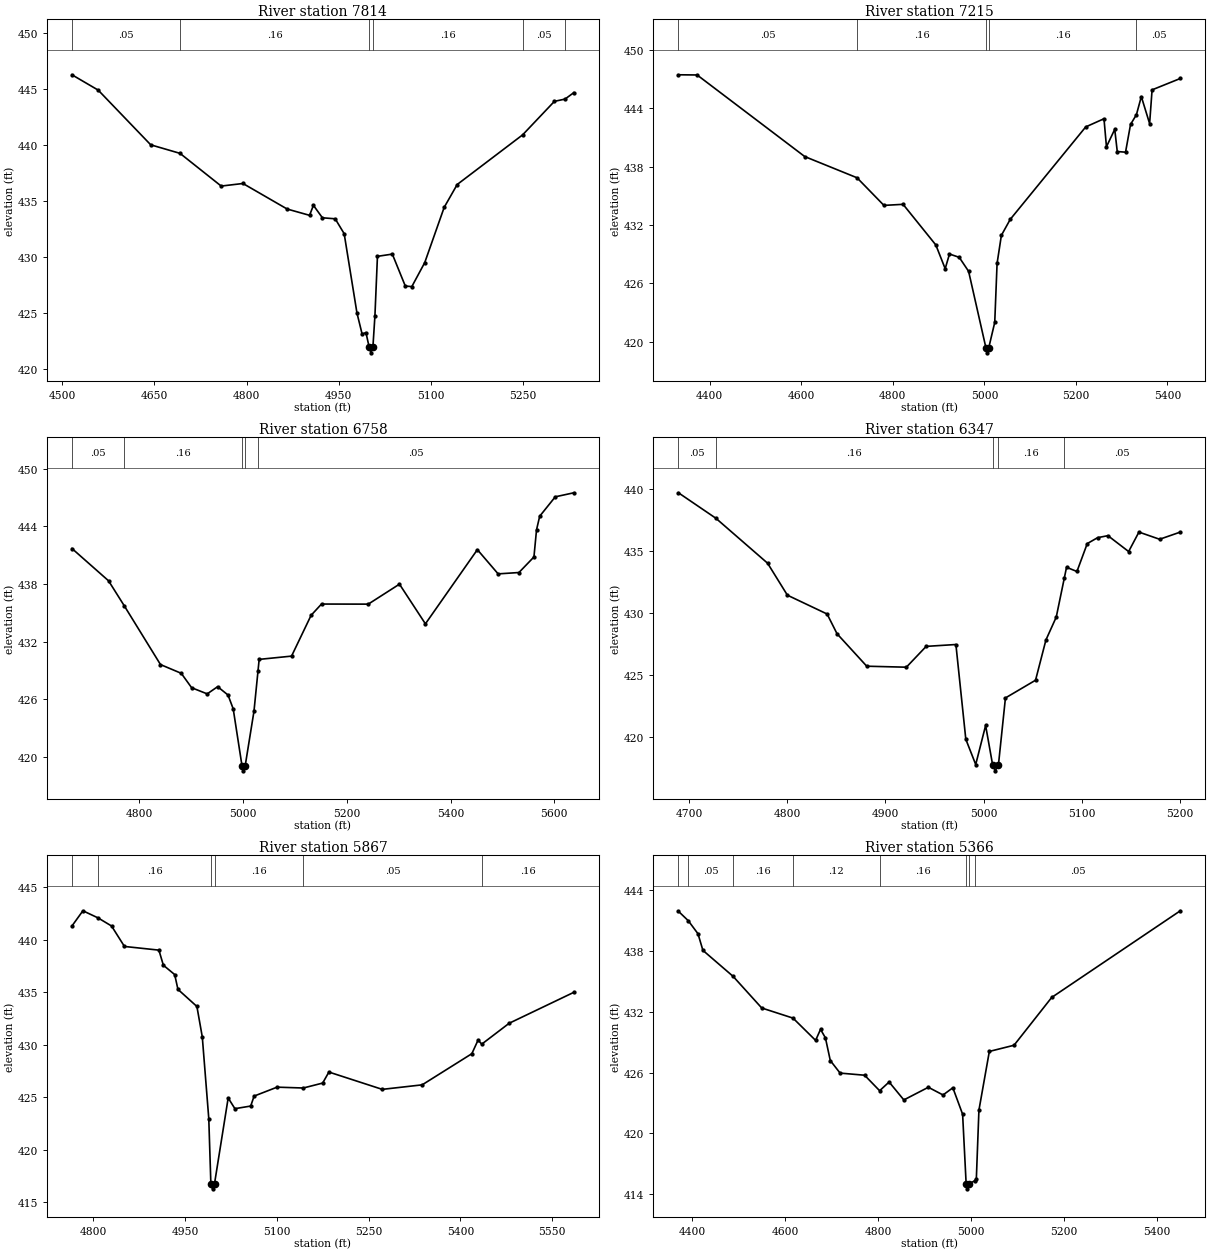
Type RM Length L Ch R = 1,7814,599,599,599
BEGIN DESCRIPTION:
UNT047 IN CCTC 14.0
END DESCRIPTION:
XS GIS Cut Line= 3
      3515449.64     10608810.21      3515849.61     10609110.19
      3516149.62     10609210.19
#Sta/Elev= 30
  4516.0  446.23  4558.7  444.86  4644.1  439.98  4691.7  439.22  4758.7  436.30
  4794.1  436.53  4866.0  434.25  4902.4  433.69  4908.7  434.58  4923.3  433.47
  4944.1  433.38  4958.7  432.05  4979.5  424.97  4987.8  423.11  4994.1  423.22
  4999.4  421.92  5002.2  421.42  5005.4  421.92  5008.7  424.72  5012.8  430.03
  5037.0  430.23  5058.1  427.38  5068.7  427.33  5089.7  429.47  5121.4  434.41
  5142.5  436.44  5248.9  440.87  5300.6  443.86  5317.8  444.06  5332.2  444.64
#Mann=6,-1,0
  4516.0    0.05       0  4691.7    0.16       0  4999.4    0.07       0
  5005.4    0.16       0  5248.9    0.05       0  5317.8    0.16       0
Bank Sta=4999.4,5005.4
Exp/Cntr=0.3,0.1

Type RM Length L Ch R = 1,7215,457,457,457
BEGIN DESCRIPTION:
UNT047 IN CCTC 13.0
END DESCRIPTION:
XS GIS Cut Line= 3
      3515149.61     10609360.19      3515849.61     10609510.19
      3516199.63     10609660.20
#Sta/Elev= 30
  4331.4  447.45  4372.3  447.43  4607.5  439.04  4721.7  436.86  4780.5  434.02
  4822.3  434.13  4893.9  429.95  4914.3  427.51  4923.7  429.02  4945.0  428.68
  4965.5  427.24  5003.4  419.36  5006.1  418.86  5009.4  419.36  5022.6  421.99
  5027.7  428.05  5037.1  430.94  5056.4  432.58  5221.4  442.09  5261.3  442.93
  5266.7  440.05  5284.8  441.84  5290.3  439.56  5308.4  439.49  5319.3  442.34
  5332.2  443.35  5342.9  445.21  5361.0  442.43  5366.4  445.90  5428.1  447.07
#Mann=5,-1,0
  4331.4    0.05       0  4721.7    0.16       0  5003.4    0.07       0
  5009.4    0.16       0  5332.2    0.05       0
Bank Sta=5003.4,5009.4
Exp/Cntr=0.3,0.1

Type RM Length L Ch R = 1,6758,411,411,411
BEGIN DESCRIPTION:
UNT047 IN CCTC 12.0
END DESCRIPTION:
XS GIS Cut Line= 2
      3515259.20     10609727.43      3516225.34     10609768.27
#Sta/Elev= 30
  4670.6  441.69  4741.1  438.33  4771.6  435.71  4841.2  429.61  4881.2  428.70
  4901.2  427.20  4931.2  426.56  4951.3  427.31  4971.3  426.44  4981.3  425.00
  4998.3  419.05  5001.1  418.55  5004.3  419.05  5021.3  424.75  5029.0  428.91
  5031.3  430.15  5093.7  430.49  5131.4  434.74  5151.4  435.91  5241.5  435.90
  5301.6  437.98  5351.6  433.85  5451.7  441.57  5491.7  439.05  5531.8  439.19
  5560.7  440.81  5565.7  443.64  5571.8  445.05  5601.8  447.07  5637.6  447.49
#Mann=5,-1,0
  4670.6    0.05       0  4771.6    0.16       0  4998.3    0.07       0
  5004.3    0.16       0  5029.0    0.05       0
Bank Sta=4998.3,5004.3
Exp/Cntr=0.3,0.1

Type RM Length L Ch R = 1,6347,480,480,480
BEGIN DESCRIPTION:
UNT047 IN CCTC 11.0
END DESCRIPTION:
XS GIS Cut Line= 3
      3515299.58     10610010.18      3515649.61     10610060.19
      3515799.61     10610110.19
#Sta/Elev= 30
  4688.9  439.70  4727.0  437.65  4779.8  434.02  4800.0  431.44  4840.5  429.92
  4850.6  428.33  4880.9  425.71  4921.3  425.63  4941.5  427.31  4971.8  427.46
  4981.9  419.82  4992.0  417.78  5002.1  420.93  5009.2  417.77  5011.9  417.27
  5015.2  417.77  5022.3  423.15  5053.0  424.58  5063.6  427.83  5074.1  429.67
  5082.3  432.81  5084.6  433.69  5095.2  433.35  5105.7  435.60  5116.3  436.08
  5126.8  436.24  5147.9  434.96  5158.4  436.53  5179.5  435.95  5200.6  436.53
#Mann=5,-1,0
  4688.9    0.05       0  4727.0    0.16       0  5009.2    0.07       0
  5015.2    0.16       0  5082.3    0.05       0
Bank Sta=5009.2,5015.2
Exp/Cntr=0.3,0.1

Type RM Length L Ch R = 1,5867,501,501,501
BEGIN DESCRIPTION:
UNT047 IN CCTC 10.0
END DESCRIPTION:
XS GIS Cut Line= 3
      3515158.56     10610098.97      3515446.73     10610199.66
      3515953.71     10610289.94
#Sta/Elev= 30
  4765.1  441.31  4783.0  442.76  4807.8  442.08  4829.8  441.31  4850.9  439.36
  4907.2  439.01  4914.5  437.57  4933.0  436.68  4938.3  435.27  4969.3  433.64
  4978.1  430.74  4988.7  422.96  4992.1  416.76  4994.8  416.26  4998.1  416.76
  5020.4  424.92  5031.4  423.90  5057.2  424.15  5062.8  425.10  5100.3  425.95
  5143.2  425.87  5174.8  426.34  5185.0  427.39  5272.2  425.74  5337.4  426.17
  5418.6  429.14  5428.8  430.44  5434.8  430.05  5479.6  432.04  5585.3  434.99
#Mann=6,-1,0
  4765.1    0.05       0  4807.8    0.16       0  4992.1    0.07       0
  4998.1    0.16       0  5143.2    0.05       0  5434.8    0.16       0
Bank Sta=4992.1,4998.1
Exp/Cntr=0.3,0.1

Type RM Length L Ch R = 1,5366,919,919,919
BEGIN DESCRIPTION:
UNT047 IN CCTC 9.0
END DESCRIPTION:
XS GIS Cut Line= 3
      3514999.63     10610310.20      3515599.61     10610510.19
      3515999.57     10610710.17
#Sta/Elev= 30
  4370.9  441.94  4392.1  441.01  4413.0  439.72  4423.6  438.08  4488.6  435.51
  4550.1  432.39  4617.4  431.39  4666.0  429.19  4676.6  430.28  4687.1  429.44
  4697.6  427.20  4718.7  425.96  4771.4  425.75  4803.7  424.22  4824.1  425.08
  4855.8  423.31  4908.5  424.56  4940.1  423.80  4961.2  424.51  4982.2  421.90
  4989.8  415.03  4992.5  414.53  4995.8  415.03  5008.1  415.32  5011.7  415.47
  5017.3  422.30  5039.7  428.10  5092.8  428.71  5173.8  433.43  5450.5  441.99
#Mann=8,-1,0
  4370.9    0.16       0  4392.1    0.05       0  4488.6    0.16       0
  4617.4    0.12       0  4803.7    0.16       0  4989.8    0.07       0
  4995.8    0.16       0  5008.1    0.05       0
Bank Sta=4989.8,4995.8
Exp/Cntr=0.3,0.1