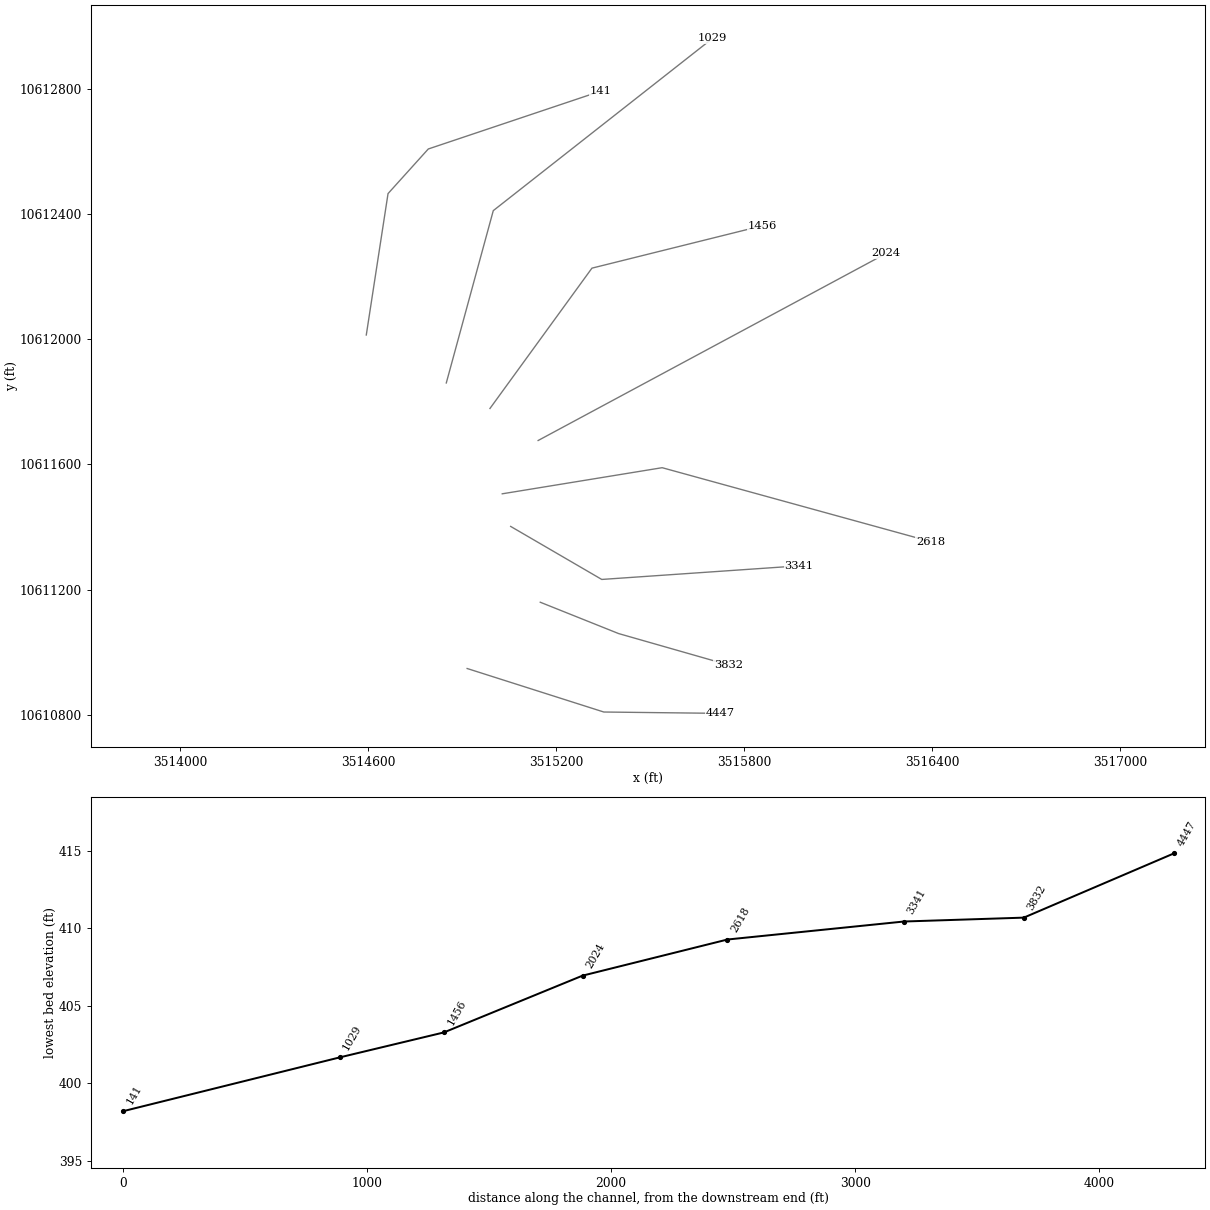
HEC-RAS study UNT047 IN CCTC.prj: UNT047 IN CCTC Base Level Engineering

--- UNT047 IN CCTC.g01 (geometry) --- (continued)

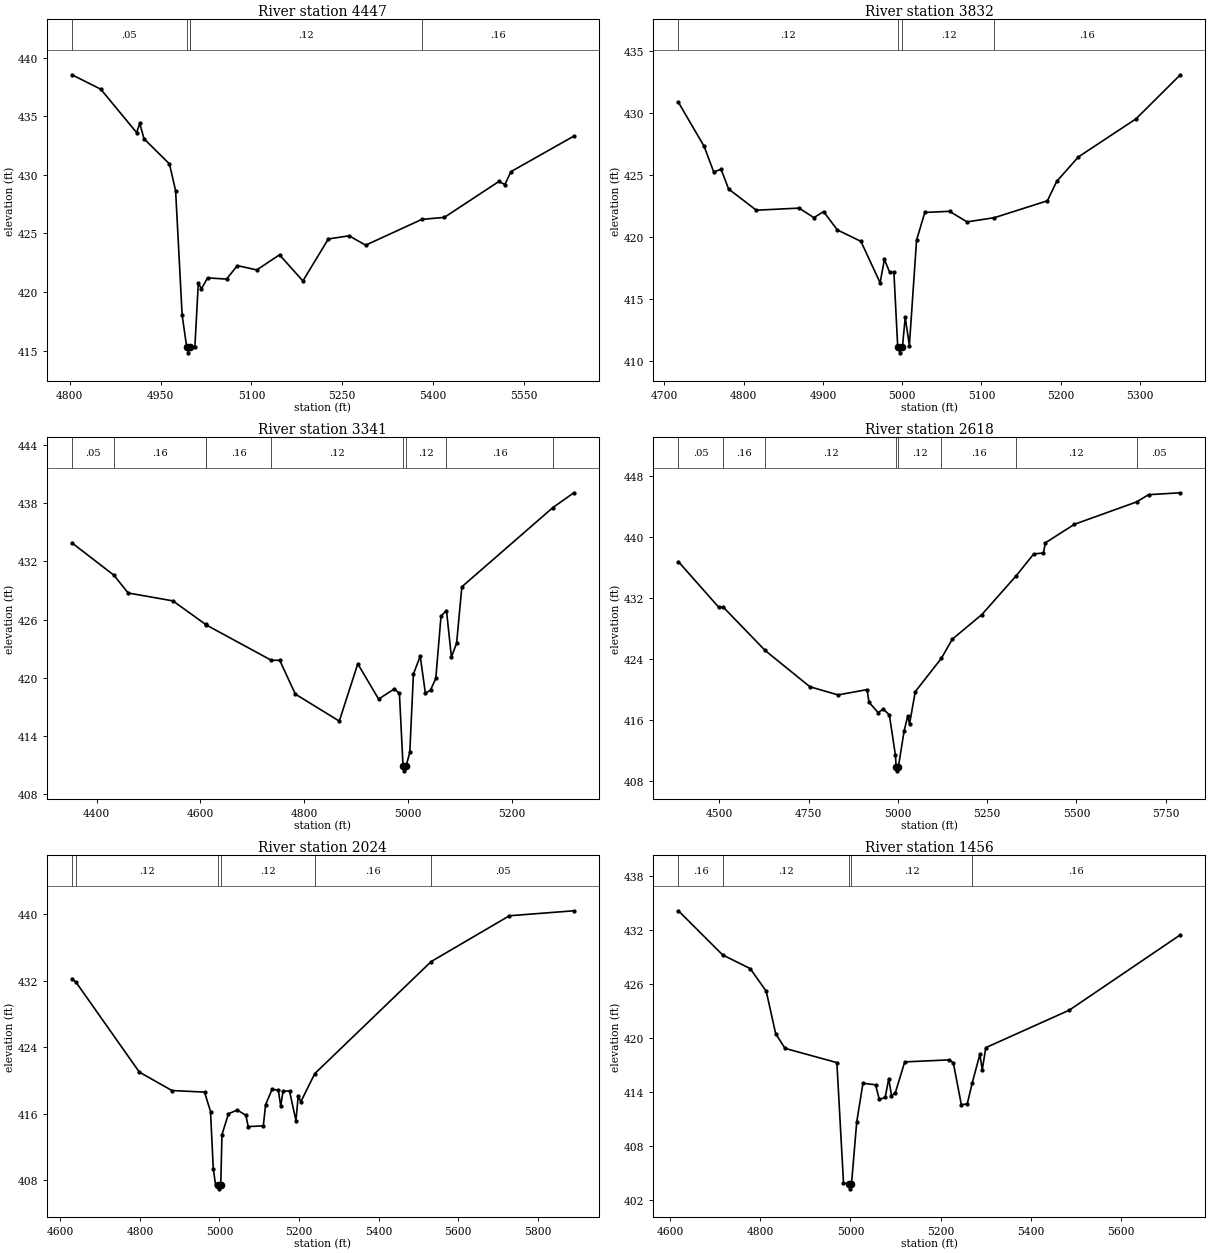
Type RM Length L Ch R = 1,4447,615,615,615
BEGIN DESCRIPTION:
UNT047 IN CCTC 8.0
END DESCRIPTION:
XS GIS Cut Line= 3
      3514916.21     10610948.64      3515352.41     10610809.76
      3515723.51     10610805.42
#Sta/Elev= 30
  4803.6  438.53  4851.2  437.30  4910.4  433.60  4915.6  434.39  4922.6  433.07
  4964.6  430.93  4974.8  428.64  4985.6  418.02  4993.1  415.32  4995.8  414.82
  4999.1  415.32  4999.3  415.32  5006.6  415.34  5012.3  420.75  5017.5  420.28
  5027.6  421.21  5059.0  421.11  5076.7  422.26  5108.9  421.89  5146.4  423.18
  5185.0  420.95  5227.0  424.53  5261.4  424.80  5288.6  424.00  5381.5  426.20
  5418.6  426.37  5508.6  429.43  5518.6  429.17  5528.6  430.27  5632.5  433.30
#Mann=5,-1,0
  4803.6    0.05       0  4993.1    0.07       0  4999.1    0.05       0
  4999.3    0.12       0  5381.5    0.16       0
Bank Sta=4993.1,4999.1
Exp/Cntr=0.3,0.1

Type RM Length L Ch R = 1,3832,491,491,491
BEGIN DESCRIPTION:
UNT047 IN CCTC 7.0
END DESCRIPTION:
XS GIS Cut Line= 3
      3515149.57     10611160.20      3515399.61     10611060.19
      3515749.60     10610960.19
#Sta/Elev= 30
  4717.6  430.86  4750.0  427.32  4762.1  425.26  4771.5  425.46  4780.9  423.88
  4815.9  422.17  4869.8  422.34  4888.6  421.57  4900.7  422.06  4918.2  420.58
  4947.9  419.66  4972.1  416.32  4977.5  418.21  4984.2  417.16  4989.5  417.16
  4994.3  411.18  4997.1  410.68  5000.3  411.18  5003.8  413.54  5009.0  411.27
  5018.1  419.76  5028.5  421.99  5059.7  422.08  5081.8  421.23  5116.4  421.57
  5183.2  422.93  5194.9  424.49  5222.2  426.46  5295.0  429.53  5350.9  433.08
#Mann=4,-1,0
  4717.6    0.12       0  4994.3    0.07       0  5000.3    0.12       0
  5116.4    0.16       0
Bank Sta=4994.3,5000.3
Exp/Cntr=0.3,0.1

Type RM Length L Ch R = 1,3341,723,723,723
BEGIN DESCRIPTION:
UNT047 IN CCTC 6.0
END DESCRIPTION:
XS GIS Cut Line= 3
      3515055.11     10611402.20      3515345.90     10611232.93
      3515974.94     10611276.32
#Sta/Elev= 30
  4352.6  433.90  4433.3  430.58  4461.0  428.74  4547.1  427.93  4610.3  425.50
  4611.4  425.45  4736.5  421.82  4752.9  421.81  4783.0  418.33  4867.7  415.55
  4903.3  421.45  4943.4  417.82  4973.5  418.86  4983.5  418.41  4990.5  410.93
  4993.2  410.43  4996.5  410.93  5003.5  412.33  5010.5  420.40  5023.6  422.24
  5033.6  418.40  5043.6  418.76  5053.6  419.95  5063.7  426.38  5074.2  426.93
  5083.7  422.15  5093.7  423.56  5103.8  429.38  5278.8  437.52  5319.6  439.06
#Mann=9,-1,0
  4352.6    0.05       0  4433.3    0.16       0  4610.3    0.12       0
  4611.4    0.16       0  4736.5    0.12       0  4990.5    0.07       0
  4996.5    0.12       0  5074.2    0.16       0  5278.8    0.05       0
Bank Sta=4990.5,4996.5
Exp/Cntr=0.3,0.1

Type RM Length L Ch R = 1,2618,594,594,594
BEGIN DESCRIPTION:
UNT047 IN CCTC 5.0
END DESCRIPTION:
XS GIS Cut Line= 3
      3515028.25     10611506.32      3515538.68     10611589.65
      3516395.42     10611353.78
#Sta/Elev= 30
  4385.3  436.71  4497.7  430.76  4511.3  430.73  4628.0  425.07  4753.6  420.30
  4832.5  419.23  4913.8  419.93  4919.1  418.27  4944.9  416.90  4958.7  417.38
  4976.1  416.61  4993.1  411.33  4995.3  409.77  4998.1  409.27  5001.3  409.77
  5017.5  414.50  5027.5  416.44  5032.7  415.43  5048.7  419.66  5122.0  424.04
  5152.4  426.54  5235.4  429.78  5330.6  434.82  5380.6  437.73  5407.8  437.85
  5413.0  439.18  5494.7  441.62  5668.7  444.55  5702.1  445.50  5791.1  445.75
#Mann=8,-1,0
  4385.3    0.05       0  4511.3    0.16       0  4628.0    0.12       0
  4995.3    0.07       0  5001.3    0.12       0  5122.0    0.16       0
  5330.6    0.12       0  5668.7    0.05       0
Bank Sta=4995.3,5001.3
Exp/Cntr=0.3,0.1

Type RM Length L Ch R = 1,2024,568,568,568
BEGIN DESCRIPTION:
UNT047 IN CCTC 4.0
END DESCRIPTION:
XS GIS Cut Line= 2
      3515142.81     10611676.44      3516253.97     10612273.68
#Sta/Elev= 30
  4629.2  432.21  4639.5  431.80  4798.5  420.99  4880.5  418.77  4962.5  418.58
  4977.5  416.24  4984.4  409.37  4990.1  407.46  4997.2  407.44  5000.0  406.94
  5003.2  407.44  5006.3  413.47  5022.6  415.97  5044.5  416.42  5066.4  415.80
  5072.1  414.43  5110.2  414.52  5115.9  417.07  5132.1  418.90  5147.8  418.83
  5154.0  416.89  5159.7  418.71  5176.0  418.71  5192.2  415.16  5197.9  418.09
  5204.6  417.43  5239.6  420.81  5532.1  434.29  5728.7  439.80  5890.7  440.40
#Mann=6,-1,0
  4629.2    0.16       0  4639.5    0.12       0  4997.2    0.07       0
  5003.2    0.12       0  5239.6    0.16       0  5532.1    0.05       0
Bank Sta=4997.2,5003.2
Exp/Cntr=0.3,0.1

Type RM Length L Ch R = 1,1456,427,427,427
BEGIN DESCRIPTION:
UNT047 IN CCTC 3.0
END DESCRIPTION:
XS GIS Cut Line= 3
      3514989.04     10611778.72      3515314.56     10612226.63
      3515858.86     10612362.06
#Sta/Elev= 30
  4617.9  434.12  4716.2  429.22  4777.3  427.71  4812.9  425.20  4833.8  420.50
  4854.6  418.86  4969.8  417.28  4984.5  403.95  4996.2  403.78  4998.9  403.28
  5002.2  403.78  5013.9  410.70  5027.7  414.99  5055.6  414.82  5064.1  413.19
  5077.1  413.42  5085.0  415.51  5091.1  413.59  5099.6  413.94  5120.5  417.36
  5218.0  417.58  5228.3  417.29  5246.1  412.63  5259.2  412.68  5270.5  415.04
  5287.4  418.21  5292.6  416.47  5300.5  418.94  5486.0  423.10  5732.5  431.45
#Mann=5,-1,0
  4617.9    0.16       0  4716.2    0.12       0  4996.2    0.07       0
  5002.2    0.12       0  5270.5    0.16       0
Bank Sta=4996.2,5002.2
Exp/Cntr=0.3,0.1

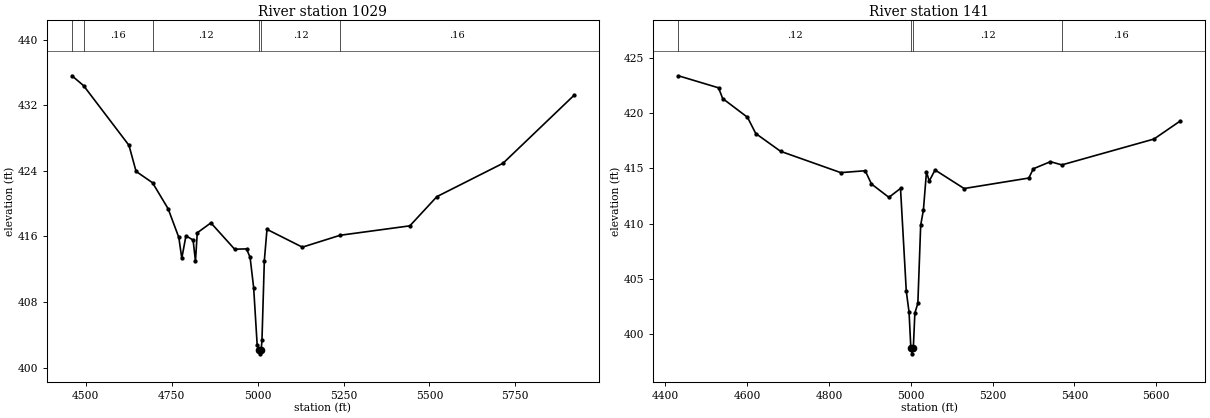
Type RM Length L Ch R = 1,1029,888,888,888
BEGIN DESCRIPTION:
UNT047 IN CCTC 2.0
END DESCRIPTION:
XS GIS Cut Line= 3
      3514849.60     10611860.14      3514999.61     10612410.19
      3515699.64     10612960.21
#Sta/Elev= 30
  4459.8  435.58  4493.6  434.38  4625.7  427.10  4646.4  423.92  4694.4  422.53
  4739.7  419.36  4770.8  415.86  4779.4  413.32  4791.5  416.06  4812.3  415.55
  4819.2  412.96  4824.4  416.43  4864.1  417.64  4933.2  414.43  4967.7  414.47
  4978.1  413.45  4988.5  409.75  4998.8  402.72  5004.5  402.17  5007.2  401.67
  5010.5  402.17  5012.7  403.34  5019.6  413.04  5027.3  416.85  5130.2  414.68
  5240.2  416.13  5443.0  417.28  5521.6  420.84  5714.1  424.91  5920.2  433.18
#Mann=6,-1,0
  4459.8    0.05       0  4493.6    0.16       0  4694.4    0.12       0
  5004.5    0.07       0  5010.5    0.12       0  5240.2    0.16       0
Bank Sta=5004.5,5010.5
Exp/Cntr=0.3,0.1

Type RM Length L Ch R = 1,141,0,0,0
BEGIN DESCRIPTION:
UNT047 IN CCTC 1.0
END DESCRIPTION:
XS GIS Cut Line= 4
      3514594.23     10612013.26      3514663.68     10612464.65
      3514792.15     10612607.01      3515340.74     10612791.03
#Sta/Elev= 30
  4431.9  423.38  4530.0  422.29  4540.1  421.32  4600.8  419.62  4621.0  418.15
  4681.7  416.54  4828.7  414.61  4888.6  414.78  4903.9  413.58  4946.5  412.37
  4974.9  413.18  4989.0  403.88  4995.8  401.97  5000.2  398.70  5003.0  398.20
  5006.2  398.70  5010.0  401.89  5017.3  402.78  5024.2  409.84  5030.9  411.23
  5038.4  414.69  5045.1  413.84  5059.3  414.85  5130.4  413.17  5288.6  414.12
  5299.6  414.96  5341.4  415.60  5369.4  415.31  5594.5  417.65  5659.0  419.29
#Mann=4,-1,0
  4431.9    0.12       0  5000.2    0.07       0  5006.2    0.12       0
  5369.4    0.16       0
Bank Sta=5000.2,5006.2
Exp/Cntr=0.3,0.1

Chan Stop Cuts=-1