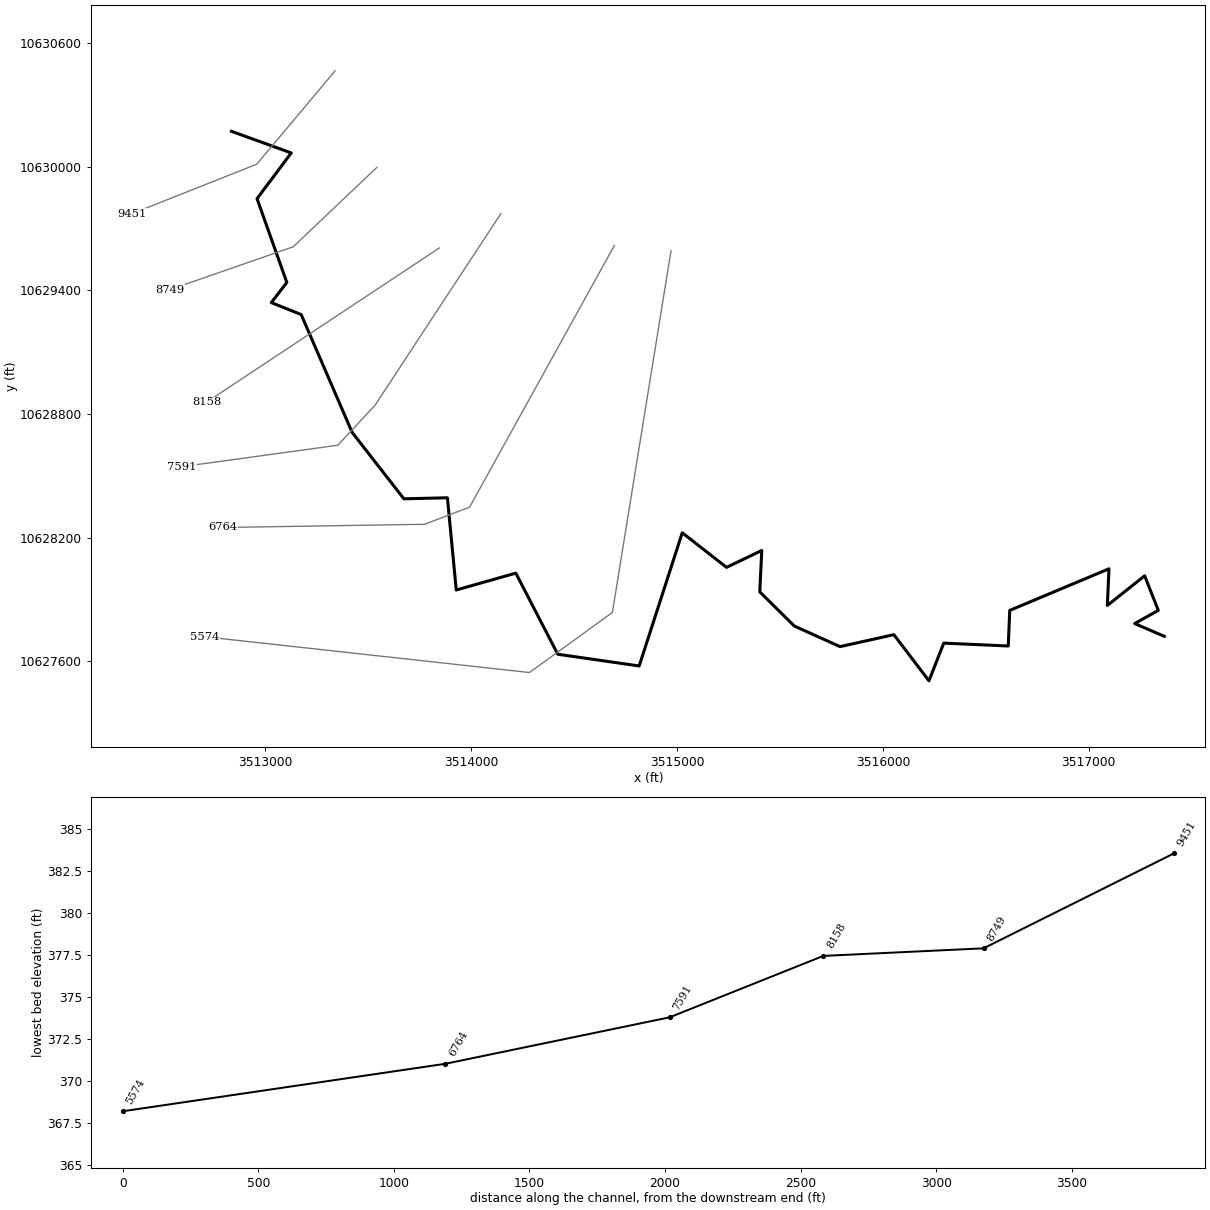
--- UNT050 IN CCTC.prj (project) ---

Proj Title=UNT050 IN CCTC Base Level Engineering
Current Plan=p01
Default Exp/Contr=0.3,0.1
English Units
Geom File=g01
Flow File=f01
Plan File=p01
Y Axis Title=Elevation
X Axis Title(PF)=Main Channel Distance
X Axis Title(XS)=Station
BEGIN DESCRIPTION:
UNT050 IN CCTC
END DESCRIPTION:
DSS Export Rating Curves= 0
DSS Export Rating Curve Sorted= 0
DSS Export Volume Flow Curves= 0
DXF OffsetX= 0
DXF OffsetY= 0
DXF ScaleX= 1
DXF ScaleY= 10

--- UNT050 IN CCTC.p01 (plan) ---

Plan Title=Multiple Run
Short Identifier=Multiple
Geom File=g01
Flow File=f01
Subcritical Flow
K Sum by GR= 0
Std Step Tol= 0.01
Critical Tol= 0.01
Num of Std Step Trials= 20
Max Error Tol= 0.3
Flow Tol Ratio= 0.001
Split Flow NTrial= 30
Split Flow Tol= 0.02
Split Flow Ratio= 0.02
Log Output Level= 0
Friction Slope Method= 1
Unsteady Friction Slope Method= 2
Unsteady Bridges Friction Slope Method= 1
Parabolic Critical Depth
Global Vel Dist=  1 , 1 , 1
Global Log Level= 0
CheckData=True
Encroach Param= -1, 0, 0, 0
BEGIN DESCRIPTION:
Multiple Run
END DESCRIPTION:

--- UNT050 IN CCTC.f01 (steady flow) ---

Flow Title=Multiple
Number of Profiles=7
Profile Names=10-year,25-year,50-year,1pct_min,100-year,1pct_plu,500-year
River Rch & RM= UNT050 IN CCTC,Reach-1,9451
    1421    1969    2424    2178    2946    3984    4339
River Rch & RM= UNT050 IN CCTC,Reach-1,8158
    1915    2690    3342    3025    4091    5533    6119
Boundary for River Rch & Prof#=UNT050 IN CCTC,Reach-1,1
Up Type=0
Dn Type=3
Dn Slope=0.005
Boundary for River Rch & Prof#=UNT050 IN CCTC,Reach-1,2
Up Type=0
Dn Type=3
Dn Slope=0.005
Boundary for River Rch & Prof#=UNT050 IN CCTC,Reach-1,3
Up Type=0
Dn Type=3
Dn Slope=0.005
Boundary for River Rch & Prof#=UNT050 IN CCTC,Reach-1,4
Up Type=0
Dn Type=3
Dn Slope=0.005
Boundary for River Rch & Prof#=UNT050 IN CCTC,Reach-1,5
Up Type=0
Dn Type=3
Dn Slope=0.005
Boundary for River Rch & Prof#=UNT050 IN CCTC,Reach-1,6
Up Type=0
Dn Type=3
Dn Slope=0.005
Boundary for River Rch & Prof#=UNT050 IN CCTC,Reach-1,7
Up Type=0
Dn Type=3
Dn Slope=0.005

--- UNT050 IN CCTC.g01 (geometry) ---

Geom Title=Existing Conditions
Program Version=4.10

River Reach=UNT050 IN CCTC  ,Reach-1
Reach XY= 30
        3512836.       10630173.      3513126.25       10630068.
        3512960.       10629846.      3513104.75       10629439.
       3513029.5       10629341.       3513174.5       10629283.
      3513421.75       10628711.      3513673.25       10628388.
      3513884.75       10628393.      3513927.75       10627945.
        3514217.       10628027.      3514420.75       10627633.
      3514816.25       10627576.       3515025.5       10628223.
       3515240.5       10628055.      3515411.75       10628137.
        3515402.       10627936.      3515569.75       10627770.
      3515791.75       10627670.       3516053.5       10627728.
      3516223.75       10627504.      3516295.75       10627687.
        3516609.       10627673.      3516616.25       10627846.
      3517098.25       10628048.      3517090.25       10627870.
       3517271.5       10628014.      3517337.75       10627846.
        3517223.       10627782.        3517367.       10627720.

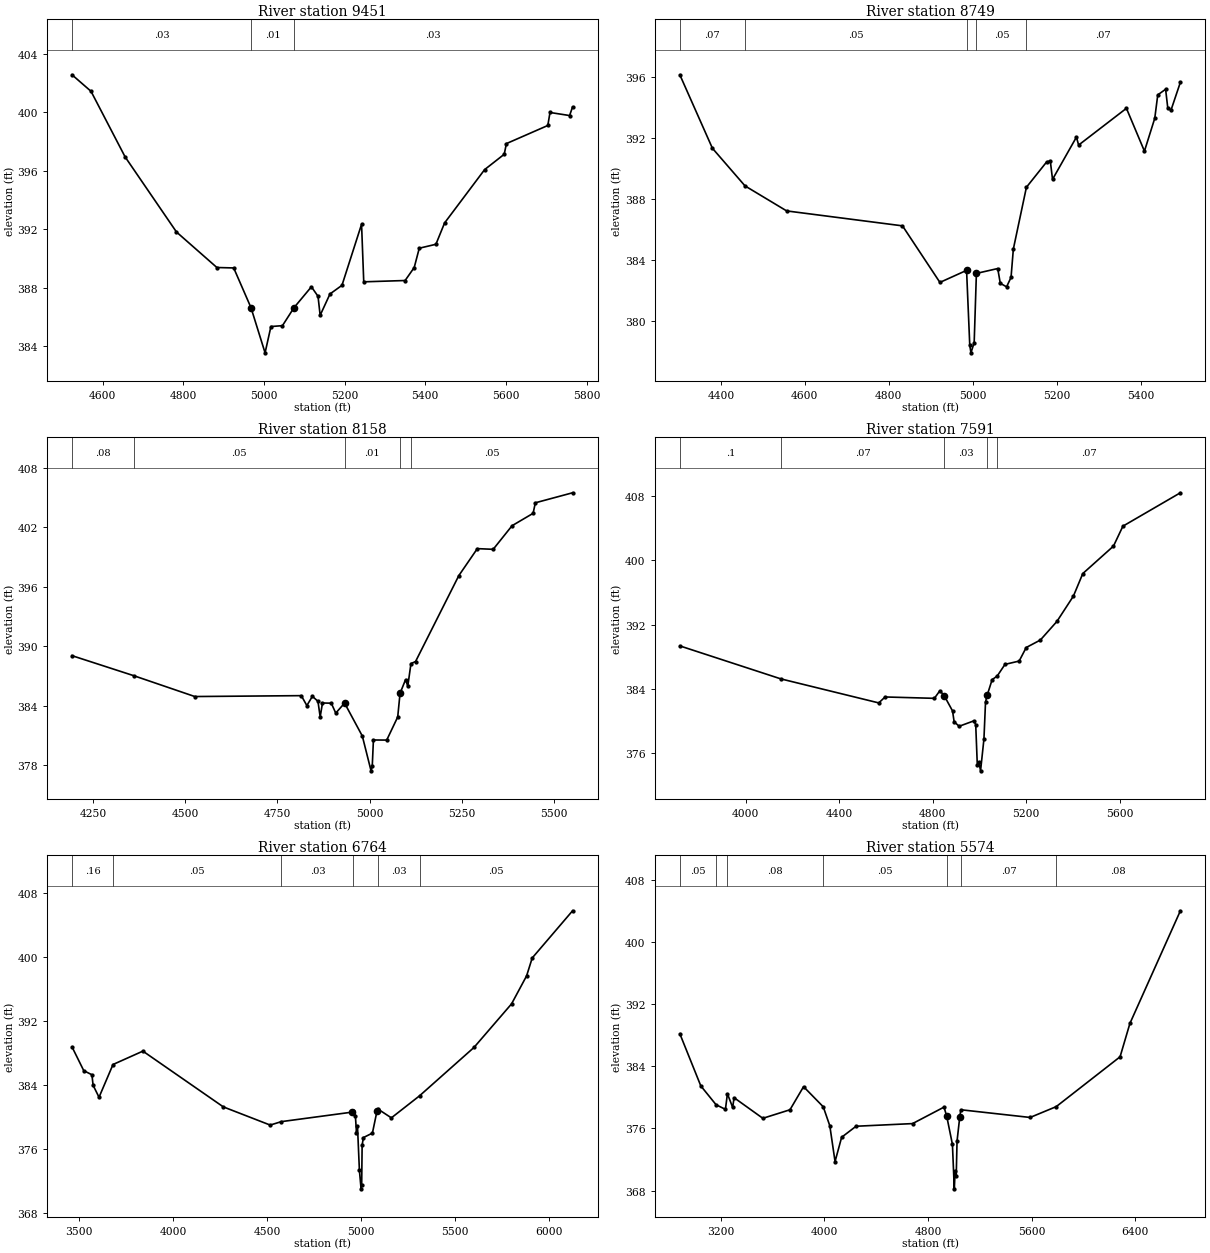
Type RM Length L Ch R = 1 ,9451    ,702,702,702
BEGIN DESCRIPTION:
UNT050 IN CCTC 6.0
END DESCRIPTION:
XS GIS Cut Line= 3
      3513338.92     10630466.41      3512958.69     10630013.25
       3512354.6      10629773.7
#Sta/Elev= 30
    4524  402.57  4571.1  401.44  4655.7  396.95  4783.1  391.81  4883.3  389.38
    4925  389.35  4967.9  386.63  5002.8  383.54  5017.3  385.34  5045.9   385.4
  5074.5  386.63  5117.7  388.06  5134.1  387.41  5139.4  386.11  5163.8  387.57
  5193.5  388.16  5242.1  392.34  5247.5   388.4  5350.1  388.49  5372.7  389.38
  5385.2   390.7  5426.5  390.97    5448  392.43  5547.3  396.08  5595.9  397.13
  5601.3  397.86    5704   399.1  5709.4  399.99    5758  399.78  5765.4  400.37
#Mann= 3 , 0 , 0
    4524     .03       0  4967.9     .01       0  5074.5     .03       0
Bank Sta=4967.9,5074.5
XS Rating Curve= 0 ,0
Exp/Cntr=0.3,0.1

Type RM Length L Ch R = 1 ,8749    ,591,591,591
BEGIN DESCRIPTION:
UNT050 IN CCTC 5.0
END DESCRIPTION:
XS GIS Cut Line= 3
        3513542.     10629997.61      3513135.78     10629612.21
      3512538.72     10629404.54
#Sta/Elev= 30
  4302.3  396.14  4379.9  391.32  4457.6  388.85  4556.7  387.21  4832.6  386.23
  4921.7  382.52  4985.2  383.31  4992.8   378.4  4995.6   377.9  5003.3  378.57
  5008.6  383.11  5059.4  383.43  5065.5  382.46  5080.5  382.23  5091.1  382.85
  5096.6  384.71  5127.7  388.76  5175.8  390.42  5184.6  390.49  5189.9  389.28
  5246.8  392.05  5252.1  391.53  5365.9  393.94  5408.8  391.13  5433.4  393.29
  5440.5  394.82  5459.2  395.19  5464.5  393.93  5472.3  393.84  5494.4  395.65
#Mann= 5 ,-1 , 0
  4302.3     .07       0  4457.6     .05       0  4985.2     .03       0
  5008.6     .05       0  5127.7     .07       0
Bank Sta=4985.2,5008.6
XS Rating Curve= 0 ,0
Exp/Cntr=0.3,0.1

Type RM Length L Ch R = 1 ,8158    ,567,567,567
BEGIN DESCRIPTION:
UNT050 IN CCTC 4.0
END DESCRIPTION:
XS GIS Cut Line= 2
      3513845.91     10629606.69      3512714.27     10628856.89
#Sta/Elev= 30
  4192.8  389.06  4360.4  387.04  4525.8  384.94  4814.6  385.03  4829.7  384.03
  4844.7  384.96  4859.8  384.46  4865.8  382.89  4872.1  384.29  4895.9  384.27
  4908.1  383.27    4932  384.28  4980.1  380.96  5003.8  377.45  5007.1  377.95
  5010.2  380.56  5046.3  380.55  5076.1  382.88  5082.4  385.26  5097.4  386.65
  5103.4  385.98    5112  388.26  5124.5  388.47  5241.8  397.13    5292  399.85
    5335  399.78  5386.2  402.16  5443.3  403.41  5449.3  404.47  5550.3  405.48
#Mann= 5 ,-1 , 0
  4192.8     .08       0  4360.4     .05       0    4932     .01       0
  5082.4     .03       0    5112     .05       0
Bank Sta=4932,5082.4
XS Rating Curve= 0 ,0
Exp/Cntr=0.3,0.1

Type RM Length L Ch R = 1 ,7591    ,827,827,827
BEGIN DESCRIPTION:
UNT050 IN CCTC 3.0
END DESCRIPTION:
XS GIS Cut Line= 4
      3514144.48     10629773.31      3513533.39     10628842.79
      3513352.83     10628648.35      3512595.85     10628544.18
#Sta/Elev= 30
  3717.6  389.36  4150.3  385.25  4569.2  382.26  4596.2     383  4807.2  382.83
  4830.8  383.78  4849.3  383.16    4885  381.26  4891.8  379.91  4913.3  379.35
  4976.8  380.03  4984.2  379.55    4991  374.53  4998.1  374.85  5004.9   373.8
  5019.4  377.77  5026.2  382.39  5033.5  383.24  5054.5  385.16    5076   385.6
  5109.5  387.06  5170.1  387.47  5200.4  389.16  5260.9  390.09  5331.6   392.4
  5402.3  395.56  5442.6  398.37  5573.9  401.79  5614.2  404.27  5860.3  408.43
#Mann= 5 ,-1 , 0
  3717.6      .1       0  4150.3     .07       0  4849.3     .03       0
  5033.5     .05       0    5076     .07       0
Bank Sta=4849.3,5033.5
XS Rating Curve= 0 ,0
Exp/Cntr=0.3,0.1

Type RM Length L Ch R = 1 ,6764    ,1190,1190,1190
BEGIN DESCRIPTION:
UNT050 IN CCTC 2.0
END DESCRIPTION:
XS GIS Cut Line= 4
      3514695.73     10629618.42      3513992.63     10628347.62
      3513773.88     10628264.29      3512794.72     10628248.67
#Sta/Elev= 30
  3461.8  388.76  3524.4  385.79  3567.9  385.28  3574.1  383.97  3605.7  382.47
  3680.1  386.56  3839.3  388.23  4267.6  381.27  4517.2     379  4576.8  379.43
  4951.9  380.61  4960.2  380.77  4970.9  380.17  4976.7  378.07    4982  378.92
  4992.3  373.35  5001.2  371.04  5004.4  371.54  5006.8   376.5  5013.7  377.44
  5061.6     378  5086.4   380.8  5091.7  380.99  5162.5   379.9  5312.5  382.65
  5602.5  388.69  5802.6  394.13  5882.6  397.62  5912.6  399.86  6127.5  405.75
#Mann= 6 ,-1 , 0
  3461.8     .16       0  3680.1     .05       0  4576.8     .03       0
  4960.2     .01       0  5091.7     .03       0  5312.5     .05       0
Bank Sta=4951.9,5086.4
XS Rating Curve= 0 ,0
Exp/Cntr=0.3,0.1

Type RM Length L Ch R = 1 ,5574    ,0,0,0
BEGIN DESCRIPTION:
UNT050 IN CCTC 1.0
END DESCRIPTION:
XS GIS Cut Line= 4
      3514970.88     10629592.77      3514686.17     10627835.85
      3514283.39     10627544.18      3512706.95      10627717.8
#Sta/Elev= 30
  2884.1  388.17    3046  381.46  3163.7  379.04  3236.1  378.44  3251.4  380.45
  3291.9  378.69  3302.8  379.94  3524.9  377.29  3734.3  378.39    3839  381.36
    3991  378.77  4041.6  376.33  4082.1  371.73  4132.8  374.85  4244.2  376.27
  4680.2  376.61    4923  378.73  4943.9  377.56  4987.9  373.94  5002.4  368.22
  5008.8  370.54  5017.3  369.88  5023.5  374.35  5044.4  377.46  5052.9  378.39
  5587.6   377.4  5788.8  378.79  6281.7   385.2  6357.6  389.49  6747.2  403.98
#Mann= 7 ,-1 , 0
  2884.1     .05       0  3163.7      .1       0  3251.4     .08       0
    3991     .05       0  4943.9     .01       0  5052.9     .07       0
  5788.8     .08       0
Bank Sta=4943.9,5044.4
XS Rating Curve= 0 ,0
Exp/Cntr=0.3,0.1

Chan Stop Cuts=-1
Use User Specified Reach Order=0
Composite Channel Slope=5