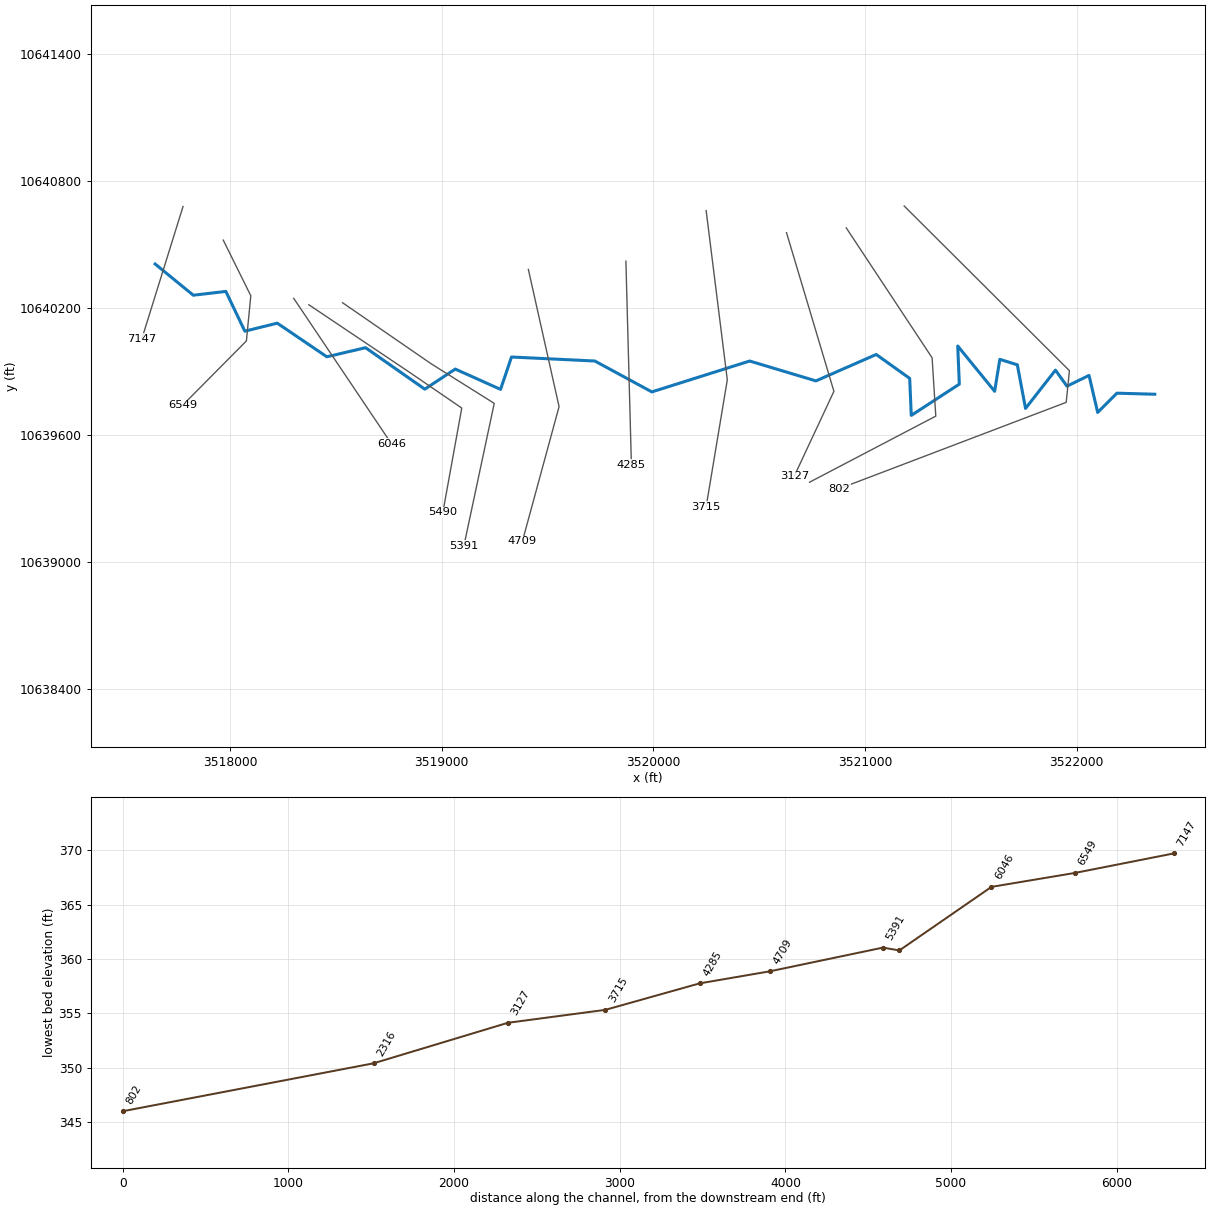
--- UNT057 IN CCTC.prj (project) ---

Proj Title=UNT057 IN CCTC Base Level Engineering
Current Plan=p01
Default Exp/Contr=0.3,0.1
English Units
Geom File=g01
Flow File=f01
Plan File=p01
Y Axis Title=Elevation
X Axis Title(PF)=Main Channel Distance
X Axis Title(XS)=Station
BEGIN DESCRIPTION:
UNT057 IN CCTC
END DESCRIPTION:
DSS Export Rating Curves= 0
DSS Export Rating Curve Sorted= 0
DSS Export Volume Flow Curves= 0
DXF OffsetX= 0
DXF OffsetY= 0
DXF ScaleX= 1
DXF ScaleY= 10

--- UNT057 IN CCTC.p01 (plan) ---

Plan Title=Multiple Run
Short Identifier=Multiple
Geom File=g01
Flow File=f01
Subcritical Flow
K Sum by GR= 0
Std Step Tol= 0.01
Critical Tol= 0.01
Num of Std Step Trials= 20
Max Error Tol= 0.3
Flow Tol Ratio= 0.001
Split Flow NTrial= 30
Split Flow Tol= 0.02
Split Flow Ratio= 0.02
Log Output Level= 0
Friction Slope Method= 1
Unsteady Friction Slope Method= 2
Unsteady Bridges Friction Slope Method= 1
Parabolic Critical Depth
Global Vel Dist=  1 , 1 , 1
Global Log Level= 0
CheckData=True
Encroach Param= -1, 0, 0, 0
BEGIN DESCRIPTION:
Multiple Run
END DESCRIPTION:

--- UNT057 IN CCTC.f01 (steady flow) ---

Flow Title=Multiple
Number of Profiles=7
Profile Names=10-year,25-year,50-year,1pct_min,100-year,1pct_plu,500-year
River Rch & RM= UNT057 IN CCTC,Reach-1,7147
    1298    1775    2165    1926    2605    3523    3760
River Rch & RM= UNT057 IN CCTC,Reach-1,6046
    1704    2365    2913    2615    3537    4783    5200
Boundary for River Rch & Prof#=UNT057 IN CCTC,Reach-1,1
Up Type=0
Dn Type=3
Dn Slope=0.005
Boundary for River Rch & Prof#=UNT057 IN CCTC,Reach-1,2
Up Type=0
Dn Type=3
Dn Slope=0.005
Boundary for River Rch & Prof#=UNT057 IN CCTC,Reach-1,3
Up Type=0
Dn Type=3
Dn Slope=0.005
Boundary for River Rch & Prof#=UNT057 IN CCTC,Reach-1,4
Up Type=0
Dn Type=3
Dn Slope=0.005
Boundary for River Rch & Prof#=UNT057 IN CCTC,Reach-1,5
Up Type=0
Dn Type=3
Dn Slope=0.005
Boundary for River Rch & Prof#=UNT057 IN CCTC,Reach-1,6
Up Type=0
Dn Type=3
Dn Slope=0.005
Boundary for River Rch & Prof#=UNT057 IN CCTC,Reach-1,7
Up Type=0
Dn Type=3
Dn Slope=0.005

--- UNT057 IN CCTC.g01 (geometry) ---

Geom Title=Existing Conditions
Program Version=4.10

River Reach=UNT057 IN CCTC  ,Reach-1
Reach XY= 30
      3517645.57     10640407.61        3517826.       10640260.
      3517979.75       10640278.       3518069.5       10640090.
      3518222.75       10640128.        3518457.       10639969.
        3518640.       10640012.        3518920.       10639816.
        3519064.       10639911.        3519278.       10639815.
      3519329.75       10639968.      3519723.75       10639949.
        3519993.       10639803.      3520455.25       10639949.
       3520768.5       10639855.      3521053.25       10639980.
       3521211.5       10639867.        3521219.       10639692.
      3521446.16      10639839.8       3521438.5       10640020.
        3521613.       10639806.       3521637.5       10639957.
      3521720.25       10639931.        3521759.       10639725.
       3521900.5       10639906.      3521954.75       10639830.
        3522059.       10639881.        3522100.       10639706.
        3522191.       10639797.      3522369.75       10639792.

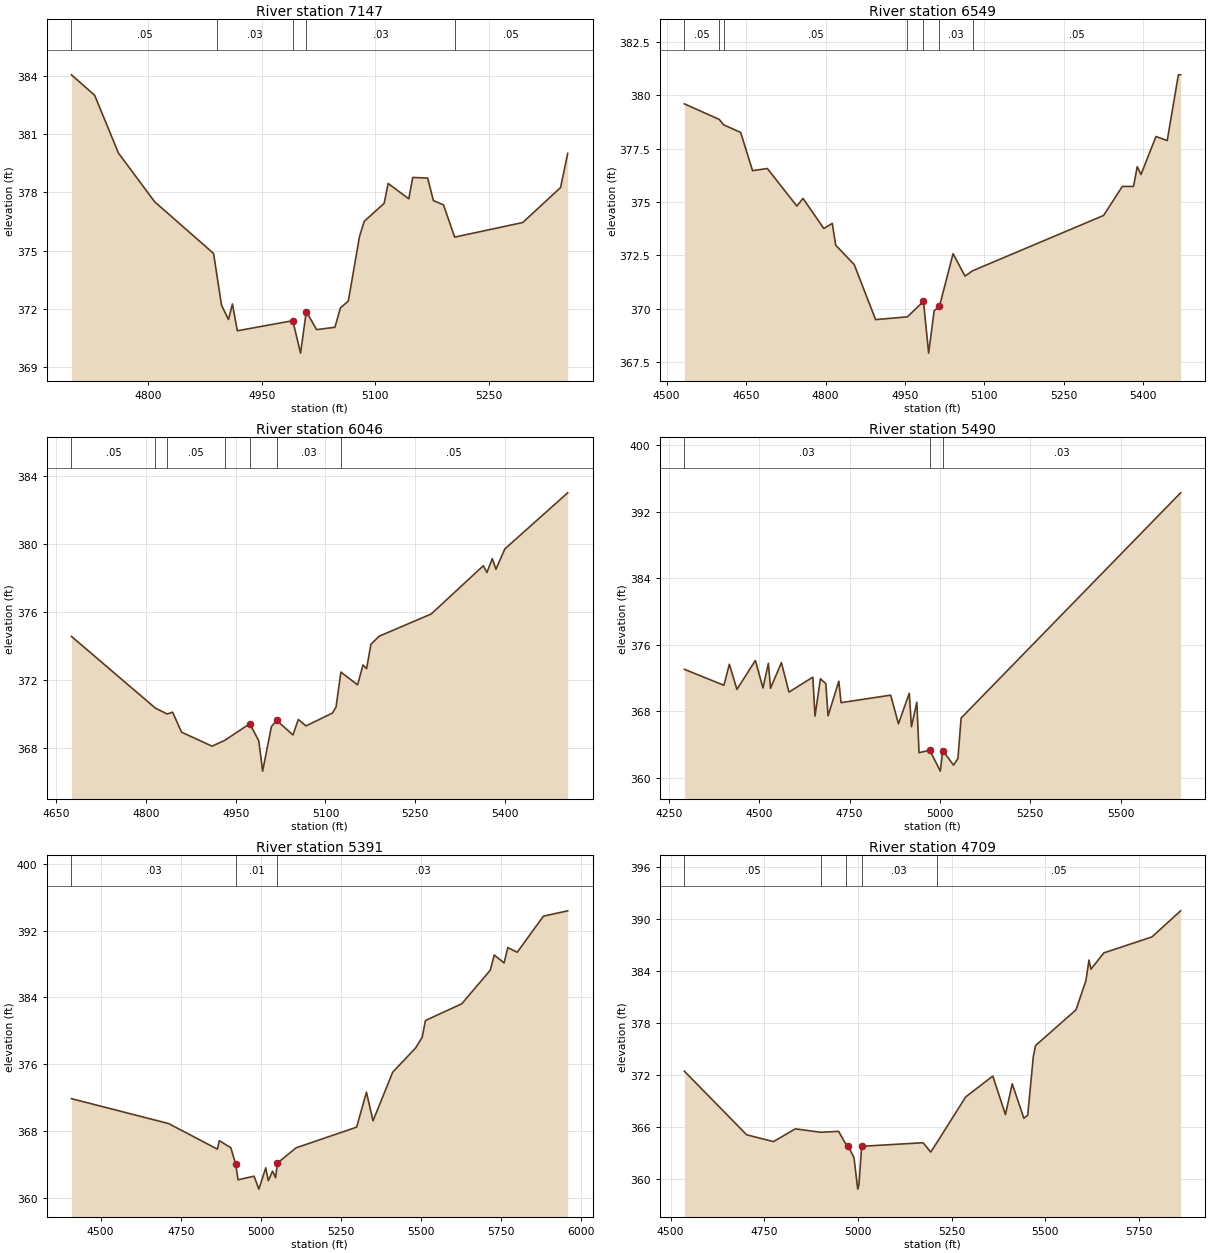
Type RM Length L Ch R = 1 ,7147    ,598,598,598
BEGIN DESCRIPTION:
UNT057 IN CCTC 8.0
END DESCRIPTION:
XS GIS Cut Line= 2
      3517777.41      10640679.4      3517582.63      10640053.5
#Sta/Elev= 30
  4698.5  384.04  4729.1  382.99  4760.5  380.02  4808.3  377.51  4886.2  374.85
  4891.3  373.56  4896.7  372.19  4905.9  371.45  4911.1  372.25  4917.6  370.87
  4990.9  371.39  5001.1  369.72  5008.7  371.86  5022.3  370.93  5046.5  371.05
  5053.8  372.05  5064.2   372.4    5079  375.72  5085.2   376.5  5111.6  377.43
  5116.8  378.45  5144.1  377.66  5149.3  378.76    5169  378.73  5176.6  377.57
  5189.9  377.35  5204.7  375.69  5294.6  376.44  5344.6  378.24    5354     380
#Mann= 5 ,-1 , 0
  4698.5     .05       0  4891.3     .03       0  4990.9     .01       0
  5008.7     .03       0  5204.7     .05       0
Bank Sta=4990.9,5008.7
XS Rating Curve= 0 ,0
Exp/Cntr=0.3,0.1

Type RM Length L Ch R = 1 ,6549    ,503,503,503
BEGIN DESCRIPTION:
Mapping XS d54edd29
END DESCRIPTION:
XS GIS Cut Line= 4
      3517967.52     10640520.51      3518097.72     10640257.49
      3518076.89     10640043.95      3517774.79     10639739.26
#Sta/Elev= 30
  4533.5   379.6  4599.4  378.87  4607.4  378.62  4639.8  378.26  4662.2  376.47
  4690.2  376.57  4745.9  374.81  4757.5  375.17  4796.8  373.76  4812.8     374
  4819.2  372.98  4854.2  372.07  4894.6  369.49  4954.5  369.62    4985  370.34
  4994.8  367.92  5005.1   369.9  5015.2  370.11  5040.9  372.58  5063.5  371.53
    5078  371.78  5325.1  374.37  5360.5  375.73  5381.7  375.73  5388.7  376.66
  5395.8  376.29  5424.1  378.07  5445.3  377.88  5466.4  380.96  5470.6  380.96
#Mann= 7 ,-1 , 0
  4533.5     .05       0  4599.4     .16       0  4607.4     .05       0
  4954.5     .03       0    4985     .01       0  5015.2     .03       0
    5078     .05       0
Bank Sta=4985,5015.2
XS Rating Curve= 0 ,0
Exp/Cntr=0.3,0.1

Type RM Length L Ch R = 1 ,6046    ,556,556,556
BEGIN DESCRIPTION:
UNT057 IN CCTC 7.0
END DESCRIPTION:
XS GIS Cut Line= 2
      3518300.44     10640245.39      3518762.67     10639557.46
#Sta/Elev= 30
  4675.8  374.57  4815.9  370.35  4835.6     370  4844.7  370.11  4859.7  368.93
  4910.7  368.11  4931.7  368.45  4973.7  369.43  4988.7  368.42  4995.1  366.64
  5009.7  369.26  5018.7  369.62  5045.7  368.77  5054.7  369.68  5067.6   369.3
  5111.7  370.06  5117.7  370.41  5125.8  372.47  5153.7  371.72  5162.7  372.89
  5168.7  372.67    5176  374.11  5189.7  374.58  5276.7  375.89  5363.7  378.73
  5369.7  378.33  5378.7  379.15  5384.7  378.52  5399.7  379.72  5504.6  383.02
#Mann= 7 ,-1 , 0
  4675.8     .05       0  4815.9     .07       0  4835.6     .05       0
  4931.7     .03       0  4973.7     .01       0  5018.7     .03       0
  5125.8     .05       0
Bank Sta=4973.7,5018.7
XS Rating Curve= 0 ,0
Exp/Cntr=0.3,0.1

Type RM Length L Ch R = 1 ,5490    ,99,99,99
BEGIN DESCRIPTION:
UNT057 IN CCTC 6.0
END DESCRIPTION:
XS GIS Cut Line= 4
      3518372.06     10640214.99      3518847.33     10639895.97
      3519094.72      10639726.7      3519005.34     10639233.81
#Sta/Elev= 30
  4292.7  373.04  4402.1  371.12  4417.1  373.65  4438.1  370.62  4489.1  374.11
  4510.1   370.8  4525.1  373.76  4531.1  370.76  4561.1  373.85  4582.1   370.3
  4648.1   372.1  4654.1  367.42  4669.1   371.9  4684.1  371.31  4690.2  367.44
  4720.1  371.61  4726.2  369.03  4863.5  369.93  4885.1  366.49    4915  370.16
    4921  366.13  4935.9  369.08    4942  363.01  4971.8   363.3  5000.9  360.79
  5007.7  363.27  5037.5  361.51  5049.6  362.31  5058.5  367.18  5665.8  394.28
#Mann= 3 , 0 , 0
  4292.7     .03       0  4971.8     .01       0  5007.7     .03       0
Bank Sta=4971.8,5007.7
XS Rating Curve= 0 ,0
Exp/Cntr=0.3,0.1

Type RM Length L Ch R = 1 ,5391    ,682,682,682
BEGIN DESCRIPTION:
UNT057 IN CCTC 5.0
END DESCRIPTION:
XS GIS Cut Line= 4
      3518531.34     10640224.54      3518950.19     10639935.91
      3519248.14     10639748.92       3519104.9     10639076.14
#Sta/Elev= 30
    4409  371.88    4712   368.9  4864.2  365.84  4870.3  366.85  4906.1  366.01
    4921  364.11  4928.8  362.17  4978.7   362.6  4993.7  361.05  5015.2   363.6
  5023.2  362.06  5036.4  363.21  5045.8  362.42  5051.7  364.17  5109.5  365.99
  5298.8  368.47  5329.4  372.65  5349.9  369.23  5411.3  375.05  5483.2  377.97
  5503.3  379.24  5513.5  381.24  5626.8  383.24  5715.7  387.26  5728.2  389.08
  5758.9  388.13  5770.4  389.97  5799.8  389.41  5881.6  393.73  5957.3  394.37
#Mann= 3 , 0 , 0
    4409     .03       0    4921     .01       0  5051.7     .03       0
Bank Sta=4921,5051.7
XS Rating Curve= 0 ,0
Exp/Cntr=0.3,0.1

Type RM Length L Ch R = 1 ,4709    ,424,424,424
BEGIN DESCRIPTION:
UNT057 IN CCTC 4.0
END DESCRIPTION:
XS GIS Cut Line= 3
      3519409.38     10640382.12      3519554.54     10639733.31
      3519381.04     10639096.37
#Sta/Elev= 30
  4536.7  372.47  4702.9  365.14  4774.4  364.35  4833.1  365.82  4900.6  365.43
  4948.6  365.53  4968.4  364.01  4973.5  363.86  4989.6  362.49  4999.6  358.87
  5002.8  359.37  5010.1  363.81    5174  364.22  5194.5  363.15  5209.9  364.17
  5287.7   369.5  5360.3  371.91    5394  367.47  5412.1  371.02  5443.2  367.04
  5453.5  367.41  5468.3  374.12  5474.3  375.43  5582.4  379.55    5609  382.94
    5617  385.29  5622.2  384.24  5656.8  386.12  5785.2  387.96  5861.7  390.97
#Mann= 5 ,-1 , 0
  4536.7     .05       0  4900.6     .03       0  4968.4     .01       0
  5010.1     .03       0  5209.9     .05       0
Bank Sta=4973.5,5010.1
XS Rating Curve= 0 ,0
Exp/Cntr=0.3,0.1

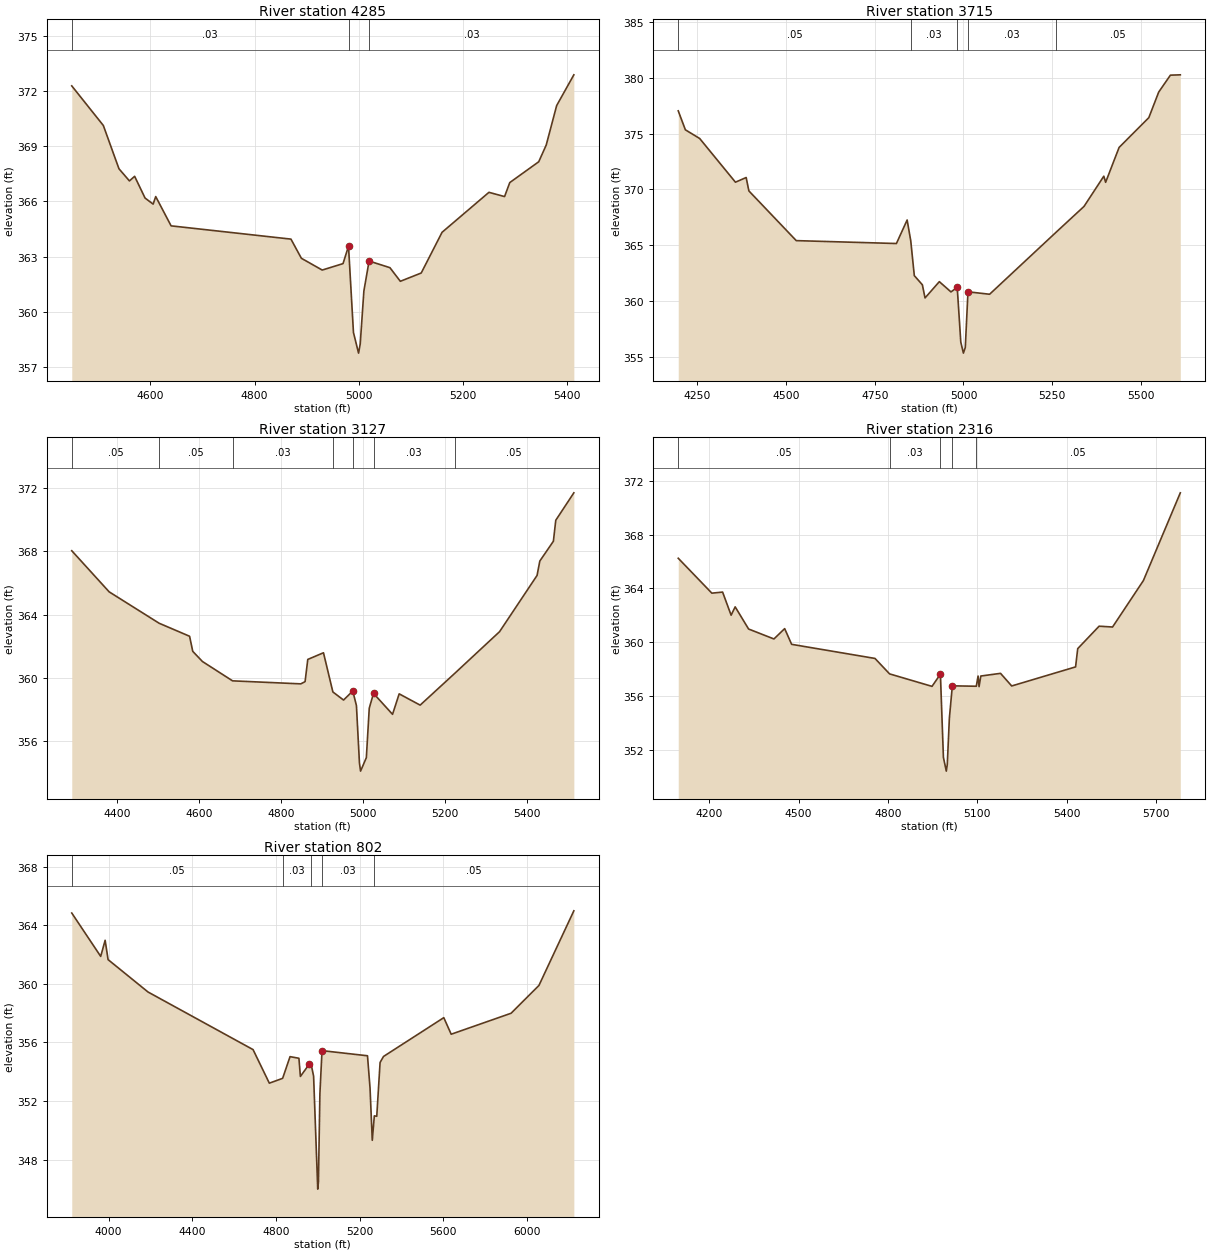
Type RM Length L Ch R = 1 ,4285    ,570,570,570
BEGIN DESCRIPTION:
UNT057 IN CCTC 3.0
END DESCRIPTION:
XS GIS Cut Line= 2
      3519870.37      10640420.8      3519896.42     10639457.25
#Sta/Elev= 30
    4449  372.27  4509.6  370.12  4539.6  367.77  4559.7  367.11  4569.7  367.36
  4589.7  366.18  4605.2  365.85  4610.2  366.26  4639.7  364.67  4869.8  363.95
  4889.8  362.91  4929.8  362.27  4969.8  362.62  4980.3  363.57  4989.8  358.88
  4999.6  357.76  5002.8  358.26  5009.8  361.13  5019.8  362.76  5059.8   362.4
  5079.8  361.66  5119.9  362.11  5159.9  364.32  5249.9  366.49  5279.9  366.26
  5289.9  367.02  5345.5  368.15  5359.9  369.06  5379.9   371.2  5412.9  372.87
#Mann= 3 , 0 , 0
    4449     .03       0  4980.3     .01       0  5019.8     .03       0
Bank Sta=4980.3,5019.8
XS Rating Curve= 0 ,0
Exp/Cntr=0.3,0.1

Type RM Length L Ch R = 1 ,3715    ,588,588,588
BEGIN DESCRIPTION:
UNT057 IN CCTC 2.0
END DESCRIPTION:
XS GIS Cut Line= 3
      3520249.61     10640660.15      3520349.61     10639860.19
       3520249.6     10639260.15
#Sta/Elev= 30
  4196.4  377.05  4216.5  375.35  4256.8  374.57  4357.6  370.65  4387.8  371.07
  4395.4  369.87  4528.9  365.41  4811.1  365.15  4841.3  367.26  4851.5  365.39
  4861.5  362.27  4884.2  361.45  4891.7  360.27    4932  361.73  4964.8  360.81
  4982.4  361.22  4992.5   356.3  4999.8  355.32  5005.1  355.82  5012.7  360.82
  5073.6   360.6  5261.2  366.17  5339.7  368.48  5395.4  371.19  5400.5  370.64
  5438.5  373.77  5522.2  376.44    5550  378.73    5583  380.25  5610.9  380.28
#Mann= 5 ,-1 , 0
  4196.4     .05       0  4851.5     .03       0  4982.4     .01       0
  5012.7     .03       0  5261.2     .05       0
Bank Sta=4982.4,5012.7
XS Rating Curve= 0 ,0
Exp/Cntr=0.3,0.1

Type RM Length L Ch R = 1 ,3127    ,811,811,811
BEGIN DESCRIPTION:
Mapping XS 602151c7
END DESCRIPTION:
XS GIS Cut Line= 3
      3520629.44     10640555.71       3520853.4      10639805.7
      3520666.05     10639404.97
#Sta/Elev= 30
  4288.5  368.02  4379.7  365.43  4501.7  363.45    4576  362.63  4583.7  361.68
  4607.3  361.04  4680.8  359.82  4847.4  359.63  4857.8  359.77  4864.4  361.17
  4902.7  361.59  4925.6  359.12  4951.7  358.61  4974.2  359.18  4983.1  358.26
  4990.5  354.63  4993.2  354.13  5007.3  354.98  5014.4   358.1  5024.8  359.03
  5071.2  357.71  5087.4     359  5138.6  358.29  5222.5  360.28  5332.4  362.92
  5423.8  366.46  5430.6  367.37  5463.7  368.62  5469.5  369.94  5513.6  371.67
#Mann= 7 ,-1 , 0
  4288.5     .05       0  4501.7     .05       0  4680.8     .03       0
  4925.6     .03       0  4974.2     .01       0  5024.8     .03       0
  5222.5     .05       0
Bank Sta=4974.2,5024.8
XS Rating Curve= 0 ,0
Exp/Cntr=0.3,0.1

Type RM Length L Ch R = 1 ,2316    ,1514,1514,1514
BEGIN DESCRIPTION:
Mapping XS a74e692c
END DESCRIPTION:
XS GIS Cut Line= 4
      3520911.68     10640578.37      3521317.51     10639964.19
      3521334.88     10639688.59      3520738.05     10639376.07
#Sta/Elev= 30
  4095.6  366.25  4208.5  363.65  4244.6  363.73  4273.2  362.01  4286.8  362.63
  4331.9  360.98    4417  360.24    4453  361.01  4476.4  359.84  4756.3  358.79
  4805.3  357.64  4947.8  356.71    4976  357.62  4986.1  351.42  4995.8   350.4
  4999.1   350.9  5006.1  354.35  5016.1  356.75  5096.5  356.72  5102.5  357.48
  5105.8  356.69  5111.7  357.48  5177.9  357.68  5215.4  356.74  5429.9  358.16
  5437.1  359.52  5508.9  361.19  5554.1  361.13  5657.7  364.59  5781.6  371.12
#Mann= 5 ,-1 , 0
  4095.6     .05       0  4805.3     .03       0    4976     .01       0
  5016.1     .03       0  5096.5     .05       0
Bank Sta=4976,5016.1
XS Rating Curve= 0 ,0
Exp/Cntr=0.3,0.1

Type RM Length L Ch R = 1 ,802     ,0,0,0
BEGIN DESCRIPTION:
UNT057 IN CCTC 1.0
END DESCRIPTION:
XS GIS Cut Line= 4
      3521185.54     10640681.68      3521966.39     10639903.43
      3521951.19     10639753.69      3520879.16     10639345.71
#Sta/Elev= 30
  3824.3  364.83  3962.6  361.87  3983.8  362.97  3997.9  361.65  4188.9  359.44
  4690.9  355.51  4768.7  353.22  4832.3  353.55  4867.7  355.03  4910.1  354.92
  4917.2  353.68  4960.2  354.53  4970.2  354.39  4980.3   353.7  5000.1  345.99
  5003.4  346.49  5010.4   352.5  5020.5  355.44  5237.9  355.09  5250.1  352.88
  5260.8  349.32  5270.6  350.99  5282.2  350.96  5298.1  354.63  5314.3  355.04
  5602.6  357.69    5638  356.56  5924.2  357.99  6057.5  359.89  6224.3  364.98
#Mann= 5 ,-1 , 0
  3824.3     .05       0  4832.3     .03       0  4970.2     .01       0
  5020.5     .03       0  5270.6     .05       0
Bank Sta=4960.2,5020.5
XS Rating Curve= 0 ,0
Exp/Cntr=0.3,0.1

Chan Stop Cuts=-1
Use User Specified Reach Order=0
Composite Channel Slope=5