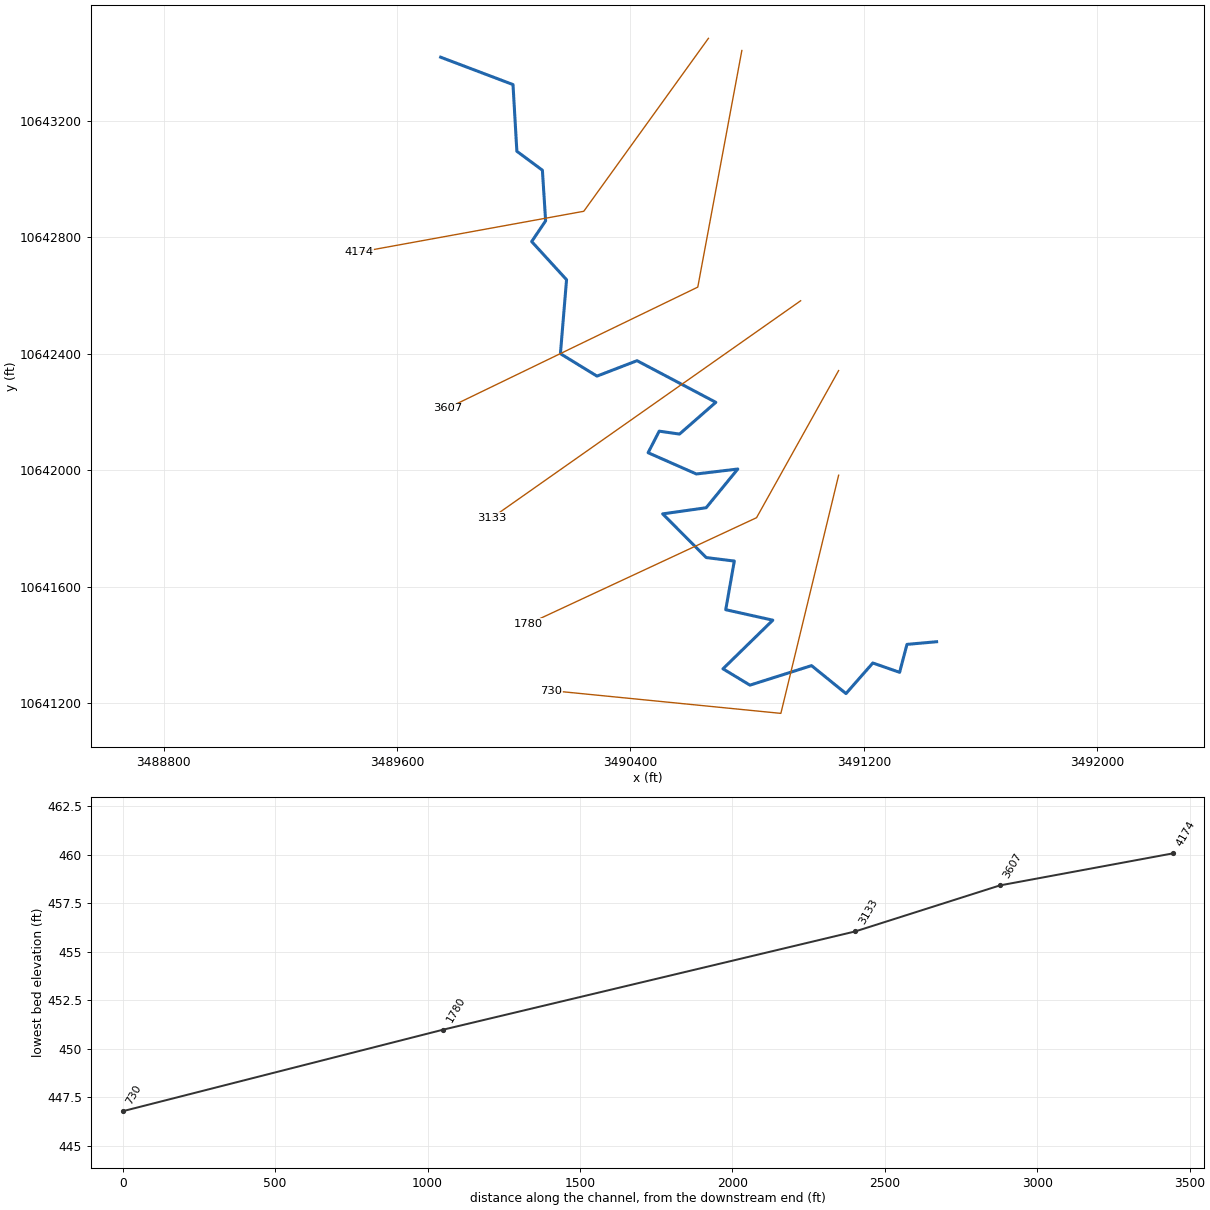
--- UNT060 IN CCTC.prj (project) ---

Proj Title=UNT060 IN CCTC Base Level Engineering
Current Plan=p01
Default Exp/Contr=0.3,0.1
English Units
Geom File=g01
Flow File=f01
Plan File=p01
BEGIN DESCRIPTION:
UNT060 IN CCTC
END DESCRIPTION:

--- UNT060 IN CCTC.p01 (plan) ---

Plan Title=Multiple Run
Short Identifier=Multiple
Geom File=g01
Flow File=f01
Subcritical Flow
K Sum by GR= 0
Std Step Tol= 0.01
Critical Tol= 0.01
Num of Std Step Trials= 20
Max Error Tol= 0.3
Flow Tol Ratio= 0.001
Split Flow NTrial= 30
Split Flow Tol= 0.02
Split Flow Ratio= 0.02
Log Output Level= 0
Friction Slope Method= 1
Unsteady Friction Slope Method= 2
Unsteady Bridges Friction Slope Method= 1
Parabolic Critical Depth
Global Vel Dist=  1 , 1 , 1
Global Log Level= 0
CheckData=True
Encroach Param= -1, 0, 0, 0
BEGIN DESCRIPTION:
Multiple Run
END DESCRIPTION:

--- UNT060 IN CCTC.f01 (steady flow) ---

Flow Title=Multiple
Number of Profiles=7
Profile Names=10-year,25-year,50-year,1pct_min,100-year,1pct_plu,500-year
River Rch & RM= UNT060 IN CCTC,Reach-1,4174
    1240    1707    2093    1872    2532    3425    3698
Boundary for River Rch & Prof#=UNT060 IN CCTC,Reach-1,1
Up Type=0
Dn Type=3
Dn Slope=0.005
Boundary for River Rch & Prof#=UNT060 IN CCTC,Reach-1,2
Up Type=0
Dn Type=3
Dn Slope=0.005
Boundary for River Rch & Prof#=UNT060 IN CCTC,Reach-1,3
Up Type=0
Dn Type=3
Dn Slope=0.005
Boundary for River Rch & Prof#=UNT060 IN CCTC,Reach-1,4
Up Type=0
Dn Type=3
Dn Slope=0.005
Boundary for River Rch & Prof#=UNT060 IN CCTC,Reach-1,5
Up Type=0
Dn Type=3
Dn Slope=0.005
Boundary for River Rch & Prof#=UNT060 IN CCTC,Reach-1,6
Up Type=0
Dn Type=3
Dn Slope=0.005
Boundary for River Rch & Prof#=UNT060 IN CCTC,Reach-1,7
Up Type=0
Dn Type=3
Dn Slope=0.005

--- UNT060 IN CCTC.g01 (geometry) ---

Geom Title=Existing Conditions

River Reach=UNT060 IN CCTC,Reach-1
Reach XY= 30
      3489749.61     10643418.00      3489997.50     10643324.00
      3490010.75     10643095.00      3490098.25     10643030.00
      3490109.25     10642856.00      3490061.50     10642785.00
      3490181.00     10642654.00      3490160.00     10642400.00
      3490285.25     10642323.00      3490422.50     10642376.00
      3490692.50     10642233.00      3490568.00     10642124.00
      3490498.50     10642134.00      3490460.50     10642060.00
      3490625.75     10641987.00      3490767.75     10642004.00
      3490659.25     10641871.00      3490510.25     10641850.00
      3490659.75     10641700.00      3490755.75     10641688.00
      3490726.50     10641521.00      3490887.75     10641485.00
      3490717.00     10641318.00      3490809.50     10641262.00
      3491020.50     10641329.00      3491138.50     10641233.00
      3491230.50     10641338.00      3491322.25     10641306.00
      3491347.50     10641402.00      3491449.00     10641411.00

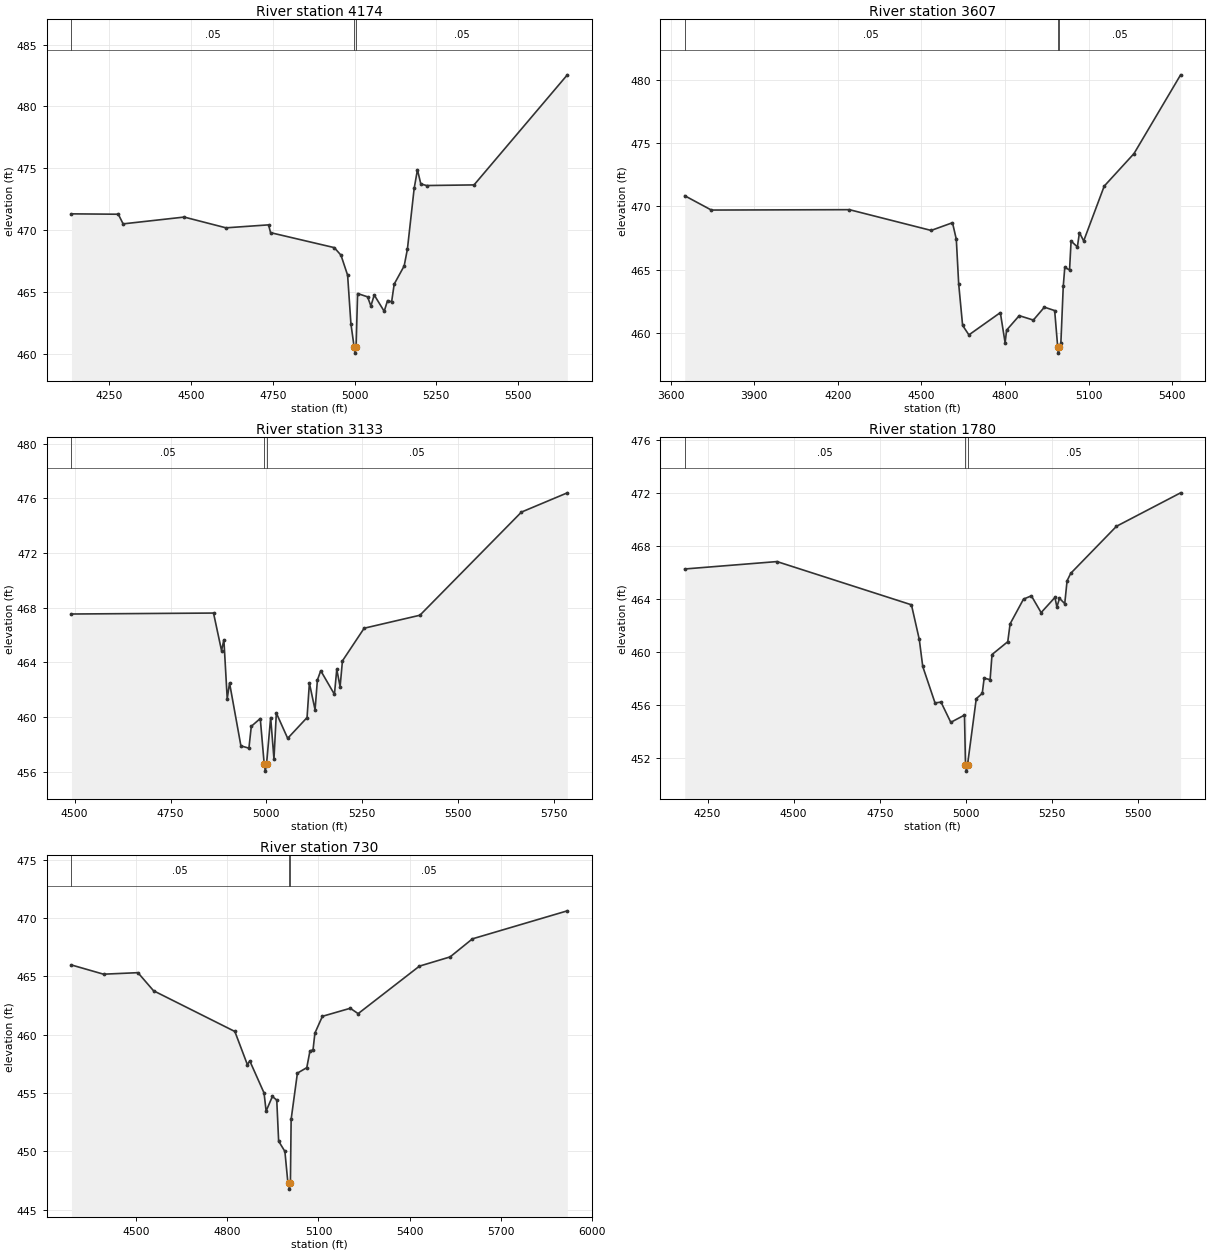
Type RM Length L Ch R = 1,4174,567,567,567
BEGIN DESCRIPTION:
UNT060 IN CCTC 3.0
END DESCRIPTION:
XS GIS Cut Line= 3
      3490667.14     10643482.78      3490240.02     10642889.00
      3489469.19     10642748.37
#Sta/Elev= 30
  4135.2  471.32  4278.3  471.29  4293.0  470.51  4479.6  471.06  4607.3  470.19
  4737.4  470.43  4743.5  469.80  4938.2  468.59  4958.6  467.98  4978.9  466.36
  4989.0  462.43  4998.8  460.56  5001.5  460.06  5004.8  460.56  5009.4  464.88
  5039.9  464.61  5050.0  463.87  5060.2  464.76  5090.7  463.44  5100.9  464.31
  5113.4  464.21  5121.2  465.64  5151.7  467.11  5161.6  468.47  5182.2  473.37
  5192.3  474.89  5202.5  473.74  5220.0  473.61  5365.2  473.66  5650.2  482.56
#Mann=3,-1,0
  4135.2    0.05       0  4998.8   0.035       0  5004.8    0.05       0
Bank Sta=4998.8,5004.8
Exp/Cntr=0.3,0.1

Type RM Length L Ch R = 1,3607,474,474,474
BEGIN DESCRIPTION:
UNT060 IN CCTC 2.0
END DESCRIPTION:
XS GIS Cut Line= 3
      3490781.68     10643441.04      3490630.65     10642628.58
      3489772.92     10642212.71
#Sta/Elev= 30
  3650.4  470.84  3745.9  469.71  4241.3  469.74  4534.7  468.10  4611.3  468.71
  4625.0  467.40  4633.5  463.88  4647.6  460.60  4670.2  459.85  4783.0  461.61
  4800.1  459.23  4805.6  460.23  4850.8  461.37  4901.5  461.02  4941.1  462.04
  4978.0  461.77  4988.8  458.91  4991.5  458.41  4994.8  458.91  5000.3  459.23
  5008.8  463.69  5014.3  465.18  5031.4  464.98  5036.9  467.26  5059.5  466.80
  5066.9  467.93  5082.1  467.27  5155.8  471.60  5262.7  474.17  5430.0  480.39
#Mann=3,-1,0
  3650.4    0.05       0  4988.8   0.035       0  4994.8    0.05       0
Bank Sta=4988.8,4994.8
Exp/Cntr=0.3,0.1

Type RM Length L Ch R = 1,3133,1353,1353,1353
BEGIN DESCRIPTION:
Mapping XS 269a803d
END DESCRIPTION:
XS GIS Cut Line= 2
      3490983.05     10642581.68      3489925.83     10641836.94
#Sta/Elev= 30
  4491.6  467.54  4862.1  467.61  4883.0  464.86  4889.1  465.66  4897.8  461.34
  4903.9  462.49  4933.5  457.89  4954.4  457.72  4960.6  459.32  4984.0  459.89
  4994.3  456.54  4997.1  456.04  5000.3  456.54  5011.1  459.96  5019.7  456.93
  5025.9  460.29  5055.5  458.44  5106.0  459.96  5112.1  462.48  5126.9  460.53
  5133.0  462.71  5141.7  463.39  5177.4  461.66  5183.5  463.49  5192.2  462.22
  5198.3  464.11  5254.9  466.50  5400.3  467.45  5665.1  475.00  5784.8  476.41
#Mann=3,-1,0
  4491.6    0.05       0  4994.3    0.03       0  5000.3    0.05       0
Bank Sta=4994.3,5000.3
Exp/Cntr=0.3,0.1

Type RM Length L Ch R = 1,1780,1050,1050,1050
BEGIN DESCRIPTION:
Mapping XS 5f112fd5
END DESCRIPTION:
XS GIS Cut Line= 3
      3491113.29     10642342.13      3490832.04     10641836.91
      3490050.75     10641472.31
#Sta/Elev= 30
  4183.6  466.26  4451.5  466.82  4842.1  463.55  4864.9  460.93  4874.9  458.89
  4910.6  456.13  4928.0  456.19  4956.4  454.66  4996.2  455.21  4999.1  451.47
  5001.8  450.97  5005.1  451.47  5030.4  456.45  5047.8  456.85  5053.3  458.00
  5070.6  457.89  5076.2  459.79  5121.9  460.76  5128.7  462.11  5167.6  463.98
  5190.5  464.23  5218.8  462.96  5259.0  464.11  5264.6  463.38  5272.1  464.04
  5287.4  463.64  5294.2  465.37  5304.8  465.93  5437.7  469.49  5624.0  472.02
#Mann=3,-1,0
  4183.6    0.05       0  4999.1   0.035       0  5005.1    0.05       0
Bank Sta=4999.1,5005.1
Exp/Cntr=0.3,0.1

Type RM Length L Ch R = 1,730,0,0,0
BEGIN DESCRIPTION:
UNT060 IN CCTC 1.0
END DESCRIPTION:
XS GIS Cut Line= 3
      3491113.29     10641982.74      3490915.37     10641165.04
      3490128.95     10641243.16
#Sta/Elev= 30
  4287.2  465.98  4392.7  465.19  4505.9  465.32  4557.3  463.77  4824.8  460.28
  4866.0  457.44  4873.9  457.76  4920.9  455.01  4927.7  453.46  4948.3  454.71
  4962.7  454.40  4968.9  450.88  4989.5  450.00  4999.4  447.29  5001.6  447.27
  5004.3  446.77  5007.6  447.27  5010.0  452.75  5030.6  456.71  5061.5  457.18
  5071.8  458.59  5082.1  458.72  5088.2  460.14  5112.9  461.58  5204.6  462.27
  5230.5  461.81  5432.1  465.88  5533.0  466.67  5606.6  468.22  5918.8  470.62
#Mann=3,-1,0
  4287.2    0.05       0  5001.6   0.035       0  5007.6    0.05       0
Bank Sta=5001.6,5007.6
Exp/Cntr=0.3,0.1

Chan Stop Cuts=-1