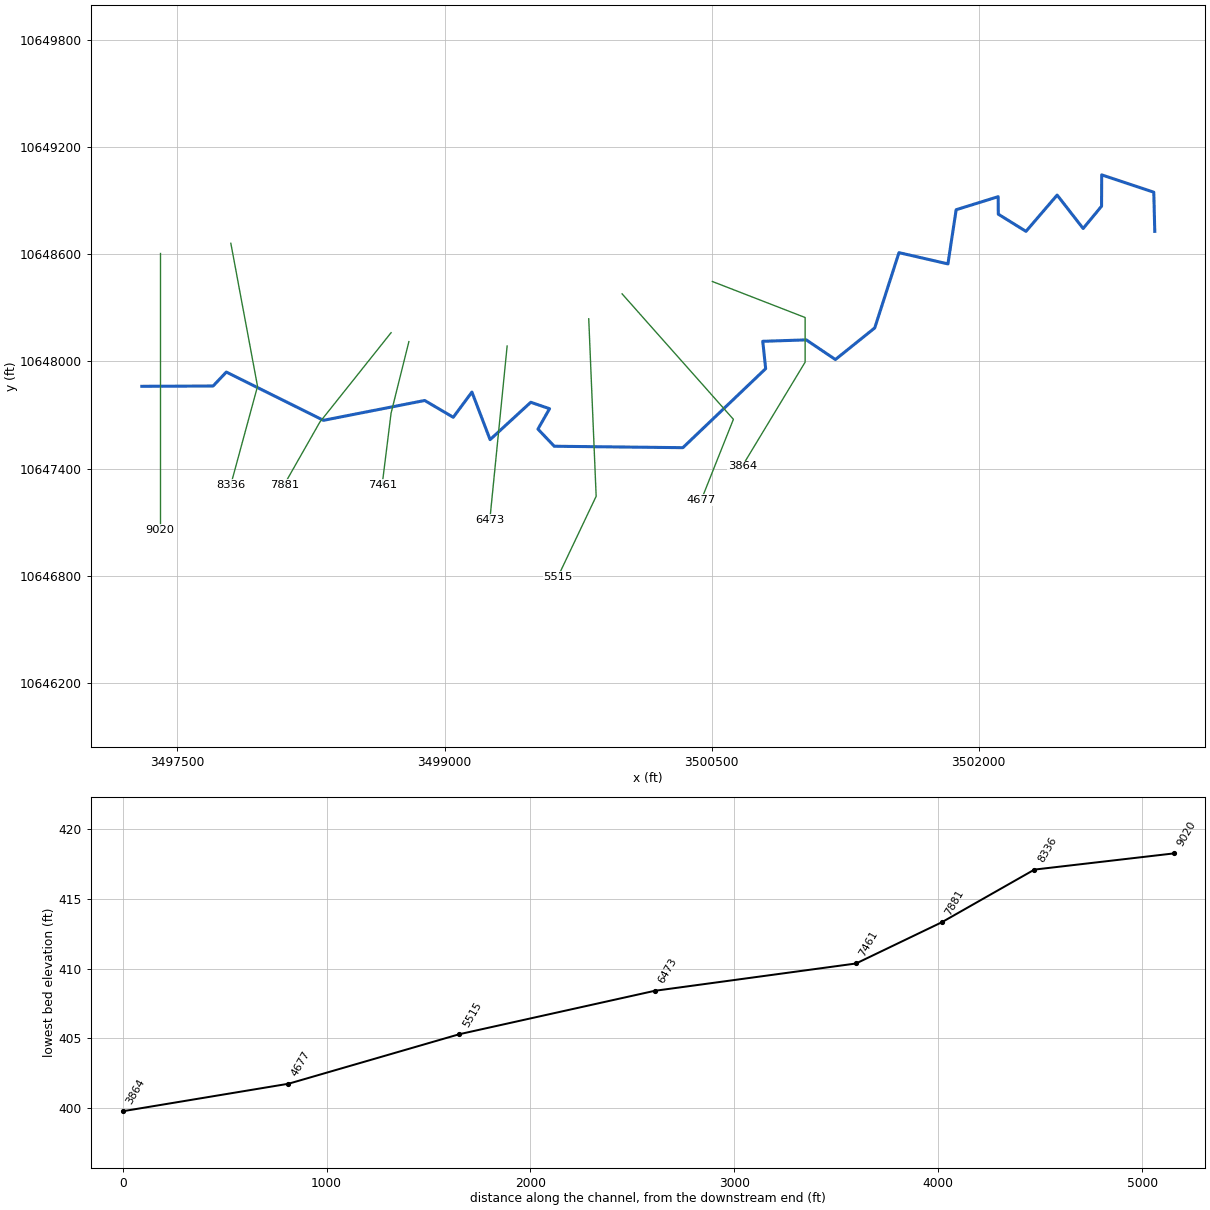
--- UNT062 IN CCTC.prj (project) ---

Proj Title=UNT062 IN CCTC Base Level Engineering
Current Plan=p01
Default Exp/Contr=0.3,0.1
English Units
Geom File=g01
Flow File=f01
Plan File=p01
BEGIN DESCRIPTION:
UNT062 IN CCTC
END DESCRIPTION:

--- UNT062 IN CCTC.p01 (plan) ---

Plan Title=Multiple Run
Short Identifier=Multiple
Geom File=g01
Flow File=f01
Subcritical Flow
K Sum by GR= 0
Std Step Tol= 0.01
Critical Tol= 0.01
Num of Std Step Trials= 20
Max Error Tol= 0.3
Flow Tol Ratio= 0.001
Split Flow NTrial= 30
Split Flow Tol= 0.02
Split Flow Ratio= 0.02
Log Output Level= 0
Friction Slope Method= 1
Unsteady Friction Slope Method= 2
Unsteady Bridges Friction Slope Method= 1
Parabolic Critical Depth
Global Vel Dist=  1 , 1 , 1
Global Log Level= 0
CheckData=True
Encroach Param= -1, 0, 0, 0
BEGIN DESCRIPTION:
Multiple Run
END DESCRIPTION:

--- UNT062 IN CCTC.f01 (steady flow) ---

Flow Title=Multiple
Number of Profiles=7
Profile Names=10-year,25-year,50-year,1pct_min,100-year,1pct_plu,500-year
River Rch & RM= UNT062 IN CCTC,Reach-1,9020
    1756    2472    3075    2790    3773    5103    5668
Boundary for River Rch & Prof#=UNT062 IN CCTC,Reach-1,1
Up Type=0
Dn Type=3
Dn Slope=0.005
Boundary for River Rch & Prof#=UNT062 IN CCTC,Reach-1,2
Up Type=0
Dn Type=3
Dn Slope=0.005
Boundary for River Rch & Prof#=UNT062 IN CCTC,Reach-1,3
Up Type=0
Dn Type=3
Dn Slope=0.005
Boundary for River Rch & Prof#=UNT062 IN CCTC,Reach-1,4
Up Type=0
Dn Type=3
Dn Slope=0.005
Boundary for River Rch & Prof#=UNT062 IN CCTC,Reach-1,5
Up Type=0
Dn Type=3
Dn Slope=0.005
Boundary for River Rch & Prof#=UNT062 IN CCTC,Reach-1,6
Up Type=0
Dn Type=3
Dn Slope=0.005
Boundary for River Rch & Prof#=UNT062 IN CCTC,Reach-1,7
Up Type=0
Dn Type=3
Dn Slope=0.005

--- UNT062 IN CCTC.g01 (geometry) ---

Geom Title=Existing Conditions

River Reach=UNT062 IN CCTC,Reach-1
Reach XY= 30
      3497299.61     10647860.19      3497700.00     10647862.00
      3497774.25     10647940.00      3498319.75     10647670.00
      3498888.50     10647781.00      3499048.75     10647687.00
      3499153.75     10647828.00      3499255.75     10647562.00
      3499484.25     10647771.00      3499589.75     10647735.00
      3499524.50     10647621.00      3499616.25     10647525.00
      3500338.50     10647517.00      3500803.50     10647959.00
      3500787.25     10648112.00      3501031.50     10648120.00
      3501195.25     10648010.00      3501416.25     10648187.00
      3501552.25     10648608.00      3501827.25     10648545.00
      3501873.50     10648848.00      3502109.50     10648921.00
      3502110.25     10648823.00      3502265.75     10648727.00
      3502440.75     10648930.00      3502586.75     10648743.00
      3502690.25     10648868.00      3502690.75     10649043.00
      3502983.50     10648946.00      3502989.00     10648727.00

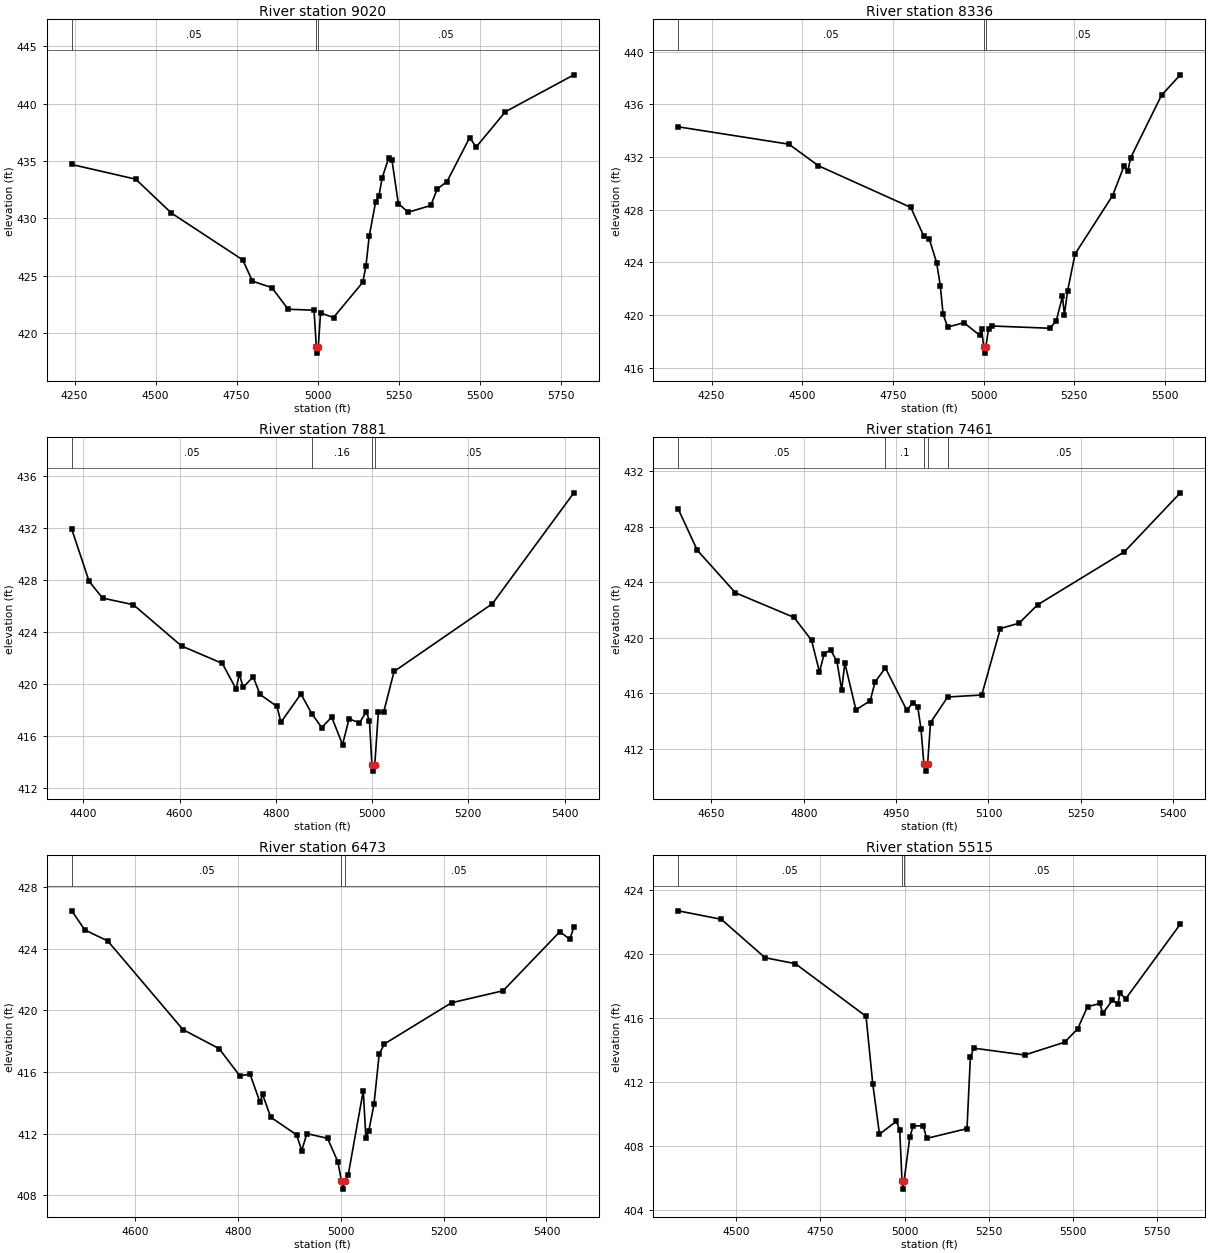
Type RM Length L Ch R = 1,9020,684,684,684
BEGIN DESCRIPTION:
UNT062 IN CCTC 11.0
END DESCRIPTION:
XS GIS Cut Line= 2
      3497400.33     10648607.54      3497400.33     10647058.94
#Sta/Elev= 30
  4241.5  434.69  4438.8  433.41  4548.8  430.46  4768.8  426.38  4798.8  424.53
  4858.8  423.96  4908.8  422.08  4988.8  422.00  4995.8  418.76  4998.6  418.26
  5001.8  418.76  5008.8  421.76  5048.8  421.36  5138.8  424.42  5148.8  425.82
  5158.8  428.43  5178.8  431.44  5188.8  431.93  5198.8  433.52  5218.8  435.24
  5228.8  435.12  5248.8  431.29  5278.8  430.53  5348.8  431.12  5368.8  432.56
  5398.8  433.20  5468.8  437.03  5488.8  436.21  5578.8  439.28  5790.1  442.50
#Mann=3,-1,0
  4241.5    0.05       0  4995.8    0.03       0  5001.8    0.05       0
Bank Sta=4995.8,5001.8
Exp/Cntr=0.3,0.1

Type RM Length L Ch R = 1,8336,455,455,455
BEGIN DESCRIPTION:
UNT062 IN CCTC 10.0
END DESCRIPTION:
XS GIS Cut Line= 3
      3497799.61     10648660.18      3497949.61     10647860.19
      3497799.62     10647310.21
#Sta/Elev= 30
  4158.2  434.29  4463.4  432.97  4544.8  431.33  4799.2  428.17  4835.6  425.96
  4850.0  425.79  4870.4  423.98  4880.6  422.23  4888.2  420.07  4900.9  419.08
  4945.9  419.41  4989.4  418.45  4994.6  418.90  5000.2  417.60  5003.0  417.10
  5006.2  417.60  5013.6  418.94  5024.0  419.16  5182.9  418.99  5200.2  419.55
  5217.4  421.41  5222.6  420.02  5231.3  421.80  5252.0  424.63  5355.6  429.07
  5386.7  431.28  5397.1  430.91  5405.7  431.96  5490.4  436.69  5542.2  438.24
#Mann=3,-1,0
  4158.2    0.05       0  5000.2   0.035       0  5006.2    0.05       0
Bank Sta=5000.2,5006.2
Exp/Cntr=0.3,0.1

Type RM Length L Ch R = 1,7881,420,420,420
BEGIN DESCRIPTION:
UNT062 IN CCTC 9.0
END DESCRIPTION:
XS GIS Cut Line= 3
      3498699.60     10648160.17      3498299.61     10647660.19
      3498099.61     10647310.19
#Sta/Elev= 30
  4375.9  431.91  4411.9  427.91  4439.9  426.62  4503.9  426.11  4604.0  422.94
  4688.8  421.60  4717.6  419.61  4724.0  420.80  4732.1  419.76  4752.9  420.57
  4767.3  419.21  4802.5  418.29  4810.5  417.07  4852.1  419.25  4874.6  417.74
  4895.3  416.67  4916.1  417.47  4938.6  415.36  4952.2  417.34  4973.8  417.03
  4988.2  417.90  4994.6  417.17  4999.6  413.82  5002.3  413.32  5005.6  413.82
  5013.0  417.84  5024.1  417.86  5045.7  420.98  5250.1  426.19  5419.3  434.71
#Mann=4,-1,0
  4375.9    0.05       0  4874.6    0.16       0  4999.6    0.07       0
  5005.6    0.05       0
Bank Sta=4999.6,5005.6
Exp/Cntr=0.3,0.1

Type RM Length L Ch R = 1,7461,988,988,988
BEGIN DESCRIPTION:
UNT062 IN CCTC 8.0
END DESCRIPTION:
XS GIS Cut Line= 3
      3498799.61     10648110.20      3498699.61     10647710.19
      3498649.61     10647310.23
#Sta/Elev= 30
  4596.2  429.28  4627.1  426.31  4689.0  423.24  4784.3  421.46  4812.7  419.81
  4825.6  417.53  4833.3  418.85  4843.6  419.11  4853.9  418.30  4861.6  416.24
  4866.8  418.16  4884.8  414.79  4908.0  415.45  4915.8  416.80  4932.6  417.82
  4967.3  414.77  4977.6  415.32  4985.3  414.98  4990.5  413.39  4995.2  410.87
  4998.0  410.37  5001.2  410.87  5005.9  413.87  5033.8  415.72  5089.1  415.86
  5119.4  420.66  5149.6  421.04  5179.8  422.37  5320.9  426.20  5411.6  430.45
#Mann=5,-1,0
  4596.2    0.05       0  4932.6     0.1       0  4995.2    0.07       0
  5001.2     0.1       0  5033.8    0.05       0
Bank Sta=4995.2,5001.2
Exp/Cntr=0.3,0.1

Type RM Length L Ch R = 1,6473,958,958,958
BEGIN DESCRIPTION:
UNT062 IN CCTC 6.0
END DESCRIPTION:
XS GIS Cut Line= 2
      3499351.49     10648085.48      3499254.26     10647113.23
#Sta/Elev= 30
  4476.2  426.45  4501.6  425.21  4546.1  424.50  4692.6  418.75  4762.9  417.52
  4803.1  415.76  4823.2  415.86  4842.5  414.04  4847.6  414.55  4863.4  413.07
  4913.7  411.93  4923.7  410.91  4933.8  412.01  4974.0  411.70  4994.1  410.18
  5001.1  408.91  5003.9  408.41  5007.1  408.91  5014.2  409.33  5043.5  414.79
  5048.6  411.73  5054.4  412.20  5064.4  413.93  5074.5  417.16  5084.5  417.82
  5215.2  420.49  5315.7  421.27  5426.2  425.10  5445.5  424.60  5453.3  425.40
#Mann=3,-1,0
  4476.2    0.05       0  5001.1   0.035       0  5007.1    0.05       0
Bank Sta=5001.1,5007.1
Exp/Cntr=0.3,0.1

Type RM Length L Ch R = 1,5515,838,838,838
BEGIN DESCRIPTION:
UNT062 IN CCTC 5.0
END DESCRIPTION:
XS GIS Cut Line= 3
      3499809.82     10648238.21      3499851.48     10647245.17
      3499636.55     10646794.51
#Sta/Elev= 30
  4327.0  422.69  4455.1  422.16  4585.2  419.76  4675.1  419.39  4885.5  416.10
  4905.5  411.89  4925.5  408.73  4975.6  409.54  4985.6  409.02  4992.6  405.80
  4995.4  405.30  4998.6  405.80  5015.6  408.54  5025.6  409.25  5055.7  409.26
  5065.7  408.47  5185.8  409.08  5195.8  413.53  5205.8  414.11  5357.1  413.68
  5476.1  414.48  5514.8  415.31  5544.2  416.70  5581.2  416.90  5589.6  416.28
  5617.8  417.09  5635.0  416.89  5640.5  417.55  5657.7  417.19  5820.2  421.86
#Mann=3,-1,0
  4327.0    0.05       0  4992.6    0.03       0  4998.6    0.05       0
Bank Sta=4992.6,4998.6
Exp/Cntr=0.3,0.1

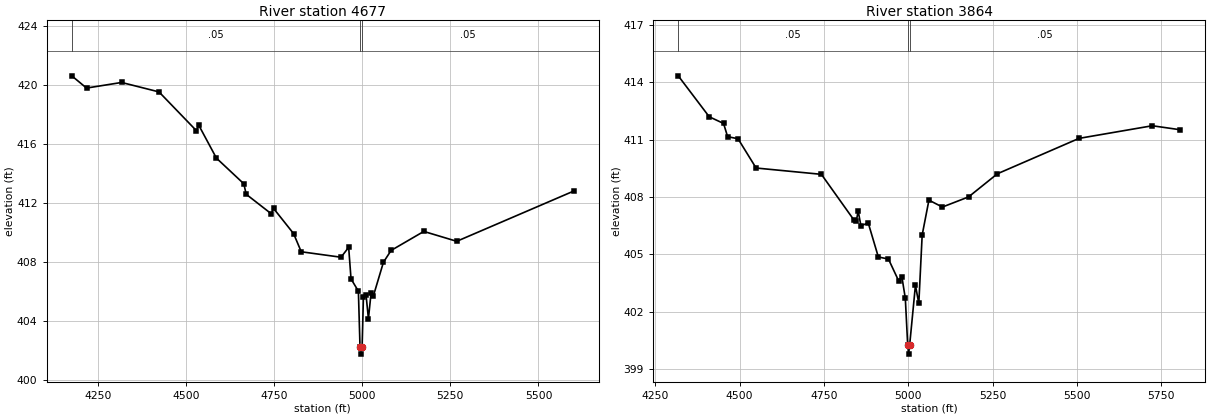
Type RM Length L Ch R = 1,4677,813,813,813
BEGIN DESCRIPTION:
UNT062 IN CCTC 4.0
END DESCRIPTION:
XS GIS Cut Line= 3
      3499997.30     10648377.13      3500622.32     10647675.73
      3500441.92     10647224.74
#Sta/Elev= 30
  4175.3  420.62  4217.2  419.79  4316.7  420.17  4422.9  419.53  4529.1  416.90
  4535.8  417.27  4585.9  415.04  4663.7  413.30  4670.4  412.59  4741.4  411.27
  4748.1  411.63  4805.0  409.92  4826.7  408.69  4939.6  408.32  4961.3  408.99
  4968.0  406.85  4988.9  406.02  4993.5  402.25  4996.2  401.75  4999.5  402.25
  5003.2  405.64  5010.7  405.75  5017.4  404.15  5024.9  405.89  5031.6  405.71
  5060.0  407.98  5081.7  408.78  5174.6  410.07  5268.1  409.40  5600.5  412.81
#Mann=3,-1,0
  4175.3    0.05       0  4993.5   0.035       0  4999.5    0.05       0
Bank Sta=4993.5,4999.5
Exp/Cntr=0.3,0.1

Type RM Length L Ch R = 1,3864,0,0,0
BEGIN DESCRIPTION:
UNT062 IN CCTC 3.0
END DESCRIPTION:
XS GIS Cut Line= 4
      3500504.29     10648446.55      3501025.09     10648245.17
      3501025.09     10647995.17      3500671.92     10647413.48
#Sta/Elev= 30
  4317.9  414.33  4409.8  412.19  4452.3  411.84  4464.3  411.15  4495.2  411.04
  4548.8  409.51  4742.4  409.18  4838.2  406.81  4846.1  406.73  4851.4  407.27
  4859.7  406.49  4881.3  406.64  4911.3  404.86  4941.3  404.75  4971.3  403.62
  4981.3  403.80  4991.3  402.70  4998.3  400.28  5001.0  399.78  5004.3  400.28
  5021.3  403.38  5031.3  402.43  5041.3  406.01  5061.3  407.83  5101.3  407.47
  5178.9  408.00  5264.4  409.21  5506.5  411.06  5723.7  411.72  5806.8  411.51
#Mann=3,-1,0
  4317.9    0.05       0  4998.3   0.035       0  5004.3    0.05       0
Bank Sta=4998.3,5004.3
Exp/Cntr=0.3,0.1

Chan Stop Cuts=-1