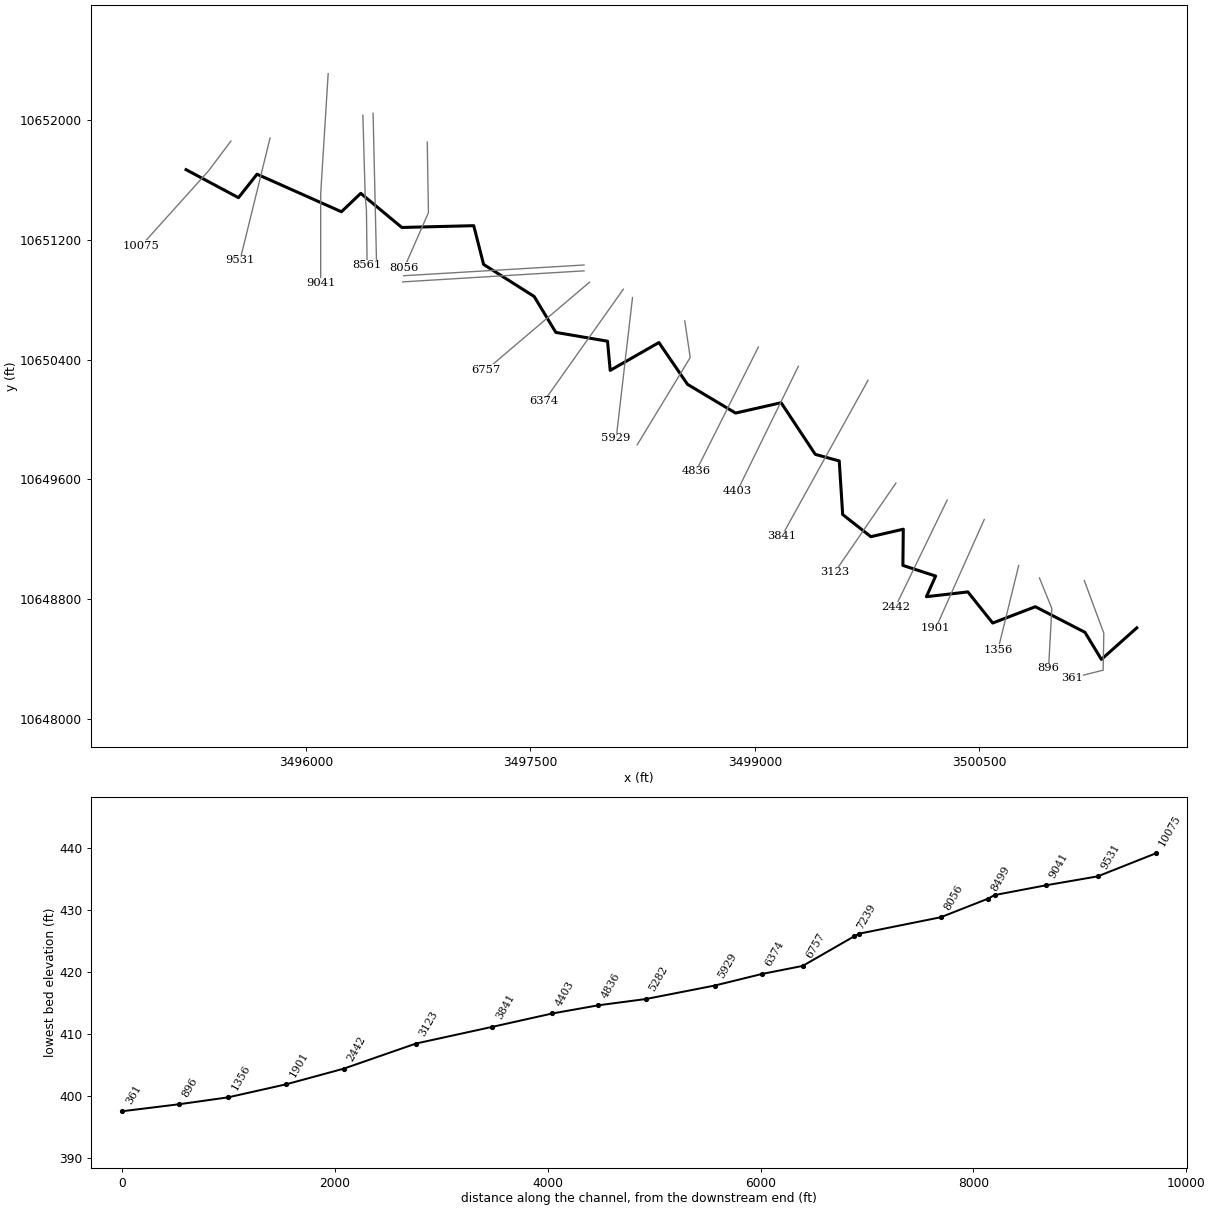
--- UNT063 IN CCTC.prj (project) ---

Proj Title=UNT063 IN CCTC Base Level Engineering
Current Plan=p01
Default Exp/Contr=0.3,0.1
English Units
Geom File=g01
Flow File=f01
Plan File=p01
BEGIN DESCRIPTION:
UNT063 IN CCTC
END DESCRIPTION:

--- UNT063 IN CCTC.p01 (plan) ---

Plan Title=Multiple Run
Short Identifier=Multiple
Geom File=g01
Flow File=f01
Subcritical Flow
K Sum by GR= 0
Std Step Tol= 0.01
Critical Tol= 0.01
Num of Std Step Trials= 20
Max Error Tol= 0.3
Flow Tol Ratio= 0.001
Split Flow NTrial= 30
Split Flow Tol= 0.02
Split Flow Ratio= 0.02
Log Output Level= 0
Friction Slope Method= 1
Unsteady Friction Slope Method= 2
Unsteady Bridges Friction Slope Method= 1
Parabolic Critical Depth
Global Vel Dist=  1 , 1 , 1
Global Log Level= 0
CheckData=True
Encroach Param= -1, 0, 0, 0
BEGIN DESCRIPTION:
Multiple Run
END DESCRIPTION:

--- UNT063 IN CCTC.f01 (steady flow) ---

Flow Title=Multiple
Number of Profiles=7
Profile Names=10-year,25-year,50-year,1pct_min,100-year,1pct_plu,500-year
River Rch & RM= UNT063 IN CCTC,Reach-1,10075
    1420    1984    2456    2220    3003    4061    4476
River Rch & RM= UNT063 IN CCTC,Reach-1,9041
    1676    2348    2913    2635    3563    4819    5320
Boundary for River Rch & Prof#=UNT063 IN CCTC,Reach-1,1
Up Type=0
Dn Type=3
Dn Slope=0.005
Boundary for River Rch & Prof#=UNT063 IN CCTC,Reach-1,2
Up Type=0
Dn Type=3
Dn Slope=0.005
Boundary for River Rch & Prof#=UNT063 IN CCTC,Reach-1,3
Up Type=0
Dn Type=3
Dn Slope=0.005
Boundary for River Rch & Prof#=UNT063 IN CCTC,Reach-1,4
Up Type=0
Dn Type=3
Dn Slope=0.005
Boundary for River Rch & Prof#=UNT063 IN CCTC,Reach-1,5
Up Type=0
Dn Type=3
Dn Slope=0.005
Boundary for River Rch & Prof#=UNT063 IN CCTC,Reach-1,6
Up Type=0
Dn Type=3
Dn Slope=0.005
Boundary for River Rch & Prof#=UNT063 IN CCTC,Reach-1,7
Up Type=0
Dn Type=3
Dn Slope=0.005

--- UNT063 IN CCTC.g01 (geometry) ---

Geom Title=Existing Conditions

River Reach=UNT063 IN CCTC,Reach-1
Reach XY= 30
      3495200.23     10651669.27      3495550.25     10651482.00
      3495674.25     10651639.00      3496238.25     10651388.00
      3496367.25     10651511.00      3496641.75     10651283.00
      3497122.00     10651295.00      3497188.00     10651036.00
      3497525.75     10650822.00      3497670.50     10650582.00
      3498016.00     10650523.00      3498033.75     10650328.00
      3498359.25     10650514.00      3498550.25     10650235.00
      3498871.25     10650043.00      3499175.75     10650112.00
      3499404.00     10649767.00      3499564.00     10649723.00
      3499587.00     10649365.00      3499775.25     10649217.00
      3499992.00     10649267.00      3499989.25     10649025.00
      3500208.00     10648954.00      3500146.50     10648816.00
      3500423.25     10648848.00      3500589.25     10648640.00
      3500874.25     10648749.00      3501205.75     10648578.00
      3501315.50     10648397.00      3501552.25     10648608.00

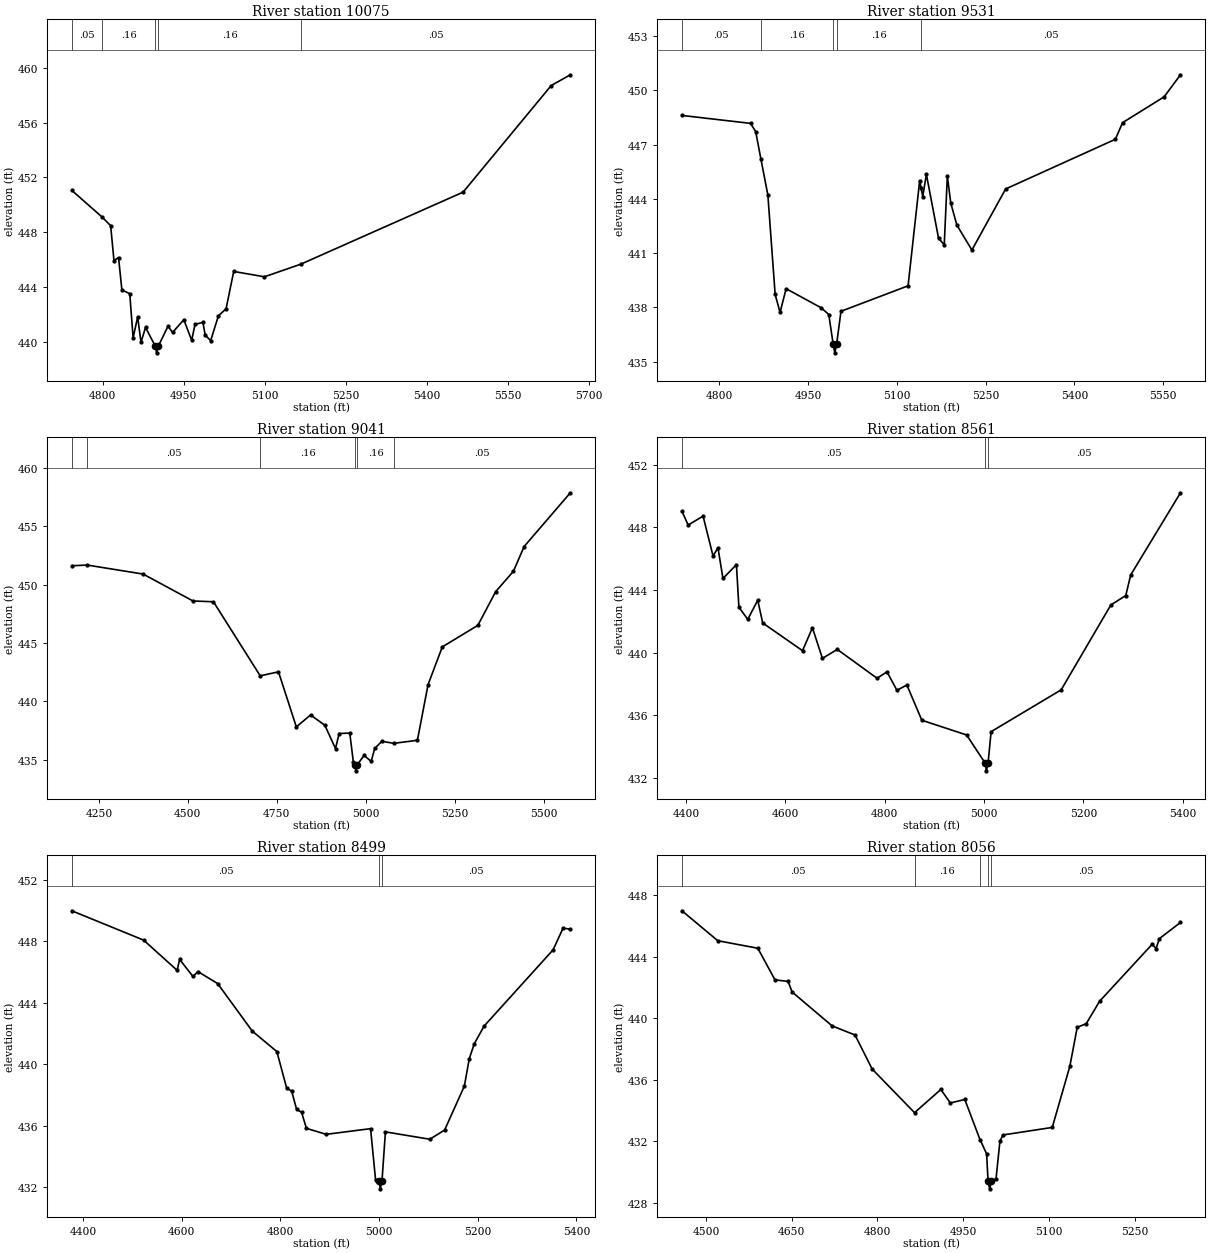
Type RM Length L Ch R = 1,10075,544,544,544
BEGIN DESCRIPTION:
UNT063 IN CCTC 18.0
END DESCRIPTION:
XS GIS Cut Line= 3
      3495499.61     10651860.18      3495349.61     10651660.19
      3494899.59     10651160.17
#Sta/Elev= 30
  4743.1  451.06  4799.4  449.10  4815.0  448.48  4821.2  445.92  4829.6  446.15
  4835.8  443.79  4850.4  443.50  4856.6  440.28  4865.0  441.80  4871.2  439.95
  4879.6  441.04  4897.4  439.68  4900.1  439.18  4903.4  439.68  4921.2  441.13
  4929.6  440.67  4950.4  441.60  4965.0  440.10  4971.2  441.26  4985.8  441.41
  4990.0  440.47  5000.2  440.08  5014.4  441.88  5028.6  442.40  5042.8  445.13
  5099.6  444.74  5166.8  445.66  5467.3  450.93  5630.3  458.72  5665.8  459.51
#Mann=5,-1,0
  4743.1    0.05       0  4799.4    0.16       0  4897.4    0.07       0
  4903.4    0.16       0  5166.8    0.05       0
Bank Sta=4897.4,4903.4
Exp/Cntr=0.3,0.1

Type RM Length L Ch R = 1,9531,490,490,490
BEGIN DESCRIPTION:
UNT063 IN CCTC 17.0
END DESCRIPTION:
XS GIS Cut Line= 2
      3495761.45     10651881.15      3495560.47     10651063.38
#Sta/Elev= 30
  4737.2  448.62  4853.1  448.18  4861.8  447.73  4870.5  446.23  4882.4  444.21
  4894.7  438.71  4903.0  437.72  4913.2  439.03  4972.6  437.97  4985.3  437.60
  4992.6  435.98  4995.4  435.48  4998.6  435.98  5005.9  437.78  5119.2  439.19
  5138.8  445.01  5141.2  444.60  5144.0  444.13  5150.1  445.36  5170.7  441.82
  5180.3  441.46  5185.5  445.27  5191.3  443.77  5201.6  442.55  5227.0  441.17
  5284.0  444.55  5469.3  447.30  5481.5  448.22  5551.7  449.65  5579.3  450.87
#Mann=5,-1,0
  4737.2    0.05       0  4870.5    0.16       0  4992.6    0.07       0
  4998.6    0.16       0  5141.2    0.05       0
Bank Sta=4992.6,4998.6
Exp/Cntr=0.3,0.1

Type RM Length L Ch R = 1,9041,480,480,480
BEGIN DESCRIPTION:
UNT063 IN CCTC 16.0
END DESCRIPTION:
XS GIS Cut Line= 3
      3496149.61     10652310.19      3496099.61     10651510.19
      3496099.61     10650910.16
#Sta/Elev= 30
  4173.8  451.62  4217.0  451.68  4374.2  450.91  4514.5  448.60  4572.1  448.53
  4703.5  442.18  4754.9  442.52  4805.0  437.80  4845.1  438.82  4885.2  437.94
  4915.2  435.94  4925.3  437.23  4955.3  437.27  4965.3  434.79  4969.9  434.53
  4972.6  434.03  4975.9  434.53  4995.4  435.35  5015.4  434.84  5025.4  435.95
  5045.4  436.56  5079.3  436.39  5145.4  436.65  5175.4  441.43  5215.4  444.66
  5315.4  446.51  5365.4  449.40  5415.4  451.15  5445.4  453.27  5575.4  457.88
#Mann=6,-1,0
  4173.8    0.16       0  4217.0    0.05       0  4703.5    0.16       0
  4969.9    0.07       0  4975.9    0.16       0  5079.3    0.05       0
Bank Sta=4969.9,4975.9
Exp/Cntr=0.3,0.1

Type RM Length L Ch R = 1,8561,62,62,62
BEGIN DESCRIPTION:
Mapping XS 9c178efe
END DESCRIPTION:
XS GIS Cut Line= 4
      3496381.44     10652032.75      3496396.64     10651496.69
      3496405.32     10651399.03      3496409.66     10651030.07
#Sta/Elev= 30
  4392.0  449.04  4404.6  448.15  4434.6  448.72  4454.6  446.18  4464.6  446.69
  4474.6  444.74  4501.7  445.62  4506.7  442.90  4524.6  442.13  4544.6  443.35
  4554.6  441.90  4634.7  440.13  4654.7  441.59  4674.7  439.64  4704.7  440.21
  4784.7  438.37  4804.7  438.78  4824.7  437.60  4844.7  437.94  4874.8  435.69
  4964.9  434.75  5002.1  432.96  5004.8  432.46  5008.1  432.96  5014.2  434.96
  5155.2  437.63  5255.2  443.05  5285.2  443.65  5295.2  444.97  5395.3  450.21
#Mann=3,-1,0
  4392.0    0.05       0  5002.1    0.04       0  5008.1    0.05       0
Bank Sta=5002.1,5008.1
Exp/Cntr=0.3,0.1

Type RM Length L Ch R = 1,8499,443,443,443
BEGIN DESCRIPTION:
UNT063 IN CCTC 15.0
END DESCRIPTION:
XS GIS Cut Line= 2
      3496449.59     10652045.77      3496473.02     10651035.34
#Sta/Elev= 30
  4377.0  449.99  4522.6  448.08  4590.6  446.11  4595.6  446.82  4622.7  445.71
  4632.7  446.03  4672.7  445.25  4742.7  442.16  4792.7  440.82  4812.7  438.43
  4822.7  438.25  4832.7  437.06  4842.7  436.87  4852.7  435.82  4892.7  435.43
  4982.7  435.80  4992.8  432.47  4999.8  432.38  5002.5  431.88  5005.8  432.38
  5012.8  435.59  5102.8  435.11  5132.8  435.71  5172.8  438.57  5182.8  440.36
  5192.8  441.32  5212.8  442.48  5352.8  447.45  5372.9  448.86  5387.7  448.79
#Mann=3,-1,0
  4377.0    0.05       0  4999.8    0.04       0  5005.8    0.05       0
Bank Sta=4999.8,5005.8
Exp/Cntr=0.3,0.1

Type RM Length L Ch R = 1,8056,767,767,767
BEGIN DESCRIPTION:
UNT063 IN CCTC 14.0
END DESCRIPTION:
XS GIS Cut Line= 3
      3496811.57     10651852.99      3496819.38     10651381.67
      3496658.08     10651014.85
#Sta/Elev= 30
  4458.0  447.00  4520.8  445.05  4590.8  444.56  4620.8  442.50  4643.7  442.40
  4650.8  441.71  4720.8  439.50  4760.8  438.91  4790.8  436.69  4864.9  433.85
  4910.9  435.36  4927.6  434.48  4952.8  434.71  4979.4  432.10  4991.0  431.17
  4993.5  429.39  4996.3  428.89  4999.5  429.39  5007.5  429.56  5014.3  432.00
  5019.8  432.40  5105.8  432.89  5136.5  436.86  5149.5  439.41  5165.3  439.65
  5188.7  441.11  5280.6  444.82  5287.5  444.54  5293.0  445.18  5330.1  446.24
#Mann=5,-1,0
  4458.0    0.05       0  4864.9    0.16       0  4979.4    0.05       0
  4993.5    0.03       0  4999.5    0.05       0
Bank Sta=4993.5,4999.5
Exp/Cntr=0.3,0.1

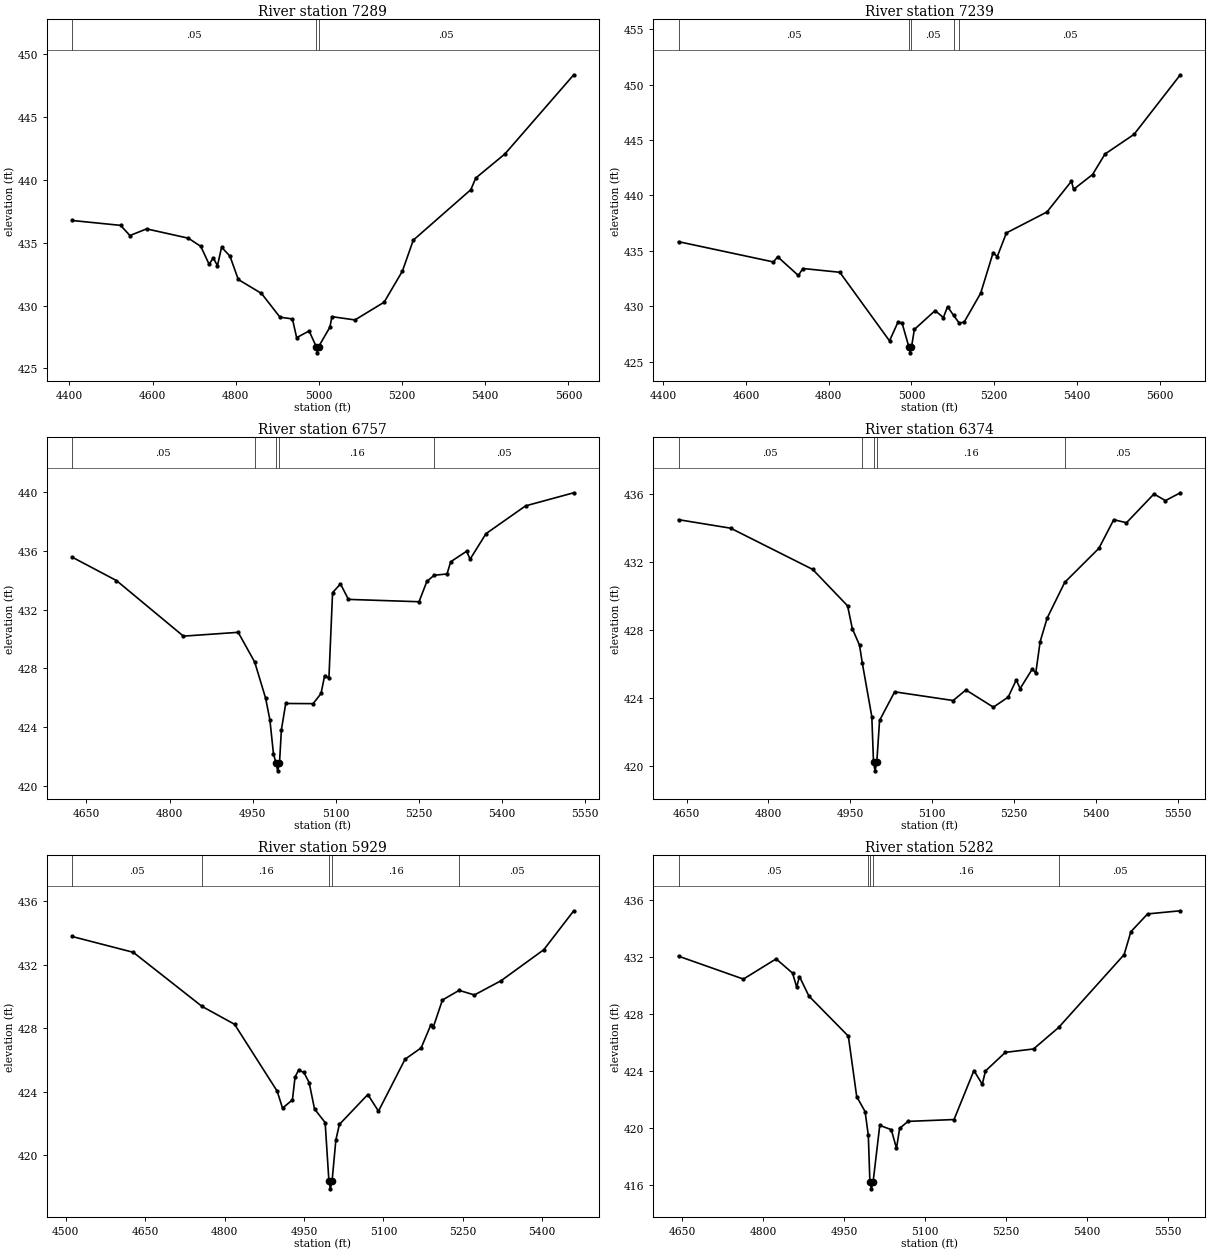
Type RM Length L Ch R = 1,7289,50,50,50
BEGIN DESCRIPTION:
UNT063 IN CCTC 13.0
END DESCRIPTION:
XS GIS Cut Line= 2
      3497858.81     10651032.28      3496654.53     10650960.68
#Sta/Elev= 30
  4406.3  436.78  4523.2  436.39  4545.7  435.58  4585.8  436.11  4686.0  435.37
  4716.0  434.72  4736.1  433.29  4746.1  433.80  4756.1  433.18  4766.1  434.65
  4786.2  433.94  4806.2  432.08  4862.0  430.97  4906.4  429.08  4936.4  428.94
  4946.5  427.45  4976.5  427.98  4993.5  426.74  4996.3  426.24  4999.5  426.74
  5026.4  428.28  5031.4  429.12  5086.7  428.86  5156.8  430.27  5200.8  432.75
  5226.9  435.21  5365.2  439.23  5377.2  440.16  5447.3  442.08  5612.7  448.38
#Mann=3,-1,0
  4406.3    0.05       0  4993.5   0.035       0  4999.5    0.05       0
Bank Sta=4993.5,4999.5
Exp/Cntr=0.3,0.1

Type RM Length L Ch R = 1,7239,482,482,482
BEGIN DESCRIPTION:
UNT063 IN CCTC 12.0
END DESCRIPTION:
XS GIS Cut Line= 2
      3497858.80     10650993.22      3496647.85     10650919.43
#Sta/Elev= 30
  4436.8  435.82  4666.4  433.99  4676.4  434.46  4726.5  432.77  4737.4  433.40
  4826.7  433.06  4946.9  426.87  4967.0  428.53  4977.0  428.51  4994.0  426.29
  4996.8  425.79  5000.0  426.29  5007.0  427.90  5057.1  429.60  5077.2  428.97
  5087.2  429.96  5102.0  429.16  5115.4  428.48  5127.3  428.56  5167.3  431.17
  5197.4  434.83  5207.4  434.47  5229.5  436.61  5327.6  438.50  5386.8  441.28
  5391.9  440.54  5437.8  441.88  5467.9  443.73  5538.0  445.50  5650.0  450.88
#Mann=5,-1,0
  4436.8    0.05       0  4994.0   0.035       0  5000.0    0.05       0
  5102.0    0.16       0  5115.4    0.05       0
Bank Sta=4994,5000
Exp/Cntr=0.3,0.1

Type RM Length L Ch R = 1,6757,383,383,383
BEGIN DESCRIPTION:
UNT063 IN CCTC 11.0
END DESCRIPTION:
XS GIS Cut Line= 2
      3497895.68     10650917.26      3497205.58     10650331.33
#Sta/Elev= 30
  4623.9  435.58  4704.2  433.98  4825.0  430.20  4923.8  430.46  4953.6  428.44
  4973.3  425.98  4981.0  424.51  4987.5  422.19  4992.3  421.54  4995.0  421.04
  4998.3  421.54  5001.8  423.84  5009.6  425.62  5059.0  425.61  5073.3  426.30
  5079.8  427.52  5087.5  427.34  5094.1  433.16  5108.4  433.75  5122.7  432.70
  5250.1  432.54  5264.3  433.93  5277.4  434.34  5300.6  434.43  5307.2  435.26
  5335.8  435.97  5342.3  435.44  5370.9  437.17  5442.3  439.06  5529.2  439.95
#Mann=5,-1,0
  4623.9    0.05       0  4953.6    0.16       0  4992.3    0.07       0
  4998.3    0.16       0  5277.4    0.05       0
Bank Sta=4992.3,4998.3
Exp/Cntr=0.3,0.1

Type RM Length L Ch R = 1,6374,445,445,445
BEGIN DESCRIPTION:
UNT063 IN CCTC 10.0
END DESCRIPTION:
XS GIS Cut Line= 2
      3498121.60     10650870.67      3497590.40     10650120.74
#Sta/Elev= 30
  4635.3  434.49  4730.8  433.99  4881.0  431.57  4944.9  429.43  4953.6  428.09
  4966.8  427.12  4971.7  426.10  4989.3  422.92  4992.4  420.24  4995.2  419.74
  4998.4  420.24  5003.5  422.70  5031.1  424.38  5138.3  423.87  5161.6  424.49
  5211.9  423.48  5239.1  424.07  5253.8  425.08  5260.9  424.57  5283.4  425.73
  5289.5  425.47  5297.6  427.33  5310.4  428.71  5342.6  430.81  5405.2  432.81
  5432.4  434.49  5455.7  434.31  5506.0  436.00  5527.0  435.61  5554.3  436.07
#Mann=5,-1,0
  4635.3    0.05       0  4971.7    0.16       0  4992.4    0.07       0
  4998.4    0.16       0  5342.6    0.05       0
Bank Sta=4992.4,4998.4
Exp/Cntr=0.3,0.1

Type RM Length L Ch R = 1,5929,647,647,647
BEGIN DESCRIPTION:
UNT063 IN CCTC 9.0
END DESCRIPTION:
XS GIS Cut Line= 2
      3498183.00     10650815.24      3498073.78     10649873.86
#Sta/Elev= 30
  4511.8  433.79  4627.6  432.79  4757.4  429.38  4818.9  428.25  4899.4  424.03
  4909.5  422.96  4928.2  423.48  4933.2  424.93  4939.7  425.35  4949.8  425.22
  4959.8  424.57  4969.9  422.91  4990.0  422.05  4997.1  418.37  4999.9  417.87
  5003.1  418.37  5010.2  420.94  5016.8  421.93  5070.6  423.82  5090.7  422.77
  5141.0  426.05  5171.3  426.76  5189.2  428.18  5194.2  428.07  5211.5  429.78
  5243.0  430.39  5271.9  430.10  5322.3  431.00  5402.8  432.95  5459.5  435.41
#Mann=5,-1,0
  4511.8    0.05       0  4757.4    0.16       0  4997.1    0.07       0
  5003.1    0.16       0  5243.0    0.05       0
Bank Sta=4997.1,5003.1
Exp/Cntr=0.3,0.1

Type RM Length L Ch R = 1,5282,446,446,446
BEGIN DESCRIPTION:
UNT063 IN CCTC 8.0
END DESCRIPTION:
XS GIS Cut Line= 3
      3498531.96     10650659.05      3498568.42     10650414.22
      3498214.44     10649831.19
#Sta/Elev= 30
  4642.9  432.05  4763.1  430.44  4823.7  431.86  4854.1  430.86  4861.8  429.88
  4866.9  430.62  4884.4  429.25  4957.5  426.43  4973.0  422.18  4988.5  421.13
  4994.5  419.46  4997.4  416.20  5000.2  415.70  5003.4  416.20  5015.7  420.16
  5037.0  419.86  5046.7  418.55  5052.5  419.95  5068.0  420.44  5153.3  420.57
  5190.1  424.01  5205.6  423.05  5211.5  423.98  5248.3  425.29  5300.6  425.53
  5347.1  427.04  5468.4  432.16  5480.9  433.77  5511.9  435.02  5572.5  435.24
#Mann=5,-1,0
  4642.9    0.05       0  4994.5    0.16       0  4997.4    0.07       0
  5003.4    0.16       0  5347.1    0.05       0
Bank Sta=4997.4,5003.4
Exp/Cntr=0.3,0.1

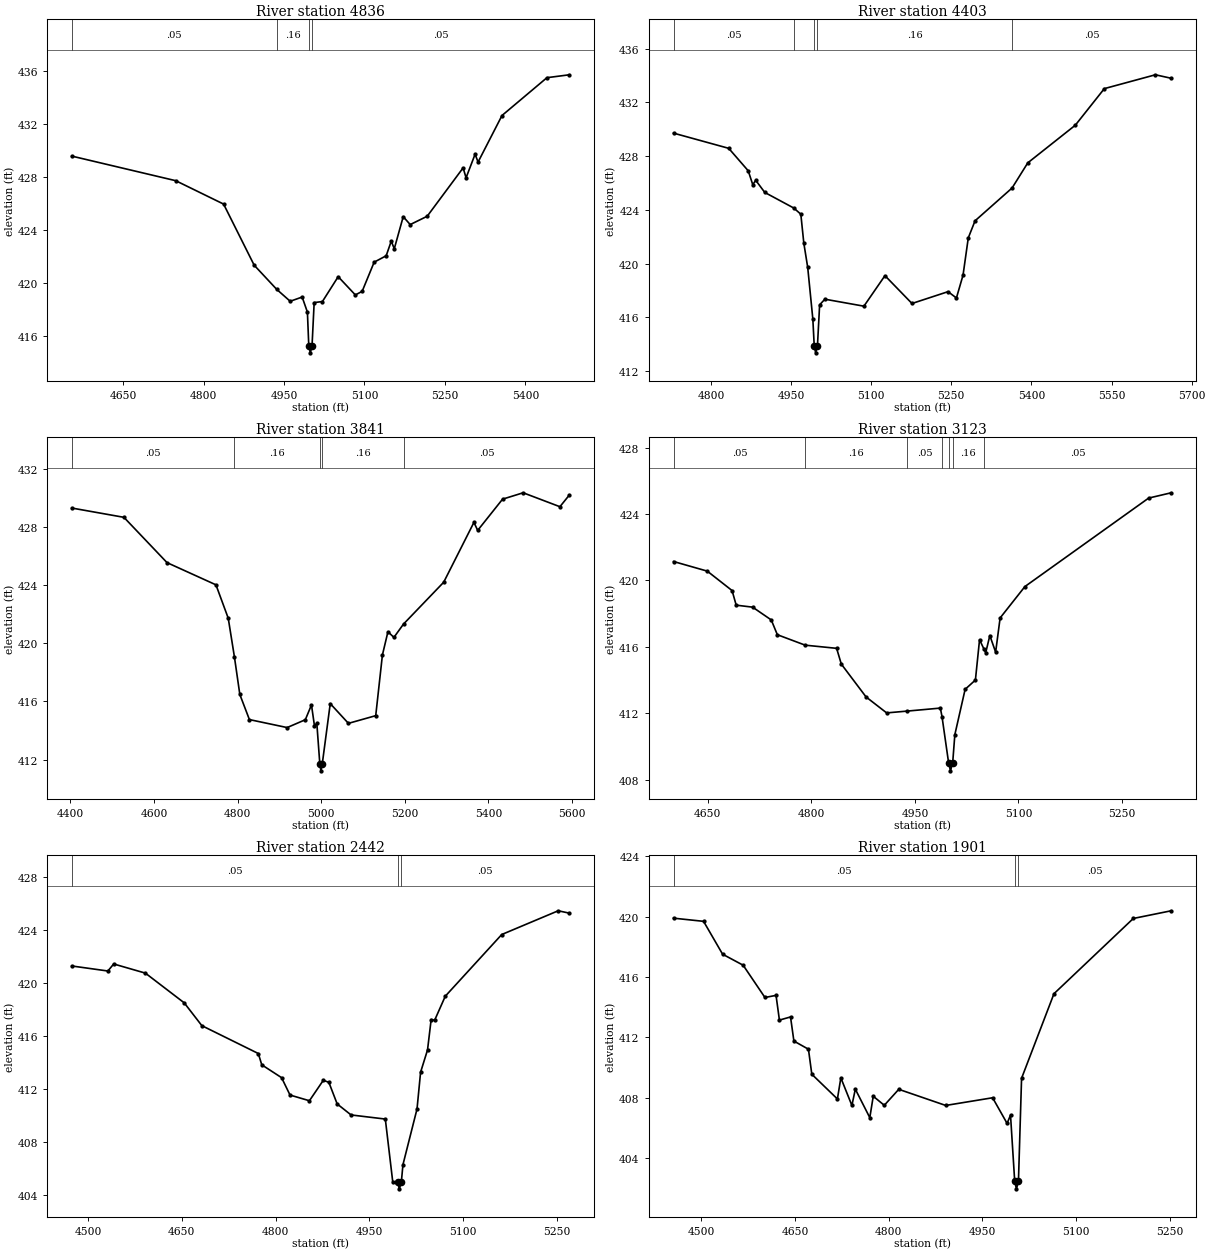
Type RM Length L Ch R = 1,4836,433,433,433
BEGIN DESCRIPTION:
UNT063 IN CCTC 7.0
END DESCRIPTION:
XS GIS Cut Line= 2
      3499023.71     10650484.24      3498607.26     10649654.82
#Sta/Elev= 30
  4554.1  429.57  4748.0  427.71  4837.3  425.94  4894.3  421.32  4936.4  419.49
  4961.5  418.59  4983.8  418.91  4993.6  417.77  4996.2  415.19  4999.0  414.69
  5002.2  415.19  5006.2  418.49  5021.6  418.57  5051.0  420.45  5083.0  419.07
  5095.7  419.34  5118.1  421.55  5140.5  422.03  5150.0  423.14  5155.6  422.56
  5172.3  424.99  5185.3  424.39  5217.0  425.02  5284.0  428.68  5289.5  427.93
  5306.3  429.71  5311.9  429.12  5356.5  432.64  5440.3  435.50  5482.2  435.72
#Mann=4,-1,0
  4554.1    0.05       0  4936.4    0.16       0  4996.2    0.03       0
  5002.2    0.05       0
Bank Sta=4996.2,5002.2
Exp/Cntr=0.3,0.1

Type RM Length L Ch R = 1,4403,562,562,562
BEGIN DESCRIPTION:
UNT063 IN CCTC 6.0
END DESCRIPTION:
XS GIS Cut Line= 2
      3499291.08     10650355.79      3498881.37     10649519.01
#Sta/Elev= 30
  4730.0  429.71  4833.3  428.58  4869.8  426.91  4878.3  425.88  4883.9  426.20
  4900.8  425.30  4955.1  424.14  4968.3  423.68  4973.9  421.53  4981.2  419.72
  4990.8  415.88  4993.4  413.87  4996.1  413.37  4999.4  413.87  5003.5  416.94
  5013.3  417.36  5086.4  416.84  5125.8  419.11  5176.4  417.04  5243.9  417.92
  5259.6  417.45  5272.0  419.15  5281.8  421.92  5294.5  423.19  5363.8  425.63
  5393.2  427.50  5482.2  430.30  5536.5  433.02  5632.1  434.05  5661.7  433.79
#Mann=5,-1,0
  4730.0    0.05       0  4955.1    0.16       0  4993.4    0.07       0
  4999.4    0.16       0  5363.8    0.05       0
Bank Sta=4993.4,4999.4
Exp/Cntr=0.3,0.1

Type RM Length L Ch R = 1,3841,718,718,718
BEGIN DESCRIPTION:
UNT063 IN CCTC 5.0
END DESCRIPTION:
XS GIS Cut Line= 2
      3499756.34     10650262.01      3499179.95     10649220.35
#Sta/Elev= 30
  4403.4  429.32  4528.2  428.68  4631.3  425.56  4748.4  424.03  4777.8  421.73
  4792.6  419.06  4805.5  416.48  4828.4  414.75  4918.7  414.20  4962.2  414.74
  4976.9  415.76  4984.0  414.33  4989.7  414.49  4996.8  411.72  4999.5  411.22
  5002.8  411.72  5021.8  415.85  5065.3  414.49  5130.6  415.02  5146.6  419.20
  5159.8  420.80  5174.1  420.41  5197.1  421.33  5293.2  424.21  5365.5  428.33
  5374.5  427.78  5434.0  429.93  5483.3  430.37  5571.2  429.41  5593.9  430.22
#Mann=5,-1,0
  4403.4    0.05       0  4792.6    0.16       0  4996.8    0.07       0
  5002.8    0.16       0  5197.1    0.05       0
Bank Sta=4996.8,5002.8
Exp/Cntr=0.3,0.1

Type RM Length L Ch R = 1,3123,681,681,681
BEGIN DESCRIPTION:
Mapping XS d29a1ba2
END DESCRIPTION:
XS GIS Cut Line= 2
      3499942.62     10649575.02      3499534.65     10648980.42
#Sta/Elev= 30
  4600.3  421.14  4649.2  420.56  4685.1  419.39  4691.1  418.51  4714.9  418.39
  4741.9  417.62  4750.7  416.73  4791.1  416.10  4836.6  415.91  4843.4  414.96
  4879.3  412.98  4909.1  412.02  4939.1  412.13  4986.9  412.31  4989.3  411.80
  4998.8  409.03  5001.6  408.53  5004.8  409.03  5007.9  410.71  5022.8  413.44
  5037.7  414.00  5043.7  416.43  5049.9  415.88  5052.6  415.64  5058.6  416.68
  5067.0  415.68  5073.5  417.74  5109.4  419.63  5288.7  424.96  5321.4  425.28
#Mann=7,-1,0
  4600.3    0.05       0  4791.1    0.16       0  4939.1    0.05       0
  4989.3    0.16       0  4998.8    0.07       0  5004.8    0.16       0
  5049.9    0.05       0
Bank Sta=4998.8,5004.8
Exp/Cntr=0.3,0.1

Type RM Length L Ch R = 1,2442,541,541,541
BEGIN DESCRIPTION:
Mapping XS 213e71f4
END DESCRIPTION:
XS GIS Cut Line= 2
      3500285.50     10649462.17      3499938.27     10648746.00
#Sta/Elev= 30
  4474.0  421.27  4531.8  420.89  4541.1  421.42  4591.8  420.73  4653.9  418.49
  4682.1  416.77  4772.4  414.67  4777.9  413.82  4809.6  412.85  4823.1  411.54
  4854.1  411.11  4876.3  412.65  4885.2  412.50  4898.5  410.87  4920.7  410.04
  4975.5  409.73  4987.4  404.99  4995.1  404.97  4997.9  404.47  5001.1  404.97
  5003.7  406.29  5026.2  410.49  5031.9  413.26  5043.0  414.94  5048.8  417.23
  5054.4  417.18  5071.4  418.99  5161.7  423.64  5252.0  425.43  5269.9  425.25
#Mann=3,-1,0
  4474.0    0.05       0  4995.1   0.035       0  5001.1    0.05       0
Bank Sta=4995.1,5001.1
Exp/Cntr=0.3,0.1

Type RM Length L Ch R = 1,1901,545,545,545
BEGIN DESCRIPTION:
UNT063 IN CCTC 4.0
END DESCRIPTION:
XS GIS Cut Line= 2
      3500532.91     10649331.98      3500207.93     10648604.03
#Sta/Elev= 30
  4455.3  419.90  4503.4  419.69  4533.9  417.51  4566.8  416.78  4601.7  414.64
  4619.5  414.78  4624.9  413.14  4642.7  413.35  4648.1  411.75  4671.4  411.21
  4676.8  409.55  4717.8  407.91  4723.3  409.31  4741.0  407.48  4746.5  408.56
  4769.7  406.67  4775.2  408.09  4792.9  407.49  4816.1  408.55  4891.3  407.48
  4966.4  407.99  4989.6  406.29  4995.1  406.84  5001.8  402.45  5004.6  401.95
  5007.8  402.45  5012.8  409.28  5064.7  414.89  5191.8  419.88  5252.5  420.39
#Mann=3,-1,0
  4455.3    0.05       0  5001.8   0.035       0  5007.8    0.05       0
Bank Sta=5001.8,5007.8
Exp/Cntr=0.3,0.1

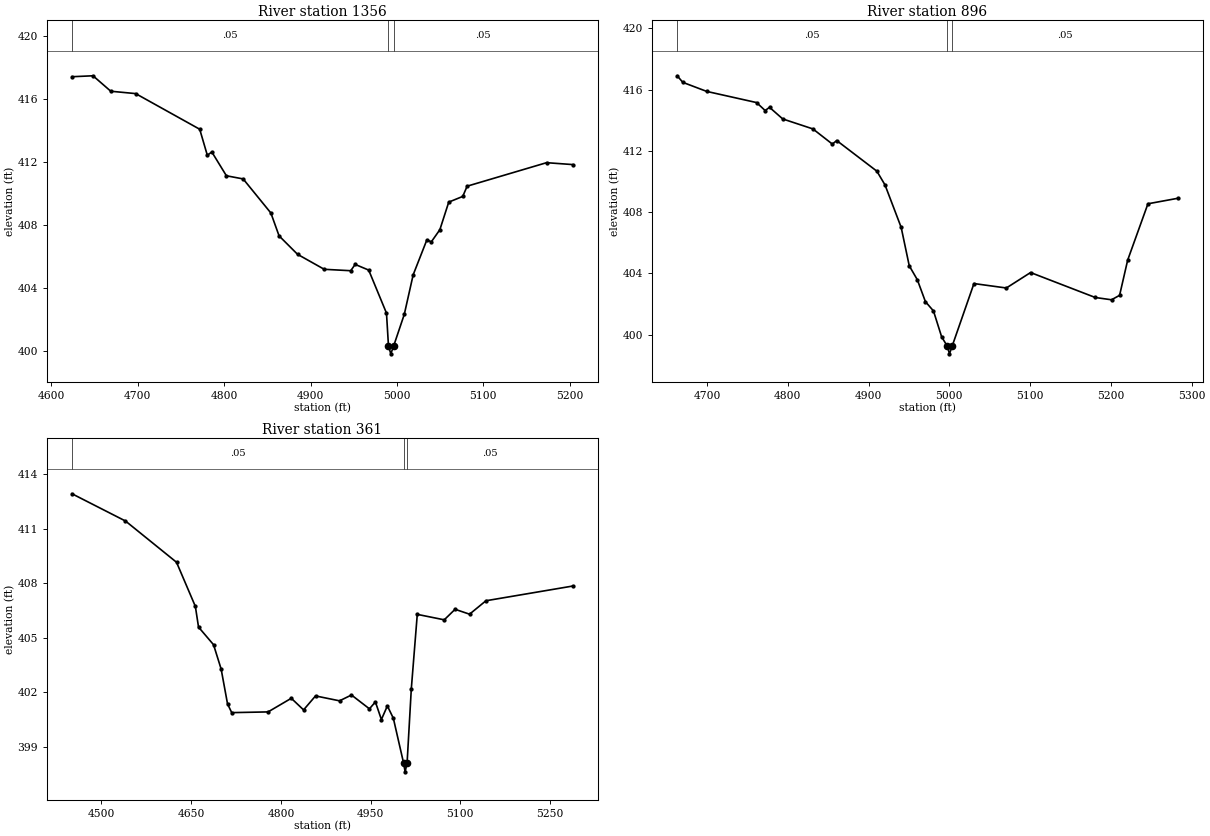
Type RM Length L Ch R = 1,1356,460,460,460
BEGIN DESCRIPTION:
UNT063 IN CCTC 3.0
END DESCRIPTION:
XS GIS Cut Line= 2
      3500762.94     10649023.83      3500624.34     10648460.74
#Sta/Elev= 30
  4623.8  417.42  4648.1  417.48  4668.7  416.50  4697.5  416.35  4771.7  414.09
  4780.5  412.44  4785.7  412.65  4802.6  411.14  4822.0  410.94  4854.1  408.78
  4863.6  407.33  4885.0  406.16  4915.9  405.21  4946.6  405.12  4951.7  405.52
  4967.4  405.16  4988.0  402.43  4990.3  400.35  4993.0  399.85  4996.3  400.35
  5008.6  402.35  5018.9  404.86  5034.8  407.08  5039.9  406.95  5049.8  407.72
  5060.1  409.47  5076.3  409.83  5081.4  410.48  5173.4  411.97  5203.7  411.85
#Mann=3,-1,0
  4623.8    0.05       0  4990.3   0.035       0  4996.3    0.05       0
Bank Sta=4990.3,4996.3
Exp/Cntr=0.3,0.1

Type RM Length L Ch R = 1,896,535,535,535
BEGIN DESCRIPTION:
UNT063 IN CCTC 2.0
END DESCRIPTION:
XS GIS Cut Line= 3
      3500901.83     10648941.35      3500984.29     10648737.36
      3500962.59     10648338.07
#Sta/Elev= 30
  4663.1  416.90  4670.1  416.47  4699.6  415.88  4761.4  415.15  4772.0  414.63
  4777.4  414.84  4793.8  414.08  4831.1  413.43  4855.2  412.44  4860.6  412.67
  4910.3  410.67  4920.4  409.77  4940.4  407.00  4950.4  404.49  4960.4  403.58
  4970.4  402.15  4980.4  401.54  4990.5  399.85  4997.5  399.24  5000.2  398.74
  5003.5  399.24  5030.5  403.33  5070.6  403.04  5100.6  404.05  5180.7  402.42
  5200.8  402.27  5210.8  402.56  5220.8  404.86  5245.9  408.54  5283.0  408.90
#Mann=3,-1,0
  4663.1    0.05       0  4997.5   0.035       0  5003.5    0.05       0
Bank Sta=4997.5,5003.5
Exp/Cntr=0.3,0.1

Type RM Length L Ch R = 1,361,0,0,0
BEGIN DESCRIPTION:
UNT063 IN CCTC 1.0
END DESCRIPTION:
XS GIS Cut Line= 4
      3501201.31     10648923.99      3501331.52     10648572.43
      3501327.18     10648325.03      3501118.83     10648272.94
#Sta/Elev= 30
  4450.8  412.92  4540.2  411.42  4625.5  409.15  4657.0  406.72  4662.3  405.58
  4687.4  404.61  4700.1  403.27  4710.8  401.35  4717.8  400.87  4778.6  400.91
  4817.4  401.66  4837.9  401.02  4857.9  401.79  4898.0  401.52  4918.0  401.84
  4948.0  401.08  4958.0  401.46  4968.0  400.49  4978.0  401.24  4988.0  400.56
  5005.0  398.11  5007.7  397.61  5011.0  398.11  5018.0  402.17  5028.0  406.28
  5073.1  405.98  5091.2  406.56  5115.4  406.29  5142.8  407.03  5287.9  407.84
#Mann=3,-1,0
  4450.8    0.05       0  5005.0   0.035       0  5011.0    0.05       0
Bank Sta=5005,5011
Exp/Cntr=0.3,0.1

Chan Stop Cuts=-1