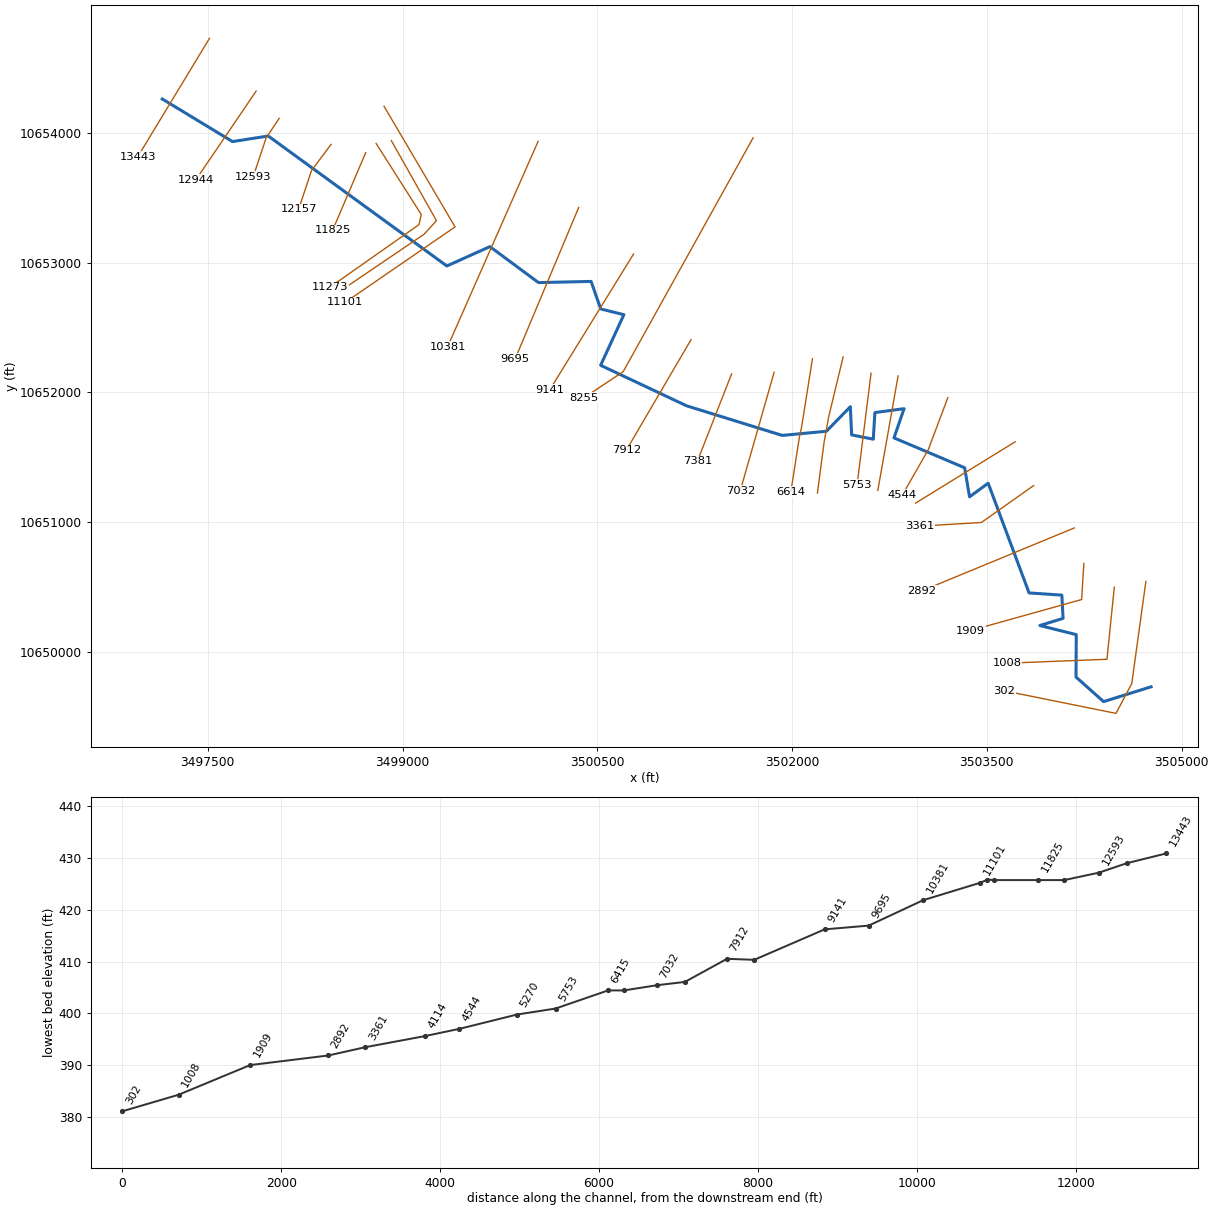
--- UNT064 IN CCTC.prj (project) ---

Proj Title=UNT064 IN CCTC Base Level Engineering
Current Plan=p01
Default Exp/Contr=0.3,0.1
English Units
Geom File=g01
Flow File=f01
Plan File=p01
Y Axis Title=Elevation
X Axis Title(PF)=Main Channel Distance
X Axis Title(XS)=Station
BEGIN DESCRIPTION:
UNT064 IN CCTC
END DESCRIPTION:
DSS Export Rating Curves= 0
DSS Export Rating Curve Sorted= 0
DSS Export Volume Flow Curves= 0
DXF OffsetX= 0
DXF OffsetY= 0
DXF ScaleX= 1
DXF ScaleY= 10

--- UNT064 IN CCTC.p01 (plan) ---

Plan Title=Multiple Run
Short Identifier=Multiple
Geom File=g01
Flow File=f01
Subcritical Flow
K Sum by GR= 0
Std Step Tol= 0.01
Critical Tol= 0.01
Num of Std Step Trials= 20
Max Error Tol= 0.3
Flow Tol Ratio= 0.001
Split Flow NTrial= 30
Split Flow Tol= 0.02
Split Flow Ratio= 0.02
Log Output Level= 0
Friction Slope Method= 1
Unsteady Friction Slope Method= 2
Unsteady Bridges Friction Slope Method= 1
Parabolic Critical Depth
Global Vel Dist=  1 , 1 , 1
Global Log Level= 0
CheckData=True
Encroach Param= -1, 0, 0, 0
BEGIN DESCRIPTION:
Multiple Run
END DESCRIPTION:

--- UNT064 IN CCTC.f01 (steady flow) ---

Flow Title=Multiple
Number of Profiles=7
Profile Names=10-year,25-year,50-year,1pct_min,100-year,1pct_plu,500-year
River Rch & RM= UNT064 IN CCTC,Reach-1,13443
    1125    1538    1875    1669    2257    3052    3261
River Rch & RM= UNT064 IN CCTC,Reach-1,12593
    1473    2037    2503    2242    3032    4101    4441
River Rch & RM= UNT064 IN CCTC,Reach-1,6415
    1711    2383    2942    2647    3580    4842    5289
Boundary for River Rch & Prof#=UNT064 IN CCTC,Reach-1,1
Up Type=0
Dn Type=3
Dn Slope=0.005
Boundary for River Rch & Prof#=UNT064 IN CCTC,Reach-1,2
Up Type=0
Dn Type=3
Dn Slope=0.005
Boundary for River Rch & Prof#=UNT064 IN CCTC,Reach-1,3
Up Type=0
Dn Type=3
Dn Slope=0.005
Boundary for River Rch & Prof#=UNT064 IN CCTC,Reach-1,4
Up Type=0
Dn Type=3
Dn Slope=0.005
Boundary for River Rch & Prof#=UNT064 IN CCTC,Reach-1,5
Up Type=0
Dn Type=3
Dn Slope=0.005
Boundary for River Rch & Prof#=UNT064 IN CCTC,Reach-1,6
Up Type=0
Dn Type=3
Dn Slope=0.005
Boundary for River Rch & Prof#=UNT064 IN CCTC,Reach-1,7
Up Type=0
Dn Type=3
Dn Slope=0.005

--- UNT064 IN CCTC.g01 (geometry) ---

Geom Title=Existing Conditions

River Reach=UNT064 IN CCTC,Reach-1
Reach XY= 30
      3497149.61     10654260.19      3497690.75     10653932.00
      3497965.75     10653975.00      3499341.50     10652974.00
      3499673.00     10653123.00      3500047.25     10652846.00
      3500452.50     10652855.00      3500526.25     10652643.00
      3500704.75     10652599.00      3500525.75     10652209.00
      3501187.75     10651897.00      3501924.25     10651669.00
      3502264.25     10651701.00      3502449.00     10651890.00
      3502458.75     10651673.00      3502625.50     10651640.00
      3502638.00     10651845.00      3502862.50     10651875.00
      3502785.00     10651650.00      3503329.00     10651420.00
      3503367.00     10651196.00      3503510.25     10651301.00
      3503825.25     10650456.00      3504077.75     10650439.00
      3504087.25     10650260.00      3503908.50     10650205.00
      3504188.75     10650135.00      3504186.75     10649808.00
      3504399.25     10649619.00      3504765.00     10649733.00

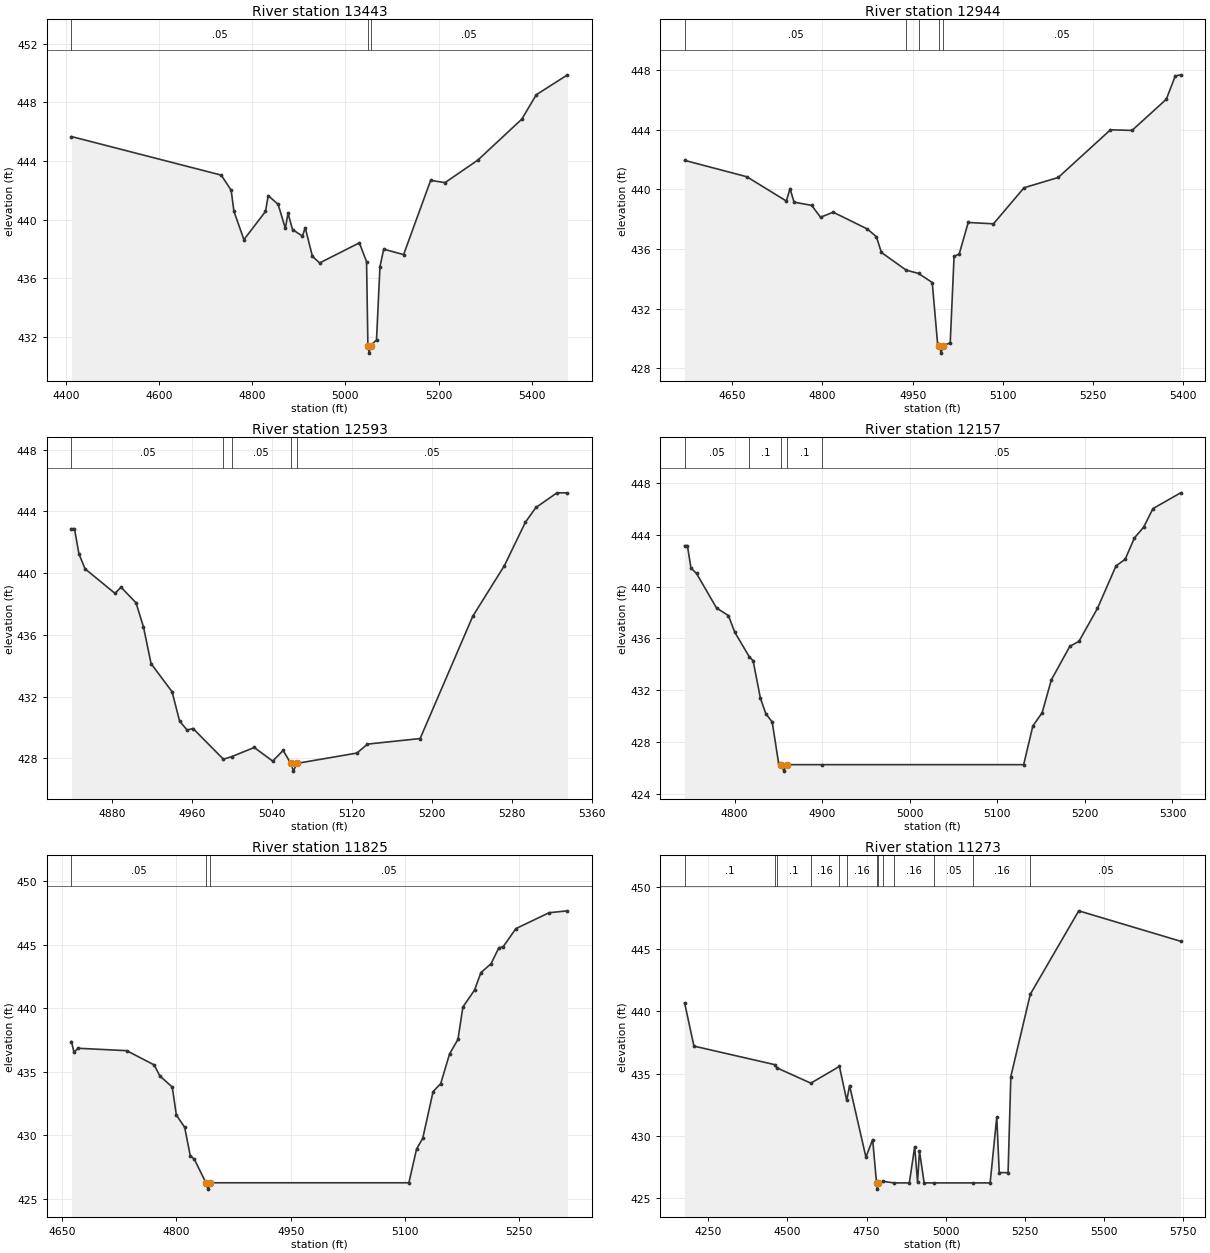
Type RM Length L Ch R = 1,13443,499,499,499
BEGIN DESCRIPTION:
UNT064 IN CCTC 22.0
END DESCRIPTION:
XS GIS Cut Line= 2
      3497513.32     10654727.13      3496961.19     10653815.60
#Sta/Elev= 30
  4411.4  445.67  4733.2  443.04  4754.5  442.01  4760.4  440.58  4781.9  438.64
  4828.2  440.56  4834.1  441.64  4855.4  441.05  4870.9  439.41  4876.7  440.43
  4886.4  439.33  4907.7  438.88  4913.6  439.46  4929.1  437.50  4944.6  437.05
  5029.9  438.42  5045.4  437.14  5048.3  431.40  5051.0  430.90  5054.3  431.40
  5066.8  431.81  5074.2  436.80  5082.3  437.99  5125.0  437.62  5183.1  442.68
  5214.1  442.53  5284.7  444.07  5379.0  446.86  5410.0  448.52  5477.1  449.88
#Mann=3,-1,0
  4411.4    0.05       0  5048.3    0.03       0  5054.3    0.05       0
Bank Sta=5048.3,5054.3
Exp/Cntr=0.3,0.1

Type RM Length L Ch R = 1,12944,351,351,351
BEGIN DESCRIPTION:
UNT064 IN CCTC 21.0
END DESCRIPTION:
XS GIS Cut Line= 2
      3497872.65     10654320.81      3497409.14     10653638.57
#Sta/Elev= 30
  4570.8  441.95  4674.2  440.85  4740.0  439.22  4746.1  440.05  4752.9  439.14
  4782.0  438.93  4796.9  438.13  4817.9  438.47  4874.8  437.34  4889.8  436.82
  4898.0  435.77  4939.3  434.58  4959.8  434.36  4982.6  433.75  4991.5  429.64
  4994.6  429.51  4997.3  429.01  5000.6  429.51  5012.5  429.70  5018.9  435.51
  5027.4  435.66  5042.4  437.78  5084.4  437.69  5135.2  440.11  5192.1  440.80
  5278.9  444.00  5314.9  443.96  5371.8  446.05  5386.7  447.61  5395.6  447.69
#Mann=5,-1,0
  4570.8    0.05       0  4939.3    0.16       0  4959.8    0.05       0
  4994.6    0.03       0  5000.6    0.05       0
Bank Sta=4994.6,5000.6
Exp/Cntr=0.3,0.1

Type RM Length L Ch R = 1,12593,436,436,436
BEGIN DESCRIPTION:
UNT064 IN CCTC 20.0
END DESCRIPTION:
XS GIS Cut Line= 3
      3498049.63     10654110.22      3497949.61     10653960.19
      3497849.62     10653660.23
#Sta/Elev= 30
  4839.1  442.88  4842.1  442.88  4846.6  441.24  4852.7  440.28  4882.7  438.69
  4888.7  439.09  4903.7  438.08  4911.2  436.51  4918.8  434.14  4939.8  432.32
  4947.3  430.43  4954.8  429.84  4960.8  429.94  4991.2  427.95  4999.5  428.12
  5022.1  428.71  5040.5  427.83  5051.0  428.52  5058.6  427.68  5061.3  427.18
  5064.6  427.68  5124.8  428.35  5135.4  428.93  5188.1  429.29  5240.8  437.21
  5272.4  440.48  5293.5  443.30  5304.0  444.25  5325.1  445.20  5335.6  445.20
#Mann=5,-1,0
  4839.1    0.05       0  4991.2    0.16       0  4999.5    0.05       0
  5058.6   0.035       0  5064.6    0.05       0
Bank Sta=5058.6,5064.6
Exp/Cntr=0.3,0.1

Type RM Length L Ch R = 1,12157,332,332,332
BEGIN DESCRIPTION:
UNT064 IN CCTC 19.0
END DESCRIPTION:
XS GIS Cut Line= 3
      3498449.64     10653910.23      3498299.61     10653710.19
      3498199.60     10653410.16
#Sta/Elev= 30
  4743.0  443.17  4746.2  443.17  4750.3  441.44  4756.6  441.02  4779.5  438.35
  4793.0  437.77  4800.3  436.48  4817.0  434.57  4821.2  434.29  4829.5  431.40
  4835.8  430.18  4843.0  429.55  4850.3  426.38  4853.6  426.25  4856.3  425.75
  4859.6  426.25  4900.4  426.25  5130.1  426.25  5140.6  429.24  5151.2  430.26
  5161.7  432.80  5182.8  435.39  5193.3  435.78  5214.4  438.33  5235.5  441.60
  5246.0  442.12  5256.6  443.77  5267.1  444.60  5277.7  446.03  5309.3  447.25
#Mann=5,-1,0
  4743.0    0.05       0  4817.0     0.1       0  4853.6   0.033       0
  4859.6     0.1       0  4900.4    0.05       0
Bank Sta=4853.6,4859.6
Exp/Cntr=0.3,0.1

Type RM Length L Ch R = 1,11825,552,552,552
BEGIN DESCRIPTION:
UNT064 IN CCTC 18.0
END DESCRIPTION:
XS GIS Cut Line= 2
      3498716.43     10653846.90      3498461.21     10653247.91
#Sta/Elev= 30
  4662.3  437.37  4665.6  436.53  4671.0  436.84  4734.8  436.65  4770.9  435.53
  4778.3  434.66  4794.6  433.79  4800.0  431.58  4810.9  430.62  4818.2  428.39
  4823.6  428.10  4838.8  426.25  4841.6  425.75  4844.8  426.25  5105.2  426.25
  5115.3  428.91  5123.4  429.75  5137.0  433.43  5147.0  434.06  5158.7  436.41
  5169.6  437.53  5176.1  440.09  5191.4  441.42  5199.7  442.79  5213.1  443.50
  5223.4  444.76  5228.8  444.82  5245.7  446.26  5289.2  447.51  5313.4  447.66
#Mann=3,-1,0
  4662.3    0.05       0  4838.8   0.033       0  4844.8    0.05       0
Bank Sta=4838.8,4844.8
Exp/Cntr=0.3,0.1

Type RM Length L Ch R = 1,11273,82,82,82
BEGIN DESCRIPTION:
UNT064 IN CCTC 17.0
END DESCRIPTION:
XS GIS Cut Line= 4
      3498796.98     10653917.32      3499144.20     10653370.43
      3499126.84     10653292.31      3498441.09     10652810.54
#Sta/Elev= 30
  4175.4  440.69  4205.0  437.22  4460.6  435.73  4467.2  435.47  4573.9  434.25
  4664.2  435.59  4687.2  432.87  4696.2  434.05  4747.9  428.31  4769.1  429.73
  4781.3  426.25  4784.1  425.75  4787.3  426.25  4800.5  426.38  4836.0  426.25
  4884.9  426.25  4901.8  429.15  4910.8  426.31  4916.9  428.79  4931.7  426.25
  4963.9  426.25  5087.2  426.25  5140.0  426.25  5160.9  431.53  5168.7  427.08
  5196.6  427.07  5205.3  434.78  5266.7  441.38  5419.7  448.07  5741.3  445.63
#Mann=13,-1,0
  4175.4     0.1       0  4460.6    0.16       0  4467.2     0.1       0
  4573.9    0.16       0  4664.2     0.1       0  4687.2    0.16       0
  4781.3   0.033       0  4787.3    0.16       0  4800.5    0.05       0
  4836.0    0.16       0  4963.9    0.05       0  5087.2    0.16       0
  5266.7    0.05       0
Bank Sta=4781.3,4787.3
Exp/Cntr=0.3,0.1

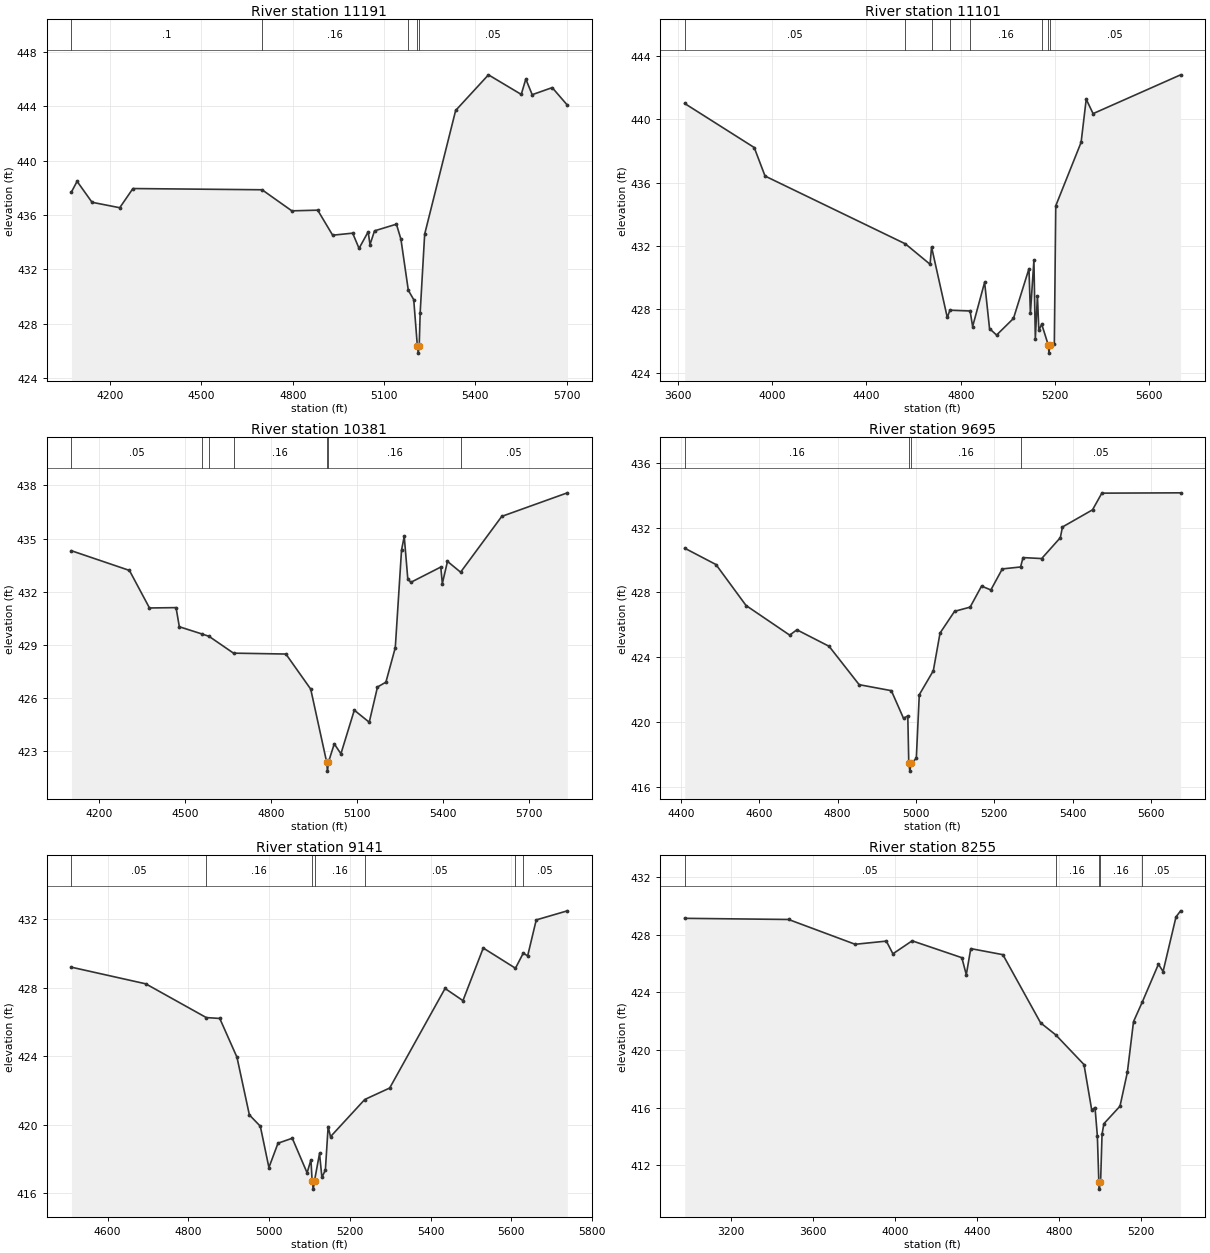
Type RM Length L Ch R = 1,11191,90,90,90
BEGIN DESCRIPTION:
Mapping XS e88672e1
END DESCRIPTION:
XS GIS Cut Line= 4
      3498914.18     10653938.98      3499261.39     10653322.69
      3499165.91     10653218.52      3498519.17     10652780.13
#Sta/Elev= 30
  4072.8  437.70  4091.3  438.48  4140.4  436.94  4231.5  436.54  4274.8  437.95
  4699.3  437.86  4797.1  436.31  4882.2  436.36  4931.3  434.52  4997.1  434.67
  5018.1  433.55  5048.0  434.77  5054.1  433.83  5069.0  434.84  5140.9  435.33
  5155.8  434.22  5180.0  430.47  5197.8  429.78  5209.8  426.35  5212.5  425.85
  5215.8  426.35  5219.0  428.83  5233.8  434.60  5335.6  443.69  5443.4  446.31
  5551.2  444.87  5566.2  446.00  5587.2  444.85  5653.0  445.37  5702.8  444.08
#Mann=5,-1,0
  4072.8     0.1       0  4699.3    0.16       0  5180.0    0.05       0
  5209.8    0.07       0  5215.8    0.05       0
Bank Sta=5209.8,5215.8
Exp/Cntr=0.3,0.1

Type RM Length L Ch R = 1,11101,720,720,720
BEGIN DESCRIPTION:
UNT064 IN CCTC 16.0
END DESCRIPTION:
XS GIS Cut Line= 3
      3498857.72     10654203.81      3499404.62     10653274.95
      3498559.61     10652694.27
#Sta/Elev= 30
  3629.4  441.00  3924.2  438.22  3970.1  436.42  4565.1  432.14  4670.0  430.85
  4676.3  431.94  4743.0  427.49  4754.2  427.95  4839.8  427.90  4850.5  426.92
  4901.3  429.71  4922.2  426.79  4952.0  426.38  5023.7  427.43  5089.4  430.57
  5095.5  427.76  5110.4  431.11  5116.4  426.14  5125.3  428.86  5131.3  426.67
  5143.4  427.07  5171.5  425.74  5174.2  425.24  5177.5  425.74  5197.0  425.82
  5203.0  434.54  5310.6  438.55  5332.2  441.27  5361.4  440.36  5732.6  442.81
#Mann=8,-1,0
  3629.4    0.05       0  4565.1     0.1       0  4676.3    0.05       0
  4754.2     0.1       0  4839.8    0.16       0  5143.4    0.05       0
  5171.5    0.07       0  5177.5    0.05       0
Bank Sta=5171.5,5177.5
Exp/Cntr=0.3,0.1

Type RM Length L Ch R = 1,10381,686,686,686
BEGIN DESCRIPTION:
UNT064 IN CCTC 15.0
END DESCRIPTION:
XS GIS Cut Line= 2
      3500044.50     10653934.07      3499346.59     10652350.76
#Sta/Elev= 30
  4103.3  434.31  4305.5  433.20  4375.5  431.08  4468.2  431.10  4479.7  430.02
  4557.1  429.62  4583.2  429.48  4668.7  428.53  4851.5  428.48  4938.1  426.50
  4993.9  422.37  4996.6  421.87  4999.9  422.37  5020.2  423.41  5043.5  422.85
  5090.2  425.31  5142.3  424.63  5171.1  426.62  5200.4  426.89  5233.2  428.84
  5255.0  434.35  5264.4  435.12  5276.9  432.71  5287.7  432.53  5391.9  433.39
  5397.4  432.46  5415.3  433.71  5461.1  433.10  5604.7  436.25  5833.6  437.58
#Mann=7,-1,0
  4103.3    0.05       0  4557.1    0.16       0  4583.2    0.05       0
  4668.7    0.16       0  4993.9    0.07       0  4999.9    0.16       0
  5461.1    0.05       0
Bank Sta=4993.9,4999.9
Exp/Cntr=0.3,0.1

Type RM Length L Ch R = 1,9695,554,554,554
BEGIN DESCRIPTION:
UNT064 IN CCTC 14.0
END DESCRIPTION:
XS GIS Cut Line= 2
      3500357.06     10653425.04      3499867.45     10652258.31
#Sta/Elev= 30
  4410.1  430.73  4489.9  429.72  4566.6  427.19  4678.0  425.36  4696.3  425.69
  4778.5  424.67  4855.2  422.30  4937.3  421.93  4968.4  420.22  4979.3  420.37
  4981.8  417.46  4984.6  416.96  4987.8  417.46  5001.0  417.74  5008.6  421.68
  5044.4  423.16  5061.6  425.49  5098.6  426.83  5138.3  427.09  5167.5  428.39
  5191.2  428.15  5220.4  429.45  5267.0  429.57  5273.4  430.15  5320.9  430.09
  5368.5  431.38  5373.9  432.04  5450.6  433.10  5474.4  434.13  5675.4  434.15
#Mann=4,-1,0
  4410.1    0.16       0  4981.8    0.07       0  4987.8    0.16       0
  5267.0    0.05       0
Bank Sta=4981.8,4987.8
Exp/Cntr=0.3,0.1

Type RM Length L Ch R = 1,9141,886,886,886
BEGIN DESCRIPTION:
UNT064 IN CCTC 13.0
END DESCRIPTION:
XS GIS Cut Line= 2
      3500778.93     10653065.64      3500133.86     10652020.01
#Sta/Elev= 30
  4510.4  429.19  4694.5  428.22  4844.5  426.25  4877.8  426.20  4920.4  423.94
  4951.2  420.57  4978.3  419.91  4999.6  417.50  5022.1  418.92  5057.5  419.21
  5094.2  417.19  5103.7  417.95  5106.6  416.74  5109.4  416.24  5112.6  416.74
  5125.0  418.32  5130.9  416.92  5139.5  417.36  5146.3  419.89  5152.2  419.30
  5237.0  421.47  5298.8  422.14  5436.0  427.95  5480.3  427.24  5530.6  430.31
  5610.4  429.13  5629.7  430.01  5640.6  429.85  5661.9  431.95  5739.0  432.48
#Mann=7,-1,0
  4510.4    0.05       0  4844.5    0.16       0  5106.6    0.07       0
  5112.6    0.16       0  5237.0    0.05       0  5610.4    0.16       0
  5629.7    0.05       0
Bank Sta=5106.6,5112.6
Exp/Cntr=0.3,0.1

Type RM Length L Ch R = 1,8255,343,343,343
BEGIN DESCRIPTION:
UNT064 IN CCTC 12.0
END DESCRIPTION:
XS GIS Cut Line= 3
      3501699.62     10653960.22      3500699.61     10652160.19
      3500399.62     10651960.20
#Sta/Elev= 30
  2974.8  429.14  3481.6  429.06  3806.5  427.34  3958.6  427.56  3990.7  426.68
  4084.5  427.58  4327.0  426.41  4348.7  425.23  4370.5  427.04  4527.2  426.62
  4711.4  421.89  4785.0  421.06  4923.0  419.00  4960.7  415.85  4976.8  416.02
  4988.2  414.06  4995.5  410.86  4998.2  410.36  5001.5  410.86  5004.2  410.93
  5011.1  414.17  5020.2  414.90  5098.6  416.11  5134.6  418.46  5164.7  421.98
  5207.6  423.34  5286.3  425.96  5308.9  425.45  5372.0  429.24  5394.5  429.66
#Mann=5,-1,0
  2974.8    0.05       0  4785.0    0.16       0  4995.5    0.07       0
  5001.5    0.16       0  5207.6    0.05       0
Bank Sta=4995.5,5001.5
Exp/Cntr=0.3,0.1

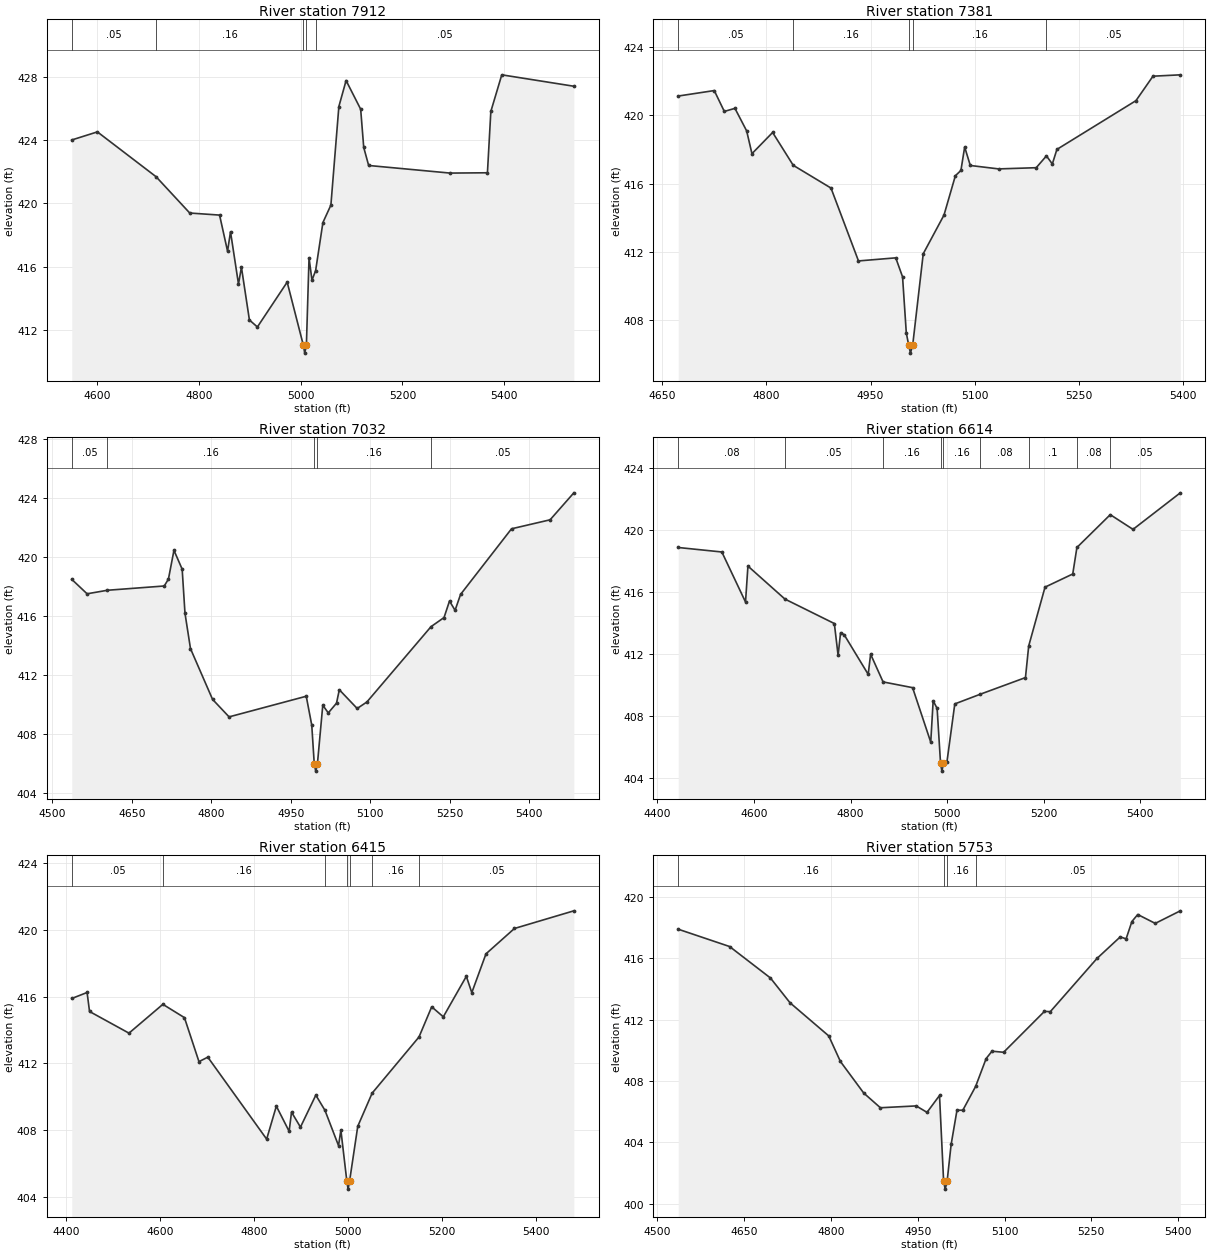
Type RM Length L Ch R = 1,7912,531,531,531
BEGIN DESCRIPTION:
UNT064 IN CCTC 11.0
END DESCRIPTION:
XS GIS Cut Line= 2
      3501221.65     10652405.94      3500722.63     10651553.46
#Sta/Elev= 30
  4549.4  424.00  4599.8  424.51  4715.3  421.68  4781.5  419.39  4840.2  419.26
  4855.9  416.98  4861.7  418.21  4877.4  414.91  4883.2  415.97  4898.9  412.64
  4914.6  412.20  4973.2  415.03  5005.0  411.05  5007.7  410.55  5011.0  411.05
  5016.2  416.56  5022.0  415.15  5029.2  415.76  5043.5  418.79  5059.2  419.89
  5074.9  426.11  5089.1  427.75  5117.8  425.94  5123.8  423.53  5133.5  422.39
  5293.8  421.91  5367.2  421.93  5373.9  425.80  5395.4  428.11  5537.2  427.39
#Mann=5,-1,0
  4549.4    0.05       0  4715.3    0.16       0  5005.0    0.07       0
  5011.0    0.16       0  5029.2    0.05       0
Bank Sta=5005,5011
Exp/Cntr=0.3,0.1

Type RM Length L Ch R = 1,7381,349,349,349
BEGIN DESCRIPTION:
UNT064 IN CCTC 10.0
END DESCRIPTION:
XS GIS Cut Line= 2
      3501534.12     10652142.01      3501270.25     10651468.45
#Sta/Elev= 30
  4672.9  421.12  4724.8  421.44  4739.3  420.22  4754.6  420.40  4771.5  419.08
  4779.1  417.75  4808.9  418.99  4838.6  417.07  4893.0  415.74  4932.6  411.48
  4986.3  411.66  4996.1  410.55  5001.5  407.27  5004.8  406.59  5007.5  406.09
  5010.8  406.59  5025.9  411.90  5055.8  414.16  5072.2  416.46  5080.2  416.77
  5085.6  418.14  5093.7  417.06  5134.5  416.86  5188.7  416.93  5203.4  417.62
  5211.9  417.15  5218.5  418.00  5332.4  420.85  5356.9  422.28  5396.3  422.36
#Mann=5,-1,0
  4672.9    0.05       0  4838.6    0.16       0  5004.8    0.07       0
  5010.8    0.16       0  5203.4    0.05       0
Bank Sta=5004.8,5010.8
Exp/Cntr=0.3,0.1

Type RM Length L Ch R = 1,7032,418,418,418
BEGIN DESCRIPTION:
Mapping XS 68be8086
END DESCRIPTION:
XS GIS Cut Line= 2
      3501861.82     10652155.57      3501601.58     10651244.72
#Sta/Elev= 30
  4536.7  418.47  4565.6  417.49  4603.9  417.73  4711.2  418.02  4719.1  418.49
  4729.5  420.44  4745.0  419.16  4750.3  416.17  4760.7  413.77  4802.3  410.33
  4833.5  409.14  4979.1  410.54  4989.5  408.58  4994.2  405.96  4997.0  405.46
  5000.2  405.96  5010.3  409.93  5020.7  409.41  5036.2  410.07  5041.5  410.98
  5075.2  409.71  5093.5  410.15  5214.5  415.26  5239.1  415.88  5249.4  417.00
  5259.9  416.37  5270.3  417.45  5366.4  421.90  5439.2  422.51  5484.0  424.34
#Mann=5,-1,0
  4536.7    0.05       0  4603.9    0.16       0  4994.2    0.07       0
  5000.2    0.16       0  5214.5    0.05       0
Bank Sta=4994.2,5000.2
Exp/Cntr=0.3,0.1

Type RM Length L Ch R = 1,6614,199,199,199
BEGIN DESCRIPTION:
UNT064 IN CCTC 9.0
END DESCRIPTION:
XS GIS Cut Line= 4
      3502157.00     10652259.39      3502073.67     10651735.06
      3502056.31     10651655.20      3501990.62     10651233.42
#Sta/Elev= 30
  4443.1  418.89  4533.4  418.60  4582.4  415.37  4587.4  417.69  4664.0  415.56
  4766.3  413.98  4774.1  411.92  4779.2  413.39  4786.6  413.26  4836.4  410.70
  4841.4  412.00  4867.2  410.21  4928.3  409.84  4965.9  406.32  4970.9  408.99
  4979.1  408.50  4986.2  404.95  4989.0  404.45  4992.2  404.95  4999.5  405.06
  5015.7  408.79  5068.8  409.42  5162.0  410.49  5168.7  412.53  5202.5  416.33
  5259.9  417.18  5268.5  418.89  5337.6  421.01  5384.7  420.06  5482.6  422.42
#Mann=9,-1,0
  4443.1    0.08       0  4664.0    0.05       0  4867.2    0.16       0
  4986.2    0.07       0  4992.2    0.16       0  5068.8    0.08       0
  5168.7     0.1       0  5268.5    0.08       0  5337.6    0.05       0
Bank Sta=4986.2,4992.2
Exp/Cntr=0.3,0.1

Type RM Length L Ch R = 1,6415,662,662,662
BEGIN DESCRIPTION:
UNT064 IN CCTC 8.0
END DESCRIPTION:
XS GIS Cut Line= 4
      3502393.12     10652273.28      3502282.00     10651811.45
      3502247.28     10651620.48      3502195.23     10651224.90
#Sta/Elev= 30
  4411.9  415.89  4444.5  416.25  4449.7  415.11  4533.6  413.81  4605.7  415.54
  4651.6  414.74  4682.5  412.10  4701.3  412.37  4826.5  407.45  4847.1  409.43
  4874.3  407.92  4879.4  409.07  4898.4  408.17  4931.1  410.09  4950.5  409.18
  4979.4  407.06  4984.4  407.99  4997.0  404.95  4999.7  404.45  5003.0  404.95
  5020.3  408.22  5050.9  410.21  5150.6  413.58  5177.6  415.39  5202.3  414.79
  5251.3  417.22  5262.9  416.24  5293.1  418.57  5353.6  420.09  5480.0  421.15
#Mann=7,-1,0
  4411.9    0.05       0  4605.7    0.16       0  4950.5    0.05       0
  4997.0    0.03       0  5003.0    0.05       0  5050.9    0.16       0
  5150.6    0.05       0
Bank Sta=4997,5003
Exp/Cntr=0.3,0.1

Type RM Length L Ch R = 1,5753,483,483,483
BEGIN DESCRIPTION:
UNT064 IN CCTC 7.0
END DESCRIPTION:
XS GIS Cut Line= 2
      3502608.39     10652148.28      3502500.76     10651287.18
#Sta/Elev= 30
  4536.0  417.91  4624.8  416.78  4695.3  414.73  4729.2  413.11  4796.1  410.95
  4816.3  409.28  4856.6  407.22  4885.4  406.26  4947.3  406.38  4966.0  405.96
  4987.6  407.06  4994.7  401.45  4997.4  400.95  5000.7  401.45  5007.7  403.87
  5017.8  406.10  5027.9  406.10  5050.0  407.65  5068.2  409.47  5078.3  409.95
  5098.4  409.88  5169.0  412.55  5179.1  412.53  5259.7  416.00  5300.0  417.41
  5310.1  417.28  5320.1  418.41  5330.2  418.87  5360.5  418.29  5403.8  419.11
#Mann=4,-1,0
  4536.0    0.16       0  4994.7    0.07       0  5000.7    0.16       0
  5050.0    0.05       0
Bank Sta=4994.7,5000.7
Exp/Cntr=0.3,0.1

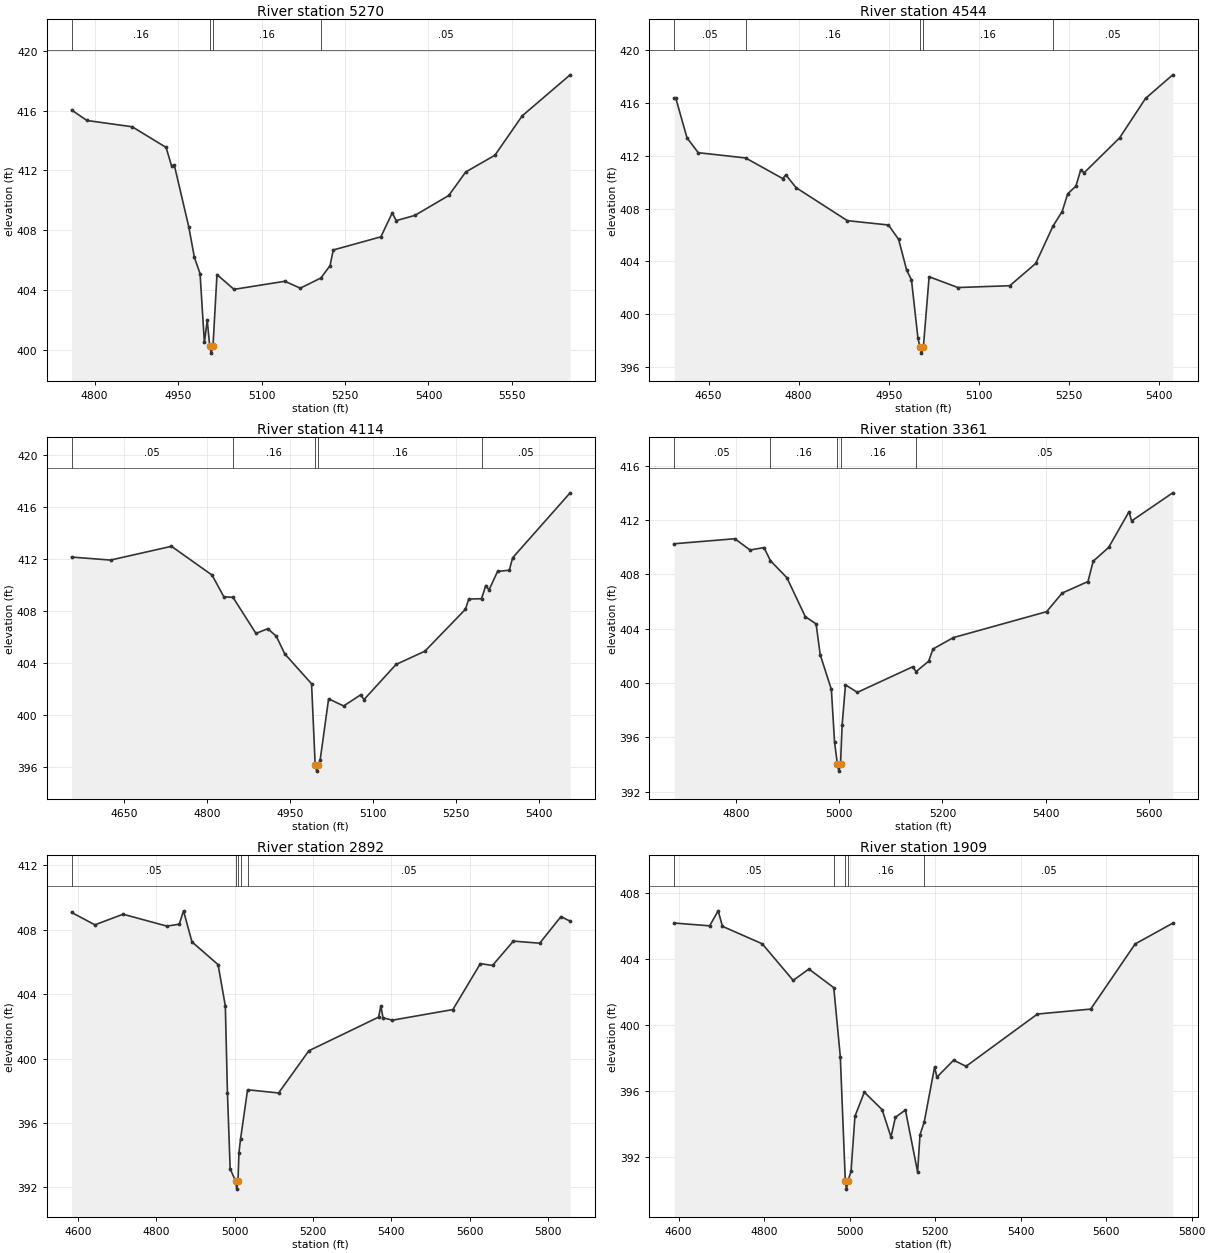
Type RM Length L Ch R = 1,5270,726,726,726
BEGIN DESCRIPTION:
UNT064 IN CCTC 6.0
END DESCRIPTION:
XS GIS Cut Line= 2
      3502816.72     10652127.41      3502660.47     10651245.45
#Sta/Elev= 30
  4758.8  416.04  4786.4  415.34  4867.7  414.92  4928.6  413.54  4938.3  412.32
  4943.4  412.35  4969.3  408.24  4979.4  406.20  4989.6  405.11  4997.4  400.51
  5002.5  402.00  5006.9  400.30  5009.6  399.80  5012.9  400.30  5020.0  405.05
  5050.5  404.06  5141.9  404.60  5169.7  404.14  5206.7  404.82  5223.1  405.64
  5228.9  406.69  5314.5  407.57  5334.9  409.17  5342.0  408.65  5375.5  409.00
  5436.4  410.33  5466.9  411.90  5519.4  413.02  5568.4  415.65  5654.5  418.39
#Mann=4,-1,0
  4758.8    0.16       0  5006.9    0.07       0  5012.9    0.16       0
  5206.7    0.05       0
Bank Sta=5006.9,5012.9
Exp/Cntr=0.3,0.1

Type RM Length L Ch R = 1,4544,430,430,430
BEGIN DESCRIPTION:
UNT064 IN CCTC 5.0
END DESCRIPTION:
XS GIS Cut Line= 3
      3503199.62     10651960.22      3503049.61     10651560.19
      3502849.63     10651210.23
#Sta/Elev= 30
  4592.8  416.36  4595.5  416.36  4614.2  413.35  4632.9  412.23  4711.8  411.83
  4773.5  410.27  4778.8  410.55  4795.8  409.58  4881.2  407.08  4949.7  406.75
  4966.6  405.66  4980.0  403.33  4988.0  402.59  4998.7  398.21  5001.9  397.54
  5004.7  397.04  5007.9  397.54  5017.4  402.83  5065.4  402.01  5151.8  402.15
  5195.0  403.84  5223.5  406.65  5238.9  407.77  5248.2  409.11  5261.9  409.70
  5269.8  410.91  5275.6  410.71  5334.6  413.35  5377.8  416.34  5423.1  418.13
#Mann=5,-1,0
  4592.8    0.05       0  4711.8    0.16       0  5001.9    0.07       0
  5007.9    0.16       0  5223.5    0.05       0
Bank Sta=5001.9,5007.9
Exp/Cntr=0.3,0.1

Type RM Length L Ch R = 1,4114,753,753,753
BEGIN DESCRIPTION:
Mapping XS 93c3cd37
END DESCRIPTION:
XS GIS Cut Line= 2
      3503718.36     10651619.80      3502951.02     10651147.58
#Sta/Elev= 30
  4555.3  412.14  4625.7  411.91  4735.8  412.97  4809.2  410.75  4830.5  409.08
  4847.0  409.04  4888.5  406.26  4909.8  406.62  4925.2  406.05  4940.6  404.68
  4989.0  402.38  4995.5  396.15  4998.3  395.65  5001.5  396.15  5004.4  396.47
  5019.8  401.22  5047.0  400.67  5077.8  401.53  5083.7  401.16  5141.7  403.87
  5193.8  404.89  5267.1  408.12  5273.0  408.91  5296.2  408.93  5303.8  409.95
  5309.7  409.61  5325.1  411.03  5346.4  411.13  5352.3  412.08  5456.3  417.09
#Mann=5,-1,0
  4555.3    0.05       0  4847.0    0.16       0  4995.5    0.07       0
  5001.5    0.16       0  5296.2    0.05       0
Bank Sta=4995.5,5001.5
Exp/Cntr=0.3,0.1

Type RM Length L Ch R = 1,3361,469,469,469
BEGIN DESCRIPTION:
UNT064 IN CCTC 4.0
END DESCRIPTION:
XS GIS Cut Line= 3
      3503860.68     10651282.96      3503457.93     10650998.26
      3502985.67     10650970.48
#Sta/Elev= 30
  4680.0  410.24  4797.5  410.61  4827.1  409.78  4854.1  409.96  4866.6  408.99
  4898.5  407.74  4934.2  404.87  4955.1  404.34  4963.0  402.08  4984.7  399.51
  4990.8  395.66  4996.4  394.00  4999.2  393.50  5002.4  394.00  5005.6  396.93
  5012.0  399.85  5035.1  399.30  5142.2  401.18  5148.9  400.83  5173.2  401.59
  5181.6  402.49  5221.0  403.33  5401.9  405.24  5432.0  406.61  5482.1  407.46
  5492.1  408.95  5522.1  409.97  5561.6  412.60  5566.6  411.92  5646.3  413.99
#Mann=5,-1,0
  4680.0    0.05       0  4866.6    0.16       0  4996.4    0.07       0
  5002.4    0.16       0  5148.9    0.05       0
Bank Sta=4996.4,5002.4
Exp/Cntr=0.3,0.1

Type RM Length L Ch R = 1,2892,983,983,983
BEGIN DESCRIPTION:
UNT064 IN CCTC 3.0
END DESCRIPTION:
XS GIS Cut Line= 2
      3504173.53     10650956.29      3502997.89     10650471.16
#Sta/Elev= 30
  4584.4  409.07  4643.9  408.30  4715.7  408.96  4827.6  408.22  4859.1  408.34
  4869.9  409.17  4891.5  407.24  4958.1  405.83  4976.6  403.26  4982.0  397.85
  4988.9  393.15  5002.9  392.39  5005.7  391.89  5008.9  392.39  5011.3  394.15
  5015.3  394.98  5033.3  398.06  5112.5  397.86  5189.6  400.48  5367.5  402.57
  5373.4  403.26  5378.8  402.53  5402.7  402.38  5557.1  403.04  5627.2  405.89
  5658.2  405.78  5711.4  407.29  5778.6  407.16  5832.7  408.81  5856.2  408.53
#Mann=5,-1,0
  4584.4    0.05       0  5002.9   0.035       0  5008.9    0.05       0
  5015.3    0.16       0  5033.3    0.05       0
Bank Sta=5002.9,5008.9
Exp/Cntr=0.3,0.1

Type RM Length L Ch R = 1,1909,901,901,901
BEGIN DESCRIPTION:
Mapping XS 822e6ca8
END DESCRIPTION:
XS GIS Cut Line= 3
      3504247.32     10650682.88      3504229.96     10650405.08
      3503374.90     10650166.36
#Sta/Elev= 30
  4589.6  406.18  4672.5  406.01  4692.5  406.92  4702.5  405.98  4795.6  404.92
  4867.9  402.70  4904.7  403.39  4962.9  402.26  4978.2  398.07  4989.9  390.54
  4992.6  390.04  4995.9  390.54  5003.3  391.11  5012.4  394.46  5034.4  395.92
  5076.0  394.86  5096.7  393.20  5107.1  394.40  5130.5  394.84  5159.0  391.08
  5164.6  393.34  5174.4  394.10  5198.8  397.46  5204.0  396.83  5243.3  397.86
  5272.3  397.49  5439.3  400.66  5563.9  400.96  5667.8  404.91  5755.7  406.17
#Mann=5,-1,0
  4589.6    0.05       0  4962.9    0.16       0  4989.9    0.07       0
  4995.9    0.16       0  5174.4    0.05       0
Bank Sta=4989.9,4995.9
Exp/Cntr=0.3,0.1

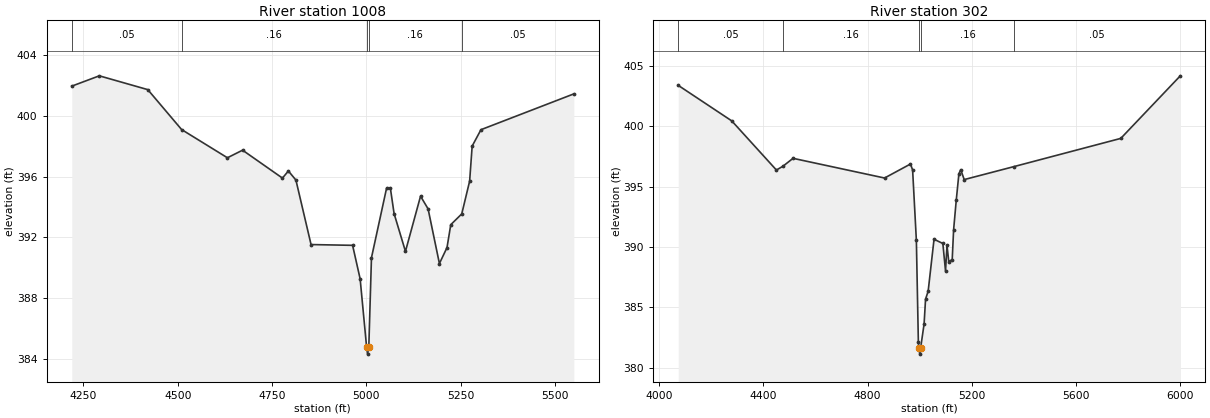
Type RM Length L Ch R = 1,1008,706,706,706
BEGIN DESCRIPTION:
UNT064 IN CCTC 2.0
END DESCRIPTION:
XS GIS Cut Line= 3
      3504481.70     10650500.61      3504425.27     10649945.01
      3503653.63     10649914.67
#Sta/Elev= 30
  4219.2  401.97  4292.2  402.65  4420.7  401.74  4510.3  399.11  4631.7  397.25
  4671.9  397.75  4777.6  395.91  4793.3  396.38  4813.3  395.78  4853.4  391.53
  4963.5  391.48  4983.5  389.27  5000.5  384.81  5003.2  384.31  5006.5  384.81
  5013.5  390.66  5053.5  395.24  5063.5  395.27  5073.5  393.57  5103.6  391.08
  5143.6  394.72  5163.6  393.88  5193.6  390.28  5213.7  391.33  5223.7  392.84
  5252.8  393.55  5273.7  395.71  5280.4  398.02  5303.7  399.10  5549.9  401.46
#Mann=5,-1,0
  4219.2    0.05       0  4510.3    0.16       0  5000.5    0.07       0
  5006.5    0.16       0  5252.8    0.05       0
Bank Sta=5000.5,5006.5
Exp/Cntr=0.3,0.1

Type RM Length L Ch R = 1,302,0,0,0
BEGIN DESCRIPTION:
UNT064 IN CCTC 1.0
END DESCRIPTION:
XS GIS Cut Line= 4
      3504724.76     10650544.00      3504616.25     10649758.38
      3504494.72     10649528.35      3503635.32     10649701.96
#Sta/Elev= 30
  4072.4  403.38  4278.1  400.44  4449.8  396.37  4475.2  396.69  4513.7  397.34
  4865.5  395.71  4965.2  396.87  4973.4  396.37  4987.8  390.54  4995.5  382.10
  4998.1  381.63  5000.9  381.13  5004.1  381.63  5017.5  383.63  5023.1  385.68
  5033.1  386.34  5055.7  390.64  5089.6  390.29  5099.9  388.01  5105.5  390.15
  5112.3  388.79  5125.6  388.96  5130.9  391.41  5141.1  393.87  5151.3  396.06
  5158.3  396.40  5171.7  395.58  5363.8  396.66  5773.6  398.99  6002.4  404.17
#Mann=5,-1,0
  4072.4    0.05       0  4475.2    0.16       0  4998.1    0.07       0
  5004.1    0.16       0  5363.8    0.05       0
Bank Sta=4998.1,5004.1
Exp/Cntr=0.3,0.1

Chan Stop Cuts=-1