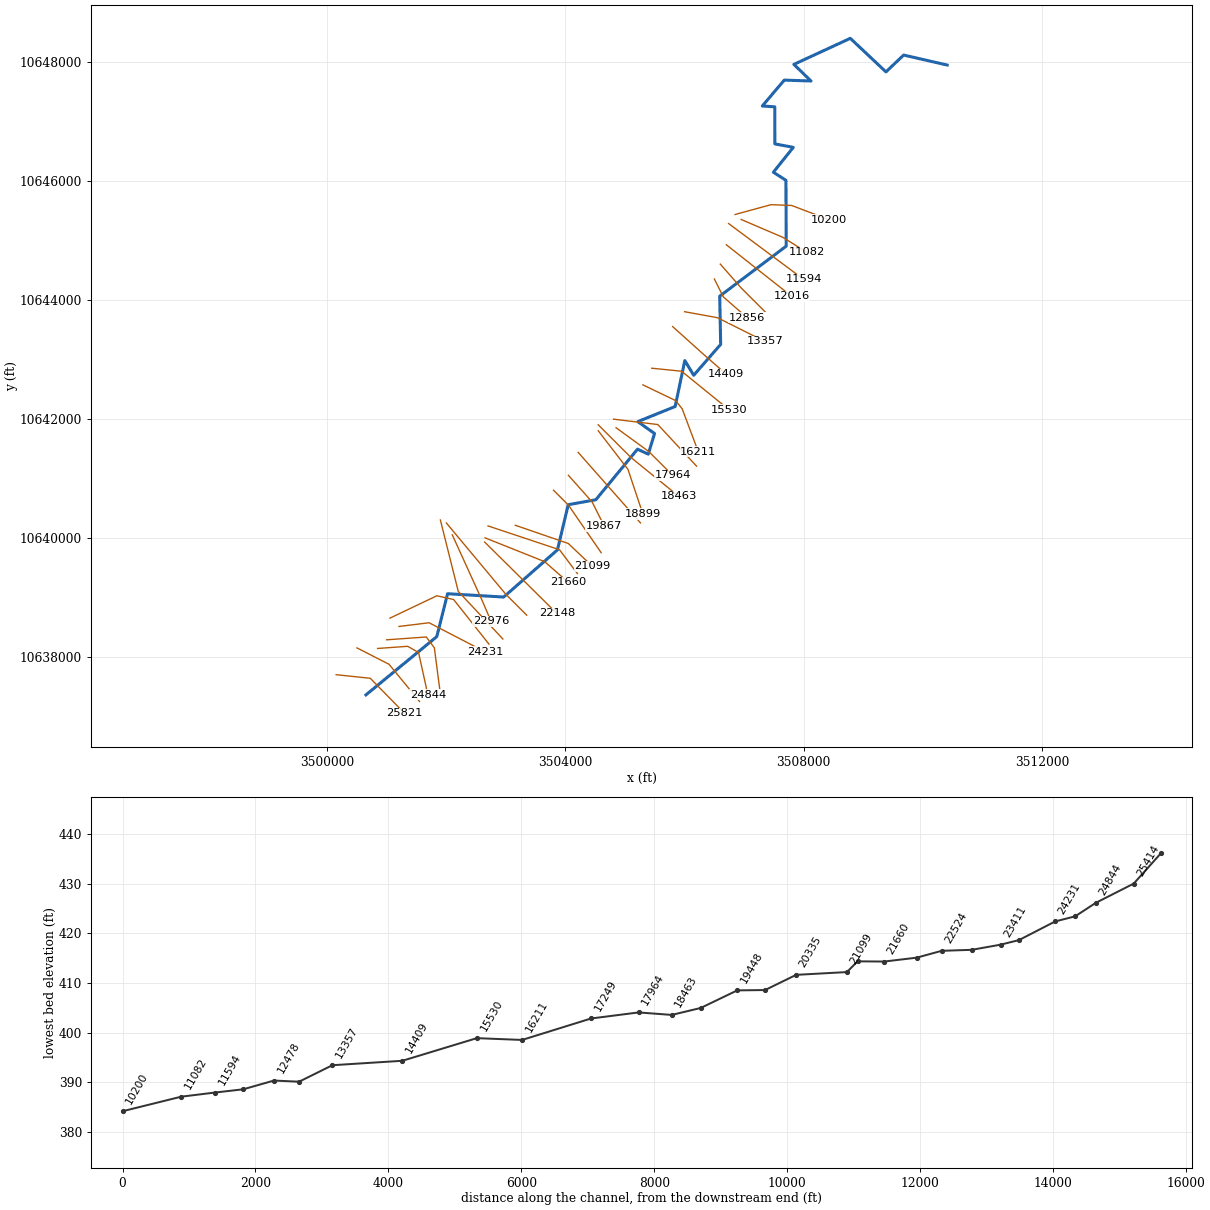
--- UNT065 IN CCTC.prj (project) ---

Proj Title=UNT065 IN CCTC Base Level Engineering
Current Plan=p01
Default Exp/Contr=0.3,0.1
English Units
Geom File=g01
Flow File=f01
Plan File=p01
Y Axis Title=Elevation
X Axis Title(PF)=Main Channel Distance
X Axis Title(XS)=Station
BEGIN DESCRIPTION:
UNT065 IN CCTC
END DESCRIPTION:
DSS Export Rating Curves= 0
DSS Export Rating Curve Sorted= 0
DSS Export Volume Flow Curves= 0
DXF OffsetX= 0
DXF OffsetY= 0
DXF ScaleX= 1
DXF ScaleY= 10

--- UNT065 IN CCTC.p01 (plan) ---

Plan Title=Multiple Run
Short Identifier=Multiple
Geom File=g01
Flow File=f01
Subcritical Flow
K Sum by GR= 0
Std Step Tol= 0.01
Critical Tol= 0.01
Num of Std Step Trials= 20
Max Error Tol= 0.3
Flow Tol Ratio= 0.001
Split Flow NTrial= 30
Split Flow Tol= 0.02
Split Flow Ratio= 0.02
Log Output Level= 0
Friction Slope Method= 1
Unsteady Friction Slope Method= 2
Unsteady Bridges Friction Slope Method= 1
Parabolic Critical Depth
Global Vel Dist=  1 , 1 , 1
Global Log Level= 0
CheckData=True
Encroach Param= -1, 0, 0, 0
BEGIN DESCRIPTION:
Multiple Run
END DESCRIPTION:

--- UNT065 IN CCTC.f01 (steady flow) ---

Flow Title=Multiple
Number of Profiles=7
Profile Names=10-year,25-year,50-year,1pct_min,100-year,1pct_plu,500-year
River Rch & RM= UNT065 IN CCTC,Reach-1,25821
     754    1008    1214    1069    1446    1956    2043
River Rch & RM= UNT065 IN CCTC,Reach-1,24231
     890    1204    1459    1293    1749    2365    2504
River Rch & RM= UNT065 IN CCTC,Reach-1,23411
    2039    2859    3547    3203    4332    5859    6451
River Rch & RM= UNT065 IN CCTC,Reach-1,12856
    2633    3724    4647    4217    5703    7712    8573
Boundary for River Rch & Prof#=UNT065 IN CCTC,Reach-1,1
Up Type=0
Dn Type=3
Dn Slope=0.005
Boundary for River Rch & Prof#=UNT065 IN CCTC,Reach-1,2
Up Type=0
Dn Type=3
Dn Slope=0.005
Boundary for River Rch & Prof#=UNT065 IN CCTC,Reach-1,3
Up Type=0
Dn Type=3
Dn Slope=0.005
Boundary for River Rch & Prof#=UNT065 IN CCTC,Reach-1,4
Up Type=0
Dn Type=3
Dn Slope=0.005
Boundary for River Rch & Prof#=UNT065 IN CCTC,Reach-1,5
Up Type=0
Dn Type=3
Dn Slope=0.005
Boundary for River Rch & Prof#=UNT065 IN CCTC,Reach-1,6
Up Type=0
Dn Type=3
Dn Slope=0.005
Boundary for River Rch & Prof#=UNT065 IN CCTC,Reach-1,7
Up Type=0
Dn Type=3
Dn Slope=0.005

--- UNT065 IN CCTC.g01 (geometry) ---

Geom Title=Existing Conditions
Program Version=4.10

River Reach=UNT065 IN CCTC  ,Reach-1
Reach XY= 30
        3500650.       10637371.      3501839.25       10638350.
        3502020.       10639071.      3502962.25       10639015.
        3503865.       10639807.       3504046.5       10640567.
       3504509.5       10640650.      3505209.25       10641500.
      3505390.25       10641416.       3505495.5       10641763.
       3505214.5       10641963.        3505842.       10642217.
        3506004.       10642989.      3506153.25       10642742.
        3506606.       10643261.        3506590.       10644071.
       3507706.5       10644912.        3507702.       10646018.
      3507490.75       10646154.       3507825.5       10646572.
       3507515.5       10646630.        3507515.       10647253.
        3507305.       10647267.        3507674.       10647702.
      3508122.75       10647687.      3507835.25       10647966.
        3508783.       10648404.        3509381.       10647840.
       3509678.5       10648123.       3510409.5       10647955.

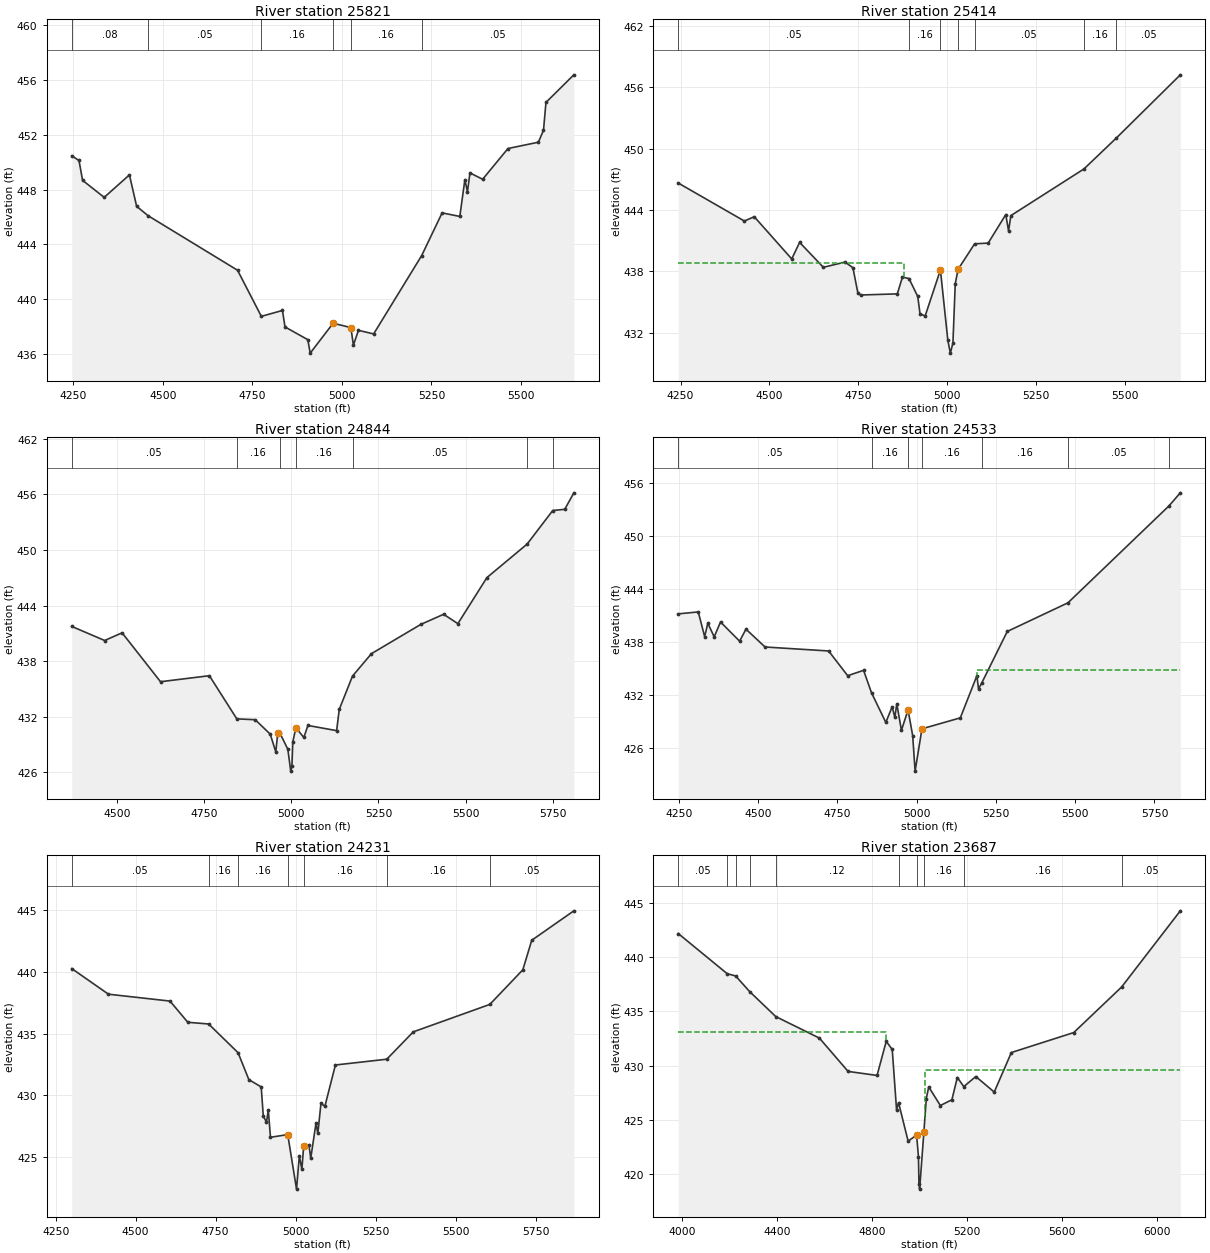
Type RM Length L Ch R = 1 ,25821   ,407,407,407
BEGIN DESCRIPTION:
UNT065 IN CCTC 38.0
END DESCRIPTION:
XS GIS Cut Line= 3
      3500149.59     10637710.19      3500722.67     10637649.74
      3501299.58     10637060.22
#Sta/Elev= 30
  4246.2  450.46  4266.3  450.12  4276.4  448.67  4336.7  447.43  4407.1  449.07
  4427.2  446.78  4458.8   446.1  4708.8  442.12  4775.2  438.76  4834.2  439.19
  4841.2  437.99  4904.9  437.06  4911.6  436.08  4975.6  438.26  5025.1  437.94
  5032.1  436.66  5046.2  437.74  5088.6  437.48  5222.7  443.19  5279.7   446.3
  5329.1  446.04  5343.2  448.72  5350.4  447.84  5357.4  449.21  5392.8  448.75
  5463.5  450.99  5548.4  451.45  5562.6  452.32  5569.5  454.35  5647.3  456.36
#Mann= 6 ,-1 , 0
  4246.2     .08       0  4458.8     .05       0  4775.2     .16       0
  4975.6     .12       0  5025.1     .16       0  5222.7     .05       0
Bank Sta=4975.6,5025.1
XS Rating Curve= 0 ,0
Exp/Cntr=0.3,0.1

Type RM Length L Ch R = 1 ,25414   ,570,570,570
BEGIN DESCRIPTION:
UNT065 IN CCTC 37.0
END DESCRIPTION:
XS GIS Cut Line= 3
       3500499.6      10638160.2      3501037.77     10637884.79
      3501549.62     10637260.17
#Sta/Elev= 30
  4243.5  446.65  4429.5  442.93  4457.3  443.35  4562.7  439.22  4584.9  440.84
  4651.6   438.4  4712.6  438.91  4734.8  438.36    4749  435.84    4757  435.69
  4859.7   435.8    4874  437.44  4892.5   437.3  4917.1  435.55  4923.5  433.86
  4937.9  433.63  4980.9  438.14  5001.8  431.24  5008.9     430  5016.1     431
  5022.6  436.79  5030.5   438.2  5077.1   440.7  5115.2  440.77  5164.7  443.56
  5172.6  441.96    5179  443.46  5384.7  448.03  5476.1  451.07  5655.6  457.24
#Mann= 7 ,-1 , 0
  4243.5     .05       0  4892.5     .16       0  4980.9     .12       0
  5030.5     .16       0  5077.1     .05       0  5384.7     .16       0
  5476.1     .05       0
#XS Ineff= 2 , 0
         4879.09  438.82
Permanent Ineff=
       F       F
Bank Sta=4980.9,5030.5
XS Rating Curve= 0 ,0
Exp/Cntr=0.3,0.1

Type RM Length L Ch R = 1 ,24844   ,311,311,311
BEGIN DESCRIPTION:
UNT065 IN CCTC 35.0
END DESCRIPTION:
XS GIS Cut Line= 4
      3500845.49     10638150.85      3501350.69      10638187.3
      3501532.99     10638083.14      3501689.18     10637375.03
#Sta/Elev= 30
  4369.3  441.75  4463.7  440.23  4513.8  441.06  4624.1  435.78  4764.4  436.43
  4843.2  431.77    4896  431.68  4939.2  430.12  4955.1  428.21  4960.8  430.24
  4966.7  430.25  4989.7  428.49    4998  426.13  5001.3  426.63    5004  429.29
  5012.8  430.81  5035.7  429.76  5047.3  431.06  5129.8   430.5  5137.3  432.79
  5175.4  436.39  5229.8  438.81  5371.1  441.96    5437  443.06  5477.9  442.05
  5561.3  447.02  5676.8  450.64  5750.3  454.26  5784.8  454.39  5810.9  456.17
#Mann= 7 ,-1 , 0
  4369.3     .05       0  4843.2     .16       0  4966.7     .12       0
  5012.8     .16       0  5175.4     .05       0  5676.8     .16       0
  5750.3     .05       0
Bank Sta=4960.8,5012.8
XS Rating Curve= 0 ,0
Exp/Cntr=0.3,0.1

Type RM Length L Ch R = 1 ,24533   ,302,302,302
BEGIN DESCRIPTION:
UNT065 IN CCTC 34.0
END DESCRIPTION:
XS GIS Cut Line= 4
      3500996.52     10638296.68      3501663.19     10638343.55
      3501798.61     10638161.26      3501887.15     10637478.99
#Sta/Elev= 30
  4248.1  441.21  4311.3  441.43  4331.4  438.63  4341.4  440.15  4361.5  438.61
  4381.5  440.29  4441.7  438.12  4461.7  439.48  4521.9  437.46  4722.4  437.01
  4782.5  434.21  4832.6  434.82  4857.6  432.28  4902.8  428.92  4922.8   430.7
  4931.2  429.49  4937.4  431.02    4952  428.03  4972.9  430.34  4987.5  427.42
  4995.1  423.41  5016.7   428.2  5137.7  429.44    5190  434.21  5195.1  432.71
  5205.1  433.38  5285.8  439.22  5477.1  442.46  5795.4  453.42  5831.5  454.91
#Mann= 7 ,-1 , 0
  4248.1     .05       0  4857.6     .16       0  4972.9     .12       0
  5016.7     .16       0  5205.1     .16       0  5477.1     .05       0
  5795.4     .16       0
#XS Ineff= 2 , 0
                         5191.02          434.81
Permanent Ineff=
       F       F
Bank Sta=4972.9,5016.7
XS Rating Curve= 0 ,0
Exp/Cntr=0.3,0.1

Type RM Length L Ch R = 1 ,24231   ,544,544,544
BEGIN DESCRIPTION:
UNT065 IN CCTC 33.0
END DESCRIPTION:
XS GIS Cut Line= 3
      3501204.86     10638520.64      3501710.07     10638583.14
      3502651.16     10638094.39
#Sta/Elev= 30
  4300.3  440.28  4414.9   438.2  4607.4  437.64    4663  435.92  4728.1  435.78
  4820.1  433.45  4853.9  431.26  4892.5  430.67    4899   428.3    4909  427.81
  4914.6  428.78  4921.5  426.58  4975.4   426.8  5002.9  422.37  5011.7  425.08
  5019.6  423.97  5025.2  425.85  5041.7  425.97  5047.3  424.87  5063.8  427.73
  5069.5  426.89  5079.3  429.33  5091.6   429.1  5124.4  432.45    5285  432.92
  5367.8  435.14  5607.1  437.37  5710.3  440.18  5738.2  442.58  5869.8  444.97
#Mann= 7 ,-1 , 0
  4300.3     .05       0  4728.1     .16       0  4820.1     .16       0
  4975.4     .12       0  5025.2     .16       0    5285     .16       0
  5607.1     .05       0
Bank Sta=4975.4,5025.2
XS Rating Curve= 0 ,0
Exp/Cntr=0.3,0.1

Type RM Length L Ch R = 1 ,23687   ,276,276,276
BEGIN DESCRIPTION:
UNT065 IN CCTC 32.0
END DESCRIPTION:
XS GIS Cut Line= 4
      3501053.83     10638661.27      3501840.28     10639036.26
      3502121.53     10638973.76      3502714.37      10638224.9
#Sta/Elev= 30
  3983.4  442.16  4189.6  438.46  4225.3  438.25  4284.3  436.81  4394.2  434.51
  4577.9  432.53  4698.8  429.46  4820.7  429.09  4859.4  432.23  4884.7  431.48
  4902.9  425.91  4911.2  426.59  4951.6  423.04  4987.2   423.6  4995.1  421.61
  4997.2  419.12    5000  418.62  5017.9  423.87  5028.1  426.96  5038.4  428.03
  5087.3  426.32  5135.9  426.85  5158.8   428.9    5186  428.06  5236.6  428.99
  5314.2  427.56  5386.4   431.2  5649.2  433.04  5850.5  437.23  6097.9  444.25
#Mann= 10 ,-1 , 0
  3983.4     .05       0  4189.6      .1       0  4225.3     .05       0
  4284.3      .1       0  4394.2     .12       0  4911.2     .16       0
  4987.2     .12       0  5017.9     .16       0    5186     .16       0
  5850.5     .05       0
#XS Ineff= 2 , 0
         4860.23  433.06 5022.16          429.61
Permanent Ineff=
       F       F
Bank Sta=4987.2,5017.9
XS Rating Curve= 0 ,0
Exp/Cntr=0.3,0.1

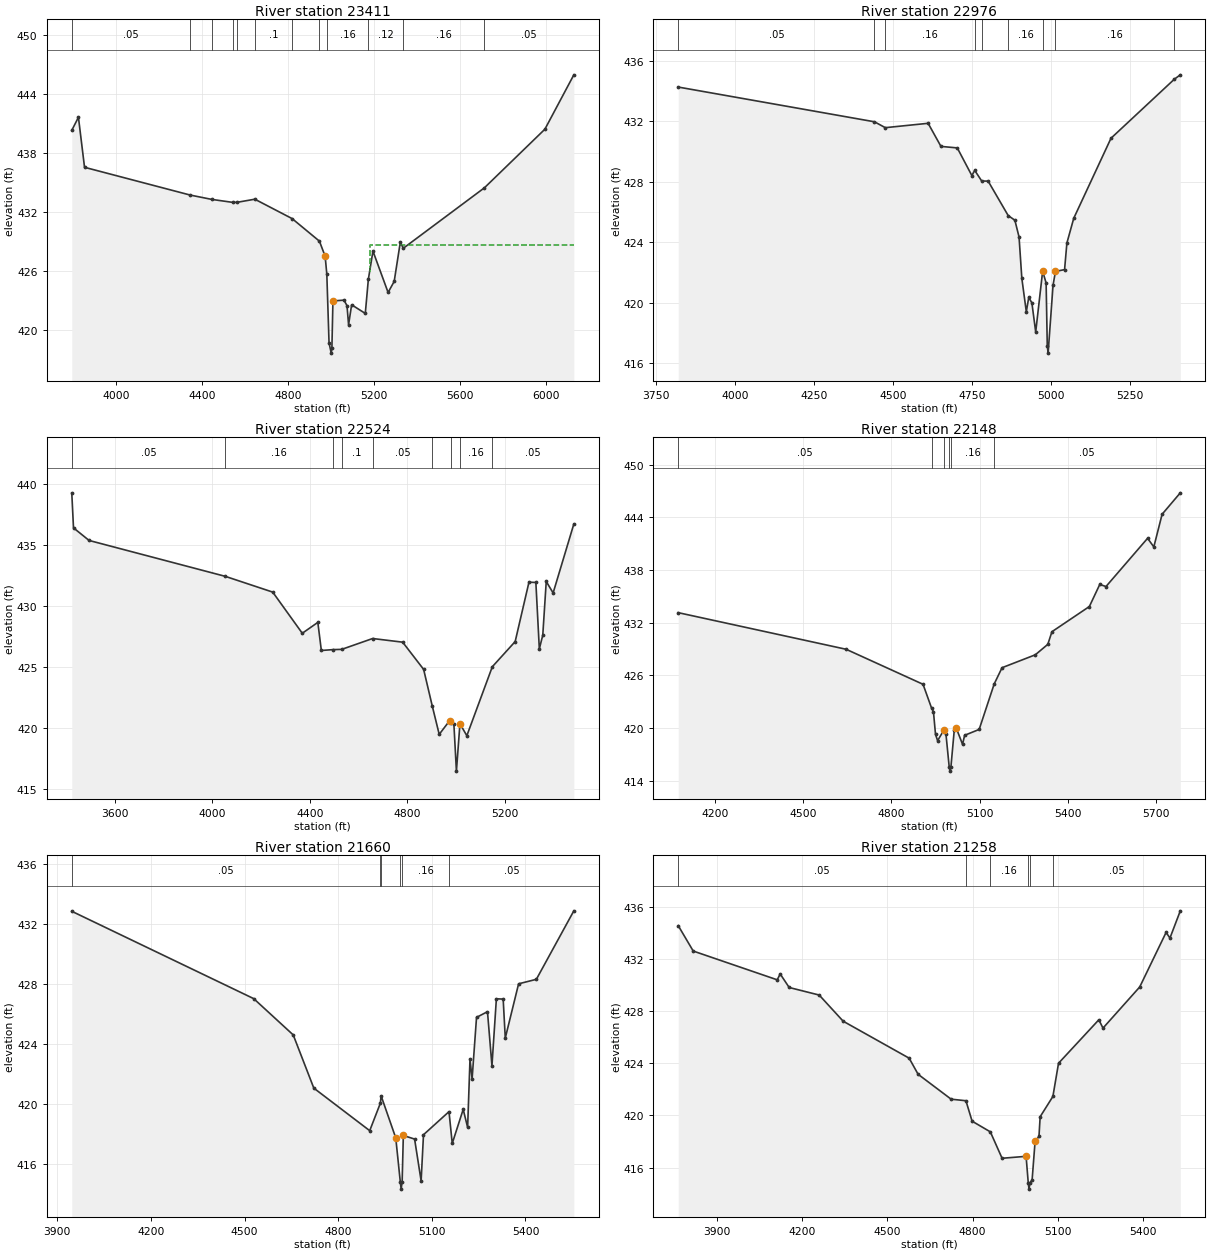
Type RM Length L Ch R = 1 ,23411   ,435,435,435
BEGIN DESCRIPTION:
UNT065 IN CCTC 31.0
END DESCRIPTION:
XS GIS Cut Line= 3
       3501899.6     10640310.22      3502199.61     10639110.19
      3502949.58     10638310.22
#Sta/Elev= 30
  3794.8  440.32  3825.8  441.65  3854.1  436.57  4345.3  433.75  4445.4  433.31
  4545.5     433  4564.5  433.02  4645.6  433.33  4818.9  431.36  4945.8  429.07
  4972.5  427.53  4980.2  425.71  4990.5  418.76  5000.6   417.7  5003.8   418.2
  5008.6     423  5059.9  423.08    5074  422.52  5081.3  420.58  5095.5  422.61
    5159  421.73  5173.2  425.19  5194.6  428.06    5265  423.86  5293.3  424.98
  5321.7  428.96  5335.8  428.35  5712.8  434.49  5993.8  440.44  6128.3  445.96
#Mann= 12 ,-1 , 0
  3794.8     .05       0  4345.3     .16       0  4445.4     .05       0
  4545.5      .1       0  4564.5     .16       0  4645.6      .1       0
  4818.9     .16       0  4945.8     .12       0  4980.2     .16       0
  5173.2     .12       0  5335.8     .16       0  5712.8     .05       0
#XS Ineff= 2 , 0
                         5178.98          428.71
Permanent Ineff=
       F       F
Bank Sta=4972.5,5008.6
XS Rating Curve= 0 ,0
Exp/Cntr=0.3,0.1

Type RM Length L Ch R = 1 ,22976   ,452,452,452
BEGIN DESCRIPTION:
UNT065 IN CCTC 30.0
END DESCRIPTION:
XS GIS Cut Line= 3
      3502099.61     10640060.18      3502599.61     10638960.19
      3502749.61     10638610.18
#Sta/Elev= 30
  3820.7  434.28  4441.8  431.98  4476.1  431.59  4611.6  431.88  4652.2  430.35
  4703.9  430.25    4750  428.42  4759.2  428.76  4781.1  428.06  4801.6  428.05
    4865  425.77  4886.2  425.46  4899.4  424.35  4908.2  421.61  4922.4   419.4
  4930.1  420.35    4940  419.99  4952.1  418.06  4974.1  422.09  4985.1   421.3
  4988.7  417.16  4991.4  416.66    5007  421.16  5014.7  422.07  5043.5  422.19
  5050.8  423.95  5072.5  425.59  5190.4  430.89  5390.9   434.8  5409.8  435.09
#Mann= 9 ,-1 , 0
  3820.7     .05       0  4441.8      .1       0  4476.1     .16       0
  4759.2     .12       0  4781.1      .1       0    4865     .16       0
  4974.1     .12       0  5014.7     .16       0  5390.9     .05       0
Bank Sta=4974.1,5014.7
XS Rating Curve= 0 ,0
Exp/Cntr=0.3,0.1

Type RM Length L Ch R = 1 ,22524   ,376,376,376
BEGIN DESCRIPTION:
UNT065 IN CCTC 29.0
END DESCRIPTION:
XS GIS Cut Line= 3
      3501999.63     10640260.17      3502999.61     10639060.19
      3503349.61     10638710.19
#Sta/Elev= 30
  3424.9  439.25    3432  436.38  3495.8  435.35    4054  432.41  4248.2  431.12
  4369.3  427.75    4433  428.64  4447.4  426.34  4495.3  426.41  4530.7  426.43
  4657.6  427.32  4780.6  427.02  4866.5  424.79  4901.4  421.83  4930.3  419.47
  4973.3   420.6  4979.8  420.41  4990.5  420.29  5000.8  416.46  5015.2  420.34
  5043.5  419.36  5147.9  425.01  5241.5  427.07    5298  431.93  5326.3  431.91
  5340.5  426.47  5354.6  427.59  5368.8  431.99    5397  431.05  5481.9   436.7
#Mann= 9 ,-1 , 0
  3424.9     .05       0    4054     .16       0  4495.3     .05       0
  4530.7      .1       0  4657.6     .05       0  4901.4     .16       0
  4979.8     .12       0  5015.2     .16       0  5147.9     .05       0
Bank Sta=4973.3,5015.2
XS Rating Curve= 0 ,0
Exp/Cntr=0.3,0.1

Type RM Length L Ch R = 1 ,22148   ,488,488,488
BEGIN DESCRIPTION:
UNT065 IN CCTC 28.0
END DESCRIPTION:
XS GIS Cut Line= 2
      3502642.02     10639940.02      3503855.96     10638739.09
#Sta/Elev= 30
  4074.7  433.13  4645.7  428.96  4907.3  424.97  4936.1  422.28  4942.7  421.85
  4949.7  419.27  4956.8  418.55  4977.5  419.72    4978  419.78  4985.1  419.35
  4996.2  415.58    4999  415.08  5002.2  415.58  5013.4  419.72  5020.4  419.97
  5041.7  418.13  5048.7  419.16  5098.2  419.83  5149.3  425.01    5176  426.86
  5289.1  428.33  5331.6  429.52  5345.7  430.96    5473  433.83  5508.3  436.34
  5529.6  436.11    5671   441.6  5692.2  440.62  5720.4  444.34  5782.3  446.78
#Mann= 6 ,-1 , 0
  4074.7     .05       0  4936.1     .12       0  4977.5     .16       0
  4996.2     .07       0  5002.2     .16       0  5149.3     .05       0
Bank Sta=4978,5020.4
XS Rating Curve= 0 ,0
Exp/Cntr=0.3,0.1

Type RM Length L Ch R = 1 ,21660   ,402,402,402
BEGIN DESCRIPTION:
UNT065 IN CCTC 27.0
END DESCRIPTION:
XS GIS Cut Line= 3
      3502649.57     10640010.21      3503649.61     10639610.19
      3504049.62     10639260.18
#Sta/Elev= 30
  3946.4  432.84  4529.4  427.01  4655.9  424.59  4721.9  421.04    4901   418.2
  4935.2  420.04  4937.4  420.53  4984.4  417.72  4998.9   414.8  5001.7   414.3
  5004.9   414.8  5008.7  417.88  5044.8  417.64  5065.7  414.85  5073.3  417.93
    5155  419.47  5165.4  417.35  5200.5  419.62  5214.7  418.42  5222.3  422.98
    5229  421.65  5243.2  425.76  5278.3  426.14  5292.6  422.53  5306.8     427
  5328.6  426.98  5335.3  424.38    5378     428  5434.9   428.3    5555  432.87
#Mann= 6 ,-1 , 0
  3946.4     .05       0  4935.2     .12       0  4937.4     .16       0
  4998.9     .07       0  5004.9     .16       0    5155     .05       0
Bank Sta=4984.4,5008.7
XS Rating Curve= 0 ,0
Exp/Cntr=0.3,0.1

Type RM Length L Ch R = 1 ,21258   ,159,159,159
BEGIN DESCRIPTION:
UNT065 IN CCTC 26.0
END DESCRIPTION:
XS GIS Cut Line= 3
      3502699.58      10640210.2      3503899.61     10639810.19
      3504199.58     10639410.22
#Sta/Elev= 30
  3765.3  434.58    3818  432.63  4113.2  430.42  4123.7  430.87  4155.3  429.83
  4260.8  429.25  4345.1  427.24    4577   424.4  4608.6  423.16  4724.6  421.25
  4776.6  421.13  4798.3  419.56  4862.4  418.74  4903.7  416.71  4988.1  416.86
  4995.6  414.84  4998.4  414.34  5001.6  414.84  5009.2  415.03  5019.7     418
  5033.4  418.39  5037.5   419.9  5082.3  421.46  5102.1  424.01  5243.8  427.35
  5258.4  426.71  5387.5  429.87  5480.2  434.06  5493.8  433.63  5530.2  435.72
#Mann= 6 ,-1 , 0
  3765.3     .05       0  4776.6     .12       0  4862.4     .16       0
  4995.6     .07       0  5001.6     .16       0  5082.3     .05       0
Bank Sta=4988.1,5019.7
XS Rating Curve= 0 ,0
Exp/Cntr=0.3,0.1

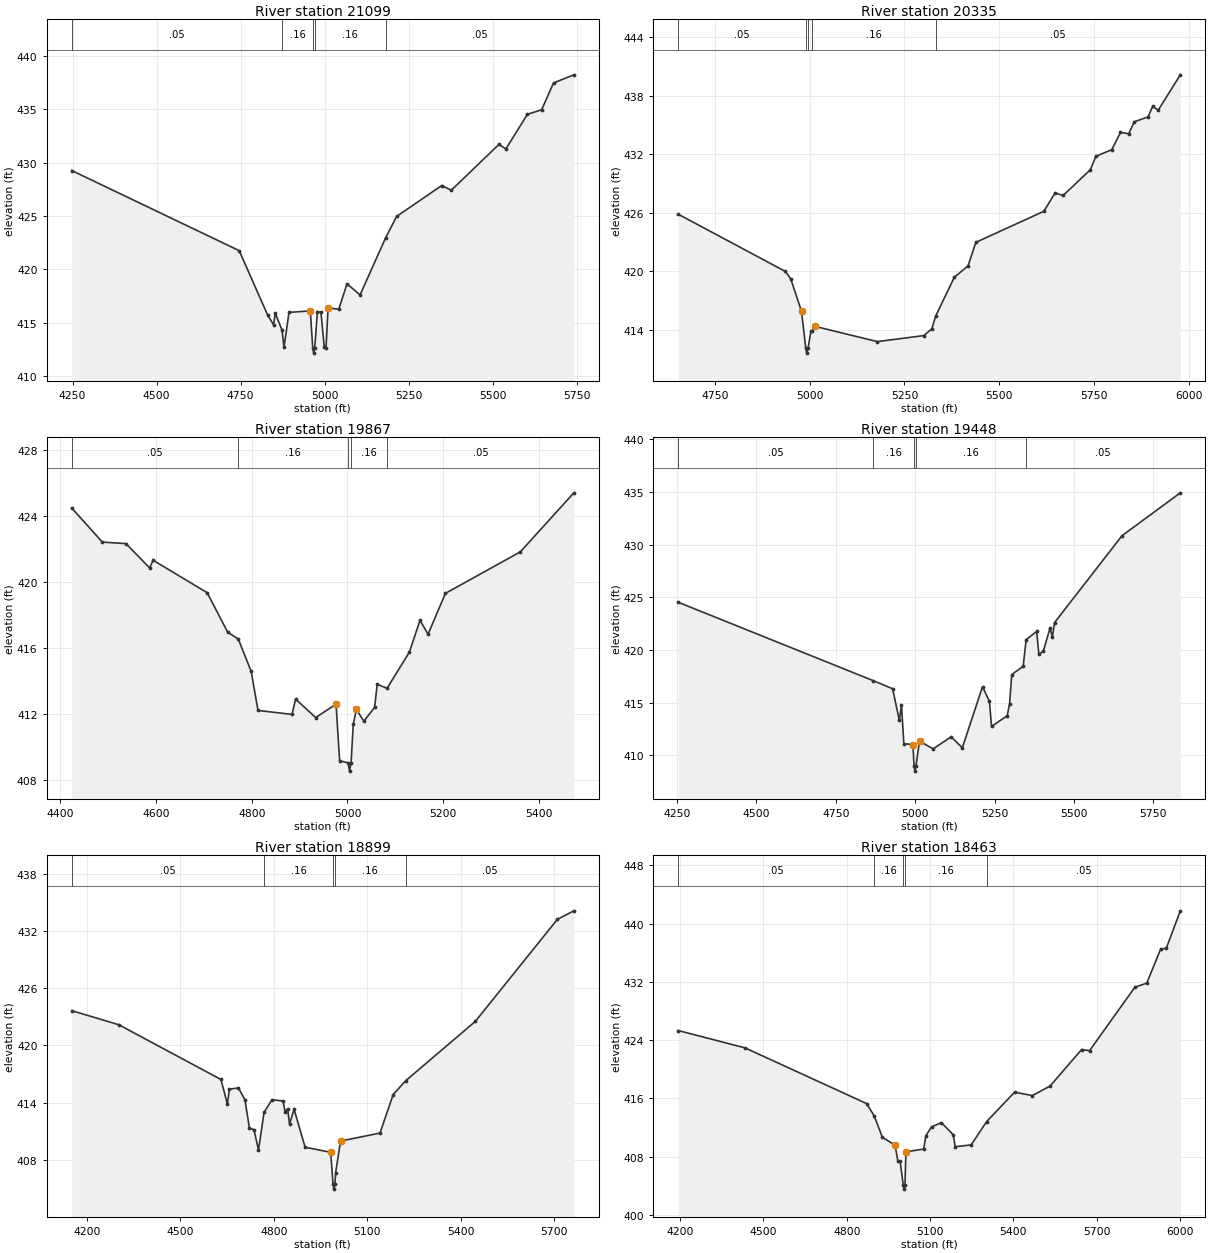
Type RM Length L Ch R = 1 ,21099   ,764,764,764
BEGIN DESCRIPTION:
UNT065 IN CCTC 25.0
END DESCRIPTION:
XS GIS Cut Line= 3
      3503158.54      10640220.8       3504047.4     10639915.25
      3504449.17     10639534.26
#Sta/Elev= 30
  4247.7  429.25  4745.8  421.76  4830.4  415.74  4847.9  414.83  4853.1  415.92
  4873.4   414.3  4879.1  412.71  4893.9  415.99  4957.3  416.13  4964.5  412.68
  4967.3  412.18  4970.5  412.68  4978.5  416.06    4989  415.99  4998.8  412.75
  5004.1  412.68  5010.2  416.42  5041.9  416.28  5066.5  418.66  5105.3  417.62
  5181.5  422.97    5214  424.96  5348.3  427.85  5376.7  427.41  5518.2  431.69
  5539.3  431.28  5603.2  434.51  5645.4  434.93  5680.9  437.44  5741.3   438.2
#Mann= 5 ,-1 , 0
  4247.7     .05       0  4873.4     .16       0  4964.5     .07       0
  4970.5     .16       0  5181.5     .05       0
Bank Sta=4957.3,5010.2
XS Rating Curve= 0 ,0
Exp/Cntr=0.3,0.1

Type RM Length L Ch R = 1 ,20335   ,468,468,468
BEGIN DESCRIPTION:
UNT065 IN CCTC 24.0
END DESCRIPTION:
XS GIS Cut Line= 3
      3503799.63     10640810.17      3504049.61     10640560.19
      3504599.64     10639760.15
#Sta/Elev= 30
  4653.2  425.86    4936  419.99  4950.2  419.21  4978.4   415.9  4989.6  412.12
  4992.3  411.62  4995.6  412.12  5003.2  413.85  5007.2  413.85  5014.2  414.36
  5178.6   412.8    5301  413.42  5322.2  414.12  5332.3  415.42  5381.5   419.4
  5417.4  420.55  5438.4  422.98  5617.6  426.16  5647.4  428.05  5668.4  427.78
  5740.1  430.41    5755   431.8  5796.9  432.48  5819.8  434.25  5841.6  434.11
  5856.2  435.34  5892.3  435.83  5904.7  436.91  5919.4  436.53  5977.6  440.15
#Mann= 5 ,-1 , 0
  4653.2     .05       0  4989.6    .035       0  4995.6     .05       0
  5007.2     .16       0  5332.3     .05       0
Bank Sta=4978.4,5014.2
XS Rating Curve= 0 ,0
Exp/Cntr=0.3,0.1

Type RM Length L Ch R = 1 ,19867   ,419,419,419
BEGIN DESCRIPTION:
UNT065 IN CCTC 23.0
END DESCRIPTION:
XS GIS Cut Line= 3
      3504049.62     10641060.17      3504449.61     10640610.19
      3504649.62     10640210.16
#Sta/Elev= 30
  4423.8  424.47  4487.7  422.41  4537.1  422.32  4586.4  420.85  4593.9  421.31
  4706.8  419.35  4749.5  416.97  4771.9  416.54  4798.8  414.59    4813  412.23
  4884.1  411.99  4891.6  412.92  4933.5   411.8  4976.1  412.61  4983.6  409.19
  5001.5  409.06  5004.3  408.56  5007.5  409.06  5012.1   411.4  5018.7  412.29
  5034.2  411.58  5056.6  412.41  5062.2  413.81  5082.7  413.57  5129.3  415.75
  5151.6  417.68  5168.4  416.84  5204.7  419.31  5361.3  421.82  5473.1  425.39
#Mann= 5 ,-1 , 0
  4423.8     .05       0  4771.9     .16       0  5001.5     .07       0
  5007.5     .16       0  5082.7     .05       0
Bank Sta=4976.1,5018.7
XS Rating Curve= 0 ,0
Exp/Cntr=0.3,0.1

Type RM Length L Ch R = 1 ,19448   ,549,549,549
BEGIN DESCRIPTION:
UNT065 IN CCTC 22.0
END DESCRIPTION:
XS GIS Cut Line= 2
      3504213.18     10641446.13      3505259.23     10640261.19
#Sta/Elev= 30
  4254.3  424.52  4867.2  417.09  4929.2  416.31  4950.4  413.31    4957   414.8
  4964.6   411.1    4993  411.01  4996.7  408.99  4999.5  408.49  5002.7  408.99
  5013.9  411.34  5056.6   410.6  5113.5  411.75  5148.6   410.7  5212.2   416.5
    5234  415.11  5240.6  412.73    5290  413.75  5297.5   414.9  5304.2  417.66
  5340.2  418.44  5349.5  420.97  5382.7  421.75  5389.6  419.57  5403.8  419.89
  5424.7  422.07  5432.2  421.23  5438.9  422.59  5651.4  430.84  5834.9  434.91
#Mann= 5 ,-1 , 0
  4254.3     .05       0  4867.2     .16       0  4996.7     .07       0
  5002.7     .16       0  5349.5     .05       0
Bank Sta=4993,5013.9
XS Rating Curve= 0 ,0
Exp/Cntr=0.3,0.1

Type RM Length L Ch R = 1 ,18899   ,436,436,436
BEGIN DESCRIPTION:
UNT065 IN CCTC 21.0
END DESCRIPTION:
XS GIS Cut Line= 3
       3504549.6      10641810.2      3505049.61     10641160.19
       3505299.6     10640410.23
#Sta/Elev= 30
    4152  423.65  4302.5  422.18  4630.5  416.44  4651.3  413.86  4657.6  415.43
  4686.6  415.55  4707.4  414.32    4722  411.34  4736.5  411.18    4751  409.04
  4768.8     413  4794.5  414.31  4829.8  414.19  4836.1  413.06  4844.3  413.36
  4850.6  411.78  4865.1  413.32  4900.5  409.34  4982.6  408.81  4990.2  405.45
  4992.9  404.95  4996.2  405.45  4998.4  406.67  5014.2  409.99  5140.7  410.82
  5182.9  414.85  5223.3  416.31  5446.4  422.52  5709.9  433.22  5762.6  434.11
#Mann= 5 ,-1 , 0
    4152     .05       0  4768.8     .16       0  4990.2     .07       0
  4996.2     .16       0  5223.3     .05       0
Bank Sta=4982.6,5014.2
XS Rating Curve= 0 ,0
Exp/Cntr=0.3,0.1

Type RM Length L Ch R = 1 ,18463   ,499,499,499
BEGIN DESCRIPTION:
UNT065 IN CCTC 20.0
END DESCRIPTION:
XS GIS Cut Line= 3
      3504549.62     10641910.18      3505099.61     10641360.19
      3505899.62     10640710.18
#Sta/Elev= 30
    4193  425.32  4433.4  422.94  4871.8  415.29  4899.5  413.55  4928.4  410.66
    4974  409.58  4984.4  407.35  4992.4  407.36  5003.7  404.05  5006.5  403.55
  5009.7  404.05  5013.2  408.67  5077.1  409.05    5085  410.88  5105.8   412.1
    5141  412.68  5184.1  410.99  5190.6  409.37  5248.1  409.62  5303.9  412.82
  5404.7  416.86  5468.6  416.39  5532.5   417.7    5646  422.71  5674.8  422.56
  5837.8  431.26  5880.9  431.83  5930.5  436.47  5951.3  436.63  6001.6  441.75
#Mann= 5 ,-1 , 0
    4193     .05       0  4899.5     .16       0  5003.7     .07       0
  5009.7     .16       0  5303.9     .05       0
Bank Sta=4974,5013.2
XS Rating Curve= 0 ,0
Exp/Cntr=0.3,0.1

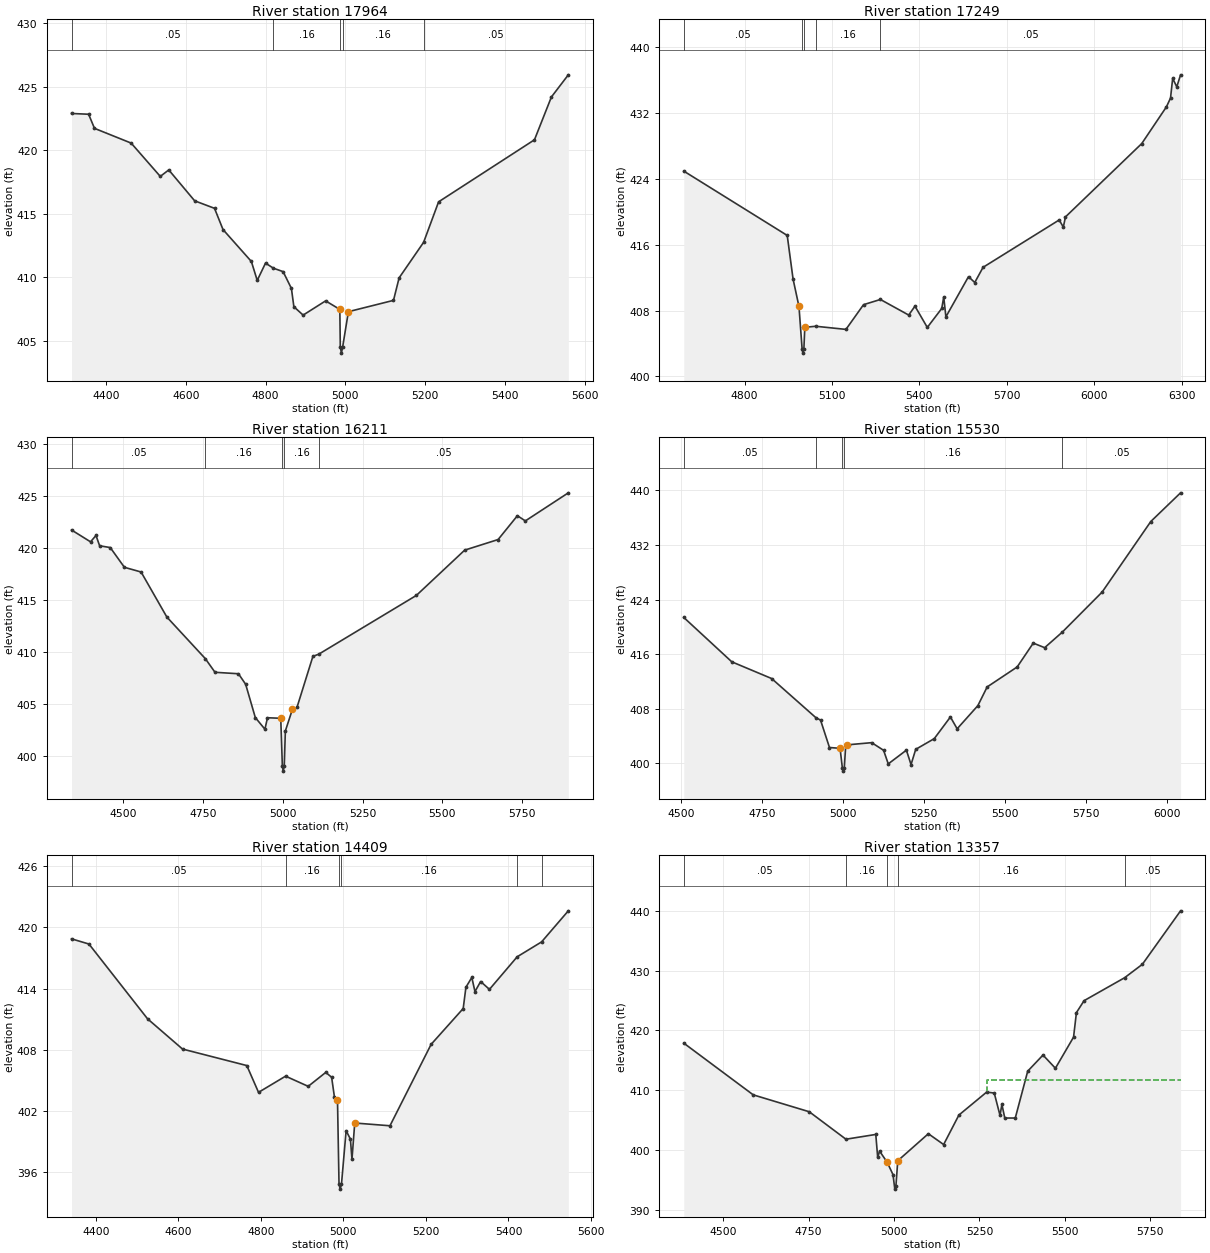
Type RM Length L Ch R = 1 ,17964   ,715,715,715
BEGIN DESCRIPTION:
UNT065 IN CCTC 19.0
END DESCRIPTION:
XS GIS Cut Line= 3
      3504849.58     10641860.21      3505399.61     10641460.19
      3505799.61     10641060.19
#Sta/Elev= 30
  4313.4   422.9  4356.3  422.84    4371  421.73    4463  420.57    4536  417.95
  4557.3  418.46  4622.2  416.03    4672  415.44  4693.3  413.77  4764.4  411.26
  4779.1  409.77  4799.9  411.13  4819.7  410.73    4844  410.46  4864.8  409.14
    4871   407.7  4894.2  407.04  4950.6  408.16  4986.2  407.49  4987.4  404.55
  4990.2  404.05  4993.4  404.55  5007.7  407.31  5120.8   408.2  5134.9  409.97
  5196.4  412.77  5233.9  415.95  5474.3  420.83  5516.8   424.2  5559.2  425.94
#Mann= 5 ,-1 , 0
  4313.4     .05       0  4819.7     .16       0  4987.4     .07       0
  4993.4     .16       0  5196.4     .05       0
Bank Sta=4986.2,5007.7
XS Rating Curve= 0 ,0
Exp/Cntr=0.3,0.1

Type RM Length L Ch R = 1 ,17249   ,1038,1038,1038
BEGIN DESCRIPTION:
UNT065 IN CCTC 18.0
END DESCRIPTION:
XS GIS Cut Line= 3
      3504807.12     10642004.37      3505550.17      10641914.1
      3506201.81     10641213.94
#Sta/Elev= 30
  4591.5  424.92  4946.6  417.11  4966.7  411.81  4986.9  408.49  4997.7  403.33
  5000.4  402.83  5003.7  403.33    5007  405.96  5044.3  406.09  5148.1  405.71
  5208.5  408.71  5266.4  409.34  5363.5  407.45    5385  408.53  5427.3  405.95
  5476.9  408.25  5483.7  409.65  5491.1  407.23  5568.7  412.11  5590.2   411.4
  5618.6  413.24    5880  418.99  5894.1  418.12  5901.5  419.36  6163.3  428.26
  6247.9  432.71    6262  433.78  6269.4  436.17  6283.5  435.14  6296.5   436.6
#Mann= 5 ,-1 , 0
  4591.5     .05       0  4997.7    .035       0  5003.7     .05       0
  5044.3     .16       0  5266.4     .05       0
Bank Sta=4986.9,5007
XS Rating Curve= 0 ,0
Exp/Cntr=0.3,0.1

Type RM Length L Ch R = 1 ,16211   ,681,681,681
BEGIN DESCRIPTION:
UNT065 IN CCTC 17.0
END DESCRIPTION:
XS GIS Cut Line= 4
      3505300.14     10642580.78      3505848.78     10642316.87
       3505959.9     10642177.99      3506230.72     10641455.78
#Sta/Elev= 30
  4337.2  421.69  4396.9  420.55    4414  421.16  4425.4  420.17  4458.7     420
  4503.1   418.1  4555.4  417.65  4636.2  413.32  4756.9  409.32  4787.2  408.01
  4860.7  407.87  4883.3  406.86  4913.6  403.66  4943.7  402.54  4951.8  403.64
  4993.4  403.59  4998.4  399.01  5001.1  398.51  5004.4  399.01  5007.8  402.37
  5030.2  404.47  5044.2  404.63  5094.2  409.54  5112.5  409.75  5418.7   415.4
  5570.1  419.75    5675  420.77  5735.5  423.06  5760.4  422.56  5895.2  425.26
#Mann= 5 ,-1 , 0
  4337.2     .05       0  4756.9     .16       0  4998.4     .07       0
  5004.4     .16       0  5112.5     .05       0
Bank Sta=4993.4,5030.2
XS Rating Curve= 0 ,0
Exp/Cntr=0.3,0.1

Type RM Length L Ch R = 1 ,15530   ,1121,1121,1121
BEGIN DESCRIPTION:
UNT065 IN CCTC 16.0
END DESCRIPTION:
XS GIS Cut Line= 3
      3505449.63     10642860.19      3505949.61     10642810.19
      3506749.57     10642160.22
#Sta/Elev= 30
  4507.8  421.38    4656  414.88  4779.1  412.43    4916  406.68  4929.9  406.35
  4957.5  402.33  4990.2  402.21  4997.2  399.37    5000  398.87  5003.2  399.37
  5007.8  402.71  5010.3  402.71  5087.8  403.04  5124.5  401.92  5138.9  399.93
  5194.9  401.94  5209.2  399.83  5223.6  402.06  5280.9  403.63  5330.7   406.8
  5351.5  405.07  5415.4  408.46  5444.1   411.2  5536.8  414.13  5586.4  417.62
  5621.6  416.95    5676  419.23    5799   425.1  5949.1  435.43    6041  439.63
#Mann= 5 ,-1 , 0
  4507.8     .05       0    4916     .16       0  4997.2     .07       0
  5003.2     .16       0    5676     .05       0
Bank Sta=4990.2,5010.3
XS Rating Curve= 0 ,0
Exp/Cntr=0.3,0.1

Type RM Length L Ch R = 1 ,14409   ,1052,1052,1052
BEGIN DESCRIPTION:
UNT065 IN CCTC 14.0
END DESCRIPTION:
XS GIS Cut Line= 3
      3505799.59     10643560.21      3506299.61     10643110.19
       3506699.6      10642760.2
#Sta/Elev= 30
  4340.9  418.88  4383.2  418.37  4525.2  411.03    4610  408.06  4765.8  406.44
  4794.2  403.81  4859.8   405.4  4914.6   404.4  4957.2  405.77  4971.4  405.29
  4978.1  403.38  4985.6  403.08  4989.3  394.81  4992.1  394.31  4995.3  394.81
  5006.5  400.05  5016.9  399.22  5020.7  397.24  5027.4   400.8  5112.8  400.53
  5212.5  408.52  5290.3  412.04  5296.9  414.13  5311.2  415.09  5318.8   413.7
  5332.5  414.69  5353.9  413.92  5421.2  417.12  5480.3  418.58  5545.1  421.63
#Mann= 6 ,-1 , 0
  4340.9     .05       0  4859.8     .16       0  4989.3     .07       0
  4995.3     .16       0  5421.2      .1       0  5480.3     .16       0
Bank Sta=4985.6,5027.4
XS Rating Curve= 0 ,0
Exp/Cntr=0.3,0.1

Type RM Length L Ch R = 1 ,13357   ,501,501,501
BEGIN DESCRIPTION:
UNT065 IN CCTC 12.0
END DESCRIPTION:
XS GIS Cut Line= 3
      3505999.58     10643810.19      3506549.61     10643710.19
      3507349.64     10643310.18
#Sta/Elev= 30
  4384.8  417.88  4588.1  409.21    4752  406.38  4859.3  401.78  4946.6  402.58
  4952.2  398.73  4957.8  399.79  4980.2  397.89  4996.9  395.86  5002.3  393.42
  5005.5  393.92  5010.9  398.17  5100.4   402.7  5145.1  400.89  5189.8  405.83
  5270.9  409.67  5293.2  409.52    5310  405.78  5315.6   407.6    5324  405.33
  5354.7  405.33  5391.1  413.18  5435.8  415.88  5472.1  413.67  5525.2  418.88
  5533.6  422.99    5556  424.99  5674.5  428.83  5726.5  431.08  5838.3  440.04
#Mann= 5 ,-1 , 0
  4384.8     .05       0  4859.3     .16       0  4980.2     .12       0
  5010.9     .16       0  5674.5     .05       0
#XS Ineff= 2 , 0
                         5271.82           411.7
Permanent Ineff=
       F       F
Bank Sta=4980.2,5010.9
XS Rating Curve= 0 ,0
Exp/Cntr=0.3,0.1

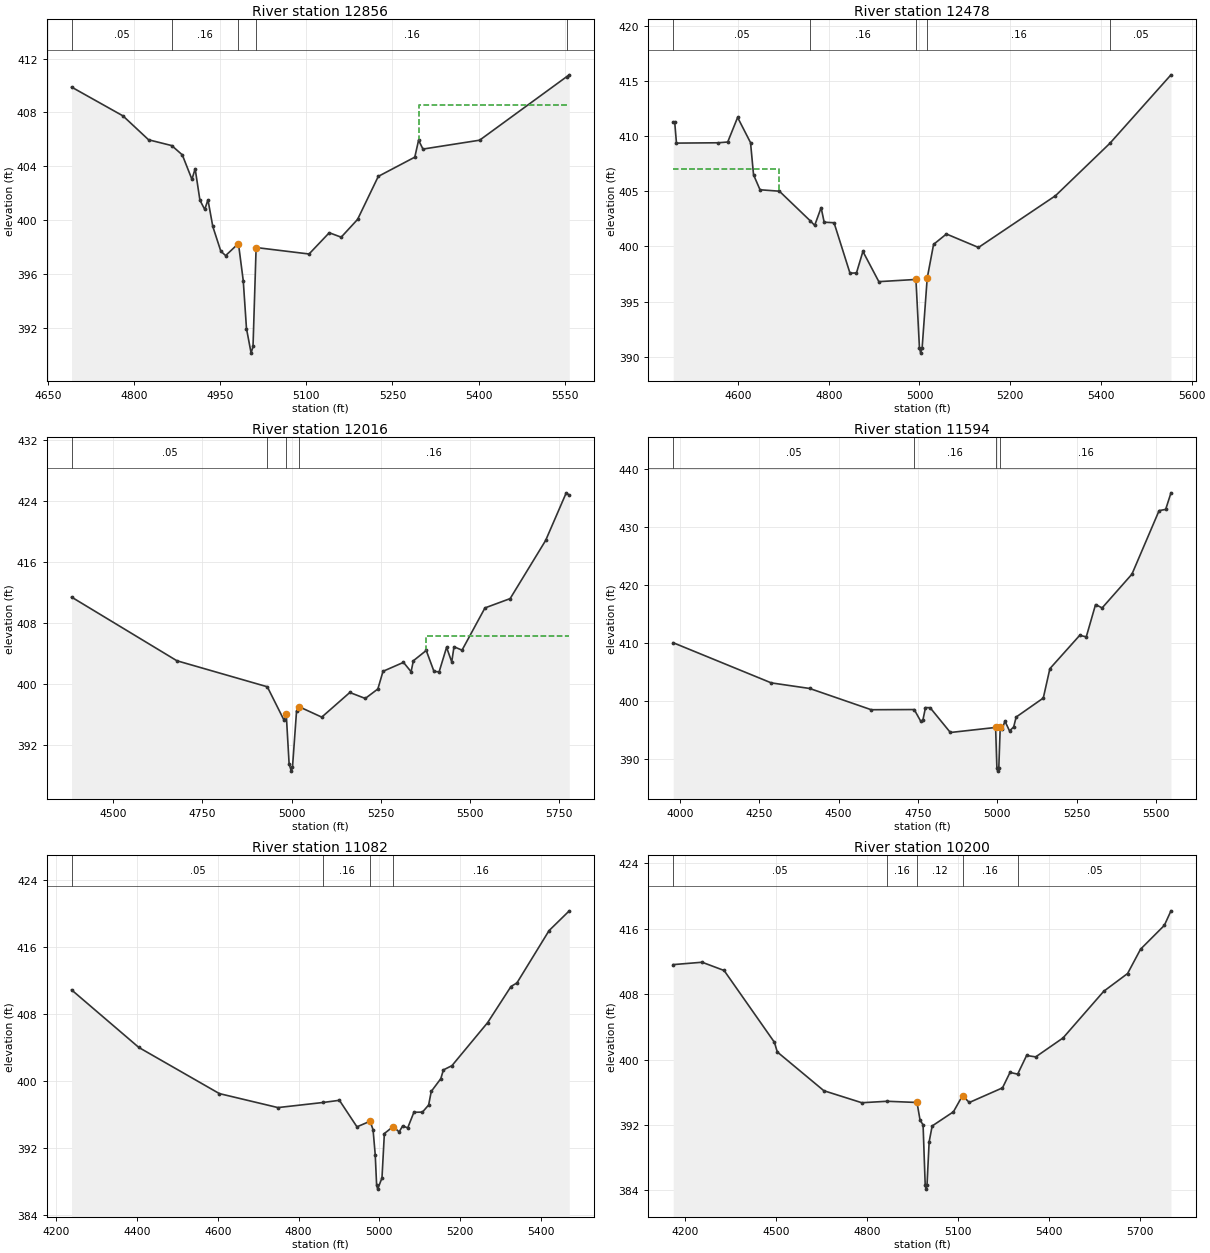
Type RM Length L Ch R = 1 ,12856   ,378,378,378
BEGIN DESCRIPTION:
UNT065 IN CCTC 11.0
END DESCRIPTION:
XS GIS Cut Line= 3
      3506499.59     10644360.22      3506649.61     10644060.19
      3507049.65     10643710.16
#Sta/Elev= 30
  4691.1  409.88  4780.6  407.74  4825.3  405.96  4865.6  405.53    4884  404.84
  4900.8  403.02  4906.4  403.81  4914.7  401.47  4923.1  400.78  4928.7   401.5
  4937.1  399.52  4951.1  397.68  4959.5  397.35  4981.8  398.25  4990.2  395.48
  4995.8  391.93  5003.9   390.1  5007.2   390.6  5012.6  397.95  5104.8  397.47
    5140  399.05  5160.8  398.72  5189.3  400.04  5225.4  403.24    5289  404.67
  5295.6  405.93  5303.2  405.27  5401.9  405.93  5553.5  410.65  5558.1  410.79
#Mann= 5 ,-1 , 0
  4691.1     .05       0  4865.6     .16       0  4981.8     .12       0
  5012.6     .16       0  5553.5     .05       0
#XS Ineff= 2 , 0
                         5296.59          408.52
Permanent Ineff=
       F       F
Bank Sta=4981.8,5012.6
XS Rating Curve= 0 ,0
Exp/Cntr=0.3,0.1

Type RM Length L Ch R = 1 ,12478   ,462,462,462
BEGIN DESCRIPTION:
UNT065 IN CCTC 10.0
END DESCRIPTION:
XS GIS Cut Line= 3
       3506599.6     10644610.19      3506949.61     10644210.19
      3507349.61     10643810.19
#Sta/Elev= 30
  4457.2  411.24  4460.5  411.24  4464.3  409.37  4556.4   409.4  4577.3  409.47
  4599.1   411.7  4627.6  409.41  4634.2   406.5  4648.5  405.14  4691.2  405.01
  4759.6  402.31    4769  401.91  4783.2  403.52  4789.9   402.2  4811.7  402.15
  4846.8  397.58  4861.1   397.6  4875.3  399.55  4910.4  396.81  4992.2  397.01
  4999.9  390.83  5002.6  390.33  5005.9  390.83    5017  397.12  5031.1  400.19
  5059.4  401.13  5130.1  399.91  5299.8   404.6  5419.7  409.35  5554.4  415.56
#Mann= 5 ,-1 , 0
  4457.2     .05       0  4759.6     .16       0  4992.2     .12       0
    5017     .16       0  5419.7     .05       0
#XS Ineff= 2 , 0
         4691.14  407.05
Permanent Ineff=
       F       F
Bank Sta=4992.2,5017
XS Rating Curve= 0 ,0
Exp/Cntr=0.3,0.1

Type RM Length L Ch R = 1 ,12016   ,422,422,422
BEGIN DESCRIPTION:
UNT065 IN CCTC 9.0
END DESCRIPTION:
XS GIS Cut Line= 2
       3506700.2     10644935.67       3507793.9     10644071.99
#Sta/Elev= 30
  4384.1  411.39  4679.1  403.04  4932.2  399.63  4978.9  395.26  4985.2  396.06
  4993.3  389.49  4999.4  388.57  5002.7  389.07  5014.1  396.47  5020.5  397.03
  5084.6  395.65  5163.2  398.88  5206.5   398.1  5241.7  399.34  5256.2  401.66
  5313.5  402.83  5334.8   401.6  5341.1  403.04  5377.2  404.39  5398.9  401.64
  5413.3  401.59  5434.1   404.8  5448.6  402.89  5454.9  404.88  5477.4  404.43
  5541.6  409.97  5612.1  411.19  5711.4  418.81  5769.2  425.06  5777.7  424.75
#Mann= 4 ,-1 , 0
  4384.1     .05       0  4932.2     .16       0  4985.2     .12       0
  5020.5     .16       0
#XS Ineff= 2 , 0
                         5377.27          406.23
Permanent Ineff=
       F       F
Bank Sta=4985.2,5020.5
XS Rating Curve= 0 ,0
Exp/Cntr=0.3,0.1

Type RM Length L Ch R = 1 ,11594   ,512,512,512
BEGIN DESCRIPTION:
UNT065 IN CCTC 8.0
END DESCRIPTION:
XS GIS Cut Line= 2
      3506739.26     10645291.58      3507997.18     10644354.65
#Sta/Elev= 30
  3978.9  410.02  4287.9  403.11  4408.8  402.15  4602.8  398.49  4738.3  398.52
  4759.2  396.47  4765.4  396.65  4773.8  398.86  4788.4  398.84  4852.2  394.57
  4994.8  395.44  4998.8  388.42  5001.5  387.92  5004.8  388.42  5009.4  395.58
  5015.6   395.1    5024  396.55  5038.6  394.84  5051.7  395.52  5059.5  397.23
    5145   400.5  5165.8  405.56  5259.7  411.29  5280.5  411.04  5309.7  416.59
  5330.5  416.02  5424.4  421.83  5509.9  432.76  5530.7  432.98  5547.4  435.83
#Mann= 4 ,-1 , 0
  3978.9     .05       0  4738.3     .16       0  4994.8     .12       0
  5009.4     .16       0
Bank Sta=4994.8,5009.4
XS Rating Curve= 0 ,0
Exp/Cntr=0.3,0.1

Type RM Length L Ch R = 1 ,11082   ,882,882,882
BEGIN DESCRIPTION:
UNT065 IN CCTC 7.0
END DESCRIPTION:
XS GIS Cut Line= 3
       3506949.6     10645360.19      3507649.61     10645060.19
      3508049.62     10644810.18
#Sta/Elev= 30
  4237.6  410.88  4404.4     404  4603.9  398.49    4749  396.82    4861  397.43
  4901.3  397.69  4944.8  394.52  4977.4  395.19  4984.7  394.17  4990.1  391.16
  4993.5  387.58  4996.2  387.08  5006.8  388.42  5012.7  393.72  5034.6  394.56
  5049.3  393.91  5058.1  394.64  5070.5  394.39  5085.9  396.26  5107.1  396.28
  5122.4  397.13  5128.9  398.75  5152.5  400.27    5159  401.32  5180.2  401.83
  5268.6  406.97  5326.4  411.28  5341.2  411.71  5420.8  417.96  5470.9  420.32
#Mann= 4 ,-1 , 0
  4237.6     .05       0    4861     .16       0  4977.4     .12       0
  5034.6     .16       0
Bank Sta=4977.4,5034.6
XS Rating Curve= 0 ,0
Exp/Cntr=0.3,0.1

Type RM Length L Ch R = 1 ,10200   ,660,660,660
BEGIN DESCRIPTION:
UNT065 IN CCTC 5.0
END DESCRIPTION:
XS GIS Cut Line= 4
       3506847.7     10645443.49      3507451.05     10645608.43
      3507798.27     10645595.41      3508423.28     10645356.69
#Sta/Elev= 30
  4160.1  411.62  4255.4  411.91  4327.9   410.9  4493.8  402.12  4503.4  400.93
    4657  396.19  4782.2  394.72  4865.8   394.9  4964.3  394.75  4974.3   392.6
  4984.3  392.01  4991.3  384.65    4994  384.15  4997.3  384.65  5004.3  389.94
  5014.3  391.88  5084.4  393.61  5114.4  395.59  5136.8  394.75  5246.3  396.54
  5271.1  398.43  5296.3  398.22  5325.8   400.5  5355.9  400.33  5446.1  402.65
  5580.4  408.36    5659  410.53  5701.8  413.51  5780.2  416.42  5802.1   418.2
#Mann= 5 ,-1 , 0
  4160.1     .05       0  4865.8     .16       0  4964.3     .12       0
  5114.4     .16       0  5296.3     .05       0
Bank Sta=4964.3,5114.4
XS Rating Curve= 0 ,0
Exp/Cntr=0.3,0.1