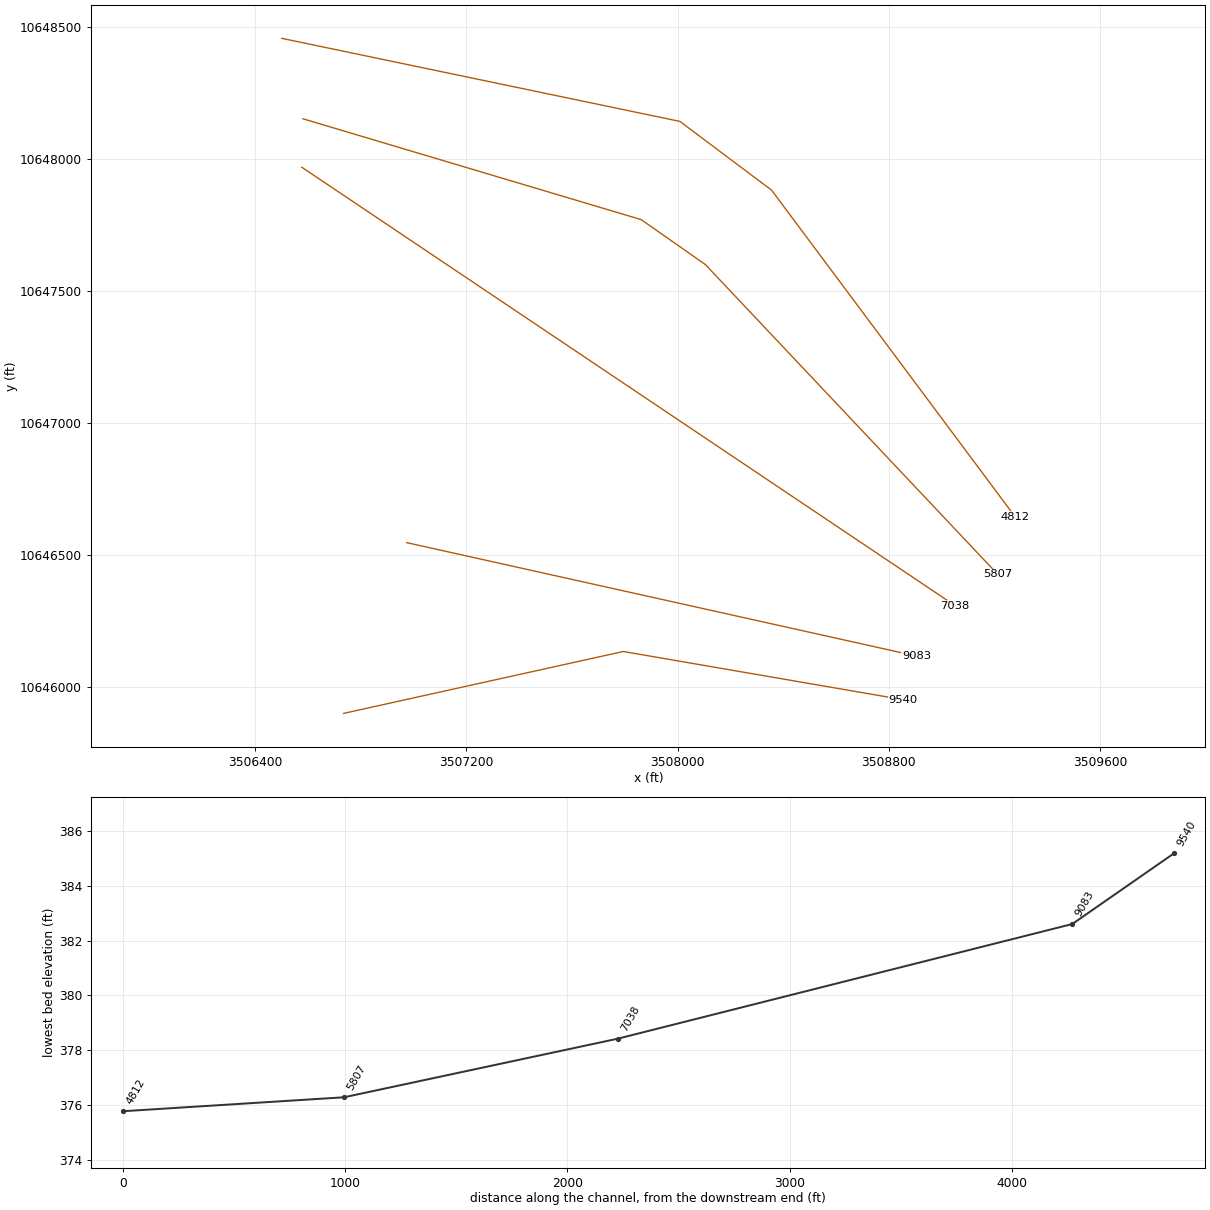
HEC-RAS study UNT065 IN CCTC.prj: UNT065 IN CCTC Base Level Engineering

--- UNT065 IN CCTC.g01 (geometry) --- (continued)

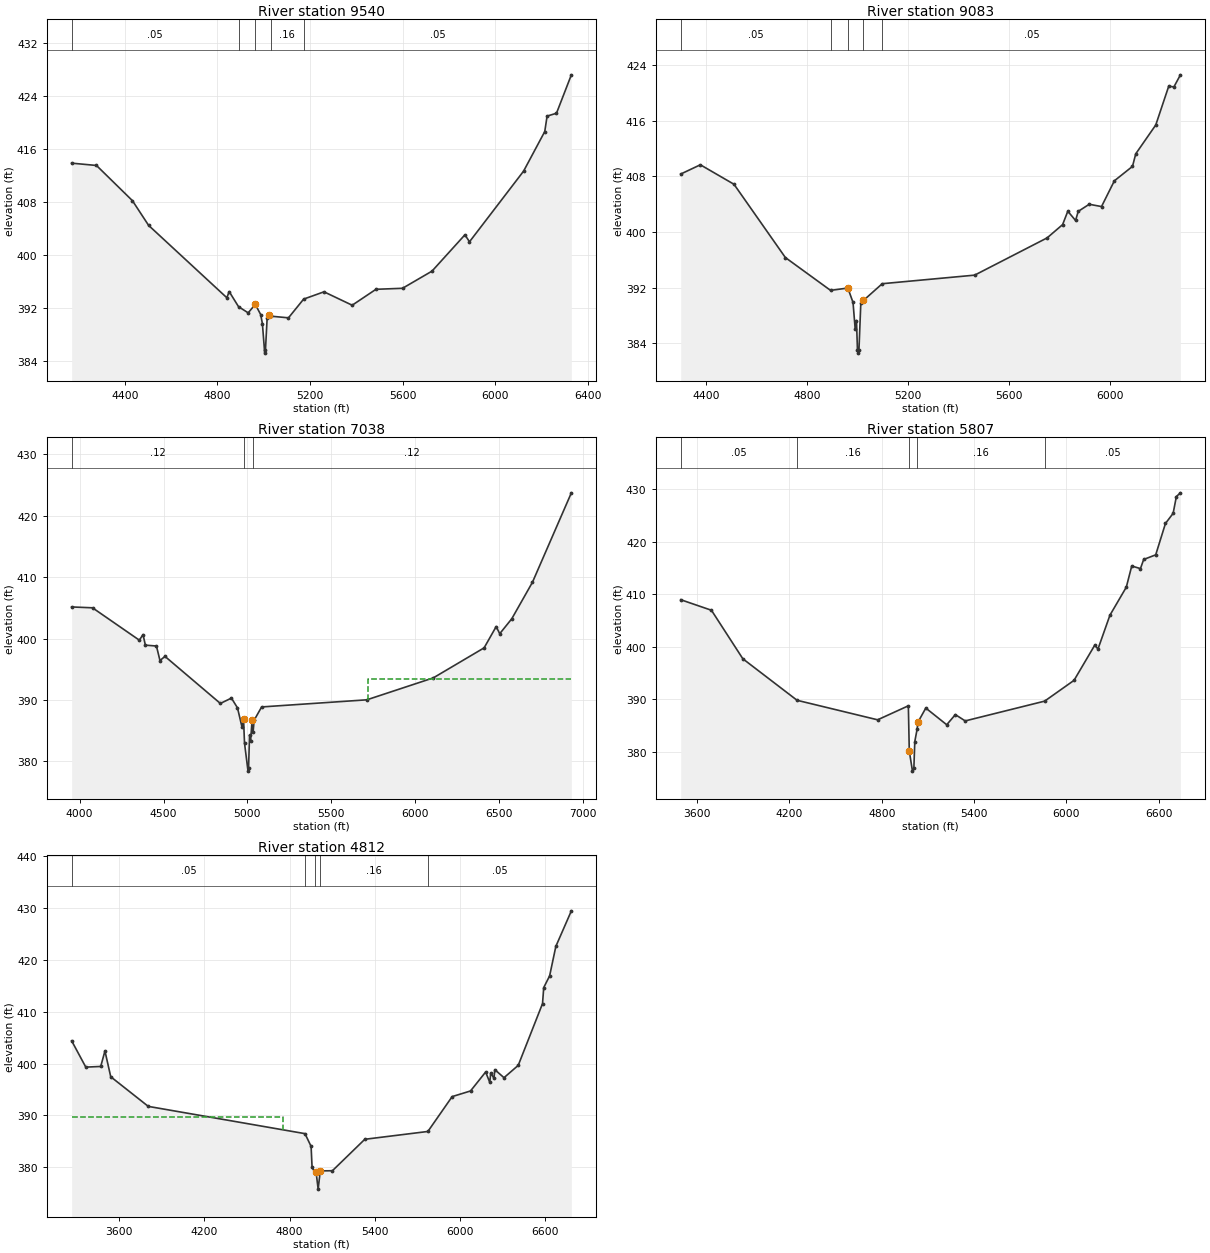
Type RM Length L Ch R = 1 ,9540    ,457,457,457
BEGIN DESCRIPTION:
UNT065 IN CCTC 4.0
END DESCRIPTION:
XS GIS Cut Line= 3
      3506734.87     10645899.22      3507793.93     10646133.61
      3508852.97     10645951.31
#Sta/Elev= 30
  4169.8  413.82  4277.1  413.47  4432.3  408.17  4502.4  404.44  4840.3  393.54
  4850.6  394.46  4890.9  392.19  4932.6  391.26  4963.3  392.54  4986.5  391.01
    4994  389.65    5004  385.19  5007.3  385.69  5014.5  390.46  5024.7  390.98
  5030.1  390.76  5106.7  390.51  5172.2  393.33  5260.2  394.43    5382  392.41
  5484.8  394.81  5599.5  394.96    5727  397.55  5869.1  403.02  5888.9  401.97
  6122.7  412.62  6214.1  418.58  6224.2  420.91  6264.8  421.34  6329.1  427.13
#Mann= 5 ,-1 , 0
  4169.8     .05       0  4890.9     .16       0  4963.3     .12       0
  5030.1     .16       0  5172.2     .05       0
Bank Sta=4963.3,5024.7
XS Rating Curve= 0 ,0
Exp/Cntr=0.3,0.1

Type RM Length L Ch R = 1 ,9083    ,2045,2045,2045
BEGIN DESCRIPTION:
Mapping XS c2c5c9fe
END DESCRIPTION:
XS GIS Cut Line= 2
      3506973.66     10646545.92      3508904.85     10646116.29
#Sta/Elev= 30
  4301.1  408.33  4378.9  409.66  4512.1  406.86  4715.4  396.34  4894.4  391.62
  4962.8  391.96  4983.3  389.89  4991.8   386.1    4997  387.29  5000.8  383.11
  5003.6  382.61  5006.8  383.11  5014.1  389.75  5024.3  390.17    5099  392.58
  5464.8  393.81  5751.7  399.16  5813.1  401.07  5833.6  402.99  5864.4  401.66
  5874.9  402.97  5918.4  403.99  5967.1  403.66    6018  407.36  6089.7  409.43
  6102.7  411.24  6181.9  415.38  6233.2  420.95  6253.6  420.84  6279.5  422.58
#Mann= 5 ,-1 , 0
  4301.1     .05       0  4894.4     .16       0  4962.8     .12       0
  5024.3     .16       0    5099     .05       0
Bank Sta=4962.8,5024.3
XS Rating Curve= 0 ,0
Exp/Cntr=0.3,0.1

Type RM Length L Ch R = 1 ,7038    ,1231,1231,1231
BEGIN DESCRIPTION:
UNT065 IN CCTC 2.0
END DESCRIPTION:
XS GIS Cut Line= 2
      3506576.28     10647967.84      3509050.19     10646307.71
#Sta/Elev= 30
  3952.4  405.15  4076.8  405.01  4355.9  399.74  4377.9  400.65  4391.9  398.93
  4457.9  398.79  4478.9  396.43  4508.9   397.1    4839  389.44    4905  390.31
  4941.1  388.72  4968.1  385.58  4977.1  386.93  4983.1  382.96  5003.9  378.42
  5007.1  378.92  5013.1  384.32  5019.1  383.29  5028.1  386.72  5034.1  384.75
  5040.3  386.71  5085.1  388.87  5712.3  390.03  6108.4   393.6  6411.5  398.49
  6483.5  401.96  6504.5  400.79  6576.5  403.23  6699.5  409.16  6931.7  423.73
#Mann= 3 ,-1 , 0
  3952.4     .12       0  4977.1      .1       0  5034.1     .12       0
#XS Ineff= 2 , 0
                         5717.33          393.43
Permanent Ineff=
       F       F
Bank Sta=4977.1,5028.1
XS Rating Curve= 0 ,0
Exp/Cntr=0.3,0.1

Type RM Length L Ch R = 1 ,5807    ,995,995,995
BEGIN DESCRIPTION:
Mapping XS 1b8e4ad8
END DESCRIPTION:
XS GIS Cut Line= 4
      3506580.55     10648151.43      3507861.77     10647769.49
      3508104.82     10647599.36      3509212.47     10646425.73
#Sta/Elev= 30
  3493.8  408.95  3693.5  406.94  3897.6  397.69    4250  389.78  4773.4  386.06
  4973.1  388.73  4979.2  380.11  4999.9  376.28  5008.9   376.8    5015  381.92
  5029.8  384.24  5035.9  385.63  5086.5   388.3  5222.4  385.12  5278.6  387.05
  5342.5  385.85  5858.8  389.62  6049.7  393.58  6184.4  400.28  6205.5  399.56
  6283.1     406  6389.5  411.34  6424.7  415.37  6481.4  414.88  6502.4  416.62
  6580.5   417.5    6644  423.49  6693.8  425.41  6714.8  428.61  6741.2  429.32
#Mann= 5 ,-1 , 0
  3493.8     .05       0    4250     .16       0  4979.2     .12       0
  5029.8     .16       0  5858.8     .05       0
Bank Sta=4979.2,5035.9
XS Rating Curve= 0 ,0
Exp/Cntr=0.3,0.1

Type RM Length L Ch R = 1 ,4812    ,0,0,0
BEGIN DESCRIPTION:
UNT065 IN CCTC 1.0
END DESCRIPTION:
XS GIS Cut Line= 4
      3506500.27     10648456.14      3508008.54     10648141.47
      3508355.76     10647881.05      3509277.62     10646644.67
#Sta/Elev= 30
  3266.5   404.4    3366  399.32  3471.1  399.45  3500.8  402.44  3541.6  397.46
  3805.9  391.74  4908.6  386.48  4951.7  384.02  4958.6  379.98  4980.9  378.85
  4987.1     379  5001.4  375.77  5016.3  379.29  5101.7  379.32  5329.7  385.39
  5773.6   386.9  5944.5  393.63  6073.8  394.72  6180.2  398.38  6209.4  396.36
  6215.6  398.17  6238.6  397.19  6244.8  398.83  6309.4  397.28  6409.5  399.66
  6580.5  411.58  6588.9  414.67  6630.5  416.94  6674.3  422.63  6783.5  429.49
#Mann= 5 ,-1 , 0
  3266.5     .05       0  4908.6     .16       0  4980.9     .12       0
  5016.3     .16       0  5773.6     .05       0
#XS Ineff= 2 , 0
         4754.55  389.75
Permanent Ineff=
       F       F
Bank Sta=4987.1,5016.3
XS Rating Curve= 0 ,0
Exp/Cntr=0.3,0.1

Chan Stop Cuts=-1
Use User Specified Reach Order=0
Composite Channel Slope=5