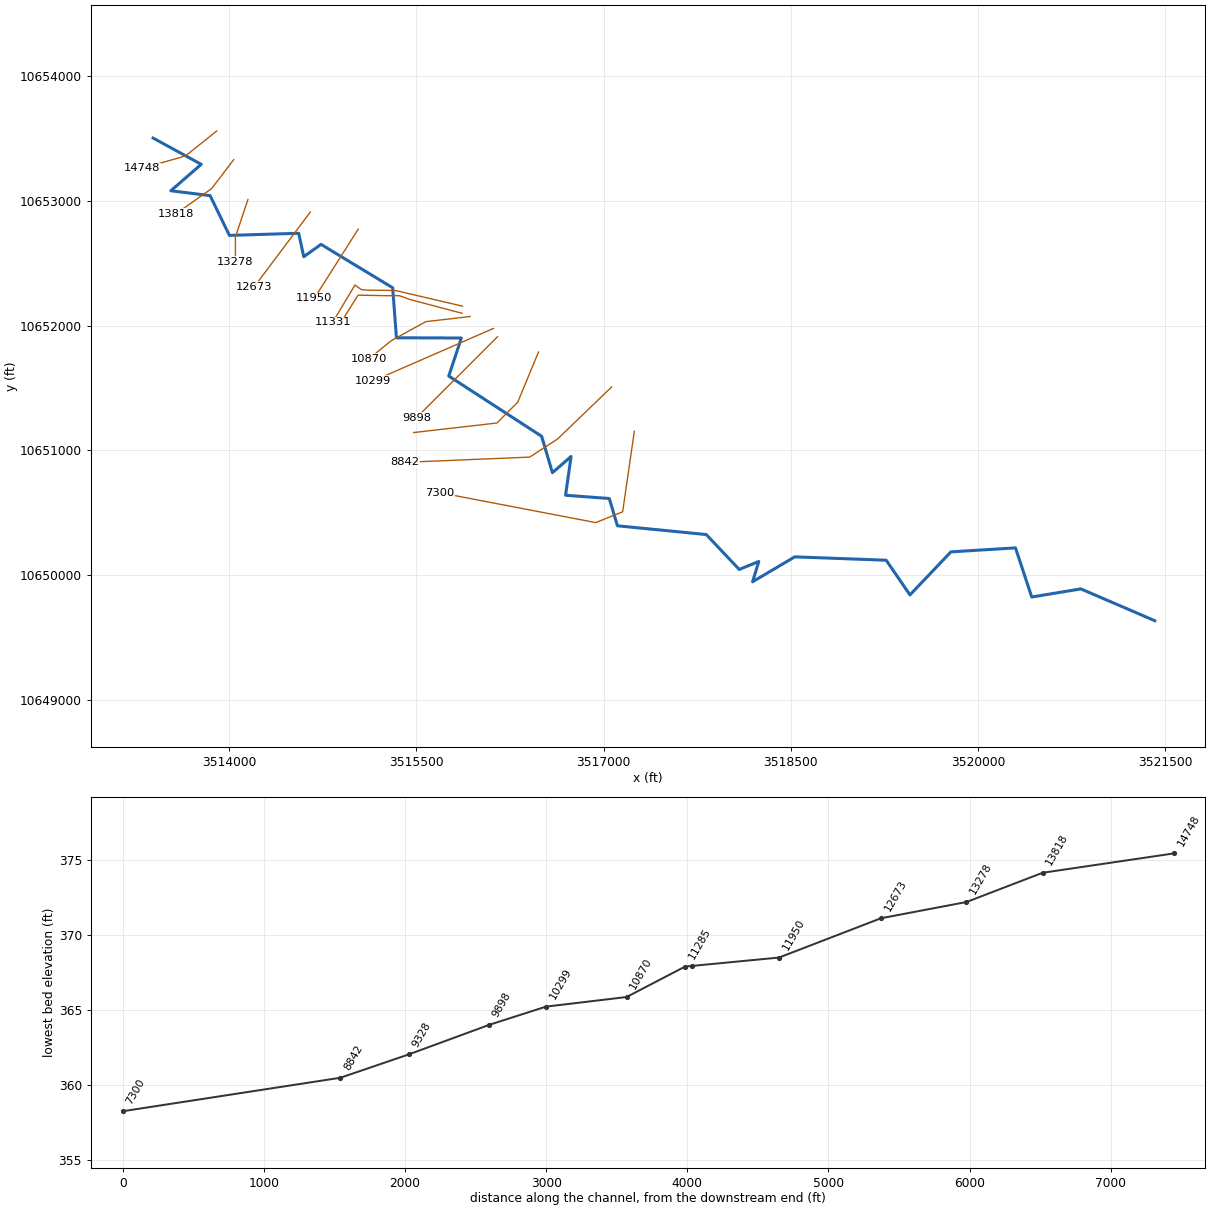
--- UNT068 IN CCTC.prj (project) ---

Proj Title=UNT068 IN CCTC Base Level Engineering
Current Plan=p01
Default Exp/Contr=0.3,0.1
English Units
Geom File=g01
Flow File=f01
Plan File=p01
Y Axis Title=Elevation
X Axis Title(PF)=Main Channel Distance
X Axis Title(XS)=Station
BEGIN DESCRIPTION:
UNT068 IN CCTC
END DESCRIPTION:
DSS Export Rating Curves= 0
DSS Export Rating Curve Sorted= 0
DSS Export Volume Flow Curves= 0
DXF OffsetX= 0
DXF OffsetY= 0
DXF ScaleX= 1
DXF ScaleY= 10

--- UNT068 IN CCTC.p01 (plan) ---

Plan Title=Multiple Run
Short Identifier=Multiple
Geom File=g01
Flow File=f01
Subcritical Flow
K Sum by GR= 0
Std Step Tol= 0.01
Critical Tol= 0.01
Num of Std Step Trials= 20
Max Error Tol= 0.3
Flow Tol Ratio= 0.001
Split Flow NTrial= 30
Split Flow Tol= 0.02
Split Flow Ratio= 0.02
Log Output Level= 0
Friction Slope Method= 1
Unsteady Friction Slope Method= 2
Unsteady Bridges Friction Slope Method= 1
Parabolic Critical Depth
Global Vel Dist=  1 , 1 , 1
Global Log Level= 0
CheckData=True
Encroach Param= -1, 0, 0, 0
BEGIN DESCRIPTION:
Multiple Run
END DESCRIPTION:

--- UNT068 IN CCTC.f01 (steady flow) ---

Flow Title=Multiple
Number of Profiles=7
Profile Names=10-year,25-year,50-year,1pct_min,100-year,1pct_plu,500-year
River Rch & RM= UNT068 IN CCTC,Reach-1,14748
    1675    2308    2830    2526    3416    4619    4966
Boundary for River Rch & Prof#=UNT068 IN CCTC,Reach-1,1
Up Type=0
Dn Type=3
Dn Slope=0.005
Boundary for River Rch & Prof#=UNT068 IN CCTC,Reach-1,2
Up Type=0
Dn Type=3
Dn Slope=0.005
Boundary for River Rch & Prof#=UNT068 IN CCTC,Reach-1,3
Up Type=0
Dn Type=3
Dn Slope=0.005
Boundary for River Rch & Prof#=UNT068 IN CCTC,Reach-1,4
Up Type=0
Dn Type=3
Dn Slope=0.005
Boundary for River Rch & Prof#=UNT068 IN CCTC,Reach-1,5
Up Type=0
Dn Type=3
Dn Slope=0.005
Boundary for River Rch & Prof#=UNT068 IN CCTC,Reach-1,6
Up Type=0
Dn Type=3
Dn Slope=0.005
Boundary for River Rch & Prof#=UNT068 IN CCTC,Reach-1,7
Up Type=0
Dn Type=3
Dn Slope=0.005

--- UNT068 IN CCTC.g01 (geometry) ---

Geom Title=Existing Conditions
Program Version=4.10

River Reach=UNT068 IN CCTC  ,Reach-1
Reach XY= 30
      3513390.07     10653503.73      3513775.75       10653293.
      3513532.25       10653081.      3513846.75       10653042.
       3514001.5       10652723.      3514556.75       10652740.
      3514597.25       10652552.      3514735.75       10652651.
      3515309.75       10652303.      3515339.75       10651902.
        3515860.       10651900.      3515759.25       10651595.
      3516503.25       10651112.      3516589.75       10650820.
      3516739.25       10650950.        3516695.       10650639.
       3517045.5       10650613.      3517110.75       10650394.
       3517822.5       10650324.       3518086.5       10650044.
       3518243.5       10650108.      3518193.25       10649945.
       3518531.5       10650145.      3519264.25       10650118.
      3519454.75       10649840.      3519782.75       10650185.
      3520300.25       10650217.       3520430.5       10649823.
        3520824.       10649888.      3521416.25       10649633.

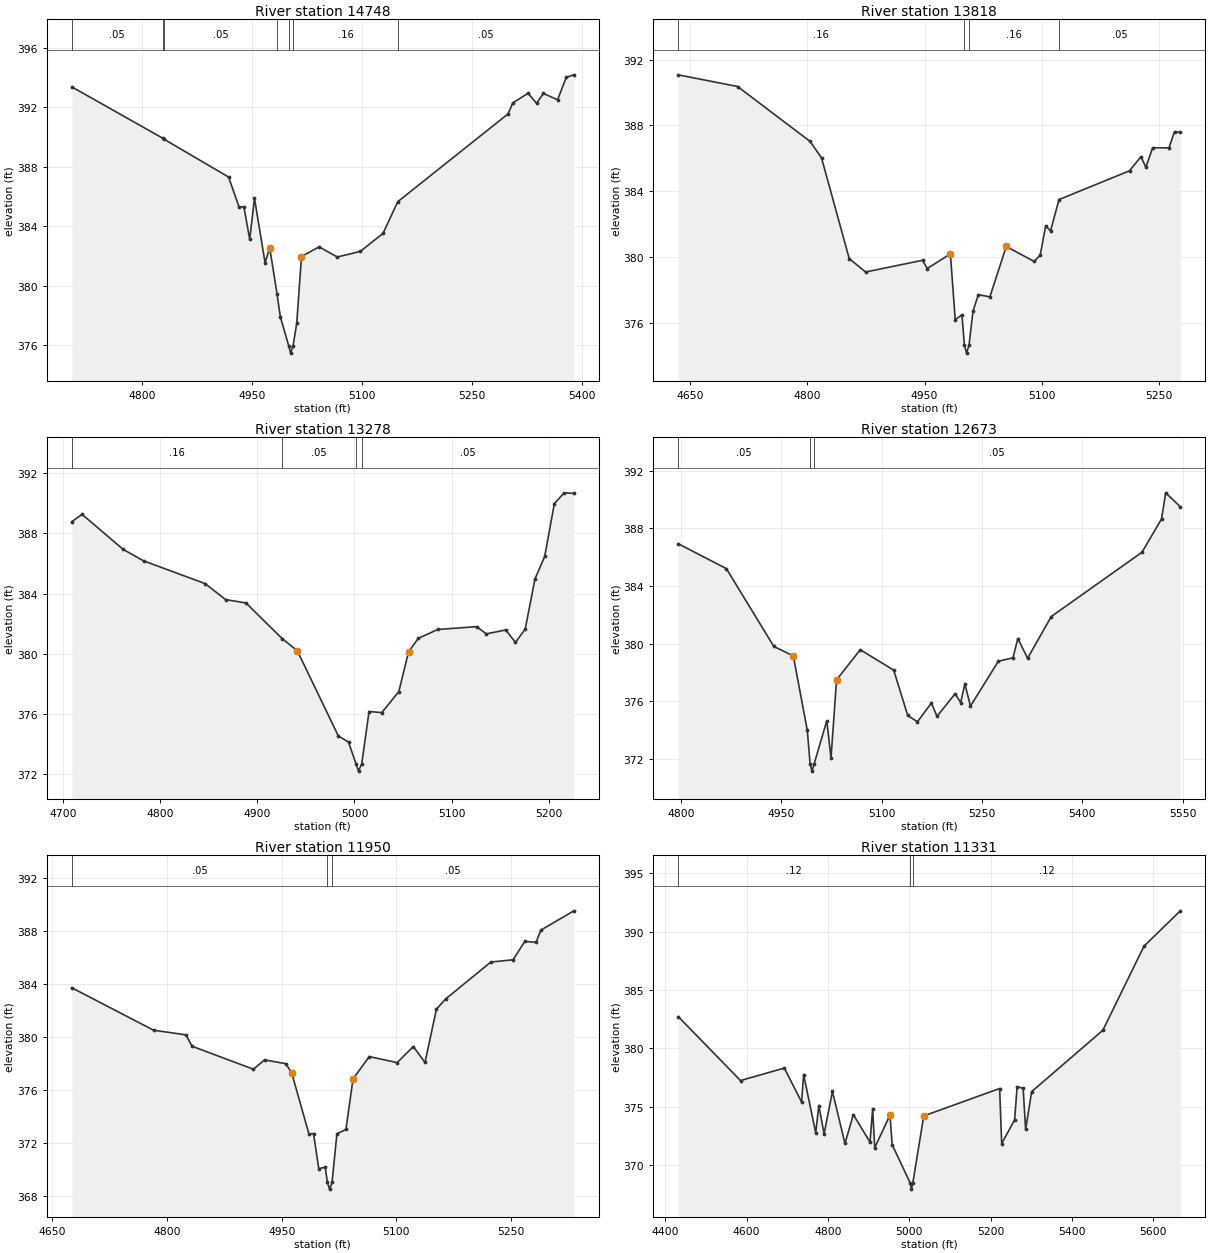
Type RM Length L Ch R = 1 ,14748   ,930,930,930
BEGIN DESCRIPTION:
UNT068 IN CCTC 14.0
END DESCRIPTION:
XS GIS Cut Line= 3
      3513899.63     10653560.21      3513649.61     10653360.19
       3513299.6     10653260.19
#Sta/Elev= 30
  4704.1  393.37  4827.9  389.92  4830.1  389.84  4917.8   387.3  4932.2  385.27
  4938.6  385.31  4946.6  383.11  4953.1  385.87  4967.5  381.54  4973.9  382.53
  4983.9  379.41  4988.3   377.9  4999.7  375.95  5002.4  375.45  5005.7  375.95
  5010.7  377.47  5017.1  381.95  5041.2   382.6  5065.9  381.92  5097.1  382.29
  5128.3  383.51  5148.3  385.64  5298.6  391.55  5305.1  392.29  5325.9  392.94
  5337.6  392.26  5346.7  392.93  5366.2   392.5  5377.9  394.01  5388.3  394.18
#Mann= 7 ,-1 , 0
  4704.1     .05       0  4827.9     .16       0  4830.1     .05       0
  4983.9     .16       0  4999.7     .07       0  5005.7     .16       0
  5148.3     .05       0
Bank Sta=4973.9,5017.1
XS Rating Curve= 0 ,0
Exp/Cntr=0.3,0.1

Type RM Length L Ch R = 1 ,13818   ,540,540,540
BEGIN DESCRIPTION:
UNT068 IN CCTC 13.0
END DESCRIPTION:
XS GIS Cut Line= 3
        3514036.     10653330.39      3513858.91     10653098.61
      3513573.56     10652896.27
#Sta/Elev= 30
  4635.3  391.07  4711.1  390.36  4803.9  387.02  4818.4  386.02  4853.8   379.9
  4874.7  379.09  4947.4   379.8  4953.5   379.3    4983  380.19  4989.2   376.2
  4997.8  376.48  5000.9  374.66  5003.7  374.16  5006.9  374.66  5011.9  376.71
  5018.7  377.71  5033.5  377.58  5054.4  380.64  5090.1  379.73  5097.8  380.12
  5104.8  381.89    5111  381.59  5121.8  383.49  5211.9  385.24  5226.6   386.1
  5232.8  385.45  5241.4  386.64  5262.3  386.63  5269.4  387.62  5276.8  387.58
#Mann= 4 ,-1 , 0
  4635.3     .16       0  5000.9     .07       0  5006.9     .16       0
  5121.8     .05       0
Bank Sta=4983,5054.4
XS Rating Curve= 0 ,0
Exp/Cntr=0.3,0.1

Type RM Length L Ch R = 1 ,13278   ,605,605,605
BEGIN DESCRIPTION:
UNT068 IN CCTC 12.0
END DESCRIPTION:
XS GIS Cut Line= 3
      3514149.62     10653010.21      3514049.61     10652710.19
      3514049.61     10652510.14
#Sta/Elev= 30
  4709.3  388.78  4719.9  389.27    4762  386.95  4783.1  386.18  4846.4  384.67
  4867.4  383.61  4888.5  383.38  4925.7  381.01  4941.2  380.21  4983.4  374.55
  4993.9  374.14  5001.5  372.71  5004.2  372.21  5007.5  372.71    5015  376.17
  5028.1   376.1  5045.6  377.49  5055.6  380.13  5065.6  381.03  5085.6  381.62
  5125.6  381.81  5135.6  381.33  5155.6  381.59  5165.6  380.76  5175.6  381.65
  5185.6  384.97  5195.6  386.47  5205.6  389.99  5215.6   390.7  5225.6  390.66
#Mann= 4 ,-1 , 0
  4709.3     .16       0  4925.7     .05       0  5001.5    .035       0
  5007.5     .05       0
Bank Sta=4941.2,5055.6
XS Rating Curve= 0 ,0
Exp/Cntr=0.3,0.1

Type RM Length L Ch R = 1 ,12673   ,723,723,723
BEGIN DESCRIPTION:
UNT068 IN CCTC 11.0
END DESCRIPTION:
XS GIS Cut Line= 3
      3514649.64     10652910.22      3514499.61     10652710.19
      3514199.64     10652310.22
#Sta/Elev= 30
  4796.3  386.94  4868.2  385.21  4939.1   379.8  4968.2  379.14  4989.1  373.97
  4993.3  371.63  4996.1  371.13  4999.3  371.63  5018.2  374.63  5024.5  372.03
  5032.8  377.48  5068.2  379.57  5118.2  378.15  5139.1     375  5153.6  374.56
  5174.5  375.87  5182.8  374.94  5209.9  376.51  5218.2   375.9  5224.5   377.2
  5232.8  375.65  5274.5  378.77  5296.3  379.01  5303.6  380.35  5318.2  378.98
  5353.6  381.88  5489.1  386.35  5518.2  388.66  5524.5  390.48  5546.3  389.51
#Mann= 3 ,-1 , 0
  4796.3     .05       0  4993.3    .035       0  4999.3     .05       0
Bank Sta=4968.2,5032.8
XS Rating Curve= 0 ,0
Exp/Cntr=0.3,0.1

Type RM Length L Ch R = 1 ,11950   ,619,619,619
BEGIN DESCRIPTION:
UNT068 IN CCTC 10.0
END DESCRIPTION:
XS GIS Cut Line= 2
       3515033.4      10652773.1      3514681.85     10652218.43
#Sta/Elev= 30
  4675.4  383.69  4782.4  380.49  4824.7  380.14  4832.8  379.28  4912.9  377.55
  4927.5  378.25  4955.2  377.97    4963  377.29  4985.7  372.65  4991.6   372.7
  4998.5  370.05  5006.9  370.17  5009.8  369.01  5012.6  368.51  5015.8  369.01
  5022.2  372.68    5034  373.01  5043.3  376.82  5064.5   378.5    5101  378.05
  5122.1  379.26  5137.4  378.06  5152.4  382.08  5164.5  382.85  5223.5  385.63
  5252.6   385.8  5267.9  387.18  5282.7  387.12  5289.1  388.04  5332.1  389.49
#Mann= 3 ,-1 , 0
  4675.4     .05       0  5009.8    .035       0  5015.8     .05       0
Bank Sta=4963,5043.3
XS Rating Curve= 0 ,0
Exp/Cntr=0.3,0.1

Type RM Length L Ch R = 1 ,11331   ,46,46,46
BEGIN DESCRIPTION:
Mapping XS bfc6810e
END DESCRIPTION:
XS GIS Cut Line= 6
      3515868.68     10652155.63       3515330.5     10652281.49
      3515109.15     10652283.66      3515059.23       10652288.
      3515007.15      10652324.9      3514829.39     10652027.58
#Sta/Elev= 30
  4432.1  382.73  4585.2  377.25  4692.9  378.32  4735.3  375.42  4740.4  377.76
  4770.1  372.77  4777.7  375.11  4790.7  372.68  4811.2  376.32    4842  371.86
  4862.6  374.33  4903.7  371.97  4910.1  374.84  4915.2   371.5  4952.8   374.3
  4957.9  371.77  5002.7  368.45  5005.4  367.95  5008.7  368.45  5035.7  374.22
  5222.3  376.57  5227.3  371.85  5259.1  373.88  5265.3  376.72  5280.1  376.59
  5286.2  373.06    5301   376.3  5476.1  381.56  5577.2  388.76  5666.5  391.79
#Mann= 3 ,-1 , 0
  4432.1     .12       0  5002.7     .04       0  5008.7     .12       0
Bank Sta=4952.8,5035.7
XS Rating Curve= 0 ,0
Exp/Cntr=0.3,0.1

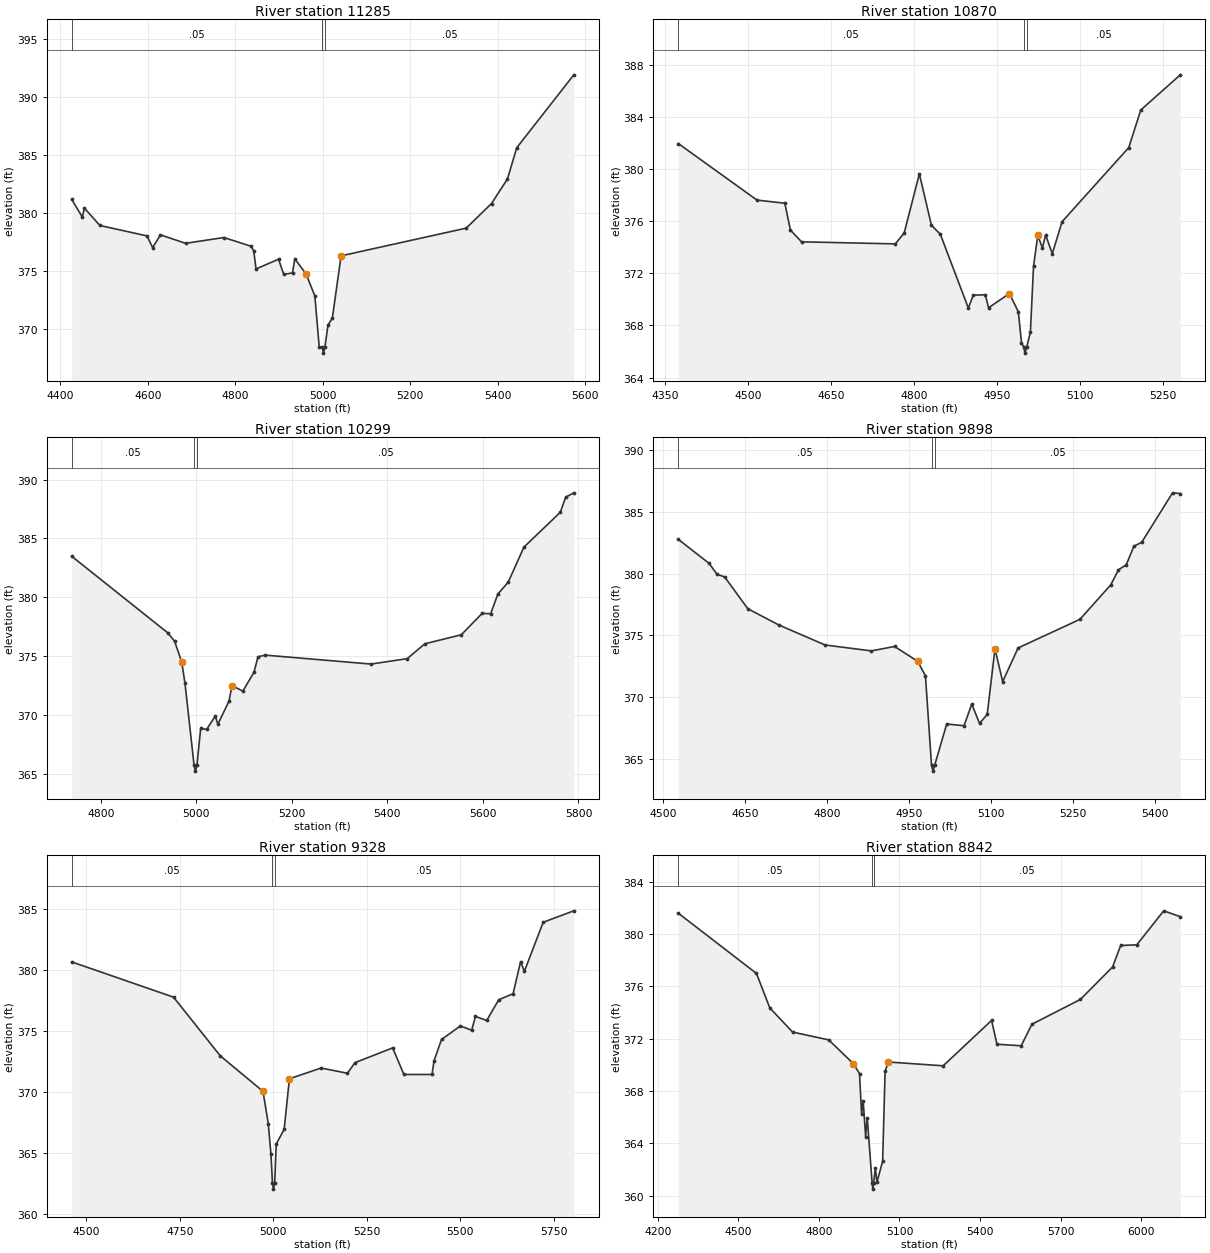
Type RM Length L Ch R = 1 ,11285   ,415,415,415
BEGIN DESCRIPTION:
UNT068 IN CCTC 9.0
END DESCRIPTION:
XS GIS Cut Line= 6
      3515865.82     10652098.55      3515447.02     10652209.21
      3515362.39      10652239.6      3515256.05      10652239.6
      3515032.53     10652243.94      3514875.67     10651993.98
#Sta/Elev= 30
  4425.8  381.16  4449.8  379.65  4454.9  380.41    4490  378.92  4597.7  378.02
  4610.8  377.01  4628.7  378.11  4686.1  377.38  4773.6  377.88  4835.6  377.13
    4842  376.73  4847.2  375.17  4898.7  376.01  4910.5   374.7  4930.6  374.83
  4935.9  376.05  4961.7  374.73  4981.7  372.84  4991.7  368.44  4998.7  368.41
  5001.4  367.91  5004.7  368.41  5011.7  370.33  5021.7  370.92  5041.7   376.3
  5327.9  378.69  5385.7  380.81  5422.2  382.93  5443.4  385.62  5573.9  391.91
#Mann= 3 ,-1 , 0
  4425.8     .05       0  4998.7     .04       0  5004.7     .05       0
Bank Sta=4961.7,5041.7
XS Rating Curve= 0 ,0
Exp/Cntr=0.3,0.1

Type RM Length L Ch R = 1 ,10870   ,571,571,571
BEGIN DESCRIPTION:
UNT068 IN CCTC 8.0
END DESCRIPTION:
XS GIS Cut Line= 4
      3515930.92     10652072.49      3515575.06     10652031.26
      3515299.45     10651879.35      3515117.14     10651731.77
#Sta/Elev= 30
  4373.5  381.96  4515.8  377.62  4566.1  377.38  4576.2  375.32  4596.3  374.42
  4765.8  374.26  4781.8  375.09  4809.3  379.63  4831.1  375.69  4847.2     375
  4897.8  369.34  4906.8  370.32  4928.6  370.36  4934.3  369.36  4972.1  370.45
  4988.2  369.05  4993.9  366.68  4997.6  366.38  5000.3  365.88  5003.6  366.38
    5010  367.49  5015.7  372.57  5023.4  374.91  5031.7  373.95  5037.5  374.95
  5049.6   373.5  5067.2  375.96  5187.8  381.65  5209.5  384.53    5281  387.23
#Mann= 3 ,-1 , 0
  4373.5     .05       0  4997.6     .03       0  5003.6     .05       0
Bank Sta=4972.1,5023.4
XS Rating Curve= 0 ,0
Exp/Cntr=0.3,0.1

Type RM Length L Ch R = 1 ,10299   ,401,401,401
BEGIN DESCRIPTION:
UNT068 IN CCTC 7.0
END DESCRIPTION:
XS GIS Cut Line= 2
      3516116.82     10651976.77      3515153.92     10651556.05
#Sta/Elev= 30
  4739.4  383.48  4940.7  376.97  4954.6  376.27  4969.6   374.5  4976.4  372.69
  4995.4  365.74  4998.2  365.24  5001.4  365.74  5009.2  368.86  5021.8  368.79
  5039.8  369.91  5045.2  369.22  5068.6  371.19  5074.7  372.51  5097.5  372.03
  5120.9  373.65  5129.2  374.95  5144.3  375.09  5365.8  374.33  5441.5  374.79
  5478.4  376.05  5554.8  376.82  5598.5  378.64  5616.2   378.6  5631.2  380.27
    5653  381.29  5685.8  384.26    5762  387.22  5773.1  388.49  5790.2  388.87
#Mann= 3 ,-1 , 0
  4739.4     .05       0  4995.4    .035       0  5001.4     .05       0
Bank Sta=4969.6,5074.7
XS Rating Curve= 0 ,0
Exp/Cntr=0.3,0.1

Type RM Length L Ch R = 1 ,9898    ,570,570,570
BEGIN DESCRIPTION:
UNT068 IN CCTC 6.0
END DESCRIPTION:
XS GIS Cut Line= 3
      3516149.63     10651910.21      3515799.61     10651560.19
      3515499.59     10651260.17
#Sta/Elev= 30
  4527.3  382.77  4583.9  380.82    4598  379.95  4612.2  379.73  4654.6  377.16
  4711.2  375.85    4796  374.23  4880.9  373.75  4923.3  374.11  4965.7  372.91
  4979.9  371.73    4991  364.53  4993.8  364.03    4997  364.53  5018.8  367.84
  5050.6   367.7  5064.7  369.45  5078.9  367.89    5093  368.61  5107.2  373.92
  5121.3  371.27  5149.6  373.99  5262.7   376.3  5319.3  379.09  5333.4  380.31
  5347.6  380.71  5361.7  382.22  5375.9  382.53  5432.4  386.53  5446.6  386.47
#Mann= 3 ,-1 , 0
  4527.3     .05       0    4991    .035       0    4997     .05       0
Bank Sta=4965.7,5107.2
XS Rating Curve= 0 ,0
Exp/Cntr=0.3,0.1

Type RM Length L Ch R = 1 ,9328    ,486,486,486
BEGIN DESCRIPTION:
UNT068 IN CCTC 5.0
END DESCRIPTION:
XS GIS Cut Line= 4
      3516478.21     10651787.81      3516311.55     10651385.05
      3516144.88     10651218.38      3515478.23     10651141.99
#Sta/Elev= 30
    4461  380.69  4733.2   377.8  4858.1  372.99  4972.4  370.08  4986.5  367.44
  4993.6  364.96  4997.7  362.56  5000.4  362.06  5003.7  362.56  5007.8  365.76
    5029  366.96  5043.1  371.11  5127.8  371.99  5198.3  371.56  5218.4  372.43
  5319.1  373.64  5349.3  371.46  5424.4  371.46  5429.8  372.58  5449.9  374.33
  5500.2  375.44  5530.4  375.09  5540.5  376.22  5570.7  375.89  5602.9  377.59
  5641.2  378.08  5661.3  380.71  5671.4  379.92  5721.7  383.94  5803.6  384.88
#Mann= 3 ,-1 , 0
    4461     .05       0  4997.7    .035       0  5003.7     .05       0
Bank Sta=4972.4,5043.1
XS Rating Curve= 0 ,0
Exp/Cntr=0.3,0.1

Type RM Length L Ch R = 1 ,8842    ,1542,1542,1542
BEGIN DESCRIPTION:
Mapping XS 834b1d57
END DESCRIPTION:
XS GIS Cut Line= 4
      3517064.01     10651507.41       3516631.7     10651090.73
      3516407.75      10650944.9      3515407.79     10650903.23
#Sta/Elev= 30
  4276.7   381.6  4567.8  376.99  4617.2  374.36  4702.1  372.51  4836.7  371.91
  4928.6  370.09  4951.2  369.33  4958.9  366.28  4964.9  367.23    4974  364.52
    4980  365.96  4998.1     361  5000.8   360.5  5004.1     361  5010.2  362.12
  5016.2  361.03  5037.3  362.64  5046.5  369.52  5058.6  370.22  5262.6  369.93
  5442.8   373.4  5462.8  371.58  5552.9  371.46  5592.9  373.11  5773.1     375
  5893.2  377.49  5923.2  379.13  5983.2  379.18  6083.3  381.78  6145.2  381.33
#Mann= 3 ,-1 , 0
  4276.7     .05       0  4998.1    .035       0  5004.1     .05       0
Bank Sta=4928.6,5058.6
XS Rating Curve= 0 ,0
Exp/Cntr=0.3,0.1

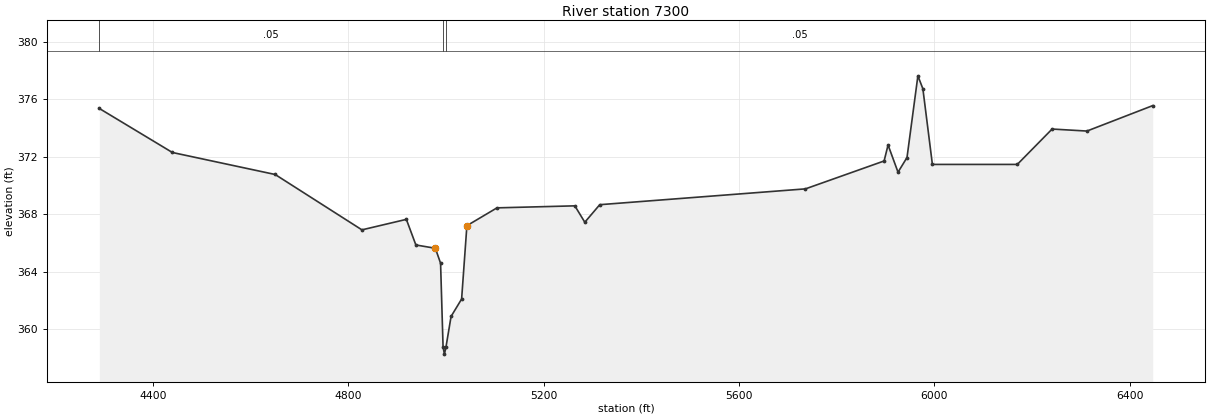
Type RM Length L Ch R = 1 ,7300    ,0,0,0
BEGIN DESCRIPTION:
UNT068 IN CCTC 4.0
END DESCRIPTION:
XS GIS Cut Line= 4
      3517246.22     10651152.42      3517152.47     10650506.55
      3516937.19     10650419.75       3515687.2     10650659.33
#Sta/Elev= 30
  4289.9  375.35  4439.5  372.29    4650  370.76  4827.7  366.91  4918.7  367.64
  4938.2  365.86  4978.1  365.63  4988.8  364.59  4993.9  358.77  4996.7  358.27
  4999.9  358.77  5010.3  360.89  5031.9   362.1  5042.7   367.2  5104.3  368.44
  5263.8  368.58  5284.2  367.44  5314.8  368.66  5736.1  369.76  5897.2   371.7
  5905.3  372.81  5925.7  370.92  5944.1  371.94  5966.4  377.62  5976.6  376.72
  5996.1  371.46    6170  371.46  6241.3  373.92  6312.6  373.78  6447.4  375.55
#Mann= 3 ,-1 , 0
  4289.9     .05       0  4993.9     .03       0  4999.9     .05       0
Bank Sta=4978.1,5042.7
XS Rating Curve= 0 ,0
Exp/Cntr=0.3,0.1

Chan Stop Cuts=-1
Use User Specified Reach Order=0
Composite Channel Slope=5