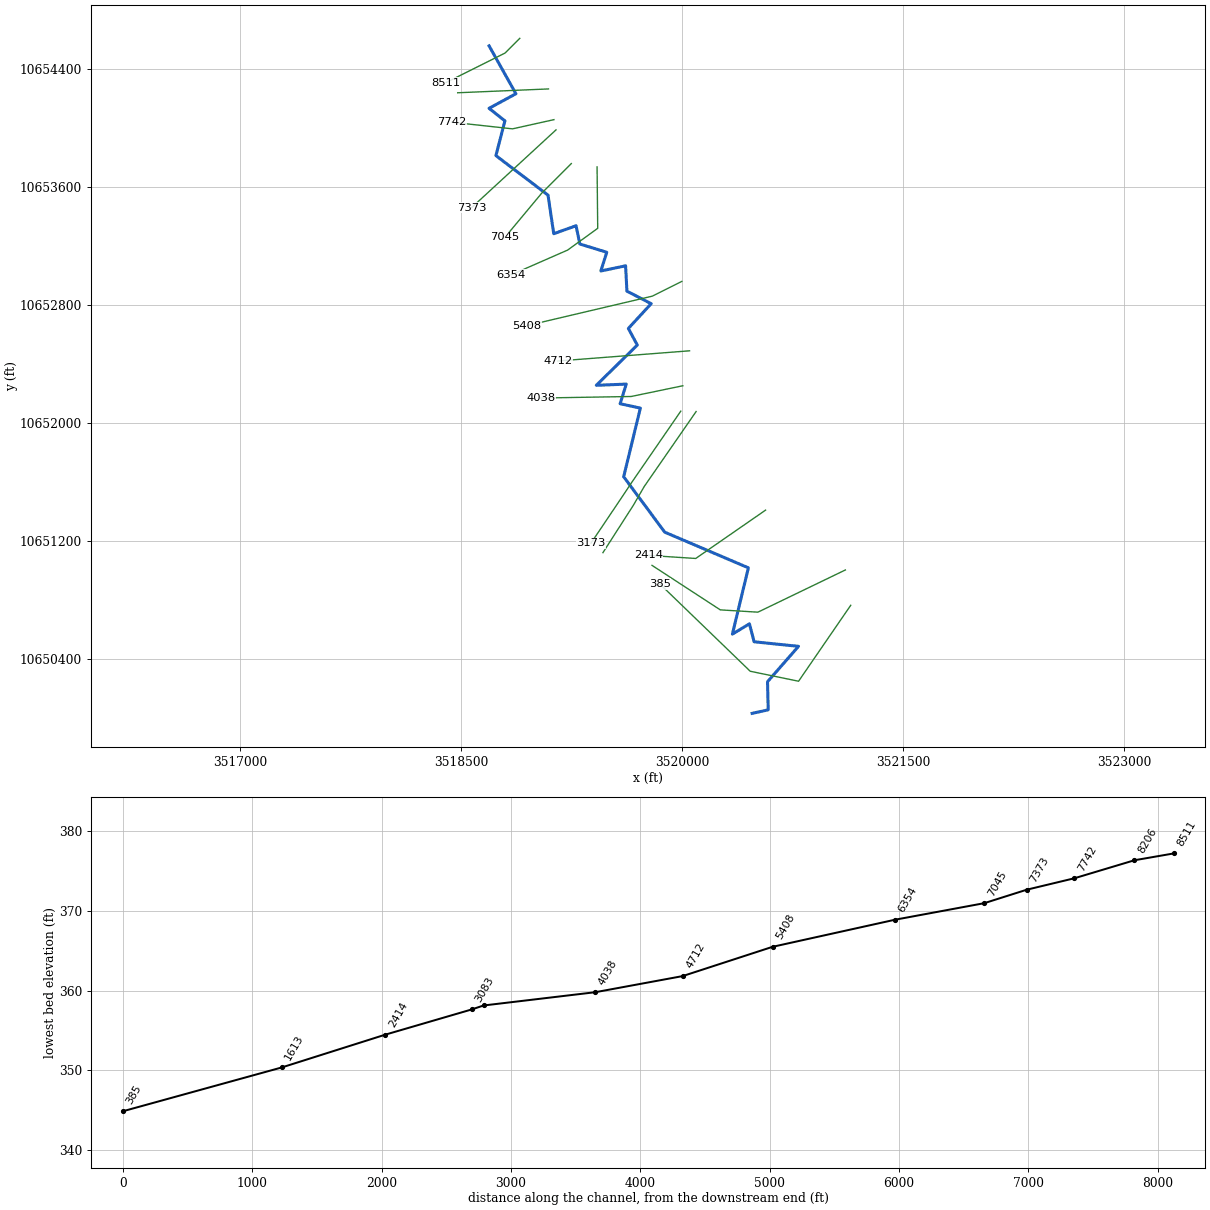
--- UNT069 IN CCTC.prj (project) ---

Proj Title=UNT069 IN CCTC Base Level Engineering
Current Plan=p01
Default Exp/Contr=0.3,0.1
English Units
Geom File=g01
Flow File=f01
Plan File=p01
BEGIN DESCRIPTION:
UNT069 IN CCTC
END DESCRIPTION:

--- UNT069 IN CCTC.p01 (plan) ---

Plan Title=Multiple Run
Short Identifier=Multiple
Geom File=g01
Flow File=f01
Subcritical Flow
K Sum by GR= 0
Std Step Tol= 0.01
Critical Tol= 0.01
Num of Std Step Trials= 20
Max Error Tol= 0.3
Flow Tol Ratio= 0.001
Split Flow NTrial= 30
Split Flow Tol= 0.02
Split Flow Ratio= 0.02
Log Output Level= 0
Friction Slope Method= 1
Unsteady Friction Slope Method= 2
Unsteady Bridges Friction Slope Method= 1
Parabolic Critical Depth
Global Vel Dist=  1 , 1 , 1
Global Log Level= 0
CheckData=True
Encroach Param= -1, 0, 0, 0
BEGIN DESCRIPTION:
Multiple Run
END DESCRIPTION:

--- UNT069 IN CCTC.f01 (steady flow) ---

Flow Title=Multiple
Number of Profiles=7
Profile Names=10-year,25-year,50-year,1pct_min,100-year,1pct_plu,500-year
River Rch & RM= UNT069 IN CCTC,Reach-1,8511
    1235    1685    2052    1822    2465    3333    3546
Boundary for River Rch & Prof#=UNT069 IN CCTC,Reach-1,1
Up Type=0
Dn Type=3
Dn Slope=0.005
Boundary for River Rch & Prof#=UNT069 IN CCTC,Reach-1,2
Up Type=0
Dn Type=3
Dn Slope=0.005
Boundary for River Rch & Prof#=UNT069 IN CCTC,Reach-1,3
Up Type=0
Dn Type=3
Dn Slope=0.005
Boundary for River Rch & Prof#=UNT069 IN CCTC,Reach-1,4
Up Type=0
Dn Type=3
Dn Slope=0.005
Boundary for River Rch & Prof#=UNT069 IN CCTC,Reach-1,5
Up Type=0
Dn Type=3
Dn Slope=0.005
Boundary for River Rch & Prof#=UNT069 IN CCTC,Reach-1,6
Up Type=0
Dn Type=3
Dn Slope=0.005
Boundary for River Rch & Prof#=UNT069 IN CCTC,Reach-1,7
Up Type=0
Dn Type=3
Dn Slope=0.005

--- UNT069 IN CCTC.g01 (geometry) ---

Geom Title=Existing Conditions

River Reach=UNT069 IN CCTC,Reach-1
Reach XY= 30
      3518691.50     10654559.00      3518873.50     10654234.00
      3518691.25     10654135.00      3518798.75     10654050.00
      3518737.75     10653814.00      3519091.50     10653546.00
      3519130.25     10653284.00      3519281.75     10653338.00
      3519307.50     10653214.00      3519490.25     10653158.00
      3519450.00     10653031.00      3519618.00     10653066.00
      3519627.00     10652894.00      3519791.75     10652809.00
      3519636.75     10652641.00      3519697.50     10652528.00
      3519419.25     10652255.00      3519622.50     10652263.00
      3519581.00     10652130.00      3519718.25     10652100.00
      3519605.00     10651634.00      3519883.75     10651258.00
      3520451.50     10651016.00      3520343.00     10650566.00
      3520458.75     10650636.00      3520490.50     10650514.00
      3520791.75     10650483.00      3520581.50     10650243.00
      3520586.00     10650052.00      3520476.75     10650028.00

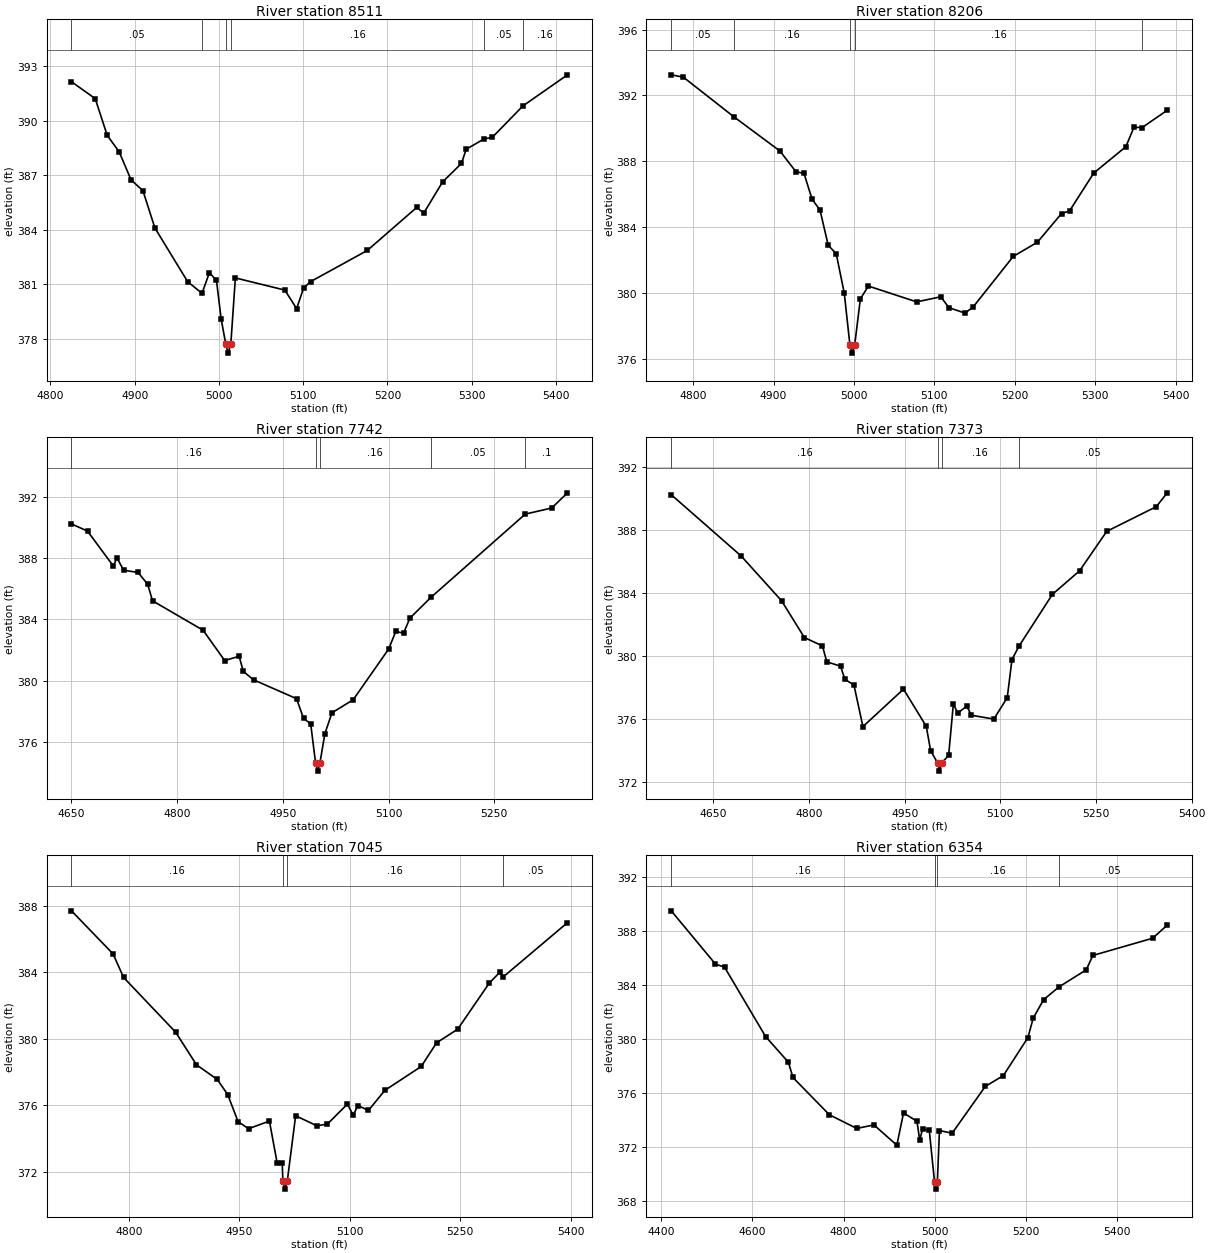
Type RM Length L Ch R = 1,8511,305,305,305
BEGIN DESCRIPTION:
UNT069 IN CCTC 12.0
END DESCRIPTION:
XS GIS Cut Line= 3
      3518899.58     10654610.16      3518799.61     10654510.19
      3518399.60     10654310.19
#Sta/Elev= 30
  4825.0  392.16  4853.2  391.23  4867.4  389.21  4881.5  388.31  4895.7  386.76
  4909.8  386.16  4924.0  384.11  4962.8  381.16  4979.9  380.51  4988.7  381.65
  4997.1  381.22  5002.7  379.08  5008.1  377.72  5010.9  377.22  5014.1  377.72
  5019.5  381.36  5078.2  380.69  5092.2  379.67  5100.5  380.81  5108.9  381.16
  5176.0  382.87  5234.7  385.24  5243.1  384.93  5265.5  386.65  5287.8  387.66
  5293.4  388.44  5314.9  389.02  5324.2  389.09  5360.8  390.83  5413.6  392.54
#Mann=6,-1,0
  4825.0    0.05       0  4979.9    0.16       0  5008.1    0.07       0
  5014.1    0.16       0  5314.9    0.05       0  5360.8    0.16       0
Bank Sta=5008.1,5014.1
Exp/Cntr=0.3,0.1

Type RM Length L Ch R = 1,8206,464,464,464
BEGIN DESCRIPTION:
UNT069 IN CCTC 11.0
END DESCRIPTION:
XS GIS Cut Line= 2
      3519094.59     10654266.68      3518478.24     10654240.64
#Sta/Elev= 30
  4772.7  393.25  4787.7  393.11  4851.2  390.68  4907.8  388.63  4927.8  387.37
  4937.8  387.27  4947.8  385.71  4957.8  385.03  4967.9  382.91  4977.9  382.39
  4987.9  380.00  4994.9  376.86  4997.6  376.36  5000.9  376.86  5007.9  379.65
  5017.9  380.43  5078.0  379.47  5108.0  379.78  5118.0  379.12  5138.0  378.79
  5148.0  379.15  5198.1  382.23  5228.1  383.09  5258.1  384.83  5268.1  384.99
  5298.2  387.29  5338.2  388.89  5348.2  390.07  5358.4  390.05  5389.6  391.10
#Mann=5,-1,0
  4772.7    0.05       0  4851.2    0.16       0  4994.9    0.07       0
  5000.9    0.16       0  5358.4    0.05       0
Bank Sta=4994.9,5000.9
Exp/Cntr=0.3,0.1

Type RM Length L Ch R = 1,7742,369,369,369
BEGIN DESCRIPTION:
Mapping XS 17d5f38e
END DESCRIPTION:
XS GIS Cut Line= 3
      3519131.82     10654058.24      3518850.61     10653995.75
      3518437.44     10654040.89
#Sta/Elev= 30
  4650.0  390.24  4672.8  389.77  4709.4  387.49  4714.5  388.02  4724.0  387.22
  4744.5  387.07  4758.1  386.30  4765.0  385.22  4836.7  383.30  4867.4  381.32
  4887.9  381.60  4893.8  380.61  4908.4  380.06  4969.3  378.83  4979.3  377.54
  4989.4  377.19  4996.4  374.60  4999.2  374.10  5002.4  374.60  5009.5  376.54
  5019.6  377.91  5049.7  378.76  5100.0  382.07  5110.1  383.22  5121.1  383.11
  5130.2  384.09  5159.9  385.44  5293.8  390.88  5331.4  391.28  5353.7  392.27
#Mann=5,-1,0
  4650.0    0.16       0  4996.4    0.07       0  5002.4    0.16       0
  5159.9    0.05       0  5293.8     0.1       0
Bank Sta=4996.4,5002.4
Exp/Cntr=0.3,0.1

Type RM Length L Ch R = 1,7373,328,328,328
BEGIN DESCRIPTION:
UNT069 IN CCTC 10.0
END DESCRIPTION:
XS GIS Cut Line= 2
      3519145.79     10653988.84      3518573.72     10653461.85
#Sta/Elev= 30
  4583.9  390.23  4693.4  386.34  4756.9  383.49  4792.7  381.15  4821.0  380.62
  4827.8  379.61  4849.4  379.33  4856.2  378.50  4870.4  378.13  4884.5  375.49
  4948.1  377.87  4983.8  375.51  4990.6  373.97  5001.8  373.16  5004.5  372.66
  5007.8  373.16  5018.9  373.67  5026.3  376.93  5033.1  376.35  5047.3  376.79
  5054.6  376.21  5089.8  375.97  5110.8  377.33  5118.2  379.75  5129.0  380.59
  5181.7  383.90  5224.2  385.39  5266.8  387.90  5344.5  389.47  5361.7  390.35
#Mann=4,-1,0
  4583.9    0.16       0  5001.8    0.07       0  5007.8    0.16       0
  5129.0    0.05       0
Bank Sta=5001.8,5007.8
Exp/Cntr=0.3,0.1

Type RM Length L Ch R = 1,7045,691,691,691
BEGIN DESCRIPTION:
UNT069 IN CCTC 9.0
END DESCRIPTION:
XS GIS Cut Line= 3
      3519249.58     10653760.16      3519049.61     10653560.19
      3518799.62     10653260.20
#Sta/Elev= 30
  4722.1  387.69  4778.6  385.10  4792.8  383.69  4863.5  380.40  4891.8  378.44
  4920.0  377.56  4934.2  376.65  4948.3  375.02  4962.5  374.60  4990.8  375.06
  5001.4  372.52  5008.2  372.52  5009.1  371.47  5011.8  370.97  5015.1  371.47
  5026.4  375.38  5055.0  374.78  5069.3  374.87  5096.7  376.08  5104.5  375.41
  5111.0  375.99  5125.3  375.70  5147.4  376.90  5196.9  378.34  5217.7  379.76
  5246.4  380.58  5289.3  383.35  5303.6  384.00  5308.2  383.72  5395.4  386.98
#Mann=4,-1,0
  4722.1    0.16       0  5009.1    0.07       0  5015.1    0.16       0
  5308.2    0.05       0
Bank Sta=5009.1,5015.1
Exp/Cntr=0.3,0.1

Type RM Length L Ch R = 1,6354,946,946,946
BEGIN DESCRIPTION:
UNT069 IN CCTC 8.0
END DESCRIPTION:
XS GIS Cut Line= 4
      3519424.42     10653737.19      3519428.76     10653320.50
      3519224.77     10653172.93      3518840.25     10653004.44
#Sta/Elev= 30
  4421.8  389.48  4518.8  385.54  4538.8  385.31  4628.8  380.18  4678.8  378.28
  4688.8  377.15  4768.8  374.39  4828.8  373.38  4866.5  373.64  4916.8  372.14
  4931.5  374.53  4960.9  373.91  4967.0  372.53  4973.2  373.33  4987.9  373.26
  4999.6  369.39  5002.4  368.89  5005.6  369.39  5010.3  373.22  5038.2  373.03
  5110.9  376.49  5150.5  377.29  5204.4  380.10  5216.0  381.54  5238.7  382.90
  5272.5  383.85  5332.2  385.11  5347.0  386.18  5477.9  387.45  5510.1  388.42
#Mann=4,-1,0
  4421.8    0.16       0  4999.6    0.07       0  5005.6    0.16       0
  5272.5    0.05       0
Bank Sta=4999.6,5005.6
Exp/Cntr=0.3,0.1

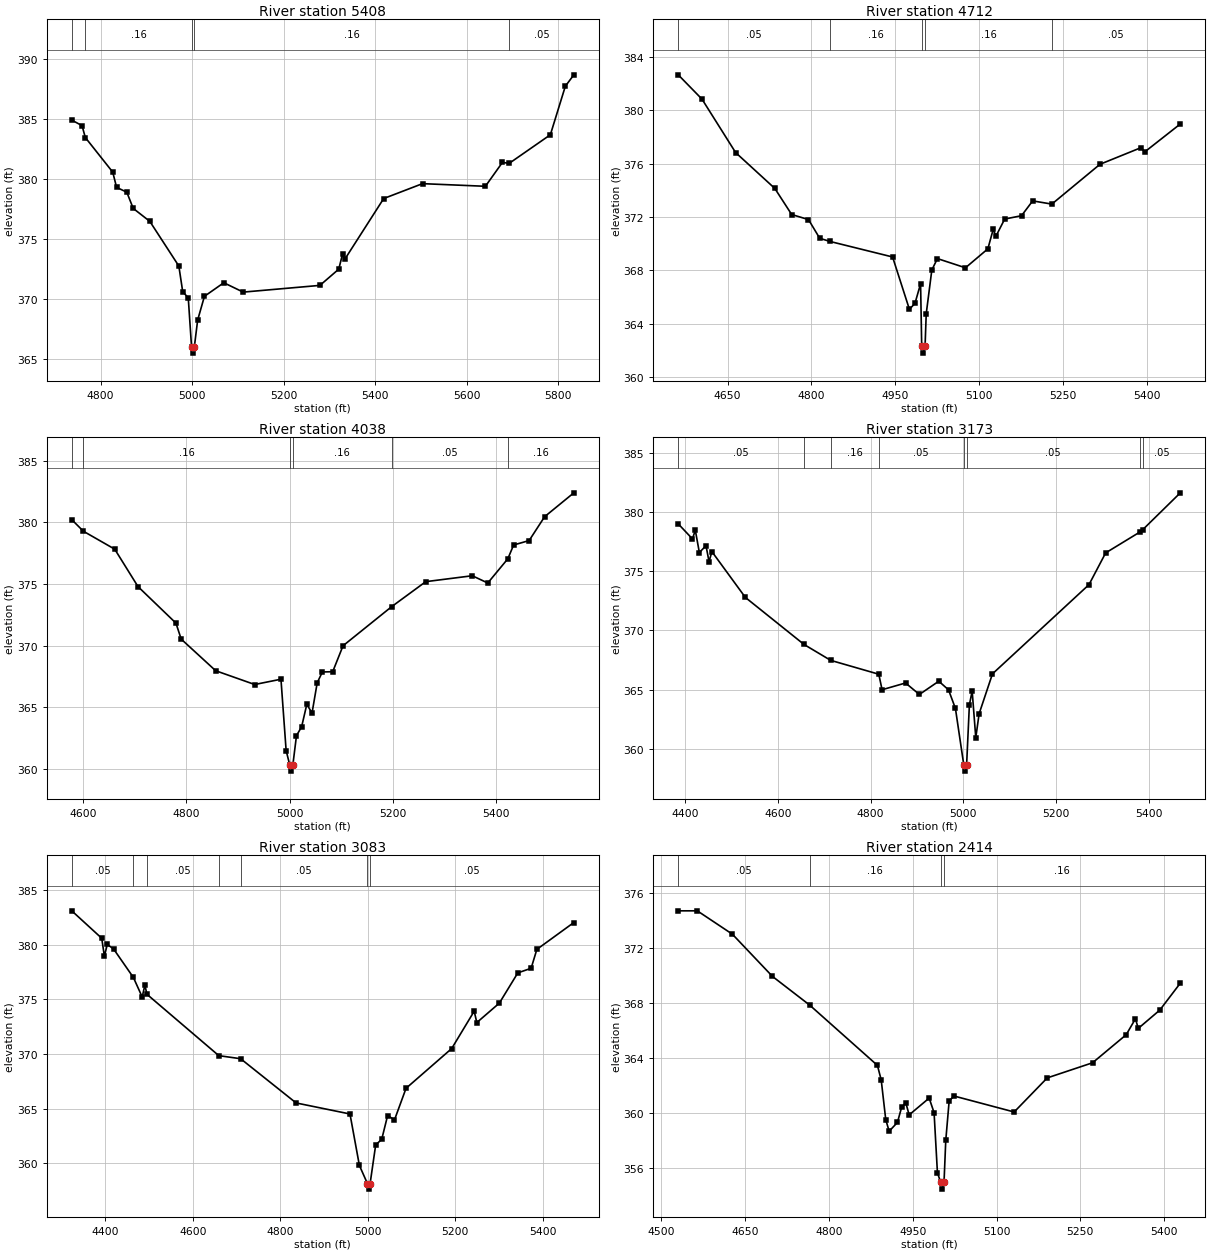
Type RM Length L Ch R = 1,5408,696,696,696
BEGIN DESCRIPTION:
UNT069 IN CCTC 7.0
END DESCRIPTION:
XS GIS Cut Line= 3
      3519999.64     10652960.20      3519799.61     10652860.19
      3518949.66     10652660.20
#Sta/Elev= 30
  4737.0  384.89  4759.4  384.43  4766.6  383.44  4826.5  380.56  4834.9  379.29
  4857.2  378.89  4871.2  377.54  4907.5  376.46  4970.9  372.74  4979.3  370.62
  4991.5  370.08  4998.7  365.99  5001.5  365.49  5004.7  365.99  5012.0  368.24
  5026.8  370.22  5069.1  371.35  5111.5  370.57  5279.1  371.13  5320.2  372.48
  5328.5  373.73  5333.7  373.32  5418.4  378.36  5503.2  379.60  5640.6  379.38
  5677.8  381.37  5692.6  381.29  5782.5  383.67  5815.2  387.71  5833.8  388.66
#Mann=5,-1,0
  4737.0    0.05       0  4766.6    0.16       0  4998.7    0.07       0
  5004.7    0.16       0  5692.6    0.05       0
Bank Sta=4998.7,5004.7
Exp/Cntr=0.3,0.1

Type RM Length L Ch R = 1,4712,674,674,674
BEGIN DESCRIPTION:
UNT069 IN CCTC 6.0
END DESCRIPTION:
XS GIS Cut Line= 2
      3520052.02     10652489.10      3519156.21     10652419.66
#Sta/Elev= 30
  4561.6  382.65  4604.1  380.83  4664.3  376.83  4734.5  374.14  4764.6  372.19
  4794.7  371.81  4814.8  370.41  4833.4  370.17  4945.2  369.01  4975.3  365.09
  4985.3  365.54  4995.3  367.01  4997.3  362.31  5000.1  361.81  5003.3  362.31
  5005.4  364.76  5015.4  368.03  5025.4  368.89  5075.6  368.20  5115.7  369.62
  5125.2  371.07  5130.2  370.57  5145.8  371.85  5175.9  372.10  5195.9  373.21
  5230.2  372.97  5316.3  375.95  5390.0  377.20  5396.5  376.88  5460.1  378.97
#Mann=5,-1,0
  4561.6    0.05       0  4833.4    0.16       0  4997.3    0.07       0
  5003.3    0.16       0  5230.2    0.05       0
Bank Sta=4997.3,5003.3
Exp/Cntr=0.3,0.1

Type RM Length L Ch R = 1,4038,865,865,865
BEGIN DESCRIPTION:
UNT069 IN CCTC 5.0
END DESCRIPTION:
XS GIS Cut Line= 3
      3520006.85     10652251.92      3519656.19     10652179.01
      3519043.13     10652168.62
#Sta/Elev= 30
  4578.5  380.23  4600.9  379.29  4661.6  377.83  4706.6  374.79  4780.0  371.82
  4790.2  370.52  4856.9  367.95  4932.4  366.83  4983.2  367.26  4993.2  361.46
  5000.2  360.29  5003.0  359.79  5006.2  360.29  5013.2  362.67  5023.2  363.40
  5033.2  365.22  5043.3  364.51  5053.3  366.97  5063.3  367.85  5083.3  367.87
  5103.3  369.98  5197.1  373.15  5263.3  375.19  5353.3  375.67  5383.3  375.08
  5422.1  377.05  5433.3  378.17  5463.3  378.53  5493.3  380.47  5549.8  382.41
#Mann=6,-1,0
  4578.5    0.05       0  4600.9    0.16       0  5000.2    0.07       0
  5006.2    0.16       0  5197.1    0.05       0  5422.1    0.16       0
Bank Sta=5000.2,5006.2
Exp/Cntr=0.3,0.1

Type RM Length L Ch R = 1,3173,90,90,90
BEGIN DESCRIPTION:
UNT069 IN CCTC 4.0
END DESCRIPTION:
XS GIS Cut Line= 4
      3519992.66     10652079.55      3519664.52     10651602.97
      3519586.40     10651485.78      3519383.27     10651183.69
#Sta/Elev= 30
  4384.7  378.99  4415.4  377.72  4421.5  378.46  4430.3  376.57  4444.6  377.15
  4451.2  375.80  4457.3  376.65  4529.6  372.78  4656.2  368.81  4713.7  367.47
  4817.5  366.30  4824.6  364.99  4875.3  365.56  4905.1  364.59  4947.0  365.71
  4968.0  364.98  4982.9  363.41  5001.0  358.62  5003.7  358.12  5007.0  358.62
  5013.0  363.71  5019.0  364.88  5026.8  360.94  5034.0  362.96  5062.8  366.33
  5271.1  373.86  5307.1  376.54  5380.5  378.29  5386.6  378.48  5468.2  381.61
#Mann=8,-1,0
  4384.7    0.05       0  4656.2    0.08       0  4713.7    0.16       0
  4817.5    0.05       0  5001.0    0.04       0  5007.0    0.05       0
  5380.5    0.16       0  5386.6    0.05       0
Bank Sta=5001,5007
Exp/Cntr=0.3,0.1

Type RM Length L Ch R = 1,3083,669,669,669
BEGIN DESCRIPTION:
UNT069 IN CCTC 3.0
END DESCRIPTION:
XS GIS Cut Line= 4
      3520096.81     10652076.91      3519745.25     10651569.11
      3519669.73     10651438.91      3519464.29     10651119.04
#Sta/Elev= 30
  4323.2  383.11  4391.7  380.60  4397.8  378.96  4404.4  380.03  4418.8  379.62
  4464.1  377.01  4484.3  375.22  4490.4  376.31  4495.1  375.47  4659.5  369.85
  4709.4  369.57  4836.3  365.52  4959.5  364.51  4981.0  359.80  4999.5  358.13
  5002.3  357.63  5005.5  358.13  5018.3  361.68  5032.1  362.19  5045.6  364.37
  5061.3  363.97  5087.7  366.86  5192.1  370.50  5243.6  373.92  5249.6  372.88
  5301.1  374.66  5343.4  377.43  5373.8  377.85  5386.9  379.58  5471.5  382.04
#Mann=7,-1,0
  4323.2    0.05       0  4464.1    0.16       0  4495.1    0.05       0
  4659.5    0.08       0  4709.4    0.05       0  4999.5    0.04       0
  5005.5    0.05       0
Bank Sta=4999.5,5005.5
Exp/Cntr=0.3,0.1

Type RM Length L Ch R = 1,2414,801,801,801
BEGIN DESCRIPTION:
Mapping XS 8a62ac0e
END DESCRIPTION:
XS GIS Cut Line= 3
      3520568.20     10651407.68      3520094.21     10651079.53
      3519772.97     10651100.26
#Sta/Elev= 30
  4530.5  374.70  4564.6  374.70  4627.4  373.00  4699.1  369.93  4765.8  367.84
  4886.9  363.46  4893.7  362.40  4901.8  359.52  4907.9  358.67  4922.7  359.31
  4930.2  360.41  4937.6  360.75  4943.7  359.86  4979.5  361.08  4988.3  360.02
  4994.3  355.65  5000.1  354.96  5002.9  354.46  5006.1  354.96  5009.2  358.00
  5015.3  360.88  5024.1  361.23  5131.6  360.07  5190.8  362.55  5271.9  363.65
  5332.1  365.69  5348.6  366.85  5353.7  366.15  5392.2  367.48  5428.9  369.44
#Mann=4,-1,0
  4530.5    0.05       0  4765.8    0.16       0  5000.1    0.07       0
  5006.1    0.16       0
Bank Sta=5000.1,5006.1
Exp/Cntr=0.3,0.1

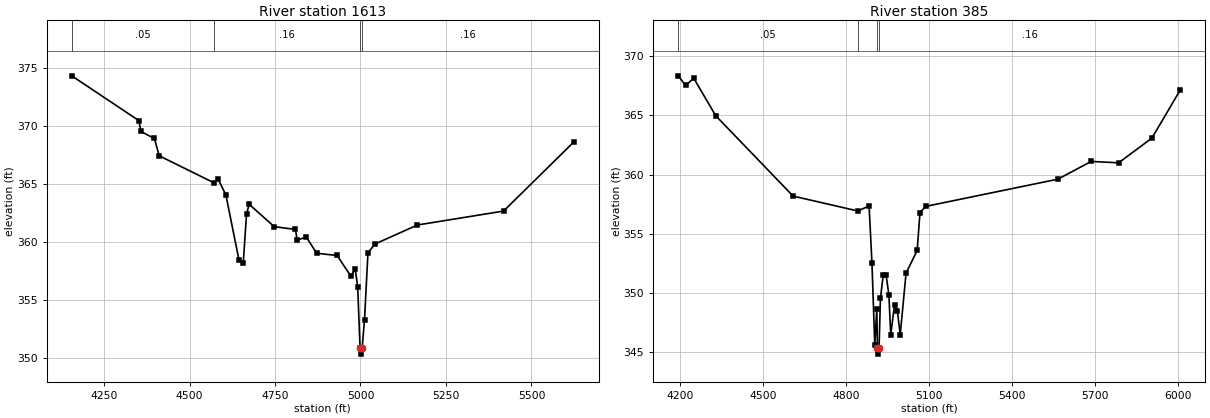
Type RM Length L Ch R = 1,1613,1228,1228,1228
BEGIN DESCRIPTION:
UNT069 IN CCTC 2.0
END DESCRIPTION:
XS GIS Cut Line= 4
      3521109.84     10651001.41      3520516.09     10650714.95
      3520260.88     10650730.57      3519797.35     10651032.65
#Sta/Elev= 30
  4155.7  374.29  4352.2  370.43  4357.7  369.50  4397.4  368.90  4411.3  367.41
  4571.1  365.09  4583.8  365.40  4606.4  364.04  4644.5  358.46  4657.2  358.19
  4666.7  362.36  4674.3  363.24  4747.7  361.31  4809.9  361.07  4814.7  360.14
  4841.5  360.43  4871.5  359.02  4931.6  358.83  4971.7  357.06  4984.6  357.64
  4991.8  356.15  4998.8  350.84  5001.5  350.34  5004.8  350.84  5011.8  353.32
  5021.8  359.04  5041.8  359.81  5166.2  361.45  5418.3  362.65  5623.9  368.60
#Mann=4,-1,0
  4155.7    0.05       0  4571.1    0.16       0  4998.8    0.07       0
  5004.8    0.16       0
Bank Sta=4998.8,5004.8
Exp/Cntr=0.3,0.1

Type RM Length L Ch R = 1,385,0,0,0
BEGIN DESCRIPTION:
UNT069 IN CCTC 1.0
END DESCRIPTION:
XS GIS Cut Line= 4
      3521146.28     10650761.79      3520792.13     10650246.20
      3520464.00     10650313.91      3519850.71     10650906.41
#Sta/Elev= 30
  4194.8  368.35  4221.2  367.54  4251.0  368.14  4330.2  364.98  4609.6  358.19
  4843.9  356.93  4884.1  357.37  4894.4  352.56  4904.6  345.64  4912.0  348.67
  4914.1  345.34  4916.8  344.84  4920.1  345.34  4925.0  349.55  4935.2  351.53
  4945.4  351.54  4955.6  349.85  4962.2  346.47  4976.0  349.01  4986.3  348.49
  4996.5  346.48  5017.6  351.68  5057.7  353.60  5067.9  356.79  5088.4  357.32
  5565.9  359.62  5686.3  361.12  5785.3  361.00  5905.5  363.09  6008.1  367.16
#Mann=4,-1,0
  4194.8    0.05       0  4843.9    0.16       0  4914.1    0.07       0
  4920.1    0.16       0
Bank Sta=4914.1,4920.1
Exp/Cntr=0.3,0.1

Chan Stop Cuts=-1