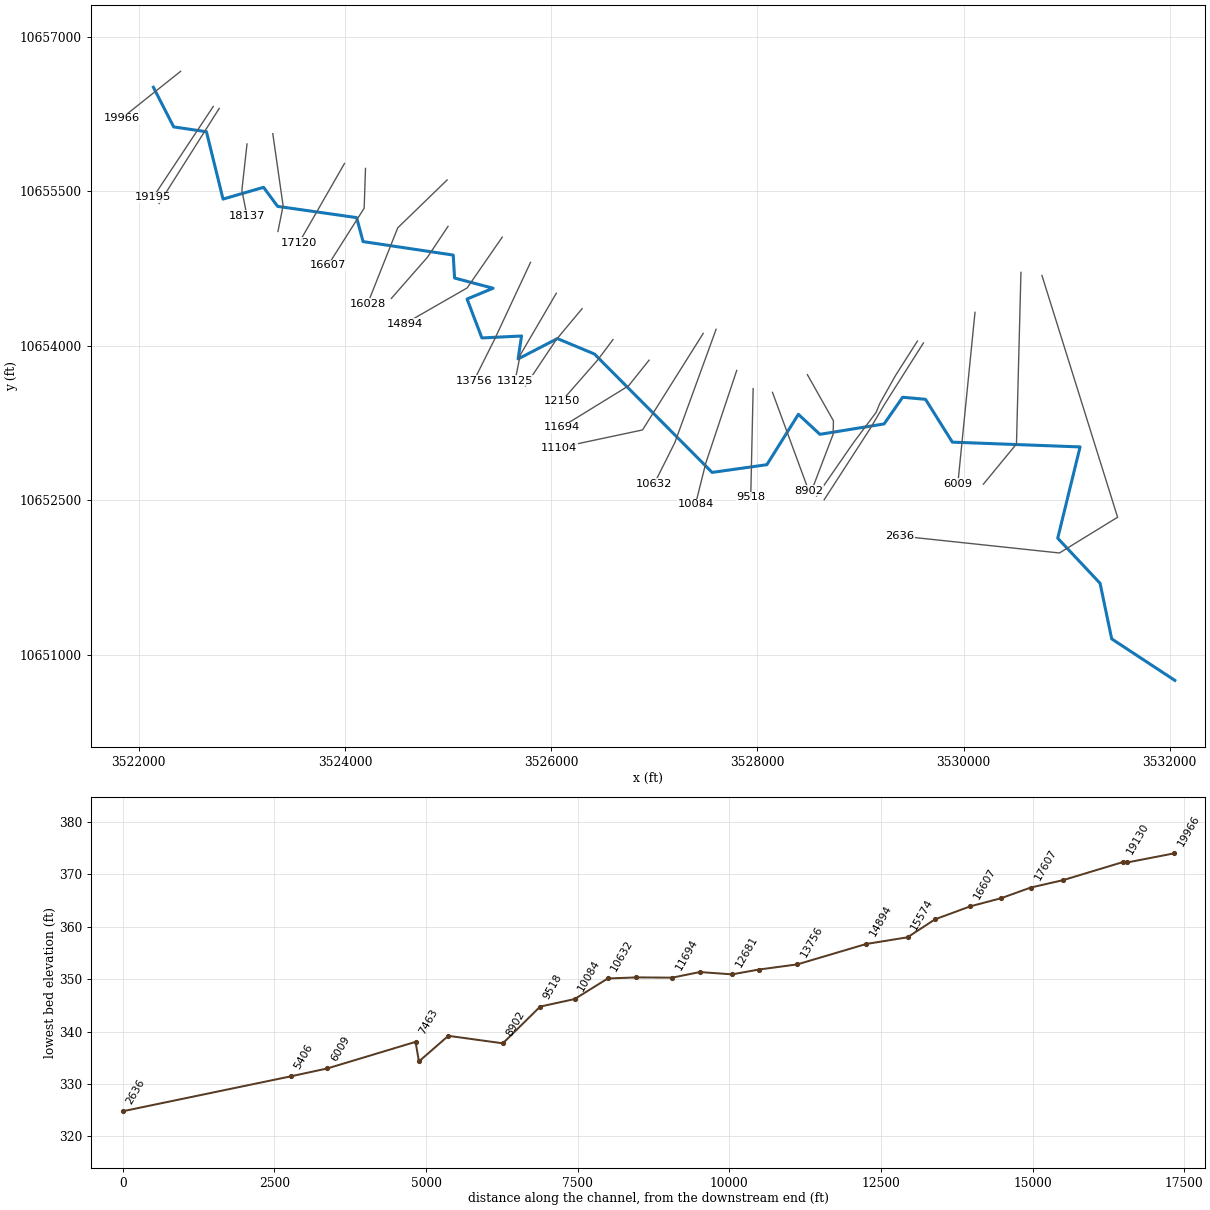
--- UNT073 IN CCTC.prj (project) ---

Proj Title=UNT073 IN CCTC Base Level Engineering
Current Plan=p01
Default Exp/Contr=0.3,0.1
English Units
Geom File=g01
Flow File=f01
Plan File=p01
Y Axis Title=Elevation
X Axis Title(PF)=Main Channel Distance
X Axis Title(XS)=Station
BEGIN DESCRIPTION:
UNT073 IN CCTC
END DESCRIPTION:
DSS Export Rating Curves= 0
DSS Export Rating Curve Sorted= 0
DSS Export Volume Flow Curves= 0
DXF OffsetX= 0
DXF OffsetY= 0
DXF ScaleX= 1
DXF ScaleY= 10

--- UNT073 IN CCTC.p01 (plan) ---

Plan Title=Multiple Run
Short Identifier=Multiple
Geom File=g01
Flow File=f01
Subcritical Flow
K Sum by GR= 0
Std Step Tol= 0.01
Critical Tol= 0.01
Num of Std Step Trials= 20
Max Error Tol= 0.3
Flow Tol Ratio= 0.001
Split Flow NTrial= 30
Split Flow Tol= 0.02
Split Flow Ratio= 0.02
Log Output Level= 0
Friction Slope Method= 1
Unsteady Friction Slope Method= 2
Unsteady Bridges Friction Slope Method= 1
Parabolic Critical Depth
Global Vel Dist=  1 , 1 , 1
Global Log Level= 0
CheckData=True
Encroach Param= -1, 0, 0, 0
BEGIN DESCRIPTION:
Multiple Run
END DESCRIPTION:

--- UNT073 IN CCTC.f01 (steady flow) ---

Flow Title=Multiple
Number of Profiles=7
Profile Names=10-year,25-year,50-year,1pct_min,100-year,1pct_plu,500-year
River Rch & RM= UNT073 IN CCTC,Reach-1,19966
    1111    1508    1830    1622    2193    2966    3140
River Rch & RM= UNT073 IN CCTC,Reach-1,18137
    1768    2456    3029    2720    3678    4974    5414
River Rch & RM= UNT073 IN CCTC,Reach-1,11104
    2390    3367    4190    3793    5130    6938    7677
Boundary for River Rch & Prof#=UNT073 IN CCTC,Reach-1,1
Up Type=0
Dn Type=3
Dn Slope=0.005
Boundary for River Rch & Prof#=UNT073 IN CCTC,Reach-1,2
Up Type=0
Dn Type=3
Dn Slope=0.005
Boundary for River Rch & Prof#=UNT073 IN CCTC,Reach-1,3
Up Type=0
Dn Type=3
Dn Slope=0.005
Boundary for River Rch & Prof#=UNT073 IN CCTC,Reach-1,4
Up Type=0
Dn Type=3
Dn Slope=0.005
Boundary for River Rch & Prof#=UNT073 IN CCTC,Reach-1,5
Up Type=0
Dn Type=3
Dn Slope=0.005
Boundary for River Rch & Prof#=UNT073 IN CCTC,Reach-1,6
Up Type=0
Dn Type=3
Dn Slope=0.005
Boundary for River Rch & Prof#=UNT073 IN CCTC,Reach-1,7
Up Type=0
Dn Type=3
Dn Slope=0.005

--- UNT073 IN CCTC.g01 (geometry) ---

Geom Title=Existing Conditions
Program Version=4.10

River Reach=UNT073 IN CCTC  ,Reach-1
Reach XY= 30
      3522141.34     10656511.14      3522338.25       10656126.
        3522656.       10656079.        3522817.       10655425.
        3523210.       10655539.       3523346.5       10655354.
       3524112.5       10655245.      3524175.25       10655012.
      3525049.75       10654881.        3525063.       10654658.
        3525436.       10654559.        3525184.       10654454.
      3525327.75       10654076.       3525712.5       10654095.
      3525678.75       10653872.       3526060.5       10654070.
       3526419.5       10653920.        3527561.       10652770.
      3528092.25       10652845.      3528397.75       10653334.
       3528606.5       10653140.      3529229.25       10653241.
        3529409.       10653500.      3529630.75       10653480.
      3529891.25       10653064.       3531130.1     10653017.52
      3530913.25       10652131.        3531324.       10651693.
        3531437.       10651153.       3532049.5       10650750.

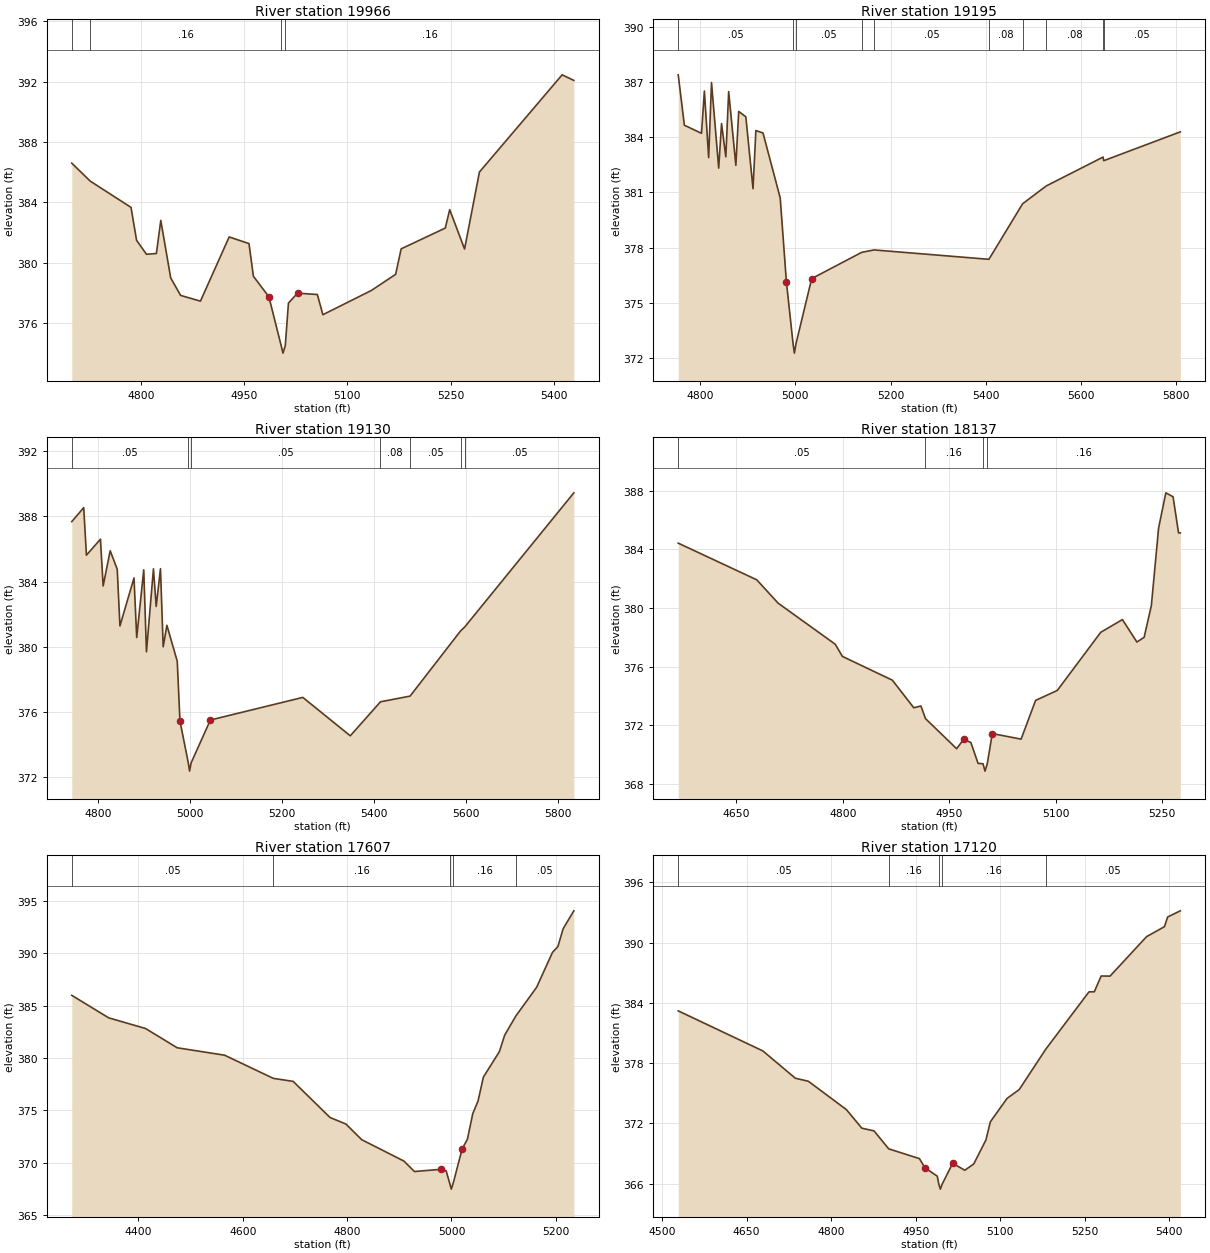
Type RM Length L Ch R = 1 ,19966   ,771,771,771
BEGIN DESCRIPTION:
UNT073 IN CCTC 28.0
END DESCRIPTION:
XS GIS Cut Line= 2
      3522405.76     10656665.75      3521835.46     10656211.33
#Sta/Elev= 30
  4699.8   386.6  4726.5  385.41  4785.9  383.66  4793.9  381.48  4808.3  380.55
  4822.7   380.6  4829.1   382.8  4843.5  378.98  4857.9  377.82  4886.7  377.44
  4928.4   381.7  4957.2  381.26  4963.6  379.09  4986.1  377.73  5003.9  374.49
  5006.6  373.99  5009.9  374.49  5014.5  377.31  5027.7  377.97  5056.5  377.88
  5064.5  376.54    5135  378.15  5170.2  379.22  5178.2  380.91  5242.3  382.29
  5248.7  383.51  5270.3   380.9  5291.9  386.01    5412  392.46    5429  392.09
#Mann= 4 ,-1 , 0
  4699.8     .05       0  4726.5     .16       0  5003.9     .07       0
  5009.9     .16       0
Bank Sta=4986.1,5027.7
XS Rating Curve= 0 ,0
Exp/Cntr=0.3,0.1

Type RM Length L Ch R = 1 ,19195   ,65,65,65
BEGIN DESCRIPTION:
UNT073 IN CCTC 27.0
END DESCRIPTION:
XS GIS Cut Line= 2
      3522722.34     10656324.94      3522139.72     10655444.09
#Sta/Elev= 30
  4753.5  387.39  4766.4  384.65  4802.5  384.21  4808.5  386.51  4817.5  382.89
  4823.5  386.97  4838.6  382.32  4844.6  384.74  4853.6  382.93  4859.6  386.48
  4874.7  382.47  4880.7   385.4  4895.7  385.11  4910.8   381.2  4916.8  384.36
  4931.8  384.23    4968   380.7    4981  376.14  4995.1  372.76  4997.8  372.26
  5001.1  372.76  5034.2  376.31  5139.5  377.74  5165.5  377.87    5407  377.36
  5477.9  380.38  5527.7  381.35  5647.2  382.92  5648.4  382.72  5809.6  384.29
#Mann= 10 ,-1 , 0
  4753.5     .05       0  4995.1     .04       0  5001.1     .05       0
  5139.5     .16       0  5165.5     .05       0    5407     .08       0
  5477.9     .05       0  5527.7     .08       0  5647.2     .16       0
  5648.4     .05       0
Bank Sta=4981,5034.2
XS Rating Curve= 0 ,0
Exp/Cntr=0.3,0.1

Type RM Length L Ch R = 1 ,19130   ,993,993,993
BEGIN DESCRIPTION:
UNT073 IN CCTC 26.0
END DESCRIPTION:
XS GIS Cut Line= 2
      3522779.67     10656305.23      3522196.34     10655381.61
#Sta/Elev= 30
  4742.9  387.68  4768.9  388.54  4774.8  385.62  4805.3   386.6  4811.2  383.73
  4826.5  385.89  4841.8  384.76  4847.7  381.27  4878.3  384.22  4884.2  380.56
  4899.5  384.72  4905.4  379.68  4920.6  384.78  4926.6  382.47  4935.9  384.79
  4941.8  379.99  4949.9  381.31  4972.4   379.1  4978.3  375.43  4996.5  372.85
  4999.2  372.35  5002.5  372.85  5044.5  375.49  5245.6  376.88  5348.9  374.52
  5414.6  376.61    5479  376.96    5589  380.97    5598  381.21  5835.3  389.45
#Mann= 7 ,-1 , 0
  4742.9     .05       0  4996.5     .04       0  5002.5     .05       0
  5414.6     .08       0    5479     .05       0    5589     .08       0
    5598     .05       0
Bank Sta=4978.3,5044.5
XS Rating Curve= 0 ,0
Exp/Cntr=0.3,0.1

Type RM Length L Ch R = 1 ,18137   ,530,530,530
BEGIN DESCRIPTION:
UNT073 IN CCTC 25.0
END DESCRIPTION:
XS GIS Cut Line= 3
      3523049.61     10655960.17      3522999.61     10655510.19
      3523049.61     10655260.19
#Sta/Elev= 30
  4568.1  384.42  4678.8  381.92  4708.9  380.33  4789.4  377.53  4799.5   376.7
  4869.9  375.08  4900.1   373.2  4910.2  373.32  4916.6  372.46  4960.5  370.41
  4970.5  371.05  4980.6  370.83  4990.7  369.41  4997.7  369.38  5000.5  368.88
  5003.7  369.38  5010.8  371.44  5051.4  371.06  5071.8   373.7  5102.4  374.38
  5163.6  378.34  5194.2  379.21  5214.6  377.68  5224.8     378    5235  380.17
  5245.2  385.45  5255.4  387.85  5265.6  387.58  5273.3  385.12  5275.8  385.12
#Mann= 4 ,-1 , 0
  4568.1     .05       0  4916.6     .16       0  4997.7     .07       0
  5003.7     .16       0
Bank Sta=4970.5,5010.8
XS Rating Curve= 0 ,0
Exp/Cntr=0.3,0.1

Type RM Length L Ch R = 1 ,17607   ,487,487,487
BEGIN DESCRIPTION:
UNT073 IN CCTC 24.0
END DESCRIPTION:
XS GIS Cut Line= 3
      3523299.61     10656060.16      3523399.61     10655360.19
      3523349.61     10655110.21
#Sta/Elev= 30
  4272.5  385.99  4343.2  383.84  4413.9  382.82  4474.5  380.98  4565.4  380.27
  4658.6  378.06  4696.7  377.77  4767.4  374.32  4797.7   373.7  4828.1   372.2
  4908.9  370.16  4929.1  369.16  4979.6  369.37  4989.8  369.23    4997  367.98
  4999.7  367.48    5003  367.98  5020.4  371.31  5030.6  372.25  5040.8  374.68
    5051  375.91  5061.2  378.18  5091.8  380.61    5102  382.19  5123.3  384.01
  5163.1  386.75  5193.7   390.1  5203.9  390.64  5214.1  392.36  5234.5  394.06
#Mann= 5 ,-1 , 0
  4272.5     .05       0  4658.6     .16       0    4997     .07       0
    5003     .16       0  5123.3     .05       0
Bank Sta=4979.6,5020.4
XS Rating Curve= 0 ,0
Exp/Cntr=0.3,0.1

Type RM Length L Ch R = 1 ,17120   ,513,513,513
BEGIN DESCRIPTION:
UNT073 IN CCTC 23.0
END DESCRIPTION:
XS GIS Cut Line= 2
       3523994.9     10655770.43      3523552.21     10654997.88
#Sta/Elev= 30
  4528.9   383.2    4679  379.21  4736.6  376.49  4759.7  376.19  4827.1  373.37
  4854.5  371.52  4876.1  371.25  4902.2  369.46  4956.6  368.49  4966.7  367.56
  4988.3  366.74    4991  365.95  4993.8  365.45    4997  365.95  5015.6  368.02
  5037.2  367.33    5053  367.96  5074.6  370.35  5082.4  372.15    5112  374.48
  5133.6  375.36  5180.8  379.39  5257.3  385.09  5266.8   385.1  5278.9  386.67
  5294.7  386.66  5359.5  390.59  5391.1  391.58  5396.9  392.55  5419.3  393.16
#Mann= 5 ,-1 , 0
  4528.9     .05       0  4902.2     .16       0    4991     .07       0
    4997     .16       0  5180.8     .05       0
Bank Sta=4966.7,5015.6
XS Rating Curve= 0 ,0
Exp/Cntr=0.3,0.1

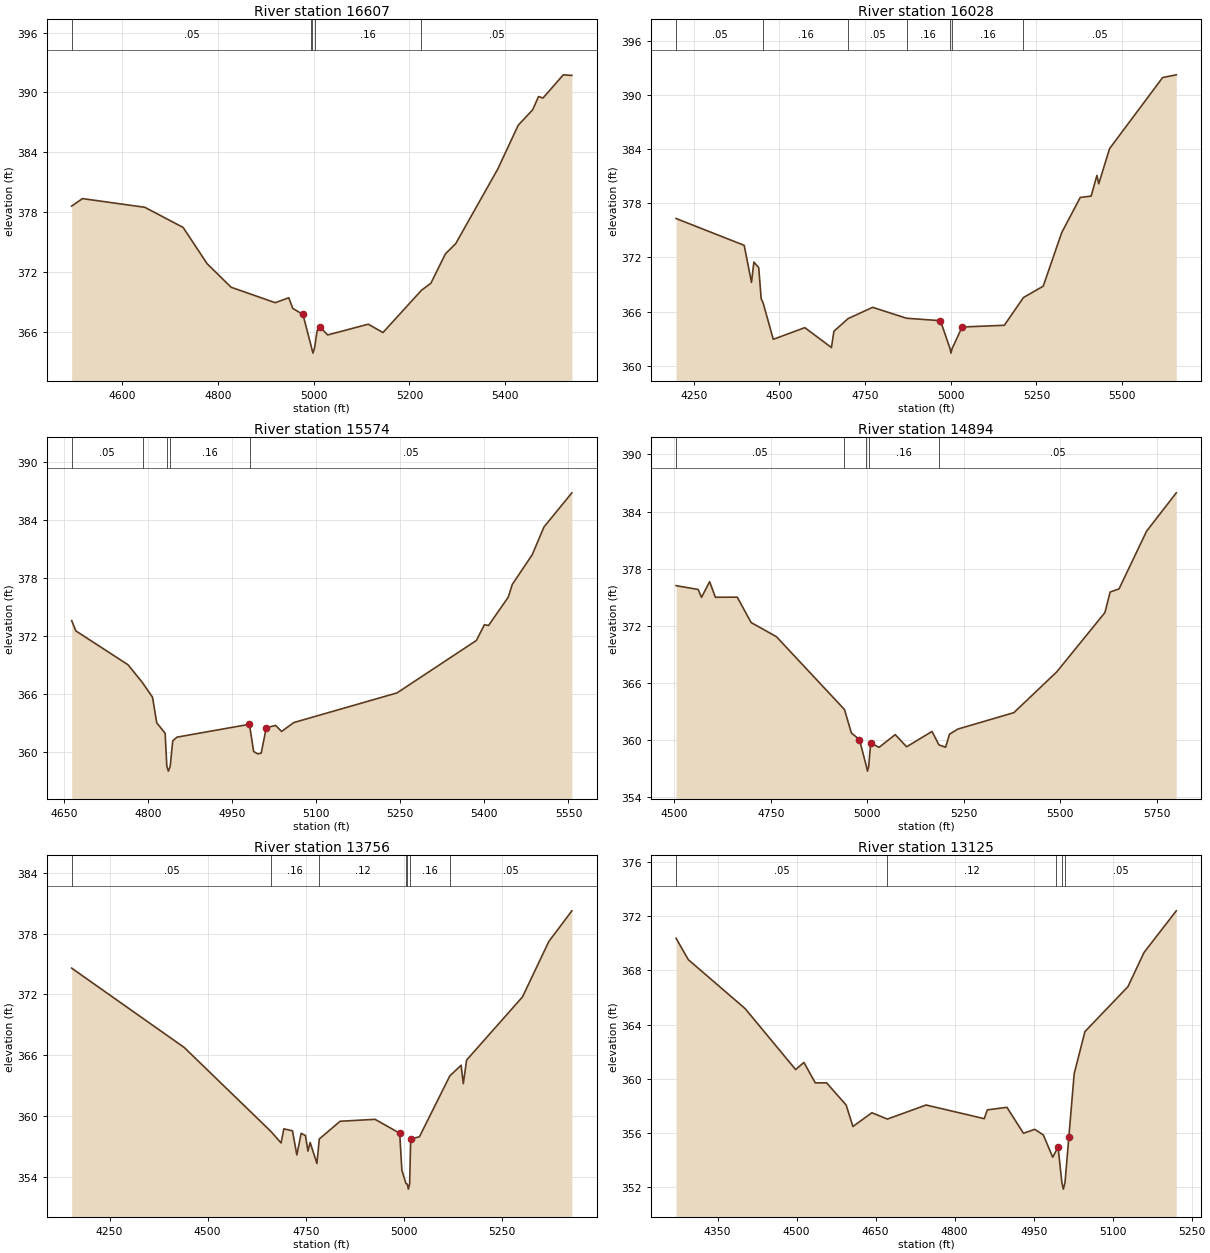
Type RM Length L Ch R = 1 ,16607   ,579,579,579
BEGIN DESCRIPTION:
UNT073 IN CCTC 22.0
END DESCRIPTION:
XS GIS Cut Line= 3
       3524198.9     10655722.67      3524185.88      10655336.4
      3523834.44     10654781.04
#Sta/Elev= 30
  4495.2  378.61  4517.7  379.36  4647.8  378.49  4727.8  376.47  4777.8  372.84
  4827.9  370.48    4920  368.93  4948.2  369.43  4956.5  368.36  4977.7  367.76
  4995.4   364.5  4995.9  364.38  4998.6  363.88  5001.9  364.38  5007.4  366.14
  5014.1  366.46  5029.4   365.7  5114.1  366.78  5144.7  365.94  5225.1  370.18
  5244.7  370.88  5275.2  373.84  5296.4  374.84  5384.6  382.35  5426.9  386.71
  5457.1  388.26  5469.3  389.58  5478.7  389.44    5521  391.76  5538.9   391.7
#Mann= 5 ,-1 , 0
  4495.2     .05       0  4995.4     .16       0  4995.9     .07       0
  5001.9     .16       0  5225.1     .05       0
Bank Sta=4977.7,5014.1
XS Rating Curve= 0 ,0
Exp/Cntr=0.3,0.1

Type RM Length L Ch R = 1 ,16028   ,454,454,454
BEGIN DESCRIPTION:
UNT073 IN CCTC 21.0
END DESCRIPTION:
XS GIS Cut Line= 3
      3524990.42     10655610.58      3524511.25      10655145.3
      3524219.58     10654409.18
#Sta/Elev= 30
  4198.4  376.31  4397.2  373.34  4418.5  369.24  4425.5  371.49  4439.6  370.87
  4446.8  367.43  4452.6  366.94  4482.1  362.94  4574.1  364.23  4651.8  362.03
    4659  363.83  4700.4  365.23    4772  366.48    4871  365.27  4969.9     365
  4997.9  361.91  5000.6  361.41  5003.9  361.91  5033.1   364.3  5156.3  364.49
  5212.1  367.56  5269.8  368.82  5323.8  374.75  5377.9  378.64  5409.6  378.79
  5426.5  381.08  5431.9  380.15  5463.4  384.04  5618.3  391.91  5658.1  392.21
#Mann= 7 ,-1 , 0
  4198.4     .05       0  4452.6     .16       0  4700.4     .05       0
    4871     .16       0  4997.9     .07       0  5003.9     .16       0
  5212.1     .05       0
Bank Sta=4969.9,5033.1
XS Rating Curve= 0 ,0
Exp/Cntr=0.3,0.1

Type RM Length L Ch R = 1 ,15574   ,680,680,680
BEGIN DESCRIPTION:
UNT073 IN CCTC 20.0
END DESCRIPTION:
XS GIS Cut Line= 3
      3524999.59     10655160.16      3524799.61     10654860.19
      3524449.63     10654460.21
#Sta/Elev= 30
  4664.1  373.56  4671.6   372.5  4764.7  368.99  4790.4  367.14  4808.3  365.63
  4815.8  362.98  4830.8   361.9  4833.8  358.48  4836.6  357.98  4839.8  358.48
  4844.3  361.11  4851.9   361.5  4981.1  362.83  4981.6  362.64  4988.6  360.01
  4996.1  359.76  5002.1  359.84  5011.1  362.48  5027.9  362.71  5038.4  362.09
  5060.2  363.01  5244.3  366.08  5385.8  371.51    5400  373.13  5407.6  373.07
  5442.7     376  5449.8  377.31  5485.4  380.39  5506.3  383.26  5556.1   386.8
#Mann= 5 ,-1 , 0
  4664.1     .05       0  4790.4     .16       0  4833.8    .035       0
  4839.8     .16       0  4981.6     .05       0
Bank Sta=4981.1,5011.1
XS Rating Curve= 0 ,0
Exp/Cntr=0.3,0.1

Type RM Length L Ch R = 1 ,14894   ,1138,1138,1138
BEGIN DESCRIPTION:
UNT073 IN CCTC 19.0
END DESCRIPTION:
XS GIS Cut Line= 3
      3525525.13       10655055.      3525184.86     10654561.96
      3524581.12     10654214.99
#Sta/Elev= 30
  4504.6  376.21  4561.7  375.81  4570.5  374.98  4591.5  376.63  4606.4  374.99
  4663.1     375    4699  372.33  4764.6  370.84  4940.7  363.19  4958.6  360.72
  4979.5  360.03  4997.5  357.21  5000.3  356.71  5003.5  357.21  5008.6  359.68
  5030.3  359.21  5072.2  360.55  5101.7  359.27  5167.4  360.88  5185.4  359.47
  5202.6  359.22  5212.7  360.59  5234.2  361.13  5379.5  362.86  5490.3  367.14
  5615.2  373.38  5628.7  375.54  5651.8  375.87    5723  381.93    5800  385.97
#Mann= 5 ,-1 , 0
  4504.6     .05       0  4940.7     .16       0  4997.5     .07       0
  5003.5     .16       0  5185.4     .05       0
Bank Sta=4979.5,5008.6
XS Rating Curve= 0 ,0
Exp/Cntr=0.3,0.1

Type RM Length L Ch R = 1 ,13756   ,631,631,631
BEGIN DESCRIPTION:
UNT073 IN CCTC 17.0
END DESCRIPTION:
XS GIS Cut Line= 3
      3525799.62     10654810.21      3525449.61     10654060.19
       3525249.6     10653660.18
#Sta/Elev= 30
  4153.5  374.59  4440.4  366.77  4661.5  358.49  4687.2  357.36  4694.3  358.75
  4716.3  358.56  4727.4  356.18  4738.4  358.31  4749.4  358.09  4755.7  356.56
  4761.3  357.41  4778.6  355.34  4784.6  357.75  4837.7   359.5  4926.8  359.69
  4989.6  358.32  4995.1  354.68  5005.5  353.36  5008.9  353.31  5011.7  352.81
  5014.9  353.31  5017.5  357.75  5039.9  357.97  5117.3  363.97  5146.1  365.02
  5151.7  363.21  5160.1  365.53  5302.6  371.76  5369.7  377.22  5428.4  380.24
#Mann= 7 ,-1 , 0
  4153.5     .05       0  4661.5     .16       0  4784.6     .12       0
  5005.5     .16       0  5008.9     .07       0  5014.9     .16       0
  5117.3     .05       0
Bank Sta=4989.6,5017.5
XS Rating Curve= 0 ,0
Exp/Cntr=0.3,0.1

Type RM Length L Ch R = 1 ,13125   ,444,444,444
BEGIN DESCRIPTION:
UNT073 IN CCTC 16.0
END DESCRIPTION:
XS GIS Cut Line= 3
      3526049.61      10654510.2      3525699.61     10653910.19
      3525649.61     10653660.17
#Sta/Elev= 30
  4271.1  370.38  4294.3   368.8  4402.2  365.18  4498.1  360.67  4513.8   361.2
  4535.3  359.69  4556.8  359.69    4594  358.05  4606.8  356.46  4642.8  357.48
  4672.2  357.01  4745.8  358.05  4856.2  357.04    4862  357.69  4899.2  357.88
  4930.6  355.96  4952.1  356.25  4968.3  355.84  4986.1  354.19  4991.7   354.6
  4996.3  354.94  5003.5  352.33  5006.3  351.83  5009.5  352.33  5016.7  355.66
  5026.9  360.37  5047.3  363.48  5128.9   366.8  5159.5  369.33  5220.7  372.41
#Mann= 5 ,-1 , 0
  4271.1     .05       0  4672.2     .12       0  4991.7     .05       0
  5003.5     .03       0  5009.5     .05       0
Bank Sta=4996.3,5016.7
XS Rating Curve= 0 ,0
Exp/Cntr=0.3,0.1

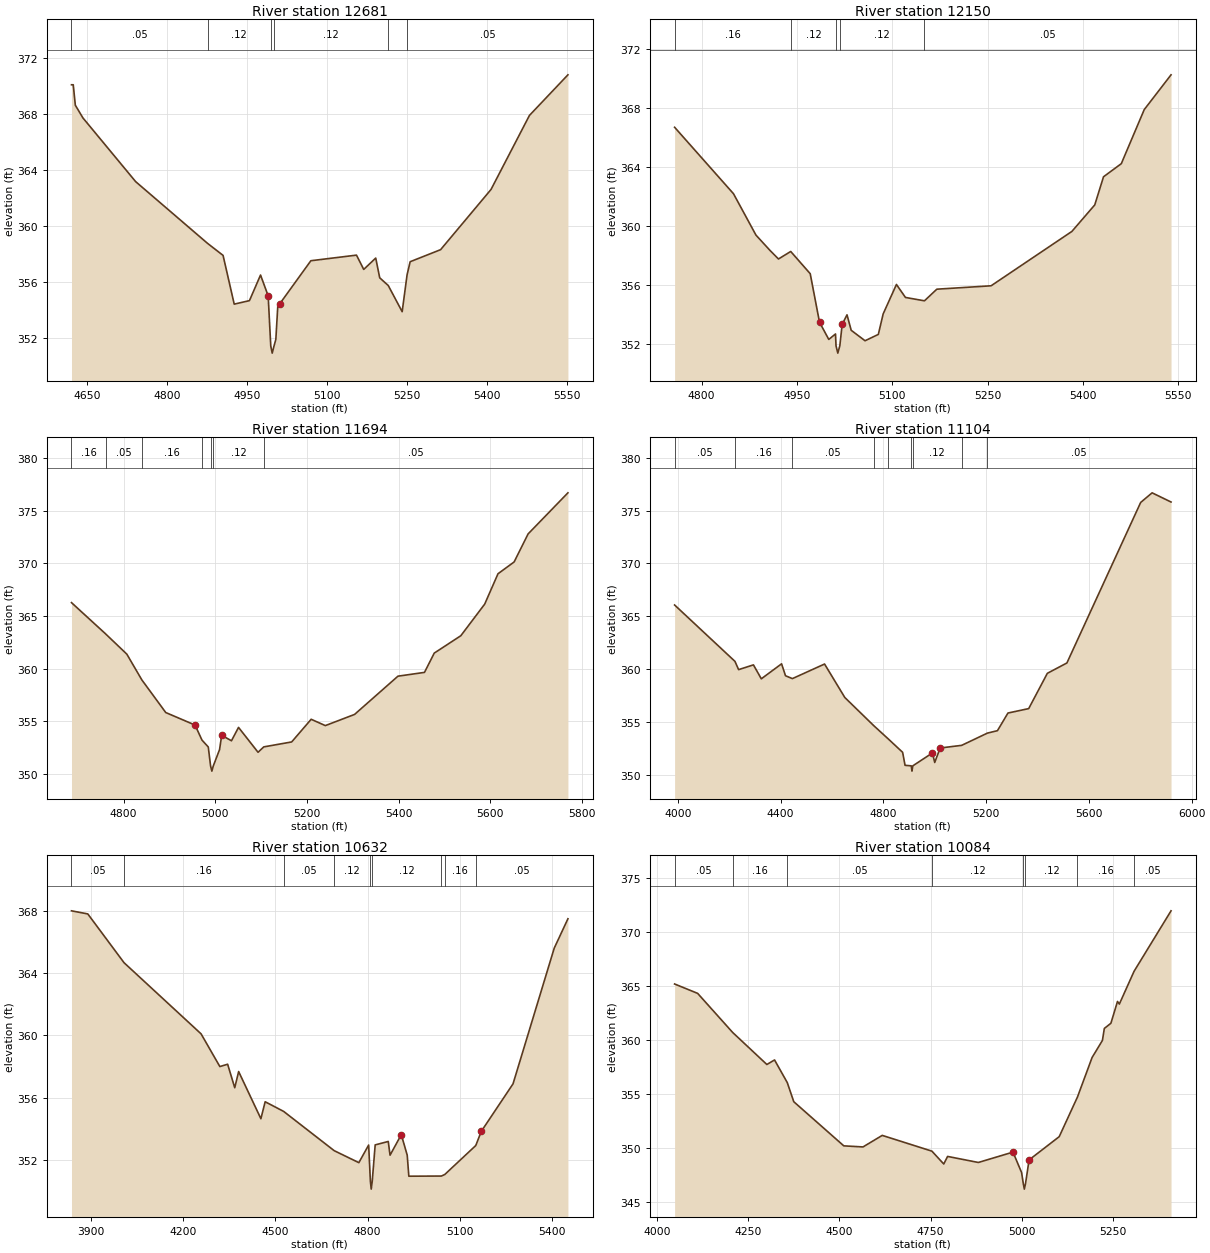
Type RM Length L Ch R = 1 ,12681   ,531,531,531
BEGIN DESCRIPTION:
UNT073 IN CCTC 15.0
END DESCRIPTION:
XS GIS Cut Line= 3
      3526299.61     10654360.19      3526049.61     10654060.19
      3525749.58     10653610.15
#Sta/Elev= 30
  4620.9  370.08  4624.2  370.08  4628.1  368.62  4642.4  367.71  4741.3  363.16
  4876.2  358.75  4905.3  357.89  4926.2  354.41  4954.8  354.66  4975.6  356.49
  4989.9     355  4994.8  351.41  4997.5  350.91  5000.8  351.41  5004.3  351.89
  5008.2  354.42  5011.4  354.42    5070  357.51  5155.6  357.91  5169.2  356.89
  5191.7   357.7  5199.2  356.29  5215.2  355.74  5241.3  353.87  5250.5   356.5
  5256.3  357.44  5313.4   358.3    5408   362.6  5480.1  367.89  5552.3  370.79
#Mann= 6 ,-1 , 0
  4620.9     .05       0  4876.2     .12       0  4994.8     .07       0
  5000.8     .12       0  5215.2     .16       0  5250.5     .05       0
Bank Sta=4989.9,5011.4
XS Rating Curve= 0 ,0
Exp/Cntr=0.3,0.1

Type RM Length L Ch R = 1 ,12150   ,456,456,456
BEGIN DESCRIPTION:
UNT073 IN CCTC 14.0
END DESCRIPTION:
XS GIS Cut Line= 3
      3526599.61     10654060.19      3526449.61     10653860.19
      3526099.62      10653460.2
#Sta/Elev= 30
  4757.4  366.68  4850.1  362.17  4885.5  359.36  4907.4  358.33  4920.9  357.74
  4940.2  358.25  4970.9  356.74  4985.5  353.45  5000.1  352.28  5010.7  352.65
  5011.5  351.85  5014.3  351.35  5017.5  351.85  5021.2   353.3  5028.8  353.95
  5035.4   352.9  5057.2  352.19  5078.1  352.62  5085.7  354.01  5106.6  356.01
  5120.8  355.13  5150.7   354.9  5170.2  355.69  5255.6  355.92  5382.8  359.61
  5418.8  361.41  5432.6  363.32  5460.6  364.21  5496.7  367.88  5538.9  370.24
#Mann= 5 ,-1 , 0
  4757.4     .16       0  4940.2     .12       0  5011.5     .07       0
  5017.5     .12       0  5150.7     .05       0
Bank Sta=4985.5,5021.2
XS Rating Curve= 0 ,0
Exp/Cntr=0.3,0.1

Type RM Length L Ch R = 1 ,11694   ,590,590,590
BEGIN DESCRIPTION:
UNT073 IN CCTC 13.0
END DESCRIPTION:
XS GIS Cut Line= 3
      3526949.59     10653860.16      3526749.61     10653610.19
      3526099.64     10653210.21
#Sta/Elev= 30
  4686.4  366.27  4760.7  363.31  4807.2  361.38  4839.9  358.94  4892.1  355.84
  4956.1  354.65  4971.1  353.23  4984.9  352.57  4989.9  350.78  4992.7  350.28
  4995.9  350.78  5009.5  352.32  5014.2  353.68  5035.5  353.16  5050.9  354.43
  5093.5  352.07    5106  352.58  5166.9  353.05  5209.4   355.2  5240.3   354.6
  5304.1  355.66  5398.8  359.29  5456.7  359.65    5478  361.48    5536  363.13
  5588.1  366.13  5617.1  369.01  5652.3  370.13  5682.8  372.79  5769.7  376.69
#Mann= 7 ,-1 , 0
  4686.4     .16       0  4760.7     .05       0  4839.9     .16       0
  4971.1     .12       0  4989.9     .07       0  4995.9     .12       0
    5106     .05       0
Bank Sta=4956.1,5014.2
XS Rating Curve= 0 ,0
Exp/Cntr=0.3,0.1

Type RM Length L Ch R = 1 ,11104   ,472,472,472
BEGIN DESCRIPTION:
UNT073 IN CCTC 12.0
END DESCRIPTION:
XS GIS Cut Line= 3
       3527474.6     10654120.08      3526886.03     10653182.54
       3526078.7     10653010.65
#Sta/Elev= 30
  3987.4  366.06  4222.4  360.72  4236.5  359.94  4294.3  360.39  4324.9  359.07
  4403.8  360.49  4419.1  359.36    4446  359.09  4571.1  360.47    4650   357.3
  4762.4  354.64  4819.9  353.36    4875  352.11  4884.4  350.88  4908.6  350.83
  4911.3  350.33  4914.6  350.83  4990.9  352.05  4999.9  351.15  5021.1  352.52
  5104.8  352.77  5205.1  353.93  5244.1  354.16    5285  355.83  5365.7  356.25
  5438.3  359.59  5514.4  360.57  5801.6  375.77  5846.1  376.68  5919.8  375.81
#Mann= 9 ,-1 , 0
  3987.4     .05       0  4222.4     .16       0    4446     .05       0
  4762.4     .16       0  4819.9     .12       0  4908.6     .07       0
  4914.6     .12       0  5104.8     .16       0  5205.1     .05       0
Bank Sta=4990.9,5021.1
XS Rating Curve= 0 ,0
Exp/Cntr=0.3,0.1

Type RM Length L Ch R = 1 ,10632   ,548,548,548
BEGIN DESCRIPTION:
UNT073 IN CCTC 11.0
END DESCRIPTION:
XS GIS Cut Line= 3
      3527599.62     10654160.21      3527199.61     10653060.19
      3526999.61     10652660.19
#Sta/Elev= 30
  3835.4  367.99  3888.6  367.79  4006.6  364.66  4257.7  360.09  4318.9  357.99
  4344.2  358.14  4367.4  356.63  4380.1  357.67  4452.6  354.64  4466.5  355.73
  4526.8  355.11  4691.4  352.59  4771.8  351.82  4803.7  352.95  4809.4  350.62
  4812.1  350.12  4815.4  350.62    4825  352.96  4867.6  353.18  4873.5   352.3
  4910.1  353.62  4929.4   352.3  4934.7  350.95    5041  350.96  5051.8  351.06
  5152.8  352.92  5170.8  353.83  5274.2  356.88  5408.4  365.59  5453.1  367.48
#Mann= 9 ,-1 , 0
  3835.4     .05       0  4006.6     .16       0  4526.8     .05       0
  4691.4     .12       0  4809.4     .07       0  4815.4     .12       0
    5041     .05       0  5051.8     .16       0  5152.8     .05       0
Bank Sta=4910.1,5170.8
XS Rating Curve= 0 ,0
Exp/Cntr=0.3,0.1

Type RM Length L Ch R = 1 ,10084   ,566,566,566
BEGIN DESCRIPTION:
UNT073 IN CCTC 10.0
END DESCRIPTION:
XS GIS Cut Line= 3
      3527799.59     10653760.14      3527499.61     10652860.19
      3527399.62     10652460.23
#Sta/Elev= 30
  4048.5   365.2  4111.7  364.33  4207.6  360.71  4301.4  357.74  4322.5  358.16
  4357.4  356.06  4375.2  354.29  4512.3   350.2    4565   350.1  4617.7  351.17
  4753.8  349.71  4786.3  348.52  4796.9  349.22  4881.2  348.66  4976.1  349.62
  4999.7  347.73  5004.4  346.69  5007.2  346.19  5010.4  346.69  5020.3   348.9
  5102.8  351.05  5152.8  354.72    5193  358.39  5221.3  359.97  5226.5  361.08
  5244.5  361.56  5262.6  363.58  5267.7  363.34  5308.1  366.38  5409.4  371.98
#Mann= 8 ,-1 , 0
  4048.5     .05       0  4207.6     .16       0  4357.4     .05       0
  4753.8     .12       0  5004.4     .07       0  5010.4     .12       0
  5152.8     .16       0  5308.1     .05       0
Bank Sta=4976.1,5020.3
XS Rating Curve= 0 ,0
Exp/Cntr=0.3,0.1

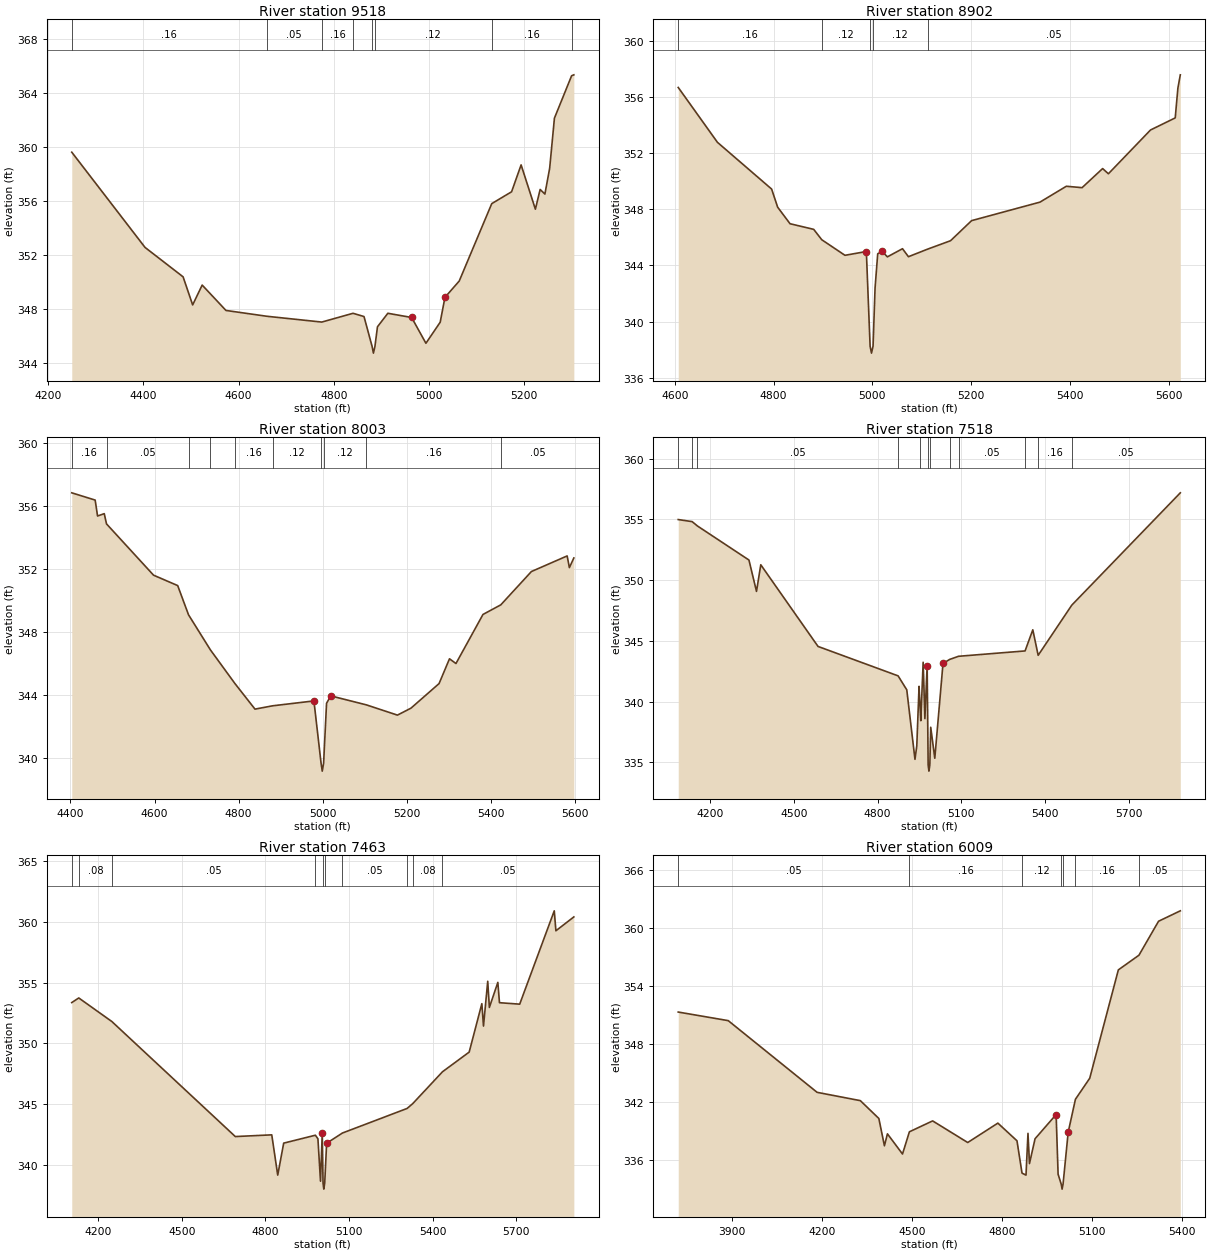
Type RM Length L Ch R = 1 ,9518    ,616,616,616
BEGIN DESCRIPTION:
UNT073 IN CCTC 9.0
END DESCRIPTION:
XS GIS Cut Line= 2
      3527958.95     10653584.08      3527935.51     10652529.44
#Sta/Elev= 30
  4249.6  359.64  4403.5  352.59  4483.5  350.41  4503.6  348.33  4523.6   349.8
  4573.6  347.92  4659.4  347.49  4774.9  347.06  4840.6  347.71  4863.6  347.47
  4880.6  345.26  4883.4  344.76  4886.6  345.26  4891.9  346.71  4913.7  347.71
  4963.7   347.4  4993.7  345.49  5023.7  347.05  5033.7  348.89  5063.7   350.1
    5132  355.83  5173.7  356.71  5193.7   358.7  5223.7  355.42  5233.7  356.88
  5243.7  356.54  5253.7  358.45  5263.7  362.16  5299.8   365.3  5304.5  365.37
#Mann= 8 ,-1 , 0
  4249.6     .16       0  4659.4     .05       0  4774.9     .16       0
  4840.6     .12       0  4880.6     .07       0  4886.6     .12       0
    5132     .16       0  5299.8     .05       0
Bank Sta=4963.7,5033.7
XS Rating Curve= 0 ,0
Exp/Cntr=0.3,0.1

Type RM Length L Ch R = 1 ,8902    ,899,899,899
BEGIN DESCRIPTION:
UNT073 IN CCTC 8.0
END DESCRIPTION:
XS GIS Cut Line= 2
      3528146.45     10653547.65      3528497.41     10652593.55
#Sta/Elev= 30
  4607.1  356.68  4686.5  352.77  4796.2  349.44  4808.4  348.15  4833.5  346.97
  4881.4  346.57  4897.7  345.83  4944.7  344.72    4988  344.99  4995.6  338.25
  4998.4  337.75  5001.6  338.25  5005.6  342.37    5011  344.83  5019.9     345
  5030.6  344.61  5061.2  345.19  5073.2  344.62  5112.1  345.16  5158.5  345.76
  5201.1  347.19  5339.6  348.51  5392.9  349.64  5424.8  349.54  5466.4   350.9
  5478.1  350.53  5563.4  353.65  5613.4  354.51  5618.8  356.63  5623.7  357.58
#Mann= 5 ,-1 , 0
  4607.1     .16       0  4897.7     .12       0  4995.6     .07       0
  5001.6     .12       0  5112.1     .05       0
Bank Sta=4988,5019.9
XS Rating Curve= 0 ,0
Exp/Cntr=0.3,0.1

Type RM Length L Ch R = 1 ,8003    ,485,485,485
BEGIN DESCRIPTION:
UNT073 IN CCTC 7.0
END DESCRIPTION:
XS GIS Cut Line= 4
      3528485.01     10653719.49       3528737.6      10653271.6
      3528734.99     10653141.39      3528539.67     10652628.35
#Sta/Elev= 30
  4403.3  356.82  4458.9  356.36  4464.6  355.35  4480.5   355.5  4485.9  354.85
  4597.7   351.6  4655.1  350.94  4680.8  349.09    4733  346.86  4790.9  344.74
  4838.8  343.11  4880.7  343.32  4978.9  343.63  4995.9  339.68  4998.7  339.18
  5001.9  339.68  5008.9  343.48  5018.9  343.95  5103.5  343.38  5177.4  342.73
  5209.5  343.17  5276.4  344.73  5301.1   346.3  5316.5     346  5380.7  349.11
  5423.1  349.72  5495.8  351.83  5580.8  352.82  5586.1  352.08  5596.7  352.69
#Mann= 10 ,-1 , 0
  4403.3     .16       0  4485.9     .05       0  4680.8     .16       0
    4733     .05       0  4790.9     .16       0  4880.7     .12       0
  4995.9     .07       0  5001.9     .12       0  5103.5     .16       0
  5423.1     .05       0
Bank Sta=4978.9,5018.9
XS Rating Curve= 0 ,0
Exp/Cntr=0.3,0.1

Type RM Length L Ch R = 1 ,7518    ,55,55,55
BEGIN DESCRIPTION:
UNT073 IN CCTC 6.0
END DESCRIPTION:
XS GIS Cut Line= 6
       3529552.5     10654045.83      3529340.68     10653712.46
      3529188.33     10653441.63      3529151.88     10653353.09
      3528935.73     10653064.03      3528574.09     10652540.64
#Sta/Elev= 30
  4085.9  354.99  4135.7  354.82  4154.9  354.46  4339.2  351.66  4366.3  349.08
  4381.6  351.27  4586.7  344.55  4873.5  342.13  4904.6  340.98    4934  335.26
  4940.5  336.37  4948.6  341.27  4951.7  339.86  4954.8  338.44  4963.3  343.25
  4969.5  338.61  4977.6  342.98  4981.2  334.79  4983.9  334.29  4987.2  334.79
  4990.4   337.9    5005  335.35  5034.4  343.15  5058.1  343.48  5090.1  343.74
  5328.4  344.18  5356.1  345.92  5375.3  343.82  5495.8  347.95  5884.5  357.19
#Mann= 12 ,-1 , 0
  4085.9     .05       0  4135.7     .08       0  4154.9     .05       0
  4873.5     .12       0  4951.7     .08       0  4981.2     .07       0
  4987.2     .08       0  5058.1     .12       0  5090.1     .05       0
  5328.4     .08       0  5375.3     .16       0  5495.8     .05       0
Bank Sta=4977.6,5034.4
XS Rating Curve= 0 ,0
Exp/Cntr=0.3,0.1

Type RM Length L Ch R = 1 ,7463    ,1454,1454,1454
BEGIN DESCRIPTION:
UNT073 IN CCTC 5.0
END DESCRIPTION:
XS GIS Cut Line= 4
      3529610.89     10654027.82      3529229.57     10653425.14
      3529095.02     10653197.27       3528647.7      10652504.2
#Sta/Elev= 30
  4104.5  353.36  4129.6  353.74  4248.6   351.8  4691.7  342.35  4822.6  342.49
    4844  339.18  4865.4  341.81  4979.2  342.46  4988.3  342.17  4997.6  338.68
  5003.9  342.66  5006.7  338.53  5009.5  338.03  5012.7  338.53  5019.6   341.8
  5076.3  342.64  5308.6  344.66  5328.9  345.06  5435.4  347.67  5531.4  349.29
  5576.9  353.27  5582.8  351.43    5598  355.11  5603.9  352.96  5634.3  355.02
  5640.2  353.35  5712.8  353.23  5836.9   360.9  5842.8  359.26  5907.2   360.4
#Mann= 10 ,-1 , 0
  4104.5     .05       0  4129.6     .08       0  4248.6     .05       0
  4979.2     .08       0  5006.7     .07       0  5012.7     .08       0
  5076.3     .05       0  5308.6     .16       0  5328.9     .08       0
  5435.4     .05       0
Bank Sta=5003.9,5019.6
XS Rating Curve= 0 ,0
Exp/Cntr=0.3,0.1

Type RM Length L Ch R = 1 ,6009    ,603,603,603
BEGIN DESCRIPTION:
UNT073 IN CCTC 4.0
END DESCRIPTION:
XS GIS Cut Line= 2
      3530110.86     10654324.65      3529944.19     10652657.96
#Sta/Elev= 30
  3719.6  351.31  3886.4  350.42  4182.9  342.99  4327.1  342.13  4388.9  340.28
  4407.5  337.45  4417.5  338.69  4467.8   336.6  4490.8   338.9  4568.3  340.03
  4685.4  337.79  4785.9   339.8  4849.7  337.97  4866.5  334.62  4879.8  334.41
  4886.4  338.74  4891.4  335.61    4910  338.18  4980.3  340.69  4986.9  334.51
  4997.4  333.46  5000.2  332.96  5003.4  333.46  5020.5  338.85  5044.7  342.27
  5092.4  344.45  5187.9  355.68  5256.6   357.2    5322  360.72  5394.6   361.8
#Mann= 7 ,-1 , 0
  3719.6     .05       0  4490.8     .16       0  4866.5     .12       0
  4997.4     .07       0  5003.4     .12       0  5044.7     .16       0
  5256.6     .05       0
Bank Sta=4980.3,5020.5
XS Rating Curve= 0 ,0
Exp/Cntr=0.3,0.1

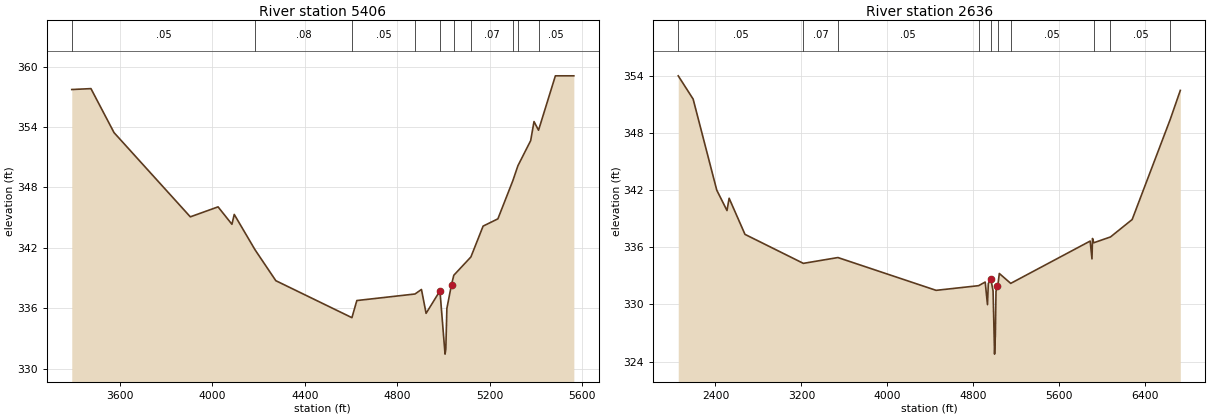
Type RM Length L Ch R = 1 ,5406    ,2770,2770,2770
BEGIN DESCRIPTION:
UNT073 IN CCTC 3.0
END DESCRIPTION:
XS GIS Cut Line= 3
      3530556.61     10654713.13       3530513.2     10653046.45
        3530192.     10652655.79
#Sta/Elev= 30
  3391.9  357.72  3474.9  357.81  3574.9  353.44    3905  345.08  4025.1  346.07
  4085.1  344.34  4095.1  345.32  4185.1  341.81  4275.1  338.74  4604.4  335.07
  4625.7  336.77  4877.4  337.42  4905.4  337.87  4925.4   335.5  4985.4  337.73
  5007.5  331.45  5010.8  331.95  5015.4  335.99  5035.4  338.35  5045.4  339.28
  5119.4   341.1  5172.2  344.16  5236.1  344.88  5300.4  348.64  5322.8  350.15
  5378.1  352.65  5392.5  354.54  5412.1  353.68    5485  359.08  5564.9  359.08
#Mann= 10 ,-1 , 0
  3391.9     .05       0  4185.1     .08       0  4604.4     .05       0
  4877.4     .08       0  4985.4     .05       0  5045.4     .08       0
  5119.4     .07       0  5300.4     .05       0  5322.8     .16       0
  5412.1     .05       0
Bank Sta=4985.4,5035.4
XS Rating Curve= 0 ,0
Exp/Cntr=0.3,0.1

Type RM Length L Ch R = 1 ,2636    ,0,0,0
BEGIN DESCRIPTION:
UNT073 IN CCTC 2.0
END DESCRIPTION:
XS GIS Cut Line= 4
      3530760.36     10654682.66      3531494.11     10652334.64
      3530929.87     10651987.42      3529384.76     10652152.35
#Sta/Elev= 30
  2053.2  353.98    2192  351.54    2412  341.99  2507.4  339.85  2527.2  341.14
    2675  337.35  3218.7  334.31  3540.4  334.92    4455  331.48    4851  331.97
  4912.3  332.35  4933.6  329.98  4941.2  332.19  4964.4  332.68  4985.7  331.42
  4999.6  324.79    5007  326.78  5012.9  331.36  5022.4  331.95  5028.3  331.81
  5043.7  333.25    5150  332.21    5890  336.65  5906.8  334.78  5911.8  336.92
  5923.3  336.47  6079.3  337.08  6281.2  338.91  6635.1  349.39  6729.6  352.45
#Mann= 10 ,-1 , 0
  2053.2     .05       0  3218.7     .07       0  3540.4     .05       0
    4851     .05       0  4964.4     .03       0  5028.3     .05       0
    5150     .05       0  5923.3     .08       0  6079.3     .05       0
  6635.1     .16       0
Bank Sta=4964.4,5022.4
XS Rating Curve= 0 ,0
Exp/Cntr=0.3,0.1

Chan Stop Cuts=-1
Use User Specified Reach Order=0
Composite Channel Slope=5