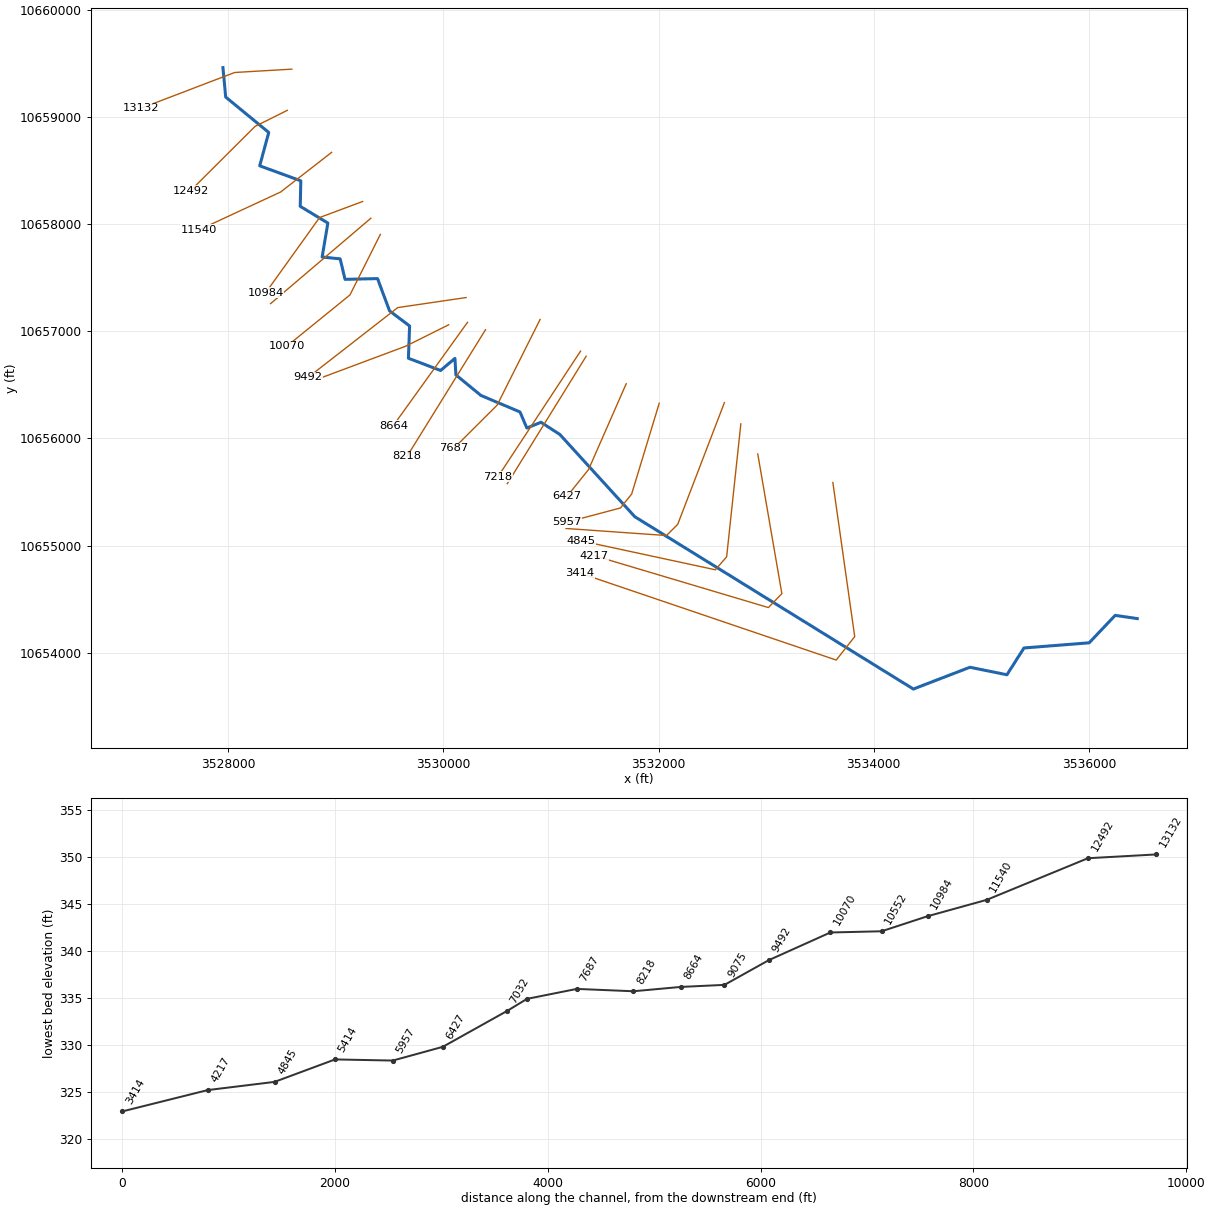
--- UNT074 IN CCTC.prj (project) ---

Proj Title=UNT074 IN CCTC Base Level Engineering
Current Plan=p01
Default Exp/Contr=0.3,0.1
English Units
Geom File=g01
Flow File=f01
Plan File=p01
Y Axis Title=Elevation
X Axis Title(PF)=Main Channel Distance
X Axis Title(XS)=Station
BEGIN DESCRIPTION:
UNT074 IN CCTC
END DESCRIPTION:
DSS Export Rating Curves= 0
DSS Export Rating Curve Sorted= 0
DSS Export Volume Flow Curves= 0
DXF OffsetX= 0
DXF OffsetY= 0
DXF ScaleX= 1
DXF ScaleY= 10

--- UNT074 IN CCTC.p01 (plan) ---

Plan Title=Multiple Run
Short Identifier=Multiple
Geom File=g01
Flow File=f01
Subcritical Flow
K Sum by GR= 0
Std Step Tol= 0.01
Critical Tol= 0.01
Num of Std Step Trials= 20
Max Error Tol= 0.3
Flow Tol Ratio= 0.001
Split Flow NTrial= 30
Split Flow Tol= 0.02
Split Flow Ratio= 0.02
Log Output Level= 0
Friction Slope Method= 1
Unsteady Friction Slope Method= 2
Unsteady Bridges Friction Slope Method= 1
Parabolic Critical Depth
Global Vel Dist=  1 , 1 , 1
Global Log Level= 0
CheckData=True
Encroach Param= -1, 0, 0, 0
BEGIN DESCRIPTION:
Multiple Run
END DESCRIPTION:

--- UNT074 IN CCTC.f01 (steady flow) ---

Flow Title=Multiple
Number of Profiles=7
Profile Names=10-year,25-year,50-year,1pct_min,100-year,1pct_plu,500-year
River Rch & RM= UNT074 IN CCTC,Reach-1,13132
    1086    1472    1784    1578    2135    2887    3047
River Rch & RM= UNT074 IN CCTC,Reach-1,10984
    1690    2338    2873    2571    3478    4703    5084
River Rch & RM= UNT074 IN CCTC,Reach-1,4845
    1895    2626    3230    2892    3911    5289    5722
Boundary for River Rch & Prof#=UNT074 IN CCTC,Reach-1,1
Up Type=0
Dn Type=3
Dn Slope=0.005
Boundary for River Rch & Prof#=UNT074 IN CCTC,Reach-1,2
Up Type=0
Dn Type=3
Dn Slope=0.005
Boundary for River Rch & Prof#=UNT074 IN CCTC,Reach-1,3
Up Type=0
Dn Type=3
Dn Slope=0.005
Boundary for River Rch & Prof#=UNT074 IN CCTC,Reach-1,4
Up Type=0
Dn Type=3
Dn Slope=0.005
Boundary for River Rch & Prof#=UNT074 IN CCTC,Reach-1,5
Up Type=0
Dn Type=3
Dn Slope=0.005
Boundary for River Rch & Prof#=UNT074 IN CCTC,Reach-1,6
Up Type=0
Dn Type=3
Dn Slope=0.005
Boundary for River Rch & Prof#=UNT074 IN CCTC,Reach-1,7
Up Type=0
Dn Type=3
Dn Slope=0.005

--- UNT074 IN CCTC.g01 (geometry) ---

Geom Title=Existing Conditions

River Reach=UNT074 IN CCTC,Reach-1
Reach XY= 30
      3527951.48     10659458.82      3527977.25     10659184.00
      3528377.25     10658854.00      3528293.25     10658543.00
      3528675.25     10658403.00      3528670.00     10658165.00
      3528926.50     10658009.00      3528873.50     10657692.00
      3529041.00     10657675.00      3529086.25     10657484.00
      3529388.50     10657491.00      3529500.25     10657190.00
      3529686.50     10657049.00      3529675.50     10656748.00
      3529974.50     10656634.00      3530107.75     10656747.00
      3530116.75     10656593.00      3530349.50     10656401.00
      3530713.00     10656247.00      3530776.00     10656097.00
      3530908.00     10656151.00      3531083.00     10656037.00
      3531779.75     10655270.00      3534368.50     10653663.00
      3534894.25     10653866.00      3535238.25     10653796.00
      3535396.75     10654046.00      3536002.50     10654094.00
      3536244.25     10654350.00      3536449.50     10654320.00

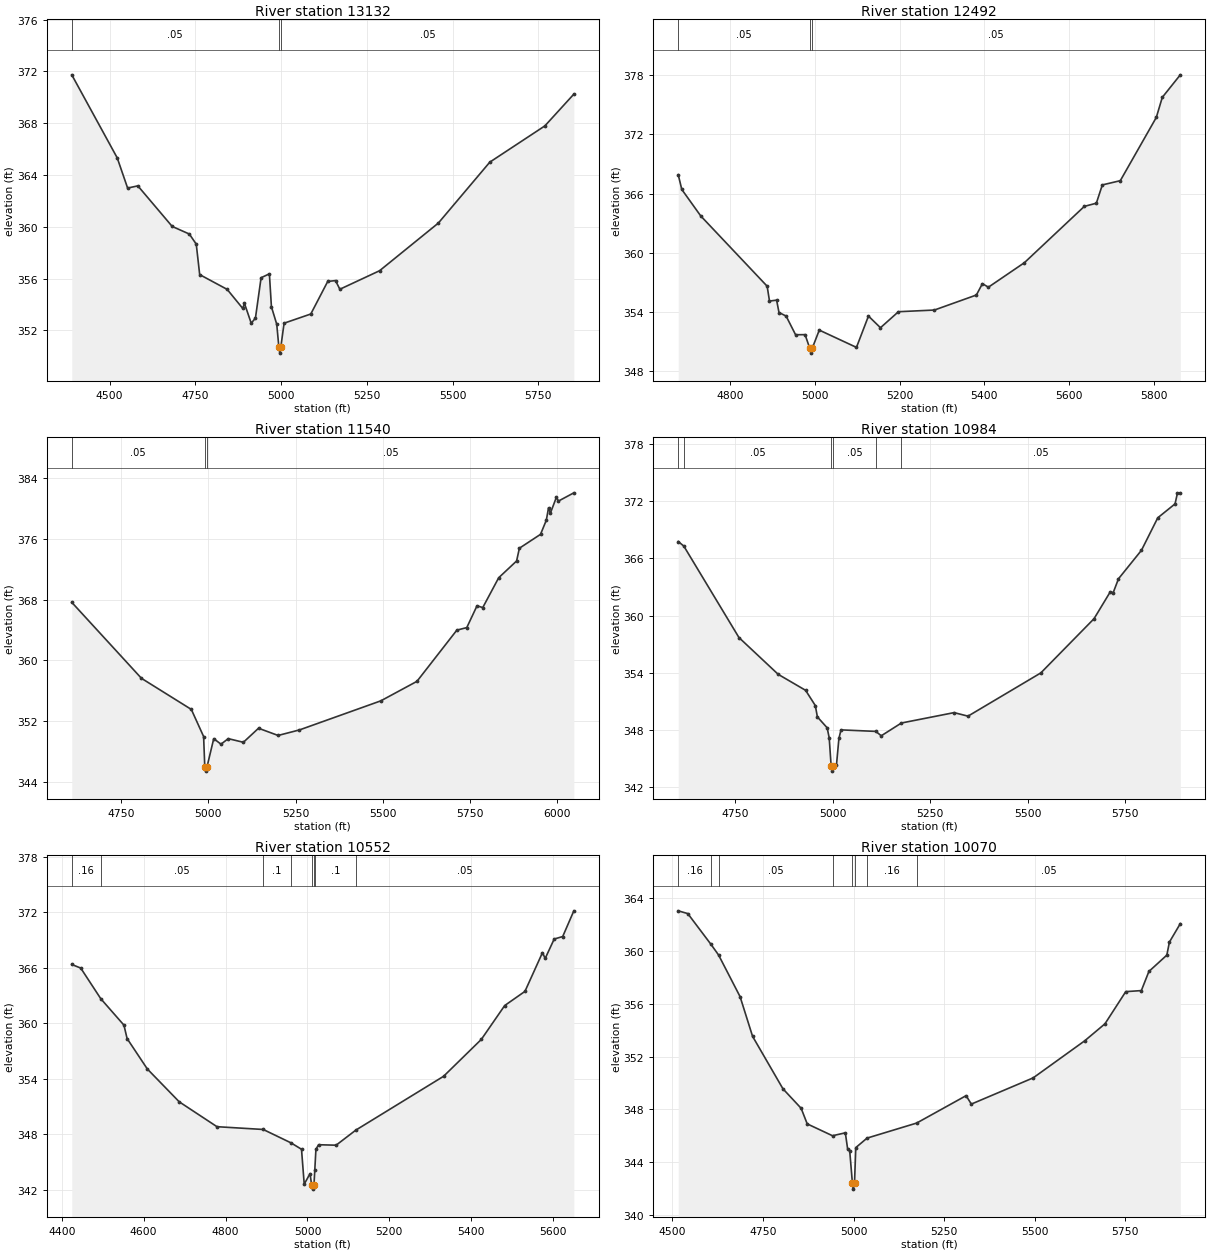
Type RM Length L Ch R = 1,13132,640,640,640
BEGIN DESCRIPTION:
UNT074 IN CCTC 19.0
END DESCRIPTION:
XS GIS Cut Line= 3
      3528591.83     10659444.47      3528060.62     10659413.22
      3527190.84     10659079.89
#Sta/Elev= 30
  4389.7  371.73  4522.2  365.32  4552.5  362.99  4582.3  363.16  4682.4  360.03
  4732.5  359.44  4752.6  358.66  4762.6  356.31  4842.7  355.17  4888.1  353.70
  4893.1  354.09  4912.8  352.56  4925.1  352.95  4941.6  356.07  4965.8  356.37
  4971.7  353.83  4987.2  352.48  4993.3  350.75  4996.1  350.25  4999.3  350.75
  5008.6  352.56  5086.5  353.27  5135.8  355.78  5158.5  355.85  5171.2  355.18
  5287.0  356.61  5458.4  360.29  5608.3  364.99  5768.9  367.79  5853.3  370.24
#Mann=3,-1,0
  4389.7    0.05       0  4993.3    0.03       0  4999.3    0.05       0
Bank Sta=4993.3,4999.3
Exp/Cntr=0.3,0.1

Type RM Length L Ch R = 1,12492,952,952,952
BEGIN DESCRIPTION:
UNT074 IN CCTC 18.0
END DESCRIPTION:
XS GIS Cut Line= 3
      3528549.63     10659060.20      3528249.61     10658910.19
      3527649.58     10658310.16
#Sta/Elev= 30
  4678.0  367.90  4686.4  366.41  4731.1  363.73  4887.7  356.62  4893.2  355.12
  4910.0  355.21  4915.6  353.96  4932.4  353.60  4954.7  351.71  4977.1  351.72
  4988.1  350.35  4990.8  349.85  4994.1  350.35  5010.6  352.18  5098.3  350.43
  5126.6  353.60  5154.9  352.42  5197.3  354.04  5282.1  354.21  5381.1  355.73
  5395.3  356.88  5409.4  356.52  5494.3  359.00  5635.7  364.70  5664.0  365.02
  5678.1  366.87  5720.5  367.30  5805.4  373.70  5819.5  375.73  5862.0  378.01
#Mann=3,-1,0
  4678.0    0.05       0  4988.1    0.03       0  4994.1    0.05       0
Bank Sta=4988.1,4994.1
Exp/Cntr=0.3,0.1

Type RM Length L Ch R = 1,11540,556,556,556
BEGIN DESCRIPTION:
UNT074 IN CCTC 16.0
END DESCRIPTION:
XS GIS Cut Line= 3
      3528961.64     10658668.41      3528487.71     10658298.64
      3527728.07     10657944.84
#Sta/Elev= 30
  4608.4  367.66  4808.1  357.65  4951.1  353.55  4986.3  349.98  4989.7  345.92
  4992.4  345.42  4995.7  345.92  5015.3  349.70  5036.1  348.97  5056.9  349.70
  5100.3  349.22  5143.7  351.07  5199.8  350.12  5261.1  350.85  5494.2  354.68
  5597.8  357.25  5712.2  364.00  5740.6  364.33  5770.0  367.21  5786.4  366.97
  5832.1  370.90  5883.4  373.11  5891.4  374.79  5952.0  376.62  5968.6  378.48
  5974.9  380.11  5980.4  379.43  5997.7  381.53  6003.2  381.00  6047.5  382.09
#Mann=3,-1,0
  4608.4    0.05       0  4989.7   0.035       0  4995.7    0.05       0
Bank Sta=4989.7,4995.7
Exp/Cntr=0.3,0.1

Type RM Length L Ch R = 1,10984,432,432,432
BEGIN DESCRIPTION:
UNT074 IN CCTC 15.0
END DESCRIPTION:
XS GIS Cut Line= 3
      3529249.57     10658210.17      3528849.61     10658060.19
      3528349.60     10657360.18
#Sta/Elev= 30
  4604.1  367.78  4618.4  367.30  4759.8  357.70  4860.4  353.84  4930.7  352.16
  4955.6  350.56  4960.9  349.37  4985.9  348.23  4991.2  347.18  4996.2  344.18
  4999.0  343.68  5002.2  344.18  5009.9  344.35  5016.1  347.11  5021.5  348.01
  5110.7  347.85  5124.7  347.39  5176.3  348.73  5311.4  349.82  5347.1  349.45
  5533.9  353.99  5670.3  359.68  5712.1  362.51  5719.4  362.41  5733.0  363.87
  5791.9  366.86  5833.7  370.27  5878.0  371.73  5884.1  372.85  5891.5  372.89
#Mann=6,-1,0
  4604.1    0.16       0  4618.4    0.05       0  4996.2   0.035       0
  5002.2    0.05       0  5110.7     0.1       0  5176.3    0.05       0
Bank Sta=4996.2,5002.2
Exp/Cntr=0.3,0.1

Type RM Length L Ch R = 1,10552,482,482,482
BEGIN DESCRIPTION:
UNT074 IN CCTC 14.0
END DESCRIPTION:
XS GIS Cut Line= 2
      3529326.24     10658053.84      3528394.29     10657257.26
#Sta/Elev= 30
  4424.5  366.37  4446.4  365.98  4495.3  362.67  4551.9  359.81  4559.6  358.36
  4609.0  355.07  4686.9  351.52  4779.1  348.83  4892.0  348.53  4959.9  347.08
  4985.5  346.39  4992.1  342.62  5006.4  343.76  5010.0  342.58  5012.7  342.08
  5016.0  342.58  5018.0  344.20  5020.7  346.39  5027.2  346.88  5070.0  346.83
  5118.1  348.46  5332.4  354.28  5424.6  358.27  5481.7  361.93  5531.1  363.46
  5573.9  367.65  5580.5  367.02  5602.5  369.12  5623.3  369.39  5650.5  372.17
#Mann=8,-1,0
  4424.5    0.16       0  4495.3    0.05       0  4892.0     0.1       0
  4959.9    0.16       0  5010.0    0.07       0  5016.0    0.16       0
  5018.0     0.1       0  5118.1    0.05       0
Bank Sta=5010,5016
Exp/Cntr=0.3,0.1

Type RM Length L Ch R = 1,10070,578,578,578
BEGIN DESCRIPTION:
UNT074 IN CCTC 13.0
END DESCRIPTION:
XS GIS Cut Line= 3
      3529414.33     10657902.99      3529132.20     10657338.73
      3528546.25     10656861.29
#Sta/Elev= 30
  4515.9  363.06  4542.3  362.85  4606.5  360.51  4627.3  359.71  4686.7  356.55
  4721.2  353.54  4805.1  349.56  4855.4  348.08  4872.1  346.90  4942.0  346.00
  4977.4  346.22  4983.9  344.97  4989.5  344.86  4996.8  342.45  4999.5  341.95
  5002.8  342.45  5006.3  345.10  5037.4  345.82  5174.3  346.96  5311.0  349.04
  5325.4  348.40  5496.3  350.39  5638.5  353.20  5694.5  354.49  5751.9  356.93
  5795.0  357.01  5815.8  358.46  5865.4  359.70  5872.5  360.69  5902.6  362.09
#Mann=8,-1,0
  4515.9    0.16       0  4606.5     0.1       0  4627.3    0.05       0
  4942.0     0.1       0  4996.8    0.07       0  5002.8     0.1       0
  5037.4    0.16       0  5174.3    0.05       0
Bank Sta=4996.8,5002.8
Exp/Cntr=0.3,0.1

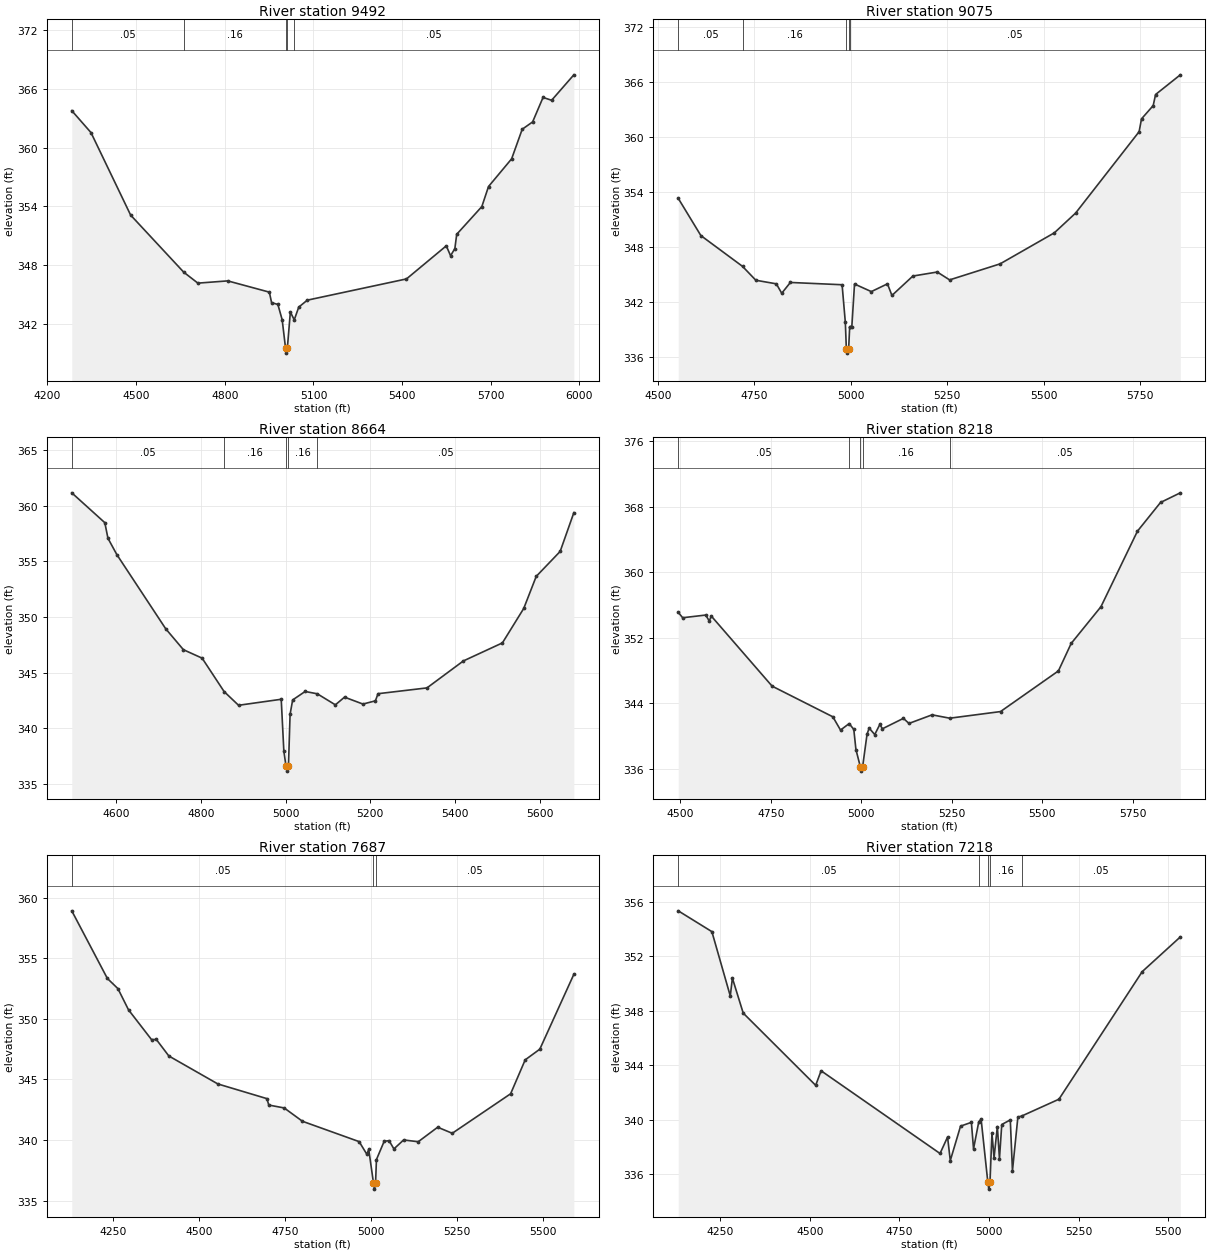
Type RM Length L Ch R = 1,9492,417,417,417
BEGIN DESCRIPTION:
UNT074 IN CCTC 12.0
END DESCRIPTION:
XS GIS Cut Line= 3
      3530211.70     10657314.27      3529576.25     10657220.52
      3528743.73     10656570.11
#Sta/Elev= 30
  4282.3  363.78  4347.3  361.54  4481.5  353.11  4661.1  347.28  4709.0  346.16
  4810.0  346.39  4950.8  345.24  4958.4  344.17  4979.7  343.98  4994.2  342.42
  5005.7  339.51  5008.4  339.01  5011.7  339.51  5021.9  343.21  5035.1  342.41
  5050.3  343.71  5079.2  344.42  5414.8  346.59  5549.5  349.97  5564.0  348.96
  5578.5  349.69  5584.8  351.15  5669.8  353.98  5692.4  356.03  5770.6  358.86
  5806.4  361.88  5841.6  362.63  5876.9  365.13  5905.9  364.84  5981.1  367.44
#Mann=5,-1,0
  4282.3    0.05       0  4661.1    0.16       0  5005.7    0.07       0
  5011.7    0.16       0  5035.1    0.05       0
Bank Sta=5005.7,5011.7
Exp/Cntr=0.3,0.1

Type RM Length L Ch R = 1,9075,411,411,411
BEGIN DESCRIPTION:
UNT074 IN CCTC 11.0
END DESCRIPTION:
XS GIS Cut Line= 3
      3530049.60     10657060.18      3529649.61     10656860.19
      3528849.61     10656560.19
#Sta/Elev= 30
  4552.9  353.29  4611.6  349.22  4719.5  345.86  4754.1  344.34  4807.2  343.95
  4821.2  342.92  4843.6  344.10  4977.7  343.85  4986.1  339.73  4988.7  336.88
  4991.5  336.38  4994.7  336.88  4997.3  339.18  4998.4  339.18  5002.8  339.18
  5009.9  343.93  5053.5  343.10  5095.3  343.95  5106.9  342.68  5161.2  344.80
  5224.4  345.24  5256.4  344.38  5387.3  346.13  5527.9  349.52  5583.1  351.68
  5747.7  360.57  5753.9  361.97  5784.2  363.42  5790.4  364.63  5854.5  366.78
#Mann=5,-1,0
  4552.9    0.05       0  4719.5    0.16       0  4988.7    0.03       0
  4994.7    0.16       0  4998.4    0.05       0
Bank Sta=4988.7,4994.7
Exp/Cntr=0.3,0.1

Type RM Length L Ch R = 1,8664,446,446,446
BEGIN DESCRIPTION:
UNT074 IN CCTC 10.0
END DESCRIPTION:
XS GIS Cut Line= 2
      3530225.02     10657083.61      3529534.96     10656120.14
#Sta/Elev= 30
  4495.3  361.14  4573.3  358.46  4580.7  357.06  4601.6  355.60  4717.0  348.94
  4758.8  347.06  4803.0  346.30  4854.9  343.30  4889.0  342.07  4989.7  342.61
  4995.9  337.95  5000.8  336.66  5003.6  336.16  5006.8  336.66  5010.6  341.26
  5016.7  342.55  5046.2  343.31  5074.9  343.10  5117.5  342.11  5139.1  342.80
  5182.6  342.18  5212.0  342.47  5218.2  343.11  5333.7  343.63  5419.6  346.05
  5511.8  347.67  5562.1  350.76  5591.6  353.64  5648.1  355.88  5680.4  359.36
#Mann=5,-1,0
  4495.3    0.05       0  4854.9    0.16       0  5000.8    0.07       0
  5006.8    0.16       0  5074.9    0.05       0
Bank Sta=5000.8,5006.8
Exp/Cntr=0.3,0.1

Type RM Length L Ch R = 1,8218,531,531,531
BEGIN DESCRIPTION:
UNT074 IN CCTC 9.0
END DESCRIPTION:
XS GIS Cut Line= 2
      3530391.95     10657014.16      3529662.78     10655833.59
#Sta/Elev= 30
  4494.1  355.11  4506.4  354.45  4570.2  354.78  4579.7  354.06  4585.6  354.65
  4753.5  346.09  4921.4  342.34  4942.6  340.72  4966.5  341.51  4979.3  340.80
  4985.2  338.34  4997.6  336.20  5000.3  335.70  5003.6  336.20  5015.9  340.21
  5021.8  340.96  5037.2  340.17  5051.2  341.40  5058.5  340.88  5116.4  342.15
  5131.8  341.53  5195.6  342.58  5244.5  342.17  5384.8  342.98  5544.8  347.95
  5580.1  351.31  5662.4  355.80  5763.2  365.03  5827.0  368.54  5881.7  369.72
#Mann=5,-1,0
  4494.1    0.05       0  4966.5    0.16       0  4997.6    0.07       0
  5003.6    0.16       0  5244.5    0.05       0
Bank Sta=4997.6,5003.6
Exp/Cntr=0.3,0.1

Type RM Length L Ch R = 1,7687,469,469,469
BEGIN DESCRIPTION:
UNT074 IN CCTC 8.0
END DESCRIPTION:
XS GIS Cut Line= 3
      3530899.63     10657110.23      3530499.61     10656310.19
      3530099.58     10655910.16
#Sta/Elev= 30
  4129.5  358.92  4233.0  353.34  4263.7  352.50  4294.5  350.75  4361.5  348.29
  4375.5  348.30  4411.8  346.94  4554.4  344.63  4696.9  343.42  4702.5  342.89
  4747.3  342.65  4800.4  341.55  4965.3  339.87  4987.6  338.83  4993.2  339.23
  5007.0  336.45  5009.7  335.95  5013.0  336.45  5015.6  338.39  5038.1  339.90
  5052.3  339.95  5066.4  339.27  5094.7  340.01  5137.1  339.86  5193.7  341.06
  5236.1  340.56  5405.8  343.82  5448.2  346.62  5490.7  347.50  5589.7  353.68
#Mann=3,-1,0
  4129.5    0.05       0  5007.0    0.03       0  5013.0    0.05       0
Bank Sta=5007,5013
Exp/Cntr=0.3,0.1

Type RM Length L Ch R = 1,7218,186,186,186
BEGIN DESCRIPTION:
UNT074 IN CCTC 7.0
END DESCRIPTION:
XS GIS Cut Line= 2
      3531275.41     10656814.57      3530507.97     10655643.90
#Sta/Elev= 30
  4133.5  355.35  4227.3  353.82  4278.6  349.09  4284.5  350.40  4314.7  347.83
  4516.7  342.52  4531.8  343.59  4863.4  337.51  4884.4  338.72  4892.0  336.99
  4920.6  339.52  4950.8  339.80  4956.8  337.85  4971.3  339.83  4977.9  340.04
  4996.7  335.39  4999.4  334.89  5002.7  335.39  5008.1  339.01  5014.0  337.20
  5023.2  339.49  5029.1  337.13  5035.5  339.64  5059.3  339.98  5065.3  336.24
  5080.4  340.18  5091.6  340.27  5194.9  341.50  5427.1  350.88  5533.3  353.43
#Mann=5,-1,0
  4133.5    0.05       0  4971.3    0.16       0  4996.7    0.07       0
  5002.7    0.16       0  5091.6    0.05       0
Bank Sta=4996.7,5002.7
Exp/Cntr=0.3,0.1

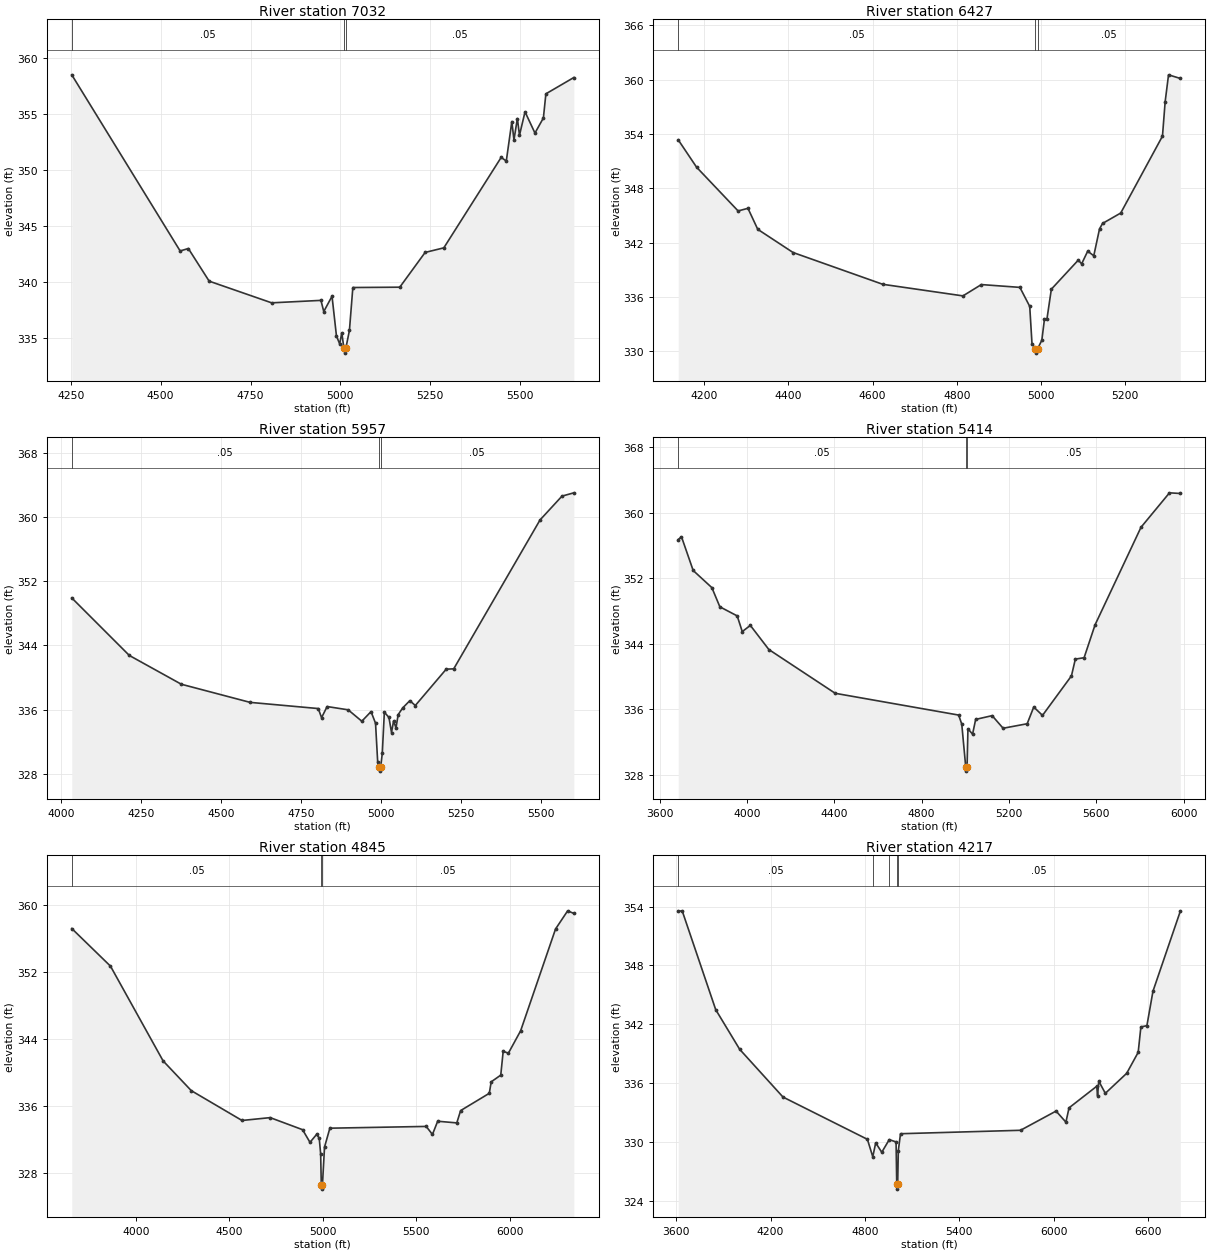
Type RM Length L Ch R = 1,7032,605,605,605
BEGIN DESCRIPTION:
UNT074 IN CCTC 6.0
END DESCRIPTION:
XS GIS Cut Line= 2
      3531327.50     10656766.84      3530594.28     10655578.08
#Sta/Elev= 30
  4252.8  358.51  4554.3  342.75  4577.1  342.97  4635.0  340.05  4808.8  338.11
  4946.0  338.33  4953.8  337.33  4976.8  338.70  4989.1  335.15  4998.1  334.43
  5004.0  335.43  5009.6  334.11  5012.3  333.61  5015.6  334.11  5025.2  335.64
  5034.7  339.48  5165.3  339.51  5235.8  342.62  5287.8  343.03  5447.3  351.12
  5461.6  350.80  5477.0  354.33  5482.9  352.69  5492.4  354.60  5498.3  353.11
  5513.7  355.20  5541.3  353.30  5564.8  354.65  5571.7  356.81  5649.5  358.27
#Mann=3,-1,0
  4252.8    0.05       0  5009.6    0.04       0  5015.6    0.05       0
Bank Sta=5009.6,5015.6
Exp/Cntr=0.3,0.1

Type RM Length L Ch R = 1,6427,470,470,470
BEGIN DESCRIPTION:
UNT074 IN CCTC 5.0
END DESCRIPTION:
XS GIS Cut Line= 3
      3531699.60     10656510.17      3531349.61     10655710.19
      3531149.64     10655460.23
#Sta/Elev= 30
  4138.1  353.34  4181.7  350.32  4280.4  345.49  4303.8  345.78  4327.1  343.46
  4411.0  340.90  4624.2  337.39  4814.8  336.11  4858.5  337.36  4950.1  337.05
  4973.5  334.95  4978.9  330.83  4986.5  330.29  4989.2  329.79  4992.5  330.29
  5002.3  331.22  5008.6  333.58  5014.5  333.58  5024.9  336.85  5088.9  340.06
  5096.9  339.65  5111.3  341.05  5125.7  340.54  5139.4  343.51  5146.6  344.11
  5189.8  345.26  5289.0  353.75  5295.4  357.56  5303.4  360.52  5331.4  360.12
#Mann=3,-1,0
  4138.1    0.05       0  4986.5    0.03       0  4992.5    0.05       0
Bank Sta=4986.5,4992.5
Exp/Cntr=0.3,0.1

Type RM Length L Ch R = 1,5957,543,543,543
BEGIN DESCRIPTION:
UNT074 IN CCTC 4.0
END DESCRIPTION:
XS GIS Cut Line= 4
      3532006.53     10656328.39      3531750.46     10655482.04
      3531646.29     10655351.83      3531143.72     10655217.52
#Sta/Elev= 30
  4032.8  349.92  4212.9  342.75  4375.7  339.16  4590.9  336.90  4804.2  336.13
  4814.5  334.99  4831.9  336.38  4897.8  335.97  4940.5  334.55  4969.3  335.75
  4983.4  334.30  4990.1  329.49  4993.5  328.83  4996.3  328.33  4999.5  328.83
  5004.5  330.53  5011.0  335.68  5025.4  335.02  5033.4  333.14  5039.8  334.57
  5047.5  333.73  5054.2  335.37  5068.6  336.22  5090.7  337.11  5107.9  336.51
  5204.6  341.04  5228.1  341.08  5498.2  359.64  5566.9  362.61  5604.0  363.02
#Mann=3,-1,0
  4032.8    0.05       0  4993.5    0.03       0  4999.5    0.05       0
Bank Sta=4993.5,4999.5
Exp/Cntr=0.3,0.1

Type RM Length L Ch R = 1,5414,569,569,569
BEGIN DESCRIPTION:
Mapping XS faf66855
END DESCRIPTION:
XS GIS Cut Line= 4
      3532612.31     10656334.09      3532178.29     10655198.70
      3532074.13     10655094.54      3531140.08     10655160.51
#Sta/Elev= 30
  3685.8  356.75  3700.7  357.09  3754.2  352.97  3839.9  350.87  3876.4  348.53
  3955.8  347.42  3979.0  345.50  4016.0  346.26  4100.8  343.31  4404.7  337.96
  4970.0  335.30  4984.2  334.19  5002.4  328.95  5005.2  328.45  5008.4  328.95
  5012.5  333.62  5033.7  332.97  5047.8  334.77  5123.3  335.23  5173.5  333.69
  5283.7  334.24  5313.8  336.28  5353.9  335.26  5486.5  340.09  5504.3  342.14
  5544.4  342.31  5594.5  346.32  5805.0  358.25  5935.4  362.46  5985.0  362.38
#Mann=3,-1,0
  3685.8    0.05       0  5002.4    0.04       0  5008.4    0.05       0
Bank Sta=5002.4,5008.4
Exp/Cntr=0.3,0.1

Type RM Length L Ch R = 1,4845,628,628,628
BEGIN DESCRIPTION:
Mapping XS eb88daf2
END DESCRIPTION:
XS GIS Cut Line= 4
      3532765.10     10656136.24      3532633.15     10654896.62
      3532528.99     10654775.09      3531277.25     10655045.55
#Sta/Elev= 30
  3656.3  357.15  3863.5  352.66  4145.1  341.36  4295.9  337.81  4567.5  334.25
  4718.3  334.59  4891.7  333.15  4931.3  331.64  4966.4  332.58  4980.7  332.16
  4988.4  330.27  4991.9  326.56  4994.7  326.06  4997.9  326.56  5009.2  331.08
  5037.7  333.33  5553.4  333.54  5586.8  332.58  5614.8  334.16  5717.1  333.96
  5737.6  335.43  5891.0  337.49  5901.3  338.86  5952.4  339.66  5965.4  342.50
  5993.3  342.28  6058.8  344.95  6245.6  357.09  6310.5  359.26  6343.6  358.95
#Mann=3,-1,0
  3656.3    0.05       0  4991.9    0.04       0  4997.9    0.05       0
Bank Sta=4991.9,4997.9
Exp/Cntr=0.3,0.1

Type RM Length L Ch R = 1,4217,803,803,803
BEGIN DESCRIPTION:
UNT074 IN CCTC 3.0
END DESCRIPTION:
XS GIS Cut Line= 4
      3532922.40     10655854.91      3533146.35     10654552.87
      3533021.35     10654422.66      3531403.11     10654906.57
#Sta/Elev= 30
  3613.3  353.53  3638.4  353.57  3851.5  343.49  4003.7  339.45  4279.0  334.58
  4815.4  330.27  4849.6  328.49  4868.2  329.91  4906.7  328.95  4954.4  330.24
  4997.6  330.00  5001.9  325.69  5004.6  325.19  5007.9  325.69  5011.8  329.10
  5025.9  330.84  5788.5  331.19  6014.4  333.15  6077.0  332.02  6096.9  333.48
  6272.9  335.68  6278.1  334.71  6285.8  336.20  6327.5  334.96  6463.2  337.00
  6536.3  339.14  6553.4  341.73  6591.7  341.86  6630.2  345.37  6804.0  353.53
#Mann=5,-1,0
  3613.3    0.05       0  4849.6    0.16       0  4954.4    0.05       0
  5001.9    0.04       0  5007.9    0.05       0
Bank Sta=5001.9,5007.9
Exp/Cntr=0.3,0.1

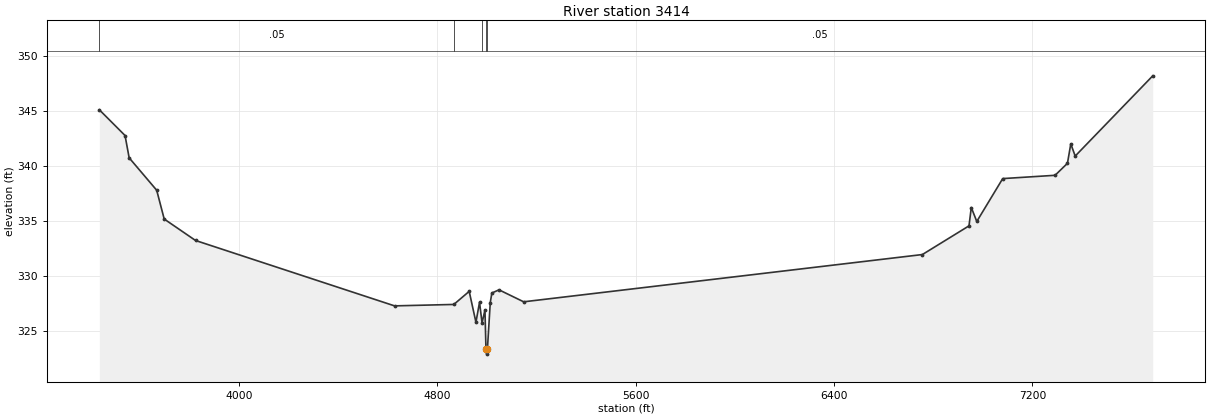
Type RM Length L Ch R = 1,3414,0,0,0
BEGIN DESCRIPTION:
UNT074 IN CCTC 2.0
END DESCRIPTION:
XS GIS Cut Line= 4
      3533620.31     10655589.33      3533823.43     10654151.83
      3533651.56     10653933.08      3531266.68     10654745.39
#Sta/Elev= 30
  3436.2  345.15  3539.9  342.81  3556.5  340.78  3667.6  337.83  3697.9  335.21
  3824.2  333.26  4627.1  327.31  4866.2  327.44  4928.2  328.63  4955.4  325.82
  4969.9  327.64  4980.0  325.76  4991.8  326.94  4995.8  323.42  4998.5  322.92
  5001.8  323.42  5013.2  327.61  5019.6  328.48  5048.5  328.77  5147.9  327.68
  6756.3  331.98  6944.4  334.59  6953.6  336.26  6975.8  334.99  7080.4  338.89
  7291.6  339.19  7341.5  340.28  7355.0  342.05  7372.8  340.94  7685.6  348.24
#Mann=5,-1,0
  3436.2    0.05       0  4866.2     0.1       0  4980.0    0.05       0
  4995.8    0.04       0  5001.8    0.05       0
Bank Sta=4995.8,5001.8
Exp/Cntr=0.3,0.1

Chan Stop Cuts=-1