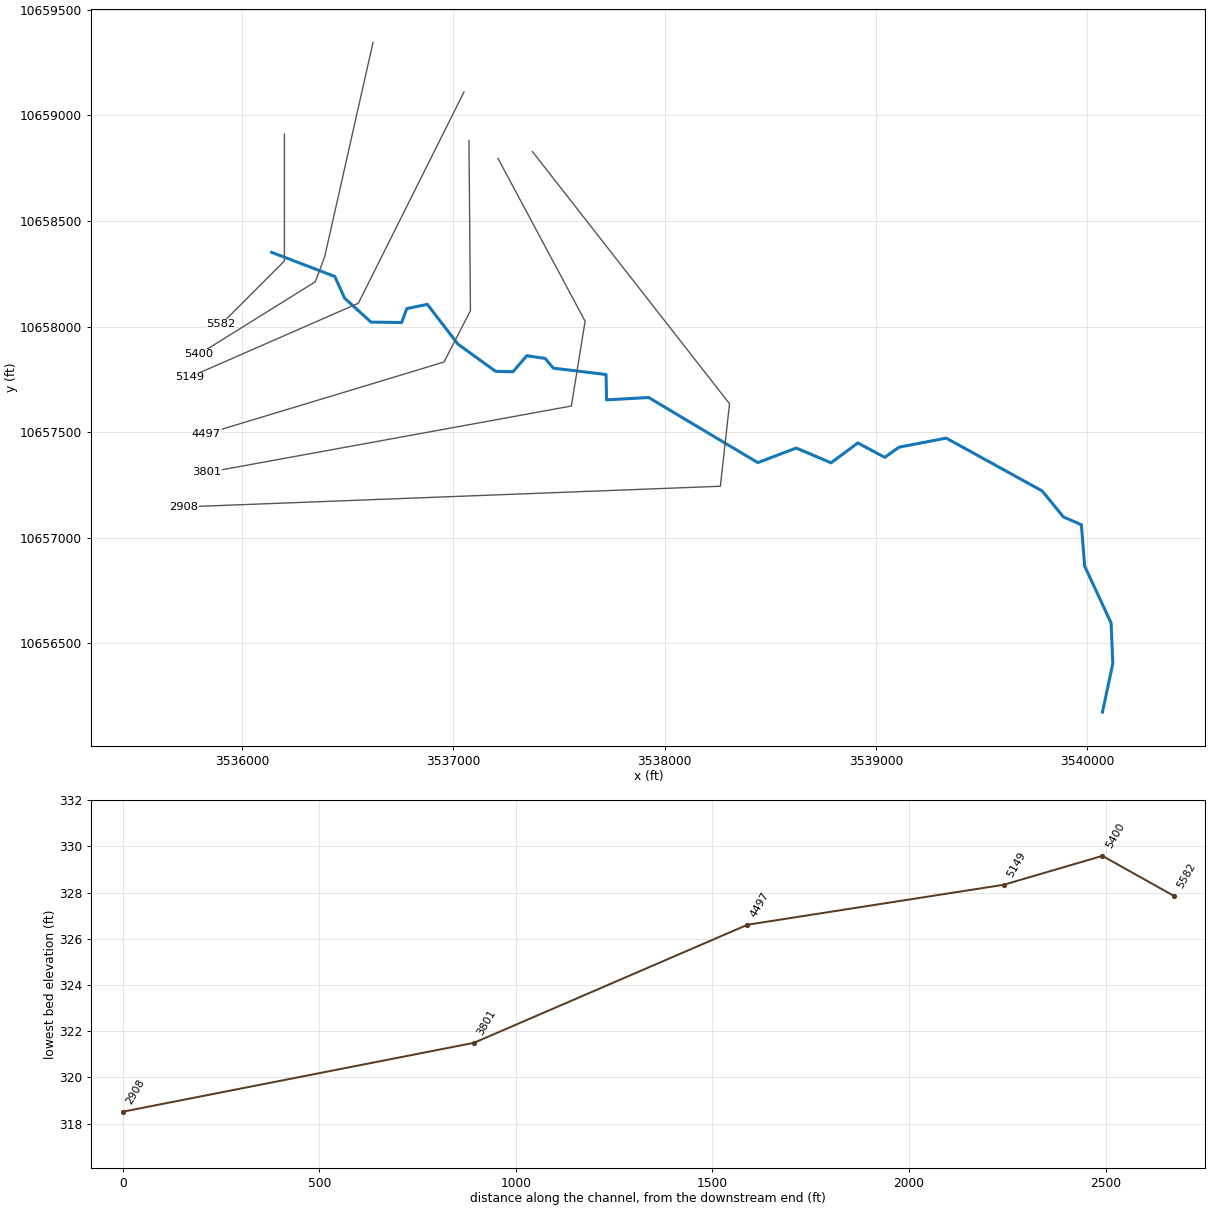
--- UNT075 IN CCTC.prj (project) ---

Proj Title=UNT075 IN CCTC Base Level Engineering
Current Plan=p01
Default Exp/Contr=0.3,0.1
English Units
Geom File=g01
Flow File=f01
Plan File=p01
Y Axis Title=Elevation
X Axis Title(PF)=Main Channel Distance
X Axis Title(XS)=Station
BEGIN DESCRIPTION:
UNT075 IN CCTC
END DESCRIPTION:
DSS Export Rating Curves= 0
DSS Export Rating Curve Sorted= 0
DSS Export Volume Flow Curves= 0
DXF OffsetX= 0
DXF OffsetY= 0
DXF ScaleX= 1
DXF ScaleY= 10

--- UNT075 IN CCTC.p01 (plan) ---

Plan Title=Multiple Run
Short Identifier=Multiple
Geom File=g01
Flow File=f01
Subcritical Flow
K Sum by GR= 0
Std Step Tol= 0.01
Critical Tol= 0.01
Num of Std Step Trials= 20
Max Error Tol= 0.3
Flow Tol Ratio= 0.001
Split Flow NTrial= 30
Split Flow Tol= 0.02
Split Flow Ratio= 0.02
Log Output Level= 0
Friction Slope Method= 1
Unsteady Friction Slope Method= 2
Unsteady Bridges Friction Slope Method= 1
Parabolic Critical Depth
Global Vel Dist=  1 , 1 , 1
Global Log Level= 0
CheckData=True
Encroach Param= -1, 0, 0, 0
BEGIN DESCRIPTION:
Multiple Run
END DESCRIPTION:

--- UNT075 IN CCTC.f01 (steady flow) ---

Flow Title=Multiple
Number of Profiles=7
Profile Names=10-year,25-year,50-year,1pct_min,100-year,1pct_plu,500-year
River Rch & RM= UNT075 IN CCTC,Reach-1,5582
    1279    1751    2138    1905    2576    3483    3727
Boundary for River Rch & Prof#=UNT075 IN CCTC,Reach-1,1
Up Type=0
Dn Type=3
Dn Slope=0.005
Boundary for River Rch & Prof#=UNT075 IN CCTC,Reach-1,2
Up Type=0
Dn Type=3
Dn Slope=0.005
Boundary for River Rch & Prof#=UNT075 IN CCTC,Reach-1,3
Up Type=0
Dn Type=3
Dn Slope=0.005
Boundary for River Rch & Prof#=UNT075 IN CCTC,Reach-1,4
Up Type=0
Dn Type=3
Dn Slope=0.005
Boundary for River Rch & Prof#=UNT075 IN CCTC,Reach-1,5
Up Type=0
Dn Type=3
Dn Slope=0.005
Boundary for River Rch & Prof#=UNT075 IN CCTC,Reach-1,6
Up Type=0
Dn Type=3
Dn Slope=0.005
Boundary for River Rch & Prof#=UNT075 IN CCTC,Reach-1,7
Up Type=0
Dn Type=3
Dn Slope=0.005

--- UNT075 IN CCTC.g01 (geometry) ---

Geom Title=Existing Conditions
Program Version=4.10

River Reach=UNT075 IN CCTC  ,Reach-1
Reach XY= 30
       3536139.5       10658351.        3536438.       10658237.
      3536484.75       10658134.       3536609.5       10658021.
      3536754.75       10658019.        3536779.       10658085.
      3536876.25       10658105.      3537020.75       10657917.
      3537199.25       10657788.      3537281.75       10657786.
      3537346.75       10657862.       3537433.5       10657849.
      3537472.75       10657803.      3537722.25       10657773.
       3537724.5       10657653.        3537924.       10657664.
       3538440.5       10657356.      3538622.75       10657425.
       3538787.5       10657355.      3538913.75       10657449.
      3539041.75       10657381.        3539109.       10657429.
       3539332.5       10657472.       3539786.5       10657222.
      3539887.25       10657099.      3539972.25       10657062.
        3539988.       10656866.        3540113.       10656597.
        3540121.       10656405.        3540072.       10656175.

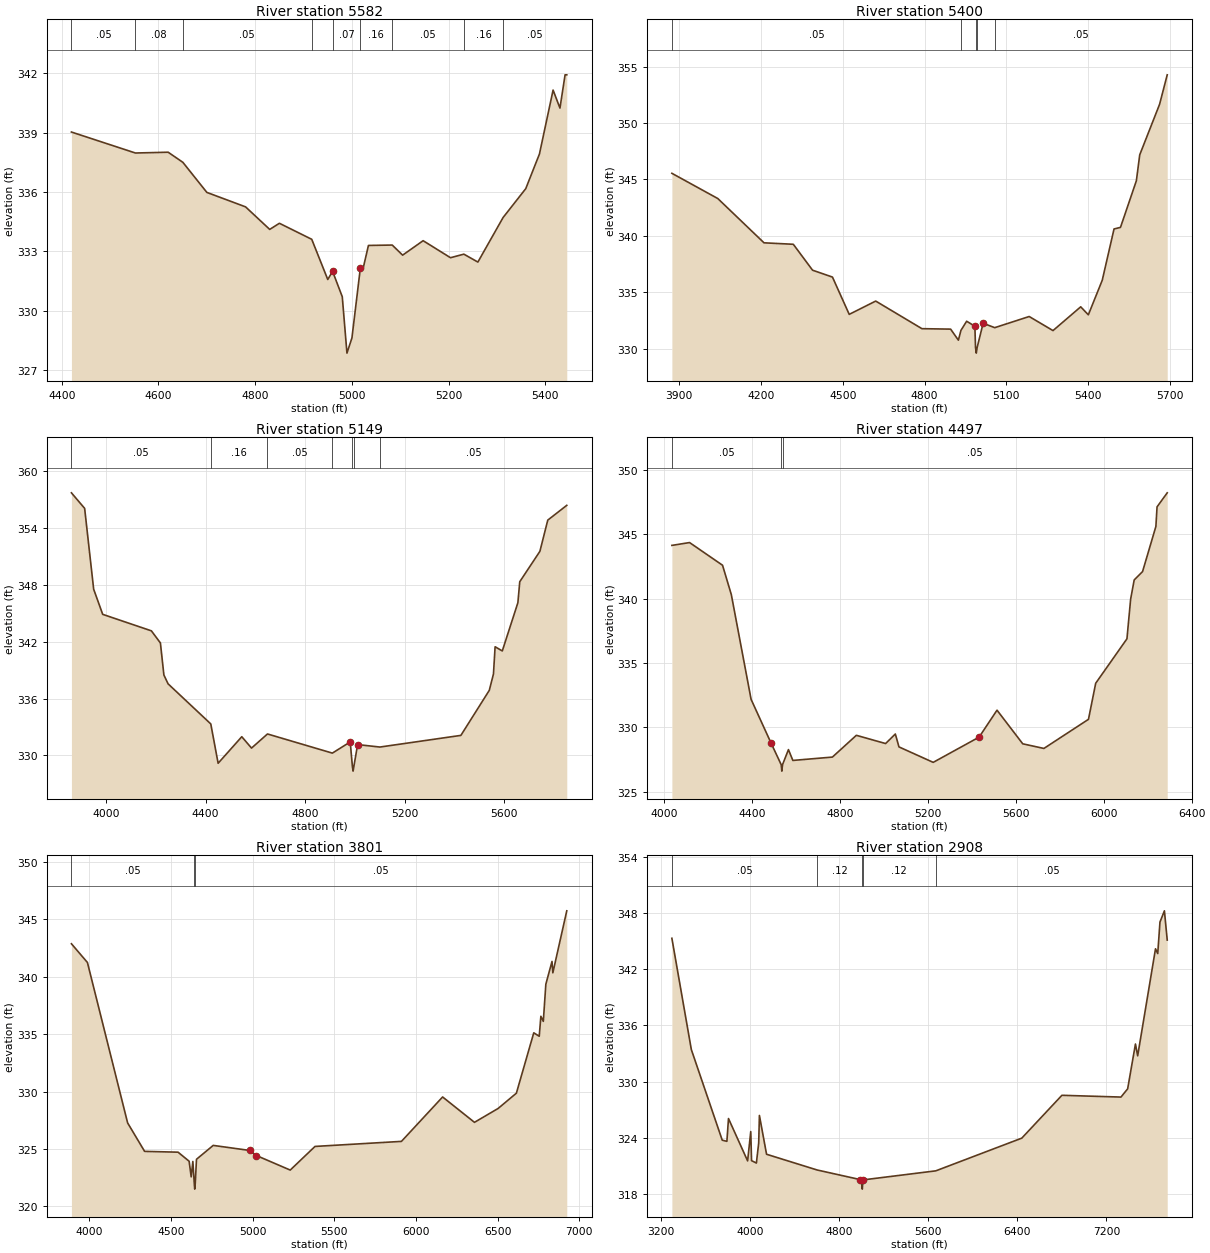
Type RM Length L Ch R = 1 ,5582    ,182,182,182
BEGIN DESCRIPTION:
UNT075 IN CCTC 5.0
END DESCRIPTION:
XS GIS Cut Line= 3
      3536199.61     10658910.15      3536199.61     10658310.19
      3535899.63     10658010.21
#Sta/Elev= 30
    4420  339.03  4552.3  337.97    4620  338.01  4650.4   337.5    4700  335.98
    4780  335.25    4830  334.11    4850  334.42  4916.9  333.61    4950  331.58
    4960  331.99    4980  330.71  4989.7  327.86    5000  328.63  5017.5  332.18
  5023.5  332.18  5034.1   333.3  5083.3  333.32  5104.8  332.81  5147.2  333.54
  5203.8  332.68  5231.4  332.86  5260.4  332.46  5312.5  334.71  5359.4  336.17
  5387.7  337.92  5415.9  341.15  5430.1  340.24  5440.7  341.92  5444.2  341.92
#Mann= 9 ,-1 , 0
    4420     .05       0  4552.3     .08       0  4650.4     .05       0
  4916.9     .16       0    4960     .07       0  5017.5     .16       0
  5083.3     .05       0  5231.4     .16       0  5312.5     .05       0
Bank Sta=4960,5017.5
XS Rating Curve= 0 ,0
Exp/Cntr=0.3,0.1

Type RM Length L Ch R = 1 ,5400    ,251,251,251
BEGIN DESCRIPTION:
Mapping XS 19de02d8
END DESCRIPTION:
XS GIS Cut Line= 4
      3536619.01     10659344.48      3536389.84     10658328.84
      3536345.57     10658211.65      3535794.07     10657868.27
#Sta/Elev= 30
  3873.7  345.55  4042.1  343.31  4211.5  339.38  4318.9  339.25  4389.5  336.95
  4462.4  336.34  4523.9  333.03    4621  334.21  4790.5  331.76  4895.7  331.72
  4924.1  330.74  4933.5  331.61  4954.4  332.42  4984.6  331.98  4986.9  330.09
  4989.7  329.59  4992.9  330.09  5014.8  332.24  5057.4  331.85  5183.7  332.84
    5271  331.59  5372.6   333.7  5400.6  332.99  5451.6  336.06  5494.8  340.61
  5518.4  340.75  5576.7  344.89    5589  347.19  5661.7  351.67  5689.8  354.29
#Mann= 5 ,-1 , 0
  3873.7     .05       0  4933.5     .16       0  4986.9     .07       0
  4992.9     .16       0  5057.4     .05       0
Bank Sta=4984.6,5014.8
XS Rating Curve= 0 ,0
Exp/Cntr=0.3,0.1

Type RM Length L Ch R = 1 ,5149    ,652,652,652
BEGIN DESCRIPTION:
UNT075 IN CCTC 4.0
END DESCRIPTION:
XS GIS Cut Line= 3
       3537049.6     10659110.16      3536549.61     10658110.19
      3535749.63      10657760.2
#Sta/Elev= 30
  3860.5   357.7  3913.6  356.06  3949.9  347.53  3986.2  344.88  4181.9  343.14
  4218.2  341.86  4232.2  338.48    4249  337.55  4420.7  333.32  4450.2  329.17
  4545.3  331.97  4584.4  330.77  4648.6  332.26  4909.4  330.24  4981.2  331.42
  4989.9  328.84  4992.7  328.34  4995.9  328.84  5010.9  331.14  5100.5  330.88
    5426  332.11  5540.2  336.86    5557  338.59  5563.6  341.46  5592.5  341.02
  5655.2  346.11  5662.7  348.32  5743.7  351.53  5775.3  354.82  5851.7  356.38
#Mann= 7 ,-1 , 0
  3860.5     .05       0  4420.7     .16       0  4648.6     .05       0
  4909.4     .16       0  4989.9     .07       0  4995.9     .16       0
  5100.5     .05       0
Bank Sta=4981.2,5010.9
XS Rating Curve= 0 ,0
Exp/Cntr=0.3,0.1

Type RM Length L Ch R = 1 ,4497    ,696,696,696
BEGIN DESCRIPTION:
UNT075 IN CCTC 3.0
END DESCRIPTION:
XS GIS Cut Line= 4
      3537073.24      10658880.7      3537080.19     10658075.14
      3536955.19     10657832.09      3535830.22     10657491.82
#Sta/Elev= 30
  4034.6  344.13  4115.1  344.35  4265.1  342.59  4305.1  340.31  4395.1  332.18
  4485.1  328.82  4532.1  327.11  4534.9  326.61  4538.1  327.11  4565.1  328.28
  4585.1  327.44  4765.1   327.7  4874.1  329.39  5007.1  328.75  5051.5  329.49
    5068  328.49  5223.8  327.29  5432.8  329.25  5514.2  331.34  5631.3  328.73
  5727.5  328.37  5930.4  330.63  5963.3  333.43  6105.5  336.88  6122.3  339.96
  6138.5  341.45  6176.6   342.1  6237.2   345.6  6242.5  347.12  6288.8  348.21
#Mann= 3 ,-1 , 0
  4034.6     .05       0  4532.1     .03       0  4538.1     .05       0
Bank Sta=4485.1,5432.8
XS Rating Curve= 0 ,0
Exp/Cntr=0.3,0.1

Type RM Length L Ch R = 1 ,3801    ,893,893,893
BEGIN DESCRIPTION:
UNT075 IN CCTC 2.0
END DESCRIPTION:
XS GIS Cut Line= 4
      3537210.71     10658795.72      3537623.05     10658025.31
      3537557.94     10657623.83      3535833.63     10657309.33
#Sta/Elev= 30
  3890.9  342.88  3988.8  341.25    4235  327.27    4339  324.79  4543.7  324.72
  4611.7  323.93  4624.2  322.57  4634.4  323.91  4643.2     322  4645.9   321.5
  4649.2     322  4656.7   324.1  4759.1  325.31  4982.6  324.87  5023.2  324.43
  5230.7  323.16  5382.5  325.22  5911.8  325.66  6163.9  329.53    6359  327.32
  6503.9  328.53  6615.6  329.86  6722.1  335.12  6755.5  334.82  6765.6  336.56
  6780.5  336.12  6796.1  339.36  6833.8  341.34  6838.9  340.35  6924.2  345.75
#Mann= 3 ,-1 , 0
  3890.9     .05       0  4643.2     .03       0  4649.2     .05       0
Bank Sta=4982.6,5023.2
XS Rating Curve= 0 ,0
Exp/Cntr=0.3,0.1

Type RM Length L Ch R = 1 ,2908    ,0,0,0
BEGIN DESCRIPTION:
UNT075 IN CCTC 1.0
END DESCRIPTION:
XS GIS Cut Line= 4
      3537373.46     10658828.28      3538306.64     10657634.68
      3538263.24     10657244.06      3535724.44     10657146.41
#Sta/Elev= 30
    3297  345.28  3471.7  333.41  3749.3  323.74    3791  323.62  3805.4  326.05
  3977.2  321.53  4005.4  324.66  4012.5  321.56  4055.9   321.3  4076.7  323.45
  4083.1  326.38  4147.3  322.24    4602  320.56  4987.7  319.54  5004.2  319.02
  5006.9  318.52  5010.2  319.02  5017.8  319.51  5667.2  320.47  6439.7  323.96
  6799.9  328.53  7330.3  328.34  7390.4  329.22  7460.4     334  7480.4  332.74
  7640.6  344.16  7660.6  343.65  7680.6  347.01  7720.6  348.21  7745.8  345.09
#Mann= 5 ,-1 , 0
    3297     .05       0    4602     .12       0  5004.2     .07       0
  5010.2     .12       0  5667.2     .05       0
Bank Sta=4987.7,5017.8
XS Rating Curve= 0 ,0
Exp/Cntr=0.3,0.1

Chan Stop Cuts=-1
Use User Specified Reach Order=0
Composite Channel Slope=5