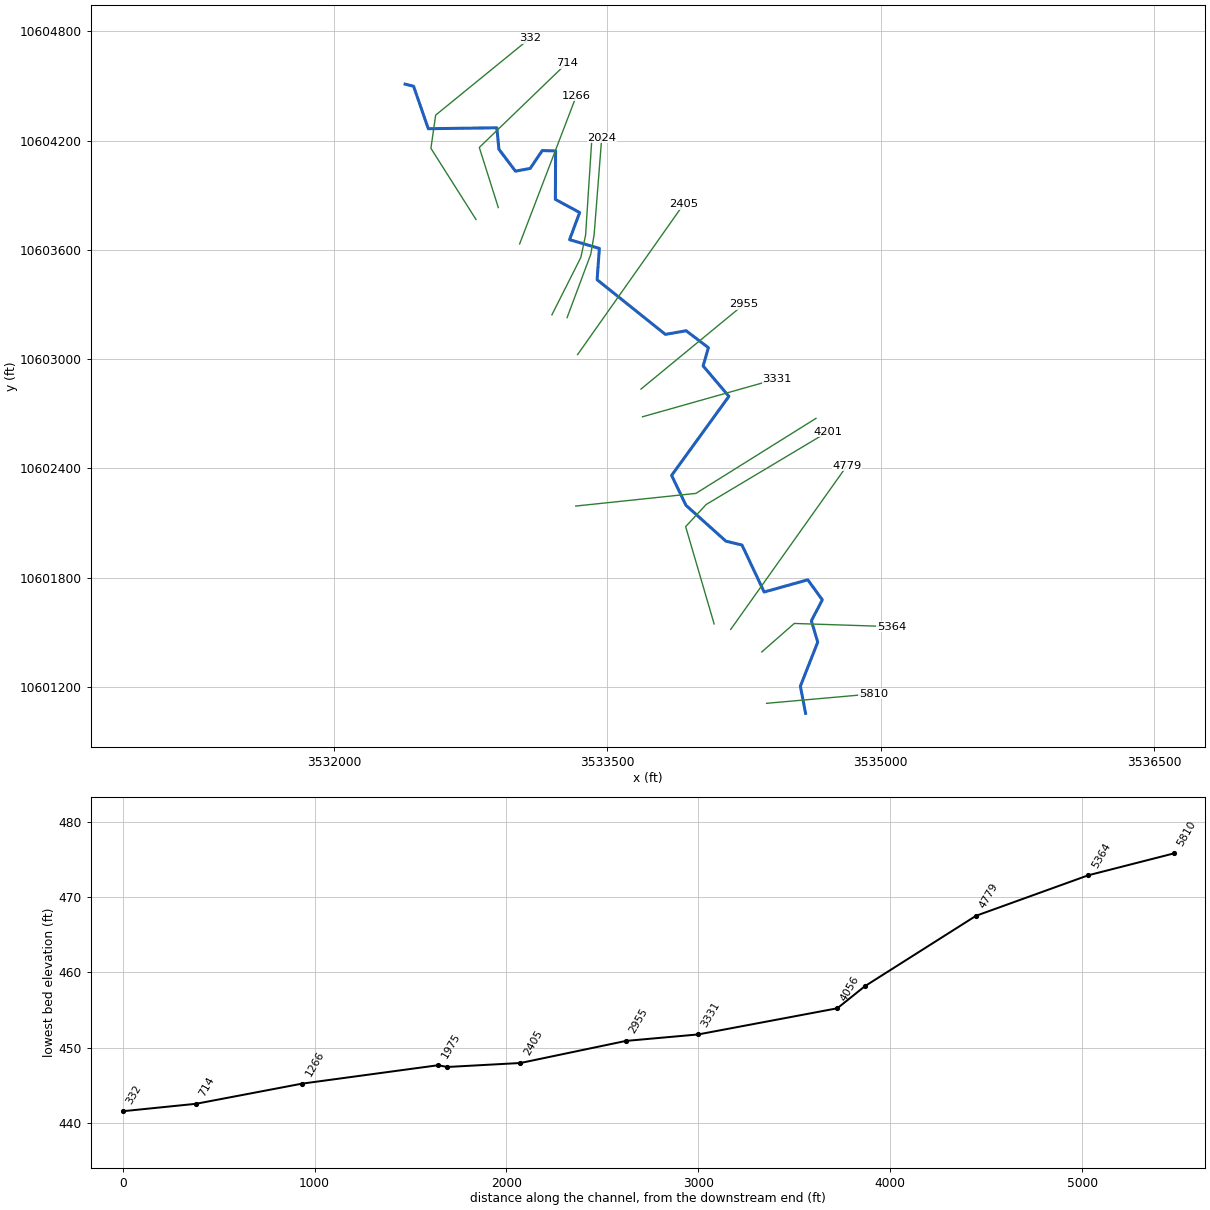
--- UNT080 IN CCTC.prj (project) ---

Proj Title=UNT080 IN CCTC Base Level Engineering
Current Plan=p01
Default Exp/Contr=0.3,0.1
English Units
Geom File=g01
Flow File=f01
Plan File=p01
Y Axis Title=Elevation
X Axis Title(PF)=Main Channel Distance
X Axis Title(XS)=Station
BEGIN DESCRIPTION:
UNT080 IN CCTC
END DESCRIPTION:
DSS Export Rating Curves= 0
DSS Export Rating Curve Sorted= 0
DSS Export Volume Flow Curves= 0
DXF OffsetX= 0
DXF OffsetY= 0
DXF ScaleX= 1
DXF ScaleY= 10

--- UNT080 IN CCTC.p01 (plan) ---

Plan Title=Multiple Run
Short Identifier=Multiple
Geom File=g01
Flow File=f01
Subcritical Flow
K Sum by GR= 0
Std Step Tol= 0.01
Critical Tol= 0.01
Num of Std Step Trials= 20
Max Error Tol= 0.3
Flow Tol Ratio= 0.001
Split Flow NTrial= 30
Split Flow Tol= 0.02
Split Flow Ratio= 0.02
Log Output Level= 0
Friction Slope Method= 1
Unsteady Friction Slope Method= 2
Unsteady Bridges Friction Slope Method= 1
Parabolic Critical Depth
Global Vel Dist=  1 , 1 , 1
Global Log Level= 0
CheckData=True
Encroach Param= -1, 0, 0, 0
BEGIN DESCRIPTION:
Multiple Run
END DESCRIPTION:

--- UNT080 IN CCTC.f01 (steady flow) ---

Flow Title=Multiple
Number of Profiles=7
Profile Names=10-year,25-year,50-year,1pct_min,100-year,1pct_plu,500-year
River Rch & RM= UNT080 IN CCTC,Reach-1,5810
     698     926    1109     972    1314    1777    1836
River Rch & RM= UNT080 IN CCTC,Reach-1,4056
    1167    1589    1933    1717    2322    3141    3340
Boundary for River Rch & Prof#=UNT080 IN CCTC,Reach-1,1
Up Type=0
Dn Type=3
Dn Slope=0.005
Boundary for River Rch & Prof#=UNT080 IN CCTC,Reach-1,2
Up Type=0
Dn Type=3
Dn Slope=0.005
Boundary for River Rch & Prof#=UNT080 IN CCTC,Reach-1,3
Up Type=0
Dn Type=3
Dn Slope=0.005
Boundary for River Rch & Prof#=UNT080 IN CCTC,Reach-1,4
Up Type=0
Dn Type=3
Dn Slope=0.005
Boundary for River Rch & Prof#=UNT080 IN CCTC,Reach-1,5
Up Type=0
Dn Type=3
Dn Slope=0.005
Boundary for River Rch & Prof#=UNT080 IN CCTC,Reach-1,6
Up Type=0
Dn Type=3
Dn Slope=0.005
Boundary for River Rch & Prof#=UNT080 IN CCTC,Reach-1,7
Up Type=0
Dn Type=3
Dn Slope=0.005

--- UNT080 IN CCTC.g01 (geometry) ---

Geom Title=Existing Conditions
Program Version=4.10

River Reach=UNT080 IN CCTC  ,Reach-1
Reach XY= 30
      3534587.92     10601055.85      3534559.25       10601205.
       3534654.5       10601447.      3534619.75       10601564.
      3534679.75       10601679.        3534600.       10601789.
       3534360.5       10601722.      3534238.75       10601980.
       3534150.5       10602001.      3533931.25       10602198.
       3533852.5       10602362.        3534167.       10602796.
       3534025.5       10602963.       3534054.5       10603063.
       3533932.5       10603156.      3533818.25       10603136.
       3533443.5       10603436.        3533456.       10603608.
       3533292.5       10603656.      3533347.75       10603805.
       3533214.5       10603877.      3533215.75       10604143.
       3533142.5       10604145.      3533076.25       10604047.
       3532995.5       10604032.      3532904.75       10604152.
      3532893.25       10604270.        3532517.       10604265.
      3532436.25       10604498.       3532389.5       10604510.

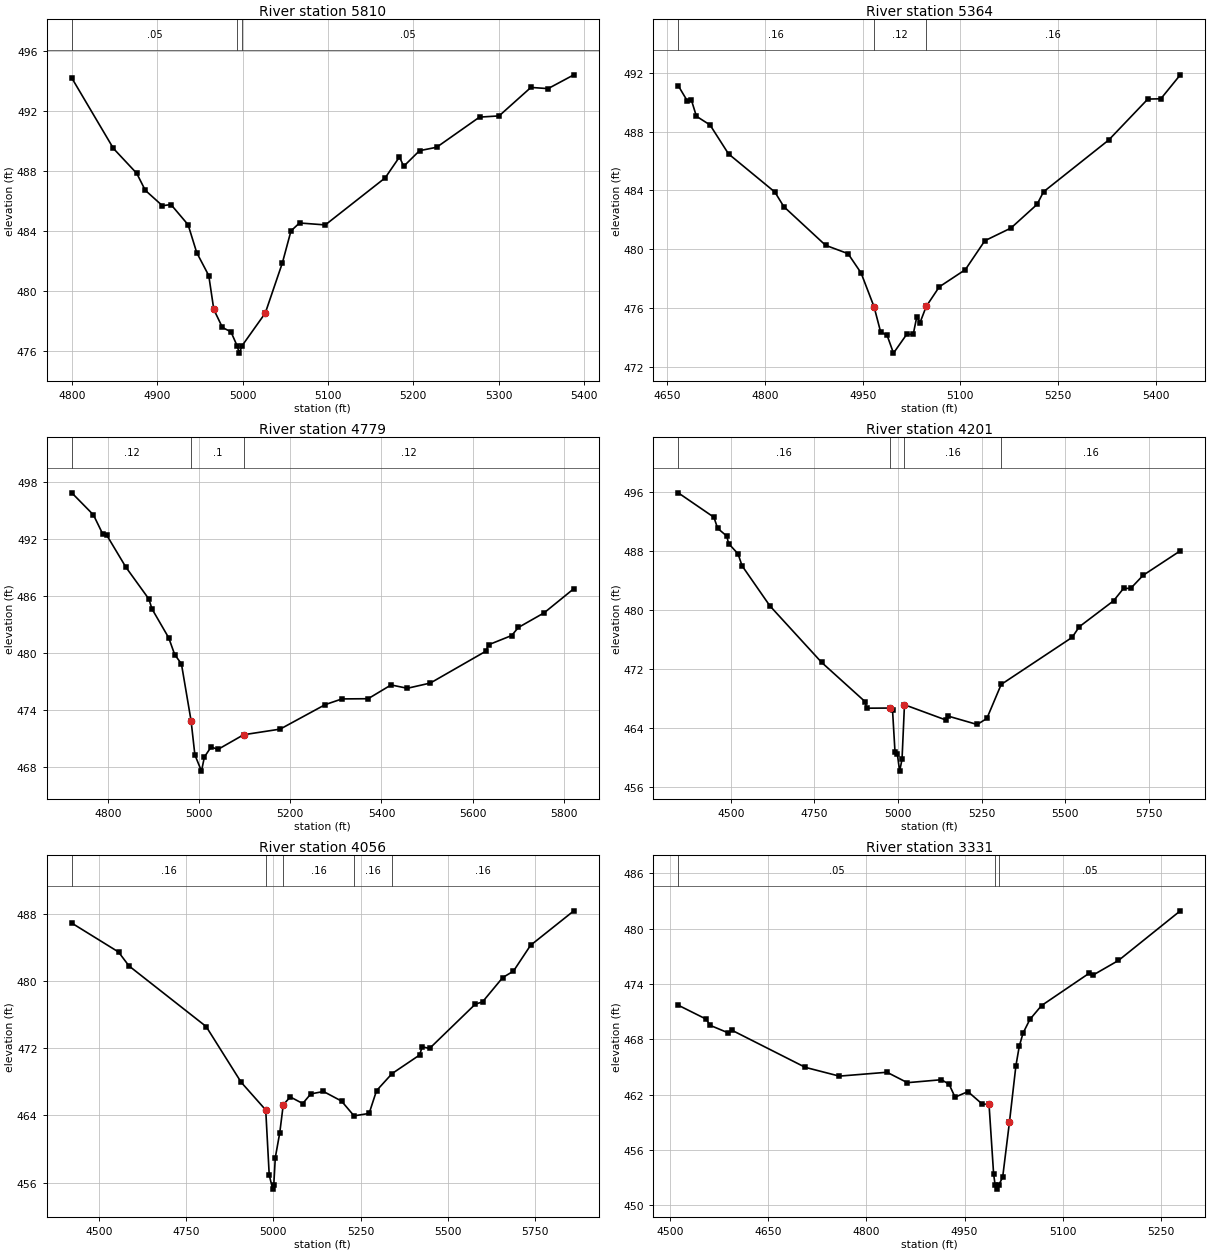
Type RM Length L Ch R = 1 ,5810    ,446,446,446
BEGIN DESCRIPTION:
UNT080 IN CCTC 11.0
END DESCRIPTION:
XS GIS Cut Line= 2
      3534373.82     10601111.05      3534959.71     10601163.13
#Sta/Elev= 30
  4799.9  494.19  4848.7  489.49    4876  487.83    4886   486.7  4906.1  485.67
  4916.1  485.75  4936.2   484.4  4946.3  482.54  4960.4  481.01  4966.3  478.75
  4976.4  477.55  4986.4  477.26  4993.5  476.34  4996.2  475.84  4999.5  476.34
  5026.6  478.51  5046.7  481.87  5056.7  483.99  5066.7  484.52  5096.9  484.39
  5167.1  487.53  5183.8  488.92  5188.8   488.3  5207.3  489.34  5227.4  489.57
  5277.6  491.58  5300.5  491.66  5337.8  493.56  5357.9  493.48  5388.1   494.4
#Mann= 3 ,-1 , 0
  4799.9     .05       0  4993.5     .03       0  4999.5     .05       0
Bank Sta=4966.3,5026.6
XS Rating Curve= 0 ,0
Exp/Cntr=0.3,0.1

Type RM Length L Ch R = 1 ,5364    ,585,585,585
BEGIN DESCRIPTION:
UNT080 IN CCTC 10.0
END DESCRIPTION:
XS GIS Cut Line= 3
      3534347.76      10601393.2      3534525.68     10601549.42
      3535059.53     10601532.06
#Sta/Elev= 30
  4666.8  491.13  4680.4  490.12  4687.1  490.14  4694.7  489.05  4715.6  488.46
    4744  486.49  4815.2  483.89  4828.9   482.9    4893  480.27  4927.5   479.7
  4947.5  478.39  4967.5  476.08  4977.5  474.38  4987.5  474.14  4997.3  472.93
  5017.6  474.21  5027.6  474.21  5033.1   475.4  5038.1  475.01  5047.6  476.11
  5067.6  477.44  5107.6  478.61  5137.6  480.58  5177.6  481.44  5217.7  483.05
  5227.7  483.91  5327.7  487.43  5387.8  490.22  5407.8  490.24  5437.7  491.87
#Mann= 3 , 0 , 0
  4666.8     .16       0  4967.5     .12       0  5047.6     .16       0
Bank Sta=4967.5,5047.6
XS Rating Curve= 0 ,0
Exp/Cntr=0.3,0.1

Type RM Length L Ch R = 1 ,4779    ,578,578,578
BEGIN DESCRIPTION:
UNT080 IN CCTC 9.0
END DESCRIPTION:
XS GIS Cut Line= 2
      3534176.94     10601516.75      3534814.77     10602414.91
#Sta/Elev= 30
  4720.5  496.83    4768  494.51  4788.9  492.45  4797.5  492.35  4839.3     489
  4889.7  485.65  4896.4  484.62  4933.2  481.57  4946.3  479.81  4961.1  478.83
  4982.3  472.83  4990.6  469.25  5005.1  467.54  5011.5  469.03  5026.3  470.09
    5041  469.82  5097.6  471.37  5177.6  471.96  5276.6  474.54  5313.4  475.14
  5370.7  475.16  5421.1  476.61  5456.8  476.26  5507.2  476.81    5629  480.16
  5635.1  480.84  5685.6  481.81  5700.4  482.66  5756.9   484.2  5822.1  486.74
#Mann= 3 , 0 , 0
  4720.5     .12       0  4982.3      .1       0  5097.6     .12       0
Bank Sta=4982.3,5097.6
XS Rating Curve= 0 ,0
Exp/Cntr=0.3,0.1

Type RM Length L Ch R = 1 ,4201    ,145,145,145
BEGIN DESCRIPTION:
UNT080 IN CCTC 8.0
END DESCRIPTION:
XS GIS Cut Line= 4
      3534085.78      10601547.1      3533929.53     10602080.96
      3534042.38     10602202.49      3534710.79      10602601.8
#Sta/Elev= 30
  4342.9  495.91  4449.5   492.6  4460.7   491.1  4488.1  490.04  4493.3  489.04
  4521.6  487.64  4533.7  486.02    4617  480.58  4771.2  472.94    4902  467.58
  4905.8  466.72  4976.6  466.74  4983.4  466.48  4990.8   460.8  4997.6  460.57
  5004.7  458.19  5011.8  459.78  5019.1  467.19  5142.9  465.12  5148.7  465.66
  5236.5  464.51  5265.4  465.33  5308.2  469.94  5520.3  476.32  5541.7  477.76
  5644.2  481.28    5674  482.96  5695.4  482.96  5732.4  484.73  5843.6  488.05
#Mann= 4 ,-1 , 0
  4342.9     .16       0  4976.6     .12       0  5019.1     .16       0
  5308.2     .16       0
Bank Sta=4976.6,5019.1
XS Rating Curve= 0 ,0
Exp/Cntr=0.3,0.1

Type RM Length L Ch R = 1 ,4056    ,725,725,725
BEGIN DESCRIPTION:
UNT080 IN CCTC 7.0
END DESCRIPTION:
XS GIS Cut Line= 3
      3533326.28     10602193.81      3533985.95     10602263.25
      3534644.83     10602675.05
#Sta/Elev= 30
  4421.7  486.89  4555.8  483.45  4585.9  481.79  4807.2  474.58  4907.6  467.95
  4978.1  464.65  4988.1  456.93    4998  455.23  5001.2  455.73  5005.6  458.99
  5018.3  461.92  5028.4  465.27  5048.5   466.2  5084.3  465.42  5107.3  466.56
  5143.8  466.85  5195.5  465.71  5231.4  463.95  5274.7  464.24    5296  466.95
  5340.5  468.98  5419.5  471.19  5426.9  472.17  5448.1  471.97    5579  477.23
  5600.2  477.52    5658  480.41  5688.7  481.17  5737.9  484.25    5862  488.35
#Mann= 5 ,-1 , 0
  4421.7     .16       0  4978.1     .12       0  5028.4     .16       0
  5231.4     .16       0  5340.5     .16       0
Bank Sta=4978.1,5028.4
XS Rating Curve= 0 ,0
Exp/Cntr=0.3,0.1

Type RM Length L Ch R = 1 ,3331    ,376,376,376
BEGIN DESCRIPTION:
UNT080 IN CCTC 6.0
END DESCRIPTION:
XS GIS Cut Line= 2
      3533692.84     10602683.84       3534430.7     10602892.18
#Sta/Elev= 30
  4512.8  471.69  4555.4  470.18  4561.4  469.51  4589.4  468.68  4594.6  468.98
  4706.9  464.95  4758.8     464  4831.6  464.42  4862.7  463.29  4914.7  463.61
  4926.4  463.12  4935.5  461.72  4955.2  462.32    4977  460.97  4987.4  460.94
  4994.4   453.4  4996.6  452.25  4999.3  451.75  5002.6  452.25  5008.2  453.03
  5018.6  459.02  5028.4   465.1  5033.6  467.25  5039.4  468.67  5049.8  470.15
  5067.6  471.65  5140.7  475.17  5145.9  474.94  5185.1  476.54  5279.5  481.92
#Mann= 3 ,-1 , 0
  4512.8     .05       0  4996.6     .03       0  5002.6     .05       0
Bank Sta=4987.4,5018.6
XS Rating Curve= 0 ,0
Exp/Cntr=0.3,0.1

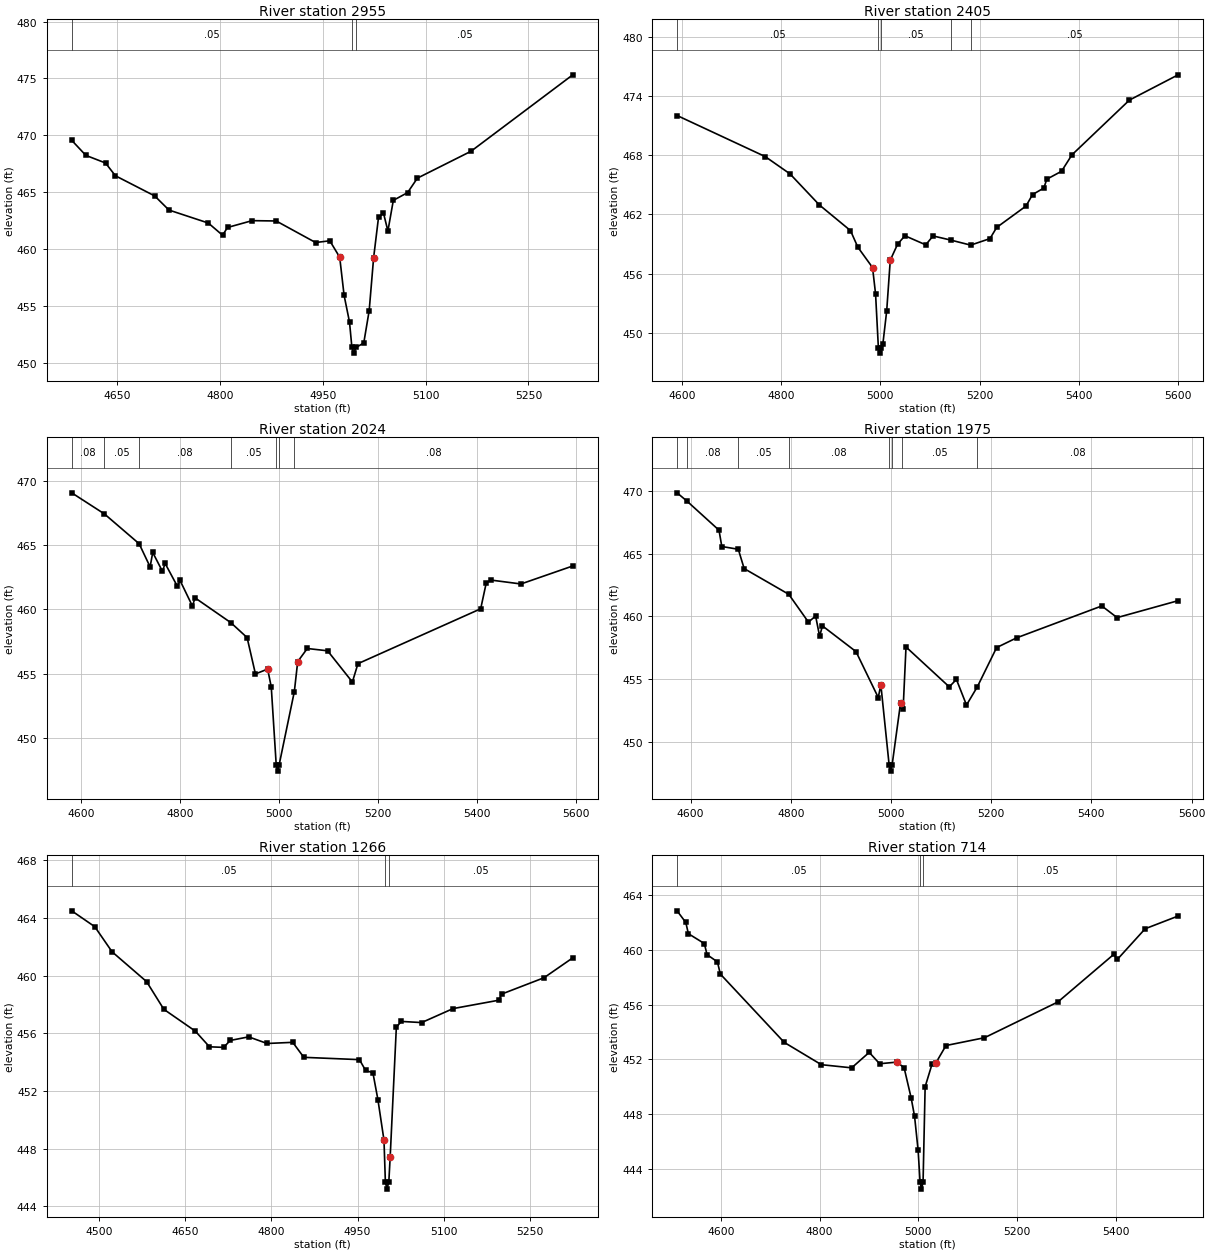
Type RM Length L Ch R = 1 ,2955    ,550,550,550
BEGIN DESCRIPTION:
UNT080 IN CCTC 5.0
END DESCRIPTION:
XS GIS Cut Line= 2
      3533684.19     10602835.78      3534248.37     10603300.14
#Sta/Elev= 30
    4584  469.57  4604.6  468.25  4633.3  467.58  4647.7  466.46    4705  464.69
  4725.8  463.45  4783.2  462.31    4804  461.24  4811.2  461.92  4847.1  462.52
  4882.2  462.49  4939.6   460.6  4960.4  460.75  4974.8  459.31  4981.2  455.97
  4989.1  453.62  4992.6  451.39  4995.3  450.89  4998.6  451.39  5009.9  451.78
  5017.8  454.62  5024.3  459.28  5031.4   462.8  5038.6   463.2  5045.1  461.61
    5053   464.3  5073.8  464.98  5088.1  466.25  5166.3  468.61  5314.7  475.32
#Mann= 3 ,-1 , 0
    4584     .05       0  4992.6     .03       0  4998.6     .05       0
Bank Sta=4974.8,5024.3
XS Rating Curve= 0 ,0
Exp/Cntr=0.3,0.1

Type RM Length L Ch R = 1 ,2405    ,381,381,381
BEGIN DESCRIPTION:
UNT080 IN CCTC 4.0
END DESCRIPTION:
XS GIS Cut Line= 2
      3533336.47     10603025.15      3533918.06     10603849.79
#Sta/Elev= 30
  4590.5  472.02    4768  467.86  4817.9  466.11  4877.1  462.96  4939.8  460.36
  4954.6  458.68  4984.2  456.62  4990.3  453.94    4996  448.45  4998.8  447.95
    5002  448.45  5005.1  448.92  5012.7  452.22  5019.9  457.37  5034.7  458.99
  5049.4  459.84  5091.3  458.92  5106.1  459.82  5142.6  459.39  5181.8  458.89
  5220.7  459.55  5234.2  460.68  5293.3  462.85  5306.4  464.01  5329.1  464.67
  5335.2  465.57  5364.8  466.37  5385.7  468.03  5501.5  473.58  5599.6  476.14
#Mann= 5 ,-1 , 0
  4590.5     .05       0    4996     .03       0    5002     .05       0
  5142.6     .08       0  5181.8     .05       0
Bank Sta=4984.2,5019.9
XS Rating Curve= 0 ,0
Exp/Cntr=0.3,0.1

Type RM Length L Ch R = 1 ,2024    ,49,49,49
BEGIN DESCRIPTION:
UNT080 IN CCTC 3.0
END DESCRIPTION:
XS GIS Cut Line= 4
      3533278.77     10603227.66      3533408.99     10603576.64
      3533427.22     10603683.41      3533468.88     10604214.68
#Sta/Elev= 30
  4580.6  469.07  4646.7  467.43    4717  465.11  4739.2  463.31  4744.5  464.43
  4764.2  462.96  4769.5  463.58  4794.5  461.79  4799.8  462.25  4824.8  460.26
  4830.1   460.9  4902.5  458.97  4935.4  457.81  4952.3  454.98    4977  455.36
  4984.3  453.97  4994.3  447.92    4997  447.42  5000.3  447.92    5031  453.61
  5037.8  455.94  5057.2  456.96  5098.3  456.78  5148.4  454.35  5159.7  455.78
    5408  460.05  5419.3  462.07  5429.3  462.28  5489.5  461.98  5594.3  463.38
#Mann= 7 ,-1 , 0
  4580.6     .08       0  4646.7     .05       0    4717     .08       0
  4902.5     .05       0  4994.3     .04       0  5000.3     .05       0
    5031     .08       0
Bank Sta=4977,5037.8
XS Rating Curve= 0 ,0
Exp/Cntr=0.3,0.1

Type RM Length L Ch R = 1 ,1975    ,709,709,709
BEGIN DESCRIPTION:
UNT080 IN CCTC 2.0
END DESCRIPTION:
XS GIS Cut Line= 4
      3533195.46     10603243.33       3533354.3     10603558.41
      3533380.34     10603680.81      3533414.19     10604201.62
#Sta/Elev= 30
  4573.1  469.84  4592.3   469.2  4656.8  466.86  4662.4  465.56  4695.3  465.34
    4707   463.8    4796  461.75  4835.3  459.53  4849.6  460.02  4857.6   458.4
  4863.2  459.23  4930.2  457.18  4974.6  453.52  4979.8  454.53  4996.3  448.15
  4999.1  447.65  5002.3  448.15  5019.1  453.08  5021.2  452.87  5024.2  452.57
    5030  457.55  5116.3  454.37  5130.6  454.96  5150.7  452.92  5172.3  454.37
  5210.8   457.5  5250.9  458.28  5420.7  460.82  5451.3  459.89    5573  461.24
#Mann= 8 ,-1 , 0
  4573.1     .05       0  4592.3     .08       0  4695.3     .05       0
    4796     .08       0  4996.3     .07       0  5002.3     .08       0
  5021.2     .05       0  5172.3     .08       0
Bank Sta=4979.8,5019.1
XS Rating Curve= 0 ,0
Exp/Cntr=0.3,0.1

Type RM Length L Ch R = 1 ,1266    ,552,552,552
BEGIN DESCRIPTION:
Mapping XS 2a780227
END DESCRIPTION:
XS GIS Cut Line= 2
      3533018.37     10603632.64       3533330.2     10604446.87
#Sta/Elev= 30
  4452.6   464.5  4492.7   463.4  4522.8  461.66  4582.9  459.59  4612.9  457.67
  4667.6  456.16  4692.3  455.07    4717  455.03  4728.4  455.51  4760.5  455.76
  4792.6   455.3  4837.2  455.38  4856.5  454.34  4953.3  454.18    4964  453.43
  4976.7  453.27  4985.4  451.41    4996  448.59  4998.4   445.7  5001.1   445.2
  5004.4   445.7  5006.8  447.46  5017.5  456.43  5026.1  456.83  5061.5  456.75
  5116.2  457.72  5195.6   458.3    5201  458.73  5274.5  459.86  5324.5  461.24
#Mann= 3 ,-1 , 0
  4452.6     .05       0  4998.4     .03       0  5004.4     .05       0
Bank Sta=4996,5006.8
XS Rating Curve= 0 ,0
Exp/Cntr=0.3,0.1

Type RM Length L Ch R = 1 ,714     ,382,382,382
BEGIN DESCRIPTION:
Mapping XS 417e1887
END DESCRIPTION:
XS GIS Cut Line= 3
      3532901.18     10603832.28      3532797.01     10604162.14
      3533278.07     10604625.87
#Sta/Elev= 30
  4511.6  462.85  4529.3     462  4534.5  461.18  4566.8  460.46  4572.3  459.65
  4593.3  459.12  4599.2  458.23  4728.5  453.24  4803.7  451.61    4865  451.38
  4900.5  452.51  4921.6  451.68  4957.1   451.8  4971.2  451.38  4985.4  449.18
  4992.3  447.84  4999.5  445.35  5003.5  443.02  5006.2  442.52  5009.5  443.02
  5013.7     450  5027.8  451.67  5034.8   451.7  5055.9  453.01  5133.8  453.58
  5282.3  456.19  5395.5  459.67  5402.7   459.3    5459  461.54  5525.7  462.47
#Mann= 3 ,-1 , 0
  4511.6     .05       0  5003.5     .03       0  5009.5     .05       0
Bank Sta=4957.1,5034.8
XS Rating Curve= 0 ,0
Exp/Cntr=0.3,0.1

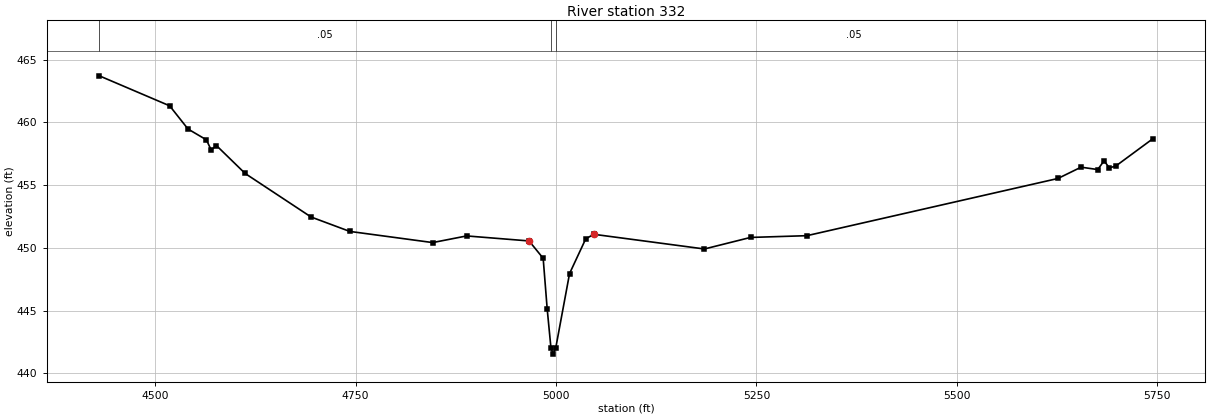
Type RM Length L Ch R = 1 ,332     ,0,0,0
BEGIN DESCRIPTION:
UNT080 IN CCTC 1.0
END DESCRIPTION:
XS GIS Cut Line= 4
      3532778.77     10603766.76      3532531.38     10604157.37
      3532557.42     10604339.66      3533074.71     10604761.04
#Sta/Elev= 30
  4430.5  463.71  4518.2  461.32  4541.1  459.47    4564  458.61  4569.9  457.81
  4576.6  458.15  4612.3  455.93  4694.5  452.46  4742.8  451.31  4846.2  450.42
  4888.6  450.95  4966.4  450.55    4984  449.17    4989  445.14  4993.7  442.03
  4996.5  441.53  4999.7  442.03  5016.9  447.95  5037.1  450.72  5047.2  451.08
  5185.1  449.91  5242.6  450.83  5312.9  450.97    5626  455.53  5654.8  456.43
  5675.6  456.24  5683.5  456.94    5690  456.38  5697.9  456.51  5744.2  458.69
#Mann= 3 ,-1 , 0
  4430.5     .05       0  4993.7     .03       0  4999.7     .05       0
Bank Sta=4966.4,5047.2
XS Rating Curve= 0 ,0
Exp/Cntr=0.3,0.1

Chan Stop Cuts=-1
Use User Specified Reach Order=0
Composite Channel Slope=5