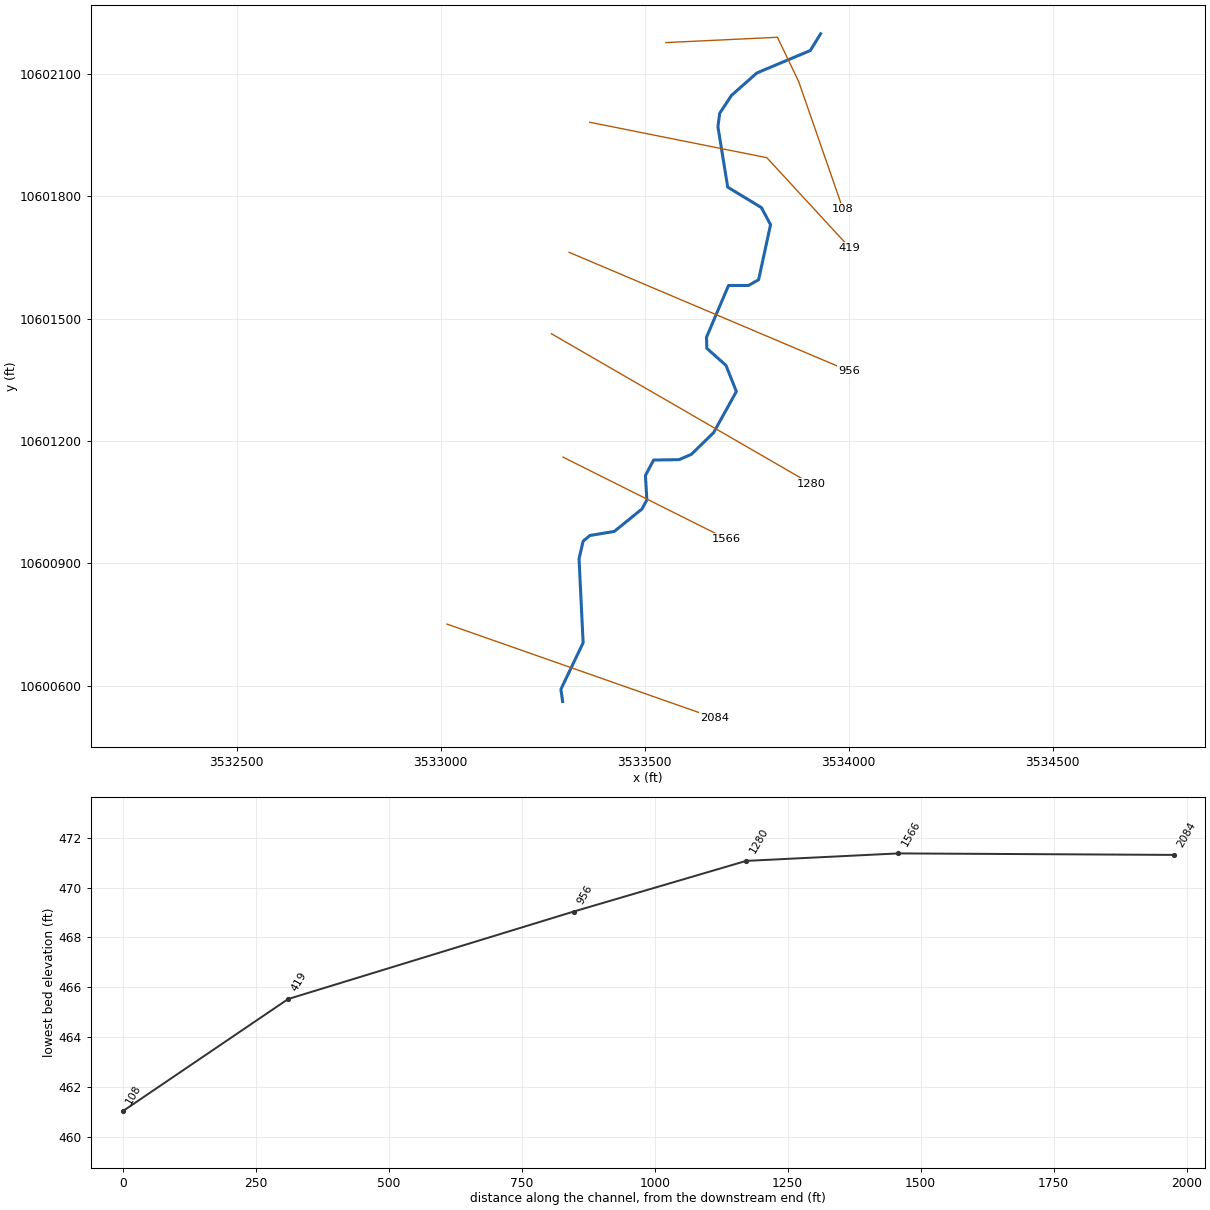
--- UNT082 IN CCTC.prj (project) ---

Proj Title=UNT082 IN CCTC Base Level Engineering
Current Plan=p01
Default Exp/Contr=0.3,0.1
English Units
Geom File=g01
Flow File=f01
Plan File=p01
Y Axis Title=Elevation
X Axis Title(PF)=Main Channel Distance
X Axis Title(XS)=Station
BEGIN DESCRIPTION:
UNT082 IN CCTC
END DESCRIPTION:
DSS Export Rating Curves= 0
DSS Export Rating Curve Sorted= 0
DSS Export Volume Flow Curves= 0
DXF OffsetX= 0
DXF OffsetY= 0
DXF ScaleX= 1
DXF ScaleY= 10

--- UNT082 IN CCTC.p01 (plan) ---

Plan Title=Multiple Run
Short Identifier=Multiple
Geom File=g01
Flow File=f01
Subcritical Flow
K Sum by GR= 0
Std Step Tol= 0.01
Critical Tol= 0.01
Num of Std Step Trials= 20
Max Error Tol= 0.3
Flow Tol Ratio= 0.001
Split Flow NTrial= 30
Split Flow Tol= 0.02
Split Flow Ratio= 0.02
Log Output Level= 0
Friction Slope Method= 1
Unsteady Friction Slope Method= 2
Unsteady Bridges Friction Slope Method= 1
Parabolic Critical Depth
Global Vel Dist=  1 , 1 , 1
Global Log Level= 0
CheckData=True
Encroach Param= -1, 0, 0, 0
BEGIN DESCRIPTION:
Multiple Run
END DESCRIPTION:

--- UNT082 IN CCTC.f01 (steady flow) ---

Flow Title=Multiple
Number of Profiles=7
Profile Names=10-year,25-year,50-year,1pct_min,100-year,1pct_plu,500-year
River Rch & RM= UNT082 IN CCTC,Reach-1,2084
     607     795     942     817    1106    1495    1515
Boundary for River Rch & Prof#=UNT082 IN CCTC,Reach-1,1
Up Type=0
Dn Type=3
Dn Slope=0.005
Boundary for River Rch & Prof#=UNT082 IN CCTC,Reach-1,2
Up Type=0
Dn Type=3
Dn Slope=0.005
Boundary for River Rch & Prof#=UNT082 IN CCTC,Reach-1,3
Up Type=0
Dn Type=3
Dn Slope=0.005
Boundary for River Rch & Prof#=UNT082 IN CCTC,Reach-1,4
Up Type=0
Dn Type=3
Dn Slope=0.005
Boundary for River Rch & Prof#=UNT082 IN CCTC,Reach-1,5
Up Type=0
Dn Type=3
Dn Slope=0.005
Boundary for River Rch & Prof#=UNT082 IN CCTC,Reach-1,6
Up Type=0
Dn Type=3
Dn Slope=0.005
Boundary for River Rch & Prof#=UNT082 IN CCTC,Reach-1,7
Up Type=0
Dn Type=3
Dn Slope=0.005

--- UNT082 IN CCTC.g01 (geometry) ---

Geom Title=Existing Conditions
Program Version=4.10

River Reach=UNT082 IN CCTC  ,Reach-1
Reach XY= 30
      3533298.75       10600561.       3533294.5       10600591.
        3533349.       10600705.        3533339.       10600911.
        3533349.       10600954.       3533365.5       10600968.
       3533425.5       10600978.      3533493.25       10601033.
      3533505.25       10601055.      3533501.75       10601115.
      3533521.75       10601153.       3533584.5       10601154.
       3533614.5       10601167.      3533668.75       10601220.
      3533724.75       10601321.      3533699.25       10601385.
      3533652.25       10601427.       3533651.5       10601454.
       3533705.5       10601581.       3533754.5       10601581.
      3533779.25       10601595.       3533808.5       10601730.
        3533786.       10601772.       3533703.5       10601822.
       3533679.5       10601970.      3533683.75       10602003.
      3533712.75       10602047.        3533775.       10602102.
        3533906.       10602157.      3533931.25       10602198.

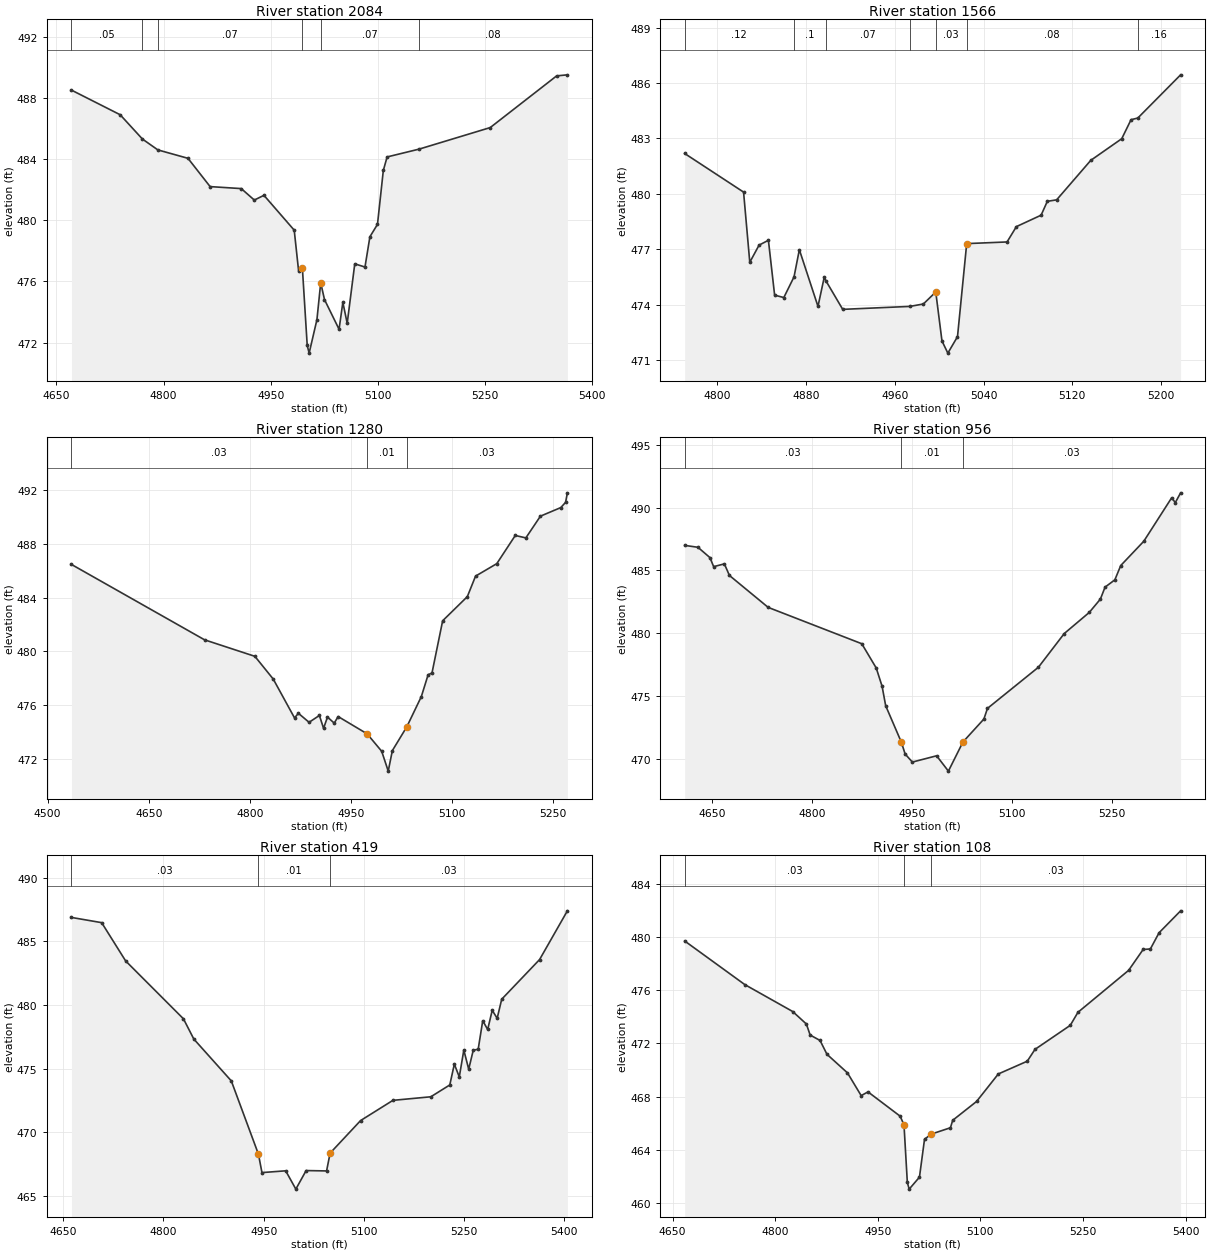
Type RM Length L Ch R = 1 ,2084    ,518,518,518
BEGIN DESCRIPTION:
UNT082 IN CCTC 4.0
END DESCRIPTION:
XS GIS Cut Line= 2
      3533015.22     10600750.82      3533670.62     10600520.78
#Sta/Elev= 30
    4671  488.51  4739.2   486.9  4770.4  485.31    4792   484.6  4834.2  484.05
  4865.2   482.2  4908.8  482.07  4927.1  481.32  4940.6  481.63    4983  479.35
  4989.1   476.7  4994.4  476.89  5001.2  471.81  5003.9  471.31  5014.8   473.5
  5020.1  475.91  5025.4  474.81  5045.8  472.87  5051.1  474.63  5057.2  473.26
  5067.8  477.15  5082.1  476.94    5089  478.92  5099.6  479.73  5107.8  483.26
  5113.1  484.14  5157.8  484.65  5257.5  486.06  5350.5  489.44  5365.6  489.51
#Mann= 6 ,-1 , 0
    4671     .05       0  4770.4      .1       0    4792     .07       0
  4994.4     .05       0  5020.1     .07       0  5157.8     .08       0
Bank Sta=4994.4,5020.1
XS Rating Curve= 0 ,0
Exp/Cntr=0.3,0.1

Type RM Length L Ch R = 1 ,1566    ,286,286,286
BEGIN DESCRIPTION:
UNT082 IN CCTC 3.0
END DESCRIPTION:
XS GIS Cut Line= 3
      3533299.61     10601160.19      3533499.61     10601060.19
       3533699.6     10600960.19
#Sta/Elev= 30
  4770.5  482.18  4823.6  480.09  4829.2  476.29  4837.6  477.22    4846  477.48
  4851.6  474.51  4859.9  474.38  4869.1   475.5  4873.9  476.97  4890.7   473.9
  4896.3  475.47  4898.1  475.26    4913  473.74  4973.5   473.9  4985.7  474.03
  4996.9  474.68  5002.5  472.03  5007.8  471.37  5016.5  472.26  5024.8   477.3
  5061.2  477.39  5069.6  478.22  5091.9  478.84  5097.5  479.59  5105.9  479.67
  5136.7  481.81  5164.6  482.98    5173  484.01  5179.1   484.1  5217.7  486.44
#Mann= 7 ,-1 , 0
  4770.5     .12       0  4869.1      .1       0  4898.1     .07       0
  4973.5     .05       0  4996.9     .03       0  5024.8     .08       0
  5179.1     .16       0
Bank Sta=4996.9,5024.8
XS Rating Curve= 0 ,0
Exp/Cntr=0.3,0.1

Type RM Length L Ch R = 1 ,1280    ,324,324,324
BEGIN DESCRIPTION:
Mapping XS 9c7f3414
END DESCRIPTION:
XS GIS Cut Line= 2
      3533271.34     10601462.62      3533908.05     10601094.44
#Sta/Elev= 30
  4535.4  486.48  4732.8  480.86  4807.4  479.63  4834.7  477.93  4866.2  475.04
    4872  475.38  4887.8  474.71  4903.1  475.22  4909.3  474.26  4915.1   475.1
  4925.1  474.65  4930.9  475.14  4973.9  473.85  4995.5  472.55  5005.2  471.07
  5011.3   472.6  5032.8  474.38  5054.3  476.63  5064.3  478.25  5070.1  478.39
  5085.9  482.28  5122.5  484.08  5134.7  485.61  5166.2  486.54  5193.6  488.64
  5209.3  488.46  5230.9  490.08  5261.1  490.72  5268.2  491.11  5270.9  491.82
#Mann= 3 , 0 , 0
  4535.4     .03       0  4973.9     .01       0  5032.8     .03       0
Bank Sta=4973.9,5032.8
XS Rating Curve= 0 ,0
Exp/Cntr=0.3,0.1

Type RM Length L Ch R = 1 ,956     ,537,537,537
BEGIN DESCRIPTION:
UNT082 IN CCTC 2.0
END DESCRIPTION:
XS GIS Cut Line= 2
      3533314.74     10601662.27      3534000.53     10601371.46
#Sta/Elev= 30
  4608.6  486.99  4628.5  486.84  4646.5  486.02  4652.1   485.3  4668.2  485.52
  4675.8   484.6    4734  482.06  4874.6  479.17  4896.3  477.24  4905.1  475.79
  4910.5  474.24  4934.2  471.32  4939.7   470.4  4950.6  469.76    4987  470.26
  5004.7  469.04  5026.6  471.36    5058  473.18  5063.4  474.03  5139.9   477.3
  5178.7  479.98  5216.3  481.66    5233  482.72    5240  483.67  5254.7  484.25
  5263.6  485.39  5298.2  487.32  5340.1  490.78  5345.5  490.39  5353.5  491.17
#Mann= 3 , 0 , 0
  4608.6     .03       0  4934.2     .01       0  5026.6     .03       0
Bank Sta=4934.2,5026.6
XS Rating Curve= 0 ,0
Exp/Cntr=0.3,0.1

Type RM Length L Ch R = 1 ,419     ,311,311,311
BEGIN DESCRIPTION:
Mapping XS cb3b4fd4
END DESCRIPTION:
XS GIS Cut Line= 3
      3533365.27     10601981.14      3533799.32     10601894.33
      3534002.32     10601674.05
#Sta/Elev= 30
  4662.3  486.89  4707.5  486.48  4743.4  483.47  4829.9  478.92  4845.4  477.33
  4901.5  474.04  4942.1  468.28  4947.4  466.83  4982.9  466.97  4998.1  465.53
  5013.5  466.99  5044.1  466.96  5049.4  468.36    5095  470.92  5143.4  472.51
  5200.1  472.79  5228.5  473.72  5235.3  475.36  5242.7  474.35  5249.5  476.46
  5256.8  474.96  5263.6  476.45    5271  476.53  5277.8  478.77  5285.2  478.08
    5292  479.59  5299.4  478.96  5306.2  480.46  5362.9  483.58  5404.5  487.41
#Mann= 3 , 0 , 0
  4662.3     .03       0  4942.1     .01       0  5049.4     .03       0
Bank Sta=4942.1,5049.4
XS Rating Curve= 0 ,0
Exp/Cntr=0.3,0.1

Type RM Length L Ch R = 1 ,108     ,0,0,0
BEGIN DESCRIPTION:
UNT082 IN CCTC 1.0
END DESCRIPTION:
XS GIS Cut Line= 4
      3533551.88     10602176.44      3533825.36     10602189.47
      3533877.45     10602080.96      3533985.97     10601768.41
#Sta/Elev= 30
  4667.8  479.71  4755.6  476.43  4825.7   474.4  4845.7  473.46  4851.2  472.63
  4865.7  472.22  4875.8  471.18  4905.8  469.78  4925.8  468.07  4935.8  468.35
  4982.8  466.52  4988.4  465.87  4993.3  461.53    4996  461.03    5011  461.93
  5018.4  464.78  5028.1  465.17  5056.3  465.65  5059.6  466.21  5094.5  467.63
  5126.3   469.7  5168.6  470.66  5179.9  471.55  5231.5  473.36  5242.7  474.34
  5316.8   477.5    5338  479.07  5348.6  479.11  5361.3  480.33  5392.8  481.98
#Mann= 3 , 0 , 0
  4667.8     .03       0  4988.4     .01       0  5028.1     .03       0
Bank Sta=4988.4,5028.1
XS Rating Curve= 0 ,0
Exp/Cntr=0.3,0.1

Chan Stop Cuts=-1
Use User Specified Reach Order=0
Composite Channel Slope=5