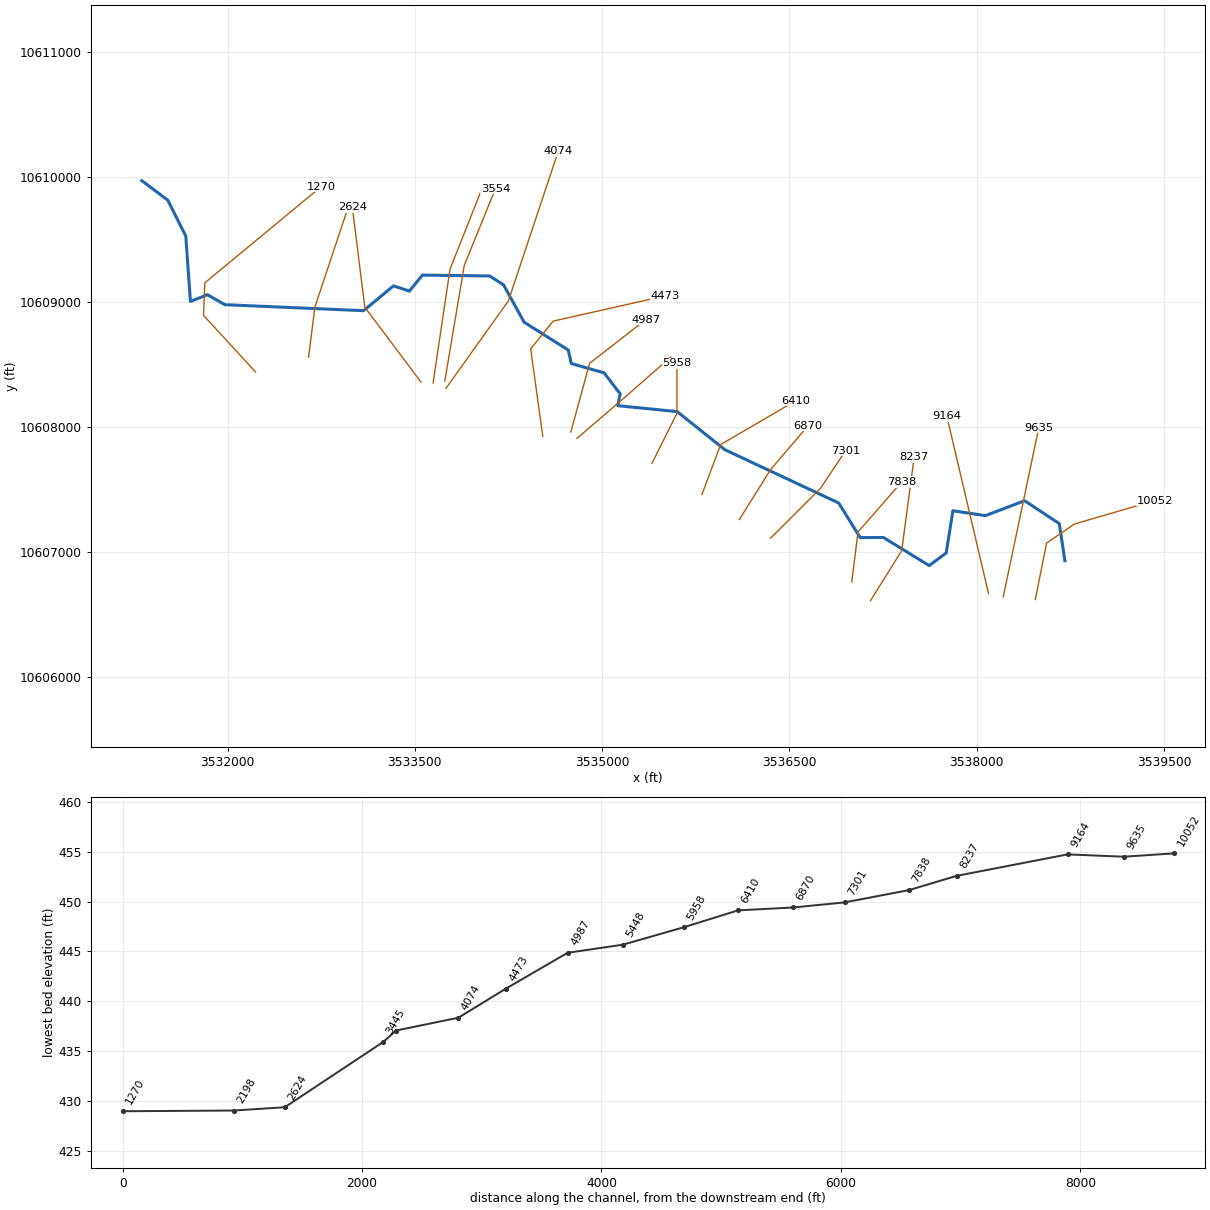
--- UNT084 IN CCTC.prj (project) ---

Proj Title=UNT084 IN CCTC Base Level Engineering
Current Plan=p01
Default Exp/Contr=0.3,0.1
English Units
Geom File=g01
Flow File=f01
Plan File=p01
BEGIN DESCRIPTION:
UNT084 IN CCTC
END DESCRIPTION:

--- UNT084 IN CCTC.p01 (plan) ---

Plan Title=Multiple Run
Short Identifier=Multiple
Geom File=g01
Flow File=f01
Subcritical Flow
K Sum by GR= 0
Std Step Tol= 0.01
Critical Tol= 0.01
Num of Std Step Trials= 20
Max Error Tol= 0.3
Flow Tol Ratio= 0.001
Split Flow NTrial= 30
Split Flow Tol= 0.02
Split Flow Ratio= 0.02
Log Output Level= 0
Friction Slope Method= 1
Unsteady Friction Slope Method= 2
Unsteady Bridges Friction Slope Method= 1
Parabolic Critical Depth
Global Vel Dist=  1 , 1 , 1
Global Log Level= 0
CheckData=True
Encroach Param= -1, 0, 0, 0
BEGIN DESCRIPTION:
Multiple Run
END DESCRIPTION:

--- UNT084 IN CCTC.f01 (steady flow) ---

Flow Title=Multiple
Number of Profiles=7
Profile Names=10-year,25-year,50-year,1pct_min,100-year,1pct_plu,500-year
River Rch & RM= UNT084 IN CCTC,Reach-1,10052
    1811    2497    3062    2734    3697    5000    5376
Boundary for River Rch & Prof#=UNT084 IN CCTC,Reach-1,1
Up Type=0
Dn Type=3
Dn Slope=0.005
Boundary for River Rch & Prof#=UNT084 IN CCTC,Reach-1,2
Up Type=0
Dn Type=3
Dn Slope=0.005
Boundary for River Rch & Prof#=UNT084 IN CCTC,Reach-1,3
Up Type=0
Dn Type=3
Dn Slope=0.005
Boundary for River Rch & Prof#=UNT084 IN CCTC,Reach-1,4
Up Type=0
Dn Type=3
Dn Slope=0.005
Boundary for River Rch & Prof#=UNT084 IN CCTC,Reach-1,5
Up Type=0
Dn Type=3
Dn Slope=0.005
Boundary for River Rch & Prof#=UNT084 IN CCTC,Reach-1,6
Up Type=0
Dn Type=3
Dn Slope=0.005
Boundary for River Rch & Prof#=UNT084 IN CCTC,Reach-1,7
Up Type=0
Dn Type=3
Dn Slope=0.005

--- UNT084 IN CCTC.g01 (geometry) ---

Geom Title=Existing Conditions

River Reach=UNT084 IN CCTC,Reach-1
Reach XY= 30
      3538706.50     10606930.00      3538661.50     10607227.00
      3538384.25     10607410.00      3538069.25     10607291.00
      3537809.50     10607330.00      3537756.00     10606992.00
      3537619.75     10606891.00      3537252.50     10607116.00
      3537067.00     10607115.00      3536895.00     10607392.00
      3535982.75     10607819.00      3535601.00     10608124.00
      3535125.75     10608171.00      3535144.25     10608267.00
      3535016.25     10608434.00      3534753.50     10608509.00
      3534729.00     10608617.00      3534375.50     10608840.00
      3534211.25     10609138.00      3534099.25     10609210.00
      3533561.00     10609217.00      3533456.50     10609089.00
      3533329.75     10609131.00      3533089.75     10608932.00
      3531979.00     10608980.00      3531839.00     10609060.00
      3531703.00     10609006.00      3531666.00     10609529.00
      3531521.75     10609817.00      3531313.75     10609973.00

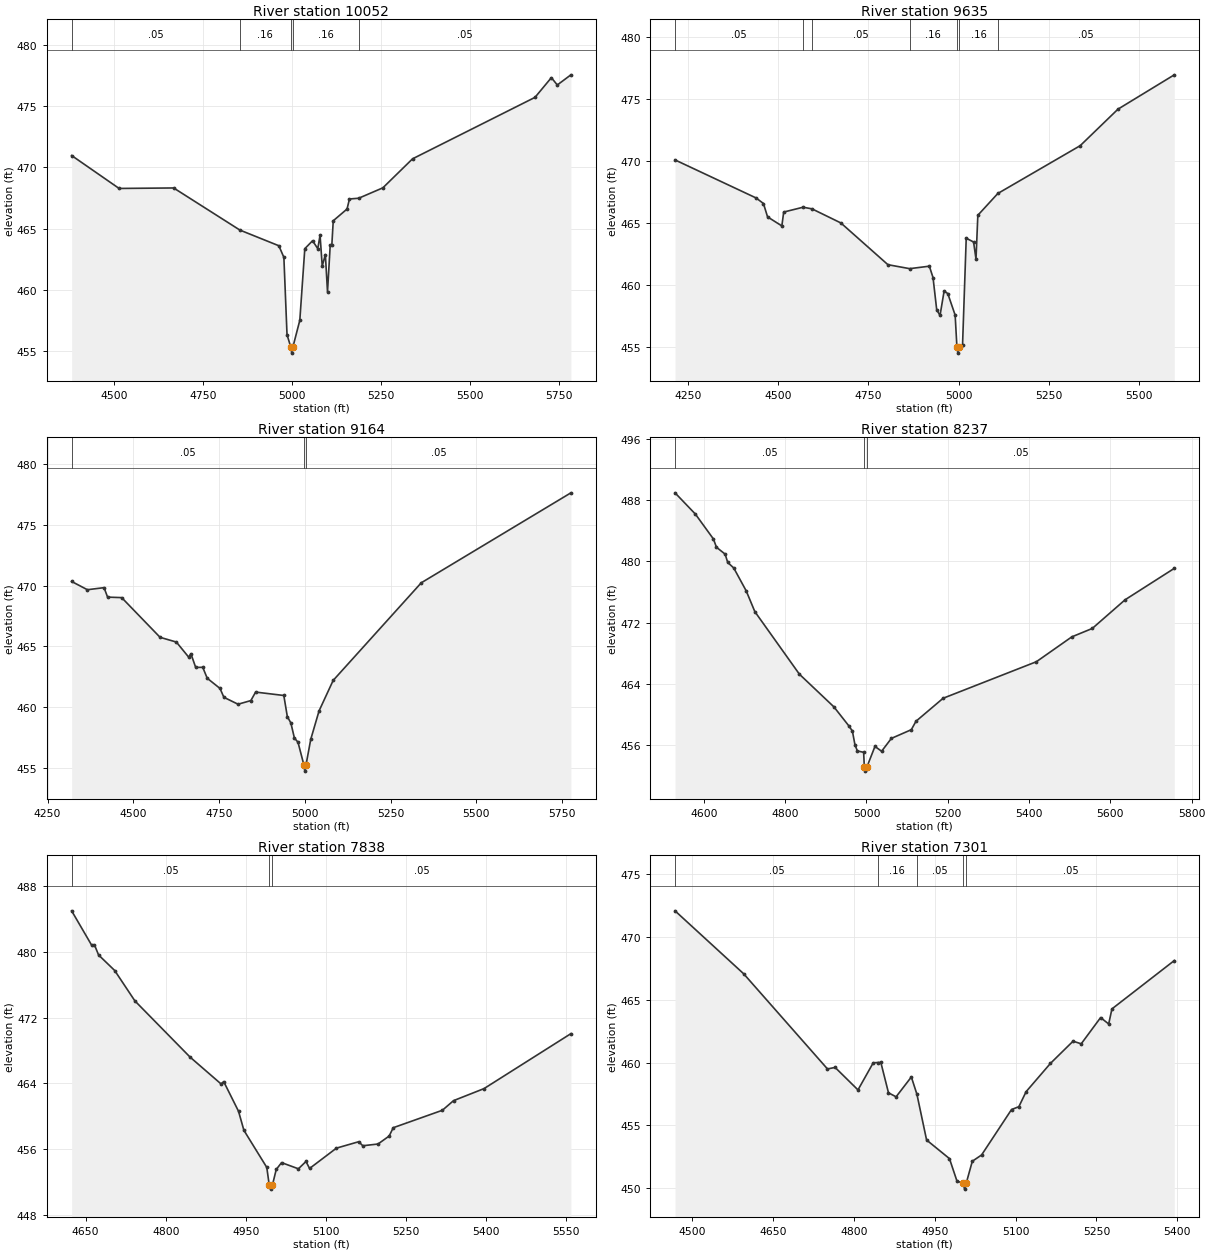
Type RM Length L Ch R = 1,10052,417,417,417
BEGIN DESCRIPTION:
UNT084 IN CCTC 18.0
END DESCRIPTION:
XS GIS Cut Line= 4
      3538469.60     10606619.53      3538559.88     10607070.93
      3538782.10     10607223.71      3539426.29     10607410.73
#Sta/Elev= 30
  4381.7  470.97  4514.9  468.28  4667.9  468.32  4853.8  464.88  4963.1  463.60
  4977.2  462.65  4986.0  456.34  4996.5  455.33  4999.2  454.83  5002.5  455.33
  5021.9  457.51  5035.9  463.36  5057.7  464.01  5072.3  463.36  5078.7  464.46
  5084.8  461.94  5093.6  462.88  5099.6  459.83  5107.2  463.64  5111.7  463.64
  5115.7  465.64  5154.4  466.60  5161.2  467.42  5187.0  467.48  5254.9  468.33
  5338.2  470.70  5681.8  475.72  5727.7  477.33  5744.3  476.73  5782.5  477.56
#Mann=5,-1,0
  4381.7    0.05       0  4853.8    0.16       0  4996.5    0.07       0
  5002.5    0.16       0  5187.0    0.05       0
Bank Sta=4996.5,5002.5
Exp/Cntr=0.3,0.1

Type RM Length L Ch R = 1,9635,471,471,471
BEGIN DESCRIPTION:
UNT084 IN CCTC 17.0
END DESCRIPTION:
XS GIS Cut Line= 2
      3538212.65     10606640.37      3538497.38     10607994.56
#Sta/Elev= 30
  4213.8  470.10  4438.4  467.03  4458.9  466.58  4470.3  465.50  4509.9  464.77
  4515.0  465.89  4568.7  466.28  4593.3  466.15  4673.5  465.01  4803.9  461.64
  4864.2  461.32  4918.7  461.52  4928.9  460.60  4939.1  458.00  4948.3  457.54
  4959.6  459.51  4969.8  459.31  4990.2  457.57  4995.1  455.00  4997.9  454.50
  5001.1  455.00  5010.7  455.15  5020.9  463.78  5041.3  463.47  5048.0  462.09
  5053.1  465.63  5108.5  467.39  5336.8  471.25  5441.6  474.20  5597.6  476.97
#Mann=7,-1,0
  4213.8    0.05       0  4568.7    0.08       0  4593.3    0.05       0
  4864.2    0.16       0  4995.1    0.07       0  5001.1    0.16       0
  5108.5    0.05       0
Bank Sta=4995.1,5001.1
Exp/Cntr=0.3,0.1

Type RM Length L Ch R = 1,9164,927,927,927
BEGIN DESCRIPTION:
UNT084 IN CCTC 16.0
END DESCRIPTION:
XS GIS Cut Line= 2
      3538094.59     10606668.17      3537761.27     10608084.79
#Sta/Elev= 30
  4320.1  470.35  4366.0  469.67  4414.6  469.84  4424.9  469.06  4466.0  469.02
  4577.9  465.75  4625.4  465.36  4661.2  464.12  4667.8  464.40  4681.7  463.27
  4702.3  463.28  4715.3  462.38  4752.6  461.54  4763.9  460.81  4805.2  460.24
  4842.5  460.54  4856.4  461.24  4938.6  460.96  4948.8  459.22  4959.1  458.70
  4969.4  457.46  4979.9  457.11  4997.2  455.23  4999.9  454.73  5003.2  455.23
  5017.1  457.35  5041.3  459.69  5082.4  462.20  5339.2  470.24  5775.4  477.65
#Mann=3,-1,0
  4320.1    0.05       0  4997.2    0.03       0  5003.2    0.05       0
Bank Sta=4997.2,5003.2
Exp/Cntr=0.3,0.1

Type RM Length L Ch R = 1,8237,399,399,399
BEGIN DESCRIPTION:
UNT084 IN CCTC 15.0
END DESCRIPTION:
XS GIS Cut Line= 3
      3537149.59     10606610.16      3537399.61     10607010.19
      3537499.61     10607760.22
#Sta/Elev= 30
  4528.9  488.98  4579.0  486.20  4623.3  482.95  4630.9  481.86  4652.2  480.96
  4658.6  479.87  4673.4  479.15  4704.0  476.16  4725.3  473.44  4834.9  465.26
  4919.9  460.98  4956.4  458.51  4965.3  457.82  4971.7  456.00  4977.6  455.22
  4993.0  455.04  4994.7  453.08  4997.4  452.58  5000.7  453.08  5020.8  455.81
  5037.2  455.18  5061.2  456.86  5110.3  458.00  5121.7  459.10  5188.5  462.11
  5418.0  466.89  5505.1  470.14  5555.5  471.24  5636.2  474.99  5757.3  479.10
#Mann=3,-1,0
  4528.9    0.05       0  4994.7    0.03       0  5000.7    0.05       0
Bank Sta=4994.7,5000.7
Exp/Cntr=0.3,0.1

Type RM Length L Ch R = 1,7838,537,537,537
BEGIN DESCRIPTION:
UNT084 IN CCTC 14.0
END DESCRIPTION:
XS GIS Cut Line= 3
      3536999.61     10606760.17      3537049.61     10607160.19
      3537399.59     10607560.16
#Sta/Elev= 30
  4623.9  484.96  4661.7  480.75  4666.7  480.82  4674.3  479.60  4704.5  477.71
  4742.3  474.02  4845.6  467.19  4903.6  463.93  4908.6  464.21  4936.3  460.61
  4946.4  458.29  4989.2  453.79  4993.8  451.65  4996.5  451.15  4999.8  451.65
  5006.9  453.54  5016.9  454.37  5048.4  453.62  5062.6  454.51  5069.3  453.66
  5119.6  456.13  5161.3  456.91  5168.9  456.42  5197.4  456.63  5218.3  457.60
  5225.9  458.61  5317.9  460.73  5338.8  461.90  5395.8  463.36  5558.5  470.04
#Mann=3,-1,0
  4623.9    0.05       0  4993.8    0.03       0  4999.8    0.05       0
Bank Sta=4993.8,4999.8
Exp/Cntr=0.3,0.1

Type RM Length L Ch R = 1,7301,431,431,431
BEGIN DESCRIPTION:
UNT084 IN CCTC 13.0
END DESCRIPTION:
XS GIS Cut Line= 3
      3536349.62     10607110.20      3536749.61     10607510.19
      3536949.60     10607810.17
#Sta/Elev= 30
  4468.2  472.08  4595.5  467.07  4751.0  459.49  4765.2  459.61  4807.6  457.82
  4835.9  459.98  4844.1  460.00  4850.0  460.01  4864.2  457.59  4878.3  457.27
  4906.6  458.85  4916.9  457.48  4934.9  453.83  4977.3  452.35  4991.4  450.54
  5002.6  450.42  5005.3  449.92  5008.6  450.42  5019.7  452.14  5036.9  452.64
  5092.5  456.26  5106.0  456.48  5119.5  457.68  5164.6  459.93  5206.6  461.70
  5221.7  461.49  5257.7  463.58  5272.7  463.07  5278.7  464.27  5394.4  468.12
#Mann=5,-1,0
  4468.2    0.05       0  4844.1    0.16       0  4916.9    0.05       0
  5002.6    0.03       0  5008.6    0.05       0
Bank Sta=5002.6,5008.6
Exp/Cntr=0.3,0.1

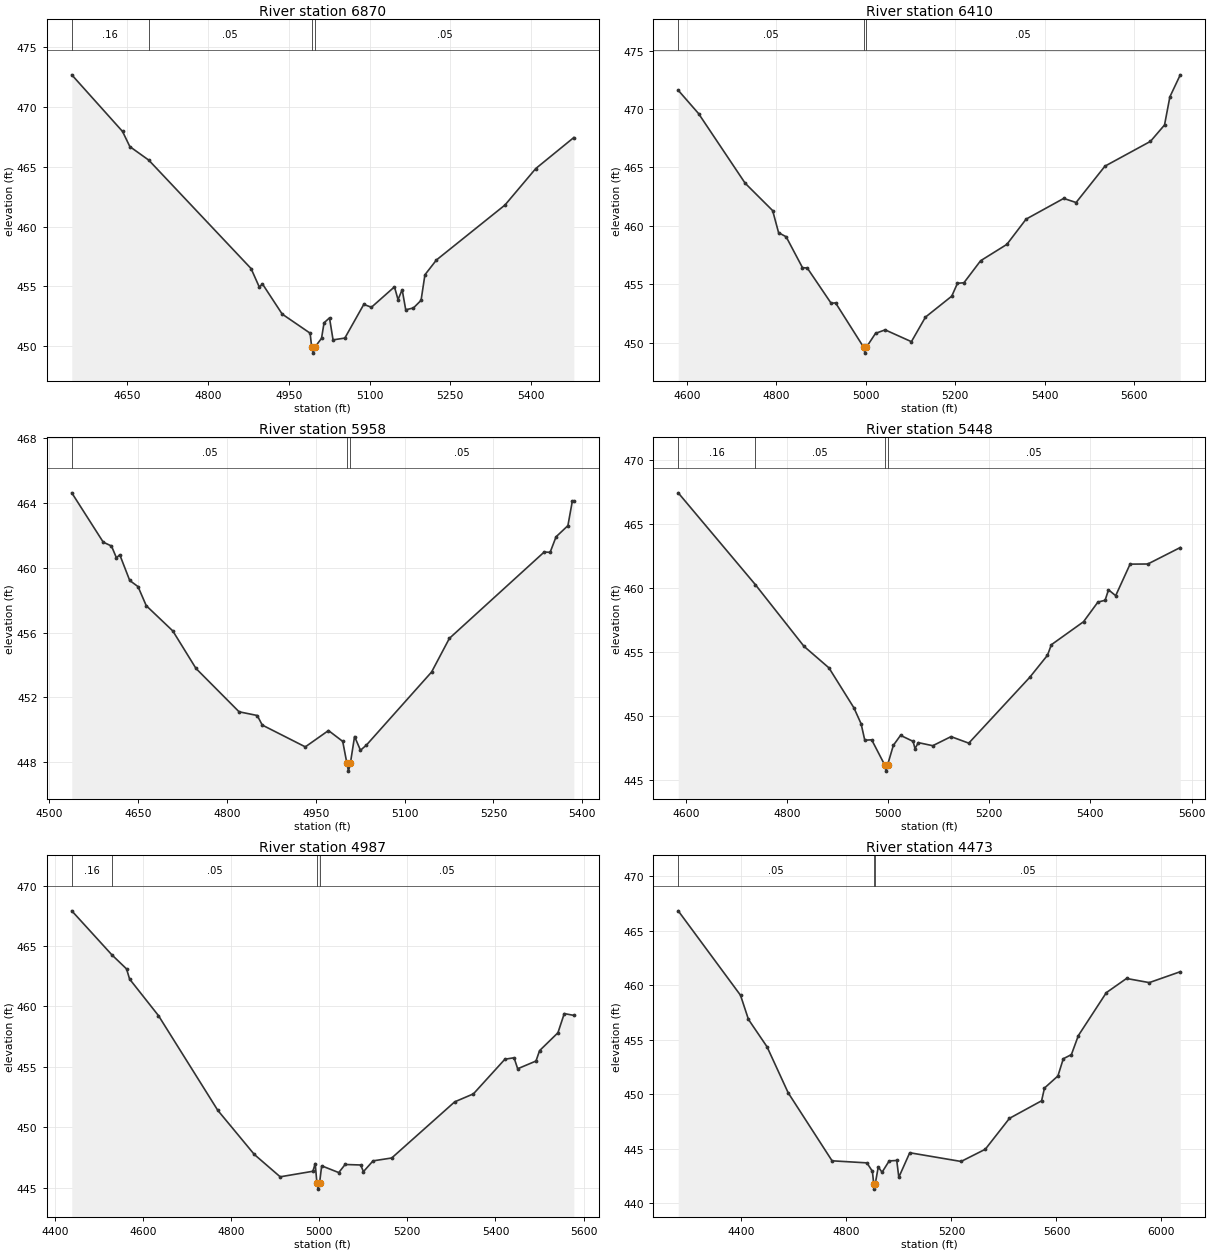
Type RM Length L Ch R = 1,6870,460,460,460
BEGIN DESCRIPTION:
UNT084 IN CCTC 12.0
END DESCRIPTION:
XS GIS Cut Line= 3
      3536099.62     10607260.21      3536349.61     10607660.19
      3536649.64     10608010.22
#Sta/Elev= 30
  4546.8  472.71  4641.1  467.97  4654.7  466.70  4689.8  465.57  4879.9  456.49
  4895.2  454.94  4901.1  455.20  4937.7  452.68  4989.6  451.08  4992.5  449.91
  4995.2  449.41  4998.5  449.91  5010.8  450.65  5015.5  451.95  5025.6  452.36
  5032.2  450.52  5054.1  450.67  5089.3  453.49  5103.5  453.25  5146.3  454.96
  5152.9  453.89  5160.6  454.72  5167.2  453.04  5181.5  453.19  5195.7  453.83
  5202.9  455.97  5224.3  457.21  5351.6  461.81  5408.7  464.86  5479.5  467.46
#Mann=4,-1,0
  4546.8    0.16       0  4689.8    0.05       0  4992.5    0.03       0
  4998.5    0.05       0
Bank Sta=4992.5,4998.5
Exp/Cntr=0.3,0.1

Type RM Length L Ch R = 1,6410,452,452,452
BEGIN DESCRIPTION:
UNT084 IN CCTC 11.0
END DESCRIPTION:
XS GIS Cut Line= 3
      3535799.60     10607460.16      3535949.61     10607860.19
      3536549.65     10608210.21
#Sta/Elev= 30
  4580.9  471.60  4626.3  469.61  4730.5  463.65  4791.9  461.31  4805.2  459.42
  4822.1  459.07  4858.6  456.43  4869.3  456.40  4922.7  453.38  4932.5  453.42
  4995.3  449.62  4998.1  449.12  5001.3  449.62  5021.8  450.81  5043.3  451.11
  5102.0  450.10  5133.4  452.20  5192.1  453.99  5204.9  455.09  5219.4  455.14
  5256.6  457.02  5315.3  458.42  5358.3  460.58  5442.3  462.35  5470.0  462.00
  5534.5  465.11  5636.2  467.23  5667.6  468.63  5679.6  471.04  5702.8  472.92
#Mann=3,-1,0
  4580.9    0.05       0  4995.3    0.03       0  5001.3    0.05       0
Bank Sta=4995.3,5001.3
Exp/Cntr=0.3,0.1

Type RM Length L Ch R = 1,5958,510,510,510
BEGIN DESCRIPTION:
UNT084 IN CCTC 10.0
END DESCRIPTION:
XS GIS Cut Line= 3
      3535399.63     10607710.22      3535599.61     10608110.19
      3535599.61     10608510.21
#Sta/Elev= 30
  4538.5  464.64  4591.6  461.59  4605.5  461.35  4613.9  460.62  4619.5  460.81
  4636.3  459.22  4650.3  458.84  4664.2  457.66  4709.0  456.10  4748.1  453.78
  4820.8  451.10  4851.5  450.87  4859.9  450.28  4932.6  448.93  4971.7  449.94
  4995.7  449.27  5002.7  447.93  5005.4  447.43  5008.7  447.93  5015.7  449.57
  5025.7  448.72  5035.7  449.04  5145.7  453.56  5175.7  455.64  5335.7  460.98
  5345.7  460.96  5355.7  461.92  5375.7  462.61  5383.2  464.13  5385.7  464.13
#Mann=3,-1,0
  4538.5    0.05       0  5002.7    0.03       0  5008.7    0.05       0
Bank Sta=5002.7,5008.7
Exp/Cntr=0.3,0.1

Type RM Length L Ch R = 1,5448,461,461,461
BEGIN DESCRIPTION:
UNT084 IN CCTC 9.0
END DESCRIPTION:
XS GIS Cut Line= 3
      3534799.63     10607910.21      3535149.61     10608210.19
      3535549.64     10608560.22
#Sta/Elev= 30
  4585.1  467.46  4737.5  460.28  4833.7  455.45  4883.1  453.76  4932.5  450.63
  4946.7  449.38  4953.9  448.10  4967.6  448.13  4993.1  446.18  4995.9  445.68
  4999.1  446.18  5010.4  447.70  5024.6  448.48  5049.4  448.01  5053.2  447.44
  5059.8  447.91  5088.3  447.67  5124.4  448.38  5159.5  447.87  5280.0  453.02
  5315.1  454.75  5322.7  455.57  5386.3  457.37  5414.8  458.91  5429.0  459.05
  5435.7  459.87  5449.9  459.41  5478.4  461.88  5513.5  461.89  5577.6  463.18
#Mann=4,-1,0
  4585.1    0.16       0  4737.5    0.05       0  4993.1    0.03       0
  4999.1    0.05       0
Bank Sta=4993.1,4999.1
Exp/Cntr=0.3,0.1

Type RM Length L Ch R = 1,4987,514,514,514
BEGIN DESCRIPTION:
UNT084 IN CCTC 8.0
END DESCRIPTION:
XS GIS Cut Line= 3
      3534749.62     10607960.22      3534899.61     10608510.19
      3535349.57     10608860.16
#Sta/Elev= 30
  4437.9  467.92  4529.1  464.27  4562.3  463.11  4569.2  462.27  4634.8  459.24
  4769.6  451.39  4852.5  447.74  4911.2  445.89  4985.5  446.35  4990.7  446.99
  4994.6  445.37  4997.3  444.87  5000.6  445.37  5005.4  446.80  5044.2  446.24
  5058.6  446.91  5093.9  446.87  5100.3  446.32  5122.0  447.21  5164.5  447.45
  5307.5  452.10  5350.0  452.76  5421.5  455.63  5442.3  455.75  5450.5  454.84
  5492.1  455.48  5500.2  456.34  5541.9  457.82  5556.3  459.41  5578.0  459.26
#Mann=4,-1,0
  4437.9    0.16       0  4529.1    0.05       0  4994.6    0.03       0
  5000.6    0.05       0
Bank Sta=4994.6,5000.6
Exp/Cntr=0.3,0.1

Type RM Length L Ch R = 1,4473,399,399,399
BEGIN DESCRIPTION:
UNT084 IN CCTC 7.0
END DESCRIPTION:
XS GIS Cut Line= 4
      3534525.15     10607925.11      3534427.93     10608626.49
      3534608.49     10608848.71      3535504.32     10609050.10
#Sta/Elev= 30
  4159.1  466.84  4396.4  459.09  4426.7  456.87  4497.4  454.36  4578.1  450.13
  4745.2  443.89  4878.1  443.70  4898.9  442.92  4903.8  441.79  4906.6  441.29
  4909.8  441.79  4921.2  443.33  4935.6  442.84  4962.8  443.88  4991.6  443.92
  4999.5  442.38  5041.1  444.63  5236.7  443.83  5328.9  444.95  5421.1  447.79
  5543.4  449.40  5554.4  450.57  5605.6  451.68  5626.1  453.26  5656.9  453.64
  5683.5  455.39  5790.1  459.33  5867.0  460.63  5953.6  460.25  6071.7  461.25
#Mann=3,-1,0
  4159.1    0.05       0  4903.8    0.03       0  4909.8    0.05       0
Bank Sta=4903.8,4909.8
Exp/Cntr=0.3,0.1

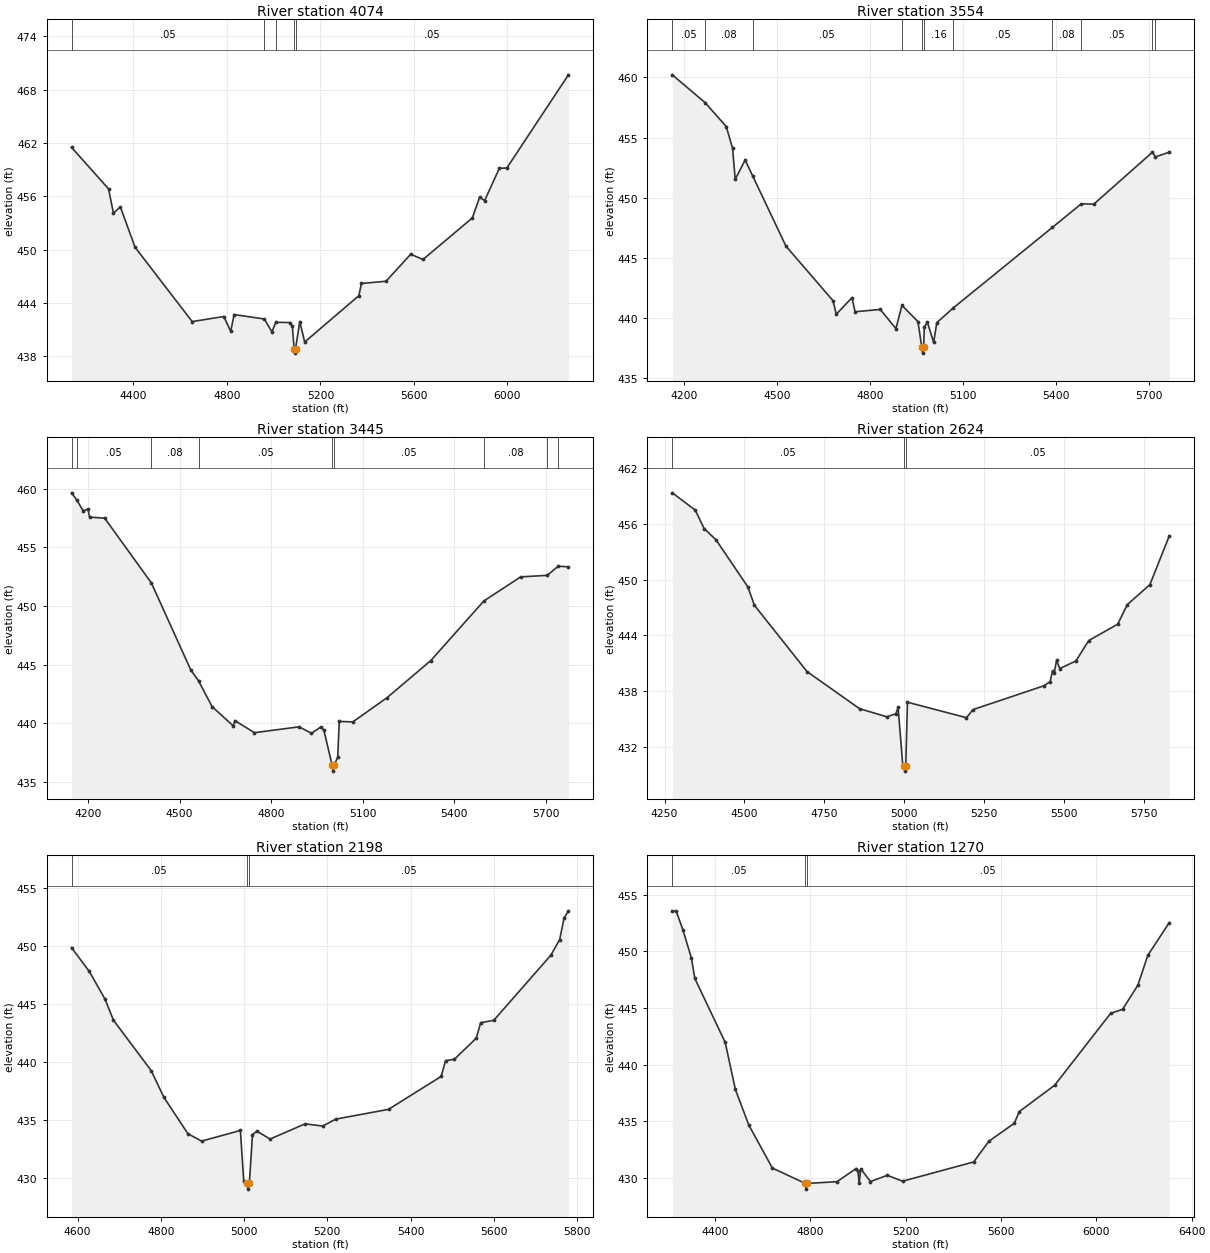
Type RM Length L Ch R = 1,4074,520,520,520
BEGIN DESCRIPTION:
UNT084 IN CCTC 6.0
END DESCRIPTION:
XS GIS Cut Line= 3
      3533749.62     10608310.21      3534249.61     10609010.19
      3534649.60     10610210.17
#Sta/Elev= 30
  4135.6  461.52  4294.1  456.84  4315.0  454.11  4344.5  454.82  4407.2  450.28
  4651.7  441.91  4786.9  442.48  4816.4  440.81  4831.1  442.70  4960.4  442.20
  4992.7  440.75  5009.3  441.83  5069.6  441.80  5080.1  441.37  5087.7  438.86
  5090.4  438.36  5093.7  438.86  5111.8  441.91  5132.8  439.61  5364.7  444.83
  5375.3  446.20  5480.7  446.45  5586.1  449.49  5638.8  448.90  5849.6  453.57
  5881.2  455.91  5902.3  455.53  5965.6  459.17  5997.2  459.19  6260.7  469.68
#Mann=5,-1,0
  4135.6    0.05       0  4960.4    0.16       0  5009.3    0.05       0
  5087.7    0.07       0  5093.7    0.05       0
Bank Sta=5087.7,5093.7
Exp/Cntr=0.3,0.1

Type RM Length L Ch R = 1,3554,109,109,109
BEGIN DESCRIPTION:
UNT084 IN CCTC 5.0
END DESCRIPTION:
XS GIS Cut Line= 3
      3533740.26     10608368.39      3533896.51     10609295.49
      3534146.52     10609910.11
#Sta/Elev= 30
  4162.0  460.21  4267.5  457.91  4336.2  455.91  4356.5  454.11  4365.1  451.53
  4397.1  453.13  4421.2  451.82  4528.9  445.97  4681.0  441.43  4691.2  440.31
  4741.9  441.69  4752.0  440.52  4833.1  440.71  4883.8  439.12  4903.3  441.05
  4954.8  439.70  4967.2  437.58  4970.0  437.08  4973.2  437.58  4975.3  439.24
  4985.3  439.65  5005.5  437.97  5015.7  439.61  5068.5  440.83  5388.8  447.53
  5482.0  449.49  5522.3  449.46  5711.6  453.78  5721.3  453.39  5765.7  453.78
#Mann=11,-1,0
  4162.0    0.05       0  4267.5    0.08       0  4421.2    0.05       0
  4903.3    0.16       0  4967.2    0.07       0  4973.2    0.16       0
  5068.5    0.05       0  5388.8    0.08       0  5482.0    0.05       0
  5711.6    0.08       0  5721.3    0.05       0
Bank Sta=4967.2,4973.2
Exp/Cntr=0.3,0.1

Type RM Length L Ch R = 1,3445,821,821,821
BEGIN DESCRIPTION:
UNT084 IN CCTC 4.0
END DESCRIPTION:
XS GIS Cut Line= 3
      3533646.50     10608352.75      3533781.93     10609264.24
      3534042.33     10609920.46
#Sta/Elev= 30
  4146.0  459.66  4163.5  459.04  4183.9  458.13  4200.1  458.27  4205.1  457.59
  4254.6  457.50  4407.4  451.98  4537.0  444.53  4562.4  443.61  4606.4  441.42
  4675.8  439.78  4680.9  440.23  4745.2  439.20  4891.5  439.70  4932.0  439.15
  4962.3  439.68  4972.4  439.43  4999.7  436.42  5002.5  435.92  5005.7  436.42
  5017.8  437.10  5023.0  440.16  5067.5  440.12  5179.7  442.19  5322.7  445.35
  5496.3  450.43  5617.1  452.49  5703.8  452.62  5740.2  453.40  5773.5  453.35
#Mann=9,-1,0
  4146.0    0.08       0  4163.5    0.05       0  4407.4    0.08       0
  4562.4    0.05       0  4999.7    0.04       0  5005.7    0.05       0
  5496.3    0.08       0  5703.8    0.05       0  5740.2    0.08       0
Bank Sta=4999.7,5005.7
Exp/Cntr=0.3,0.1

Type RM Length L Ch R = 1,2624,426,426,426
BEGIN DESCRIPTION:
UNT084 IN CCTC 3.0
END DESCRIPTION:
XS GIS Cut Line= 3
      3533549.61     10608360.19      3533099.61     10608960.19
      3532999.61     10609760.16
#Sta/Elev= 30
  4274.2  459.35  4346.1  457.49  4374.2  455.49  4410.7  454.31  4510.7  449.23
  4531.5  447.24  4696.1  440.11  4860.7  436.11  4946.1  435.24  4974.2  435.56
  4981.5  436.25  4996.1  429.99  4999.3  429.89  5002.1  429.39  5005.3  429.89
  5010.7  436.81  5195.5  435.14  5215.7  436.01  5437.4  438.57  5457.5  439.02
  5465.1  440.19  5470.1  439.90  5477.7  441.32  5487.8  440.43  5538.2  441.25
  5578.5  443.45  5669.2  445.21  5699.4  447.32  5770.0  449.47  5830.4  454.69
#Mann=3,-1,0
  4274.2    0.05       0  4999.3    0.03       0  5005.3    0.05       0
Bank Sta=4999.3,5005.3
Exp/Cntr=0.3,0.1

Type RM Length L Ch R = 1,2198,928,928,928
BEGIN DESCRIPTION:
UNT084 IN CCTC 2.0
END DESCRIPTION:
XS GIS Cut Line= 3
      3532649.61     10608560.23      3532699.61     10608960.19
      3532949.60     10609710.15
#Sta/Elev= 30
  4585.5  449.89  4628.3  447.83  4666.1  445.44  4686.2  443.63  4776.9  439.28
  4807.2  436.99  4865.1  433.84  4897.9  433.20  4991.2  434.12  4999.1  429.78
  5006.7  429.56  5009.4  429.06  5012.7  429.56  5020.2  433.76  5030.7  434.06
  5062.4  433.38  5146.7  434.69  5188.8  434.50  5220.5  435.10  5347.0  435.94
  5473.5  438.78  5484.0  440.14  5505.1  440.26  5557.8  442.08  5568.3  443.41
  5599.9  443.62  5737.0  449.24  5758.1  450.58  5768.6  452.43  5779.1  453.06
#Mann=3,-1,0
  4585.5    0.05       0  5006.7    0.03       0  5012.7    0.05       0
Bank Sta=5006.7,5012.7
Exp/Cntr=0.3,0.1

Type RM Length L Ch R = 1,1270,0,0,0
BEGIN DESCRIPTION:
UNT084 IN CCTC 1.0
END DESCRIPTION:
XS GIS Cut Line= 4
      3532224.66     10608441.31      3531807.97     10608894.45
      3531818.39     10609154.87      3532750.35     10609925.43
#Sta/Elev= 30
  4220.2  453.58  4237.1  453.53  4265.4  451.85  4300.6  449.40  4314.7  447.61
  4442.4  441.95  4484.9  437.80  4541.6  434.64  4640.3  430.85  4779.1  429.49
  4781.8  428.99  4785.1  429.49  4911.6  429.65  4991.7  430.81  4999.3  430.63
  5004.3  429.51  5011.7  430.78  5051.7  429.66  5122.9  430.21  5186.7  429.69
  5485.0  431.39  5548.9  433.22  5655.7  434.81  5676.5  435.84  5825.0  438.17
  6059.5  444.51  6110.1  444.88  6174.1  447.00  6215.8  449.64  6305.7  452.53
#Mann=3,-1,0
  4220.2    0.05       0  4779.1    0.03       0  4785.1    0.05       0
Bank Sta=4779.1,4785.1
Exp/Cntr=0.3,0.1

Chan Stop Cuts=-1