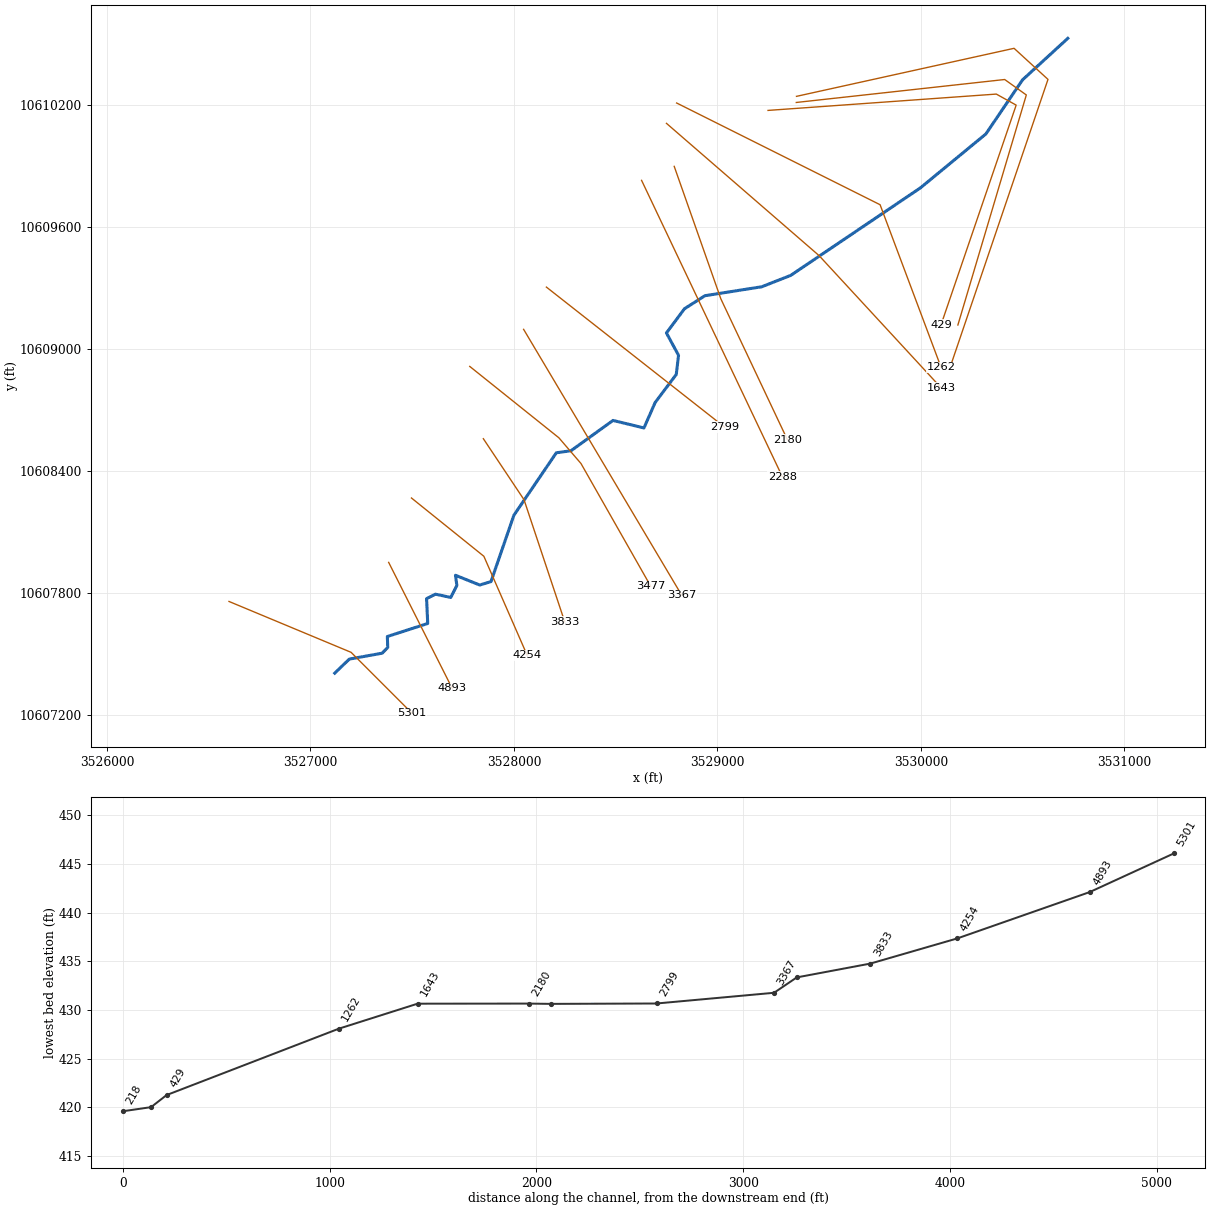
--- UNT085 IN CCTC.prj (project) ---

Proj Title=UNT085 IN CCTC Base Level Engineering
Current Plan=p01
Default Exp/Contr=0.3,0.1
English Units
Geom File=g01
Flow File=f01
Plan File=p01
Y Axis Title=Elevation
X Axis Title(PF)=Main Channel Distance
X Axis Title(XS)=Station
BEGIN DESCRIPTION:
UNT085 IN CCTC
END DESCRIPTION:
DSS Export Rating Curves= 0
DSS Export Rating Curve Sorted= 0
DSS Export Volume Flow Curves= 0
DXF OffsetX= 0
DXF OffsetY= 0
DXF ScaleX= 1
DXF ScaleY= 10

--- UNT085 IN CCTC.p01 (plan) ---

Plan Title=Multiple Run
Short Identifier=Multiple
Geom File=g01
Flow File=f01
Subcritical Flow
K Sum by GR= 0
Std Step Tol= 0.01
Critical Tol= 0.01
Num of Std Step Trials= 20
Max Error Tol= 0.3
Flow Tol Ratio= 0.001
Split Flow NTrial= 30
Split Flow Tol= 0.02
Split Flow Ratio= 0.02
Log Output Level= 0
Friction Slope Method= 1
Unsteady Friction Slope Method= 2
Unsteady Bridges Friction Slope Method= 1
Parabolic Critical Depth
Global Vel Dist=  1 , 1 , 1
Global Log Level= 0
CheckData=True
Encroach Param= -1, 0, 0, 0
BEGIN DESCRIPTION:
Multiple Run
END DESCRIPTION:

--- UNT085 IN CCTC.f01 (steady flow) ---

Flow Title=Multiple
Number of Profiles=7
Profile Names=10-year,25-year,50-year,1pct_min,100-year,1pct_plu,500-year
River Rch & RM= UNT085 IN CCTC,Reach-1,5301
     832    1119    1350    1192    1612    2180    2288
River Rch & RM= UNT085 IN CCTC,Reach-1,3477
    1631    2264    2790    2507    3390    4585    4992
Boundary for River Rch & Prof#=UNT085 IN CCTC,Reach-1,1
Up Type=0
Dn Type=3
Dn Slope=0.005
Boundary for River Rch & Prof#=UNT085 IN CCTC,Reach-1,2
Up Type=0
Dn Type=3
Dn Slope=0.005
Boundary for River Rch & Prof#=UNT085 IN CCTC,Reach-1,3
Up Type=0
Dn Type=3
Dn Slope=0.005
Boundary for River Rch & Prof#=UNT085 IN CCTC,Reach-1,4
Up Type=0
Dn Type=3
Dn Slope=0.005
Boundary for River Rch & Prof#=UNT085 IN CCTC,Reach-1,5
Up Type=0
Dn Type=3
Dn Slope=0.005
Boundary for River Rch & Prof#=UNT085 IN CCTC,Reach-1,6
Up Type=0
Dn Type=3
Dn Slope=0.005
Boundary for River Rch & Prof#=UNT085 IN CCTC,Reach-1,7
Up Type=0
Dn Type=3
Dn Slope=0.005

--- UNT085 IN CCTC.g01 (geometry) ---

Geom Title=Existing Conditions
Program Version=4.10

River Reach=UNT085 IN CCTC  ,Reach-1
Reach XY= 30
      3527119.25       10607408.        3527191.       10607477.
      3527352.25       10607506.      3527379.75       10607534.
      3527377.75       10607588.      3527576.25       10607652.
       3527570.5       10607774.        3527614.       10607796.
       3527689.5       10607780.       3527719.5       10607839.
       3527712.5       10607889.      3527831.75       10607841.
      3527887.25       10607858.      3527999.75       10608184.
      3528208.25       10608491.      3528280.25       10608501.
        3528487.       10608650.        3528639.       10608613.
        3528694.       10608738.      3528797.75       10608876.
        3528809.       10608970.       3528749.5       10609080.
      3528838.25       10609199.      3528938.75       10609263.
      3529218.25       10609307.       3529360.5       10609363.
      3529997.75       10609793.       3530319.5       10610058.
      3530499.75       10610324.      3530722.25       10610528.

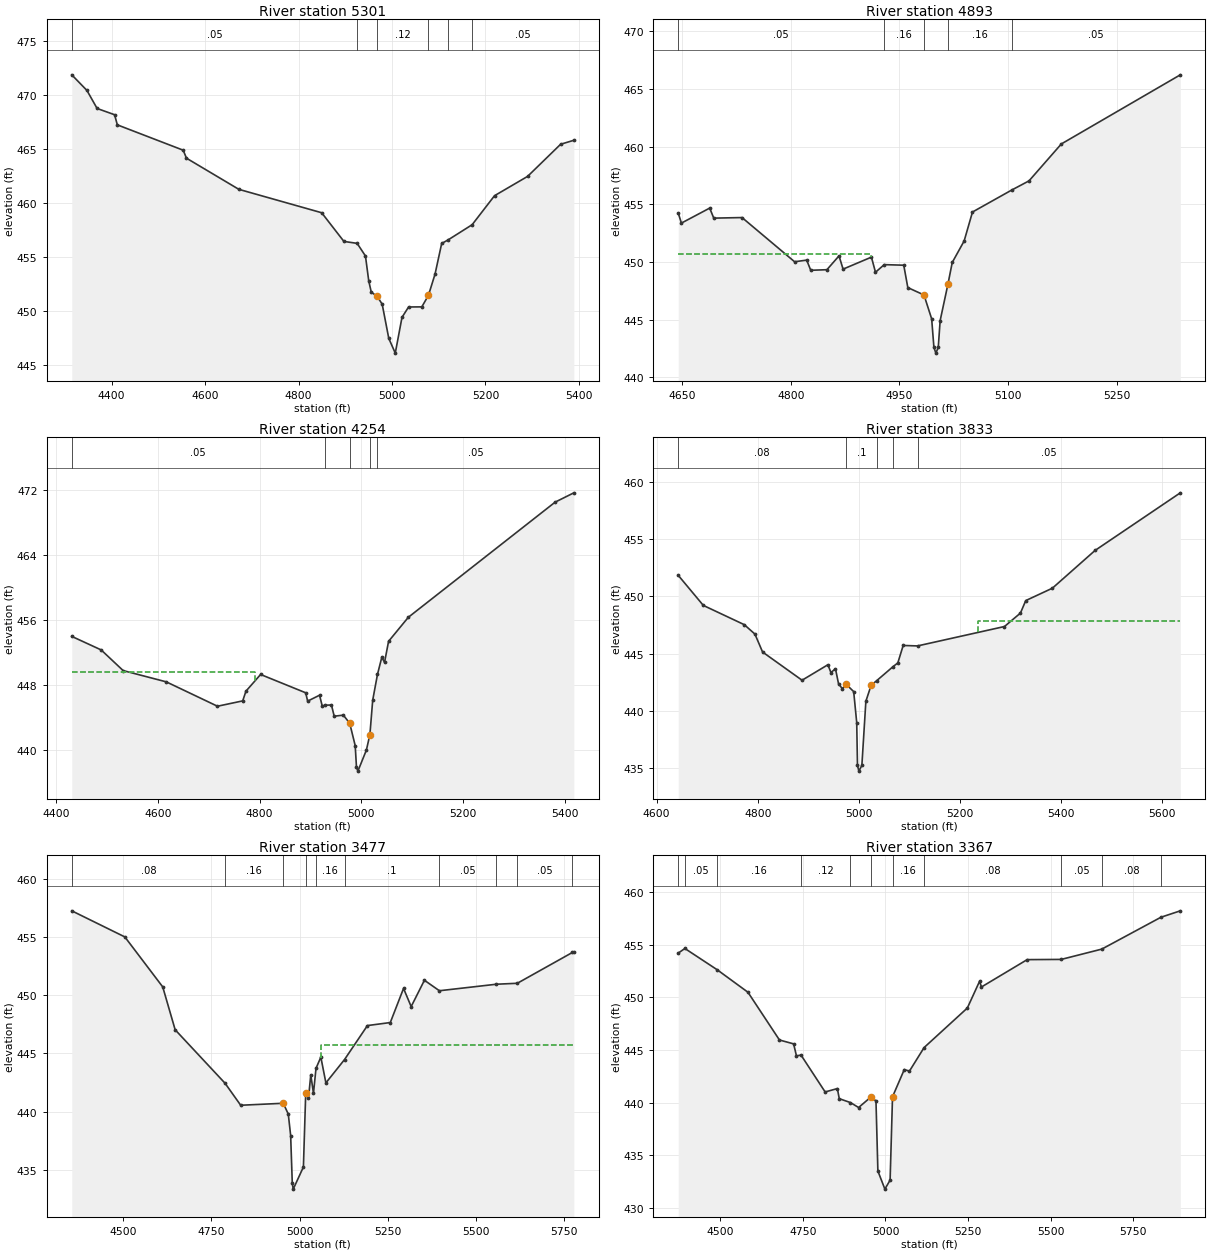
Type RM Length L Ch R = 1 ,5301    ,408,408,408
BEGIN DESCRIPTION:
UNT085 IN CCTC 11.0
END DESCRIPTION:
XS GIS Cut Line= 3
      3526599.57      10607760.2      3527199.61     10607510.19
      3527499.61     10607210.19
#Sta/Elev= 30
  4314.8   471.9  4347.3  470.45    4369  468.78  4406.4   468.2  4412.3  467.26
  4553.2  464.91  4560.2  464.17  4672.3  461.28  4849.5  459.11  4897.1  456.45
  4925.4  456.27  4943.2   455.1  4950.2   452.8  4955.6  451.75  4968.4  451.35
    4979  450.63  4993.1  447.46    5007  446.09  5021.4  449.41  5035.5  450.37
  5063.8  450.38    5078  451.45  5092.1  453.42  5106.3  456.26  5120.4   456.6
  5171.5     458  5219.4  460.69  5290.1  462.48  5360.8  465.46  5389.1  465.83
#Mann= 6 ,-1 , 0
  4314.8     .05       0  4925.4     .16       0  4968.4     .12       0
    5078     .16       0  5120.4     .16       0  5171.5     .05       0
Bank Sta=4968.4,5078
XS Rating Curve= 0 ,0
Exp/Cntr=0.3,0.1

Type RM Length L Ch R = 1 ,4893    ,639,639,639
BEGIN DESCRIPTION:
UNT085 IN CCTC 10.0
END DESCRIPTION:
XS GIS Cut Line= 2
      3527384.25     10607952.31      3527696.06     10607333.87
#Sta/Elev= 30
  4644.8  454.25  4649.2  453.38  4688.2  454.68  4693.8  453.81  4732.8  453.86
  4805.3  450.03    4822  450.17  4827.6  449.29  4849.9  449.34  4866.6  450.54
  4872.2  449.39  4911.3  450.43  4916.9  449.12    4929  449.78  4955.9  449.73
  4961.5  447.79  4983.8  447.15  4994.4  445.08  4997.5  442.61  5000.2  442.11
  5003.5  442.61  5006.1  444.93  5016.8  448.07  5022.8  449.97  5039.2  451.83
  5050.7  454.34  5104.7  456.24  5128.7  457.04  5173.3  460.24  5337.4  466.23
#Mann= 5 ,-1 , 0
  4644.8     .05       0    4929     .16       0  4983.8     .12       0
  5016.8     .16       0  5104.7     .05       0
#XS Ineff= 2 , 0
         4911.36  450.66
Permanent Ineff=
       F       F
Bank Sta=4983.8,5016.8
XS Rating Curve= 0 ,0
Exp/Cntr=0.3,0.1

Type RM Length L Ch R = 1 ,4254    ,421,421,421
BEGIN DESCRIPTION:
UNT085 IN CCTC 9.0
END DESCRIPTION:
XS GIS Cut Line= 3
      3527496.27     10608268.77      3527852.17     10607982.32
      3528064.74     10607496.44
#Sta/Elev= 30
  4430.7  453.99  4488.5  452.32  4531.7  449.77  4616.5  448.38  4717.2  445.37
  4766.8  446.03  4773.2  447.23    4802  449.29  4890.6  447.03  4894.5     446
  4917.9  446.73  4923.3  445.36  4927.7   445.5  4941.3  445.52  4946.7  444.14
  4964.7  444.27  4977.2  443.27    4988  440.51  4990.5  437.86  4993.3  437.36
    5010  439.96  5016.9  441.87  5022.4  446.11  5031.8   449.3  5040.3  451.41
  5045.7  450.79  5053.6  453.38  5092.5  456.35  5381.1  470.56  5417.9  471.71
#Mann= 5 ,-1 , 0
  4430.7     .05       0  4927.7     .16       0  4977.2     .12       0
  5016.9     .16       0  5031.8     .05       0
#XS Ineff= 2 , 0
         4791.36  449.62
Permanent Ineff=
       F       F
Bank Sta=4977.2,5016.9
XS Rating Curve= 0 ,0
Exp/Cntr=0.3,0.1

Type RM Length L Ch R = 1 ,3833    ,356,356,356
BEGIN DESCRIPTION:
UNT085 IN CCTC 8.0
END DESCRIPTION:
XS GIS Cut Line= 3
      3527849.61     10608560.19      3528049.61     10608260.19
      3528249.61      10607660.2
#Sta/Elev= 30
  4642.8  451.83  4692.4  449.21  4773.5  447.53  4794.5  446.71  4809.6  445.15
  4887.7  442.69  4938.8  444.04  4944.8  443.36  4953.8  443.69  4959.8  442.39
  4967.3  441.95  4974.8  442.34  4989.8   441.7  4995.8     439  4997.3  435.27
  5000.1  434.77    5006  435.27  5013.9  440.86  5024.4  442.26    5035  442.64
  5067.5  443.87  5077.1   444.2  5087.7  445.72  5116.1  445.68    5288  447.37
  5319.6  448.54  5330.1  449.63  5382.8  450.71  5467.2     454  5635.8  459.02
#Mann= 5 ,-1 , 0
  4642.8     .08       0  4974.8      .1       0    5035     .12       0
  5067.5     .16       0  5116.1     .05       0
#XS Ineff= 2 , 0
                         5235.45          447.83
Permanent Ineff=
       F       F
Bank Sta=4974.8,5024.4
XS Rating Curve= 0 ,0
Exp/Cntr=0.3,0.1

Type RM Length L Ch R = 1 ,3477    ,110,110,110
BEGIN DESCRIPTION:
UNT085 IN CCTC 7.0
END DESCRIPTION:
XS GIS Cut Line= 4
      3527782.71      10608915.5      3528220.94     10608564.55
       3528329.6     10608438.05      3528672.37     10607834.95
#Sta/Elev= 30
  4354.9  457.24  4505.2     455  4612.5  450.71  4647.7  447.03    4789  442.44
  4833.3  440.55  4953.9  440.72  4968.1  439.79  4974.8  437.95  4979.4  433.85
  4982.1  433.35  5010.9  435.25  5017.5  441.63  5025.2  441.14  5031.8  443.16
  5039.4  441.58  5046.6  443.72  5060.3  444.68  5074.6  442.47  5127.3  444.47
  5192.2  447.39    5257  447.65  5294.5  450.58  5316.1  449.02  5353.6  451.28
    5396  450.38  5557.7  450.94  5616.7  451.02  5772.9  453.67  5776.8  453.71
#Mann= 10 ,-1 , 0
  4354.9     .08       0    4789     .16       0  4953.9     .16       0
  5017.5     .16       0  5046.6     .16       0  5127.3      .1       0
    5396     .05       0  5557.7     .08       0  5616.7     .05       0
  5772.9     .08       0
#XS Ineff= 2 , 0
                         5060.91          445.69
Permanent Ineff=
       F       F
Bank Sta=4953.9,5017.5
XS Rating Curve= 0 ,0
Exp/Cntr=0.3,0.1

Type RM Length L Ch R = 1 ,3367    ,568,568,568
BEGIN DESCRIPTION:
UNT085 IN CCTC 6.0
END DESCRIPTION:
XS GIS Cut Line= 2
       3528047.5     10609097.74      3528824.37     10607791.38
#Sta/Elev= 30
  4372.7  454.21  4392.8  454.65  4490.5  452.63  4583.7  450.49  4679.1  445.95
    4722  445.58  4730.5  444.45  4744.5  444.51  4817.4  441.01  4854.4  441.33
  4860.2  440.37    4894     440  4918.7  439.53  4955.7  440.52  4971.3  440.16
  4977.1  433.49  4998.3  431.77  5014.1  432.63  5021.4  440.55    5057  443.14
  5072.6  442.99    5117  445.23  5247.9  448.99  5284.9  451.53  5290.7  450.99
    5429  453.59  5532.1  453.61  5654.9  454.59    5834  457.62  5892.6  458.23
#Mann= 11 ,-1 , 0
  4372.7     .08       0  4392.8     .05       0  4490.5     .16       0
  4744.5     .12       0    4894     .16       0  4955.7     .16       0
  5021.4     .16       0    5117     .08       0  5532.1     .05       0
  5654.9     .08       0    5834     .05       0
Bank Sta=4955.7,5021.4
XS Rating Curve= 0 ,0
Exp/Cntr=0.3,0.1

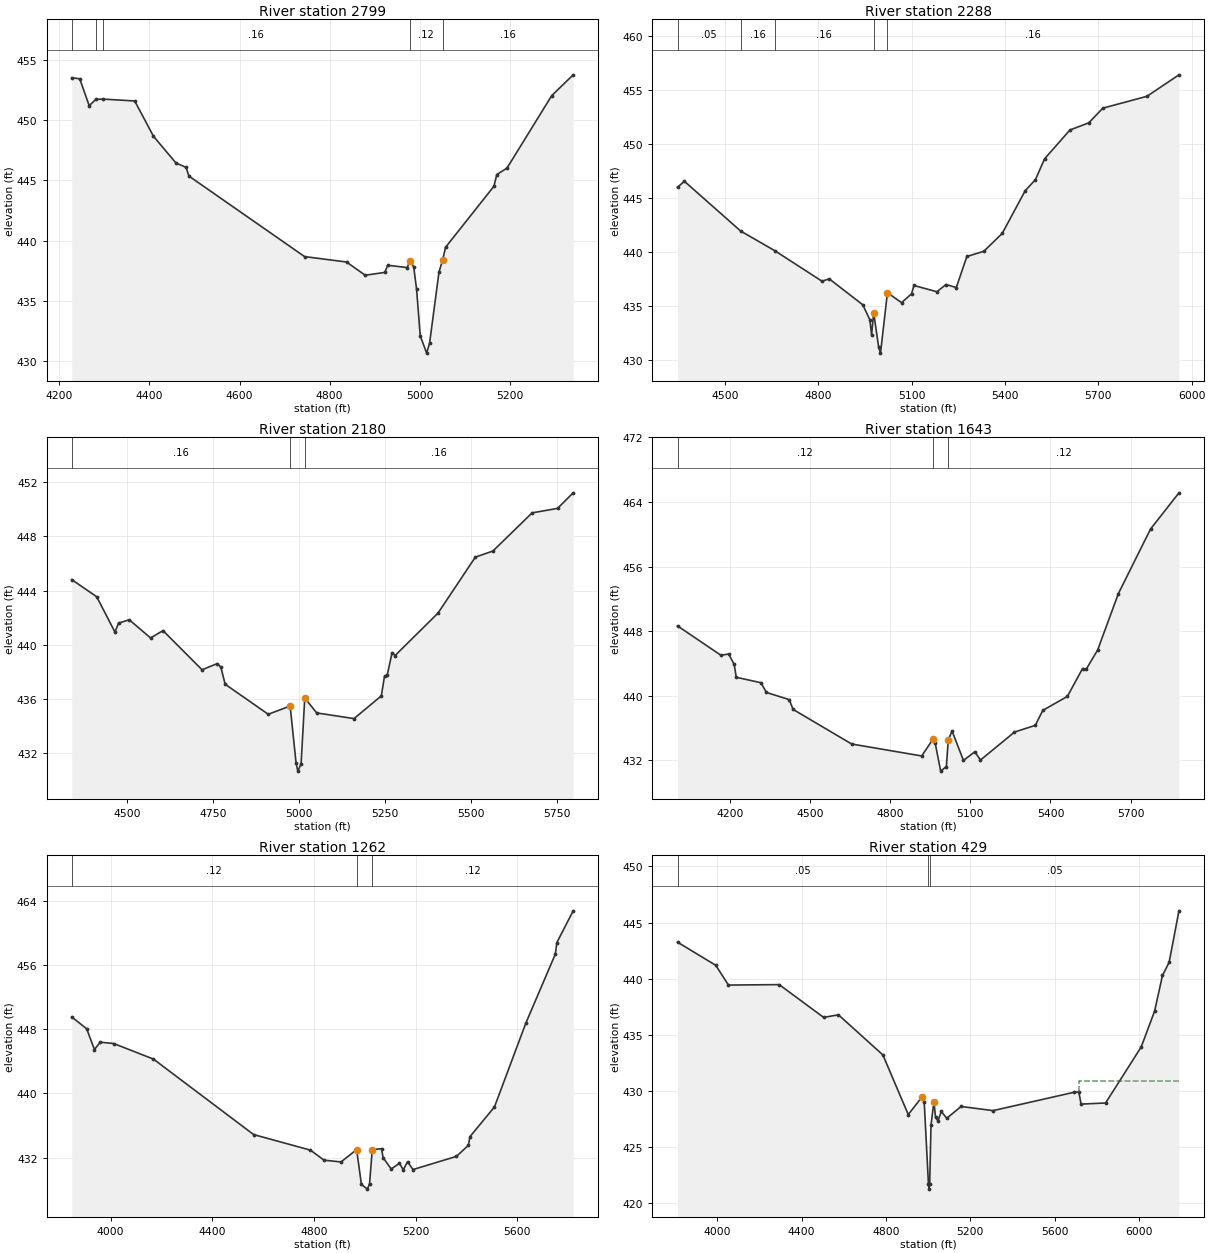
Type RM Length L Ch R = 1 ,2799    ,511,511,511
BEGIN DESCRIPTION:
UNT085 IN CCTC 5.0
END DESCRIPTION:
XS GIS Cut Line= 2
      3528159.49     10609305.36      3529034.51     10608617.85
#Sta/Elev= 30
  4227.7  453.52  4245.5  453.43  4266.4   451.2  4281.1  451.72  4296.1  451.75
  4367.5  451.59  4409.1  448.66  4458.9  446.45  4481.4  446.08  4487.8  445.36
  4744.4  438.68  4837.5  438.23  4879.1  437.13  4922.5  437.37  4928.8  437.96
  4972.2  437.77  4978.5  438.35  4986.6  437.83    4993  435.96  5001.1  432.11
  5015.3  430.67  5021.9  431.51  5042.7   437.4  5050.8  438.39  5057.2  439.45
  5164.7  444.52    5171  445.49  5193.6  446.02    5293  452.04  5340.5  453.76
#Mann= 5 ,-1 , 0
  4227.7     .05       0  4281.1     .08       0  4296.1     .16       0
  4978.5     .12       0  5050.8     .16       0
Bank Sta=4978.5,5050.8
XS Rating Curve= 0 ,0
Exp/Cntr=0.3,0.1

Type RM Length L Ch R = 1 ,2288    ,108,108,108
BEGIN DESCRIPTION:
UNT085 IN CCTC 4.0
END DESCRIPTION:
XS GIS Cut Line= 2
      3528627.32     10609830.03      3529319.21     10608373.41
#Sta/Elev= 30
  4346.6  446.01  4368.8  446.56  4550.1  441.94  4658.7  440.14  4811.7  437.29
  4834.4  437.52  4942.5  435.11  4965.2  433.72  4970.8  432.34  4977.5  434.38
  4993.5  431.18  4999.4  430.63  5021.7  436.23  5067.2  435.31  5099.2  436.13
  5107.1   436.9  5180.8  436.32  5209.9  436.99  5243.2  436.71  5277.2  439.59
  5331.7  440.07  5390.9  441.73  5464.6  445.68  5497.8  446.72  5527.2  448.65
  5608.5  451.31  5669.1  451.98  5714.5  453.34  5856.4  454.44  5959.2  456.43
#Mann= 5 ,-1 , 0
  4346.6     .05       0  4550.1     .16       0  4658.7     .16       0
  4977.5     .12       0  5021.7     .16       0
Bank Sta=4977.5,5021.7
XS Rating Curve= 0 ,0
Exp/Cntr=0.3,0.1

Type RM Length L Ch R = 1 ,2180    ,537,537,537
BEGIN DESCRIPTION:
Mapping XS 06c23fb2
END DESCRIPTION:
XS GIS Cut Line= 3
      3528787.71     10609898.69      3529016.88     10609247.63
      3529344.33     10608554.61
#Sta/Elev= 30
  4339.5  444.81  4412.1  443.54  4465.1  440.93  4475.6   441.6  4506.6  441.84
  4568.5   440.5  4604.7  441.04    4718  438.15    4762   438.6  4772.6  438.35
  4785.2  437.08  4910.4  434.86    4974  435.47  4991.3  431.24  4996.4  430.66
  5005.8  431.21  5016.4  436.06  5051.2  434.96  5159.5  434.54  5238.8  436.22
  5248.1  437.67    5256  437.76  5270.2  439.42  5278.8   439.2  5403.7  442.34
    5512  446.47    5563  446.92  5676.9  449.74  5750.7  450.07  5796.2  451.22
#Mann= 3 , 0 , 0
  4339.5     .16       0    4974     .12       0  5016.4     .16       0
Bank Sta=4974,5016.4
XS Rating Curve= 0 ,0
Exp/Cntr=0.3,0.1

Type RM Length L Ch R = 1 ,1643    ,381,381,381
BEGIN DESCRIPTION:
UNT085 IN CCTC 3.0
END DESCRIPTION:
XS GIS Cut Line= 3
       3528749.6     10610110.19      3529499.61     10609460.19
      3530099.63     10608810.17
#Sta/Elev= 30
  4003.9  448.65  4166.8     445  4195.3  445.17  4216.1  443.88  4223.8  442.28
  4315.9  441.61  4336.8   440.4  4422.3  439.51  4436.5   438.3  4655.9  434.01
    4918  432.53  4960.8  434.64  4968.4  434.15    4989  430.65  5010.3  431.22
  5017.6  434.55  5031.8  435.62  5074.3  431.97  5116.9  433.05  5137.9  432.02
  5265.4  435.49  5343.1  436.32  5371.5  438.18  5463.3  439.91    5520  443.35
  5534.2   443.3  5576.7  445.67  5654.4  452.66  5774.6  460.65    5881  465.14
#Mann= 3 , 0 , 0
  4003.9     .12       0  4960.8      .1       0  5017.6     .12       0
Bank Sta=4960.8,5017.6
XS Rating Curve= 0 ,0
Exp/Cntr=0.3,0.1

Type RM Length L Ch R = 1 ,1262    ,833,833,833
BEGIN DESCRIPTION:
UNT085 IN CCTC 2.0
END DESCRIPTION:
XS GIS Cut Line= 3
      3528799.64     10610210.17      3529799.61     10609710.19
      3530099.61     10608910.19
#Sta/Elev= 30
    3847  449.54  3905.7  448.07  3936.4  445.48  3958.8   446.4  4011.9  446.23
  4168.4  444.29  4562.5  434.88  4786.1  432.94  4839.2  431.69  4906.3  431.47
  4967.7  433.01  4986.4  428.66  5010.1  428.08  5018.4  428.76  5029.1  433.01
  5065.6  433.12  5071.8     432  5103.8  430.59  5135.9   431.3    5151  430.49
  5167.9   431.5  5189.3  430.52  5360.2  432.16  5407.3  433.55  5413.6  434.63
  5509.7  438.32  5633.4  448.79  5749.1  457.37  5755.3  458.82  5819.4  462.77
#Mann= 3 , 0 , 0
    3847     .12       0  4967.7      .1       0  5029.1     .12       0
Bank Sta=4967.7,5029.1
XS Rating Curve= 0 ,0
Exp/Cntr=0.3,0.1

Type RM Length L Ch R = 1 ,429     ,75,75,75
BEGIN DESCRIPTION:
Mapping XS 092129cb
END DESCRIPTION:
XS GIS Cut Line= 4
      3529248.77     10610173.73      3530370.75     10610254.03
       3530468.4     10610199.77      3530099.47     10609121.18
#Sta/Elev= 30
  3812.3  443.25  3993.6  441.19  4053.8  439.43  4294.4  439.47  4504.9  436.55
  4575.1  436.78  4785.6  433.21  4905.9   427.9  4970.2  429.45  4981.6     429
  5001.5  421.76  5004.2  421.26  5007.5  421.76  5013.7  426.95  5027.4  429.05
  5035.4  427.65  5046.7  427.33  5062.4  428.18  5088.4  427.57  5156.3  428.62
  5307.6  428.25  5693.1  429.89  5714.5  429.91  5724.8  428.83  5841.1  428.93
  6010.2  433.93  6073.6  437.12  6110.8  440.29  6142.2  441.45  6188.8  446.04
#Mann= 3 ,-1 , 0
  3812.3     .05       0  5001.5     .03       0  5007.5     .05       0
#XS Ineff= 2 , 0
                          5714.2          430.85
Permanent Ineff=
       F       F
Bank Sta=4970.2,5027.4
XS Rating Curve= 0 ,0
Exp/Cntr=0.3,0.1

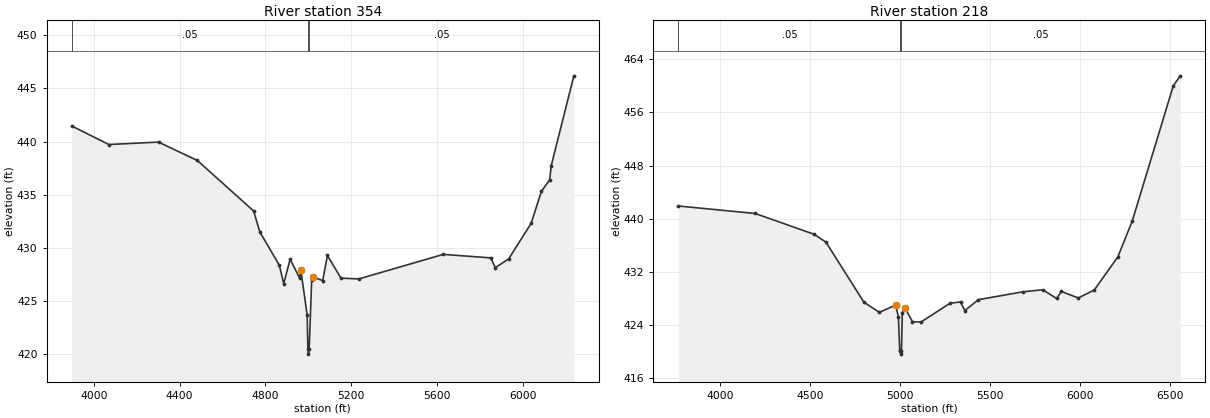
Type RM Length L Ch R = 1 ,354     ,136,136,136
BEGIN DESCRIPTION:
Mapping XS 12de9a84
END DESCRIPTION:
XS GIS Cut Line= 4
      3529387.65     10610212.79      3530411.98     10610325.64
      3530518.31     10610249.69      3530181.95     10609119.06
#Sta/Elev= 30
  3897.1  441.47  4070.1  439.73  4301.5  439.96  4482.6  438.23    4745  433.48
  4774.3  431.49  4864.9  428.38    4885  426.65  4915.2  428.94  4959.1  427.18
  4965.3  427.89  4994.8  423.66  4997.9  420.52  5000.7  420.02  5003.9  420.52
  5015.7  426.98    5023  427.26  5067.1  426.94  5089.1   429.3  5151.7  427.17
  5235.1  427.09  5629.4   429.4  5850.7  429.07  5871.6  428.15  5934.2  428.98
  6038.5  432.31  6086.9  435.33  6125.3  436.41  6132.4  437.74  6237.9  446.19
#Mann= 3 ,-1 , 0
  3897.1     .05       0  4997.9     .03       0  5003.9     .05       0
Bank Sta=4965.3,5023
XS Rating Curve= 0 ,0
Exp/Cntr=0.3,0.1

Type RM Length L Ch R = 1 ,218     ,0,0,0
BEGIN DESCRIPTION:
UNT085 IN CCTC 1.0
END DESCRIPTION:
XS GIS Cut Line= 4
       3529388.7     10610242.86      3530458.11     10610478.96
      3530624.77     10610326.19      3530152.56     10608937.33
#Sta/Elev= 30
  3768.2  441.91  4195.3  440.78  4521.5  437.66  4588.4  436.47  4798.9  427.43
  4884.8  425.89  4976.6  426.99  4990.8  425.17  4998.2  420.26    5002   420.1
  5004.7   419.6    5008   420.1  5012.4  425.86  5026.6  426.57  5068.9   424.5
  5116.3  424.43  5278.5  427.28    5336  427.45  5359.9  426.16  5435.4   427.8
  5681.1  428.98  5792.9  429.29  5869.4  427.98  5895.5  429.04  5989.6  428.06
  6078.1  429.24  6209.2  434.23  6289.3  439.62  6517.7  460.03  6556.4  461.51
#Mann= 3 ,-1 , 0
  3768.2     .05       0    5002     .03       0    5008     .05       0
Bank Sta=4976.6,5026.6
XS Rating Curve= 0 ,0
Exp/Cntr=0.3,0.1

Chan Stop Cuts=-1
Use User Specified Reach Order=0
Composite Channel Slope=5