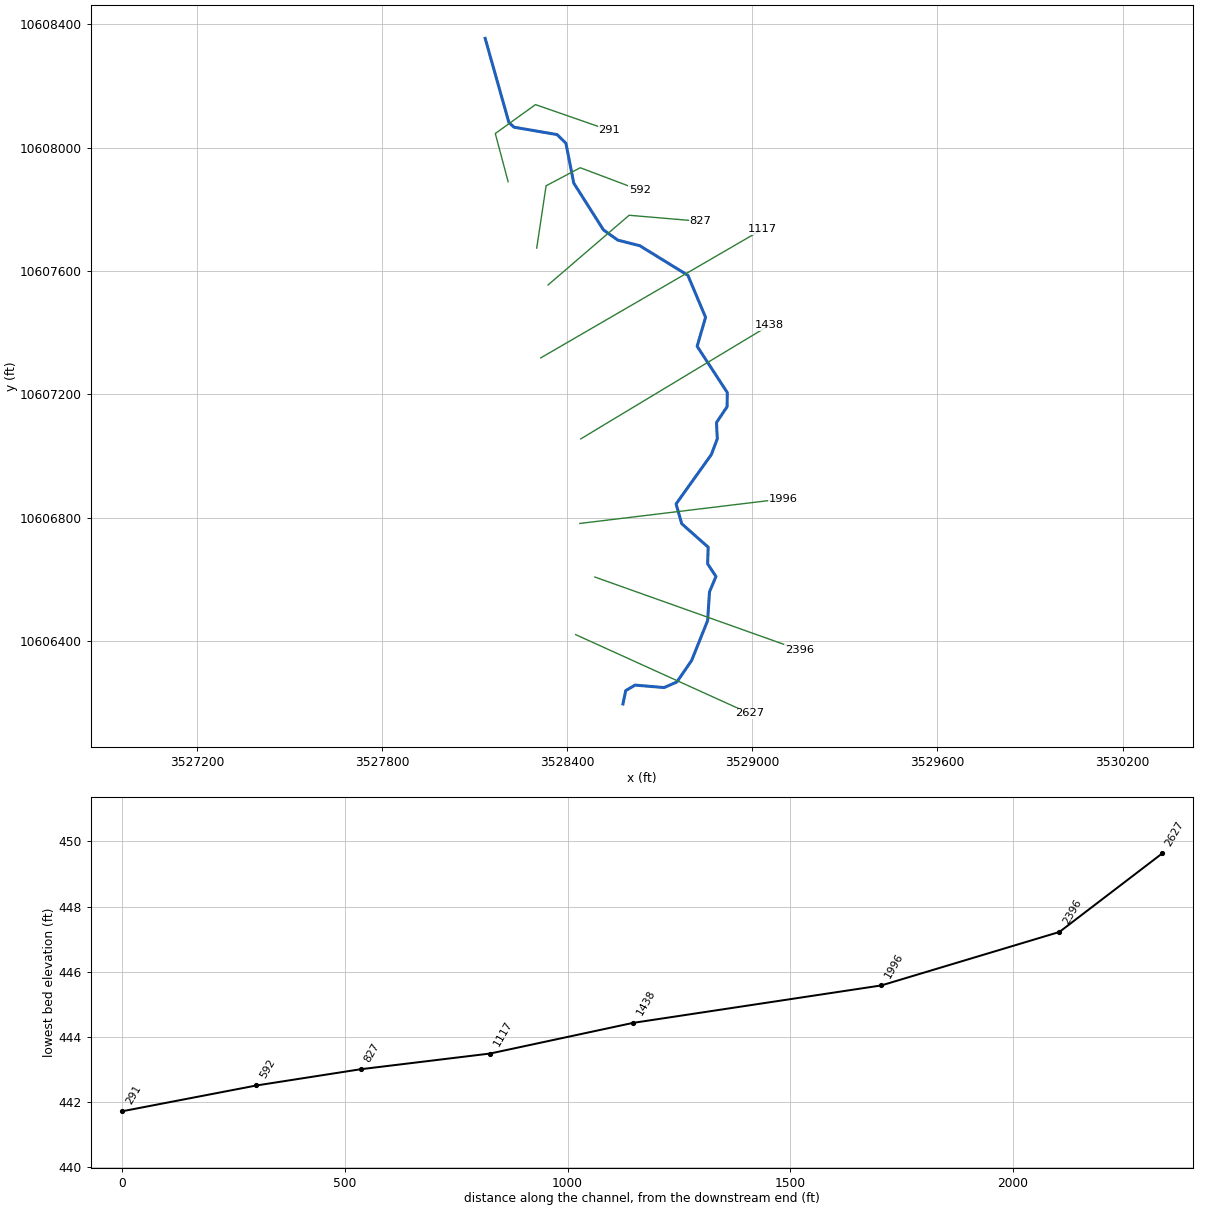
--- UNT086 IN CCTC.prj (project) ---

Proj Title=UNT086 IN CCTC Base Level Engineering
Current Plan=p01
Default Exp/Contr=0.3,0.1
English Units
Geom File=g01
Flow File=f01
Plan File=p01
Y Axis Title=Elevation
X Axis Title(PF)=Main Channel Distance
X Axis Title(XS)=Station
BEGIN DESCRIPTION:
UNT086 IN CCTC
END DESCRIPTION:
DSS Export Rating Curves= 0
DSS Export Rating Curve Sorted= 0
DSS Export Volume Flow Curves= 0
DXF OffsetX= 0
DXF OffsetY= 0
DXF ScaleX= 1
DXF ScaleY= 10

--- UNT086 IN CCTC.p01 (plan) ---

Plan Title=Multiple Run
Short Identifier=Multiple
Geom File=g01
Flow File=f01
Subcritical Flow
K Sum by GR= 0
Std Step Tol= 0.01
Critical Tol= 0.01
Num of Std Step Trials= 20
Max Error Tol= 0.3
Flow Tol Ratio= 0.001
Split Flow NTrial= 30
Split Flow Tol= 0.02
Split Flow Ratio= 0.02
Log Output Level= 0
Friction Slope Method= 1
Unsteady Friction Slope Method= 2
Unsteady Bridges Friction Slope Method= 1
Parabolic Critical Depth
Global Vel Dist=  1 , 1 , 1
Global Log Level= 0
CheckData=True
Encroach Param= -1, 0, 0, 0
BEGIN DESCRIPTION:
Multiple Run
END DESCRIPTION:

--- UNT086 IN CCTC.f01 (steady flow) ---

Flow Title=Multiple
Number of Profiles=7
Profile Names=10-year,25-year,50-year,1pct_min,100-year,1pct_plu,500-year
River Rch & RM= UNT086 IN CCTC,Reach-1,2627
     710     939    1120     978    1322    1788    1834
Boundary for River Rch & Prof#=UNT086 IN CCTC,Reach-1,1
Up Type=0
Dn Type=3
Dn Slope=0.005
Boundary for River Rch & Prof#=UNT086 IN CCTC,Reach-1,2
Up Type=0
Dn Type=3
Dn Slope=0.005
Boundary for River Rch & Prof#=UNT086 IN CCTC,Reach-1,3
Up Type=0
Dn Type=3
Dn Slope=0.005
Boundary for River Rch & Prof#=UNT086 IN CCTC,Reach-1,4
Up Type=0
Dn Type=3
Dn Slope=0.005
Boundary for River Rch & Prof#=UNT086 IN CCTC,Reach-1,5
Up Type=0
Dn Type=3
Dn Slope=0.005
Boundary for River Rch & Prof#=UNT086 IN CCTC,Reach-1,6
Up Type=0
Dn Type=3
Dn Slope=0.005
Boundary for River Rch & Prof#=UNT086 IN CCTC,Reach-1,7
Up Type=0
Dn Type=3
Dn Slope=0.005

--- UNT086 IN CCTC.g01 (geometry) ---

Geom Title=Existing Conditions
Program Version=4.10

River Reach=UNT086 IN CCTC  ,Reach-1
Reach XY= 30
      3528580.97     10606196.78        3528590.       10606240.
      3528620.25       10606258.       3528714.5       10606250.
      3528755.75       10606268.      3528803.75       10606338.
       3528855.5       10606467.       3528861.5       10606560.
       3528882.5       10606610.       3528855.5       10606651.
      3528857.25       10606705.       3528771.5       10606781.
      3528753.25       10606845.       3528867.5       10607005.
      3528886.75       10607056.      3528884.25       10607109.
       3528918.5       10607160.      3528919.25       10607206.
       3528821.5       10607356.      3528848.75       10607450.
       3528791.5       10607586.       3528635.5       10607682.
       3528564.5       10607700.        3528518.       10607733.
       3528421.5       10607885.      3528396.25       10608014.
      3528367.75       10608042.      3528228.25       10608066.
       3528211.5       10608081.       3528134.5       10608354.

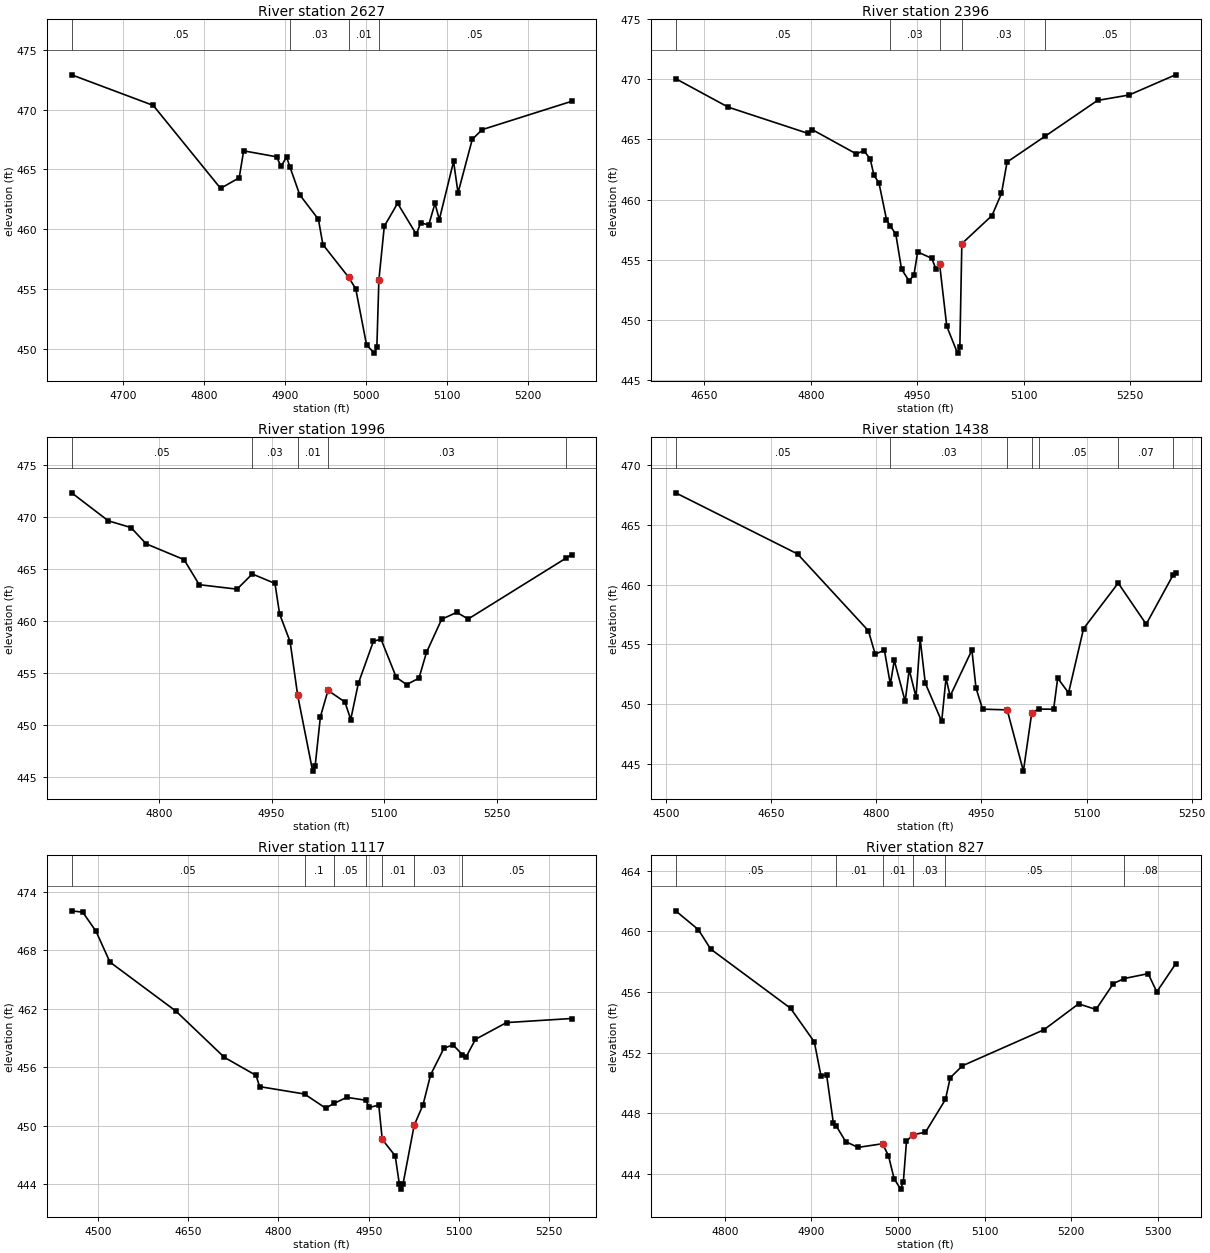
Type RM Length L Ch R = 1 ,2627    ,231,231,231
BEGIN DESCRIPTION:
UNT086 IN CCTC 6.0
END DESCRIPTION:
XS GIS Cut Line= 2
       3528427.8     10606421.52      3528990.22     10606166.35
#Sta/Elev= 30
  4636.3  472.92  4737.1  470.36  4820.3  463.42  4843.3   464.3  4848.8  466.56
  4889.5  466.06    4895  465.26  4901.8  466.04    4906  465.21  4918.1  462.88
  4941.2  460.83  4946.7  458.72  4978.7  455.96  4987.3  455.01  5000.7  450.31
  5010.2  449.63  5013.4  450.13  5015.9  455.75  5022.6  460.25    5039  462.17
  5062.1  459.58  5067.6  460.53  5077.5  460.36  5085.2  462.16  5090.6  460.81
  5108.2  465.67  5113.7  463.04  5131.3  467.52  5143.4  468.33  5253.9   470.7
#Mann= 4 ,-1 , 0
  4636.3     .05       0    4906     .03       0  4978.7     .01       0
  5015.9     .05       0
Bank Sta=4978.7,5015.9
XS Rating Curve= 0 ,0
Exp/Cntr=0.3,0.1

Type RM Length L Ch R = 1 ,2396    ,400,400,400
BEGIN DESCRIPTION:
UNT086 IN CCTC 5.0
END DESCRIPTION:
XS GIS Cut Line= 2
      3528489.91     10606608.22      3529153.04     10606372.13
#Sta/Elev= 30
  4609.8  470.06  4683.8  467.69  4796.5   465.5  4801.8  465.83  4864.2   463.8
  4874.8  464.07  4883.7  463.39    4889  462.03  4896.1  461.38  4906.7  458.34
  4911.9  457.81  4919.8  457.12  4927.9  454.21  4938.5  453.23  4945.3  453.71
  4950.6  455.64  4970.4  455.11  4976.2  454.24  4981.5  454.61  4991.6  449.45
  5006.7  447.22    5010  447.72  5012.8  456.33  5055.3  458.67  5068.6  460.51
  5076.5  463.12  5129.8  465.26  5203.9  468.25  5248.3   468.7  5313.7  470.38
#Mann= 5 ,-1 , 0
  4609.8     .05       0  4911.9     .03       0  4981.5     .01       0
  5012.8     .03       0  5129.8     .05       0
Bank Sta=4981.5,5012.8
XS Rating Curve= 0 ,0
Exp/Cntr=0.3,0.1

Type RM Length L Ch R = 1 ,1996    ,558,558,558
BEGIN DESCRIPTION:
UNT086 IN CCTC 4.0
END DESCRIPTION:
XS GIS Cut Line= 2
      3528441.28     10606781.84      3529100.96      10606861.7
#Sta/Elev= 30
  4684.3  472.33    4733  469.64  4763.2  468.99  4783.3  467.43  4833.7  465.91
  4853.9   463.5  4904.2  463.07  4924.4  464.53  4954.6  463.62  4960.7   460.7
  4974.7  458.02  4984.8  452.85  5004.7  445.58    5008  446.08    5015  450.81
  5025.1  453.34  5047.6  452.22  5055.3  450.54  5065.4  454.01  5085.5  458.07
  5095.6  458.26  5115.8   454.6  5129.5   453.9    5146  454.51    5156  456.99
  5176.2  460.18  5196.3  460.84  5211.4   460.2  5341.7  466.06  5348.8  466.39
#Mann= 5 ,-1 , 0
  4684.3     .05       0  4924.4     .03       0  4984.8     .01       0
  5025.1     .03       0  5341.7     .08       0
Bank Sta=4984.8,5025.1
XS Rating Curve= 0 ,0
Exp/Cntr=0.3,0.1

Type RM Length L Ch R = 1 ,1438    ,321,321,321
BEGIN DESCRIPTION:
UNT086 IN CCTC 3.0
END DESCRIPTION:
XS GIS Cut Line= 2
      3528444.71     10607056.13      3529055.24     10607423.83
#Sta/Elev= 30
  4514.2  467.65    4688  462.55    4789  456.14  4798.7  454.19  4811.8  454.52
  4820.3  451.68  4825.9  453.67  4841.4  450.25  4847.2  452.89  4856.9  450.61
  4862.8  455.46  4870.1  451.77  4893.5  448.58  4899.7   452.2  4905.5  450.69
  4936.6  454.53  4942.4  451.37  4951.8   449.6  4986.9  449.54    5010  444.43
    5022  449.32  5032.4  449.61  5053.1  449.59  5058.9  452.19  5074.4  450.96
  5095.8  456.32  5145.2  460.12  5185.1  456.69  5223.7  460.82  5226.9     461
#Mann= 7 ,-1 , 0
  4514.2     .05       0  4820.3     .03       0  4986.9     .01       0
    5022     .03       0  5032.4     .05       0  5145.2     .07       0
  5223.7     .05       0
Bank Sta=4986.9,5022
XS Rating Curve= 0 ,0
Exp/Cntr=0.3,0.1

Type RM Length L Ch R = 1 ,1117    ,290,290,290
BEGIN DESCRIPTION:
UNT086 IN CCTC 2.0
END DESCRIPTION:
XS GIS Cut Line= 2
       3528314.6     10607318.36      3529032.99     10607735.07
#Sta/Elev= 30
  4456.4  472.05  4474.8  471.91  4496.9  469.95    4520  466.79  4629.6  461.76
    4710  457.02  4762.8  455.16  4768.7  454.01  4843.3  453.25  4878.4   451.8
  4892.1  452.28  4913.6  452.91  4945.1  452.61  4950.9  451.87  4966.7  452.11
  4972.4   448.6    4994   446.9  5000.9  443.99  5003.7  443.49  5006.9  443.99
  5025.5  450.04  5040.2  452.14  5052.8  455.22  5074.9  457.94    5090   458.3
  5105.4   457.3  5111.6  457.04  5127.3  458.86  5178.9  460.58  5286.9     461
#Mann= 7 ,-1 , 0
  4456.4     .05       0  4843.3      .1       0  4892.1     .05       0
  4945.1     .03       0  4972.4     .01       0  5025.5     .03       0
  5105.4     .05       0
Bank Sta=4972.4,5025.5
XS Rating Curve= 0 ,0
Exp/Cntr=0.3,0.1

Type RM Length L Ch R = 1 ,827     ,235,235,235
BEGIN DESCRIPTION:
Mapping XS cd0b0918
END DESCRIPTION:
XS GIS Cut Line= 3
      3528338.49     10607554.92      3528601.09     10607780.62
      3528831.09     10607761.09
#Sta/Elev= 30
  4743.3  461.35  4769.5  460.11  4783.7  458.83  4875.9  454.93  4903.4  452.71
    4911  450.49  4917.6  450.53  4925.3  447.39  4928.6  447.18  4939.6  446.14
  4953.8  445.76  4982.1     446    4989  445.21  4995.5   443.7    5003  443.01
  5006.2  443.51  5009.8  446.17  5017.5   446.6  5031.7  446.76  5054.8  448.92
  5060.3  450.35  5074.4  451.14  5168.4  453.51  5208.5  455.22  5228.6  454.85
  5248.7  456.56  5261.3  456.89  5288.8  457.21  5298.8  456.01  5320.4  457.84
#Mann= 6 ,-1 , 0
  4743.3     .05       0  4928.6     .01       0  4982.1     .01       0
  5017.5     .03       0  5054.8     .05       0  5261.3     .08       0
Bank Sta=4982.1,5017.5
XS Rating Curve= 0 ,0
Exp/Cntr=0.3,0.1

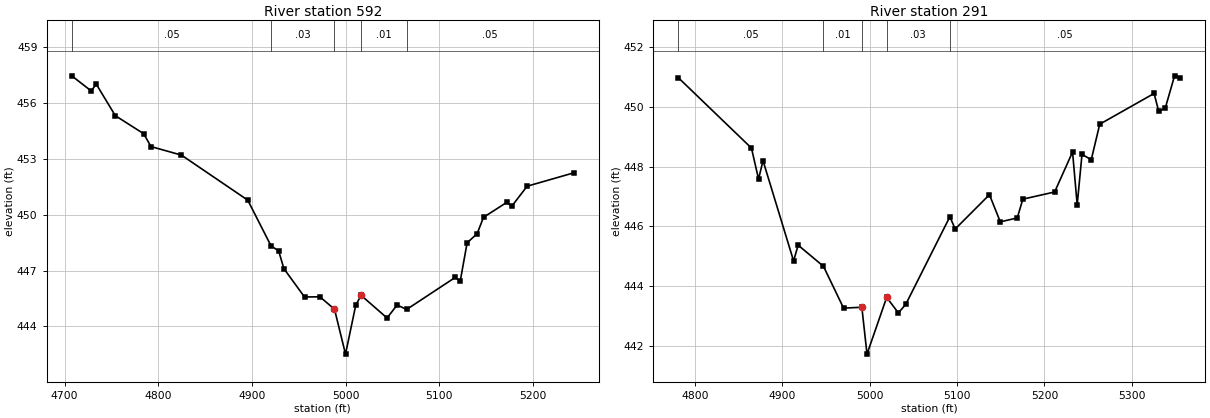
Type RM Length L Ch R = 1 ,592     ,301,301,301
BEGIN DESCRIPTION:
Mapping XS 119eca22
END DESCRIPTION:
XS GIS Cut Line= 4
       3528301.6     10607674.25      3528331.99     10607876.11
      3528442.67      10607934.7      3528636.25     10607861.57
#Sta/Elev= 30
  4707.6  457.46  4728.3  456.65  4733.8  457.01  4754.1  455.32  4784.4  454.35
  4792.2  453.66  4824.8   453.2  4895.6  450.78  4920.4  448.33  4928.6  448.05
  4934.2   447.1  4956.2  445.58  4972.6  445.59  4987.6  444.95  4988.2  444.93
    5000  442.51  5010.9  445.13  5016.6  445.67  5044.4  444.45  5055.1  445.15
  5065.3  444.91  5117.2  446.63  5122.5  446.42  5129.9  448.49  5140.6  448.98
  5147.4  449.86  5172.2  450.66  5177.5  450.45    5194  451.53  5243.9  452.25
#Mann= 5 ,-1 , 0
  4707.6     .05       0  4920.4     .03       0  4987.6     .01       0
  5016.6     .01       0  5065.3     .05       0
Bank Sta=4988.2,5016.6
XS Rating Curve= 0 ,0
Exp/Cntr=0.3,0.1

Type RM Length L Ch R = 1 ,291     ,0,0,0
BEGIN DESCRIPTION:
UNT086 IN CCTC 1.0
END DESCRIPTION:
XS GIS Cut Line= 4
      3528209.02      10607889.2      3528167.34     10608045.49
      3528297.55     10608139.24      3528535.85     10608056.36
#Sta/Elev= 30
    4781  450.98  4864.8  448.62  4872.9  447.58    4878   448.2    4913  444.84
  4918.2  445.37  4947.2  444.66  4970.2  443.26  4991.1  443.29    4997  441.72
  5019.5  443.62  5032.9   443.1  5041.4  443.39  5091.8  446.32  5097.9  445.91
  5137.1  447.06  5149.5  446.15  5168.9  446.28  5175.3  446.91  5211.7  447.15
  5232.2  448.49  5237.5  446.72    5243  448.41  5253.6  448.23  5263.3  449.42
  5325.5  450.45  5330.8  449.85  5338.3  449.96  5348.9  451.04  5355.5  450.98
#Mann= 5 ,-1 , 0
    4781     .05       0  4947.2     .01       0  4991.1     .01       0
  5019.5     .03       0  5091.8     .05       0
Bank Sta=4991.1,5019.5
XS Rating Curve= 0 ,0
Exp/Cntr=0.3,0.1

Chan Stop Cuts=-1
Use User Specified Reach Order=0
Composite Channel Slope=5