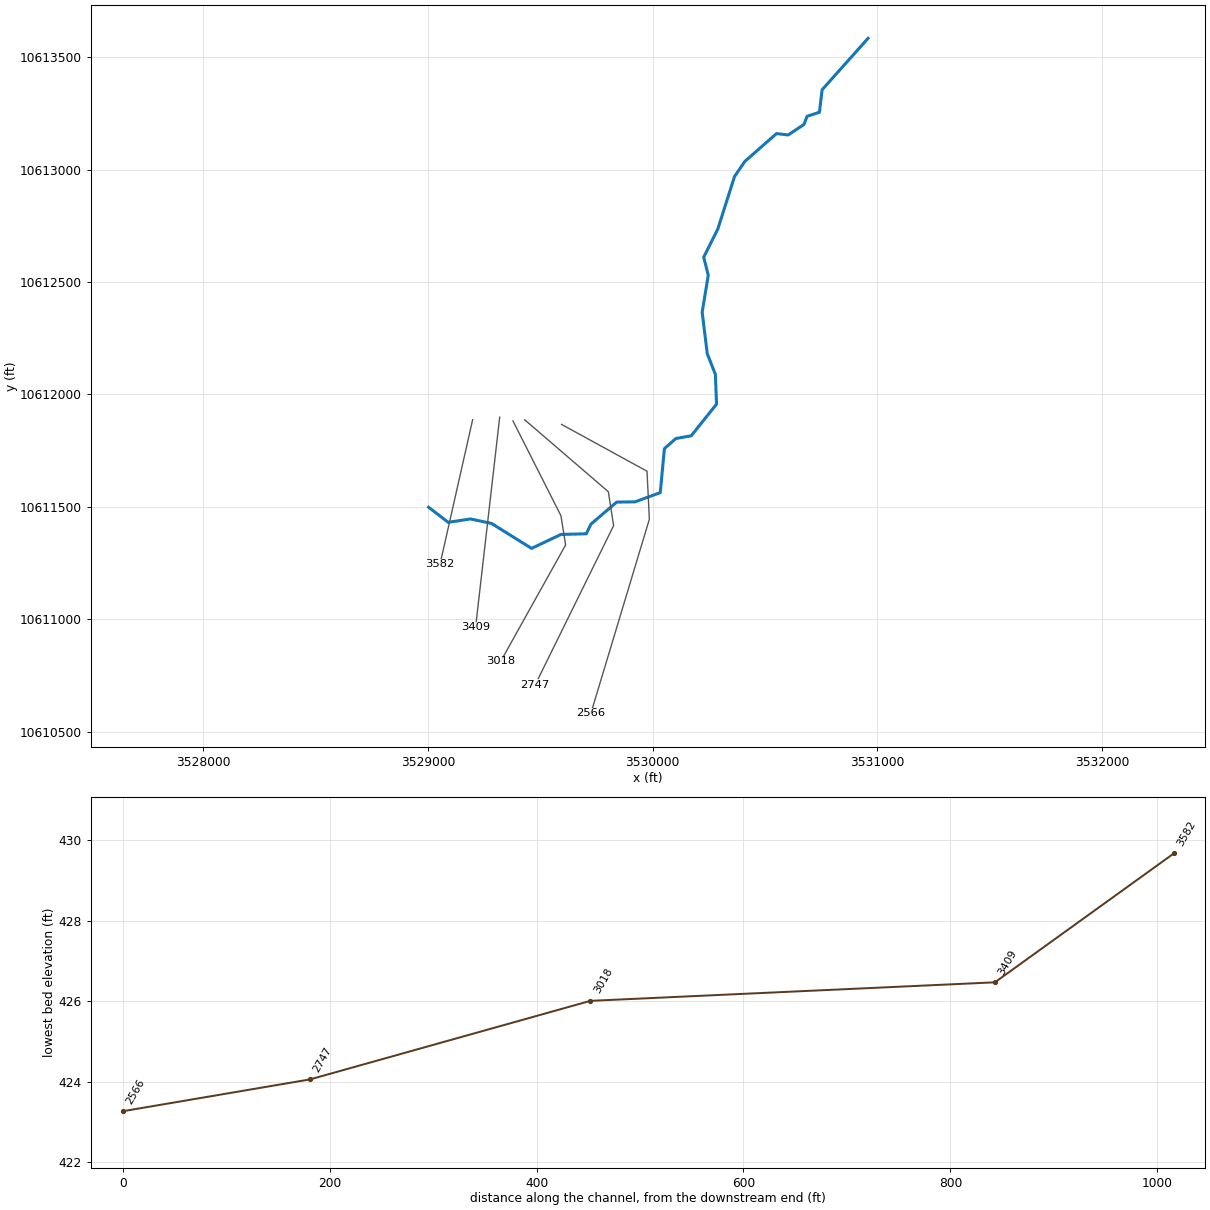
--- UNT087 IN CCTC.prj (project) ---

Proj Title=UNT087 IN CCTC Base Level Engineering
Current Plan=p01
Default Exp/Contr=0.3,0.1
English Units
Geom File=g01
Flow File=f01
Plan File=p01
BEGIN DESCRIPTION:
UNT087 IN CCTC
END DESCRIPTION:

--- UNT087 IN CCTC.p01 (plan) ---

Plan Title=Multiple Run
Short Identifier=Multiple
Geom File=g01
Flow File=f01
Subcritical Flow
K Sum by GR= 0
Std Step Tol= 0.01
Critical Tol= 0.01
Num of Std Step Trials= 20
Max Error Tol= 0.3
Flow Tol Ratio= 0.001
Split Flow NTrial= 30
Split Flow Tol= 0.02
Split Flow Ratio= 0.02
Log Output Level= 0
Friction Slope Method= 1
Unsteady Friction Slope Method= 2
Unsteady Bridges Friction Slope Method= 1
Parabolic Critical Depth
Global Vel Dist=  1 , 1 , 1
Global Log Level= 0
CheckData=True
Encroach Param= -1, 0, 0, 0
BEGIN DESCRIPTION:
Multiple Run
END DESCRIPTION:

--- UNT087 IN CCTC.f01 (steady flow) ---

Flow Title=Multiple
Number of Profiles=7
Profile Names=10-year,25-year,50-year,1pct_min,100-year,1pct_plu,500-year
River Rch & RM= UNT087 IN CCTC,Reach-1,3582
     749     997    1196    1049    1418    1918    1986
Boundary for River Rch & Prof#=UNT087 IN CCTC,Reach-1,1
Up Type=0
Dn Type=3
Dn Slope=0.005
Boundary for River Rch & Prof#=UNT087 IN CCTC,Reach-1,2
Up Type=0
Dn Type=3
Dn Slope=0.005
Boundary for River Rch & Prof#=UNT087 IN CCTC,Reach-1,3
Up Type=0
Dn Type=3
Dn Slope=0.005
Boundary for River Rch & Prof#=UNT087 IN CCTC,Reach-1,4
Up Type=0
Dn Type=3
Dn Slope=0.005
Boundary for River Rch & Prof#=UNT087 IN CCTC,Reach-1,5
Up Type=0
Dn Type=3
Dn Slope=0.005
Boundary for River Rch & Prof#=UNT087 IN CCTC,Reach-1,6
Up Type=0
Dn Type=3
Dn Slope=0.005
Boundary for River Rch & Prof#=UNT087 IN CCTC,Reach-1,7
Up Type=0
Dn Type=3
Dn Slope=0.005

--- UNT087 IN CCTC.g01 (geometry) ---

Geom Title=Existing Conditions

River Reach=UNT087 IN CCTC,Reach-1
Reach XY= 30
      3529002.00     10611498.32      3529089.25     10611431.00
      3529189.00     10611446.00      3529282.25     10611426.00
      3529460.50     10611315.00      3529591.25     10611377.00
      3529704.25     10611380.00      3529724.75     10611423.00
      3529839.50     10611521.00      3529920.50     10611522.00
      3530033.25     10611563.00      3530051.75     10611759.00
      3530102.75     10611804.00      3530171.00     10611816.00
      3530283.75     10611957.00      3530278.50     10612090.00
      3530242.50     10612181.00      3530219.75     10612366.00
      3530247.00     10612531.00      3530226.50     10612611.00
      3530290.00     10612738.00      3530363.75     10612970.00
      3530409.50     10613037.00      3530550.50     10613161.00
      3530602.75     10613155.00      3530673.00     10613202.00
      3530686.75     10613238.00      3530741.75     10613256.00
      3530753.50     10613356.00      3530958.00     10613585.00

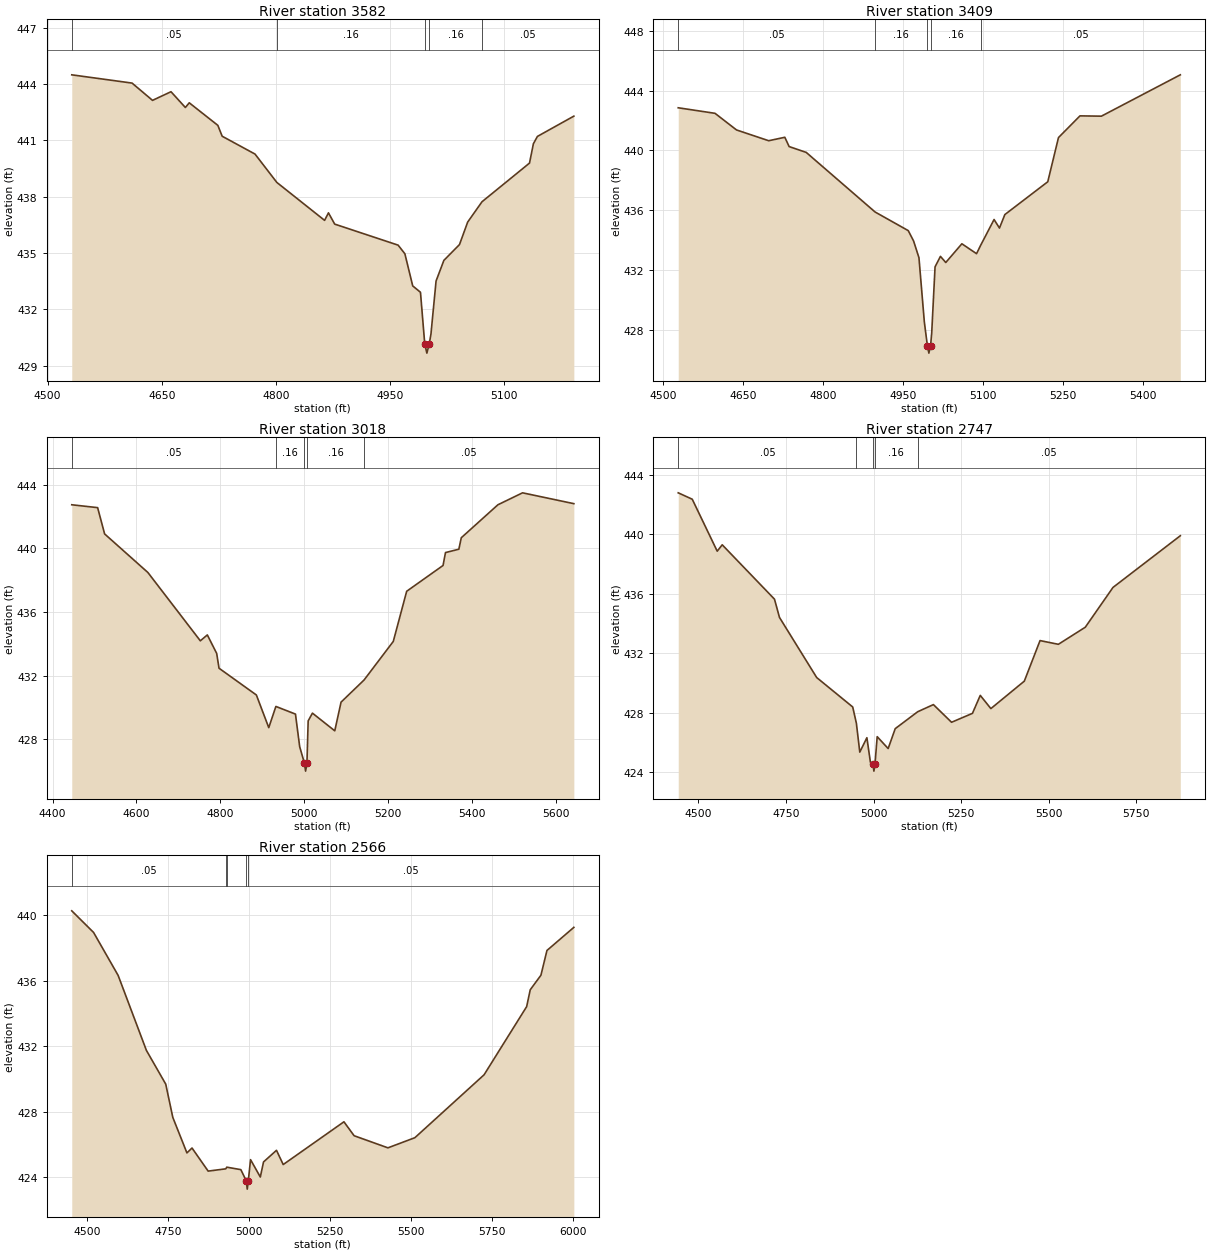
Type RM Length L Ch R = 1,3582,173,173,173
BEGIN DESCRIPTION:
UNT087 IN CCTC 2.0
END DESCRIPTION:
XS GIS Cut Line= 2
      3529198.29     10611887.53      3529052.85     10611243.44
#Sta/Elev= 30
  4531.7  444.49  4611.0  444.05  4637.9  443.13  4662.2  443.59  4681.1  442.75
  4686.2  443.00  4723.8  441.80  4729.5  441.22  4772.7  440.27  4801.4  438.76
  4864.2  436.74  4869.3  437.14  4877.5  436.54  4960.9  435.42  4969.8  434.96
  4980.1  433.25  4990.3  432.91  4995.9  430.17  4998.7  429.67  5001.9  430.17
  5004.1  430.69  5010.8  433.51  5021.1  434.61  5041.6  435.45  5052.4  436.65
  5071.2  437.73  5133.7  439.79  5138.8  440.82  5144.1  441.21  5192.0  442.29
#Mann=5,-1,0
  4531.7    0.05       0  4801.4    0.16       0  4995.9    0.07       0
  5001.9    0.16       0  5071.2    0.05       0
Bank Sta=4995.9,5001.9
Exp/Cntr=0.3,0.1

Type RM Length L Ch R = 1,3409,391,391,391
BEGIN DESCRIPTION:
Mapping XS 229fed10
END DESCRIPTION:
XS GIS Cut Line= 2
      3529318.68     10611898.75      3529211.27     10610963.20
#Sta/Elev= 30
  4527.9  442.85  4596.9  442.48  4637.2  441.37  4697.6  440.65  4727.8  440.88
  4735.9  440.26  4768.0  439.87  4897.2  435.89  4959.3  434.65  4969.3  433.96
  4979.4  432.84  4989.5  428.55  4995.2  426.97  4998.0  426.47  5001.2  426.97
  5003.3  427.80  5009.6  432.23  5019.7  432.93  5029.7  432.52  5059.9  433.77
  5087.4  433.11  5095.6  433.70  5120.3  435.39  5130.4  434.82  5140.5  435.72
  5221.0  437.91  5241.1  440.86  5281.4  442.31  5321.6  442.29  5469.6  445.05
#Mann=5,-1,0
  4527.9    0.05       0  4897.2    0.16       0  4995.2    0.07       0
  5001.2    0.16       0  5095.6    0.05       0
Bank Sta=4995.2,5001.2
Exp/Cntr=0.3,0.1

Type RM Length L Ch R = 1,3018,271,271,271
BEGIN DESCRIPTION:
Mapping XS c46e7022
END DESCRIPTION:
XS GIS Cut Line= 4
      3529377.72     10611882.23      3529591.25     10611460.38
      3529612.08     10611330.17      3529323.00     10610811.92
#Sta/Elev= 30
  4445.6  442.73  4507.3  442.55  4524.0  440.90  4627.2  438.48  4752.4  434.19
  4769.1  434.56  4791.4  433.40  4797.0  432.47  4886.1  430.79  4915.7  428.74
  4932.7  430.07  4979.4  429.59  4989.5  427.54  5000.8  426.51  5003.6  426.01
  5006.8  426.51  5009.7  429.16  5019.9  429.65  5073.2  428.54  5088.2  430.34
  5143.1  431.73  5212.8  434.15  5244.8  437.30  5331.6  438.92  5337.4  439.73
  5369.3  439.94  5375.1  440.66  5462.5  442.73  5521.3  443.48  5643.7  442.80
#Mann=5,-1,0
  4445.6    0.05       0  4932.7    0.16       0  5000.8    0.07       0
  5006.8    0.16       0  5143.1    0.05       0
Bank Sta=5000.8,5006.8
Exp/Cntr=0.3,0.1

Type RM Length L Ch R = 1,2747,181,181,181
BEGIN DESCRIPTION:
Mapping XS 500886d2
END DESCRIPTION:
XS GIS Cut Line= 4
      3529429.83     10611887.44      3529802.19     10611567.15
      3529825.63     10611416.11      3529476.68     10610707.80
#Sta/Elev= 30
  4442.2  442.80  4482.2  442.37  4553.5  438.87  4567.8  439.30  4717.0  435.64
  4731.3  434.41  4837.6  430.36  4940.4  428.38  4950.9  427.28  4960.6  425.34
  4980.9  426.31  4991.0  424.65  4998.1  424.56  5000.9  424.06  5004.1  424.56
  5010.3  426.38  5041.6  425.58  5061.8  426.92  5126.0  428.06  5170.8  428.54
  5222.6  427.35  5282.3  427.95  5304.6  429.16  5334.9  428.27  5430.4  430.12
  5475.3  432.85  5527.6  432.60  5604.5  433.75  5683.6  436.43  5875.8  439.91
#Mann=5,-1,0
  4442.2    0.05       0  4950.9    0.16       0  4998.1    0.07       0
  5004.1    0.16       0  5126.0    0.05       0
Bank Sta=4998.1,5004.1
Exp/Cntr=0.3,0.1

Type RM Length L Ch R = 1,2566,0,0,0
BEGIN DESCRIPTION:
UNT087 IN CCTC 1.0
END DESCRIPTION:
XS GIS Cut Line= 4
      3529594.10     10611866.74      3529974.34     10611658.39
      3529984.76     10611444.85      3529724.47     10610580.68
#Sta/Elev= 30
  4453.2  440.26  4520.5  438.94  4596.3  436.32  4683.6  431.74  4743.3  429.68
  4765.1  427.65  4808.7  425.48  4824.4  425.78  4874.2  424.37  4928.8  424.51
  4931.7  424.61  4975.1  424.46  4992.1  423.77  4994.9  423.27  4998.1  423.77
  5005.1  425.07  5035.2  424.01  5045.2  424.93  5085.2  425.64  5105.9  424.77
  5293.4  427.38  5324.8  426.53  5429.2  425.79  5512.4  426.41  5726.0  430.25
  5857.4  434.41  5868.5  435.44  5901.5  436.33  5920.1  437.84  6003.1  439.25
#Mann=5,-1,0
  4453.2    0.05       0  4928.8    0.16       0  4931.7    0.05       0
  4992.1    0.03       0  4998.1    0.05       0
Bank Sta=4992.1,4998.1
Exp/Cntr=0.3,0.1

Chan Stop Cuts=-1