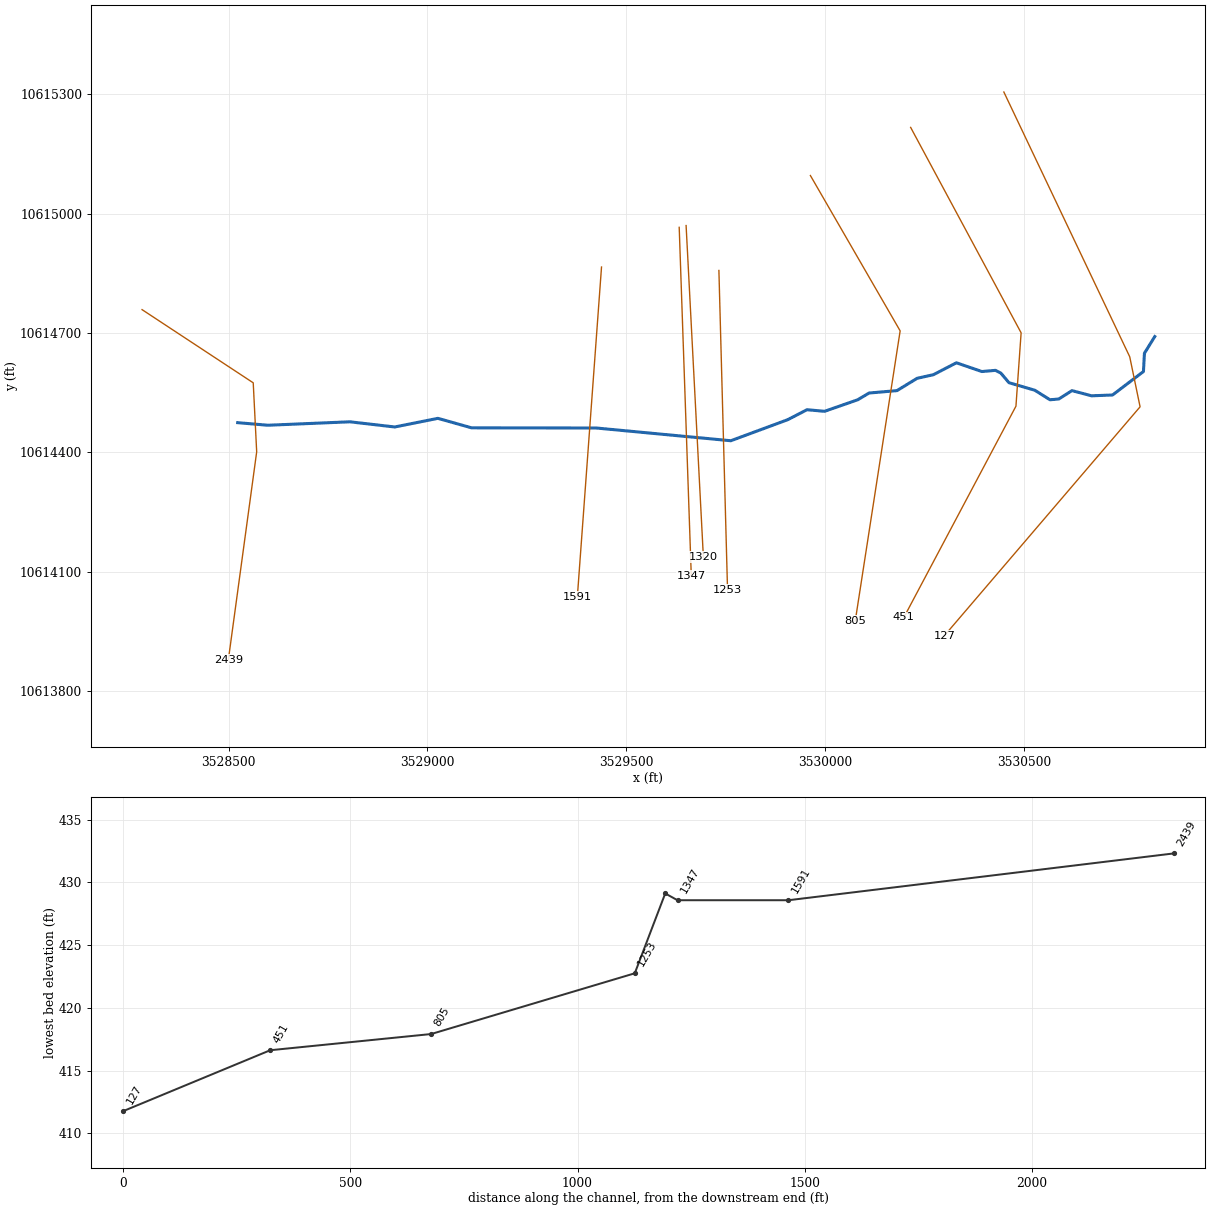
--- UNT088 IN CCTC.prj (project) ---

Proj Title=UNT088 IN CCTC Base Level Engineering
Current Plan=p01
Default Exp/Contr=0.3,0.1
English Units
Geom File=g01
Flow File=f01
Plan File=p01
Y Axis Title=Elevation
X Axis Title(PF)=Main Channel Distance
X Axis Title(XS)=Station
BEGIN DESCRIPTION:
UNT088 IN CCTC
END DESCRIPTION:
DSS Export Rating Curves= 0
DSS Export Rating Curve Sorted= 0
DSS Export Volume Flow Curves= 0
DXF OffsetX= 0
DXF OffsetY= 0
DXF ScaleX= 1
DXF ScaleY= 10

--- UNT088 IN CCTC.p01 (plan) ---

Plan Title=Multiple Run
Short Identifier=Multiple
Geom File=g01
Flow File=f01
Subcritical Flow
K Sum by GR= 0
Std Step Tol= 0.01
Critical Tol= 0.01
Num of Std Step Trials= 20
Max Error Tol= 0.3
Flow Tol Ratio= 0.001
Split Flow NTrial= 30
Split Flow Tol= 0.02
Split Flow Ratio= 0.02
Log Output Level= 0
Friction Slope Method= 1
Unsteady Friction Slope Method= 2
Unsteady Bridges Friction Slope Method= 1
Parabolic Critical Depth
Global Vel Dist=  1 , 1 , 1
Global Log Level= 0
CheckData=True
Encroach Param= -1, 0, 0, 0
BEGIN DESCRIPTION:
Multiple Run
END DESCRIPTION:

--- UNT088 IN CCTC.f01 (steady flow) ---

Flow Title=Multiple
Program Version=4.10
Number of Profiles= 7
Profile Names=10-year,25-year,50-year,1pct_min,100-year,1pct_plu,500-year
River Rch & RM=UNT088 IN CCTC,Reach-1         ,2439
  431.73   431.9  432.03  431.92  432.15   432.4  432.41
River Rch & RM=UNT088 IN CCTC,Reach-1         ,1591
     613     803     952     826    1118    1512    1532
Boundary for River Rch & Prof#=UNT088 IN CCTC,Reach-1         , 1
Up Type= 0
Dn Type= 3
Dn Slope=0.005
Boundary for River Rch & Prof#=UNT088 IN CCTC,Reach-1         , 2
Up Type= 0
Dn Type= 3
Dn Slope=0.005
Boundary for River Rch & Prof#=UNT088 IN CCTC,Reach-1         , 3
Up Type= 0
Dn Type= 3
Dn Slope=0.005
Boundary for River Rch & Prof#=UNT088 IN CCTC,Reach-1         , 4
Up Type= 0
Dn Type= 3
Dn Slope=0.005
Boundary for River Rch & Prof#=UNT088 IN CCTC,Reach-1         , 5
Up Type= 0
Dn Type= 3
Dn Slope=0.005
Boundary for River Rch & Prof#=UNT088 IN CCTC,Reach-1         , 6
Up Type= 0
Dn Type= 3
Dn Slope=0.005
Boundary for River Rch & Prof#=UNT088 IN CCTC,Reach-1         , 7
Up Type= 0
Dn Type= 3
Dn Slope=0.005
DSS Import GetInterval= 0
DSS Import GetPeak= 0
DSS Import FillOption= 0

--- UNT088 IN CCTC.g01 (geometry) ---

Geom Title=Existing Conditions
Program Version=4.10

River Reach=UNT088 IN CCTC  ,Reach-1
Reach XY= 30
      3528523.06     10614474.45      3528599.01     10614467.94
      3528805.18     10614476.62      3528918.02      10614463.6
      3529026.53      10614485.3      3529111.17     10614461.43
      3529424.75       10614461.        3529763.       10614429.
      3529906.25       10614482.       3529954.5       10614507.
      3529998.75       10614503.        3530082.       10614532.
      3530110.75       10614549.      3530180.75       10614555.
       3530231.5       10614586.      3530272.25       10614595.
      3530330.25       10614625.      3530394.25       10614603.
       3530428.5       10614606.        3530442.       10614599.
      3530462.25       10614575.      3530527.25       10614556.
       3530565.5       10614532.      3530587.75       10614534.
      3530620.75       10614555.        3530670.       10614542.
      3530722.75       10614544.       3530800.5       10614603.
        3530803.       10614649.        3530829.       10614691.

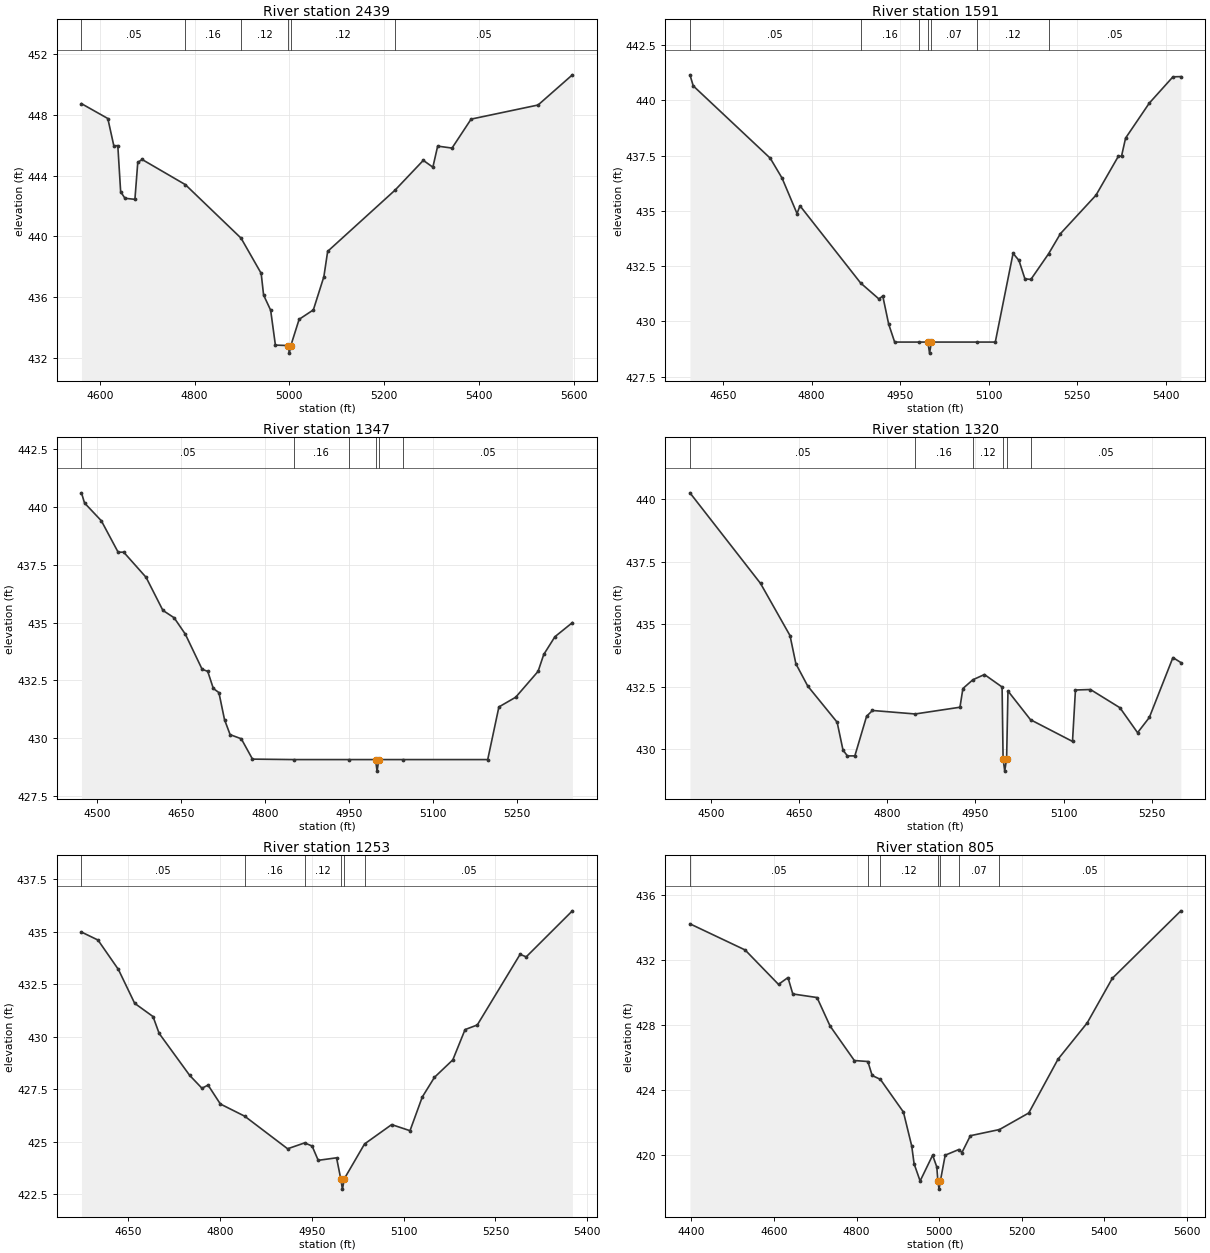
Type RM Length L Ch R = 1 ,2439    ,848,848,848
BEGIN DESCRIPTION:
Mapping XS fa53106e
END DESCRIPTION:
XS GIS Cut Line= 4
      3528282.58     10614758.68      3528562.12     10614574.64
       3528570.8     10614401.03      3528499.63     10613878.47
#Sta/Elev= 30
  4561.2  448.75  4616.8  447.77  4629.5  445.97  4637.9  445.98  4643.9  442.94
    4653  442.51    4674  442.44    4680  444.87  4689.1  445.07  4780.4  443.41
    4898  439.88  4940.4  437.56  4945.5  436.13  4960.4  435.13  4970.4  432.83
    4997   432.8  4999.8   432.3    5003   432.8  5020.5  434.53  5050.5  435.15
  5072.7  437.34  5080.7  439.01    5223  443.05  5282.5  445.01  5302.7  444.56
  5312.8  445.95  5343.1  445.82  5383.4  447.73  5524.7  448.66  5597.1  450.65
#Mann= 6 ,-1 , 0
  4561.2     .05       0  4780.4     .16       0    4898     .12       0
    4997     .07       0    5003     .12       0    5223     .05       0
Bank Sta=4997,5003
XS Rating Curve= 0 ,0
Exp/Cntr=0.3,0.1

Type RM Length L Ch R = 1 ,1591    ,244,244,244
BEGIN DESCRIPTION:
UNT088 IN CCTC 3.0
END DESCRIPTION:
XS GIS Cut Line= 2
      3529437.88     10614865.81      3529377.12     10614036.84
#Sta/Elev= 30
  4594.1  441.15  4599.7  440.65  4730.1  437.38  4750.1  436.48  4775.4  434.88
  4780.4  435.23  4883.1  431.74    4914  431.02  4920.6  431.15  4930.6  429.88
  4940.7  429.07  4981.7  429.07    4997  429.07  4999.8  428.57    5003  429.07
  5080.3  429.07  5111.1  429.07  5141.2  433.08  5151.2  432.76  5161.2  431.93
  5171.3   431.9  5201.3  433.06  5221.4  433.97  5281.6  435.71  5319.7  437.48
  5324.8  437.47  5331.7  438.29  5371.8  439.87  5411.9  441.06  5425.3  441.07
#Mann= 7 ,-1 , 0
  4594.1     .05       0  4883.1     .16       0  4981.7     .07       0
    4997     .07       0    5003     .07       0  5080.3     .12       0
  5201.3     .05       0
Bank Sta=4997,5003
XS Rating Curve= 0 ,0
Exp/Cntr=0.3,0.1

Type RM Length L Ch R = 1 ,1347    ,27,27,27
BEGIN DESCRIPTION:
UNT088 IN CCTC 2.0
END DESCRIPTION:
XS GIS Cut Line= 2
       3529633.2     10614965.65      3529663.58     10614088.97
#Sta/Elev= 30
  4471.6  440.62  4477.1  440.18  4507.1  439.41  4537.1  438.05  4547.1  438.05
  4587.1  436.96  4617.1  435.53  4637.2  435.21  4657.2   434.5  4687.2  432.98
  4697.2  432.89  4707.2  432.15  4717.2  431.97  4727.2   430.8  4737.2  430.15
  4757.2  429.97  4777.2  429.09  4850.8  429.07  4948.8  429.07    4997  429.07
  4999.8  428.57    5003  429.07  5046.8  429.07  5197.5  429.07  5217.5  431.35
  5247.5  431.77  5287.5  432.89  5297.6  433.62  5317.6  434.39  5348.8     435
#Mann= 6 ,-1 , 0
  4471.6     .05       0  4850.8     .16       0  4948.8     .12       0
    4997     .07       0    5003     .12       0  5046.8     .05       0
Bank Sta=4997,5003
XS Rating Curve= 0 ,0
Exp/Cntr=0.3,0.1

Type RM Length L Ch R = 1 ,1320    ,67,67,67
BEGIN DESCRIPTION:
Mapping XS 3e9328b7
END DESCRIPTION:
XS GIS Cut Line= 2
      3529650.55     10614970.07      3529693.96      10614136.7
#Sta/Elev= 30
  4464.7  440.26  4584.7  436.63  4634.8  434.54  4644.8  433.41  4664.9  432.52
  4714.9  431.07  4724.9  429.95  4732.4  429.72    4745  429.72    4765  431.31
    4775  431.54  4847.6   431.4  4923.7  431.67  4928.7  432.42  4945.6  432.77
  4965.3  432.98  4995.3  432.48    4997  429.61  4999.8  429.11    5003  429.61
  5005.3  432.32  5043.6  431.17    5115   430.3    5120  432.36  5145.5  432.38
  5195.6  431.65  5225.6  430.65  5245.6  431.26  5285.7  433.66  5299.2  433.46
#Mann= 6 ,-1 , 0
  4464.7     .05       0  4847.6     .16       0  4945.6     .12       0
    4997     .07       0    5003     .12       0  5043.6     .05       0
Bank Sta=4997,5003
XS Rating Curve= 0 ,0
Exp/Cntr=0.3,0.1

Type RM Length L Ch R = 1 ,1253    ,448,448,448
BEGIN DESCRIPTION:
Mapping XS 86b5cc52
END DESCRIPTION:
XS GIS Cut Line= 2
      3529733.02     10614857.16      3529754.71     10614054.75
#Sta/Elev= 30
  4573.1  434.98  4600.1   434.6  4633.5   433.2  4660.1  431.59  4690.1  430.96
  4700.1  430.16  4750.1  428.16  4770.1  427.55  4780.1   427.7  4800.2   426.8
    4840  426.22  4910.2  424.67    4938  424.95  4950.2   424.8  4960.2  424.12
  4990.2  424.24    4997  423.25  4999.8  422.75    5003  423.25    5036   424.9
  5080.3  425.82  5110.3  425.53  5130.3  427.13  5150.3  428.07  5180.3   428.9
  5200.3  430.34  5220.3  430.56  5290.3  433.92  5300.3   433.8  5375.8  435.99
#Mann= 6 ,-1 , 0
  4573.1     .05       0    4840     .16       0    4938     .12       0
    4997     .07       0    5003     .12       0    5036     .05       0
Bank Sta=4997,5003
XS Rating Curve= 0 ,0
Exp/Cntr=0.3,0.1

Type RM Length L Ch R = 1 ,805     ,354,354,354
BEGIN DESCRIPTION:
Mapping XS b9329e89
END DESCRIPTION:
XS GIS Cut Line= 3
      3529963.06     10615095.89      3530188.75     10614705.27
       3530075.9     10613976.08
#Sta/Elev= 30
  4396.5  434.25  4530.1  432.64    4611  430.52  4633.9  430.94  4645.6  429.93
  4704.3  429.71  4735.8  427.96  4794.7  425.83  4827.4  425.77  4837.8  424.91
  4857.7  424.67  4913.5  422.66  4933.7  420.56  4939.4  419.47    4954  418.41
  4984.3     420  4994.4  419.27    4997  418.41  4999.8  417.91    5003  418.41
  5014.7     420  5047.8  420.35  5055.2  420.16  5075.7   421.2  5146.2  421.58
  5217.1   422.6  5287.9  425.91  5358.7  428.15  5419.4  430.89  5585.5  435.05
#Mann= 7 ,-1 , 0
  4396.5     .05       0  4827.4     .16       0  4857.7     .12       0
    4997     .07       0    5003     .12       0  5047.8     .07       0
  5146.2     .05       0
Bank Sta=4997,5003
XS Rating Curve= 0 ,0
Exp/Cntr=0.3,0.1

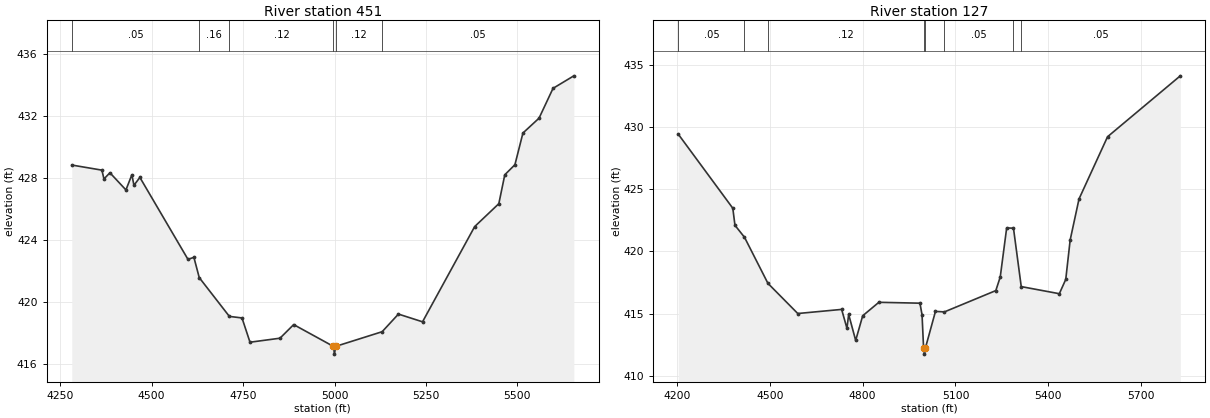
Type RM Length L Ch R = 1 ,451     ,324,324,324
BEGIN DESCRIPTION:
Mapping XS c3535ba2
END DESCRIPTION:
XS GIS Cut Line= 4
      3530215.14     10615216.86      3530492.93     10614700.33
      3530479.91     10614515.87      3530198.08     10613984.72
#Sta/Elev= 30
  4281.6  428.85    4364  428.52  4369.6  427.95  4385.9  428.35  4429.7  427.24
  4445.9  428.22  4451.6  427.54  4467.8  428.05  4599.3  422.75  4615.5  422.88
  4630.1  421.57  4712.5  419.06    4747  418.96  4768.9  417.39  4850.9  417.65
  4888.3  418.53    4997  417.12  4999.8  416.62    5003  417.12  5130.2  418.07
  5174.7  419.21  5240.6  418.71  5383.2  424.87  5449.2  426.35  5465.5  428.22
  5493.2  428.87  5515.1  430.92  5559.1  431.88  5597.4  433.81  5654.3  434.62
#Mann= 6 ,-1 , 0
  4281.6     .05       0  4630.1     .16       0  4712.5     .12       0
    4997     .07       0    5003     .12       0  5130.2     .05       0
Bank Sta=4997,5003
XS Rating Curve= 0 ,0
Exp/Cntr=0.3,0.1

Type RM Length L Ch R = 1 ,127     ,0,0,0
BEGIN DESCRIPTION:
UNT088 IN CCTC 1.0
END DESCRIPTION:
XS GIS Cut Line= 4
      3530449.52     10615305.82      3530766.01     10614640.16
      3530792.05     10614514.29      3530299.82     10613938.65
#Sta/Elev= 30
  4203.9  429.42  4380.3  423.47  4387.3   422.1  4418.1  421.14  4493.9  417.44
  4590.3  415.02  4732.1  415.35  4749.3  413.83  4754.8  414.95  4777.5  412.86
  4800.2  414.84  4852.4  415.92  4985.2  415.85    4992  414.93    4997  412.26
  4999.8  411.76    5003  412.26  5035.4  415.19  5064.4  415.15  5230.5  416.86
  5244.8  417.95  5265.6  421.89  5287.6  421.87  5312.7  417.18  5435.8  416.61
  5456.6  417.76  5470.9  420.93  5499.5  424.22  5591.7  429.21  5826.9   434.1
#Mann= 8 ,-1 , 0
  4203.9     .05       0  4418.1     .16       0  4493.9     .12       0
    4997     .07       0    5003     .12       0  5064.4     .05       0
  5287.6      .1       0  5312.7     .05       0
Bank Sta=4997,5003
XS Rating Curve= 0 ,0
Exp/Cntr=0.3,0.1

Chan Stop Cuts=-1
Use User Specified Reach Order=0
Composite Channel Slope=5