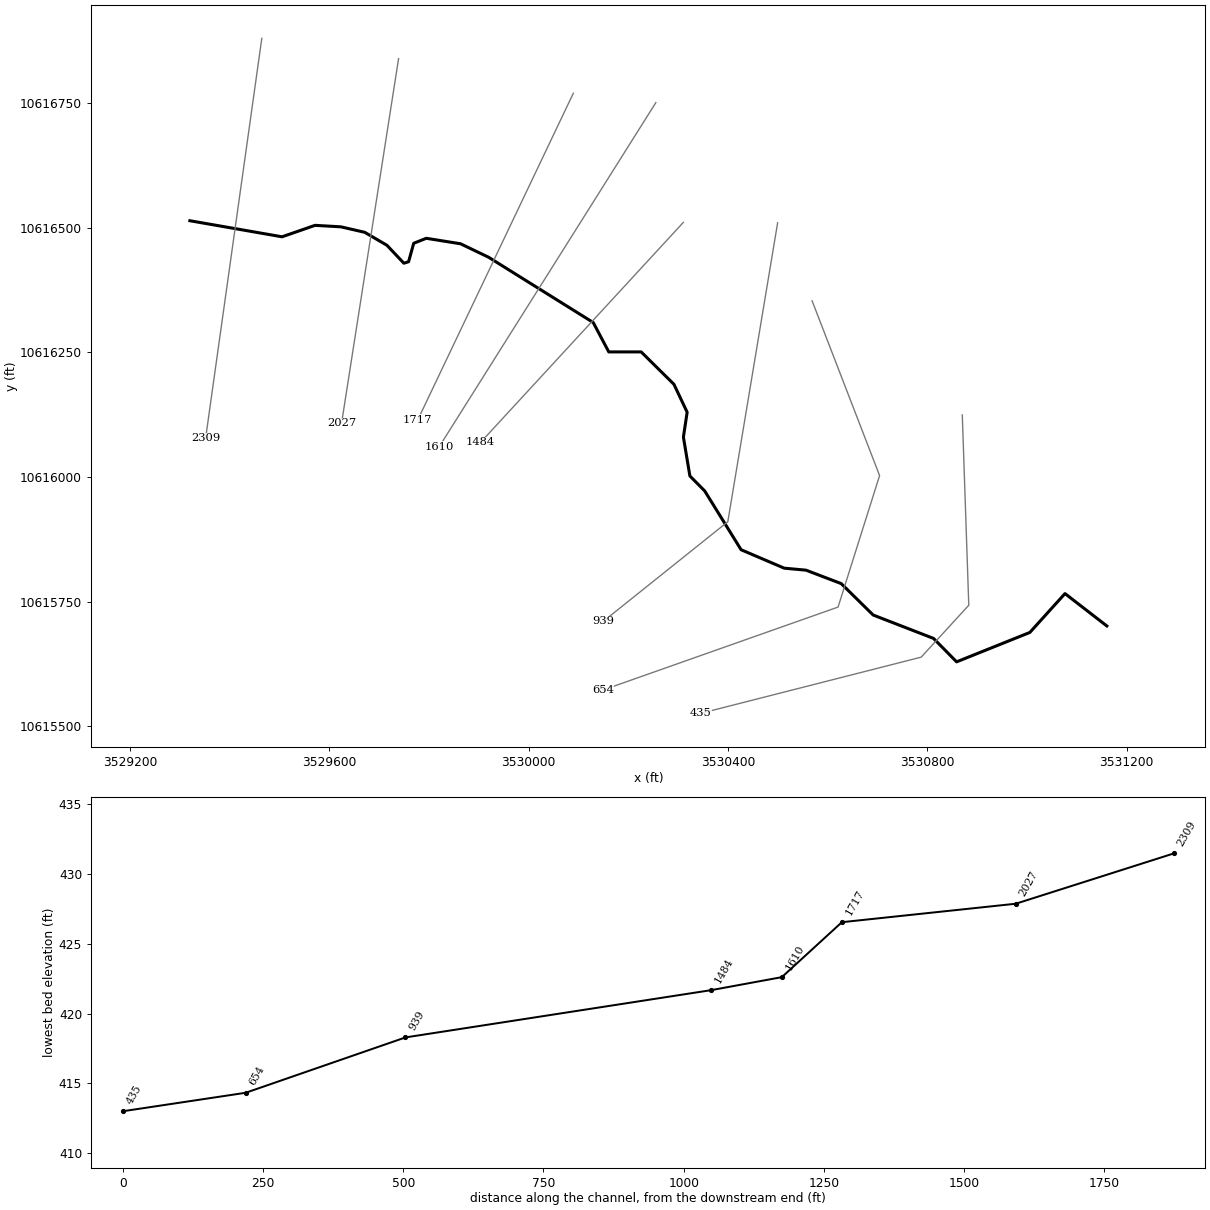
--- UNT089 IN CCTC.prj (project) ---

Proj Title=UNT089 IN CCTC Base Level Engineering
Current Plan=p01
Default Exp/Contr=0.3,0.1
English Units
Geom File=g01
Flow File=f01
Plan File=p01
BEGIN DESCRIPTION:
UNT089 IN CCTC
END DESCRIPTION:

--- UNT089 IN CCTC.p01 (plan) ---

Plan Title=Multiple Run
Short Identifier=Multiple
Geom File=g01
Flow File=f01
Subcritical Flow
K Sum by GR= 0
Std Step Tol= 0.01
Critical Tol= 0.01
Num of Std Step Trials= 20
Max Error Tol= 0.3
Flow Tol Ratio= 0.001
Split Flow NTrial= 30
Split Flow Tol= 0.02
Split Flow Ratio= 0.02
Log Output Level= 0
Friction Slope Method= 1
Unsteady Friction Slope Method= 2
Unsteady Bridges Friction Slope Method= 1
Parabolic Critical Depth
Global Vel Dist=  1 , 1 , 1
Global Log Level= 0
CheckData=True
Encroach Param= -1, 0, 0, 0
BEGIN DESCRIPTION:
Multiple Run
END DESCRIPTION:

--- UNT089 IN CCTC.f01 (steady flow) ---

Flow Title=Multiple
Number of Profiles=7
Profile Names=10-year,25-year,50-year,1pct_min,100-year,1pct_plu,500-year
River Rch & RM= UNT089 IN CCTC,Reach-1,2309
     383     487     568     485     656     888     872
Boundary for River Rch & Prof#=UNT089 IN CCTC,Reach-1,1
Up Type=0
Dn Type=3
Dn Slope=0.005
Boundary for River Rch & Prof#=UNT089 IN CCTC,Reach-1,2
Up Type=0
Dn Type=3
Dn Slope=0.005
Boundary for River Rch & Prof#=UNT089 IN CCTC,Reach-1,3
Up Type=0
Dn Type=3
Dn Slope=0.005
Boundary for River Rch & Prof#=UNT089 IN CCTC,Reach-1,4
Up Type=0
Dn Type=3
Dn Slope=0.005
Boundary for River Rch & Prof#=UNT089 IN CCTC,Reach-1,5
Up Type=0
Dn Type=3
Dn Slope=0.005
Boundary for River Rch & Prof#=UNT089 IN CCTC,Reach-1,6
Up Type=0
Dn Type=3
Dn Slope=0.005
Boundary for River Rch & Prof#=UNT089 IN CCTC,Reach-1,7
Up Type=0
Dn Type=3
Dn Slope=0.005

--- UNT089 IN CCTC.g01 (geometry) ---

Geom Title=Existing Conditions

River Reach=UNT089 IN CCTC,Reach-1
Reach XY= 30
      3529320.06     10616514.26      3529505.00     10616482.00
      3529571.25     10616505.00      3529623.25     10616502.00
      3529671.00     10616491.00      3529715.50     10616465.00
      3529749.50     10616429.00      3529759.00     10616432.00
      3529769.25     10616469.00      3529794.50     10616479.00
      3529863.25     10616468.00      3529919.50     10616441.00
      3530129.50     10616310.00      3530160.75     10616251.00
      3530225.75     10616251.00      3530291.50     10616186.00
      3530318.00     10616130.00      3530310.50     10616080.00
      3530323.50     10616002.00      3530353.25     10615972.00
      3530426.25     10615854.00      3530512.75     10615817.00
      3530556.50     10615813.00      3530627.25     10615786.00
      3530691.25     10615723.00      3530812.50     10615676.00
      3530858.75     10615629.00      3531005.75     10615688.00
      3531076.25     10615766.00      3531160.25     10615701.00

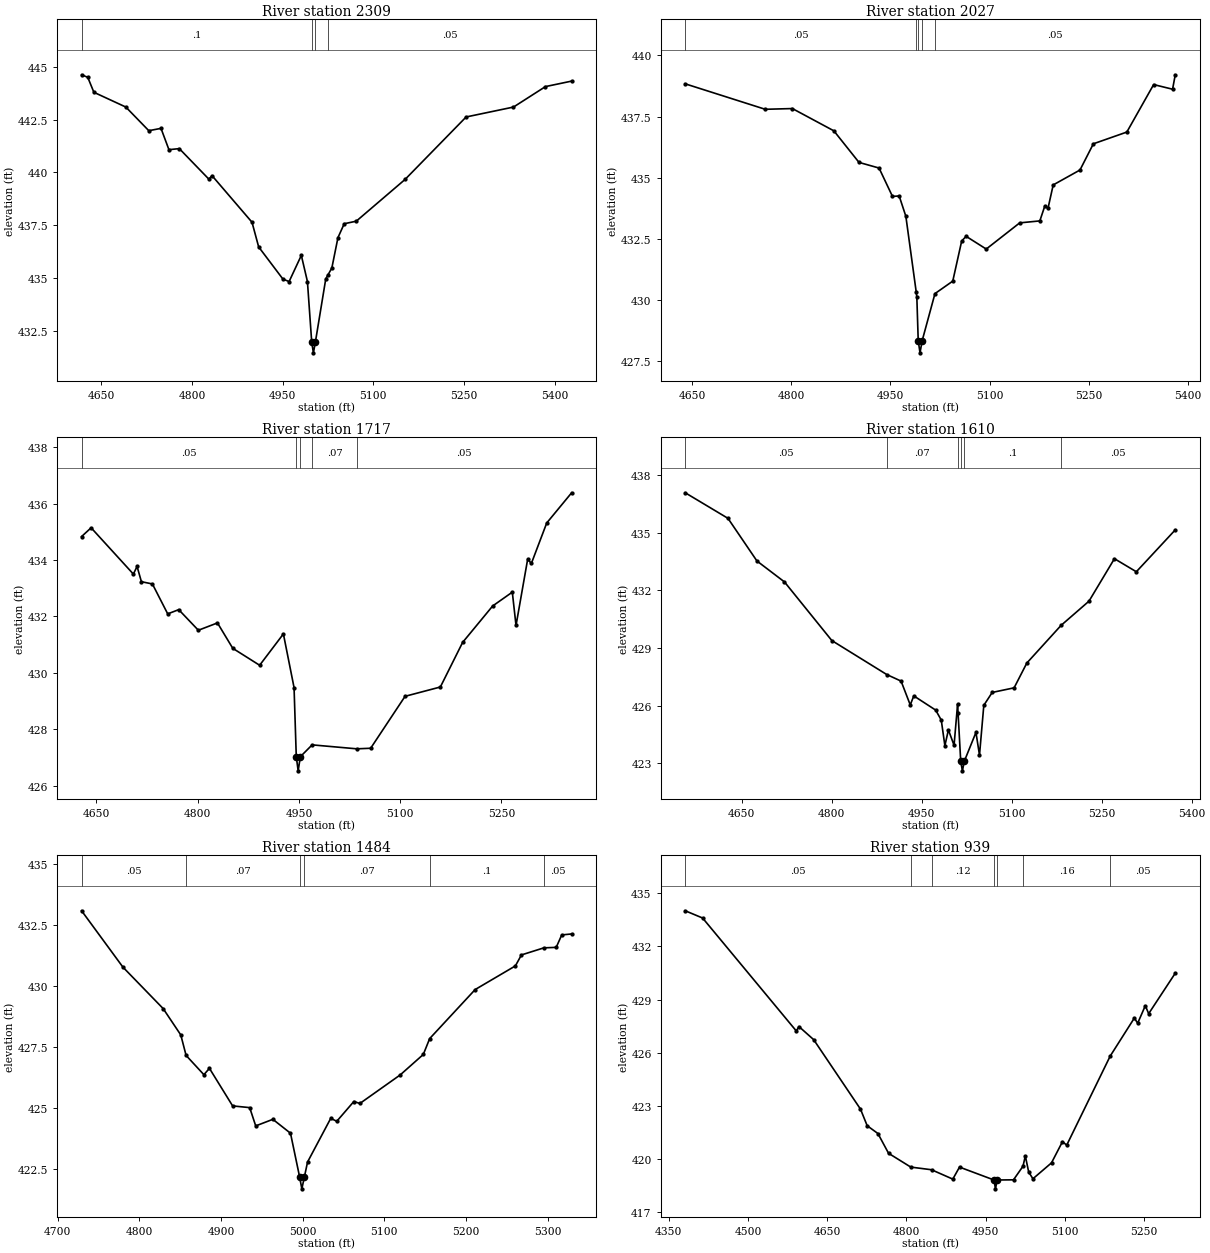
Type RM Length L Ch R = 1,2309,282,282,282
BEGIN DESCRIPTION:
UNT089 IN CCTC 4.0
END DESCRIPTION:
XS GIS Cut Line= 2
      3529464.43     10616880.29      3529351.58     10616077.28
#Sta/Elev= 30
  4617.3  444.63  4627.5  444.51  4637.6  443.80  4690.5  443.10  4728.5  441.98
  4748.7  442.09  4761.8  441.08  4779.0  441.13  4828.0  439.68  4833.1  439.85
  4899.3  437.64  4910.3  436.47  4950.6  434.94  4960.7  434.83  4980.9  436.07
  4991.0  434.83  4998.1  431.95  5000.9  431.45  5004.1  431.95  5021.3  434.95
  5025.3  435.16  5031.4  435.47  5041.5  436.91  5051.9  437.57  5071.8  437.69
  5152.6  439.67  5253.6  442.63  5332.0  443.10  5384.9  444.07  5428.2  444.33
#Mann=4,-1,0
  4617.3     0.1       0  4998.1    0.07       0  5004.1     0.1       0
  5025.3    0.05       0
Bank Sta=4998.1,5004.1
Exp/Cntr=0.3,0.1

Type RM Length L Ch R = 1,2027,310,310,310
BEGIN DESCRIPTION:
Mapping XS 5dd12e79
END DESCRIPTION:
XS GIS Cut Line= 2
      3529738.92     10616839.60      3529624.48     10616107.90
#Sta/Elev= 30
  4639.9  438.84  4760.8  437.80  4801.8  437.83  4864.5  436.92  4902.5  435.63
  4932.8  435.40  4953.1  434.24  4963.2  434.26  4973.3  433.43  4988.9  430.35
  4989.9  430.13  4992.0  428.35  4994.7  427.85  4998.0  428.35  5017.3  430.27
  5044.2  430.78  5057.7  432.42  5064.4  432.61  5094.8  432.09  5145.4  433.16
  5175.8  433.24  5183.2  433.84  5188.2  433.76  5196.0  434.71  5236.5  435.32
  5256.7  436.39  5307.3  436.87  5347.8  438.81  5376.4  438.62  5380.5  439.21
#Mann=5,-1,0
  4639.9    0.05       0  4988.9     0.1       0  4992.0    0.07       0
  4998.0     0.1       0  5017.3    0.05       0
Bank Sta=4992,4998
Exp/Cntr=0.3,0.1

Type RM Length L Ch R = 1,1717,107,107,107
BEGIN DESCRIPTION:
Mapping XS 2cf48c24
END DESCRIPTION:
XS GIS Cut Line= 2
      3530089.60     10616770.14      3529777.42     10616114.57
#Sta/Elev= 30
  4628.0  434.83  4642.1  435.14  4704.7  433.50  4710.2  433.77  4716.6  433.23
  4732.9  433.15  4755.6  432.09  4771.9  432.24  4801.0  431.51  4829.3  431.77
  4852.0  430.87  4891.8  430.27  4927.0  431.38  4942.8  429.48  4946.1  427.03
  4948.9  426.53  4952.1  427.03  4969.6  427.45  5035.7  427.31  5056.3  427.33
  5107.3  429.17  5159.6  429.50  5192.6  431.08  5237.1  432.37  5266.2  432.86
  5271.7  431.68  5288.9  434.02  5294.5  433.88  5317.2  435.31  5354.1  436.38
#Mann=5,-1,0
  4628.0    0.05       0  4946.1    0.07       0  4952.1    0.05       0
  4969.6    0.07       0  5035.7    0.05       0
Bank Sta=4946.1,4952.1
Exp/Cntr=0.3,0.1

Type RM Length L Ch R = 1,1610,126,126,126
BEGIN DESCRIPTION:
Mapping XS 6343fcfc
END DESCRIPTION:
XS GIS Cut Line= 2
      3530255.18     10616751.28      3529820.09     10616060.13
#Sta/Elev= 30
  4555.9  437.07  4627.1  435.74  4675.4  433.52  4721.3  432.43  4800.2  429.38
  4891.8  427.61  4915.6  427.27  4930.9  426.03  4936.8  426.50  4973.3  425.76
  4982.6  425.24  4988.6  423.91  4994.5  424.73  5003.9  423.93  5009.8  426.07
  5010.6  425.61  5015.0  423.10  5017.8  422.60  5021.0  423.10  5040.4  424.60
  5046.3  423.42  5053.5  426.01  5067.5  426.68  5104.0  426.92  5125.2  428.21
  5182.3  430.17  5228.8  431.43  5271.2  433.64  5307.7  432.96  5372.6  435.14
#Mann=6,-1,0
  4555.9    0.05       0  4891.8    0.07       0  5010.6     0.1       0
  5015.0    0.07       0  5021.0     0.1       0  5182.3    0.05       0
Bank Sta=5015,5021
Exp/Cntr=0.3,0.1

Type RM Length L Ch R = 1,1484,545,545,545
BEGIN DESCRIPTION:
UNT089 IN CCTC 3.0
END DESCRIPTION:
XS GIS Cut Line= 2
      3530310.30     10616510.84      3529903.48     10616069.41
#Sta/Elev= 30
  4729.1  433.07  4779.7  430.76  4829.0  429.06  4850.6  427.98  4857.1  427.14
  4878.9  426.35  4885.7  426.61  4914.1  425.07  4935.0  425.00  4942.4  424.25
  4963.4  424.52  4985.0  423.95  4996.1  422.17  4998.9  421.67  5002.1  422.17
  5005.9  422.77  5034.3  424.56  5041.7  424.44  5062.6  425.25  5070.0  425.17
  5119.4  426.34  5147.7  427.18  5155.5  427.83  5211.2  429.84  5260.5  430.81
  5267.9  431.26  5295.4  431.55  5310.5  431.57  5317.3  432.08  5329.4  432.12
#Mann=6,-1,0
  4729.1    0.05       0  4857.1    0.07       0  4996.1    0.07       0
  5002.1    0.07       0  5155.5     0.1       0  5295.4    0.05       0
Bank Sta=4996.1,5002.1
Exp/Cntr=0.3,0.1

Type RM Length L Ch R = 1,939,285,285,285
BEGIN DESCRIPTION:
UNT089 IN CCTC 2.0
END DESCRIPTION:
XS GIS Cut Line= 3
      3530499.61     10616510.18      3530399.61     10615910.19
      3530149.63     10615710.20
#Sta/Elev= 30
  4381.1  434.02  4414.0  433.61  4591.5  427.22  4596.5  427.47  4624.4  426.73
  4713.1  422.80  4725.8  421.86  4746.1  421.42  4766.3  420.30  4808.4  419.52
  4847.7  419.37  4888.0  418.84  4900.7  419.52  4966.1  418.79  4968.8  418.29
  4972.1  418.79  5003.0  418.80  5021.0  419.57  5025.4  420.15  5031.8  419.24
  5039.8  418.86  5075.0  419.76  5095.8  420.96  5103.8  420.76  5186.2  425.80
  5231.9  427.95  5238.3  427.66  5252.7  428.65  5259.1  428.20  5309.5  430.49
#Mann=7,-1,0
  4381.1    0.05       0  4808.4    0.16       0  4847.7    0.12       0
  4966.1    0.07       0  4972.1    0.12       0  5021.0    0.16       0
  5186.2    0.05       0
Bank Sta=4966.1,4972.1
Exp/Cntr=0.3,0.1

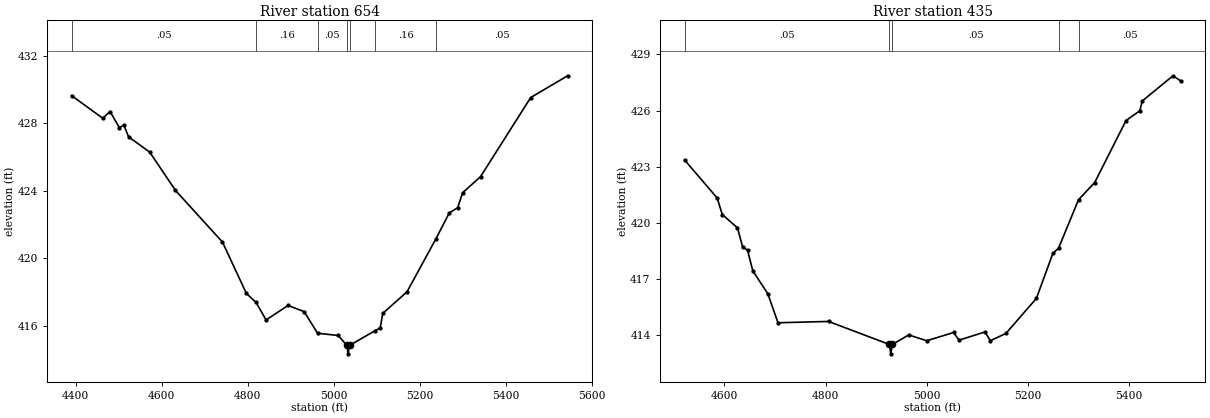
Type RM Length L Ch R = 1,654,219,219,219
BEGIN DESCRIPTION:
Mapping XS 48936318
END DESCRIPTION:
XS GIS Cut Line= 4
      3530568.77     10616353.54      3530704.20     10616002.82
      3530620.87     10615738.93      3530148.61     10615572.25
#Sta/Elev= 30
  4390.5  429.64  4463.0  428.30  4479.8  428.70  4501.3  427.75  4512.0  427.89
  4522.9  427.20  4572.1  426.29  4632.0  424.02  4741.2  420.96  4796.9  417.91
  4819.4  417.38  4842.6  416.34  4893.9  417.20  4931.4  416.83  4962.4  415.55
  5010.4  415.42  5030.7  414.83  5033.4  414.33  5036.7  414.83  5096.7  415.71
  5108.2  415.87  5114.0  416.73  5170.5  418.01  5237.4  421.14  5268.6  422.68
  5288.4  423.00  5299.6  423.88  5341.5  424.84  5458.1  429.53  5544.0  430.82
#Mann=7,-1,0
  4390.5    0.05       0  4819.4    0.16       0  4962.4    0.05       0
  5030.7    0.03       0  5036.7    0.05       0  5096.7    0.16       0
  5237.4    0.05       0
Bank Sta=5030.7,5036.7
Exp/Cntr=0.3,0.1

Type RM Length L Ch R = 1,435,0,0,0
BEGIN DESCRIPTION:
UNT089 IN CCTC 1.0
END DESCRIPTION:
XS GIS Cut Line= 4
      3530870.17     10616124.54      3530883.20     10615742.59
      3530787.71     10615638.43      3530345.04     10615525.59
#Sta/Elev= 30
  4521.4  423.36  4585.8  421.33  4595.8  420.45  4625.8  419.74  4635.8  418.74
  4645.8  418.54  4656.2  417.44  4685.8  416.22  4705.9  414.67  4805.9  414.74
  4926.1  413.51  4928.9  413.01  4932.1  413.51  4964.3  414.02  5000.0  413.71
  5053.0  414.15  5063.6  413.74  5115.2  414.18  5125.5  413.71  5156.4  414.10
  5216.6  415.97  5249.3  418.38  5260.4  418.65  5299.9  421.24  5331.9  422.16
  5393.8  425.47  5421.0  425.99  5426.1  426.52  5486.7  427.86  5501.7  427.59
#Mann=5,-1,0
  4521.4    0.05       0  4926.1    0.03       0  4932.1    0.05       0
  5260.4    0.16       0  5299.9    0.05       0
Bank Sta=4926.1,4932.1
Exp/Cntr=0.3,0.1

Chan Stop Cuts=-1