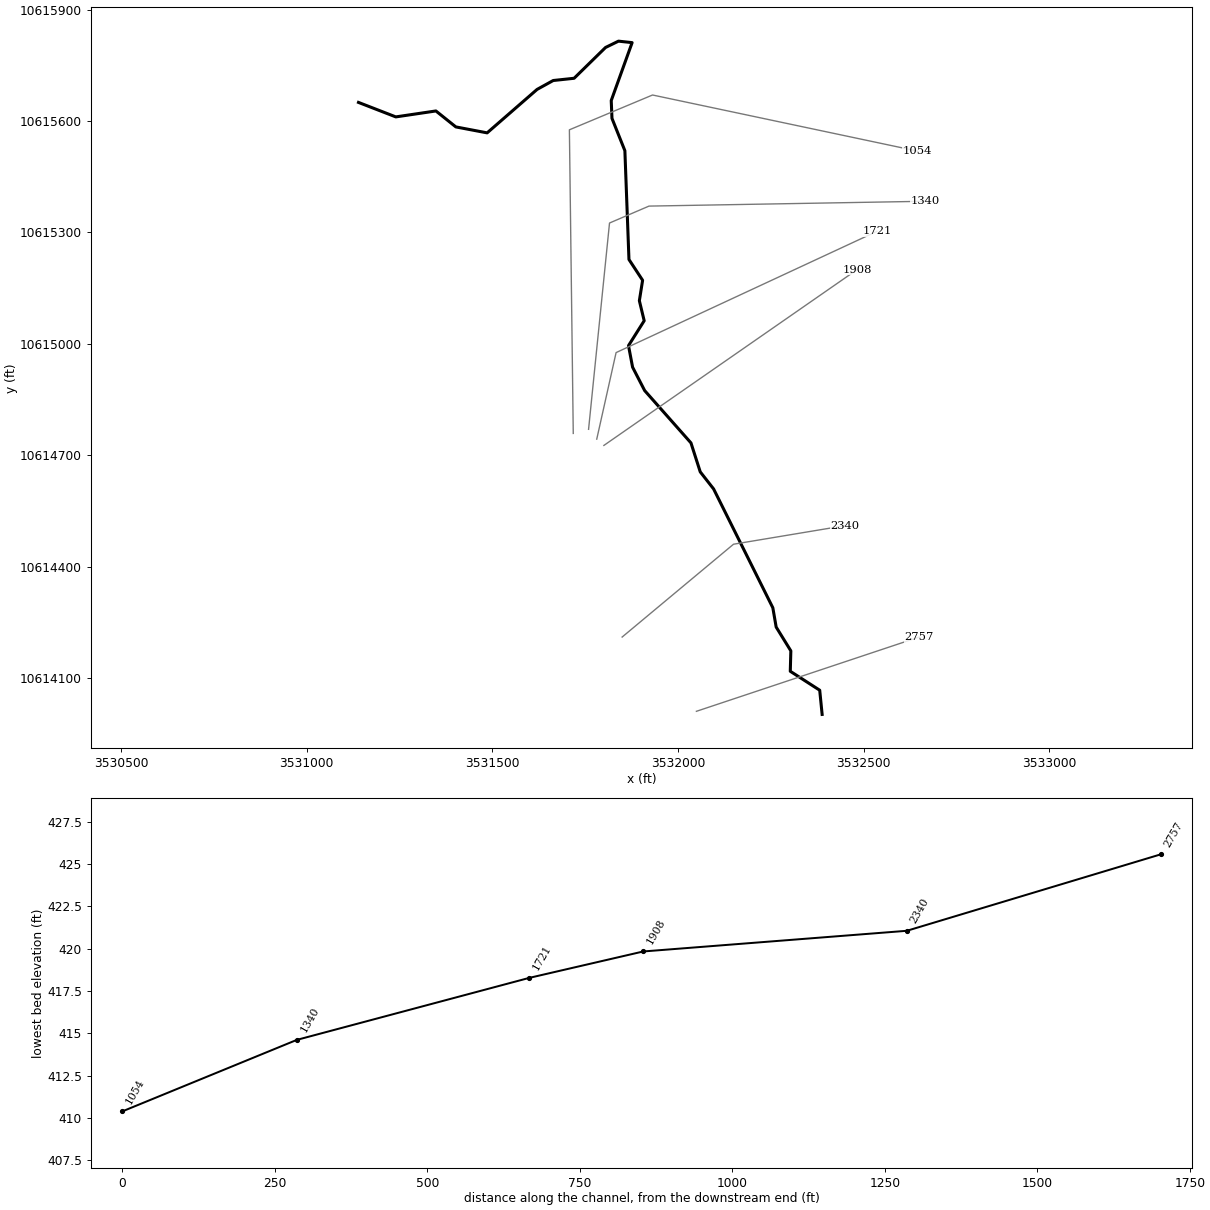
--- UNT090 IN CCTC.prj (project) ---

Proj Title=UNT090 IN CCTC Base Level Engineering
Current Plan=p01
Default Exp/Contr=0.3,0.1
English Units
Geom File=g01
Flow File=f01
Plan File=p01
BEGIN DESCRIPTION:
UNT090 IN CCTC
END DESCRIPTION:

--- UNT090 IN CCTC.p01 (plan) ---

Plan Title=Multiple Run
Short Identifier=Multiple
Geom File=g01
Flow File=f01
Subcritical Flow
K Sum by GR= 0
Std Step Tol= 0.01
Critical Tol= 0.01
Num of Std Step Trials= 20
Max Error Tol= 0.3
Flow Tol Ratio= 0.001
Split Flow NTrial= 30
Split Flow Tol= 0.02
Split Flow Ratio= 0.02
Log Output Level= 0
Friction Slope Method= 1
Unsteady Friction Slope Method= 2
Unsteady Bridges Friction Slope Method= 1
Parabolic Critical Depth
Global Vel Dist=  1 , 1 , 1
Global Log Level= 0
CheckData=True
Encroach Param= -1, 0, 0, 0
BEGIN DESCRIPTION:
Multiple Run
END DESCRIPTION:

--- UNT090 IN CCTC.f01 (steady flow) ---

Flow Title=Multiple
Number of Profiles=7
Profile Names=10-year,25-year,50-year,1pct_min,100-year,1pct_plu,500-year
River Rch & RM= UNT090 IN CCTC,Reach-1,2757
     732     967    1153    1005    1360    1839    1882
Boundary for River Rch & Prof#=UNT090 IN CCTC,Reach-1,1
Up Type=0
Dn Type=3
Dn Slope=0.005
Boundary for River Rch & Prof#=UNT090 IN CCTC,Reach-1,2
Up Type=0
Dn Type=3
Dn Slope=0.005
Boundary for River Rch & Prof#=UNT090 IN CCTC,Reach-1,3
Up Type=0
Dn Type=3
Dn Slope=0.005
Boundary for River Rch & Prof#=UNT090 IN CCTC,Reach-1,4
Up Type=0
Dn Type=3
Dn Slope=0.005
Boundary for River Rch & Prof#=UNT090 IN CCTC,Reach-1,5
Up Type=0
Dn Type=3
Dn Slope=0.005
Boundary for River Rch & Prof#=UNT090 IN CCTC,Reach-1,6
Up Type=0
Dn Type=3
Dn Slope=0.005
Boundary for River Rch & Prof#=UNT090 IN CCTC,Reach-1,7
Up Type=0
Dn Type=3
Dn Slope=0.005

--- UNT090 IN CCTC.g01 (geometry) ---

Geom Title=Existing Conditions

River Reach=UNT090 IN CCTC,Reach-1
Reach XY= 30
      3532388.29     10614001.80      3532381.75     10614067.00
      3532302.50     10614118.00      3532304.00     10614173.00
      3532264.50     10614237.00      3532255.50     10614289.00
      3532096.00     10614609.00      3532060.00     10614655.00
      3532035.00     10614733.00      3531910.25     10614874.00
      3531877.75     10614937.00      3531866.75     10614995.00
      3531909.00     10615062.00      3531896.00     10615116.00
      3531904.75     10615171.00      3531868.00     10615227.00
      3531857.00     10615520.00      3531822.25     10615607.00
      3531820.25     10615655.00      3531876.50     10615811.00
      3531839.75     10615815.00      3531805.00     10615798.00
      3531720.25     10615715.00      3531664.00     10615709.00
      3531620.50     10615685.00      3531486.00     10615568.00
      3531401.75     10615584.00      3531348.00     10615627.00
      3531240.00     10615611.00      3531139.50     10615650.00

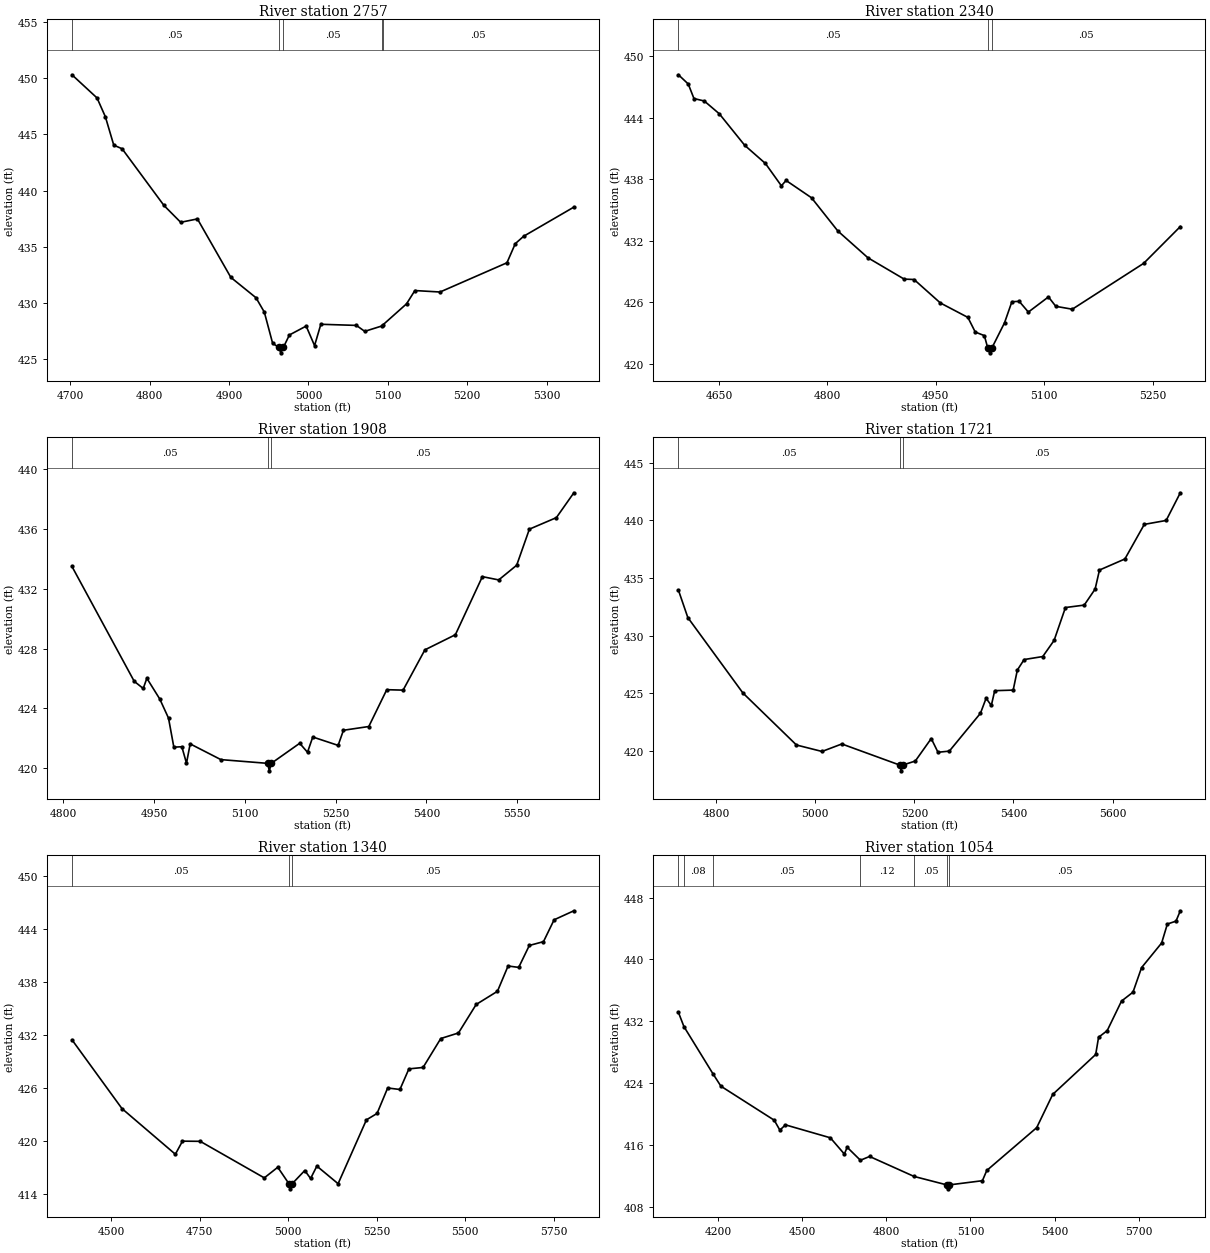
Type RM Length L Ch R = 1,2757,417,417,417
BEGIN DESCRIPTION:
UNT090 IN CCTC 3.0
END DESCRIPTION:
XS GIS Cut Line= 3
      3532049.64     10614010.20      3532349.61     10614110.19
      3532649.59     10614210.18
#Sta/Elev= 30
  4702.0  450.30  4733.6  448.24  4744.1  446.57  4754.7  444.04  4765.2  443.72
  4817.9  438.68  4839.0  437.18  4860.1  437.48  4902.2  432.28  4933.9  430.47
  4944.4  429.19  4954.9  426.41  4962.5  426.07  4965.2  425.57  4968.5  426.07
  4976.0  427.16  4997.1  427.95  5007.7  426.21  5015.6  428.11  5060.4  428.01
  5070.9  427.48  5092.5  427.96  5093.7  428.05  5123.6  429.93  5134.1  431.11
  5165.8  430.98  5250.1  433.58  5260.6  435.28  5271.2  435.94  5334.4  438.53
#Mann=5,-1,0
  4702.0    0.05       0  4962.5    0.03       0  4968.5    0.05       0
  5092.5    0.12       0  5093.7    0.05       0
Bank Sta=4962.5,4968.5
Exp/Cntr=0.3,0.1

Type RM Length L Ch R = 1,2340,432,432,432
BEGIN DESCRIPTION:
UNT090 IN CCTC 2.0
END DESCRIPTION:
XS GIS Cut Line= 3
      3531849.62     10614210.20      3532149.61     10614460.19
      3532449.58     10614510.18
#Sta/Elev= 30
  4593.9  448.20  4607.5  447.30  4615.4  445.88  4629.7  445.64  4650.5  444.39
  4685.7  441.31  4714.3  439.54  4736.4  437.36  4742.9  437.88  4778.1  436.19
  4814.5  432.95  4856.2  430.33  4906.3  428.25  4920.0  428.21  4956.4  425.92
  4994.5  424.51  5004.7  423.08  5017.3  422.73  5021.9  421.55  5024.7  421.05
  5027.9  421.55  5045.2  423.98  5055.4  426.04  5065.5  426.08  5078.2  425.03
  5106.0  426.51  5116.2  425.59  5139.0  425.31  5237.8  429.79  5288.5  433.38
#Mann=3,-1,0
  4593.9    0.05       0  5021.9    0.03       0  5027.9    0.05       0
Bank Sta=5021.9,5027.9
Exp/Cntr=0.3,0.1

Type RM Length L Ch R = 1,1908,187,187,187
BEGIN DESCRIPTION:
Mapping XS ece1a72f
END DESCRIPTION:
XS GIS Cut Line= 2
      3531800.44     10614726.25      3532481.82     10615199.32
#Sta/Elev= 30
  4814.1  433.48  4917.0  425.81  4931.9  425.33  4937.9  426.01  4959.2  424.63
  4973.7  423.35  4982.5  421.41  4995.7  421.44  5003.4  420.34  5009.5  421.63
  5060.2  420.58  5137.5  420.33  5140.3  419.83  5143.5  420.33  5190.5  421.67
  5203.4  421.07  5212.1  422.09  5254.0  421.53  5262.8  422.54  5304.7  422.79
  5334.4  425.25  5361.4  425.22  5397.4  427.91  5447.8  428.92  5492.4  432.80
  5519.4  432.58  5549.1  433.56  5570.1  435.97  5614.7  436.74  5643.6  438.40
#Mann=3,-1,0
  4814.1    0.05       0  5137.5    0.03       0  5143.5    0.05       0
Bank Sta=5137.5,5143.5
Exp/Cntr=0.3,0.1

Type RM Length L Ch R = 1,1721,381,381,381
BEGIN DESCRIPTION:
Mapping XS 407ae069
END DESCRIPTION:
XS GIS Cut Line= 3
      3531781.23     10614743.16      3531833.31     10614976.22
      3532535.55     10615302.63
#Sta/Elev= 30
  4723.7  433.94  4742.7  431.56  4853.9  425.02  4962.0  420.51  5013.6  419.95
  5053.6  420.60  5170.5  418.77  5173.3  418.27  5176.5  418.77  5201.9  419.12
  5234.1  421.07  5247.7  419.88  5270.6  419.98  5333.4  423.26  5344.8  424.56
  5355.4  423.94  5362.2  425.22  5399.5  425.27  5407.9  427.01  5421.6  427.92
  5459.2  428.18  5482.1  429.58  5505.0  432.43  5542.9  432.64  5564.9  434.03
  5573.7  435.68  5625.0  436.64  5664.2  439.64  5708.3  439.98  5736.9  442.38
#Mann=3,-1,0
  4723.7    0.05       0  5170.5    0.03       0  5176.5    0.05       0
Bank Sta=5170.5,5176.5
Exp/Cntr=0.3,0.1

Type RM Length L Ch R = 1,1340,286,286,286
BEGIN DESCRIPTION:
Mapping XS ef6a6f14
END DESCRIPTION:
XS GIS Cut Line= 4
      3531759.20     10614769.63      3531815.63     10615325.21
      3531921.96     10615370.78      3532665.42     10615383.79
#Sta/Elev= 30
  4389.5  431.46  4530.8  423.68  4681.6  418.52  4701.7  420.00  4751.9  419.98
  4932.8  415.85  4970.9  417.05  5003.7  415.11  5006.4  414.61  5009.7  415.11
  5047.1  416.68  5063.6  415.78  5081.3  417.18  5141.3  415.19  5221.3  422.41
  5251.3  423.13  5281.3  426.01  5315.9  425.84  5341.3  428.17  5381.3  428.33
  5431.3  431.60  5481.3  432.23  5531.3  435.45  5591.4  436.94  5621.4  439.80
  5651.4  439.64  5681.4  442.12  5721.4  442.55  5751.4  445.02  5807.2  446.04
#Mann=3,-1,0
  4389.5    0.05       0  5003.7    0.03       0  5009.7    0.05       0
Bank Sta=5003.7,5009.7
Exp/Cntr=0.3,0.1

Type RM Length L Ch R = 1,1054,0,0,0
BEGIN DESCRIPTION:
UNT090 IN CCTC 1.0
END DESCRIPTION:
XS GIS Cut Line= 4
      3531717.97     10614758.55      3531707.56     10615576.22
      3531931.52     10615669.97      3532644.79     10615518.98
#Sta/Elev= 30
  4058.7  433.18  4078.3  431.34  4181.4  425.27  4210.3  423.64  4400.4  419.25
  4420.4  417.97  4440.4  418.65  4600.4  416.98  4650.4  414.88  4660.4  415.76
  4707.6  414.08  4740.4  414.57  4899.0  411.99  5016.6  410.89  5019.3  410.39
  5022.6  410.89  5142.6  411.44  5158.2  412.76  5336.2  418.29  5393.3  422.58
  5546.6  427.74  5556.8  429.96  5587.5  430.81  5638.6  434.63  5679.5  435.78
  5710.1  438.95  5781.7  442.13  5802.1  444.58  5832.8  444.95  5848.3  446.29
#Mann=7,-1,0
  4058.7    0.05       0  4078.3    0.08       0  4181.4    0.05       0
  4707.6    0.12       0  4899.0    0.05       0  5016.6    0.03       0
  5022.6    0.05       0
Bank Sta=5016.6,5022.6
Exp/Cntr=0.3,0.1

Chan Stop Cuts=-1