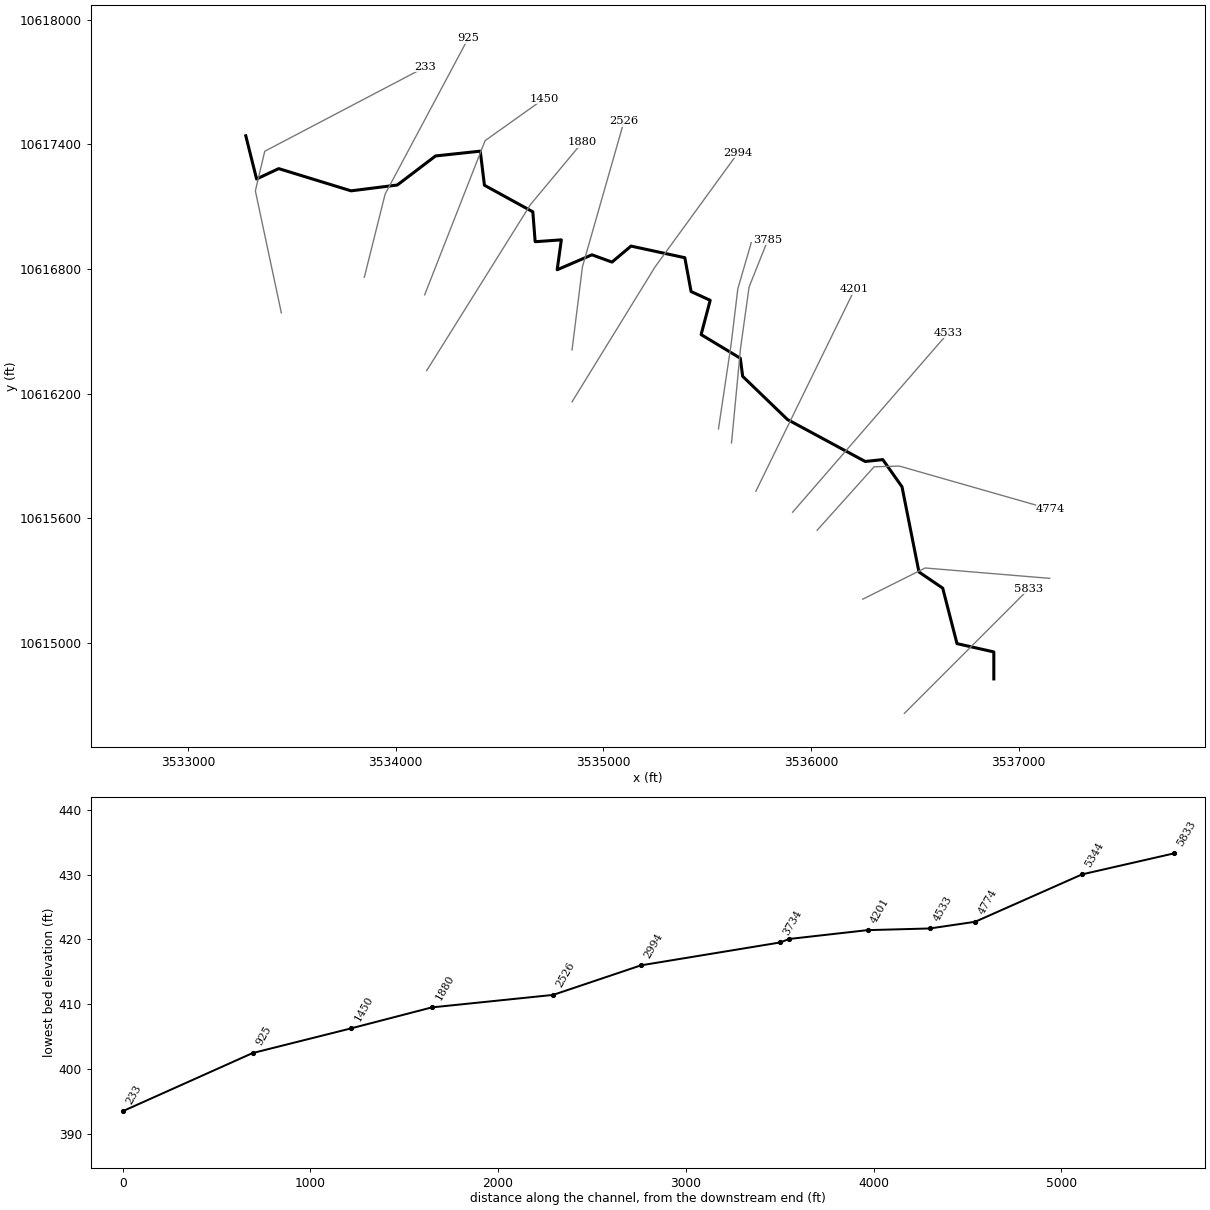
--- UNT091 IN CCTC.prj (project) ---

Proj Title=UNT091 IN CCTC Base Level Engineering
Current Plan=p01
Default Exp/Contr=0.3,0.1
English Units
Geom File=g01
Flow File=f01
Plan File=p01
BEGIN DESCRIPTION:
UNT091 IN CCTC
END DESCRIPTION:

--- UNT091 IN CCTC.p01 (plan) ---

Plan Title=Multiple Run
Short Identifier=Multiple
Geom File=g01
Flow File=f01
Subcritical Flow
K Sum by GR= 0
Std Step Tol= 0.01
Critical Tol= 0.01
Num of Std Step Trials= 20
Max Error Tol= 0.3
Flow Tol Ratio= 0.001
Split Flow NTrial= 30
Split Flow Tol= 0.02
Split Flow Ratio= 0.02
Log Output Level= 0
Friction Slope Method= 1
Unsteady Friction Slope Method= 2
Unsteady Bridges Friction Slope Method= 1
Parabolic Critical Depth
Global Vel Dist=  1 , 1 , 1
Global Log Level= 0
CheckData=True
Encroach Param= -1, 0, 0, 0
BEGIN DESCRIPTION:
Multiple Run
END DESCRIPTION:

--- UNT091 IN CCTC.f01 (steady flow) ---

Flow Title=Multiple
Number of Profiles=7
Profile Names=10-year,25-year,50-year,1pct_min,100-year,1pct_plu,500-year
River Rch & RM= UNT091 IN CCTC,Reach-1,5833
    1330    1833    2249    2016    2726    3687    3990
River Rch & RM= UNT091 IN CCTC,Reach-1,4774
    1877    2637    3278    2972    4019    5435    6023
Boundary for River Rch & Prof#=UNT091 IN CCTC,Reach-1,1
Up Type=0
Dn Type=3
Dn Slope=0.005
Boundary for River Rch & Prof#=UNT091 IN CCTC,Reach-1,2
Up Type=0
Dn Type=3
Dn Slope=0.005
Boundary for River Rch & Prof#=UNT091 IN CCTC,Reach-1,3
Up Type=0
Dn Type=3
Dn Slope=0.005
Boundary for River Rch & Prof#=UNT091 IN CCTC,Reach-1,4
Up Type=0
Dn Type=3
Dn Slope=0.005
Boundary for River Rch & Prof#=UNT091 IN CCTC,Reach-1,5
Up Type=0
Dn Type=3
Dn Slope=0.005
Boundary for River Rch & Prof#=UNT091 IN CCTC,Reach-1,6
Up Type=0
Dn Type=3
Dn Slope=0.005
Boundary for River Rch & Prof#=UNT091 IN CCTC,Reach-1,7
Up Type=0
Dn Type=3
Dn Slope=0.005

--- UNT091 IN CCTC.g01 (geometry) ---

Geom Title=Existing Conditions

River Reach=UNT091 IN CCTC,Reach-1
Reach XY= 30
      3536880.25     10614826.00      3536880.25     10614956.00
      3536703.00     10614996.00      3536634.25     10615263.00
      3536519.75     10615341.00      3536438.25     10615751.00
      3536345.75     10615882.00      3536261.00     10615873.00
      3535886.75     10616075.00      3535671.00     10616283.00
      3535659.75     10616370.00      3535471.00     10616484.00
      3535514.75     10616649.00      3535422.75     10616691.00
      3535392.50     10616854.00      3535133.50     10616910.00
      3535042.00     10616833.00      3534945.25     10616868.00
      3534778.00     10616796.00      3534798.00     10616940.00
      3534672.00     10616931.00      3534660.75     10617075.00
      3534427.75     10617203.00      3534407.75     10617367.00
      3534192.50     10617344.00      3534008.25     10617204.00
      3533785.75     10617176.00      3533437.25     10617283.00
      3533330.75     10617233.00      3533278.75     10617441.00

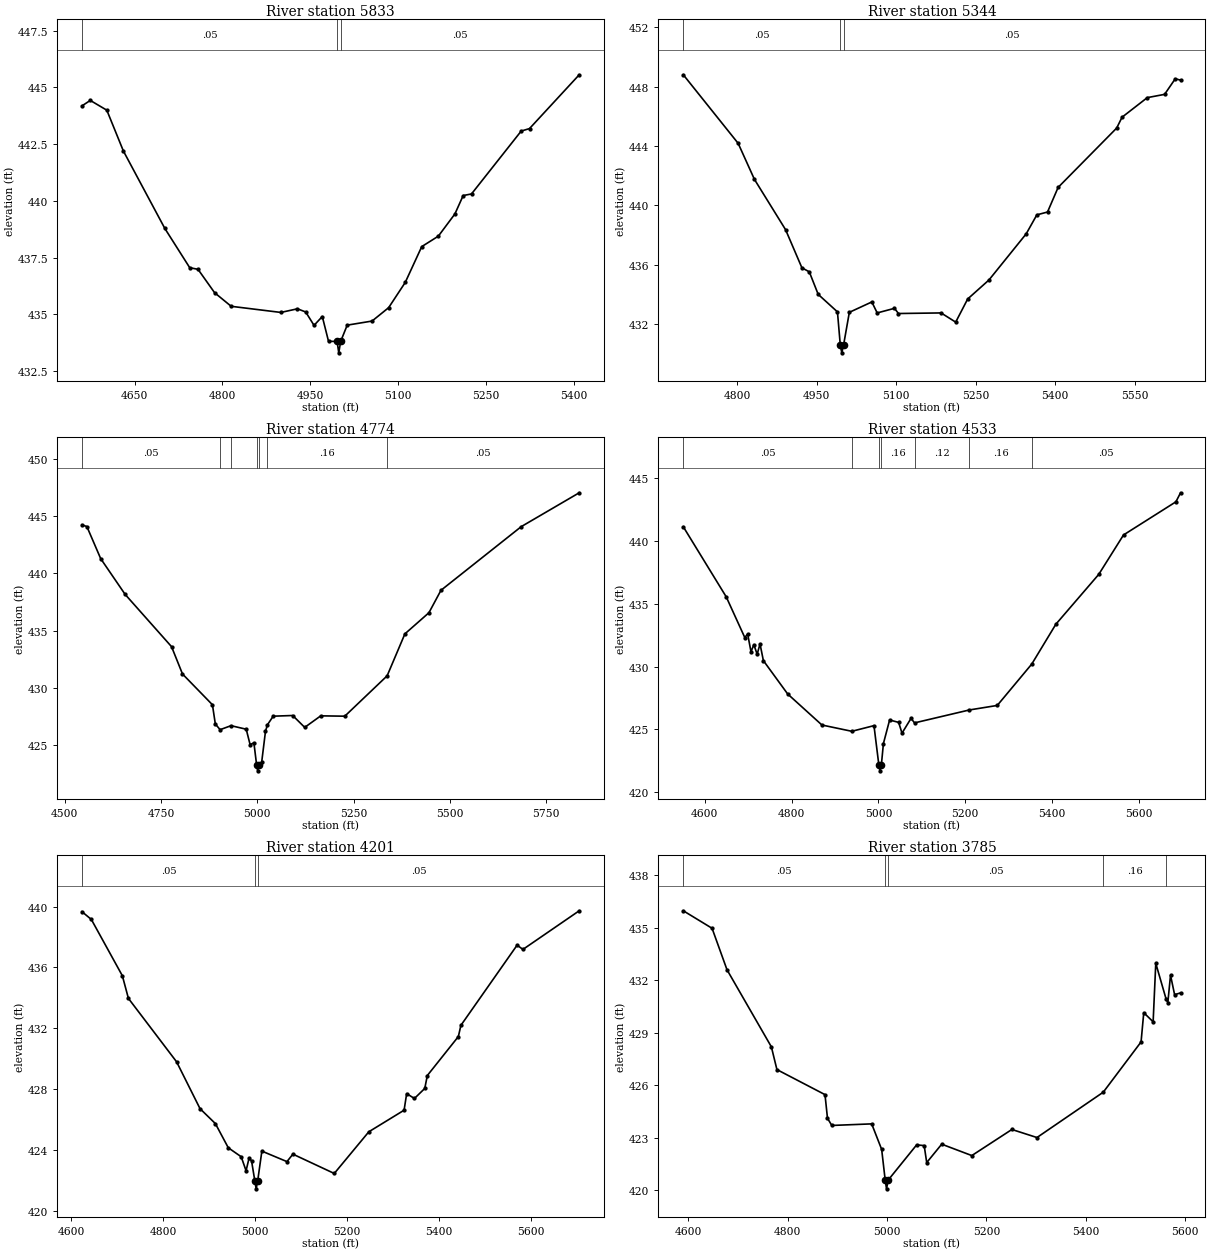
Type RM Length L Ch R = 1,5833,489,489,489
BEGIN DESCRIPTION:
UNT091 IN CCTC 12.0
END DESCRIPTION:
XS GIS Cut Line= 3
      3536449.60     10614660.18      3536749.61     10614960.19
      3537049.58     10615260.16
#Sta/Elev= 30
  4560.3  444.18  4574.5  444.42  4602.7  443.99  4631.0  442.19  4701.7  438.78
  4744.2  437.05  4758.3  436.98  4786.6  435.95  4814.9  435.35  4899.7  435.08
  4928.0  435.24  4942.1  435.10  4956.3  434.51  4970.4  434.90  4981.0  433.81
  4995.7  433.80  4998.5  433.30  5001.7  433.80  5012.9  434.52  5055.3  434.70
  5083.6  435.29  5111.9  436.40  5140.1  437.98  5168.4  438.44  5196.7  439.42
  5210.8  440.23  5225.0  440.30  5309.8  443.07  5324.0  443.18  5408.8  445.55
#Mann=3,-1,0
  4560.3    0.05       0  4995.7    0.03       0  5001.7    0.05       0
Bank Sta=4995.7,5001.7
Exp/Cntr=0.3,0.1

Type RM Length L Ch R = 1,5344,570,570,570
BEGIN DESCRIPTION:
UNT091 IN CCTC 11.0
END DESCRIPTION:
XS GIS Cut Line= 3
      3536249.65     10615210.21      3536549.61     10615360.19
      3537149.57     10615310.19
#Sta/Elev= 30
  4698.8  448.80  4802.2  444.18  4832.9  441.75  4891.6  438.36  4922.4  435.79
  4936.3  435.52  4953.1  434.00  4989.4  432.82  4994.8  430.56  4997.6  430.06
  5000.8  430.56  5011.8  432.79  5054.2  433.49  5064.3  432.75  5096.9  433.06
  5104.4  432.71  5184.7  432.75  5212.3  432.13  5234.9  433.69  5275.0  434.97
  5345.2  438.08  5365.3  439.36  5385.4  439.55  5405.4  441.21  5515.8  445.21
  5525.9  445.94  5573.5  447.26  5606.1  447.48  5626.2  448.53  5636.2  448.44
#Mann=3,-1,0
  4698.8    0.05       0  4994.8    0.03       0  5000.8    0.05       0
Bank Sta=4994.8,5000.8
Exp/Cntr=0.3,0.1

Type RM Length L Ch R = 1,4774,241,241,241
BEGIN DESCRIPTION:
UNT091 IN CCTC 10.0
END DESCRIPTION:
XS GIS Cut Line= 4
      3536029.63     10615541.88      3536303.91     10615847.41
      3536425.44     10615850.88      3537154.60     10615642.55
#Sta/Elev= 30
  4544.9  444.24  4557.6  444.10  4593.5  441.29  4657.0  438.16  4777.4  433.59
  4805.8  431.20  4883.5  428.51  4891.0  426.83  4903.4  426.33  4931.7  426.68
  4971.2  426.37  4981.2  425.03  4991.2  425.17  4998.2  423.23  5001.0  422.73
  5004.2  423.23  5011.2  423.46  5021.2  426.19  5026.3  426.76  5041.2  427.51
  5091.8  427.57  5123.0  426.53  5164.6  427.54  5227.0  427.51  5336.9  431.04
  5383.0  434.71  5445.4  436.56  5476.6  438.52  5685.0  444.09  5835.4  447.05
#Mann=7,-1,0
  4544.9    0.05       0  4903.4    0.16       0  4931.7    0.12       0
  4998.2    0.07       0  5004.2    0.12       0  5026.3    0.16       0
  5336.9    0.05       0
Bank Sta=4998.2,5004.2
Exp/Cntr=0.3,0.1

Type RM Length L Ch R = 1,4533,332,332,332
BEGIN DESCRIPTION:
UNT091 IN CCTC 9.0
END DESCRIPTION:
XS GIS Cut Line= 2
      3535911.55     10615628.66      3536661.58     10616493.28
#Sta/Elev= 30
  4550.9  441.14  4649.7  435.56  4692.4  432.32  4699.0  432.60  4706.7  431.19
  4713.3  431.75  4720.9  430.99  4727.5  431.81  4735.2  430.48  4791.2  427.82
  4870.0  425.35  4938.8  424.85  4989.8  425.30  5000.9  422.20  5003.6  421.70
  5006.9  422.20  5011.5  423.87  5025.8  425.75  5046.6  425.56  5054.3  424.70
  5075.1  425.88  5083.2  425.52  5209.4  426.55  5273.6  426.91  5353.1  430.21
  5408.5  433.38  5507.2  437.35  5564.2  440.49  5684.8  443.13  5695.5  443.85
#Mann=7,-1,0
  4550.9    0.05       0  4938.8    0.16       0  5000.9    0.07       0
  5006.9    0.16       0  5083.2    0.12       0  5209.4    0.16       0
  5353.1    0.05       0
Bank Sta=5000.9,5006.9
Exp/Cntr=0.3,0.1

Type RM Length L Ch R = 1,4201,416,416,416
BEGIN DESCRIPTION:
Mapping XS cf5cc708
END DESCRIPTION:
XS GIS Cut Line= 2
      3535734.47     10615729.35      3536210.18     10616701.61
#Sta/Elev= 30
  4623.2  439.66  4643.6  439.15  4711.1  435.45  4724.3  433.96  4829.2  429.79
  4880.2  426.71  4913.6  425.73  4941.7  424.14  4969.8  423.55  4980.4  422.63
  4986.8  423.44  4992.3  423.29  4999.6  421.94  5002.4  421.44  5005.6  421.94
  5014.8  423.92  5069.4  423.23  5082.4  423.72  5172.4  422.45  5247.6  425.19
  5324.4  426.61  5330.0  427.70  5346.9  427.38  5369.4  428.04  5375.0  428.89
  5442.5  431.45  5448.1  432.19  5570.4  437.46  5583.1  437.18  5705.6  439.72
#Mann=3,-1,0
  4623.2    0.05       0  4999.6    0.03       0  5005.6    0.05       0
Bank Sta=4999.6,5005.6
Exp/Cntr=0.3,0.1

Type RM Length L Ch R = 1,3785,51,51,51
BEGIN DESCRIPTION:
UNT091 IN CCTC 8.0
END DESCRIPTION:
XS GIS Cut Line= 4
      3535617.42     10615962.57      3535660.83     10616418.30
      3535702.06     10616713.44      3535793.20     10616941.29
#Sta/Elev= 30
  4589.9  435.96  4647.8  434.96  4677.9  432.59  4767.2  428.19  4778.4  426.89
  4875.2  425.46  4880.2  424.11  4888.9  423.70  4969.2  423.79  4989.3  422.33
  4996.4  420.58  4999.1  420.08  5002.4  420.58  5059.7  422.59  5074.9  422.55
  5080.0  421.58  5110.2  422.63  5170.8  421.98  5251.5  423.47  5302.0  423.01
  5435.5  425.60  5511.6  428.47  5517.0  430.14  5535.9  429.62  5541.2  432.96
  5562.2  430.90  5565.5  430.72  5570.9  432.28  5579.1  431.17  5591.1  431.27
#Mann=5,-1,0
  4589.9    0.05       0  4996.4    0.04       0  5002.4    0.05       0
  5435.5    0.16       0  5562.2    0.05       0
Bank Sta=4996.4,5002.4
Exp/Cntr=0.3,0.1

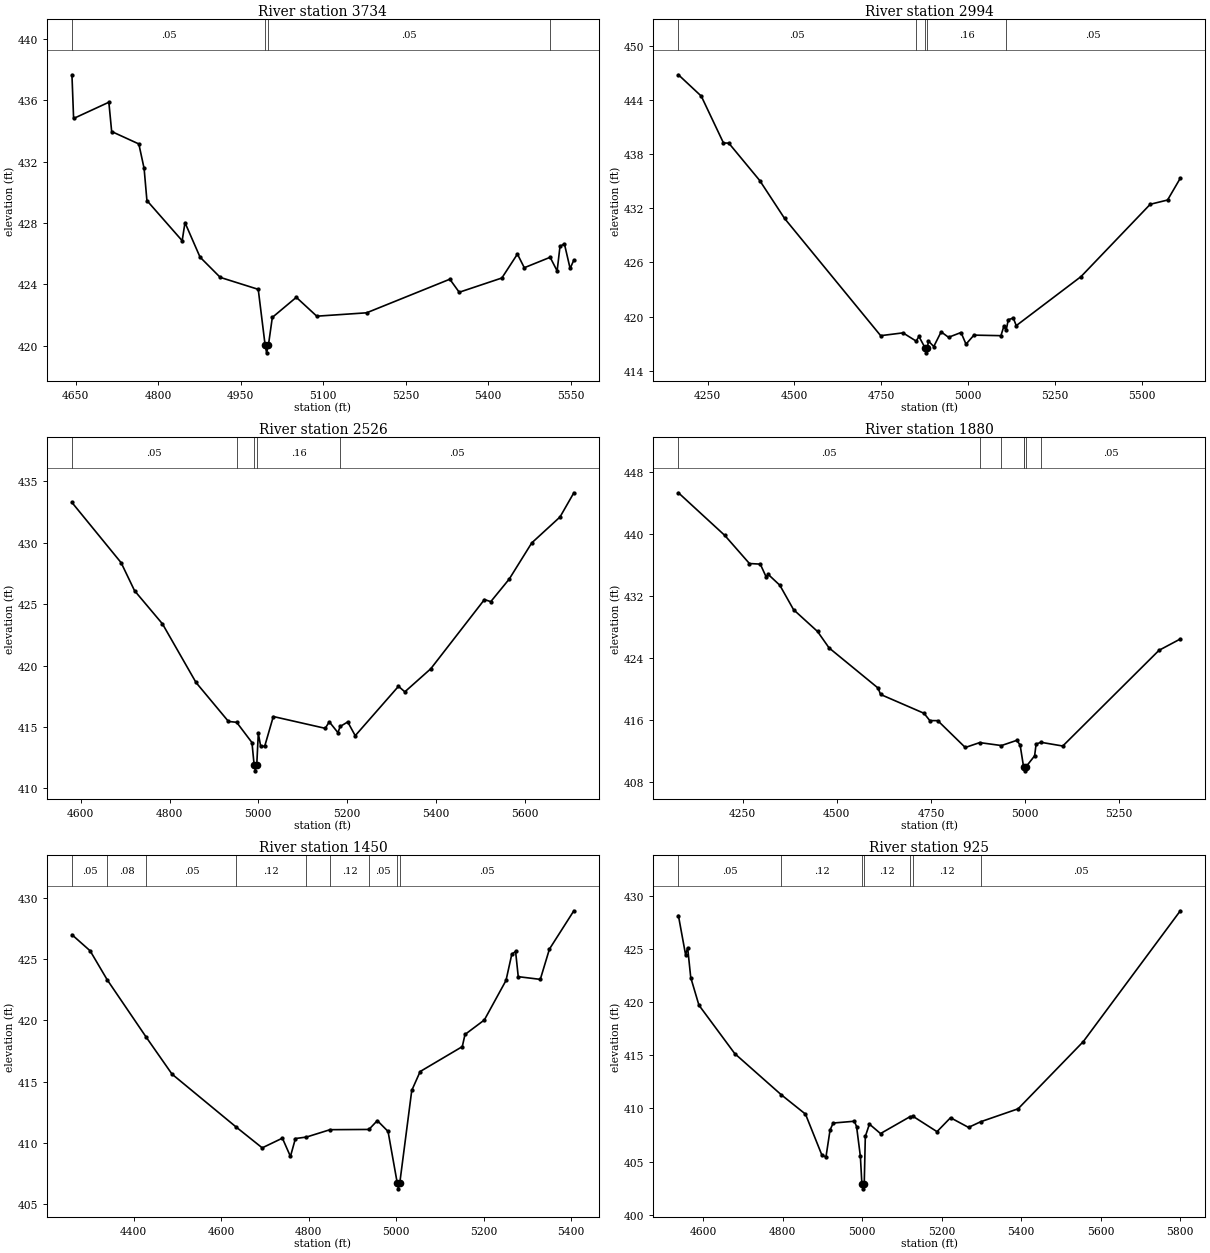
Type RM Length L Ch R = 1,3734,740,740,740
BEGIN DESCRIPTION:
UNT091 IN CCTC 7.0
END DESCRIPTION:
XS GIS Cut Line= 4
      3535554.50     10616029.90      3535615.26     10616435.66
      3535647.81     10616704.76      3535712.45     10616926.69
#Sta/Elev= 30
  4643.5  437.66  4646.5  434.81  4710.6  435.87  4715.7  433.96  4765.1  433.15
  4774.7  431.55  4779.8  429.46  4843.9  426.84  4849.0  428.02  4876.4  425.77
  4913.1  424.45  4982.2  423.67  4994.7  420.03  4997.4  419.53  5000.7  420.03
  5007.8  421.84  5051.4  423.15  5088.6  421.92  5179.2  422.14  5330.5  424.33
  5347.6  423.48  5425.1  424.41  5453.4  425.97  5465.9  425.08  5512.9  425.76
  5525.6  424.87  5530.8  426.47  5538.8  426.64  5549.2  425.03  5556.0  425.58
#Mann=4,-1,0
  4643.5    0.05       0  4994.7    0.04       0  5000.7    0.05       0
  5512.9    0.08       0
Bank Sta=4994.7,5000.7
Exp/Cntr=0.3,0.1

Type RM Length L Ch R = 1,2994,468,468,468
BEGIN DESCRIPTION:
UNT091 IN CCTC 6.0
END DESCRIPTION:
XS GIS Cut Line= 3
      3534849.60     10616160.17      3535249.61     10616810.19
      3535649.60     10617360.18
#Sta/Elev= 30
  4166.2  446.77  4231.9  444.41  4295.7  439.23  4311.2  439.20  4400.0  435.07
  4471.5  430.87  4747.8  417.90  4812.0  418.21  4849.8  417.30  4857.9  417.81
  4876.2  416.50  4878.9  416.00  4882.2  416.50  4885.0  417.31  4900.5  416.70
  4921.7  418.32  4943.0  417.72  4978.9  418.25  4993.2  416.96  5016.0  417.96
  5093.7  417.90  5102.2  418.96  5108.5  418.48  5114.9  419.67  5129.2  419.85
  5137.7  419.01  5324.0  424.44  5523.0  432.44  5572.8  432.91  5609.5  435.33
#Mann=5,-1,0
  4166.2    0.05       0  4849.8    0.16       0  4876.2    0.07       0
  4882.2    0.16       0  5108.5    0.05       0
Bank Sta=4876.2,4882.2
Exp/Cntr=0.3,0.1

Type RM Length L Ch R = 1,2526,646,646,646
BEGIN DESCRIPTION:
UNT091 IN CCTC 5.0
END DESCRIPTION:
XS GIS Cut Line= 3
      3534849.61     10616410.22      3534899.61     10616810.19
      3535099.61     10617510.20
#Sta/Elev= 30
  4580.1  433.27  4690.9  428.37  4721.2  426.09  4784.1  423.39  4859.7  418.62
  4932.8  415.45  4951.3  415.38  4985.8  413.73  4990.6  411.93  4993.3  411.43
  4996.6  411.93  5000.1  414.48  5005.3  413.45  5014.4  413.42  5033.9  415.85
  5150.9  414.89  5160.0  415.42  5179.5  414.54  5184.6  415.04  5201.6  415.41
  5218.5  414.29  5316.0  418.31  5330.3  417.86  5388.8  419.74  5509.7  425.37
  5524.0  425.20  5565.6  427.04  5616.3  429.98  5680.0  432.09  5711.2  434.06
#Mann=5,-1,0
  4580.1    0.05       0  4951.3    0.16       0  4990.6    0.07       0
  4996.6    0.16       0  5184.6    0.05       0
Bank Sta=4990.6,4996.6
Exp/Cntr=0.3,0.1

Type RM Length L Ch R = 1,1880,430,430,430
BEGIN DESCRIPTION:
UNT091 IN CCTC 4.0
END DESCRIPTION:
XS GIS Cut Line= 3
      3534149.59     10616310.16      3534649.61     10617110.19
      3534899.58     10617410.16
#Sta/Elev= 30
  4079.0  445.35  4202.3  439.85  4267.7  436.23  4296.6  436.15  4311.9  434.53
  4317.8  434.82  4348.5  433.43  4385.0  430.28  4448.7  427.47  4479.4  425.35
  4609.7  420.17  4616.2  419.35  4731.7  416.92  4747.1  415.98  4768.3  415.97
  4841.4  412.51  4879.7  413.14  4937.5  412.76  4978.2  413.43  4987.1  412.84
  4996.2  410.05  4996.4  410.00  4999.2  409.50  5002.4  410.00  5025.7  411.44
  5029.6  412.95  5042.3  413.18  5100.5  412.70  5356.3  425.04  5412.9  426.50
#Mann=7,-1,0
  4079.0    0.05       0  4879.7    0.16       0  4937.5    0.12       0
  4996.2    0.16       0  4996.4    0.07       0  5002.4    0.16       0
  5042.3    0.05       0
Bank Sta=4996.4,5002.4
Exp/Cntr=0.3,0.1

Type RM Length L Ch R = 1,1450,525,525,525
BEGIN DESCRIPTION:
UNT091 IN CCTC 3.0
END DESCRIPTION:
XS GIS Cut Line= 3
      3534139.99     10616675.23      3534430.79     10617417.43
      3534715.94     10617620.49
#Sta/Elev= 30
  4259.3  426.97  4300.8  425.66  4339.8  423.30  4429.4  418.60  4488.0  415.61
  4635.2  411.28  4694.2  409.60  4740.3  410.39  4758.7  408.90  4770.1  410.36
  4795.3  410.48  4849.2  411.08  4938.1  411.10  4957.3  411.82  4981.8  410.94
  5002.7  406.76  5005.5  406.26  5008.7  406.76  5036.0  414.28  5055.2  415.82
  5151.5  417.85  5157.7  418.84  5201.9  420.02  5251.4  423.24  5264.6  425.37
  5273.3  425.61  5279.4  423.55  5329.8  423.33  5350.7  425.80  5406.5  428.92
#Mann=9,-1,0
  4259.3    0.05       0  4339.8    0.08       0  4429.4    0.05       0
  4635.2    0.12       0  4795.3    0.05       0  4849.2    0.12       0
  4938.1    0.05       0  5002.7    0.03       0  5008.7    0.05       0
Bank Sta=5002.7,5008.7
Exp/Cntr=0.3,0.1

Type RM Length L Ch R = 1,925,692,692,692
BEGIN DESCRIPTION:
UNT091 IN CCTC 2.0
END DESCRIPTION:
XS GIS Cut Line= 3
      3533849.60     10616760.15      3533949.61     10617160.19
      3534349.63     10617910.23
#Sta/Elev= 30
  4538.2  428.15  4556.3  424.45  4561.4  425.13  4569.2  422.32  4589.8  419.72
  4680.0  415.16  4796.6  411.30  4857.8  409.47  4899.0  405.62  4909.3  405.43
  4919.6  407.97  4927.4  408.63  4980.7  408.80  4986.3  408.30  4995.9  405.49
  4999.6  402.94  5002.4  402.44  5005.6  402.94  5008.3  407.37  5018.6  408.53
  5046.5  407.64  5119.9  409.21  5128.0  409.27  5188.6  407.82  5222.6  409.13
  5267.9  408.22  5298.3  408.75  5392.6  409.97  5556.5  416.29  5800.6  428.60
#Mann=7,-1,0
  4538.2    0.05       0  4796.6    0.12       0  4999.6    0.07       0
  5005.6    0.12       0  5119.9    0.16       0  5128.0    0.12       0
  5298.3    0.05       0
Bank Sta=4999.6,5005.6
Exp/Cntr=0.3,0.1

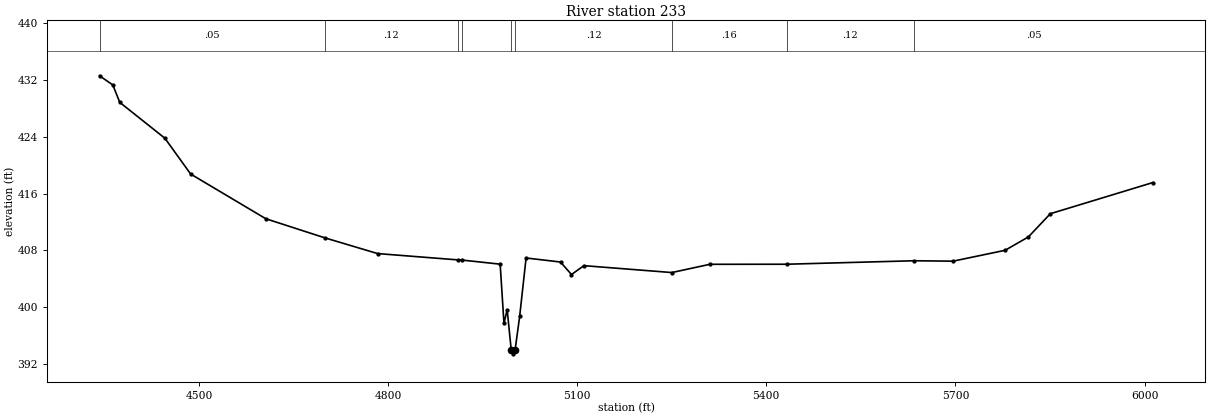
Type RM Length L Ch R = 1,233,0,0,0
BEGIN DESCRIPTION:
UNT091 IN CCTC 1.0
END DESCRIPTION:
XS GIS Cut Line= 4
      3533449.90     10616588.77      3533324.89     10617175.61
      3533370.03     10617366.58      3534144.29     10617772.81
#Sta/Elev= 30
  4342.4  432.58  4363.5  431.29  4374.5  428.84  4446.1  423.79  4487.0  418.75
  4606.2  412.46  4699.6  409.78  4783.5  407.56  4910.9  406.67  4917.9  406.64
  4977.9  406.07  4983.9  397.75  4989.0  399.65  4995.5  393.95  4998.2  393.45
  5001.5  393.95  5008.8  398.71  5019.0  406.94  5073.6  406.37  5091.0  404.61
  5110.7  405.86  5250.2  404.89  5310.5  406.05  5432.2  406.06  5634.5  406.55
  5696.2  406.49  5778.8  408.02  5815.7  409.90  5850.6  413.17  6013.0  417.55
#Mann=9,-1,0
  4342.4    0.05       0  4699.6    0.12       0  4910.9    0.16       0
  4917.9    0.12       0  4995.5    0.07       0  5001.5    0.12       0
  5250.2    0.16       0  5432.2    0.12       0  5634.5    0.05       0
Bank Sta=4995.5,5001.5
Exp/Cntr=0.3,0.1

Chan Stop Cuts=-1