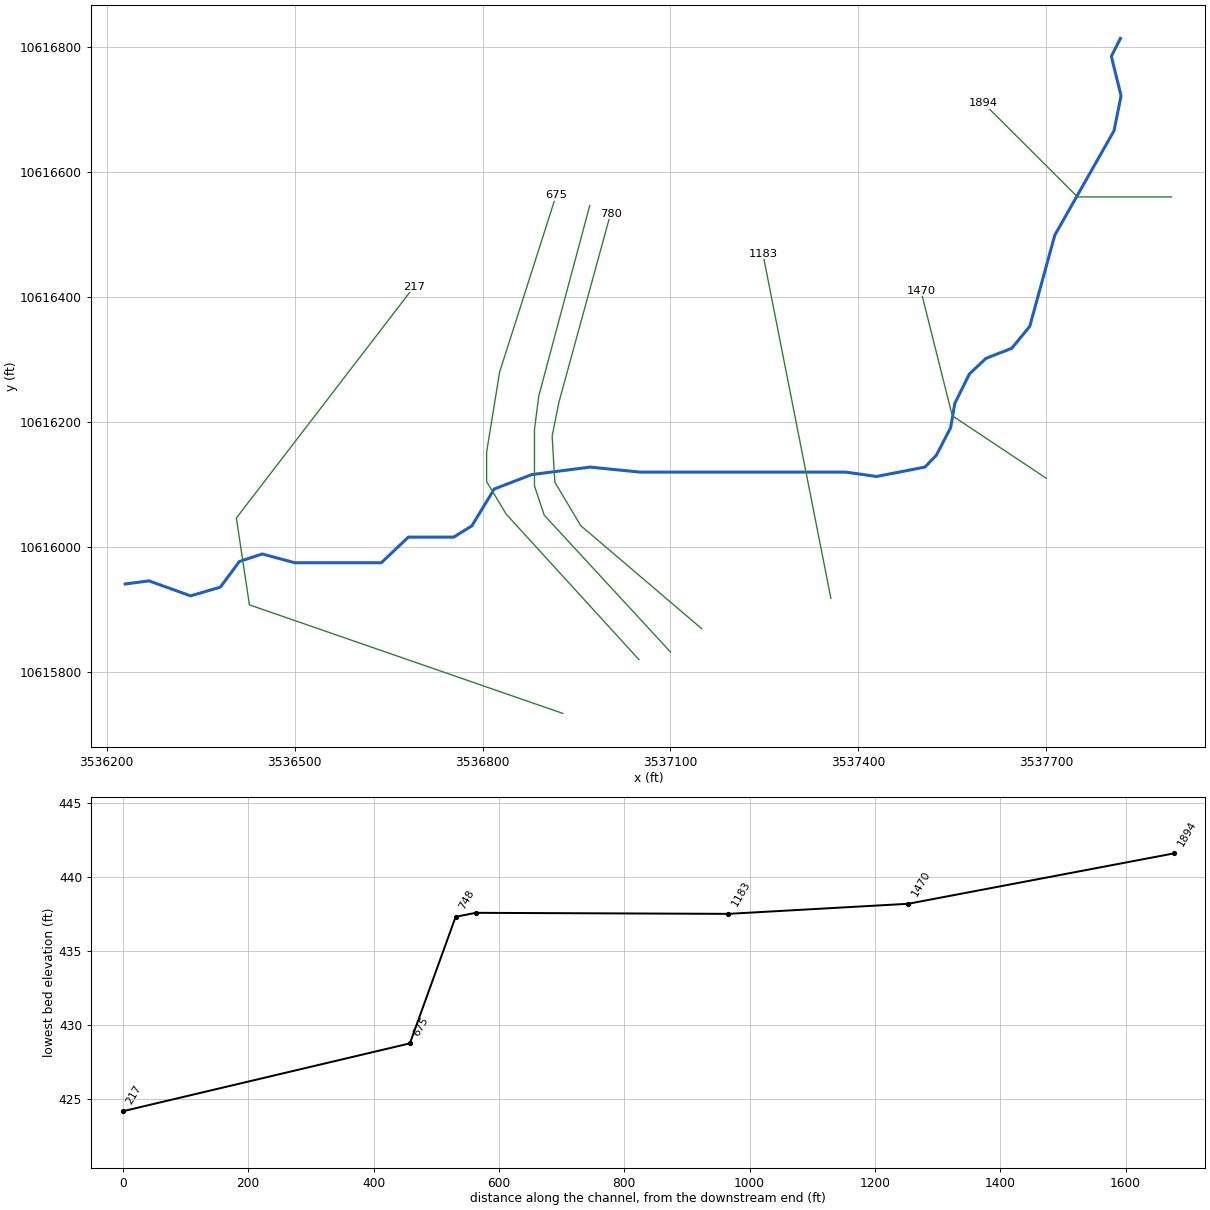
--- UNT092 IN CCTC.prj (project) ---

Proj Title=UNT092 IN CCTC Base Level Engineering
Current Plan=p01
Default Exp/Contr=0.3,0.1
English Units
Geom File=g01
Flow File=f01
Plan File=p01
BEGIN DESCRIPTION:
UNT092 IN CCTC
END DESCRIPTION:

--- UNT092 IN CCTC.p01 (plan) ---

Plan Title=Multiple Run
Short Identifier=Multiple
Geom File=g01
Flow File=f01
Subcritical Flow
K Sum by GR= 0
Std Step Tol= 0.01
Critical Tol= 0.01
Num of Std Step Trials= 20
Max Error Tol= 0.3
Flow Tol Ratio= 0.001
Split Flow NTrial= 30
Split Flow Tol= 0.02
Split Flow Ratio= 0.02
Log Output Level= 0
Friction Slope Method= 1
Unsteady Friction Slope Method= 2
Unsteady Bridges Friction Slope Method= 1
Parabolic Critical Depth
Global Vel Dist=  1 , 1 , 1
Global Log Level= 0
CheckData=True
Encroach Param= -1, 0, 0, 0
BEGIN DESCRIPTION:
Multiple Run
END DESCRIPTION:

--- UNT092 IN CCTC.f01 (steady flow) ---

Flow Title=Multiple
Number of Profiles=7
Profile Names=10-year,25-year,50-year,1pct_min,100-year,1pct_plu,500-year
River Rch & RM= UNT092 IN CCTC,Reach-1,1894
     336     421     485     410     555     750     720
Boundary for River Rch & Prof#=UNT092 IN CCTC,Reach-1,1
Up Type=0
Dn Type=3
Dn Slope=0.005
Boundary for River Rch & Prof#=UNT092 IN CCTC,Reach-1,2
Up Type=0
Dn Type=3
Dn Slope=0.005
Boundary for River Rch & Prof#=UNT092 IN CCTC,Reach-1,3
Up Type=0
Dn Type=3
Dn Slope=0.005
Boundary for River Rch & Prof#=UNT092 IN CCTC,Reach-1,4
Up Type=0
Dn Type=3
Dn Slope=0.005
Boundary for River Rch & Prof#=UNT092 IN CCTC,Reach-1,5
Up Type=0
Dn Type=3
Dn Slope=0.005
Boundary for River Rch & Prof#=UNT092 IN CCTC,Reach-1,6
Up Type=0
Dn Type=3
Dn Slope=0.005
Boundary for River Rch & Prof#=UNT092 IN CCTC,Reach-1,7
Up Type=0
Dn Type=3
Dn Slope=0.005

--- UNT092 IN CCTC.g01 (geometry) ---

Geom Title=Existing Conditions

River Reach=UNT092 IN CCTC,Reach-1
Reach XY= 30
      3537817.97     10616813.90      3537803.50     10616785.00
      3537819.00     10616722.00      3537807.75     10616666.00
      3537713.25     10616499.00      3537673.25     10616353.00
      3537644.50     10616318.00      3537603.50     10616302.00
      3537577.00     10616277.00      3537553.75     10616230.00
      3537547.00     10616191.00      3537524.25     10616147.00
      3537506.00     10616128.00      3537428.75     10616113.00
      3537379.75     10616120.00      3537052.00     10616120.00
      3536971.75     10616128.00      3536878.50     10616116.00
      3536818.75     10616093.00      3536783.00     10616034.00
      3536754.00     10616016.00      3536681.75     10616016.00
      3536638.50     10615975.00      3536500.50     10615975.00
      3536448.50     10615989.00      3536412.00     10615977.00
      3536381.75     10615936.00      3536334.25     10615922.00
      3536267.75     10615946.00      3536229.75     10615941.00

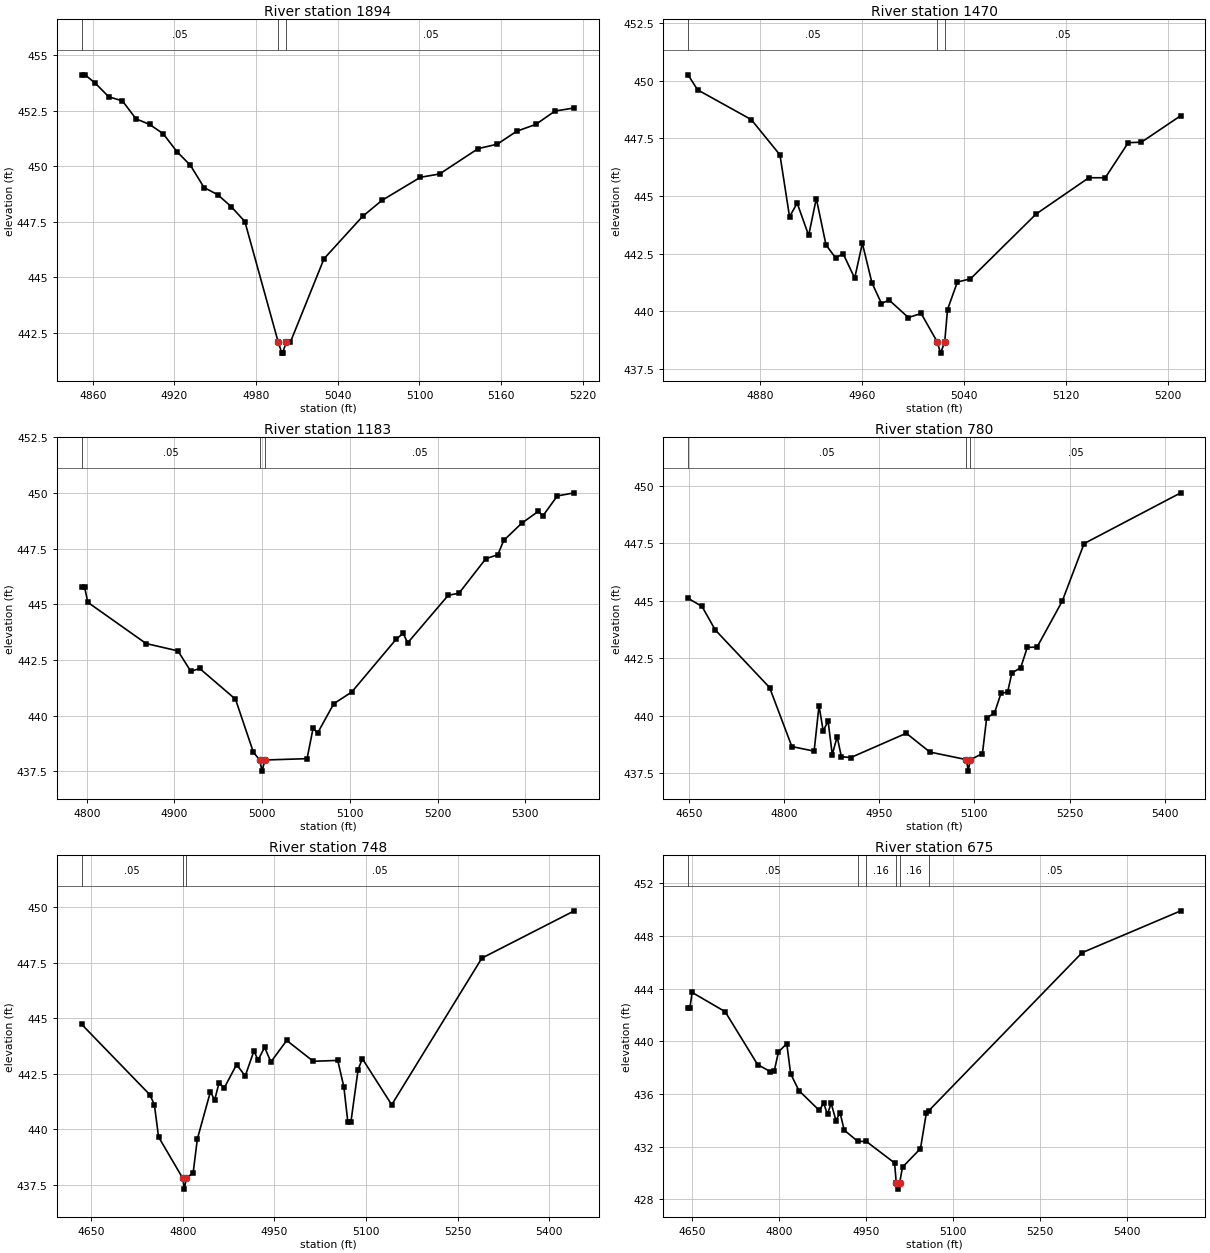
Type RM Length L Ch R = 1,1894,424,424,424
BEGIN DESCRIPTION:
UNT092 IN CCTC 3.0
END DESCRIPTION:
XS GIS Cut Line= 3
      3537899.57     10616560.19      3537749.61     10616560.19
      3537599.60     10616710.20
#Sta/Elev= 30
  4851.7  454.11  4854.2  454.11  4861.7  453.74  4871.7  453.12  4881.7  452.94
  4891.7  452.13  4901.7  451.88  4911.7  451.46  4921.7  450.66  4931.7  450.04
  4941.7  449.04  4951.7  448.72  4961.7  448.18  4971.7  447.51  4996.2  442.09
  4998.9  441.59  4999.4  441.59  5002.2  442.09  5005.2  442.09  5029.9  445.84
  5058.2  447.74  5072.4  448.46  5100.7  449.50  5114.8  449.65  5143.1  450.79
  5157.2  450.99  5171.4  451.57  5185.5  451.88  5199.6  452.48  5213.8  452.62
#Mann=3,-1,0
  4851.7    0.05       0  4996.2   0.035       0  5002.2    0.05       0
Bank Sta=4996.2,5002.2
Exp/Cntr=0.3,0.1

Type RM Length L Ch R = 1,1470,287,287,287
BEGIN DESCRIPTION:
UNT092 IN CCTC 2.0
END DESCRIPTION:
XS GIS Cut Line= 3
      3537699.60     10616110.19      3537549.61     10616210.19
      3537499.62     10616410.16
#Sta/Elev= 30
  4823.6  450.25  4831.1  449.60  4873.2  448.31  4895.7  446.78  4903.2  444.10
  4909.2  444.69  4918.2  443.29  4924.2  444.89  4931.8  442.88  4939.3  442.32
  4945.3  442.49  4954.3  441.44  4960.3  442.95  4967.8  441.24  4975.3  440.34
  4981.3  440.49  4996.4  439.73  5006.4  439.91  5018.9  438.69  5021.7  438.19
  5024.9  438.69  5027.1  440.08  5034.8  441.27  5045.1  441.41  5096.6  444.22
  5137.9  445.79  5150.8  445.79  5168.8  447.31  5179.1  447.33  5210.0  448.48
#Mann=3,-1,0
  4823.6    0.05       0  5018.9    0.03       0  5024.9    0.05       0
Bank Sta=5018.9,5024.9
Exp/Cntr=0.3,0.1

Type RM Length L Ch R = 1,1183,403,403,403
BEGIN DESCRIPTION:
Mapping XS 146042ea
END DESCRIPTION:
XS GIS Cut Line= 2
      3537355.96     10615917.98      3537247.45     10616469.20
#Sta/Elev= 30
  4794.1  445.76  4797.6  445.76  4801.3  445.09  4867.7  443.24  4904.0  442.91
  4918.7  441.99  4928.8  442.12  4969.6  440.74  4990.0  438.36  4997.2  438.01
  4999.9  437.51  5003.2  438.01  5051.2  438.07  5058.1  439.44  5063.2  439.22
  5081.7  440.54  5102.1  441.06  5153.1  443.45  5160.8  443.70  5165.9  443.27
  5212.2  445.41  5224.4  445.50  5255.0  447.05  5268.7  447.23  5275.4  447.87
  5295.8  448.64  5314.9  449.18  5320.0  448.97  5336.5  449.87  5355.9  450.01
#Mann=3,-1,0
  4794.1    0.05       0  4997.2    0.03       0  5003.2    0.05       0
Bank Sta=4997.2,5003.2
Exp/Cntr=0.3,0.1

Type RM Length L Ch R = 1,780,32,32,32
BEGIN DESCRIPTION:
Mapping XS 02709dac
END DESCRIPTION:
XS GIS Cut Line= 6
      3537149.83     10615869.49      3536956.69     10616034.42
      3536915.46     10616103.86      3536911.12     10616177.65
      3536921.97     10616231.90      3537004.43     10616533.52
#Sta/Elev= 30
  4648.5  445.11  4670.6  444.75  4691.4  443.73  4777.1  441.22  4812.2  438.65
  4847.3  438.45  4855.0  440.43  4861.6  439.33  4869.3  439.76  4875.9  438.30
  4883.6  439.08  4890.2  438.21  4905.0  438.17  4992.6  439.23  5029.8  438.41
  5087.5  438.08  5090.2  437.58  5093.5  438.08  5112.6  438.34  5119.3  439.90
  5131.6  440.11  5141.9  440.97  5152.3  441.02  5159.0  441.85  5173.0  442.09
  5183.4  442.97  5198.7  442.98  5238.4  444.98  5272.9  447.49  5425.3  449.70
#Mann=3,-1,0
  4648.5    0.05       0  5087.5   0.033       0  5093.5    0.05       0
Bank Sta=5087.5,5093.5
Exp/Cntr=0.3,0.1

Type RM Length L Ch R = 1,748,73,73,73
BEGIN DESCRIPTION:
Mapping XS 1b90bc8a
END DESCRIPTION:
XS GIS Cut Line= 6
      3537099.94     10615832.28      3536898.53     10616051.06
      3536882.91     10616097.93      3536882.91     10616188.21
      3536889.85     10616242.03      3536971.13     10616546.40
#Sta/Elev= 30
  4634.3  444.74  4746.2  441.56  4753.5  441.12  4760.4  439.66  4799.8  437.81
  4802.6  437.31  4805.8  437.81  4817.0  438.04  4823.9  439.57  4845.3  441.70
  4852.2  441.32  4859.5  442.11  4867.7  441.86  4888.1  442.92  4902.3  442.41
  4916.6  443.54  4923.2  443.12  4934.0  443.70  4944.3  443.04  4970.2  444.01
  5013.7  443.07  5053.8  443.11  5063.8  441.91  5070.3  440.33  5075.3  440.33
  5087.0  442.68  5094.0  443.19  5142.1  441.11  5289.8  447.72  5441.1  449.85
#Mann=3,-1,0
  4634.3    0.05       0  4799.8   0.033       0  4805.8    0.05       0
Bank Sta=4799.8,4805.8
Exp/Cntr=0.3,0.1

Type RM Length L Ch R = 1,675,458,458,458
BEGIN DESCRIPTION:
Mapping XS a3d599c5
END DESCRIPTION:
XS GIS Cut Line= 6
      3537049.54     10615820.19      3536837.77     10616052.79
      3536806.52     10616104.88      3536806.52     10616151.75
      3536827.35     10616280.22      3536917.64     10616563.26
#Sta/Elev= 30
  4642.6  442.56  4645.9  442.56  4649.7  443.71  4706.6  442.25  4762.6  438.23
  4784.4  437.70  4791.1  437.71  4798.6  439.20  4812.9  439.82  4819.5  437.54
  4833.7  436.26  4868.9  434.75  4876.4  435.30  4883.1  434.45  4889.3  435.30
  4897.7  433.98  4904.7  434.58  4911.9  433.25  4935.3  432.40  4950.1  432.39
  4998.7  430.76  5001.6  429.27  5004.3  428.77  5007.6  429.27  5012.4  430.44
  5043.4  431.85  5053.4  434.52  5057.6  434.72  5322.0  446.73  5492.2  449.91
#Mann=6,-1,0
  4642.6    0.05       0  4935.3    0.12       0  4950.1    0.16       0
  5001.6    0.07       0  5007.6    0.16       0  5057.6    0.05       0
Bank Sta=5001.6,5007.6
Exp/Cntr=0.3,0.1

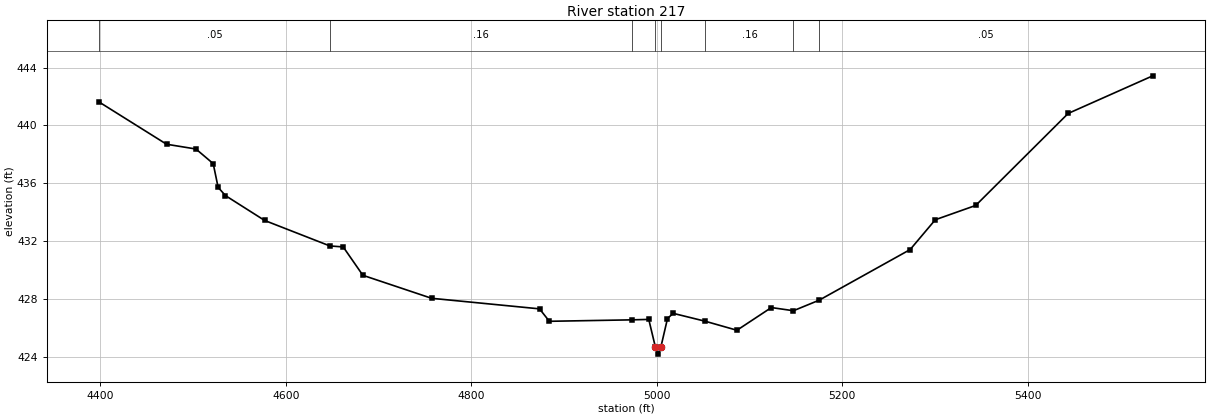
Type RM Length L Ch R = 1,217,0,0,0
BEGIN DESCRIPTION:
UNT092 IN CCTC 1.0
END DESCRIPTION:
XS GIS Cut Line= 4
      3536928.05     10615734.04      3536428.04     10615907.65
      3536407.21     10616046.54      3536690.83     10616416.63
#Sta/Elev= 30
  4398.8  441.61  4471.3  438.70  4503.0  438.37  4521.6  437.36  4526.9  435.72
  4534.8  435.15  4577.1  433.43  4647.4  431.67  4661.8  431.60  4683.0  429.64
  4757.1  428.05  4873.5  427.32  4884.1  426.46  4972.9  426.56  4991.3  426.59
  4998.4  424.69  5001.2  424.19  5004.4  424.69  5011.5  426.65  5017.6  427.01
  5052.4  426.46  5086.4  425.84  5123.5  427.41  5147.3  427.19  5175.1  427.92
  5273.2  431.42  5300.3  433.48  5343.9  434.47  5443.6  440.83  5534.8  443.43
#Mann=8,-1,0
  4398.8    0.05       0  4647.4    0.16       0  4972.9    0.12       0
  4998.4    0.07       0  5004.4    0.12       0  5052.4    0.16       0
  5147.3    0.12       0  5175.1    0.05       0
Bank Sta=4998.4,5004.4
Exp/Cntr=0.3,0.1

Chan Stop Cuts=-1