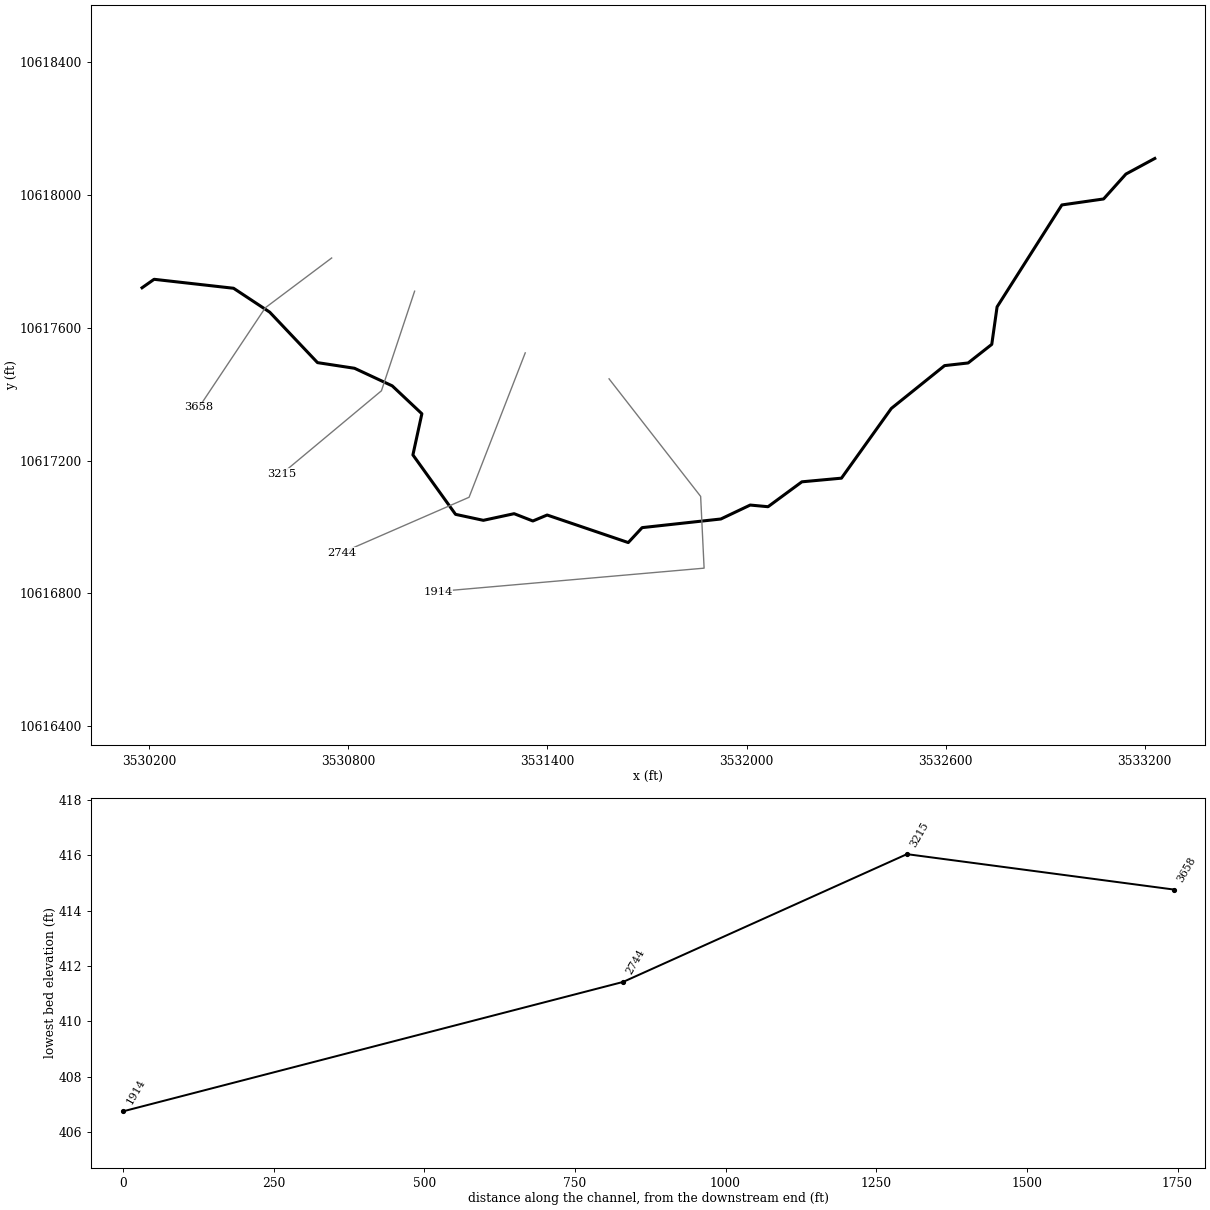
--- UNT093 IN CCTC.prj (project) ---

Proj Title=UNT093 IN CCTC Base Level Engineering
Current Plan=p01
Default Exp/Contr=0.3,0.1
English Units
Geom File=g01
Flow File=f01
Plan File=p01
BEGIN DESCRIPTION:
UNT093 IN CCTC
END DESCRIPTION:

--- UNT093 IN CCTC.p01 (plan) ---

Plan Title=Multiple Run
Short Identifier=Multiple
Geom File=g01
Flow File=f01
Subcritical Flow
K Sum by GR= 0
Std Step Tol= 0.01
Critical Tol= 0.01
Num of Std Step Trials= 20
Max Error Tol= 0.3
Flow Tol Ratio= 0.001
Split Flow NTrial= 30
Split Flow Tol= 0.02
Split Flow Ratio= 0.02
Log Output Level= 0
Friction Slope Method= 1
Unsteady Friction Slope Method= 2
Unsteady Bridges Friction Slope Method= 1
Parabolic Critical Depth
Global Vel Dist=  1 , 1 , 1
Global Log Level= 0
CheckData=True
Encroach Param= -1, 0, 0, 0
BEGIN DESCRIPTION:
Multiple Run
END DESCRIPTION:

--- UNT093 IN CCTC.f01 (steady flow) ---

Flow Title=Multiple
Number of Profiles=7
Profile Names=10-year,25-year,50-year,1pct_min,100-year,1pct_plu,500-year
River Rch & RM= UNT093 IN CCTC,Reach-1,3658
     793    1055    1265    1108    1498    2026    2095
Boundary for River Rch & Prof#=UNT093 IN CCTC,Reach-1,1
Up Type=0
Dn Type=3
Dn Slope=0.005
Boundary for River Rch & Prof#=UNT093 IN CCTC,Reach-1,2
Up Type=0
Dn Type=3
Dn Slope=0.005
Boundary for River Rch & Prof#=UNT093 IN CCTC,Reach-1,3
Up Type=0
Dn Type=3
Dn Slope=0.005
Boundary for River Rch & Prof#=UNT093 IN CCTC,Reach-1,4
Up Type=0
Dn Type=3
Dn Slope=0.005
Boundary for River Rch & Prof#=UNT093 IN CCTC,Reach-1,5
Up Type=0
Dn Type=3
Dn Slope=0.005
Boundary for River Rch & Prof#=UNT093 IN CCTC,Reach-1,6
Up Type=0
Dn Type=3
Dn Slope=0.005
Boundary for River Rch & Prof#=UNT093 IN CCTC,Reach-1,7
Up Type=0
Dn Type=3
Dn Slope=0.005

--- UNT093 IN CCTC.g01 (geometry) ---

Geom Title=Existing Conditions

River Reach=UNT093 IN CCTC,Reach-1
Reach XY= 30
      3530178.22     10617720.51      3530214.50     10617746.00
      3530454.00     10617719.00      3530563.00     10617647.00
      3530707.00     10617495.00      3530818.50     10617478.00
      3530932.25     10617425.00      3531021.50     10617341.00
      3530994.50     10617217.00      3531123.00     10617038.00
      3531206.75     10617020.00      3531299.50     10617040.00
      3531356.00     10617018.00      3531399.00     10617036.00
      3531643.50     10616953.00      3531685.25     10616998.00
      3531922.50     10617024.00      3532011.00     10617066.00
      3532064.75     10617061.00      3532166.75     10617136.00
      3532286.00     10617147.00      3532436.25     10617357.00
      3532596.75     10617486.00      3532667.75     10617494.00
      3532739.00     10617550.00      3532755.00     10617663.00
      3532950.25     10617970.00      3533076.00     10617988.00
      3533143.25     10618063.00      3533230.25     10618110.00

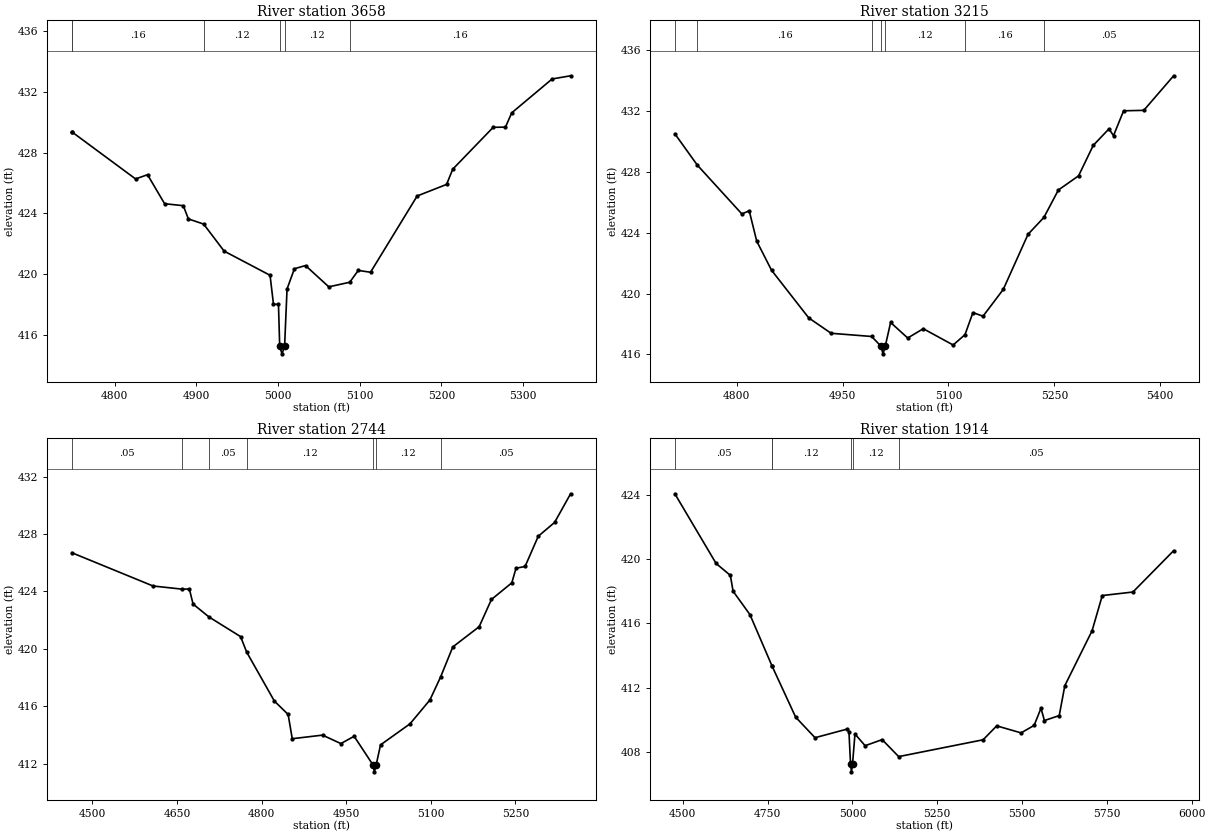
Type RM Length L Ch R = 1,3658,443,443,443
BEGIN DESCRIPTION:
UNT093 IN CCTC 3.0
END DESCRIPTION:
XS GIS Cut Line= 3
      3530749.62     10617810.20      3530549.61     10617660.19
      3530349.59     10617360.16
#Sta/Elev= 30
  4747.5  429.34  4748.3  429.34  4825.6  426.27  4840.2  426.55  4861.1  424.64
  4884.0  424.51  4890.2  423.64  4908.9  423.30  4934.0  421.52  4990.2  419.93
  4994.4  418.02  5000.5  418.02  5002.0  415.26  5004.8  414.76  5008.0  415.26
  5011.0  419.03  5020.0  420.36  5033.6  420.57  5062.1  419.17  5087.7  419.47
  5098.2  420.25  5113.2  420.13  5170.3  425.15  5206.3  425.91  5213.8  426.91
  5263.4  429.67  5278.4  429.68  5286.0  430.62  5335.5  432.85  5358.1  433.06
#Mann=6,-1,0
  4747.5     0.1       0  4748.3    0.16       0  4908.9    0.12       0
  5002.0    0.07       0  5008.0    0.12       0  5087.7    0.16       0
Bank Sta=5002,5008
Exp/Cntr=0.3,0.1

Type RM Length L Ch R = 1,3215,471,471,471
BEGIN DESCRIPTION:
UNT093 IN CCTC 2.0
END DESCRIPTION:
XS GIS Cut Line= 3
      3530999.61     10617710.19      3530899.61     10617410.19
      3530599.64     10617160.22
#Sta/Elev= 30
  4712.3  430.49  4744.2  428.43  4807.2  425.23  4817.7  425.43  4828.3  423.44
  4849.3  421.53  4902.0  418.40  4933.7  417.39  4991.1  417.18  5004.4  416.54
  5007.2  416.04  5010.4  416.54  5018.0  418.10  5042.2  417.08  5064.3  417.69
  5106.6  416.62  5123.4  417.30  5134.6  418.75  5148.9  418.51  5177.6  420.27
  5212.7  423.89  5235.2  425.00  5255.7  426.80  5284.3  427.73  5305.1  429.73
  5327.3  430.81  5333.8  430.37  5348.1  432.00  5376.7  432.03  5419.0  434.30
#Mann=7,-1,0
  4712.3     0.1       0  4744.2    0.16       0  4991.1    0.12       0
  5004.4    0.07       0  5010.4    0.12       0  5123.4    0.16       0
  5235.2    0.05       0
Bank Sta=5004.4,5010.4
Exp/Cntr=0.3,0.1

Type RM Length L Ch R = 1,2744,830,830,830
BEGIN DESCRIPTION:
Mapping XS 28956867
END DESCRIPTION:
XS GIS Cut Line= 3
      3531333.01     10617524.39      3531163.72     10617089.45
      3530780.95     10616922.80
#Sta/Elev= 30
  4463.7  426.70  4607.7  424.38  4659.1  424.16  4672.1  424.17  4678.7  423.12
  4706.9  422.22  4762.9  420.85  4773.7  419.77  4822.7  416.36  4847.2  415.42
  4854.5  413.73  4908.2  413.98  4940.7  413.39  4964.2  413.90  4997.3  411.92
  5000.1  411.42  5003.3  411.92  5011.0  413.30  5063.3  414.77  5098.5  416.43
  5117.4  418.03  5139.1  420.13  5185.8  421.54  5207.6  423.44  5243.7  424.60
  5251.2  425.62  5267.2  425.74  5290.6  427.85  5319.5  428.81  5347.9  430.81
#Mann=7,-1,0
  4463.7    0.05       0  4659.1    0.16       0  4706.9    0.05       0
  4773.7    0.12       0  4997.3    0.07       0  5003.3    0.12       0
  5117.4    0.05       0
Bank Sta=4997.3,5003.3
Exp/Cntr=0.3,0.1

Type RM Length L Ch R = 1,1914,0,0,0
BEGIN DESCRIPTION:
UNT093 IN CCTC 1.0
END DESCRIPTION:
XS GIS Cut Line= 4
      3531585.62     10617446.19      3531861.64     10617092.06
      3531872.05     10616875.91      3531070.02     10616805.60
#Sta/Elev= 30
  4476.4  424.09  4598.1  419.74  4640.0  419.00  4648.1  418.01  4697.8  416.55
  4762.6  413.36  4763.0  413.34  4832.6  410.15  4889.7  408.87  4984.7  409.41
  4989.7  409.25  4994.3  407.24  4997.1  406.74  5000.3  407.24  5007.4  409.10
  5037.4  408.37  5087.5  408.75  5136.3  407.69  5385.2  408.74  5425.3  409.61
  5497.1  409.17  5535.7  409.64  5555.8  410.71  5565.9  409.94  5609.6  410.25
  5626.1  412.12  5706.4  415.54  5736.5  417.74  5826.9  417.96  5946.9  420.54
#Mann=6,-1,0
  4476.4    0.05       0  4762.6    0.16       0  4763.0    0.12       0
  4994.3    0.07       0  5000.3    0.12       0  5136.3    0.05       0
Bank Sta=4994.3,5000.3
Exp/Cntr=0.3,0.1

Chan Stop Cuts=-1