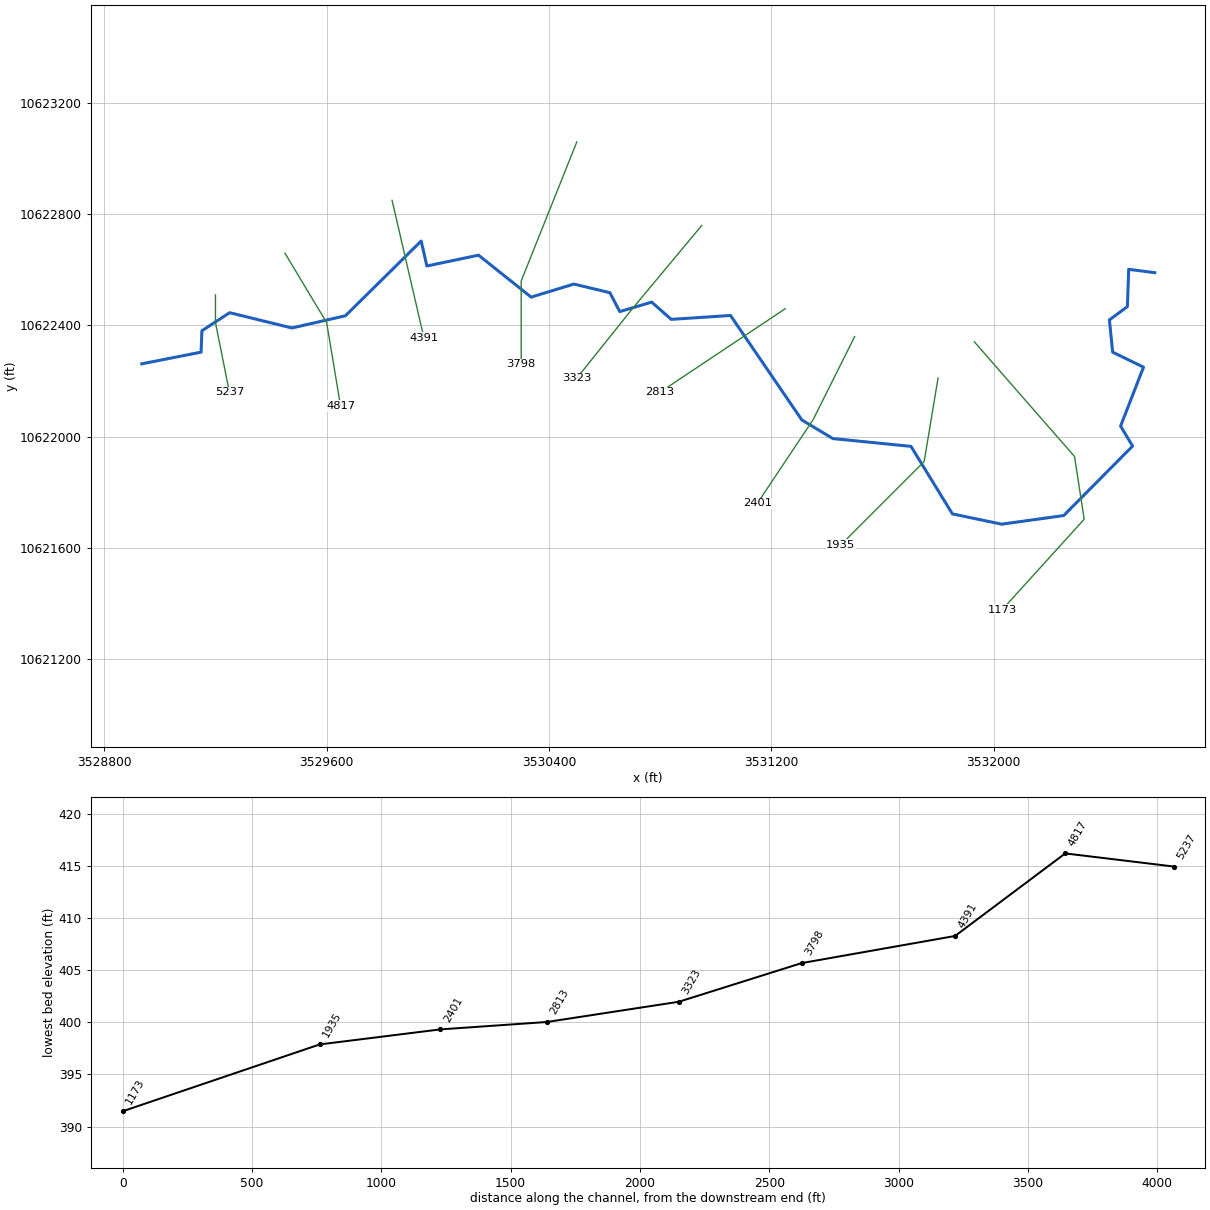
--- UNT095 IN CCTC.prj (project) ---

Proj Title=UNT095 IN CCTC Base Level Engineering
Current Plan=p01
Default Exp/Contr=0.3,0.1
English Units
Geom File=g01
Flow File=f01
Plan File=p01
Y Axis Title=Elevation
X Axis Title(PF)=Main Channel Distance
X Axis Title(XS)=Station
BEGIN DESCRIPTION:
UNT095 IN CCTC
END DESCRIPTION:
DSS Export Rating Curves= 0
DSS Export Rating Curve Sorted= 0
DSS Export Volume Flow Curves= 0
DXF OffsetX= 0
DXF OffsetY= 0
DXF ScaleX= 1
DXF ScaleY= 10

--- UNT095 IN CCTC.p01 (plan) ---

Plan Title=Multiple Run
Short Identifier=Multiple
Geom File=g01
Flow File=f01
Subcritical Flow
K Sum by GR= 0
Std Step Tol= 0.01
Critical Tol= 0.01
Num of Std Step Trials= 20
Max Error Tol= 0.3
Flow Tol Ratio= 0.001
Split Flow NTrial= 30
Split Flow Tol= 0.02
Split Flow Ratio= 0.02
Log Output Level= 0
Friction Slope Method= 1
Unsteady Friction Slope Method= 2
Unsteady Bridges Friction Slope Method= 1
Parabolic Critical Depth
Global Vel Dist=  1 , 1 , 1
Global Log Level= 0
CheckData=True
Encroach Param= -1, 0, 0, 0
BEGIN DESCRIPTION:
Multiple Run
END DESCRIPTION:

--- UNT095 IN CCTC.f01 (steady flow) ---

Flow Title=Multiple
Number of Profiles=7
Profile Names=10-year,25-year,50-year,1pct_min,100-year,1pct_plu,500-year
River Rch & RM= UNT095 IN CCTC,Reach-1,5237
    1060    1436    1742    1543    2086    2821    2982
Boundary for River Rch & Prof#=UNT095 IN CCTC,Reach-1,1
Up Type=0
Dn Type=3
Dn Slope=0.005
Boundary for River Rch & Prof#=UNT095 IN CCTC,Reach-1,2
Up Type=0
Dn Type=3
Dn Slope=0.005
Boundary for River Rch & Prof#=UNT095 IN CCTC,Reach-1,3
Up Type=0
Dn Type=3
Dn Slope=0.005
Boundary for River Rch & Prof#=UNT095 IN CCTC,Reach-1,4
Up Type=0
Dn Type=3
Dn Slope=0.005
Boundary for River Rch & Prof#=UNT095 IN CCTC,Reach-1,5
Up Type=0
Dn Type=3
Dn Slope=0.005
Boundary for River Rch & Prof#=UNT095 IN CCTC,Reach-1,6
Up Type=0
Dn Type=3
Dn Slope=0.005
Boundary for River Rch & Prof#=UNT095 IN CCTC,Reach-1,7
Up Type=0
Dn Type=3
Dn Slope=0.005

--- UNT095 IN CCTC.g01 (geometry) ---

Geom Title=Existing Conditions

River Reach=UNT095 IN CCTC,Reach-1
Reach XY= 30
      3528934.50     10622262.00      3529147.75     10622304.00
      3529150.75     10622381.00      3529250.50     10622446.00
      3529474.50     10622391.00      3529667.25     10622435.00
      3529939.75     10622704.00      3529960.25     10622614.00
      3530146.00     10622653.00      3530335.50     10622502.00
      3530489.25     10622549.00      3530618.75     10622518.00
      3530654.25     10622450.00      3530769.25     10622484.00
      3530839.50     10622422.00      3531052.75     10622436.00
      3531309.50     10622060.00      3531421.25     10621993.00
      3531702.25     10621965.00      3531851.25     10621722.00
      3532028.25     10621685.00      3532251.75     10621716.00
      3532499.75     10621966.00      3532456.50     10622038.00
      3532539.00     10622250.00      3532428.00     10622304.00
      3532416.25     10622420.00      3532481.00     10622468.00
      3532485.75     10622602.00      3532579.50     10622590.00

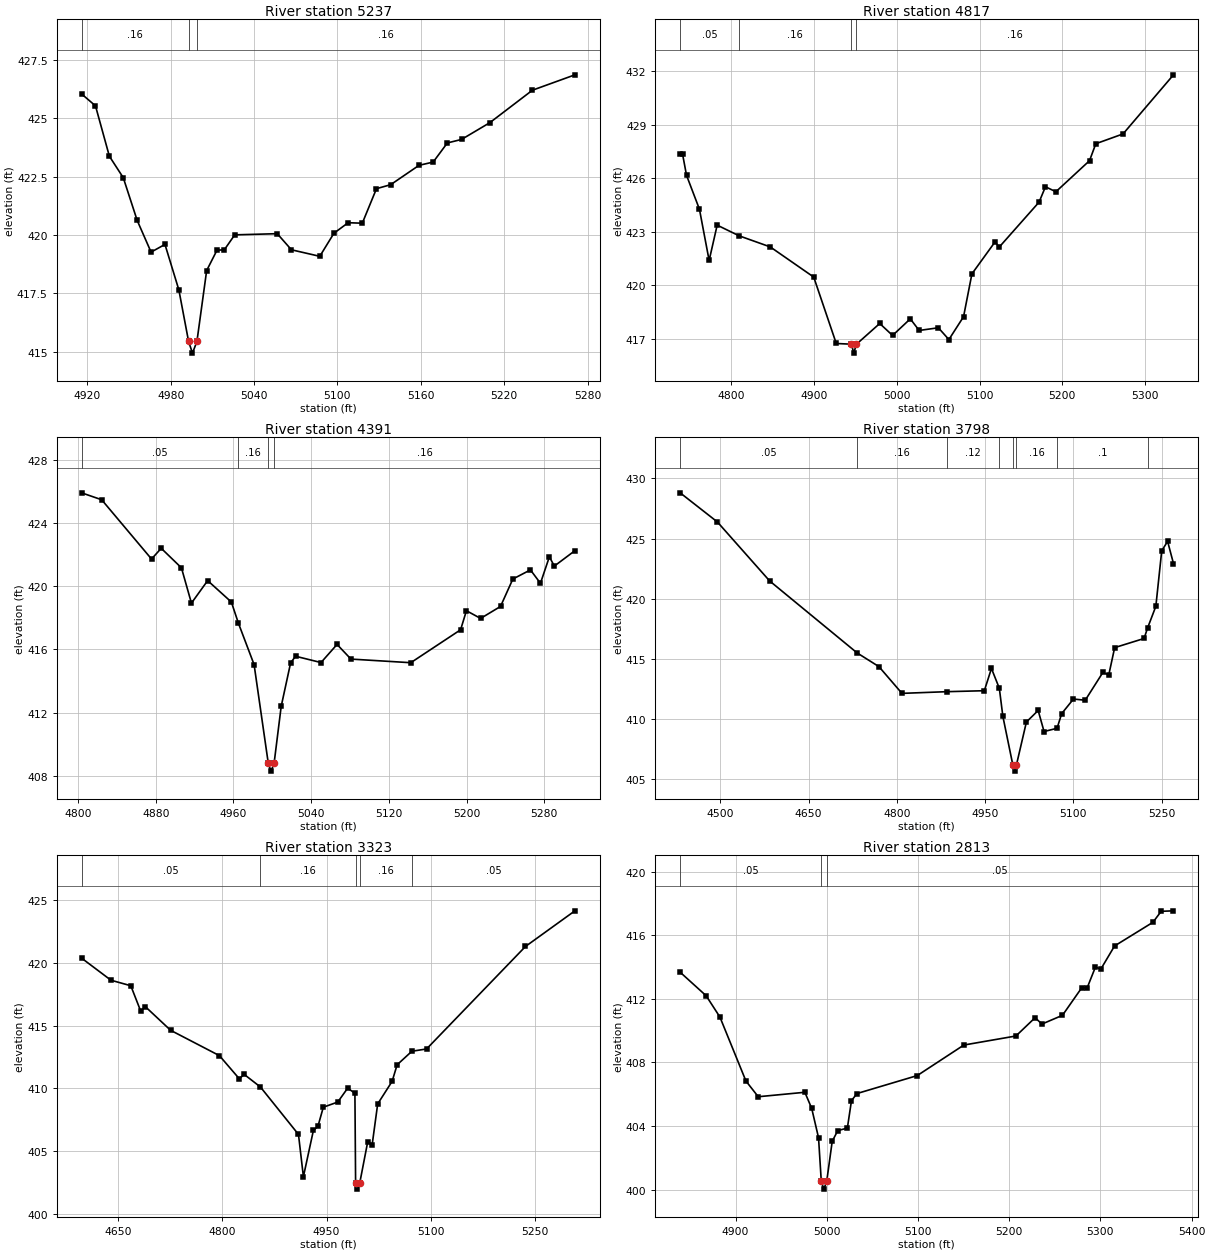
Type RM Length L Ch R = 1,5237,420,420,420
BEGIN DESCRIPTION:
UNT095 IN CCTC 9.0
END DESCRIPTION:
XS GIS Cut Line= 3
      3529199.61     10622510.22      3529199.61     10622410.19
      3529249.61     10622160.17
#Sta/Elev= 30
  4915.9  426.05  4925.9  425.54  4935.9  423.38  4945.9  422.46  4955.9  420.63
  4965.9  419.27  4975.9  419.60  4985.9  417.65  4992.9  415.44  4995.7  414.94
  4998.9  415.44  5005.9  418.48  5013.4  419.36  5018.5  419.36  5026.1  420.01
  5056.7  420.06  5066.9  419.37  5087.3  419.09  5097.5  420.08  5107.7  420.53
  5117.9  420.51  5128.1  421.99  5138.3  422.16  5158.7  422.99  5168.9  423.13
  5179.1  423.95  5189.3  424.10  5209.7  424.82  5240.3  426.21  5270.9  426.87
#Mann=3,-1,0
  4915.9    0.16       0  4992.9    0.07       0  4998.9    0.16       0
Bank Sta=4992.9,4998.9
Exp/Cntr=0.3,0.1

Type RM Length L Ch R = 1,4817,426,426,426
BEGIN DESCRIPTION:
UNT095 IN CCTC 8.0
END DESCRIPTION:
XS GIS Cut Line= 3
      3529449.62     10622660.16      3529599.61     10622410.19
      3529649.62     10622110.14
#Sta/Elev= 30
  4738.5  427.35  4741.4  427.35  4746.2  426.16  4761.8  424.26  4773.5  421.39
  4783.2  423.37  4809.8  422.77  4847.3  422.15  4899.8  420.46  4927.0  416.74
  4945.4  416.70  4948.1  416.20  4951.4  416.70  4979.5  417.86  4995.0  417.19
  5016.4  418.12  5027.1  417.47  5050.3  417.62  5063.0  416.96  5080.7  418.24
  5090.8  420.64  5118.7  422.43  5123.8  422.14  5171.9  424.66  5179.6  425.52
  5192.2  425.24  5232.8  426.98  5240.4  427.93  5273.3  428.48  5334.2  431.79
#Mann=4,-1,0
  4738.5    0.05       0  4809.8    0.16       0  4945.4    0.07       0
  4951.4    0.16       0
Bank Sta=4945.4,4951.4
Exp/Cntr=0.3,0.1

Type RM Length L Ch R = 1,4391,593,593,593
BEGIN DESCRIPTION:
UNT095 IN CCTC 7.0
END DESCRIPTION:
XS GIS Cut Line= 2
      3529835.03     10622850.37      3529949.62     10622355.57
#Sta/Elev= 30
  4803.7  425.94  4824.4  425.50  4875.7  421.74  4885.7  422.42  4906.5  421.18
  4916.8  418.94  4933.5  420.37  4957.9  419.01  4965.2  417.66  4981.3  415.04
  4995.9  408.78  4998.7  408.28  5001.9  408.78  5009.2  412.39  5018.9  415.15
  5024.0  415.57  5050.2  415.17  5066.7  416.32  5081.0  415.39  5142.6  415.16
  5193.9  417.25  5199.9  418.46  5214.5  417.97  5235.0  418.73  5247.7  420.47
  5265.8  421.05  5276.1  420.20  5285.3  421.88  5290.4  421.29  5311.6  422.27
#Mann=4,-1,0
  4803.7    0.05       0  4965.2    0.16       0  4995.9    0.07       0
  5001.9    0.16       0
Bank Sta=4995.9,5001.9
Exp/Cntr=0.3,0.1

Type RM Length L Ch R = 1,3798,475,475,475
BEGIN DESCRIPTION:
UNT095 IN CCTC 6.0
END DESCRIPTION:
XS GIS Cut Line= 3
      3530499.61     10623060.19      3530299.61     10622560.19
      3530299.61     10622260.21
#Sta/Elev= 30
  4431.6  428.80  4494.9  426.38  4583.7  421.48  4732.4  415.50  4769.5  414.36
  4808.6  412.14  4884.6  412.28  4948.6  412.36  4960.7  414.21  4974.1  412.56
  4980.1  410.23  4997.1  406.18  4999.9  405.68  5003.1  406.18  5020.1  409.76
  5040.1  410.72  5050.1  408.97  5072.2  409.24  5080.1  410.46  5100.1  411.67
  5120.1  411.57  5150.1  413.88  5160.1  413.67  5170.1  415.94  5220.1  416.70
  5226.2  417.59  5240.1  419.37  5250.1  423.98  5260.1  424.77  5270.1  422.92
#Mann=8,-1,0
  4431.6    0.05       0  4732.4    0.16       0  4884.6    0.12       0
  4974.1    0.16       0  4997.1    0.07       0  5003.1    0.16       0
  5072.2     0.1       0  5226.2    0.05       0
Bank Sta=4997.1,5003.1
Exp/Cntr=0.3,0.1

Type RM Length L Ch R = 1,3323,510,510,510
BEGIN DESCRIPTION:
UNT095 IN CCTC 5.0
END DESCRIPTION:
XS GIS Cut Line= 3
      3530949.59     10622760.16      3530699.61     10622460.19
      3530499.63     10622210.22
#Sta/Elev= 30
  4597.2  420.38  4639.5  418.62  4668.1  418.18  4682.4  416.15  4688.9  416.52
  4725.4  414.63  4795.7  412.61  4824.3  410.77  4831.5  411.11  4854.8  410.11
  4909.6  406.33  4916.7  402.96  4931.1  406.65  4937.6  406.97  4945.4  408.50
  4966.2  408.91  4980.5  410.02  4990.9  409.61  4991.9  402.47  4994.6  401.97
  4997.9  402.47  5009.3  405.73  5015.7  405.49  5023.7  408.76  5044.5  410.56
  5051.7  411.88  5073.0  412.96  5094.1  413.14  5236.6  421.31  5307.8  424.15
#Mann=5,-1,0
  4597.2    0.05       0  4854.8    0.16       0  4991.9    0.07       0
  4997.9    0.16       0  5073.0    0.05       0
Bank Sta=4991.9,4997.9
Exp/Cntr=0.3,0.1

Type RM Length L Ch R = 1,2813,412,412,412
BEGIN DESCRIPTION:
UNT095 IN CCTC 4.0
END DESCRIPTION:
XS GIS Cut Line= 3
      3531249.60     10622460.18      3531099.61     10622360.19
      3530799.63     10622160.20
#Sta/Elev= 30
  4839.3  413.67  4867.8  412.19  4882.9  410.85  4911.4  406.83  4924.9  405.84
  4976.0  406.12  4983.5  405.11  4991.0  403.26  4994.0  400.53  4996.8  400.03
  5000.0  400.53  5006.0  403.04  5012.1  403.71  5022.6  403.87  5027.1  405.59
  5033.1  406.04  5099.2  407.17  5150.3  409.09  5207.4  409.66  5228.4  410.81
  5235.9  410.41  5258.4  410.96  5279.5  412.69  5285.5  412.69  5294.5  413.99
  5300.5  413.87  5315.5  415.32  5357.6  416.81  5366.6  417.50  5380.1  417.53
#Mann=3,-1,0
  4839.3    0.05       0  4994.0   0.035       0  5000.0    0.05       0
Bank Sta=4994,5000
Exp/Cntr=0.3,0.1

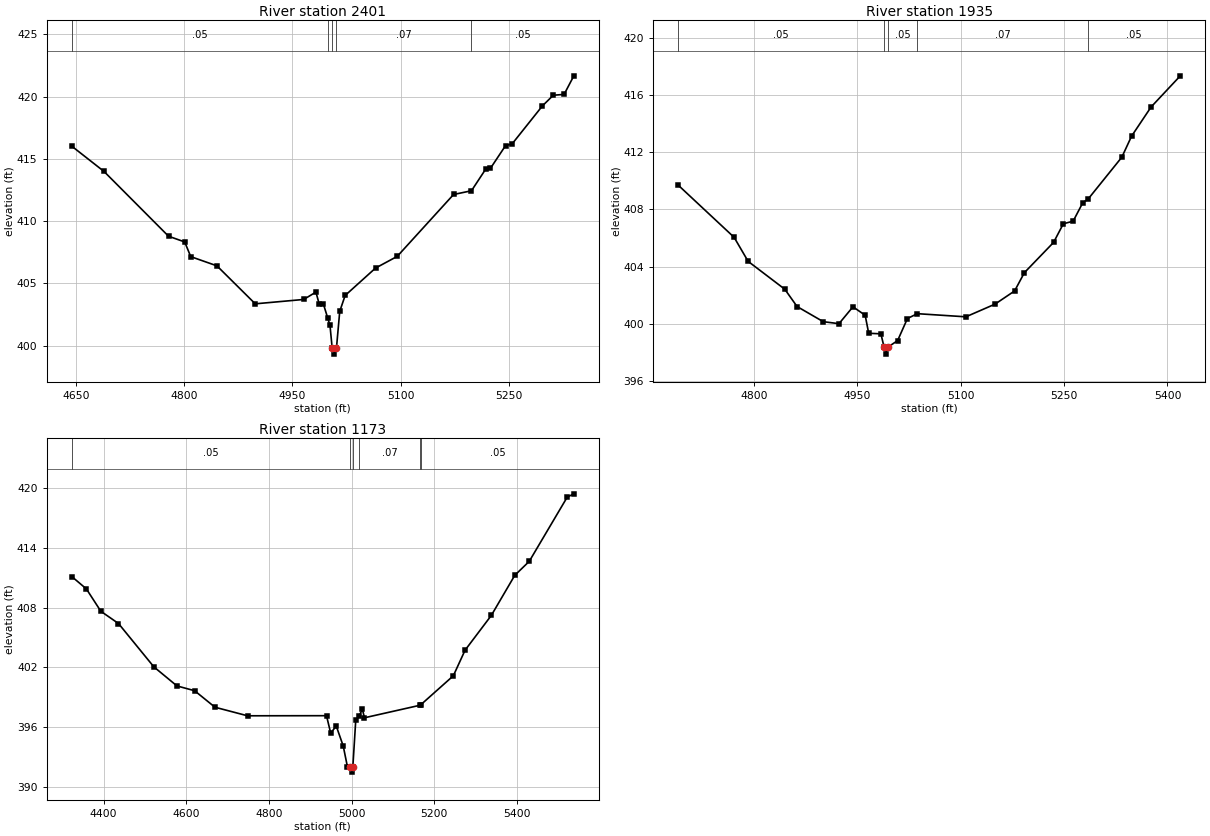
Type RM Length L Ch R = 1,2401,466,466,466
BEGIN DESCRIPTION:
UNT095 IN CCTC 3.0
END DESCRIPTION:
XS GIS Cut Line= 3
      3531499.59     10622360.16      3531349.61     10622060.19
      3531149.63     10621760.22
#Sta/Elev= 30
  4644.2  416.02  4688.9  413.99  4778.3  408.79  4800.7  408.33  4809.1  407.15
  4845.4  406.41  4898.5  403.36  4965.6  403.71  4982.6  404.30  4987.1  403.36
  4993.1  403.32  4999.0  402.21  5002.1  401.63  5005.1  399.82  5007.9  399.32
  5011.1  399.82  5015.6  402.75  5023.1  404.03  5065.2  406.23  5095.3  407.17
  5173.4  412.14  5198.2  412.44  5218.4  414.22  5224.5  414.24  5245.5  416.07
  5254.5  416.20  5296.6  419.26  5311.6  420.11  5326.6  420.18  5340.1  421.67
#Mann=5,-1,0
  4644.2    0.05       0  4999.0    0.07       0  5005.1    0.07       0
  5011.1    0.07       0  5198.2    0.05       0
Bank Sta=5005.1,5011.1
Exp/Cntr=0.3,0.1

Type RM Length L Ch R = 1,1935,762,762,762
BEGIN DESCRIPTION:
UNT095 IN CCTC 2.0
END DESCRIPTION:
XS GIS Cut Line= 3
      3531799.62     10622210.23      3531749.61     10621910.19
      3531449.64     10621610.22
#Sta/Elev= 30
  4690.2  409.70  4771.3  406.05  4791.6  404.37  4844.8  402.42  4862.6  401.21
  4900.6  400.15  4923.4  400.01  4943.7  401.19  4961.4  400.60  4966.5  399.34
  4984.2  399.30  4988.8  398.38  4991.6  397.88  4994.8  398.38  5008.5  398.83
  5022.7  400.37  5037.0  400.71  5107.5  400.49  5149.9  401.38  5178.2  402.30
  5192.4  403.58  5234.8  405.70  5248.9  407.00  5263.1  407.18  5277.2  408.48
  5284.7  408.72  5333.8  411.66  5347.9  413.13  5376.2  415.17  5418.6  417.35
#Mann=5,-1,0
  4690.2    0.05       0  4988.8   0.035       0  4994.8    0.05       0
  5037.0    0.07       0  5284.7    0.05       0
Bank Sta=4988.8,4994.8
Exp/Cntr=0.3,0.1

Type RM Length L Ch R = 1,1173,0,0,0
BEGIN DESCRIPTION:
UNT095 IN CCTC 1.0
END DESCRIPTION:
XS GIS Cut Line= 4
      3531930.53     10622340.80      3532290.77     10621928.48
      3532325.49     10621702.79      3532030.32     10621377.24
#Sta/Elev= 30
  4322.8  411.12  4358.1  409.88  4393.2  407.63  4435.9  406.40  4521.4  402.05
  4577.4  400.13  4620.1  399.65  4669.4  397.99  4748.2  397.13  4939.4  397.14
  4949.5  395.39  4963.0  396.10  4979.9  394.09  4990.0  392.02  4997.1  391.97
  4999.9  391.47  5003.1  391.97  5010.2  396.69  5018.2  397.11  5026.3  397.78
  5031.3  396.93  5164.8  398.18  5168.2  398.26  5246.4  401.15  5274.8  403.72
  5338.3  407.21  5395.1  411.24  5430.2  412.65  5522.1  419.10  5538.1  419.43
#Mann=6,-1,0
  4322.8    0.05       0  4997.1   0.035       0  5003.1    0.05       0
  5018.2    0.07       0  5164.8    0.12       0  5168.2    0.05       0
Bank Sta=4997.1,5003.1
Exp/Cntr=0.3,0.1

Chan Stop Cuts=-1