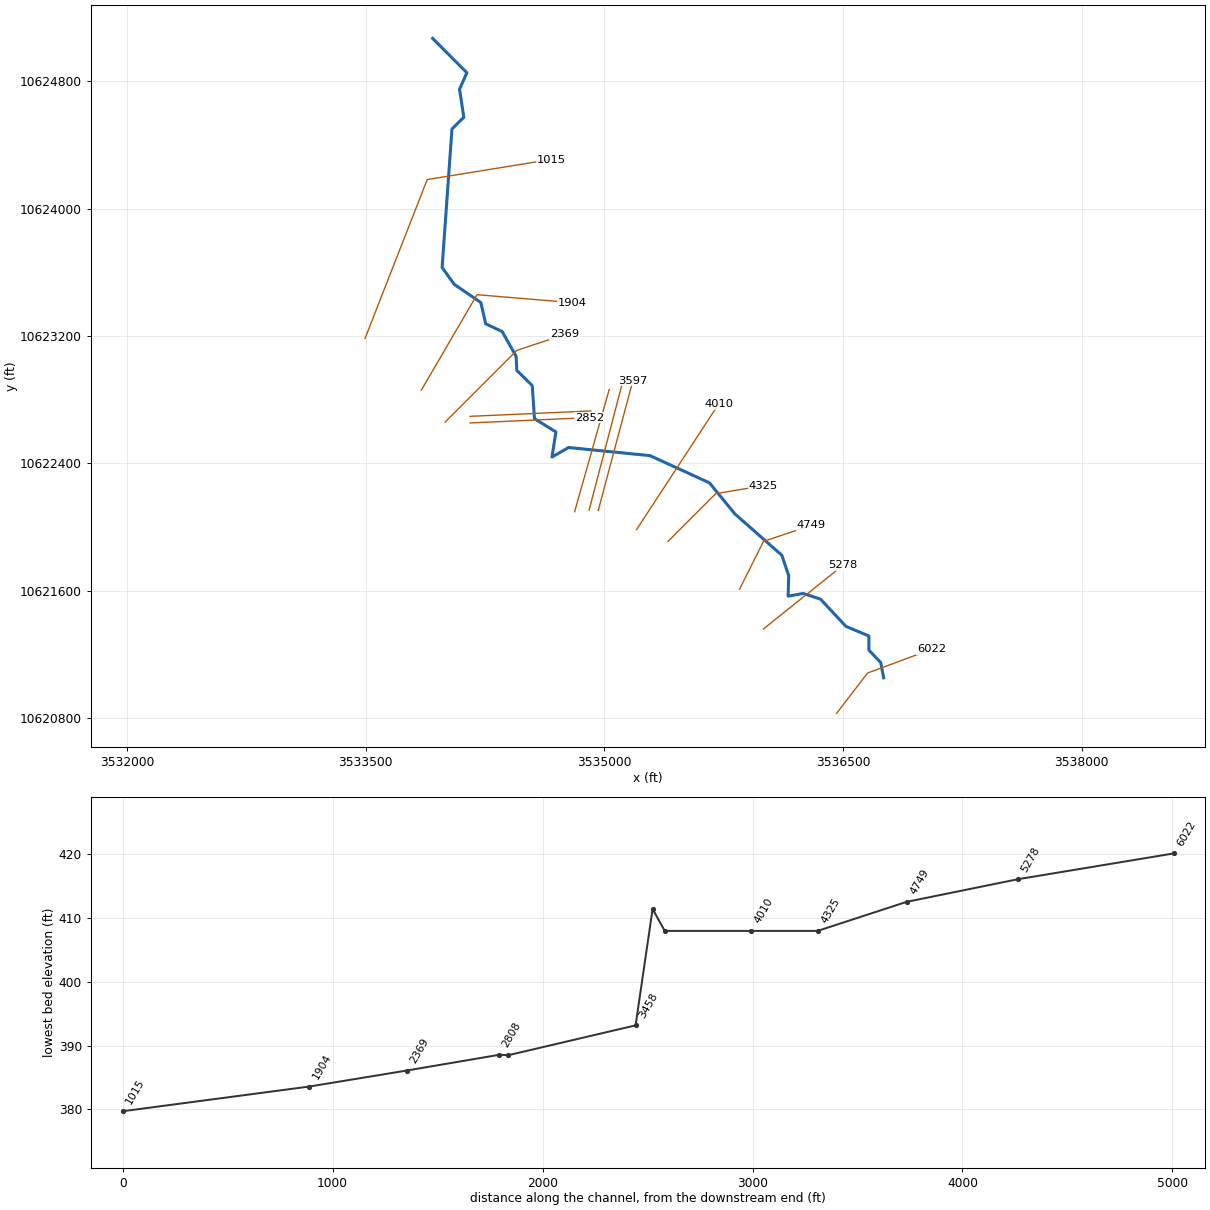
--- UNT096 IN CCTC.prj (project) ---

Proj Title=UNT096 IN CCTC Base Level Engineering
Current Plan=p01
Default Exp/Contr=0.3,0.1
English Units
Geom File=g01
Flow File=f01
Plan File=p01
BEGIN DESCRIPTION:
UNT096 IN CCTC
END DESCRIPTION:

--- UNT096 IN CCTC.p01 (plan) ---

Plan Title=Multiple Run
Short Identifier=Multiple
Geom File=g01
Flow File=f01
Subcritical Flow
K Sum by GR= 0
Std Step Tol= 0.01
Critical Tol= 0.01
Num of Std Step Trials= 20
Max Error Tol= 0.3
Flow Tol Ratio= 0.001
Split Flow NTrial= 30
Split Flow Tol= 0.02
Split Flow Ratio= 0.02
Log Output Level= 0
Friction Slope Method= 1
Unsteady Friction Slope Method= 2
Unsteady Bridges Friction Slope Method= 1
Parabolic Critical Depth
Global Vel Dist=  1 , 1 , 1
Global Log Level= 0
CheckData=True
Encroach Param= -1, 0, 0, 0
BEGIN DESCRIPTION:
Multiple Run
END DESCRIPTION:

--- UNT096 IN CCTC.f01 (steady flow) ---

Flow Title=Multiple
Number of Profiles=7
Profile Names=10-year,25-year,50-year,1pct_min,100-year,1pct_plu,500-year
River Rch & RM= UNT096 IN CCTC,Reach-1,6022
    1317    1807    2211    1974    2670    3611    3880
Boundary for River Rch & Prof#=UNT096 IN CCTC,Reach-1,1
Up Type=0
Dn Type=3
Dn Slope=0.005
Boundary for River Rch & Prof#=UNT096 IN CCTC,Reach-1,2
Up Type=0
Dn Type=3
Dn Slope=0.005
Boundary for River Rch & Prof#=UNT096 IN CCTC,Reach-1,3
Up Type=0
Dn Type=3
Dn Slope=0.005
Boundary for River Rch & Prof#=UNT096 IN CCTC,Reach-1,4
Up Type=0
Dn Type=3
Dn Slope=0.005
Boundary for River Rch & Prof#=UNT096 IN CCTC,Reach-1,5
Up Type=0
Dn Type=3
Dn Slope=0.005
Boundary for River Rch & Prof#=UNT096 IN CCTC,Reach-1,6
Up Type=0
Dn Type=3
Dn Slope=0.005
Boundary for River Rch & Prof#=UNT096 IN CCTC,Reach-1,7
Up Type=0
Dn Type=3
Dn Slope=0.005

--- UNT096 IN CCTC.g01 (geometry) ---

Geom Title=Existing Conditions

River Reach=UNT096 IN CCTC,Reach-1
Reach XY= 30
      3536754.75     10621053.00      3536736.00     10621149.00
      3536662.00     10621227.00      3536661.75     10621316.00
      3536517.75     10621376.00      3536358.25     10621547.00
      3536248.50     10621583.00      3536154.50     10621566.00
      3536158.00     10621695.00      3536114.75     10621823.00
      3535819.75     10622083.00      3535660.00     10622278.00
      3535286.75     10622449.00      3534775.00     10622500.00
      3534670.50     10622440.00      3534695.50     10622598.00
      3534560.75     10622681.00      3534546.50     10622889.00
      3534449.50     10622985.00      3534445.25     10623073.00
      3534357.25     10623229.00      3534254.25     10623277.00
      3534223.50     10623411.00      3534056.75     10623525.00
      3533980.25     10623631.00      3534042.25     10624501.00
      3534116.75     10624575.00      3534089.75     10624751.00
      3534136.00     10624855.00      3533920.50     10625071.00

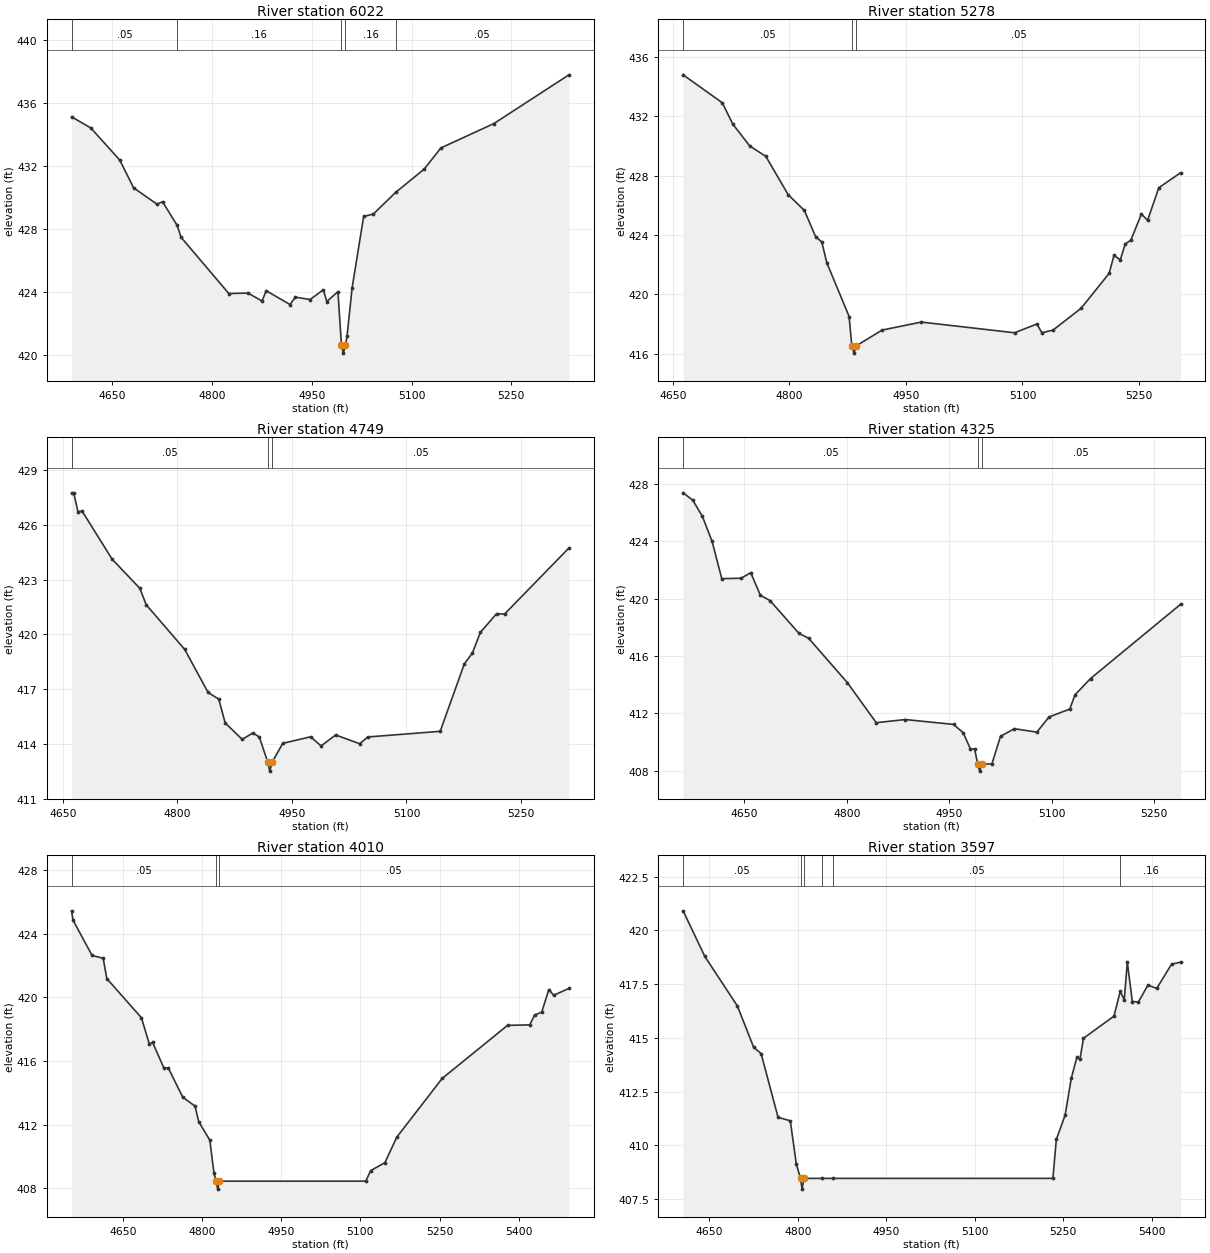
Type RM Length L Ch R = 1,6022,744,744,744
BEGIN DESCRIPTION:
UNT096 IN CCTC 10.0
END DESCRIPTION:
XS GIS Cut Line= 3
      3536459.01     10620829.52      3536653.47     10621083.01
      3537055.46     10621232.02
#Sta/Elev= 30
  4588.5  435.13  4617.5  434.42  4661.0  432.38  4681.9  430.61  4717.2  429.57
  4725.4  429.73  4747.4  428.22  4753.2  427.47  4825.1  423.89  4854.0  423.92
  4875.0  423.41  4881.3  424.07  4917.1  423.19  4925.2  423.66  4947.4  423.51
  4967.2  424.13  4972.5  423.38  4989.2  424.01  4994.5  420.60  4997.3  420.10
  5000.5  420.60  5002.9  421.17  5010.5  424.24  5027.9  428.79  5042.5  428.95
  5076.0  430.32  5119.1  431.81  5144.1  433.15  5223.8  434.70  5336.7  437.80
#Mann=5,-1,0
  4588.5    0.05       0  4747.4    0.16       0  4994.5    0.07       0
  5000.5    0.16       0  5076.0    0.05       0
Bank Sta=4994.5,5000.5
Exp/Cntr=0.3,0.1

Type RM Length L Ch R = 1,5278,529,529,529
BEGIN DESCRIPTION:
UNT096 IN CCTC 9.0
END DESCRIPTION:
XS GIS Cut Line= 3
      3535999.60     10621360.18      3536249.61     10621560.19
      3536499.59     10621760.18
#Sta/Elev= 30
  4663.2  434.78  4713.6  432.90  4727.2  431.46  4748.8  430.00  4769.7  429.29
  4798.5  426.71  4819.3  425.65  4833.7  423.89  4841.7  423.53  4848.1  422.14
  4876.9  418.51  4880.3  416.55  4883.1  416.05  4886.3  416.55  4919.3  417.60
  4969.8  418.14  5089.8  417.42  5118.6  418.01  5125.0  417.42  5139.4  417.60
  5175.5  419.07  5211.5  421.41  5217.9  422.64  5225.9  422.32  5232.3  423.40
  5239.5  423.65  5253.1  425.41  5261.1  424.99  5275.5  427.18  5303.5  428.19
#Mann=3,-1,0
  4663.2    0.05       0  4880.3    0.03       0  4886.3    0.05       0
Bank Sta=4880.3,4886.3
Exp/Cntr=0.3,0.1

Type RM Length L Ch R = 1,4749,424,424,424
BEGIN DESCRIPTION:
UNT096 IN CCTC 8.0
END DESCRIPTION:
XS GIS Cut Line= 3
      3535849.60     10621610.17      3535999.61     10621910.19
      3536299.65     10622010.20
#Sta/Elev= 30
  4661.2  427.75  4664.0  427.75  4669.6  426.72  4675.2  426.74  4714.3  424.12
  4750.7  422.52  4759.0  421.62  4809.4  419.18  4840.1  416.82  4854.1  416.45
  4862.5  415.15  4884.8  414.25  4898.8  414.60  4907.2  414.38  4918.2  413.01
  4920.9  412.51  4924.2  413.01  4937.9  414.03  4974.3  414.39  4988.2  413.89
  5007.2  414.49  5038.8  414.01  5049.3  414.38  5144.2  414.69  5175.8  418.38
  5186.4  418.98  5196.9  420.11  5218.0  421.13  5228.5  421.11  5312.9  424.73
#Mann=3,-1,0
  4661.2    0.05       0  4918.2    0.03       0  4924.2    0.05       0
Bank Sta=4918.2,4924.2
Exp/Cntr=0.3,0.1

Type RM Length L Ch R = 1,4325,315,315,315
BEGIN DESCRIPTION:
UNT096 IN CCTC 7.0
END DESCRIPTION:
XS GIS Cut Line= 3
      3535399.61     10621910.19      3535699.61     10622210.19
      3535999.61     10622260.19
#Sta/Elev= 30
  4560.2  427.38  4574.3  426.87  4588.5  425.73  4602.6  423.99  4616.8  421.39
  4645.1  421.42  4659.2  421.81  4673.3  420.23  4687.5  419.86  4729.9  417.57
  4744.0  417.23  4800.6  414.14  4843.0  411.34  4885.5  411.56  4956.2  411.22
  4970.3  410.64  4980.9  409.51  4987.0  409.51  4991.6  408.46  4994.4  407.96
  4997.6  408.46  5012.3  408.46  5025.0  410.39  5045.3  410.92  5078.2  410.68
  5096.0  411.74  5126.4  412.29  5134.0  413.28  5156.8  414.42  5288.6  419.60
#Mann=3,-1,0
  4560.2    0.05       0  4991.6    0.03       0  4997.6    0.05       0
Bank Sta=4991.6,4997.6
Exp/Cntr=0.3,0.1

Type RM Length L Ch R = 1,4010,413,413,413
BEGIN DESCRIPTION:
UNT096 IN CCTC 6.0
END DESCRIPTION:
XS GIS Cut Line= 2
      3535202.22     10621984.30      3535717.85     10622773.37
#Sta/Elev= 30
  4552.6  425.43  4555.3  424.85  4591.5  422.63  4612.6  422.45  4619.4  421.18
  4685.0  418.72  4700.1  417.06  4706.1  417.18  4727.2  415.59  4736.3  415.54
  4763.4  413.73  4786.6  413.17  4793.6  412.20  4814.7  411.03  4822.4  408.99
  4826.8  408.46  4829.5  407.96  4832.8  408.46  5110.2  408.46  5119.4  409.12
  5146.4  409.62  5168.9  411.22  5255.0  414.91  5378.8  418.24  5420.9  418.27
  5430.1  418.89  5443.6  419.07  5457.1  420.49  5466.3  420.13  5495.2  420.56
#Mann=3,-1,0
  4552.6    0.05       0  4826.8   0.033       0  4832.8    0.05       0
Bank Sta=4826.8,4832.8
Exp/Cntr=0.3,0.1

Type RM Length L Ch R = 1,3597,58,58,58
BEGIN DESCRIPTION:
Mapping XS 2e02bccf
END DESCRIPTION:
XS GIS Cut Line= 2
      3534961.29     10622104.76      3535178.75     10622919.13
#Sta/Elev= 30
  4605.8  420.91  4642.5  418.79  4697.8  416.48  4725.3  414.56  4737.9  414.27
  4766.7  411.30  4787.4  411.14  4797.7  409.11  4804.7  408.46  4807.4  407.96
  4810.7  408.46  4840.8  408.46  4860.3  408.46  5232.4  408.46  5238.2  410.27
  5253.1  411.40  5263.5  413.11  5273.1  414.10  5278.3  414.01  5284.2  414.98
  5335.9  416.01  5346.5  417.16  5353.3  416.77  5358.5  418.52  5367.0  416.69
  5377.3  416.67  5393.4  417.45  5408.4  417.30  5433.5  418.43  5448.7  418.52
#Mann=6,-1,0
  4605.8    0.05       0  4804.7    0.03       0  4810.7    0.05       0
  4840.8    0.16       0  4860.3    0.05       0  5346.5    0.16       0
Bank Sta=4804.7,4810.7
Exp/Cntr=0.3,0.1

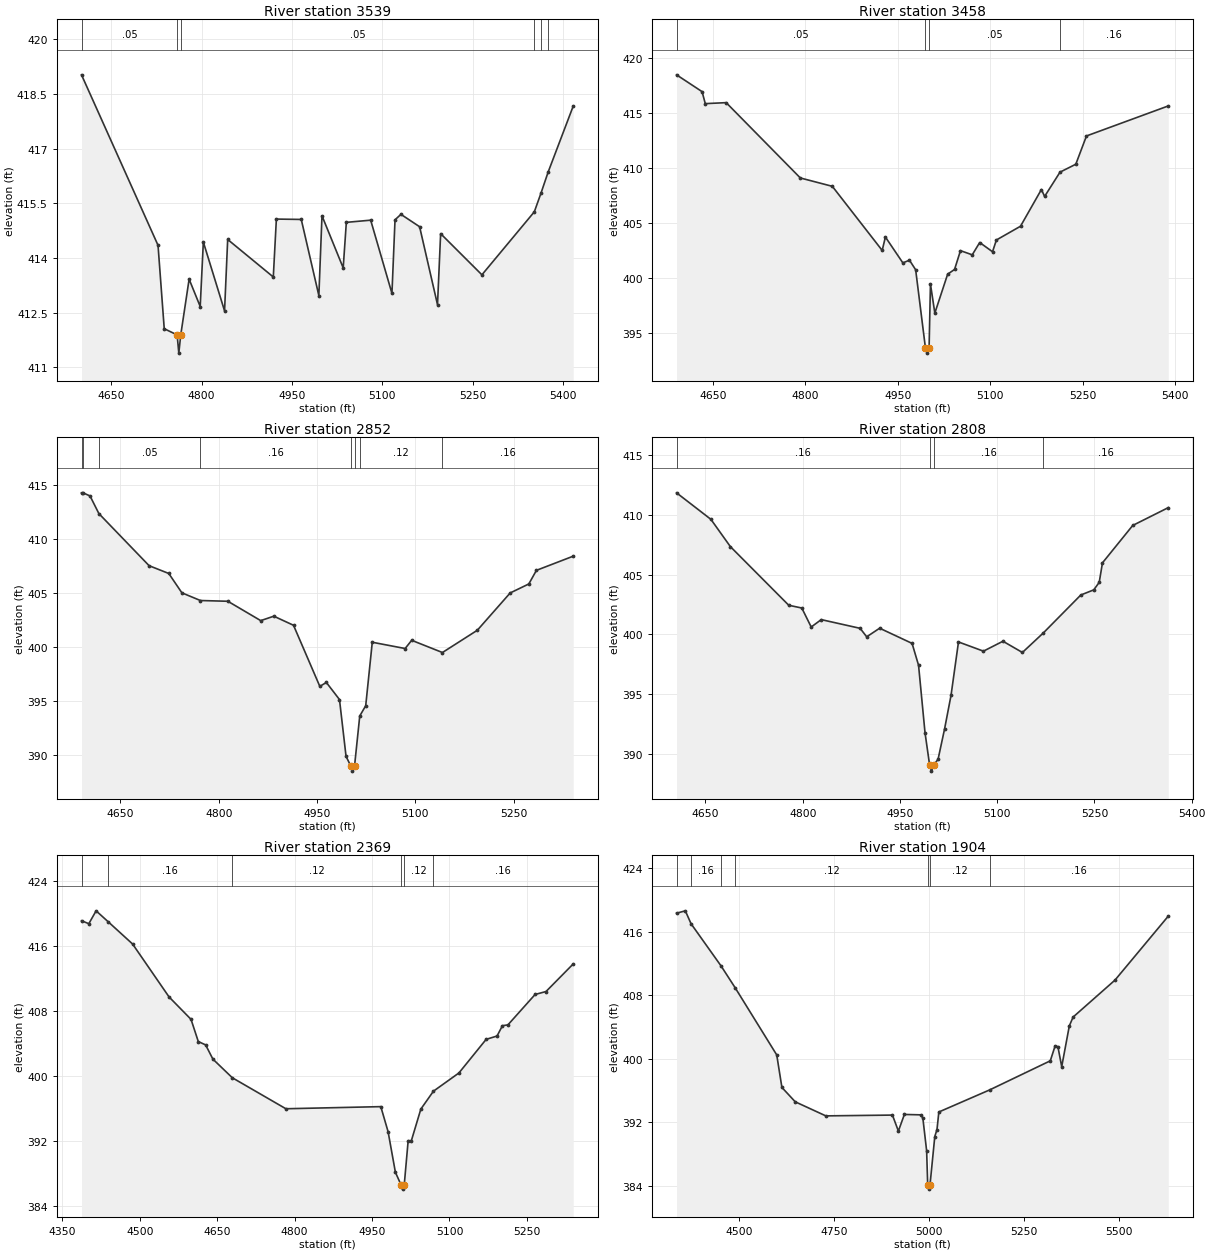
Type RM Length L Ch R = 1,3539,81,81,81
BEGIN DESCRIPTION:
Mapping XS faeb8539
END DESCRIPTION:
XS GIS Cut Line= 2
      3534904.00     10622107.36      3535110.65     10622896.76
#Sta/Elev= 30
  4600.6  419.03  4727.6  414.35  4737.9  412.06  4759.3  411.89  4762.1  411.39
  4765.3  411.89  4779.2  413.42  4797.6  412.67  4802.8  414.44  4838.0  412.55
  4843.2  414.51  4918.9  413.48  4924.0  415.07  4965.3  415.06  4994.5  412.97
  4999.7  415.16  5034.9  413.73  5040.1  414.98  5080.5  415.04  5115.8  413.03
  5120.9  415.05  5130.7  415.20  5161.7  414.86  5191.4  412.72  5196.6  414.67
  5265.1  413.54  5352.1  415.27  5363.1  415.78  5375.0  416.36  5416.6  418.17
#Mann=6,-1,0
  4600.6    0.05       0  4759.3    0.03       0  4765.3    0.05       0
  5352.1    0.16       0  5363.1    0.12       0  5375.0    0.16       0
Bank Sta=4759.3,4765.3
Exp/Cntr=0.3,0.1

Type RM Length L Ch R = 1,3458,606,606,606
BEGIN DESCRIPTION:
UNT096 IN CCTC 5.0
END DESCRIPTION:
XS GIS Cut Line= 2
      3534812.87     10622097.01      3535030.33     10622864.50
#Sta/Elev= 30
  4590.9  418.47  4632.3  416.94  4637.5  415.85  4671.4  415.94  4791.7  409.09
  4843.6  408.33  4924.5  402.50  4929.7  403.72  4958.0  401.37  4968.8  401.61
  4978.8  400.74  4994.6  393.66  4997.3  393.16  5000.6  393.66  5002.8  399.45
  5009.9  396.80  5030.7  400.34  5041.9  400.77  5051.5  402.48  5070.6  402.10
  5082.7  403.22  5103.5  402.38  5109.8  403.45  5148.9  404.70  5182.8  408.04
  5188.0  407.41  5213.0  409.62  5238.6  410.34  5255.9  412.91  5388.6  415.64
#Mann=4,-1,0
  4590.9    0.05       0  4994.6    0.03       0  5000.6    0.05       0
  5213.0    0.16       0
Bank Sta=4994.6,5000.6
Exp/Cntr=0.3,0.1

Type RM Length L Ch R = 1,2852,44,44,44
BEGIN DESCRIPTION:
UNT096 IN CCTC 4.0
END DESCRIPTION:
XS GIS Cut Line= 2
      3534156.62     10622654.27      3534905.66     10622688.08
#Sta/Elev= 30
  4590.8  414.23  4593.2  414.23  4603.8  413.94  4617.3  412.31  4693.9  407.49
  4723.9  406.77  4743.9  404.98  4772.1  404.27  4814.0  404.20  4864.1  402.41
  4884.1  402.82  4914.1  401.98  4954.2  396.33  4964.2  396.69  4984.2  395.11
  4994.2  389.86  5001.2  388.99  5004.0  388.49  5007.2  388.99  5015.1  393.59
  5024.2  394.54  5034.2  400.41  5084.3  399.83  5094.3  400.59  5141.2  399.46
  5194.4  401.52  5244.5  404.97  5272.9  405.80  5284.5  407.06  5340.6  408.37
#Mann=8,-1,0
  4590.8    0.05       0  4593.2    0.16       0  4617.3    0.05       0
  4772.1    0.16       0  5001.2    0.07       0  5007.2    0.16       0
  5015.1    0.12       0  5141.2    0.16       0
Bank Sta=5001.2,5007.2
Exp/Cntr=0.3,0.1

Type RM Length L Ch R = 1,2808,439,439,439
BEGIN DESCRIPTION:
Mapping XS 0d6bebc4
END DESCRIPTION:
XS GIS Cut Line= 2
      3534156.65     10622695.94      3534914.39     10622729.79
#Sta/Elev= 30
  4605.4  411.84  4658.4  409.62  4688.4  407.34  4778.5  402.43  4798.6  402.20
  4813.1  400.61  4828.6  401.23  4888.6  400.50  4898.7  399.79  4918.7  400.51
  4968.7  399.24  4978.7  397.41  4988.7  391.75  4995.8  389.05  4998.5  388.55
  5001.8  389.05  5008.8  389.54  5018.8  392.07  5028.8  394.89  5040.3  399.36
  5078.8  398.59  5108.9  399.42  5138.9  398.48  5171.1  400.11  5229.0  403.29
  5249.0  403.72  5257.4  404.35  5262.4  405.98  5309.1  409.11  5363.9  410.60
#Mann=4,-1,0
  4605.4    0.16       0  4995.8    0.07       0  5001.8    0.16       0
  5171.1    0.16       0
Bank Sta=4995.8,5001.8
Exp/Cntr=0.3,0.1

Type RM Length L Ch R = 1,2369,465,465,465
BEGIN DESCRIPTION:
UNT096 IN CCTC 3.0
END DESCRIPTION:
XS GIS Cut Line= 3
      3533999.58     10622660.16      3534449.61     10623110.19
      3534749.64     10623210.20
#Sta/Elev= 30
  4387.0  419.08  4401.2  418.72  4415.3  420.30  4438.8  418.95  4486.0  416.22
  4556.7  409.71  4599.2  406.96  4613.3  404.23  4627.5  403.82  4641.6  402.07
  4679.2  399.78  4783.0  395.97  4966.9  396.23  4981.0  393.16  4995.2  388.16
  5006.3  386.59  5009.0  386.09  5012.3  386.59  5019.9  392.04  5026.1  392.04
  5044.5  395.93  5068.9  398.13  5118.3  400.37  5171.0  404.50  5192.1  404.91
  5202.6  406.18  5213.2  406.28  5265.9  410.02  5287.0  410.38  5339.7  413.77
#Mann=6,-1,0
  4387.0    0.05       0  4438.8    0.16       0  4679.2    0.12       0
  5006.3    0.07       0  5012.3    0.12       0  5068.9    0.16       0
Bank Sta=5006.3,5012.3
Exp/Cntr=0.3,0.1

Type RM Length L Ch R = 1,1904,889,889,889
BEGIN DESCRIPTION:
UNT096 IN CCTC 2.0
END DESCRIPTION:
XS GIS Cut Line= 3
      3533849.61     10622860.19      3534199.61     10623460.19
      3534799.61     10623410.19
#Sta/Elev= 30
  4334.1  418.31  4357.2  418.61  4372.4  416.98  4451.5  411.67  4488.6  408.93
  4598.3  400.47  4611.9  396.38  4647.1  394.57  4727.7  392.80  4903.4  392.90
  4919.1  390.89  4934.9  392.98  4977.9  392.93  4983.6  392.53  4993.6  388.40
  4996.4  384.08  4999.1  383.58  5002.4  384.08  5015.1  390.20  5020.9  391.08
  5025.8  393.29  5159.4  396.06  5319.7  399.73  5332.3  401.59  5339.8  401.51
  5349.8  398.99  5369.9  404.13  5379.9  405.24  5490.3  409.89  5630.8  417.94
#Mann=7,-1,0
  4334.1    0.05       0  4372.4    0.16       0  4451.5    0.05       0
  4488.6    0.12       0  4996.4    0.07       0  5002.4    0.12       0
  5159.4    0.16       0
Bank Sta=4996.4,5002.4
Exp/Cntr=0.3,0.1

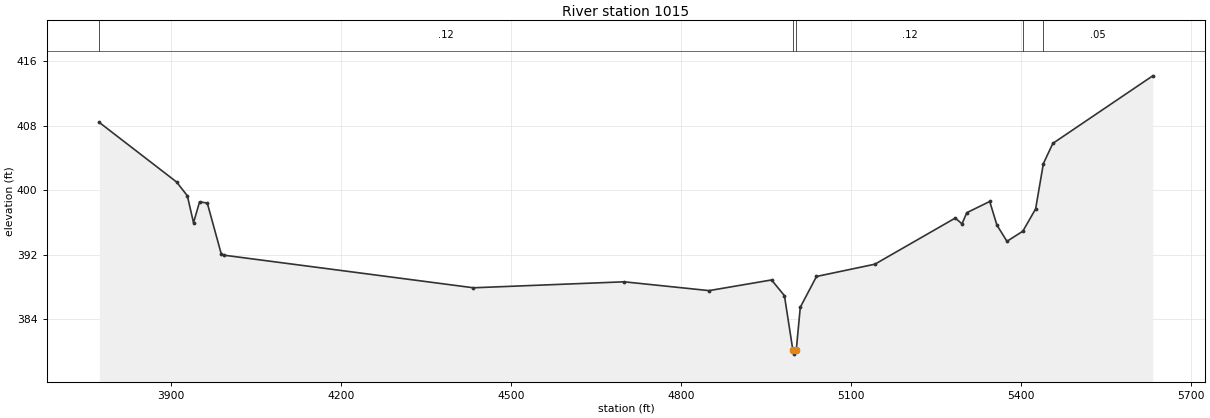
Type RM Length L Ch R = 1,1015,0,0,0
BEGIN DESCRIPTION:
UNT096 IN CCTC 1.0
END DESCRIPTION:
XS GIS Cut Line= 3
      3533496.10     10623185.41      3533886.74     10624183.70
      3534663.61     10624309.56
#Sta/Elev= 30
  3773.6  408.38  3909.8  401.02  3928.9  399.31  3939.8  395.97  3950.5  398.55
  3964.1  398.41  3988.6  392.15  3994.0  391.95  4433.8  387.92  4699.7  388.66
  4849.6  387.57  4959.9  388.89  4982.6  386.95  4997.5  380.21  5000.2  379.71
  5003.5  380.21  5010.6  385.51  5039.2  389.32  5142.3  390.84  5284.1  396.55
  5296.0  395.83  5304.4  397.21  5344.9  398.60  5357.6  395.68  5375.3  393.67
  5403.3  394.92  5425.9  397.68  5439.6  403.29  5456.3  405.79  5632.6  414.15
#Mann=5,-1,0
  3773.6    0.12       0  4997.5    0.07       0  5003.5    0.12       0
  5403.3    0.16       0  5439.6    0.05       0
Bank Sta=4997.5,5003.5
Exp/Cntr=0.3,0.1

Chan Stop Cuts=-1