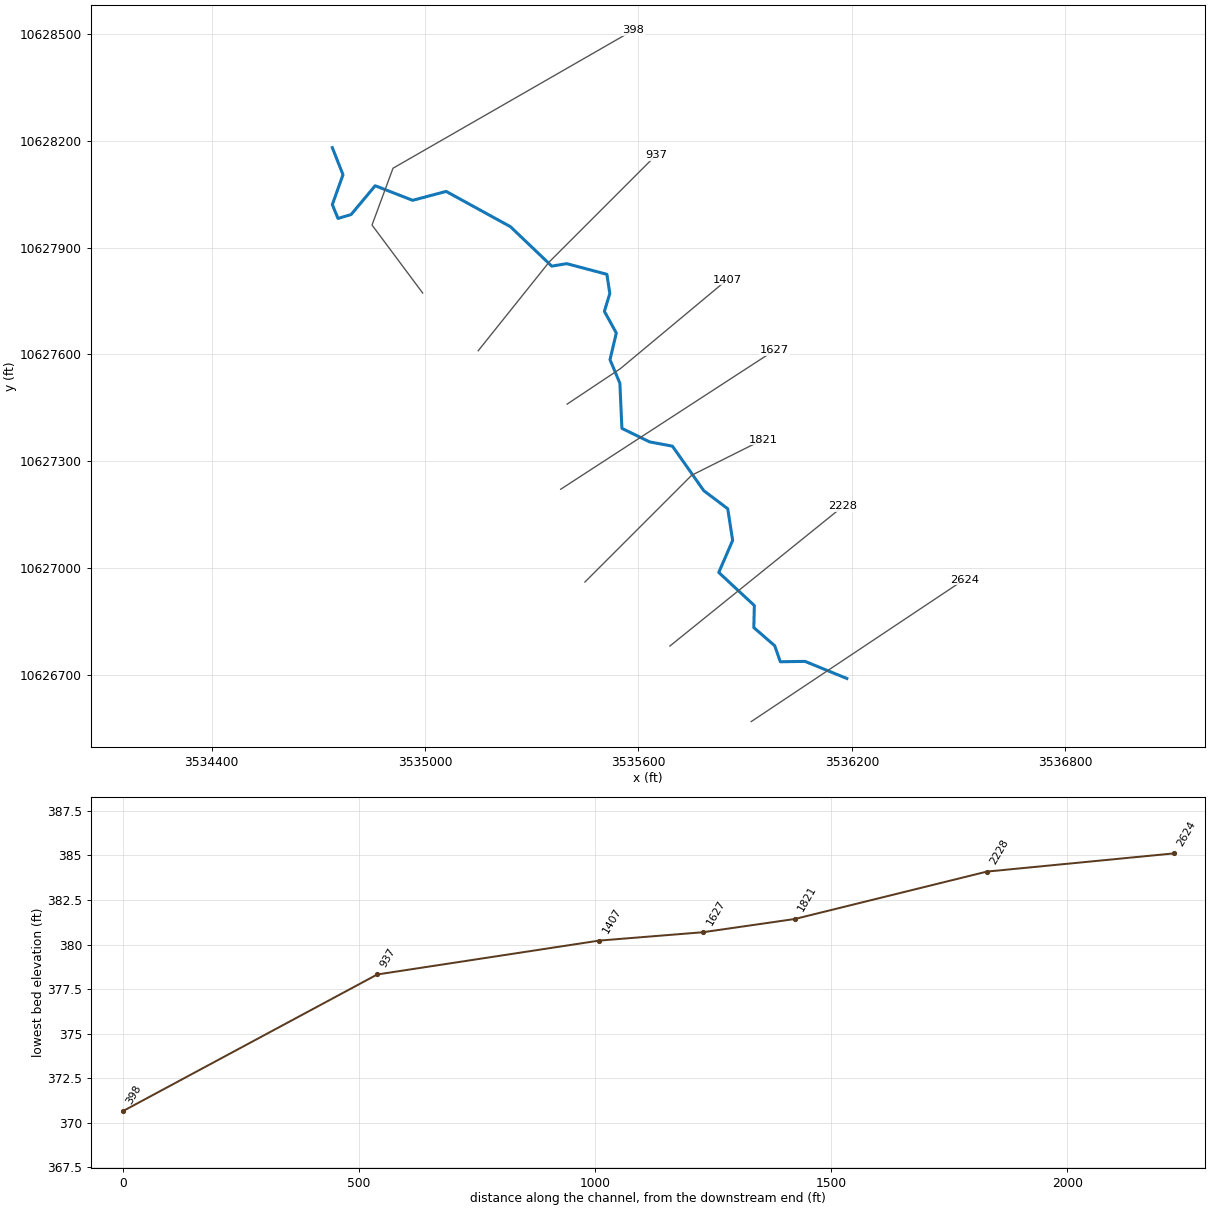
--- UNT097 IN CCTC.prj (project) ---

Proj Title=UNT097 IN CCTC Base Level Engineering
Current Plan=p01
Default Exp/Contr=0.3,0.1
English Units
Geom File=g01
Flow File=f01
Plan File=p01
BEGIN DESCRIPTION:
UNT097 IN CCTC
END DESCRIPTION:

--- UNT097 IN CCTC.p01 (plan) ---

Plan Title=Multiple Run
Short Identifier=Multiple
Geom File=g01
Flow File=f01
Subcritical Flow
K Sum by GR= 0
Std Step Tol= 0.01
Critical Tol= 0.01
Num of Std Step Trials= 20
Max Error Tol= 0.3
Flow Tol Ratio= 0.001
Split Flow NTrial= 30
Split Flow Tol= 0.02
Split Flow Ratio= 0.02
Log Output Level= 0
Friction Slope Method= 1
Unsteady Friction Slope Method= 2
Unsteady Bridges Friction Slope Method= 1
Parabolic Critical Depth
Global Vel Dist=  1 , 1 , 1
Global Log Level= 0
CheckData=True
Encroach Param= -1, 0, 0, 0
BEGIN DESCRIPTION:
Multiple Run
END DESCRIPTION:

--- UNT097 IN CCTC.f01 (steady flow) ---

Flow Title=Multiple
Number of Profiles=7
Profile Names=10-year,25-year,50-year,1pct_min,100-year,1pct_plu,500-year
River Rch & RM= UNT097 IN CCTC,Reach-1,2624
     990    1338    1621    1435    1941    2625    2772
Boundary for River Rch & Prof#=UNT097 IN CCTC,Reach-1,1
Up Type=0
Dn Type=3
Dn Slope=0.005
Boundary for River Rch & Prof#=UNT097 IN CCTC,Reach-1,2
Up Type=0
Dn Type=3
Dn Slope=0.005
Boundary for River Rch & Prof#=UNT097 IN CCTC,Reach-1,3
Up Type=0
Dn Type=3
Dn Slope=0.005
Boundary for River Rch & Prof#=UNT097 IN CCTC,Reach-1,4
Up Type=0
Dn Type=3
Dn Slope=0.005
Boundary for River Rch & Prof#=UNT097 IN CCTC,Reach-1,5
Up Type=0
Dn Type=3
Dn Slope=0.005
Boundary for River Rch & Prof#=UNT097 IN CCTC,Reach-1,6
Up Type=0
Dn Type=3
Dn Slope=0.005
Boundary for River Rch & Prof#=UNT097 IN CCTC,Reach-1,7
Up Type=0
Dn Type=3
Dn Slope=0.005

--- UNT097 IN CCTC.g01 (geometry) ---

Geom Title=Existing Conditions

River Reach=UNT097 IN CCTC,Reach-1
Reach XY= 30
      3536185.75     10626689.00      3536068.25     10626737.00
      3535998.75     10626736.00      3535983.00     10626781.00
      3535924.25     10626832.00      3535925.75     10626894.00
      3535825.75     10626987.00      3535864.75     10627077.00
      3535851.00     10627166.00      3535783.50     10627217.00
      3535695.50     10627342.00      3535631.25     10627354.00
      3535553.50     10627392.00      3535547.75     10627519.00
      3535520.00     10627585.00      3535537.75     10627660.00
      3535504.25     10627721.00      3535519.50     10627771.00
      3535511.25     10627825.00      3535398.25     10627855.00
      3535356.25     10627848.00      3535240.00     10627959.00
      3535059.50     10628058.00      3534965.25     10628033.00
      3534860.00     10628074.00      3534792.25     10627993.00
      3534755.50     10627982.00      3534739.50     10628021.00
      3534769.50     10628105.00      3534739.50     10628181.00

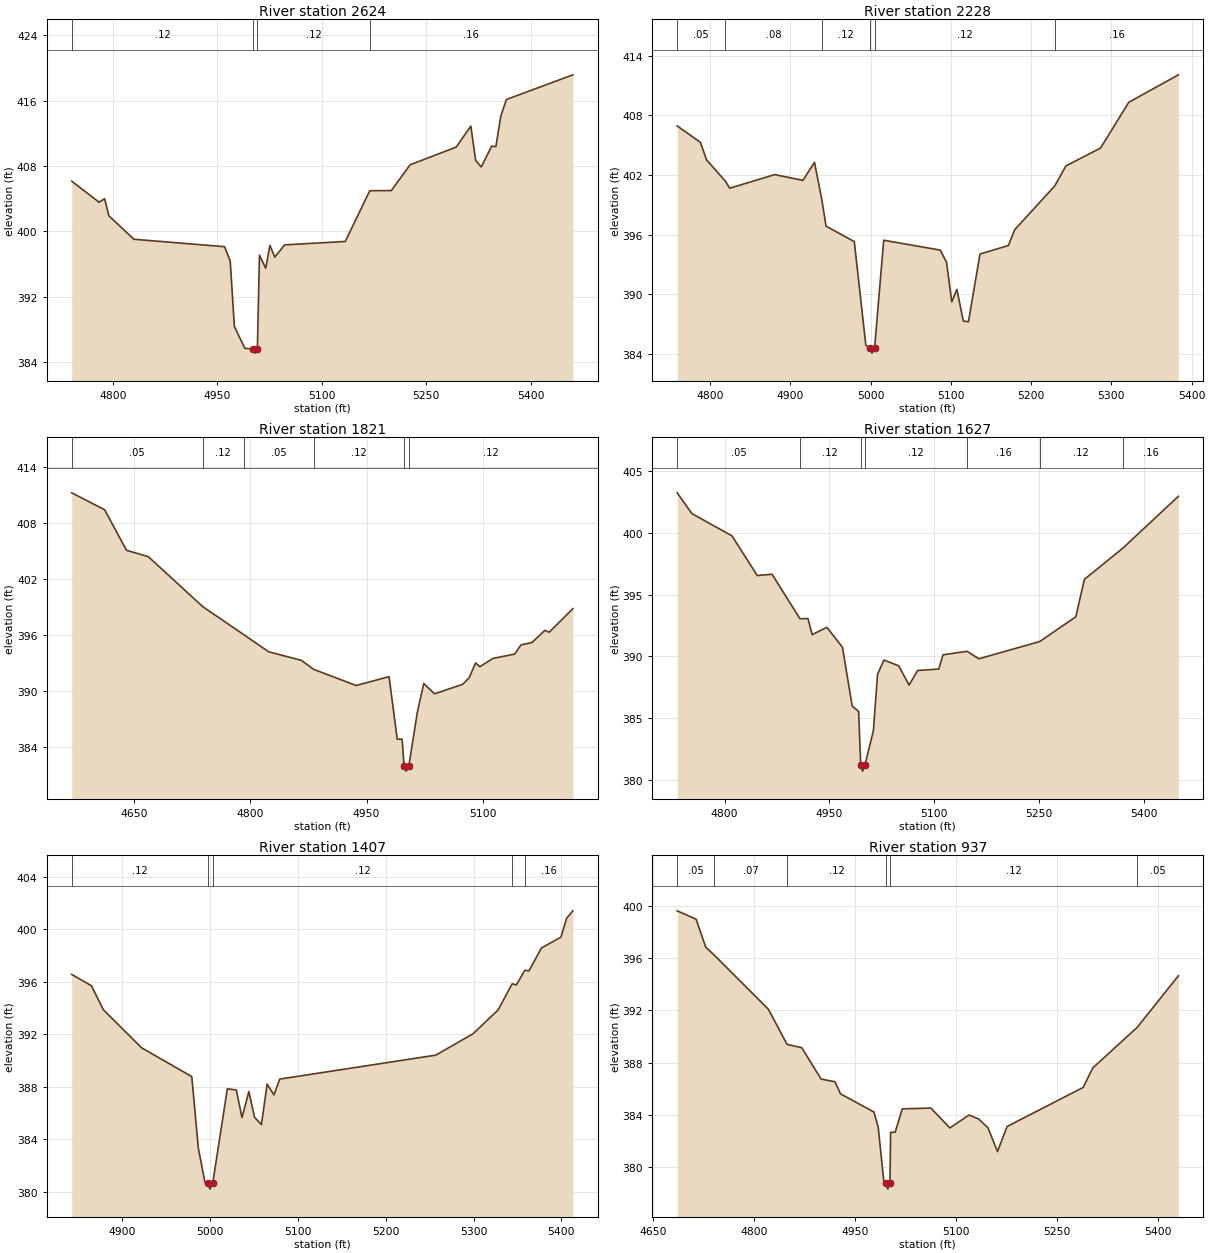
Type RM Length L Ch R = 1,2624,396,396,396
BEGIN DESCRIPTION:
UNT097 IN CCTC 5.0
END DESCRIPTION:
XS GIS Cut Line= 3
      3535916.97     10626567.83      3536216.97     10626767.83
      3536515.80     10626967.05
#Sta/Elev= 30
  4740.8  406.16  4780.0  403.59  4788.1  404.01  4794.1  401.93  4830.1  399.05
  4960.3  398.14  4968.4  396.37  4974.4  388.36  4989.4  385.70  5001.4  385.61
  5004.2  385.11  5007.4  385.61  5010.4  397.10  5019.4  395.50  5025.4  398.30
  5032.4  396.86  5046.5  398.36  5133.6  398.78  5168.8  404.99  5199.7  405.01
  5226.8  408.17  5292.9  410.33  5313.9  412.91  5320.9  408.68  5328.9  407.90
  5343.9  410.46  5349.9  410.38  5356.9  414.10  5365.0  416.16  5460.5  419.18
#Mann=4,-1,0
  4740.8    0.12       0  5001.4    0.07       0  5007.4    0.12       0
  5168.8    0.16       0
Bank Sta=5001.4,5007.4
Exp/Cntr=0.3,0.1

Type RM Length L Ch R = 1,2228,407,407,407
BEGIN DESCRIPTION:
Mapping XS 24df45c5
END DESCRIPTION:
XS GIS Cut Line= 2
      3535688.40     10626780.20      3536174.51     10627172.56
#Sta/Elev= 30
  4758.8  406.93  4787.6  405.29  4795.5  403.51  4818.6  401.40  4824.3  400.67
  4880.3  402.04  4915.5  401.46  4929.9  403.27  4939.0  399.55  4944.3  396.86
  4979.5  395.30  4993.9  384.89  4998.8  384.59  5001.6  384.09  5004.8  384.59
  5016.2  395.44  5086.6  394.45  5094.5  393.23  5101.0  389.24  5107.4  390.50
  5115.4  387.32  5121.8  387.24  5136.2  394.05  5171.6  394.91  5179.4  396.49
  5229.4  400.90  5243.3  402.91  5286.5  404.71  5321.7  409.31  5383.5  412.07
#Mann=6,-1,0
  4758.8    0.05       0  4818.6    0.08       0  4939.0    0.12       0
  4998.8    0.07       0  5004.8    0.12       0  5229.4    0.16       0
Bank Sta=4998.8,5004.8
Exp/Cntr=0.3,0.1

Type RM Length L Ch R = 1,1821,194,194,194
BEGIN DESCRIPTION:
UNT097 IN CCTC 4.0
END DESCRIPTION:
XS GIS Cut Line= 3
      3535449.57     10626960.15      3535749.61     10627260.19
      3535949.59     10627360.18
#Sta/Elev= 30
  4568.9  411.21  4611.4  409.40  4639.7  405.06  4667.9  404.38  4738.3  399.03
  4791.2  396.04  4823.5  394.20  4865.9  393.28  4881.7  392.32  4936.6  390.59
  4979.1  391.54  4989.7  384.85  4996.0  384.85  4998.6  381.93  5001.3  381.43
  5004.6  381.93  5015.6  387.68  5024.0  390.81  5037.9  389.70  5074.3  390.72
  5082.7  391.42  5091.0  393.01  5096.6  392.61  5113.4  393.49  5141.4  393.95
  5149.7  394.94  5163.7  395.18  5180.5  396.49  5186.1  396.29  5216.8  398.82
#Mann=6,-1,0
  4568.9    0.05       0  4738.3    0.12       0  4791.2    0.05       0
  4881.7    0.12       0  4998.6    0.07       0  5004.6    0.12       0
Bank Sta=4998.6,5004.6
Exp/Cntr=0.3,0.1

Type RM Length L Ch R = 1,1627,220,220,220
BEGIN DESCRIPTION:
Mapping XS 13fcf1ec
END DESCRIPTION:
XS GIS Cut Line= 2
      3535381.50     10627220.89      3535982.63     10627611.52
#Sta/Elev= 30
  4732.3  403.26  4753.2  401.58  4810.6  399.77  4846.8  396.55  4867.9  396.66
  4907.9  393.05  4919.3  393.06  4925.3  391.76  4946.4  392.35  4968.6  390.75
  4982.6  385.97  4991.8  385.53  4994.8  381.19  4997.5  380.69  5000.8  381.19
  5012.9  383.96  5018.9  388.55  5028.0  389.70  5049.1  389.23  5064.0  387.67
  5076.2  388.85  5106.5  388.97  5112.4  390.12  5146.9  390.41  5163.8  389.80
  5250.9  391.20  5302.5  393.21  5314.7  396.24  5369.9  398.78  5449.2  402.98
#Mann=7,-1,0
  4732.3    0.05       0  4907.9    0.12       0  4994.8    0.07       0
  5000.8    0.12       0  5146.9    0.16       0  5250.9    0.12       0
  5369.9    0.16       0
Bank Sta=4994.8,5000.8
Exp/Cntr=0.3,0.1

Type RM Length L Ch R = 1,1407,470,470,470
BEGIN DESCRIPTION:
UNT097 IN CCTC 3.0
END DESCRIPTION:
XS GIS Cut Line= 3
      3535399.65     10627460.21      3535549.61     10627560.19
      3535849.58     10627810.16
#Sta/Elev= 30
  4842.4  396.57  4864.9  395.70  4878.4  393.88  4922.0  390.98  4979.1  388.79
  4986.6  383.33  4994.1  380.74  4997.1  380.72  4999.8  380.22  5003.1  380.72
  5019.6  387.86  5029.8  387.77  5036.3  385.67  5044.1  387.65  5050.6  385.69
  5058.4  385.13  5064.9  388.21  5072.7  387.40  5079.3  388.60  5256.9  390.42
  5299.2  392.04  5327.9  393.86  5343.9  395.85  5348.7  395.77  5358.4  396.89
  5363.0  396.83  5377.3  398.58  5399.5  399.41  5406.0  400.85  5413.1  401.41
#Mann=5,-1,0
  4842.4    0.12       0  4997.1    0.07       0  5003.1    0.12       0
  5343.9    0.05       0  5358.4    0.16       0
Bank Sta=4997.1,5003.1
Exp/Cntr=0.3,0.1

Type RM Length L Ch R = 1,937,539,539,539
BEGIN DESCRIPTION:
UNT097 IN CCTC 2.0
END DESCRIPTION:
XS GIS Cut Line= 3
      3535149.59     10627610.17      3535349.61     10627860.19
      3535649.58     10628160.16
#Sta/Elev= 30
  4686.3  399.61  4714.3  398.97  4728.7  396.83  4740.4  396.27  4821.6  392.09
  4849.5  389.39  4871.2  389.14  4900.0  386.74  4920.8  386.53  4928.8  385.61
  4978.5  384.22  4984.9  383.04  4992.9  379.03  4996.3  378.82  4999.0  378.32
  5002.3  378.82  5003.3  382.67  5010.0  382.67  5020.6  384.46  5063.1  384.52
  5091.3  383.00  5119.6  383.99  5133.8  383.69  5147.9  383.01  5162.0  381.19
  5176.2  383.11  5289.3  386.10  5303.5  387.59  5369.6  390.70  5430.7  394.64
#Mann=6,-1,0
  4686.3    0.05       0  4740.4    0.07       0  4849.5    0.12       0
  4996.3    0.07       0  5002.3    0.12       0  5369.6    0.05       0
Bank Sta=4996.3,5002.3
Exp/Cntr=0.3,0.1

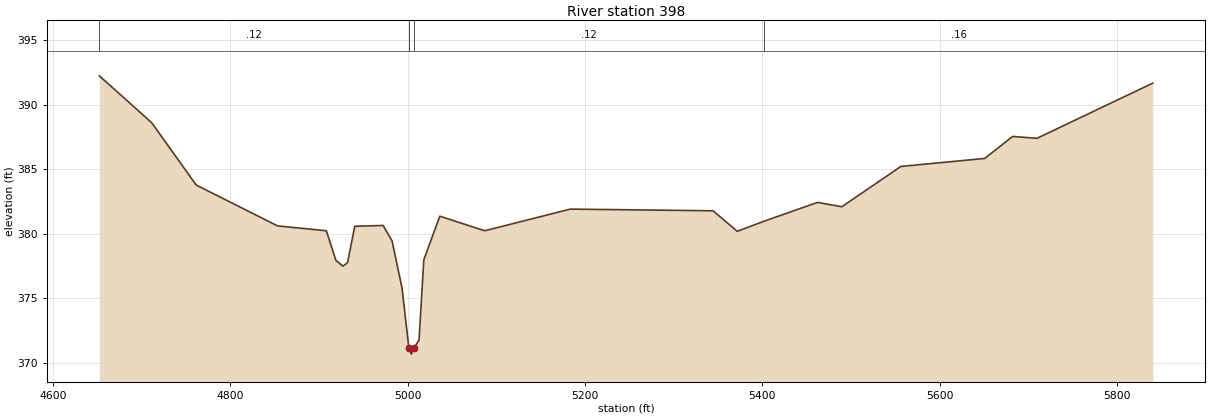
Type RM Length L Ch R = 1,398,0,0,0
BEGIN DESCRIPTION:
UNT097 IN CCTC 1.0
END DESCRIPTION:
XS GIS Cut Line= 4
      3534993.46     10627772.52      3534851.09     10627963.50
      3534910.12     10628123.22      3535585.89     10628511.36
#Sta/Elev= 30
  4652.4  392.24  4711.5  388.60  4761.6  383.77  4853.3  380.60  4908.4  380.22
  4919.1  377.93  4927.0  377.47  4932.3  377.75  4940.4  380.57  4972.4  380.63
  4982.5  379.43  4993.7  375.78  5001.4  371.15  5004.1  370.65  5007.4  371.15
  5012.9  371.75  5018.3  377.97  5036.3  381.35  5087.0  380.22  5183.4  381.90
  5344.4  381.77  5371.7  380.18  5401.9  380.96  5462.3  382.42  5489.6  382.08
  5556.2  385.21  5650.7  385.83  5682.3  387.54  5709.6  387.39  5840.2  391.67
#Mann=4,-1,0
  4652.4    0.12       0  5001.4    0.07       0  5007.4    0.12       0
  5401.9    0.16       0
Bank Sta=5001.4,5007.4
Exp/Cntr=0.3,0.1

Chan Stop Cuts=-1