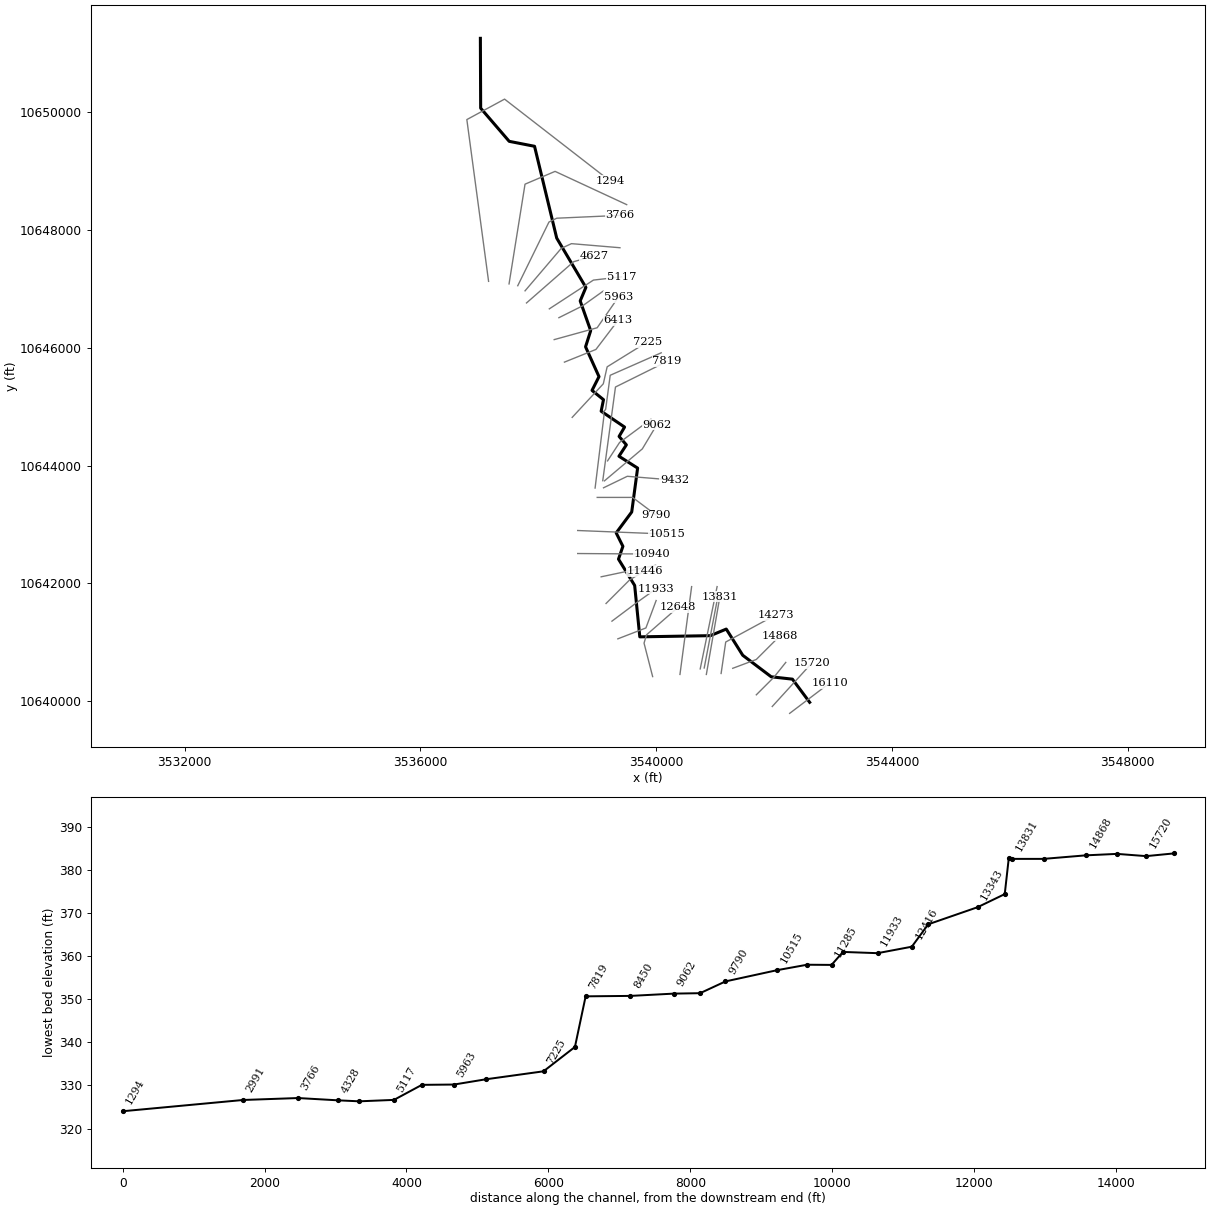
--- UNT099 IN CCTC.prj (project) ---

Proj Title=UNT099 IN CCTC Base Level Engineering
Current Plan=p01
Default Exp/Contr=0.3,0.1
English Units
Geom File=g01
Flow File=f01
Plan File=p01
BEGIN DESCRIPTION:
UNT099 IN CCTC
END DESCRIPTION:

--- UNT099 IN CCTC.p01 (plan) ---

Plan Title=Multiple Run
Short Identifier=Multiple
Geom File=g01
Flow File=f01
Subcritical Flow
K Sum by GR= 0
Std Step Tol= 0.01
Critical Tol= 0.01
Num of Std Step Trials= 20
Max Error Tol= 0.3
Flow Tol Ratio= 0.001
Split Flow NTrial= 30
Split Flow Tol= 0.02
Split Flow Ratio= 0.02
Log Output Level= 0
Friction Slope Method= 1
Unsteady Friction Slope Method= 2
Unsteady Bridges Friction Slope Method= 1
Parabolic Critical Depth
Global Vel Dist=  1 , 1 , 1
Global Log Level= 0
CheckData=True
Encroach Param= -1, 0, 0, 0
BEGIN DESCRIPTION:
Multiple Run
END DESCRIPTION:

--- UNT099 IN CCTC.f01 (steady flow) ---

Flow Title=Multiple
Number of Profiles=7
Profile Names=10-year,25-year,50-year,1pct_min,100-year,1pct_plu,500-year
River Rch & RM= UNT099 IN CCTC,Reach-1,16110
    1579    2190    2699    2426    3281    4437    4833
River Rch & RM= UNT099 IN CCTC,Reach-1,12416
    2958    4220    5299    4840    6546    8852    9967
River Rch & RM= UNT099 IN CCTC,Reach-1,1294
    3195    4567    5741    5248    7098    9599   10826
Boundary for River Rch & Prof#=UNT099 IN CCTC,Reach-1,1
Up Type=0
Dn Type=3
Dn Slope=0.005
Boundary for River Rch & Prof#=UNT099 IN CCTC,Reach-1,2
Up Type=0
Dn Type=3
Dn Slope=0.005
Boundary for River Rch & Prof#=UNT099 IN CCTC,Reach-1,3
Up Type=0
Dn Type=3
Dn Slope=0.005
Boundary for River Rch & Prof#=UNT099 IN CCTC,Reach-1,4
Up Type=0
Dn Type=3
Dn Slope=0.005
Boundary for River Rch & Prof#=UNT099 IN CCTC,Reach-1,5
Up Type=0
Dn Type=3
Dn Slope=0.005
Boundary for River Rch & Prof#=UNT099 IN CCTC,Reach-1,6
Up Type=0
Dn Type=3
Dn Slope=0.005
Boundary for River Rch & Prof#=UNT099 IN CCTC,Reach-1,7
Up Type=0
Dn Type=3
Dn Slope=0.005

--- UNT099 IN CCTC.g01 (geometry) ---

Geom Title=Existing Conditions

River Reach=UNT099 IN CCTC,Reach-1
Reach XY= 30
      3542605.00     10639983.00      3542312.25     10640376.00
      3541952.75     10640416.00      3541469.50     10640781.00
      3541189.75     10641226.00      3540920.25     10641114.00
      3539722.25     10641094.00      3539635.25     10641966.00
      3539360.75     10642413.00      3539435.50     10642630.00
      3539321.75     10642858.00      3539585.25     10643213.00
      3539685.25     10643958.00      3539368.50     10644159.00
      3539494.50     10644352.00      3539370.75     10644495.00
      3539464.00     10644654.00      3539066.50     10644923.00
      3539106.25     10645119.00      3538911.50     10645276.00
      3539029.75     10645510.00      3538801.75     10646016.00
      3538888.75     10646290.00      3538710.75     10646795.00
      3538807.50     10647024.00      3538312.25     10647861.00
      3537936.00     10649419.00      3537506.00     10649503.00
      3537021.75     10650066.00      3537016.75     10651251.00

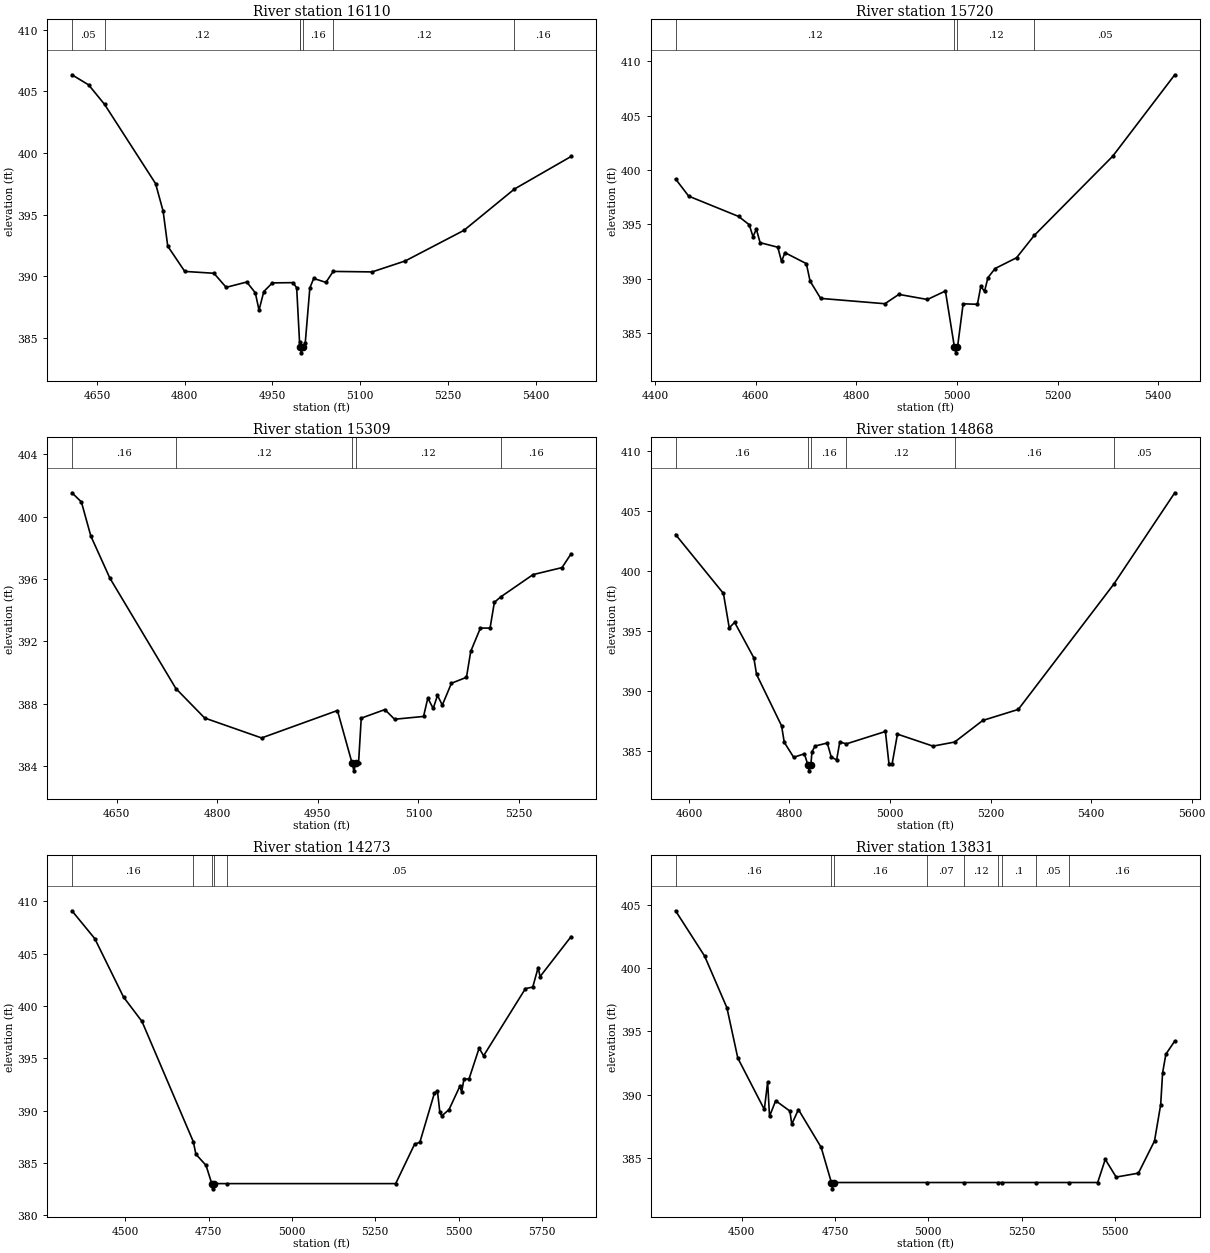
Type RM Length L Ch R = 1,16110,390,390,390
BEGIN DESCRIPTION:
UNT099 IN CCTC 29.0
END DESCRIPTION:
XS GIS Cut Line= 2
      3542265.39     10639795.25      3542945.66     10640310.87
#Sta/Elev= 30
  4607.3  406.35  4635.9  405.53  4663.1  403.95  4750.3  397.53  4763.2  395.30
  4771.1  392.46  4800.2  390.41  4850.1  390.26  4871.0  389.12  4906.3  389.55
  4920.9  388.67  4927.2  387.27  4935.4  388.78  4950.0  389.48  4985.4  389.50
  4991.6  389.08  4996.5  384.67  4996.9  384.31  4999.7  383.81  5002.9  384.31
  5006.2  384.58  5014.1  389.07  5020.7  389.84  5041.6  389.52  5054.0  390.41
  5120.6  390.37  5177.3  391.26  5277.6  393.74  5364.0  397.09  5460.9  399.73
#Mann=7,-1,0
  4607.3    0.05       0  4663.1    0.12       0  4996.5    0.16       0
  4996.9    0.07       0  5002.9    0.16       0  5054.0    0.12       0
  5364.0    0.16       0
Bank Sta=4996.9,5002.9
Exp/Cntr=0.3,0.1

Type RM Length L Ch R = 1,15720,411,411,411
BEGIN DESCRIPTION:
Mapping XS e5b01bea
END DESCRIPTION:
XS GIS Cut Line= 2
      3541970.19     10639912.39      3542638.28     10640645.55
#Sta/Elev= 30
  4440.9  399.18  4467.0  397.60  4566.3  395.73  4587.3  394.97  4594.7  393.88
  4601.5  394.55  4608.9  393.32  4644.0  392.90  4651.5  391.59  4658.2  392.40
  4700.8  391.39  4708.2  389.78  4729.2  388.19  4856.9  387.70  4884.6  388.56
  4941.3  388.09  4977.1  388.87  4995.1  383.68  4997.8  383.18  5001.1  383.68
  5012.3  387.69  5040.7  387.65  5047.4  389.30  5054.8  388.84  5061.6  390.10
  5075.8  390.94  5118.4  391.93  5153.5  393.98  5309.6  401.28  5432.8  408.77
#Mann=4,-1,0
  4440.9    0.12       0  4995.1    0.07       0  5001.1    0.12       0
  5153.5    0.05       0
Bank Sta=4995.1,5001.1
Exp/Cntr=0.3,0.1

Type RM Length L Ch R = 1,15309,441,441,441
BEGIN DESCRIPTION:
UNT099 IN CCTC 28.0
END DESCRIPTION:
XS GIS Cut Line= 3
      3541699.64     10640110.22      3541999.61     10640410.19
      3542199.62     10640660.21
#Sta/Elev= 30
  4583.3  401.54  4597.4  400.95  4611.5  398.76  4639.8  396.07  4738.3  388.98
  4781.2  387.09  4866.1  385.81  4979.2  387.57  5001.0  384.20  5003.7  383.70
  5007.0  384.20  5010.7  384.20  5014.7  387.08  5049.9  387.63  5064.4  387.01
  5107.6  387.19  5114.0  388.37  5122.0  387.70  5128.4  388.54  5135.6  387.92
  5149.2  389.32  5171.6  389.70  5178.0  391.37  5192.4  392.86  5206.8  392.86
  5213.2  394.51  5222.7  394.86  5270.9  396.29  5314.1  396.74  5327.7  397.63
#Mann=5,-1,0
  4583.3    0.16       0  4738.3    0.12       0  5001.0    0.07       0
  5007.0    0.12       0  5222.7    0.16       0
Bank Sta=5001,5007
Exp/Cntr=0.3,0.1

Type RM Length L Ch R = 1,14868,595,595,595
BEGIN DESCRIPTION:
UNT099 IN CCTC 27.0
END DESCRIPTION:
XS GIS Cut Line= 3
      3541299.63     10640560.20      3541699.61     10640710.19
      3542099.63     10641110.21
#Sta/Elev= 30
  4573.5  403.06  4668.7  398.15  4680.3  395.28  4691.0  395.74  4729.2  392.78
  4734.6  391.40  4784.4  387.11  4789.7  385.74  4808.4  384.49  4829.8  384.78
  4836.6  383.86  4839.3  383.36  4842.6  383.86  4844.9  384.97  4851.2  385.43
  4875.2  385.68  4883.2  384.51  4893.9  384.27  4900.1  385.76  4913.4  385.61
  4990.9  386.64  4998.0  383.93  5004.2  383.93  5014.8  386.42  5085.5  385.42
  5128.6  385.76  5184.5  387.56  5255.2  388.48  5444.9  398.91  5566.4  406.54
#Mann=6,-1,0
  4573.5    0.16       0  4836.6    0.07       0  4842.6    0.16       0
  4913.4    0.12       0  5128.6    0.16       0  5444.9    0.05       0
Bank Sta=4836.6,4842.6
Exp/Cntr=0.3,0.1

Type RM Length L Ch R = 1,14273,442,442,442
BEGIN DESCRIPTION:
UNT099 IN CCTC 26.0
END DESCRIPTION:
XS GIS Cut Line= 3
      3541102.17     10640472.36      3541180.29     10641006.17
      3542022.28     10641461.89
#Sta/Elev= 30
  4340.5  409.10  4409.0  406.44  4495.2  400.86  4550.5  398.53  4704.5  387.04
  4712.2  385.85  4742.6  384.78  4759.8  383.04  4762.5  382.54  4765.8  383.04
  4804.2  383.04  5311.3  383.04  5368.2  386.82  5383.7  386.98  5427.4  391.68
  5436.4  391.90  5443.6  389.89  5449.3  389.50  5471.2  390.11  5503.6  392.33
  5509.2  391.80  5516.0  393.03  5531.1  393.03  5561.5  395.98  5574.9  395.25
  5700.4  401.67  5722.3  401.81  5738.5  403.68  5744.2  402.81  5837.4  406.64
#Mann=5,-1,0
  4340.5    0.16       0  4704.5     0.1       0  4759.8   0.033       0
  4765.8     0.1       0  4804.2    0.05       0
Bank Sta=4759.8,4765.8
Exp/Cntr=0.3,0.1

Type RM Length L Ch R = 1,13831,48,48,48
BEGIN DESCRIPTION:
UNT099 IN CCTC 25.0
END DESCRIPTION:
XS GIS Cut Line= 2
      3540851.69     10640455.88      3541080.86     10641773.60
#Sta/Elev= 30
  4323.0  404.53  4401.0  400.94  4460.6  396.86  4489.8  392.88  4560.8  388.82
  4569.7  390.97  4574.8  388.28  4591.3  389.51  4629.3  388.69  4634.4  387.65
  4652.2  388.81  4713.1  385.82  4740.5  383.04  4743.3  382.54  4746.5  383.04
  4996.4  383.04  5096.6  383.04  5185.9  383.04  5197.9  383.04  5288.6  383.04
  5377.9  383.04  5454.0  383.04  5474.3  384.87  5503.5  383.47  5563.1  383.78
  5606.3  386.33  5622.8  389.20  5627.9  391.71  5636.7  393.19  5660.5  394.23
#Mann=9,-1,0
  4323.0    0.16       0  4740.5    0.07       0  4746.5    0.16       0
  4996.4    0.07       0  5096.6    0.12       0  5185.9    0.05       0
  5197.9     0.1       0  5288.6    0.05       0  5377.9    0.16       0
Bank Sta=4740.5,4746.5
Exp/Cntr=0.3,0.1

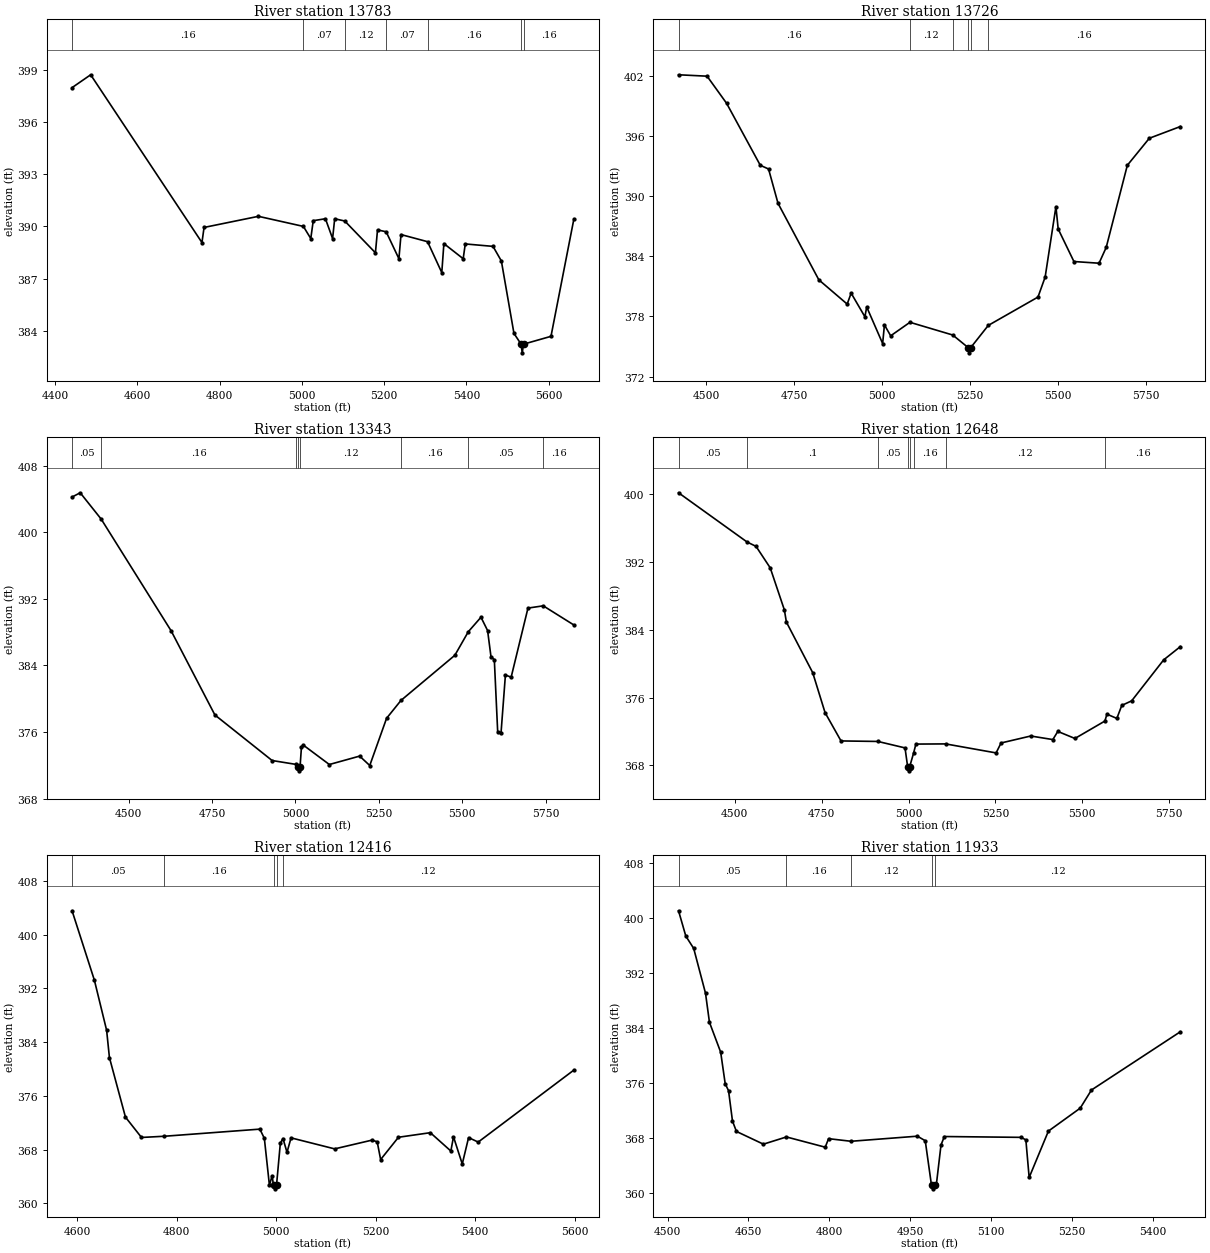
Type RM Length L Ch R = 1,13783,57,57,57
BEGIN DESCRIPTION:
Mapping XS 5c438de8
END DESCRIPTION:
XS GIS Cut Line= 2
      3540815.25     10640565.35      3541044.41     10641763.23
#Sta/Elev= 30
  4441.4  397.99  4486.6  398.73  4757.1  389.07  4762.2  389.94  4894.3  390.58
  5003.6  390.00  5021.6  389.30  5027.6  390.33  5057.2  390.44  5074.6  389.30
  5079.7  390.44  5104.2  390.31  5178.7  388.48  5183.8  389.80  5204.8  389.69
  5235.8  388.14  5240.9  389.53  5305.4  389.12  5340.0  387.34  5345.1  389.01
  5392.0  388.14  5397.1  388.99  5464.5  388.85  5484.8  388.01  5515.4  383.84
  5532.7  383.22  5535.5  382.72  5538.7  383.22  5605.4  383.67  5661.0  390.42
#Mann=7,-1,0
  4441.4    0.16       0  5003.6    0.07       0  5104.2    0.12       0
  5204.8    0.07       0  5305.4    0.16       0  5532.7    0.07       0
  5538.7    0.16       0
Bank Sta=5532.7,5538.7
Exp/Cntr=0.3,0.1

Type RM Length L Ch R = 1,13726,383,383,383
BEGIN DESCRIPTION:
UNT099 IN CCTC 24.0
END DESCRIPTION:
XS GIS Cut Line= 2
      3540747.52     10640549.65      3541034.09     10641946.46
#Sta/Elev= 30
  4421.4  402.14  4502.5  402.00  4558.0  399.29  4653.7  393.10  4677.2  392.73
  4704.1  389.30  4820.1  381.66  4900.6  379.24  4911.9  380.33  4951.0  377.97
  4956.1  378.95  5001.4  375.30  5006.5  377.16  5024.2  376.07  5079.0  377.42
  5200.6  376.15  5245.2  374.87  5248.0  374.37  5251.2  374.87  5301.6  377.11
  5442.8  379.94  5463.2  381.94  5493.8  388.97  5500.2  386.74  5544.9  383.49
  5616.3  383.32  5636.7  384.90  5696.7  393.10  5759.2  395.80  5847.3  396.97
#Mann=6,-1,0
  4421.4    0.16       0  5079.0    0.12       0  5200.6    0.07       0
  5245.2    0.07       0  5251.2    0.07       0  5301.6    0.16       0
Bank Sta=5245.2,5251.2
Exp/Cntr=0.3,0.1

Type RM Length L Ch R = 1,13343,695,695,695
BEGIN DESCRIPTION:
Mapping XS 0ba8dea1
END DESCRIPTION:
XS GIS Cut Line= 2
      3540403.78     10640455.97      3540601.89     10641946.46
#Sta/Elev= 30
  4330.7  404.22  4355.1  404.73  4418.1  401.56  4627.5  388.15  4758.7  378.04
  4930.1  372.57  5000.9  372.11  5007.9  371.83  5010.6  371.33  5013.9  371.83
  5018.0  374.17  5023.0  374.44  5101.6  372.09  5192.4  373.10  5222.7  371.97
  5273.1  377.64  5316.3  379.79  5477.7  385.21  5518.0  388.04  5556.0  389.78
  5575.8  388.18  5585.9  385.06  5596.0  384.67  5606.0  376.05  5616.1  375.90
  5629.2  382.84  5646.4  382.58  5696.8  390.88  5742.6  391.15  5834.3  388.85
#Mann=8,-1,0
  4330.7    0.05       0  4418.1    0.16       0  5000.9    0.12       0
  5007.9    0.07       0  5013.9    0.12       0  5316.3    0.16       0
  5518.0    0.05       0  5742.6    0.16       0
Bank Sta=5007.9,5013.9
Exp/Cntr=0.3,0.1

Type RM Length L Ch R = 1,12648,232,232,232
BEGIN DESCRIPTION:
UNT099 IN CCTC 23.0
END DESCRIPTION:
XS GIS Cut Line= 4
      3539940.23     10640419.51      3539794.40     10640987.18
      3539836.07     10641127.80      3540371.73     10641595.85
#Sta/Elev= 30
  4338.0  400.10  4535.1  394.31  4561.1  393.79  4601.9  391.26  4642.6  386.31
  4648.4  384.88  4724.1  378.93  4759.7  374.22  4805.6  370.89  4911.7  370.83
  4989.8  370.07  4997.3  367.87  5000.1  367.37  5003.3  367.87  5014.8  369.51
  5021.1  370.52  5106.7  370.54  5251.9  369.48  5266.2  370.65  5351.6  371.47
  5415.2  371.05  5429.5  372.01  5478.8  371.18  5565.0  373.23  5570.9  374.04
  5599.4  373.54  5613.6  375.07  5642.1  375.61  5734.1  380.43  5782.1  381.99
#Mann=8,-1,0
  4338.0    0.05       0  4535.1     0.1       0  4911.7    0.05       0
  4997.3    0.03       0  5003.3    0.05       0  5014.8    0.16       0
  5106.7    0.12       0  5565.0    0.16       0
Bank Sta=4997.3,5003.3
Exp/Cntr=0.3,0.1

Type RM Length L Ch R = 1,12416,483,483,483
BEGIN DESCRIPTION:
UNT099 IN CCTC 22.0
END DESCRIPTION:
XS GIS Cut Line= 3
      3539349.65     10641060.20      3539826.12     10641244.88
      3539999.61     10641710.18
#Sta/Elev= 30
  4590.3  403.57  4635.1  393.24  4659.7  385.77  4665.3  381.72  4697.5  372.85
  4729.7  369.82  4775.7  370.00  4967.4  371.06  4976.4  369.69  4986.6  362.69
  4992.0  364.13  4994.8  362.67  4997.6  362.17  5000.8  362.67  5008.5  368.96
  5013.8  369.66  5021.9  367.61  5030.0  369.76  5117.6  368.12  5192.4  369.42
  5203.0  369.18  5209.9  366.53  5245.7  369.85  5309.7  370.53  5350.9  367.80
  5356.2  369.92  5373.8  365.87  5386.5  369.80  5405.8  369.13  5597.9  379.85
#Mann=5,-1,0
  4590.3    0.05       0  4775.7    0.16       0  4994.8    0.07       0
  5000.8    0.16       0  5013.8    0.12       0
Bank Sta=4994.8,5000.8
Exp/Cntr=0.3,0.1

Type RM Length L Ch R = 1,11933,487,487,487
BEGIN DESCRIPTION:
UNT099 IN CCTC 21.0
END DESCRIPTION:
XS GIS Cut Line= 3
      3539249.61     10641360.19      3539649.61     10641660.19
      3539999.60     10641910.18
#Sta/Elev= 30
  4520.4  401.07  4533.9  397.39  4548.5  395.60  4570.4  389.09  4577.7  384.87
  4598.5  380.53  4606.9  375.94  4613.1  374.93  4620.4  370.52  4627.7  369.01
  4677.7  367.16  4720.4  368.21  4792.3  366.72  4798.5  367.96  4840.1  367.58
  4963.1  368.32  4977.7  367.66  4989.3  361.17  4992.0  360.67  4995.3  361.17
  4998.5  361.43  5006.9  367.04  5013.1  368.27  5155.6  368.15  5164.2  367.78
  5170.3  362.32  5206.0  369.06  5264.9  372.39  5285.8  375.03  5450.5  383.49
#Mann=5,-1,0
  4520.4    0.05       0  4720.4    0.16       0  4840.1    0.12       0
  4989.3    0.07       0  4995.3    0.12       0
Bank Sta=4989.3,4995.3
Exp/Cntr=0.3,0.1

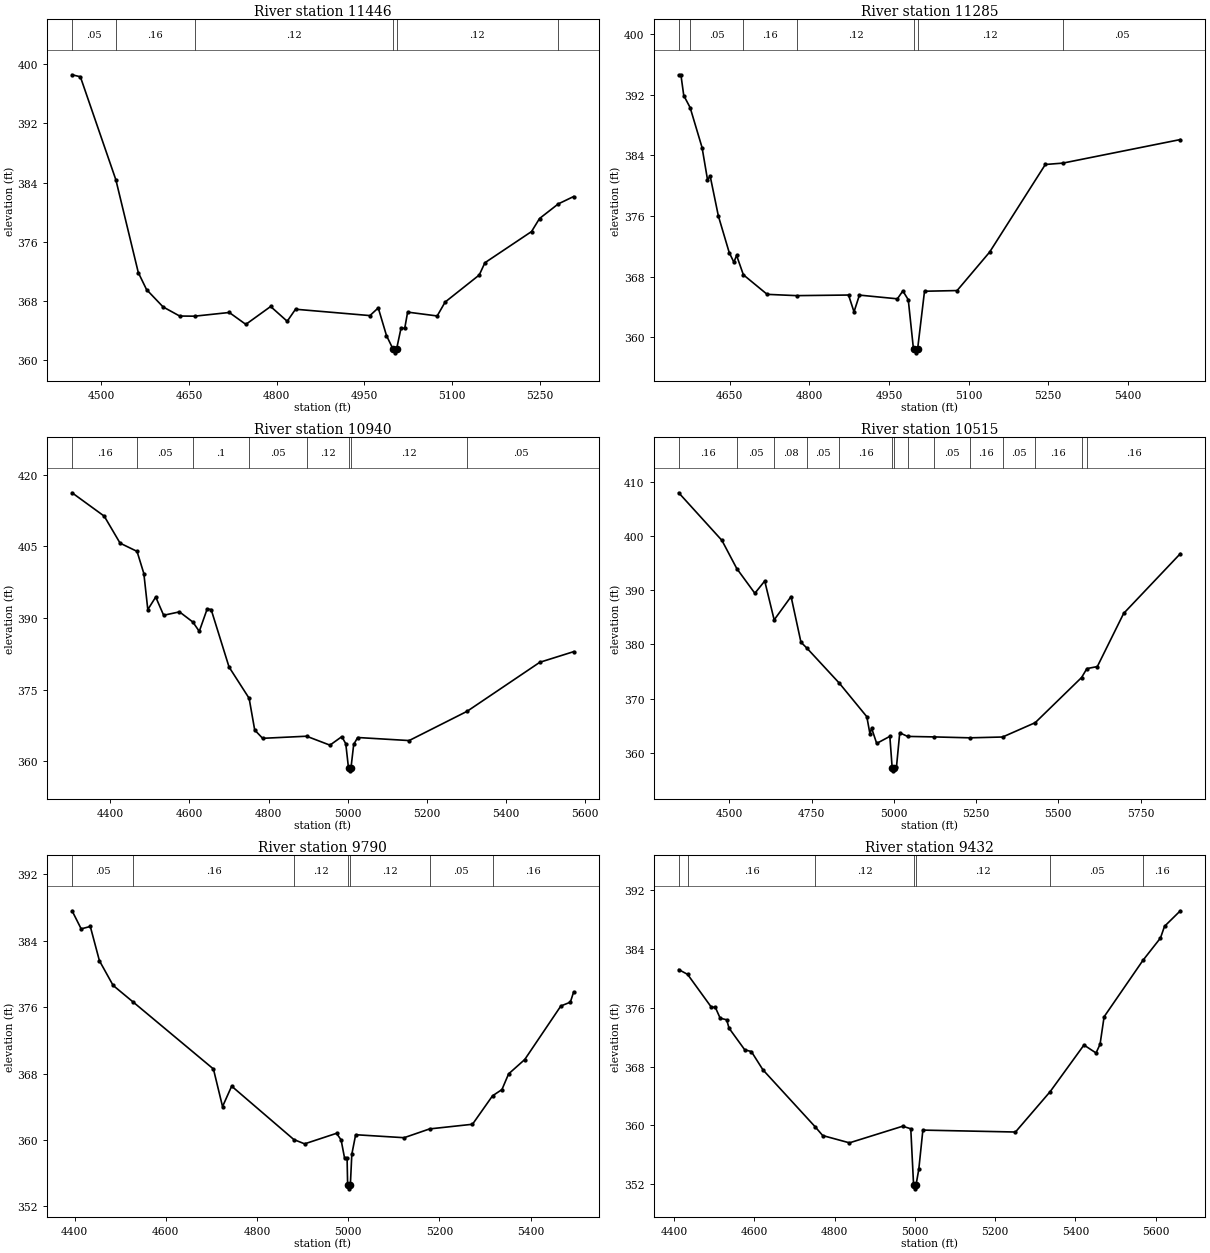
Type RM Length L Ch R = 1,11446,161,161,161
BEGIN DESCRIPTION:
UNT099 IN CCTC 20.0
END DESCRIPTION:
XS GIS Cut Line= 3
      3539149.60     10641660.18      3539549.61     10642060.19
      3539799.65     10642210.21
#Sta/Elev= 30
  4450.2  398.58  4464.4  398.31  4525.1  384.36  4563.4  371.82  4577.5  369.52
  4605.8  367.17  4634.1  365.94  4659.7  365.92  4718.9  366.42  4747.2  364.81
  4789.6  367.23  4817.9  365.23  4832.1  366.86  4959.3  366.00  4973.5  367.04
  4987.6  363.29  4998.8  361.46  5001.5  360.96  5004.8  361.46  5012.4  364.29
  5018.8  364.29  5023.7  366.47  5074.2  365.95  5087.8  367.83  5146.1  371.49
  5155.8  373.15  5235.5  377.37  5249.1  379.13  5281.2  381.11  5307.5  382.11
#Mann=6,-1,0
  4450.2    0.05       0  4525.1    0.16       0  4659.7    0.12       0
  4998.8    0.07       0  5004.8    0.12       0  5281.2    0.05       0
Bank Sta=4998.8,5004.8
Exp/Cntr=0.3,0.1

Type RM Length L Ch R = 1,11285,345,345,345
BEGIN DESCRIPTION:
UNT099 IN CCTC 19.0
END DESCRIPTION:
XS GIS Cut Line= 2
      3539066.57     10642112.94      3539991.06     10642308.25
#Sta/Elev= 30
  4554.1  394.65  4558.2  394.65  4563.6  391.91  4575.6  390.32  4598.1  385.04
  4608.3  380.82  4613.4  381.26  4628.8  376.01  4649.2  371.19  4658.0  369.91
  4663.1  370.81  4675.9  368.25  4720.7  365.67  4776.2  365.50  4874.0  365.58
  4884.3  363.36  4894.5  365.57  4966.0  365.08  4976.3  366.12  4986.5  364.96
  4996.0  358.65  4998.1  358.45  5000.8  357.95  5004.1  358.45  5017.1  366.08
  5078.5  366.17  5139.8  371.25  5244.7  382.81  5277.6  382.99  5499.0  386.10
#Mann=7,-1,0
  4554.1     0.1       0  4575.6    0.05       0  4675.9    0.16       0
  4776.2    0.12       0  4998.1    0.07       0  5004.1    0.12       0
  5277.6    0.05       0
Bank Sta=4998.1,5004.1
Exp/Cntr=0.3,0.1

Type RM Length L Ch R = 1,10940,425,425,425
BEGIN DESCRIPTION:
UNT099 IN CCTC 18.0
END DESCRIPTION:
XS GIS Cut Line= 2
      3538668.34     10642507.91      3539935.21     10642499.23
#Sta/Elev= 30
  4303.6  416.22  4384.9  411.32  4424.9  405.67  4467.7  403.95  4484.9  399.31
  4494.9  391.76  4514.9  394.39  4534.9  390.57  4574.9  391.28  4608.6  389.16
  4624.9  387.20  4644.9  391.90  4654.9  391.77  4700.1  379.73  4750.8  373.18
  4764.9  366.54  4784.9  364.80  4895.9  365.24  4954.9  363.37  4984.9  365.15
  4994.9  363.67  5001.9  358.49  5004.6  357.99  5007.9  358.49  5014.9  363.51
  5024.9  364.97  5154.9  364.33  5301.4  370.46  5484.9  380.72  5570.5  382.95
#Mann=8,-1,0
  4303.6    0.16       0  4467.7    0.05       0  4608.6     0.1       0
  4750.8    0.05       0  4895.9    0.12       0  5001.9    0.07       0
  5007.9    0.12       0  5301.4    0.05       0
Bank Sta=5001.9,5007.9
Exp/Cntr=0.3,0.1

Type RM Length L Ch R = 1,10515,725,725,725
BEGIN DESCRIPTION:
UNT099 IN CCTC 17.0
END DESCRIPTION:
XS GIS Cut Line= 2
      3538668.37     10642898.53      3540191.76     10642837.77
#Sta/Elev= 30
  4346.1  407.93  4477.4  399.16  4522.5  393.98  4577.5  389.42  4607.5  391.68
  4636.2  384.52  4687.6  388.82  4717.6  380.41  4735.4  379.34  4834.6  372.84
  4917.8  366.69  4927.3  363.54  4932.3  364.58  4947.8  361.77  4987.8  363.07
  4994.9  357.22  4997.6  356.72  5000.9  357.22  5007.9  357.41  5017.9  363.72
  5041.7  363.06  5120.7  362.97  5231.3  362.80  5330.5  362.95  5429.6  365.59
  5570.6  373.91  5586.7  375.55  5618.4  375.92  5698.4  385.71  5870.7  396.72
#Mann=14,-1,0
  4346.1    0.16       0  4522.5    0.05       0  4636.2    0.08       0
  4735.4    0.05       0  4834.6    0.16       0  4994.9    0.07       0
  5000.9    0.16       0  5041.7    0.12       0  5120.7    0.05       0
  5231.3    0.16       0  5330.5    0.05       0  5429.6    0.16       0
  5570.6    0.05       0  5586.7    0.16       0
Bank Sta=4994.9,5000.9
Exp/Cntr=0.3,0.1

Type RM Length L Ch R = 1,9790,358,358,358
BEGIN DESCRIPTION:
UNT099 IN CCTC 16.0
END DESCRIPTION:
XS GIS Cut Line= 3
      3538999.63     10643460.19      3539599.61     10643460.19
      3539999.62     10643160.18
#Sta/Elev= 30
  4394.3  387.62  4414.3  385.44  4434.3  385.73  4454.3  381.60  4484.3  378.63
  4528.2  376.63  4704.3  368.56  4724.3  364.03  4744.3  366.49  4880.6  360.06
  4904.3  359.54  4974.3  360.81  4984.3  360.01  4991.8  357.85  4997.4  357.85
  4998.6  354.62  5001.3  354.12  5004.6  354.62  5007.8  358.29  5016.2  360.64
  5122.4  360.28  5178.4  361.34  5272.4  361.90  5316.4  365.33  5337.0  366.08
  5351.6  367.97  5387.0  369.70  5466.2  376.15  5487.0  376.61  5494.3  377.85
#Mann=7,-1,0
  4394.3    0.05       0  4528.2    0.16       0  4880.6    0.12       0
  4998.6    0.07       0  5004.6    0.12       0  5178.4    0.05       0
  5316.4    0.16       0
Bank Sta=4998.6,5004.6
Exp/Cntr=0.3,0.1

Type RM Length L Ch R = 1,9432,370,370,370
BEGIN DESCRIPTION:
UNT099 IN CCTC 15.0
END DESCRIPTION:
XS GIS Cut Line= 3
      3539106.75     10643623.37      3539510.37     10643818.67
      3540308.93     10643753.57
#Sta/Elev= 30
  4411.9  381.18  4434.0  380.53  4492.8  376.10  4503.2  376.04  4515.1  374.58
  4531.3  374.36  4537.3  373.22  4576.5  370.27  4592.8  370.05  4621.7  367.56
  4752.3  359.79  4770.6  358.63  4837.2  357.64  4969.9  359.90  4990.0  359.55
  4997.0  351.89  4999.7  351.39  5003.0  351.89  5010.0  354.06  5020.1  359.37
  5250.8  359.11  5337.4  364.61  5421.4  370.93  5451.5  369.85  5461.5  371.03
  5471.6  374.77  5568.4  382.44  5612.0  385.47  5622.1  387.06  5661.5  389.17
#Mann=7,-1,0
  4411.9    0.05       0  4434.0    0.16       0  4752.3    0.12       0
  4997.0    0.07       0  5003.0    0.12       0  5337.4    0.05       0
  5568.4    0.16       0
Bank Sta=4997,5003
Exp/Cntr=0.3,0.1

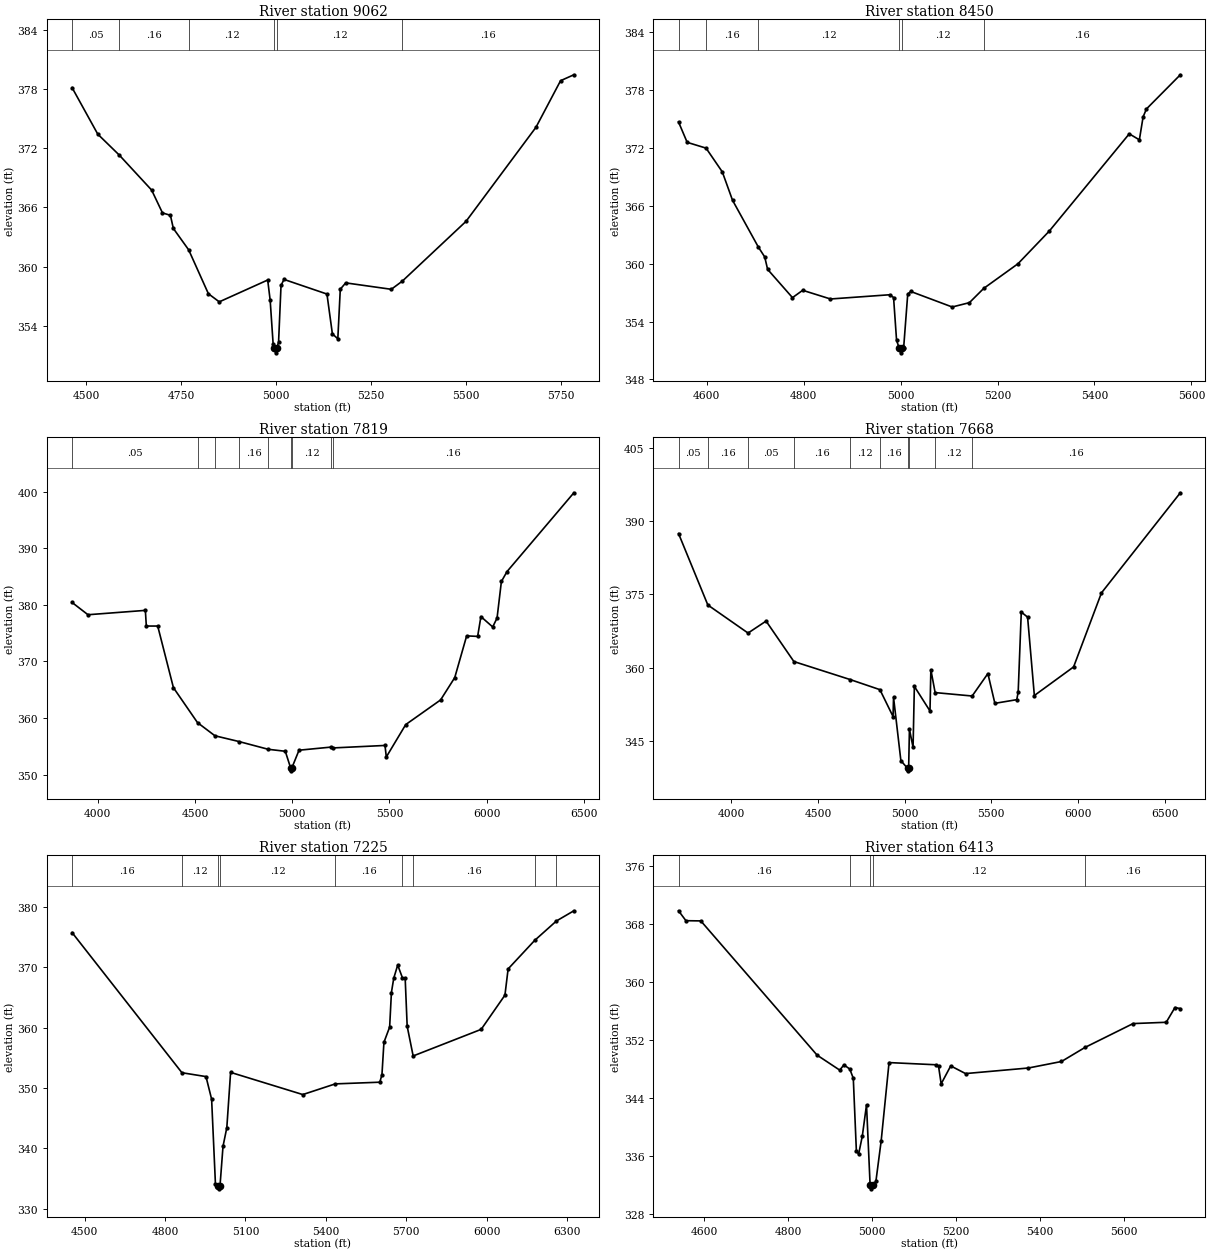
Type RM Length L Ch R = 1,9062,612,612,612
BEGIN DESCRIPTION:
UNT099 IN CCTC 14.0
END DESCRIPTION:
XS GIS Cut Line= 3
      3539122.95     10643741.42      3539765.32     10644283.97
      3540012.37     10644695.70
#Sta/Elev= 30
  4463.4  378.13  4531.1  373.42  4588.0  371.29  4672.9  367.76  4701.4  365.45
  4722.3  365.21  4730.0  363.88  4770.4  361.71  4822.3  357.27  4850.9  356.45
  4978.4  358.66  4984.9  356.62  4992.7  352.20  4996.2  351.79  4999.0  351.29
  5002.2  351.79  5007.0  352.35  5013.5  358.11  5021.3  358.72  5134.4  357.24
  5148.7  353.21  5163.0  352.71  5169.5  357.73  5183.8  358.37  5303.8  357.72
  5332.9  358.55  5500.6  364.60  5684.7  374.12  5749.4  378.83  5784.4  379.43
#Mann=6,-1,0
  4463.4    0.05       0  4588.0    0.16       0  4770.4    0.12       0
  4996.2    0.07       0  5002.2    0.12       0  5332.9    0.16       0
Bank Sta=4996.2,5002.2
Exp/Cntr=0.3,0.1

Type RM Length L Ch R = 1,8450,631,631,631
BEGIN DESCRIPTION:
UNT099 IN CCTC 13.0
END DESCRIPTION:
XS GIS Cut Line= 3
      3539175.04     10644079.96      3539379.04     10644392.47
      3539911.38     10644786.32
#Sta/Elev= 30
  4541.7  374.68  4559.5  372.57  4598.5  371.97  4632.0  369.51  4653.1  366.57
  4706.6  361.70  4719.5  360.70  4725.5  359.41  4776.8  356.48  4797.9  357.24
  4855.2  356.34  4977.8  356.78  4985.4  356.49  4991.6  352.05  4997.0  351.26
  4999.8  350.76  5003.0  351.26  5006.2  351.28  5014.6  356.83  5020.8  357.12
  5106.4  355.51  5141.9  355.96  5171.5  357.44  5242.1  359.99  5306.8  363.38
  5471.7  373.45  5492.6  372.83  5500.3  375.21  5507.2  376.03  5577.1  379.57
#Mann=6,-1,0
  4541.7    0.05       0  4598.5    0.16       0  4706.6    0.12       0
  4997.0    0.07       0  5003.0    0.12       0  5171.5    0.16       0
Bank Sta=4997,5003
Exp/Cntr=0.3,0.1

Type RM Length L Ch R = 1,7819,151,151,151
BEGIN DESCRIPTION:
UNT099 IN CCTC 12.0
END DESCRIPTION:
XS GIS Cut Line= 3
      3539093.62     10643743.88      3539309.52     10645333.62
      3540183.38     10645767.32
#Sta/Elev= 30
  3868.1  380.44  3949.9  378.27  4244.9  379.04  4249.9  376.27  4308.4  376.27
  4389.2  365.37  4513.0  359.19  4602.7  356.86  4727.7  355.83  4876.7  354.47
  4964.4  354.12  4991.9  351.16  4994.7  350.66  4997.9  351.16  5035.0  354.31
  5199.8  354.86  5208.7  354.71  5477.0  355.15  5483.7  353.11  5583.5  358.84
  5762.8  363.20  5835.6  367.15  5896.8  374.53  5953.3  374.44  5970.1  377.94
  6030.7  376.11  6053.1  377.68  6075.4  384.15  6104.5  385.91  6448.0  399.84
#Mann=9,-1,0
  3868.1    0.05       0  4513.0    0.16       0  4602.7    0.12       0
  4727.7    0.16       0  4876.7    0.12       0  4991.9    0.07       0
  4997.9    0.12       0  5199.8    0.12       0  5208.7    0.16       0
Bank Sta=4991.9,4997.9
Exp/Cntr=0.3,0.1

Type RM Length L Ch R = 1,7668,443,443,443
BEGIN DESCRIPTION:
UNT099 IN CCTC 11.0
END DESCRIPTION:
XS GIS Cut Line= 6
      3538963.76     10643619.01      3539114.72     10644850.71
      3539098.01     10644898.18      3539142.87     10644955.47
      3539220.27     10645533.00      3540086.01     10645914.46
#Sta/Elev= 30
  3695.7  387.47  3864.8  372.85  4096.8  367.11  4200.8  369.56  4361.2  361.28
  4685.5  357.60  4857.5  355.53  4933.4  350.03  4936.2  353.95  4978.5  341.01
  5017.3  339.42  5020.1  338.92  5023.3  339.42  5027.9  347.44  5048.8  343.71
  5056.3  356.20  5146.5  351.16  5151.5  359.61  5176.1  354.93  5389.7  354.23
  5480.5  358.82  5520.8  352.73  5647.1  353.48  5655.3  355.03  5673.2  371.40
  5709.6  370.37  5748.6  354.33  5975.0  360.18  6135.8  375.33  6590.8  395.81
#Mann=10,-1,0
  3695.7    0.05       0  3864.8    0.16       0  4096.8    0.05       0
  4361.2    0.16       0  4685.5    0.12       0  4857.5    0.16       0
  5017.3    0.07       0  5023.3    0.16       0  5176.1    0.12       0
  5389.7    0.16       0
Bank Sta=5017.3,5023.3
Exp/Cntr=0.3,0.1

Type RM Length L Ch R = 1,7225,812,812,812
BEGIN DESCRIPTION:
UNT099 IN CCTC 10.0
END DESCRIPTION:
XS GIS Cut Line= 4
      3538575.22     10644818.68      3539103.00     10645388.13
      3539168.28     10645676.29      3539848.17     10646097.37
#Sta/Elev= 30
  4453.5  375.76  4863.3  352.52  4953.0  351.88  4974.0  348.13  4988.2  334.13
  4999.3  333.77  5002.1  333.27  5005.3  333.77  5016.5  340.32  5030.7  343.42
  5044.8  352.58  5314.1  348.90  5435.2  350.67  5601.3  350.95  5609.3  352.19
  5616.7  357.56  5638.0  360.09  5644.6  365.82  5653.3  368.19  5668.1  370.37
  5685.6  368.27  5695.9  368.22  5703.4  360.22  5725.7  355.30  5979.4  359.71
  6068.0  365.38  6079.9  369.73  6179.0  374.46  6260.1  377.68  6325.1  379.37
#Mann=9,-1,0
  4453.5    0.16       0  4863.3    0.12       0  4999.3    0.07       0
  5005.3    0.12       0  5435.2    0.16       0  5685.6    0.05       0
  5725.7    0.16       0  6179.0    0.12       0  6260.1    0.16       0
Bank Sta=4999.3,5005.3
Exp/Cntr=0.3,0.1

Type RM Length L Ch R = 1,6413,450,450,450
BEGIN DESCRIPTION:
UNT099 IN CCTC 9.0
END DESCRIPTION:
XS GIS Cut Line= 3
      3538443.27     10645756.19      3538978.00     10645971.47
      3539353.00     10646464.53
#Sta/Elev= 30
  4538.8  369.85  4556.4  368.48  4591.9  368.45  4869.0  349.90  4922.9  347.83
  4933.0  348.55  4946.9  347.98  4955.3  346.70  4962.6  336.71  4968.0  336.22
  4976.8  338.71  4986.8  343.04  4995.4  331.92  4998.1  331.42  5001.4  331.92
  5009.2  332.46  5021.7  338.03  5040.5  348.87  5151.3  348.57  5158.4  348.39
  5164.7  345.93  5187.5  348.41  5222.8  347.35  5372.6  348.12  5451.5  349.02
  5507.4  350.96  5622.1  354.26  5701.1  354.44  5721.9  356.48  5734.7  356.33
#Mann=5,-1,0
  4538.8    0.16       0  4946.9    0.12       0  4995.4    0.07       0
  5001.4    0.12       0  5507.4    0.16       0
Bank Sta=4995.4,5001.4
Exp/Cntr=0.3,0.1

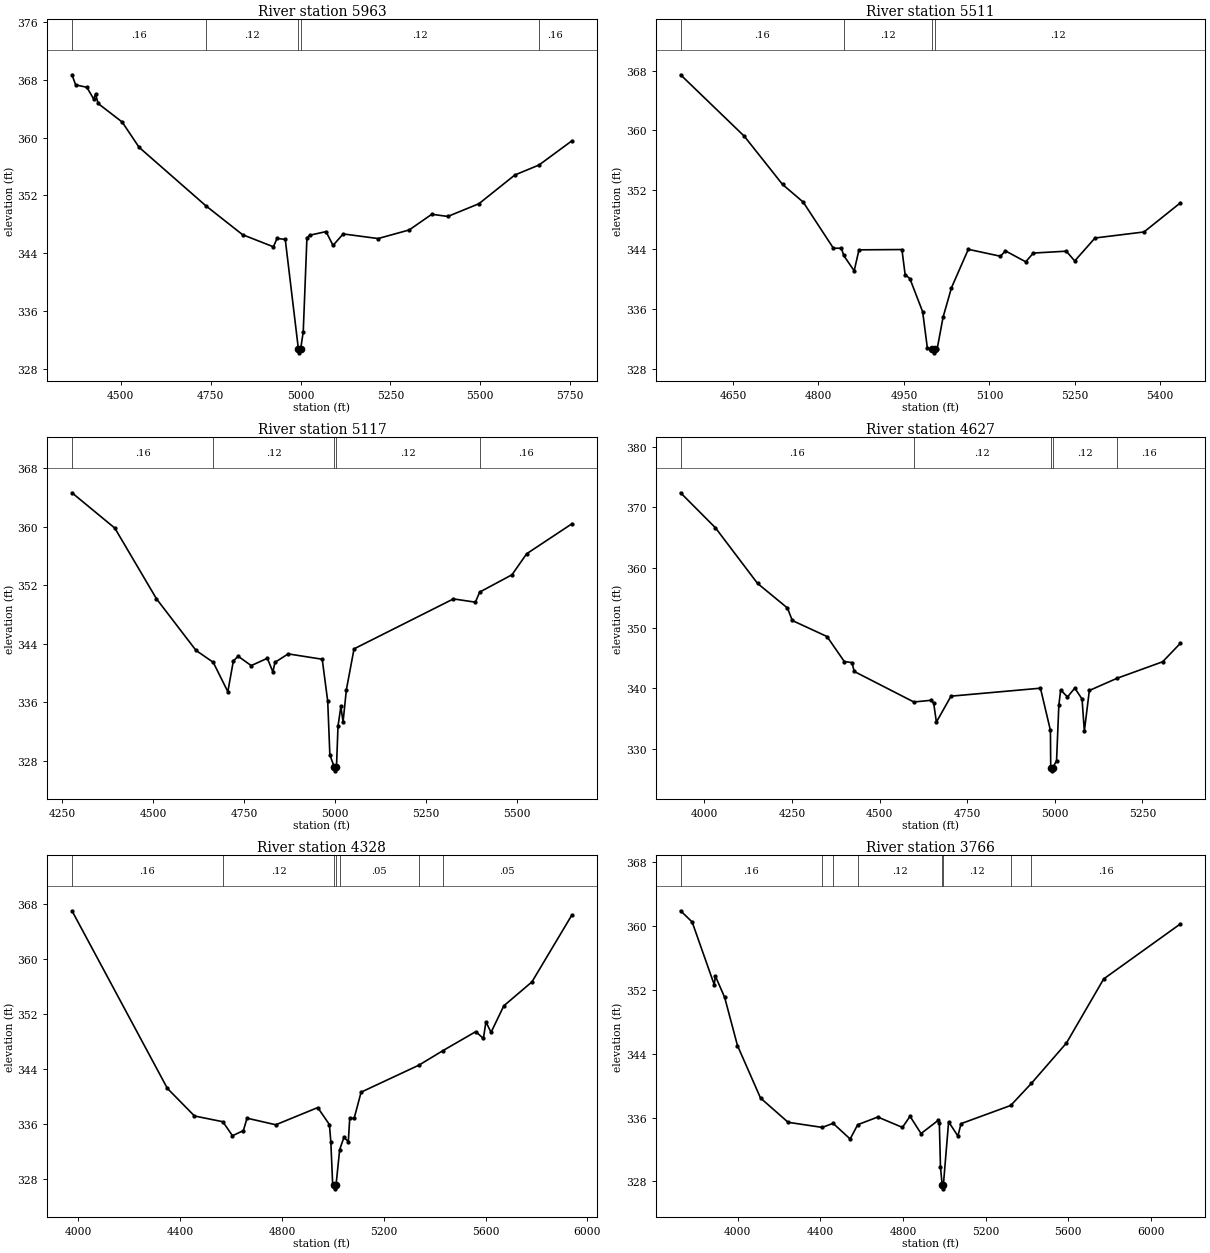
Type RM Length L Ch R = 1,5963,452,452,452
BEGIN DESCRIPTION:
UNT099 IN CCTC 8.0
END DESCRIPTION:
XS GIS Cut Line= 3
      3538269.67     10646138.13      3538998.83     10646339.52
      3539359.92     10646860.32
#Sta/Elev= 30
  4364.3  368.69  4374.6  367.29  4405.7  366.96  4424.8  365.33  4430.0  366.03
  4436.9  364.72  4503.9  362.15  4551.0  358.65  4736.1  350.58  4838.9  346.55
  4924.5  344.88  4934.8  346.04  4957.5  345.90  4994.1  330.70  4996.8  330.20
  5000.1  330.70  5007.5  333.09  5017.8  346.13  5026.2  346.49  5070.9  346.98
  5090.4  345.07  5118.6  346.66  5215.7  346.02  5302.2  347.21  5365.0  349.38
  5409.6  349.08  5496.1  350.84  5596.1  354.82  5663.3  356.20  5754.5  359.54
#Mann=5,-1,0
  4364.3    0.16       0  4736.1    0.12       0  4994.1    0.07       0
  5000.1    0.12       0  5663.3    0.16       0
Bank Sta=4994.1,5000.1
Exp/Cntr=0.3,0.1

Type RM Length L Ch R = 1,5511,394,394,394
BEGIN DESCRIPTION:
UNT099 IN CCTC 7.0
END DESCRIPTION:
XS GIS Cut Line= 3
      3538349.60     10646510.19      3538749.61     10646710.19
      3539099.58     10646960.17
#Sta/Elev= 30
  4558.0  367.44  4669.8  359.20  4736.9  352.73  4773.2  350.36  4826.3  344.16
  4840.3  344.17  4844.3  343.20  4862.7  341.13  4871.1  343.95  4946.5  343.99
  4952.1  340.64  4960.5  340.08  4982.9  335.64  4991.2  330.74  4999.4  330.63
  5002.2  330.13  5005.4  330.63  5008.3  330.63  5018.7  334.91  5033.5  338.87
  5063.0  344.02  5119.5  343.09  5128.1  343.81  5163.7  342.35  5177.3  343.52
  5235.0  343.77  5249.8  342.46  5285.4  345.54  5371.4  346.35  5435.3  350.26
#Mann=4,-1,0
  4558.0    0.16       0  4844.3    0.12       0  4999.4    0.07       0
  5005.4    0.12       0
Bank Sta=4999.4,5005.4
Exp/Cntr=0.3,0.1

Type RM Length L Ch R = 1,5117,490,490,490
BEGIN DESCRIPTION:
UNT099 IN CCTC 6.0
END DESCRIPTION:
XS GIS Cut Line= 3
      3538186.87     10646660.25      3538935.61     10647148.55
      3539413.04     10647202.80
#Sta/Elev= 30
  4276.4  364.66  4394.2  359.83  4508.8  350.16  4617.4  343.11  4664.8  341.48
  4705.0  337.46  4720.1  341.66  4733.3  342.31  4769.2  341.03  4813.6  342.03
  4828.8  340.17  4834.7  341.48  4870.9  342.63  4964.5  341.90  4979.6  336.16
  4985.5  328.84  4997.7  327.14  5000.4  326.64  5003.7  327.14  5007.9  332.76
  5015.8  335.44  5021.8  333.32  5030.9  337.73  5052.0  343.32  5325.3  350.15
  5385.7  349.70  5397.4  351.08  5486.3  353.45  5526.6  356.32  5650.8  360.41
#Mann=5,-1,0
  4276.4    0.16       0  4664.8    0.12       0  4997.7    0.07       0
  5003.7    0.12       0  5397.4    0.16       0
Bank Sta=4997.7,5003.7
Exp/Cntr=0.3,0.1

Type RM Length L Ch R = 1,4627,299,299,299
BEGIN DESCRIPTION:
UNT099 IN CCTC 5.0
END DESCRIPTION:
XS GIS Cut Line= 3
      3537799.63     10646760.21      3538599.61     10647460.19
      3538949.62     10647560.19
#Sta/Elev= 30
  3931.8  372.40  4031.0  366.62  4151.5  357.38  4236.9  353.30  4250.7  351.23
  4349.9  348.57  4399.2  344.43  4421.0  344.25  4427.7  342.78  4597.8  337.72
  4647.9  338.01  4654.5  337.50  4662.1  334.39  4703.9  338.69  4959.2  340.01
  4987.7  333.01  4988.5  326.81  4991.2  326.31  4994.5  326.81  5005.2  328.02
  5011.7  337.18  5016.9  339.72  5036.4  338.55  5057.2  340.03  5078.0  338.21
  5084.5  332.89  5098.8  339.63  5177.8  341.65  5308.1  344.39  5358.8  347.46
#Mann=5,-1,0
  3931.8    0.16       0  4597.8    0.12       0  4988.5    0.07       0
  4994.5    0.12       0  5177.8    0.16       0
Bank Sta=4988.5,4994.5
Exp/Cntr=0.3,0.1

Type RM Length L Ch R = 1,4328,562,562,562
BEGIN DESCRIPTION:
UNT099 IN CCTC 4.0
END DESCRIPTION:
XS GIS Cut Line= 4
      3537774.76     10646965.90      3538388.93     10647686.41
      3538562.54     10647766.70      3539385.90     10647697.37
#Sta/Elev= 30
  3974.8  366.95  4349.7  341.14  4456.2  337.13  4567.7  336.29  4605.6  334.26
  4648.4  335.00  4662.7  336.81  4775.8  335.85  4940.6  338.35  4986.5  335.88
  4992.0  333.40  4999.4  327.10  5006.4  327.04  5009.2  326.54  5012.4  327.04
  5026.8  332.24  5043.5  334.01  5060.8  333.41  5066.3  336.78  5083.7  336.78
  5111.0  340.59  5338.5  344.52  5432.3  346.62  5561.5  349.38  5591.6  348.40
  5601.6  350.80  5621.7  349.28  5671.9  353.14  5782.3  356.61  5939.1  366.32
#Mann=7,-1,0
  3974.8    0.16       0  4567.7    0.12       0  5006.4    0.07       0
  5012.4    0.12       0  5026.8    0.05       0  5338.5    0.16       0
  5432.3    0.05       0
Bank Sta=5006.4,5012.4
Exp/Cntr=0.3,0.1

Type RM Length L Ch R = 1,3766,775,775,775
BEGIN DESCRIPTION:
UNT099 IN CCTC 3.0
END DESCRIPTION:
XS GIS Cut Line= 4
      3537651.06     10647052.68      3538180.59     10648133.46
      3538312.97     10648198.56      3539380.66     10648246.30
#Sta/Elev= 30
  3723.2  361.88  3779.2  360.48  3886.1  352.63  3891.7  353.70  3936.7  351.03
  3998.6  345.01  4110.2  338.44  4243.8  335.40  4409.0  334.76  4461.5  335.27
  4544.2  333.31  4580.7  335.10  4678.1  336.06  4797.3  334.76  4834.0  336.15
  4887.3  333.99  4970.2  335.64  4975.9  335.31  4981.4  329.81  4989.5  327.57
  4992.2  327.07  4995.5  327.57  5020.8  335.46  5065.8  333.68  5080.9  335.23
  5321.6  337.51  5421.7  340.28  5591.4  345.33  5771.6  353.35  6143.0  360.24
#Mann=8,-1,0
  3723.2    0.16       0  4409.0    0.12       0  4461.5    0.16       0
  4580.7    0.12       0  4989.5    0.07       0  4995.5    0.12       0
  5321.6    0.05       0  5421.7    0.16       0
Bank Sta=4989.5,4995.5
Exp/Cntr=0.3,0.1

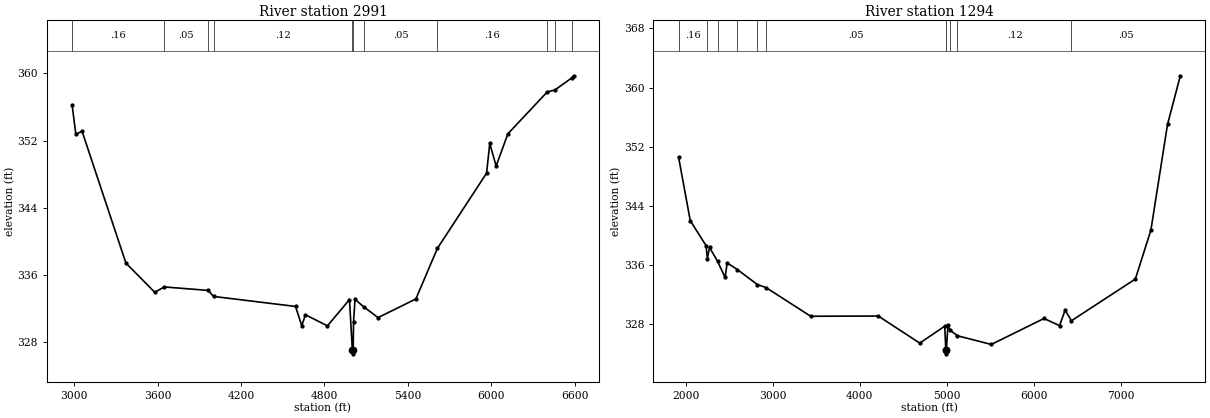
Type RM Length L Ch R = 1,2991,1697,1697,1697
BEGIN DESCRIPTION:
UNT099 IN CCTC 2.0
END DESCRIPTION:
XS GIS Cut Line= 4
      3537503.31     10647083.43      3537774.58     10648776.15
      3538284.57     10648993.17      3539499.82     10648428.94
#Sta/Elev= 30
  2984.9  356.26  3012.0  352.76  3056.9  353.10  3371.9  337.43  3579.1  333.95
  3648.5  334.58  3962.9  334.17  4002.6  333.45  4591.9  332.26  4636.8  329.96
  4662.8  331.27  4821.6  329.95  4979.7  333.08  5000.4  327.12  5003.1  326.62
  5006.4  327.12  5009.0  330.45  5019.8  333.10  5080.6  332.24  5185.1  330.93
  5457.2  333.15  5611.7  339.16  5965.6  348.12  5988.5  351.66  6034.3  348.97
  6119.0  352.81  6401.6  357.78  6457.1  358.02  6578.8  359.46  6593.3  359.71
#Mann=11,-1,0
  2984.9    0.16       0  3648.5    0.05       0  3962.9    0.16       0
  4002.6    0.12       0  5000.4    0.07       0  5006.4    0.12       0
  5080.6    0.05       0  5611.7    0.16       0  6401.6    0.05       0
  6457.1    0.16       0  6578.8    0.05       0
Bank Sta=5000.4,5006.4
Exp/Cntr=0.3,0.1

Type RM Length L Ch R = 1,1294,0,0,0
BEGIN DESCRIPTION:
UNT099 IN CCTC 1.0
END DESCRIPTION:
XS GIS Cut Line= 4
      3537156.10     10647126.80      3536787.17     10649872.07
      3537427.36     10650219.30      3539216.17     10648831.61
#Sta/Elev= 30
  1920.0  350.62  2054.6  342.01  2236.4  338.63  2250.4  336.89  2276.6  338.39
  2368.5  336.50  2454.9  334.34  2478.4  336.30  2597.0  335.39  2825.8  333.37
  2924.3  332.97  3437.4  329.09  4213.8  329.12  4690.0  325.46  4977.1  327.75
  4989.2  324.51  4991.9  324.01  4995.2  324.51  5014.0  327.87  5036.3  327.23
  5123.4  326.45  5511.3  325.28  6117.2  328.79  6295.2  327.82  6359.4  329.92
  6431.6  328.48  7166.0  334.12  7344.3  340.73  7535.3  355.03  7682.2  361.59
#Mann=11,-1,0
  1920.0    0.16       0  2250.4    0.12       0  2368.5    0.16       0
  2597.0    0.12       0  2825.8    0.16       0  2924.3    0.05       0
  4989.2    0.03       0  4995.2    0.05       0  5036.3    0.16       0
  5123.4    0.12       0  6431.6    0.05       0
Bank Sta=4989.2,4995.2
Exp/Cntr=0.3,0.1

Chan Stop Cuts=-1