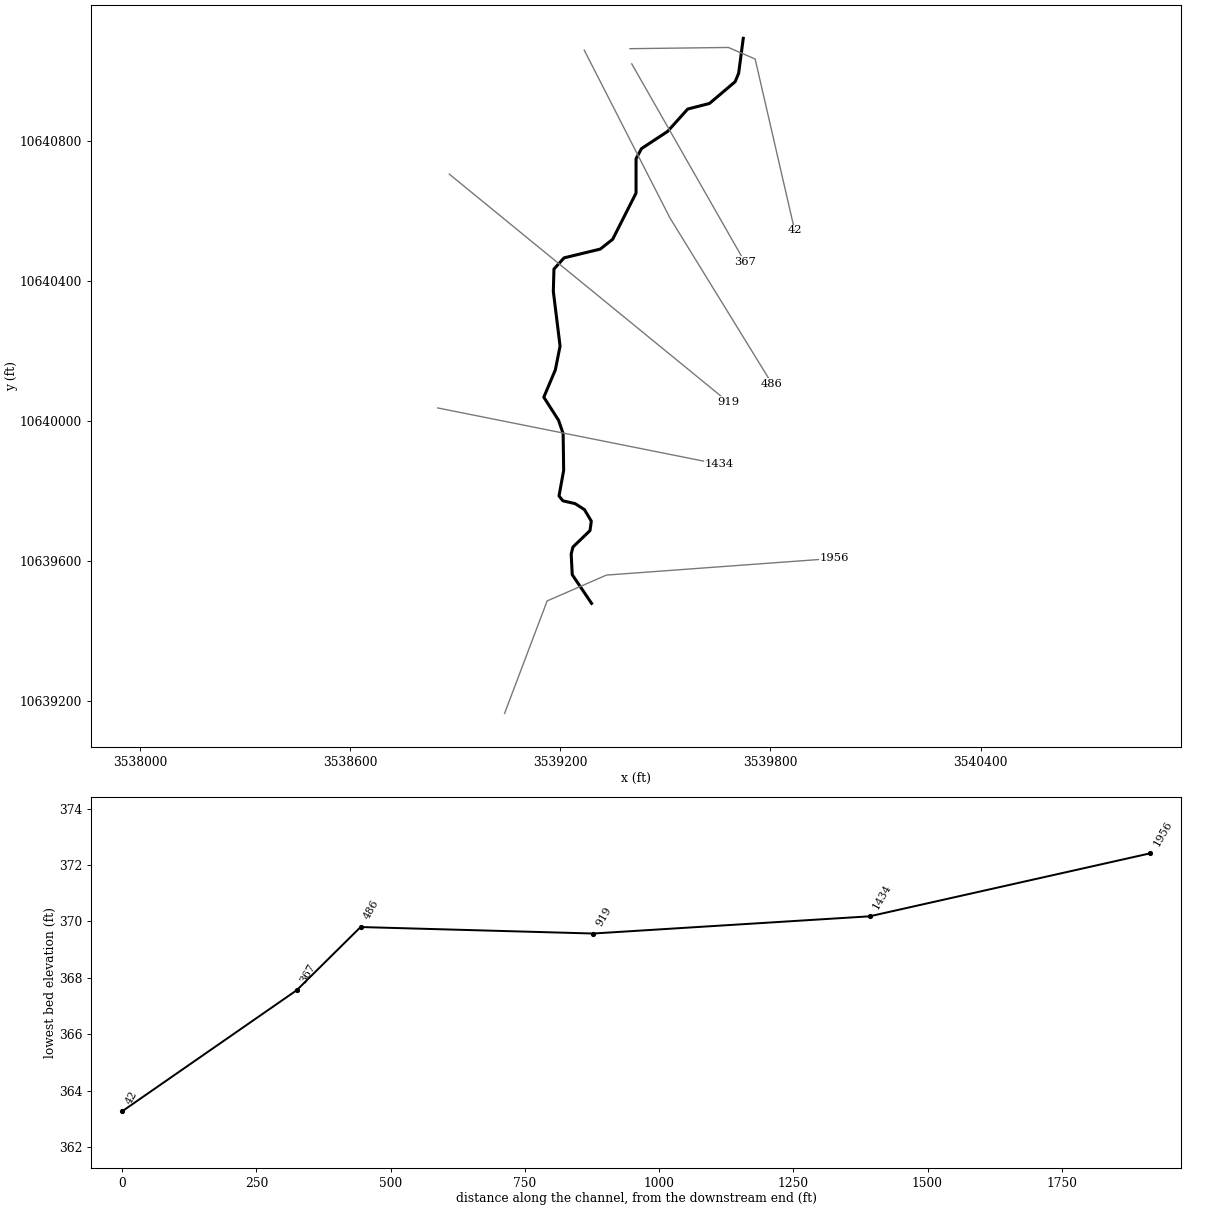
--- UNT100 IN CCTC.prj (project) ---

Proj Title=UNT100 IN CCTC Base Level Engineering
Current Plan=p01
Default Exp/Contr=0.3,0.1
English Units
Geom File=g01
Flow File=f01
Plan File=p01
BEGIN DESCRIPTION:
UNT100 IN CCTC
END DESCRIPTION:

--- UNT100 IN CCTC.p01 (plan) ---

Plan Title=Multiple Run
Short Identifier=Multiple
Geom File=g01
Flow File=f01
Subcritical Flow
K Sum by GR= 0
Std Step Tol= 0.01
Critical Tol= 0.01
Num of Std Step Trials= 20
Max Error Tol= 0.3
Flow Tol Ratio= 0.001
Split Flow NTrial= 30
Split Flow Tol= 0.02
Split Flow Ratio= 0.02
Log Output Level= 0
Friction Slope Method= 1
Unsteady Friction Slope Method= 2
Unsteady Bridges Friction Slope Method= 1
Parabolic Critical Depth
Global Vel Dist=  1 , 1 , 1
Global Log Level= 0
CheckData=True
Encroach Param= -1, 0, 0, 0
BEGIN DESCRIPTION:
Multiple Run
END DESCRIPTION:

--- UNT100 IN CCTC.f01 (steady flow) ---

Flow Title=Multiple
Number of Profiles=7
Profile Names=10-year,25-year,50-year,1pct_min,100-year,1pct_plu,500-year
River Rch & RM= UNT100 IN CCTC,Reach-1,1956
    1500    2082    2567    2310    3124    4225    4613
Boundary for River Rch & Prof#=UNT100 IN CCTC,Reach-1,1
Up Type=0
Dn Type=3
Dn Slope=0.005
Boundary for River Rch & Prof#=UNT100 IN CCTC,Reach-1,2
Up Type=0
Dn Type=3
Dn Slope=0.005
Boundary for River Rch & Prof#=UNT100 IN CCTC,Reach-1,3
Up Type=0
Dn Type=3
Dn Slope=0.005
Boundary for River Rch & Prof#=UNT100 IN CCTC,Reach-1,4
Up Type=0
Dn Type=3
Dn Slope=0.005
Boundary for River Rch & Prof#=UNT100 IN CCTC,Reach-1,5
Up Type=0
Dn Type=3
Dn Slope=0.005
Boundary for River Rch & Prof#=UNT100 IN CCTC,Reach-1,6
Up Type=0
Dn Type=3
Dn Slope=0.005
Boundary for River Rch & Prof#=UNT100 IN CCTC,Reach-1,7
Up Type=0
Dn Type=3
Dn Slope=0.005

--- UNT100 IN CCTC.g01 (geometry) ---

Geom Title=Existing Conditions

River Reach=UNT100 IN CCTC,Reach-1
Reach XY= 30
      3539289.00     10639480.00      3539233.75     10639562.00
      3539230.75     10639621.00      3539235.75     10639641.00
      3539284.50     10639688.00      3539288.25     10639715.00
      3539268.50     10639748.00      3539242.00     10639765.00
      3539207.00     10639773.00      3539196.00     10639787.00
      3539209.25     10639860.00      3539207.75     10639965.00
      3539194.75     10640003.00      3539152.50     10640069.00
      3539185.50     10640147.00      3539199.00     10640215.00
      3539179.75     10640371.00      3539181.50     10640435.00
      3539210.50     10640467.00      3539313.75     10640492.00
      3539349.25     10640520.00      3539416.00     10640652.00
      3539416.00     10640750.00      3539431.50     10640779.00
      3539506.00     10640828.00      3539563.50     10640892.00
      3539625.75     10640908.00      3539699.00     10640970.00
      3539709.00     10640994.00      3539722.25     10641094.00

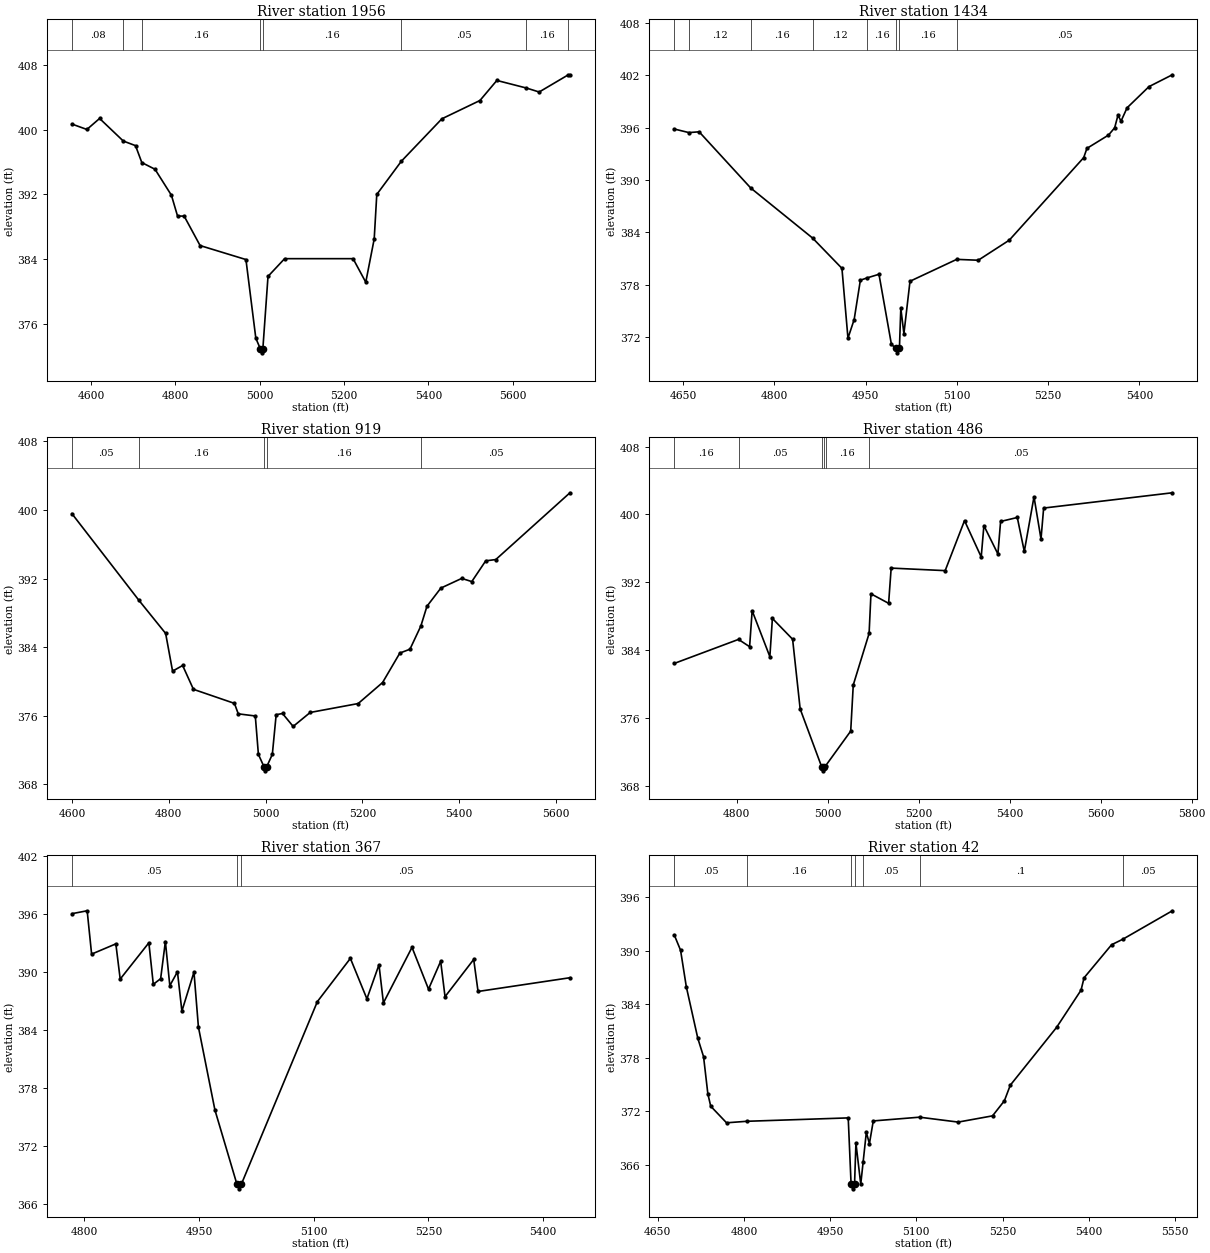
Type RM Length L Ch R = 1,1956,522,522,522
BEGIN DESCRIPTION:
UNT100 IN CCTC 3.0
END DESCRIPTION:
XS GIS Cut Line= 4
      3539040.53     10639165.89      3539162.06     10639487.07
      3539331.33     10639560.86      3539982.42     10639608.60
#Sta/Elev= 30
  4554.8  400.69  4590.4  400.02  4620.5  401.38  4676.7  398.59  4705.7  398.02
  4720.6  395.93  4751.9  395.10  4790.8  391.89  4805.3  389.32  4821.0  389.31
  4858.8  385.67  4967.5  383.94  4990.9  374.22  5001.6  372.91  5004.4  372.41
  5007.6  372.91  5019.8  381.86  5059.2  384.05  5221.5  384.05  5251.6  381.14
  5271.6  386.49  5277.7  391.99  5335.9  396.09  5432.1  401.34  5522.3  403.60
  5562.4  406.08  5632.6  405.14  5662.7  404.65  5731.6  406.77  5735.7  406.78
#Mann=8,-1,0
  4554.8    0.08       0  4676.7    0.05       0  4720.6    0.16       0
  5001.6    0.07       0  5007.6    0.16       0  5335.9    0.05       0
  5632.6    0.16       0  5731.6    0.05       0
Bank Sta=5001.6,5007.6
Exp/Cntr=0.3,0.1

Type RM Length L Ch R = 1,1434,515,515,515
BEGIN DESCRIPTION:
Mapping XS 82e27d91
END DESCRIPTION:
XS GIS Cut Line= 2
      3538849.53     10640038.29      3539652.52     10639877.69
#Sta/Elev= 30
  4635.3  395.85  4659.4  395.44  4676.2  395.53  4761.1  389.08  4862.8  383.34
  4911.0  379.87  4920.9  371.86  4931.1  374.00  4941.3  378.51  4952.6  378.78
  4971.9  379.19  4992.3  371.17  4999.5  370.68  5002.3  370.18  5005.5  370.68
  5007.8  375.29  5012.9  372.38  5022.9  378.39  5099.7  380.90  5135.1  380.80
  5186.1  383.10  5308.5  392.57  5313.8  393.63  5349.2  395.15  5359.4  395.99
  5364.8  397.42  5369.9  396.76  5379.8  398.28  5415.8  400.71  5454.2  402.07
#Mann=8,-1,0
  4635.3    0.05       0  4659.4    0.12       0  4761.1    0.16       0
  4862.8    0.12       0  4952.6    0.16       0  4999.5    0.07       0
  5005.5    0.16       0  5099.7    0.05       0
Bank Sta=4999.5,5005.5
Exp/Cntr=0.3,0.1

Type RM Length L Ch R = 1,919,433,433,433
BEGIN DESCRIPTION:
Mapping XS 020f0caf
END DESCRIPTION:
XS GIS Cut Line= 2
      3538882.63     10640706.07      3539679.42     10640055.10
#Sta/Elev= 30
  4600.0  399.58  4738.4  389.47  4793.7  385.60  4808.0  381.20  4828.8  381.86
  4851.1  379.08  4935.8  377.44  4943.7  376.22  4978.9  375.97  4985.3  371.49
  4996.7  370.07  4999.5  369.57  5002.7  370.07  5014.1  371.50  5022.0  376.12
  5035.1  376.26  5057.1  374.75  5092.3  376.38  5191.4  377.42  5241.8  379.87
  5277.5  383.31  5298.4  383.76  5321.0  386.48  5333.5  388.77  5362.2  390.89
  5405.3  392.02  5426.1  391.65  5454.9  394.07  5475.7  394.22  5628.9  402.01
#Mann=5,-1,0
  4600.0    0.05       0  4738.4    0.16       0  4996.7    0.07       0
  5002.7    0.16       0  5321.0    0.05       0
Bank Sta=4996.7,5002.7
Exp/Cntr=0.3,0.1

Type RM Length L Ch R = 1,486,119,119,119
BEGIN DESCRIPTION:
UNT100 IN CCTC 2.0
END DESCRIPTION:
XS GIS Cut Line= 3
      3539268.02     10641060.26      3539512.81     10640581.10
      3539804.49     10640107.12
#Sta/Elev= 30
  4662.9  382.45  4804.1  385.28  4828.5  384.42  4834.1  388.66  4873.0  383.25
  4878.6  387.75  4923.0  385.30  4939.6  377.09  4986.7  370.30  4989.4  369.80
  4992.7  370.30  4995.5  370.39  5050.7  374.48  5056.3  379.91  5091.1  385.98
  5095.2  390.65  5134.0  389.53  5139.6  393.68  5258.3  393.38  5300.8  399.27
  5337.5  394.99  5343.4  398.68  5374.2  395.34  5380.1  399.17  5416.8  399.64
  5432.2  395.64  5453.5  402.08  5468.9  397.10  5474.7  400.75  5757.5  402.55
#Mann=6,-1,0
  4662.9    0.16       0  4804.1    0.05       0  4986.7    0.07       0
  4992.7    0.05       0  4995.5    0.16       0  5091.1    0.05       0
Bank Sta=4986.7,4992.7
Exp/Cntr=0.3,0.1

Type RM Length L Ch R = 1,367,325,325,325
BEGIN DESCRIPTION:
Mapping XS 20a164b9
END DESCRIPTION:
XS GIS Cut Line= 2
      3539403.78     10641021.03      3539726.64     10640455.15
#Sta/Elev= 30
  4783.6  396.00  4803.6  396.30  4809.4  391.82  4841.1  392.88  4846.8  389.24
  4884.3  392.99  4890.1  388.70  4899.7  389.28  4905.9  393.12  4911.7  388.56
  4921.7  389.99  4927.5  385.93  4943.3  389.96  4949.1  384.29  4970.7  375.71
  4999.4  368.06  5002.2  367.56  5005.4  368.06  5104.7  386.91  5147.9  391.38
  5169.5  387.20  5185.3  390.72  5191.1  386.78  5228.5  392.52  5250.1  388.20
  5266.0  391.08  5271.7  387.42  5309.2  391.27  5314.9  387.96  5435.1  389.38
#Mann=3,-1,0
  4783.6    0.05       0  4999.4   0.035       0  5005.4    0.05       0
Bank Sta=4999.4,5005.4
Exp/Cntr=0.3,0.1

Type RM Length L Ch R = 1,42,0,0,0
BEGIN DESCRIPTION:
UNT100 IN CCTC 1.0
END DESCRIPTION:
XS GIS Cut Line= 4
      3539398.60     10641064.44      3539679.82     10641067.91
      3539756.21     10641034.92      3539869.06     10640545.31
#Sta/Elev= 30
  4678.6  391.76  4689.6  390.04  4699.6  385.94  4719.6  380.16  4729.6  378.10
  4737.1  373.92  4742.1  372.54  4769.6  370.68  4805.0  370.85  4981.4  371.23
  4986.4  363.77  4989.1  363.27  4992.4  363.77  4994.8  368.40  5003.2  363.79
  5007.4  366.31  5012.9  369.61  5018.3  368.34  5025.0  370.89  5105.5  371.31
  5172.8  370.76  5232.6  371.46  5253.2  373.15  5263.5  374.90  5344.0  381.38
  5386.6  385.56  5391.9  386.95  5439.8  390.66  5459.4  391.28  5545.5  394.47
#Mann=7,-1,0
  4678.6    0.05       0  4805.0    0.16       0  4986.4    0.07       0
  4992.4    0.16       0  5007.4    0.05       0  5105.5     0.1       0
  5459.4    0.05       0
Bank Sta=4986.4,4992.4
Exp/Cntr=0.3,0.1

Chan Stop Cuts=-1