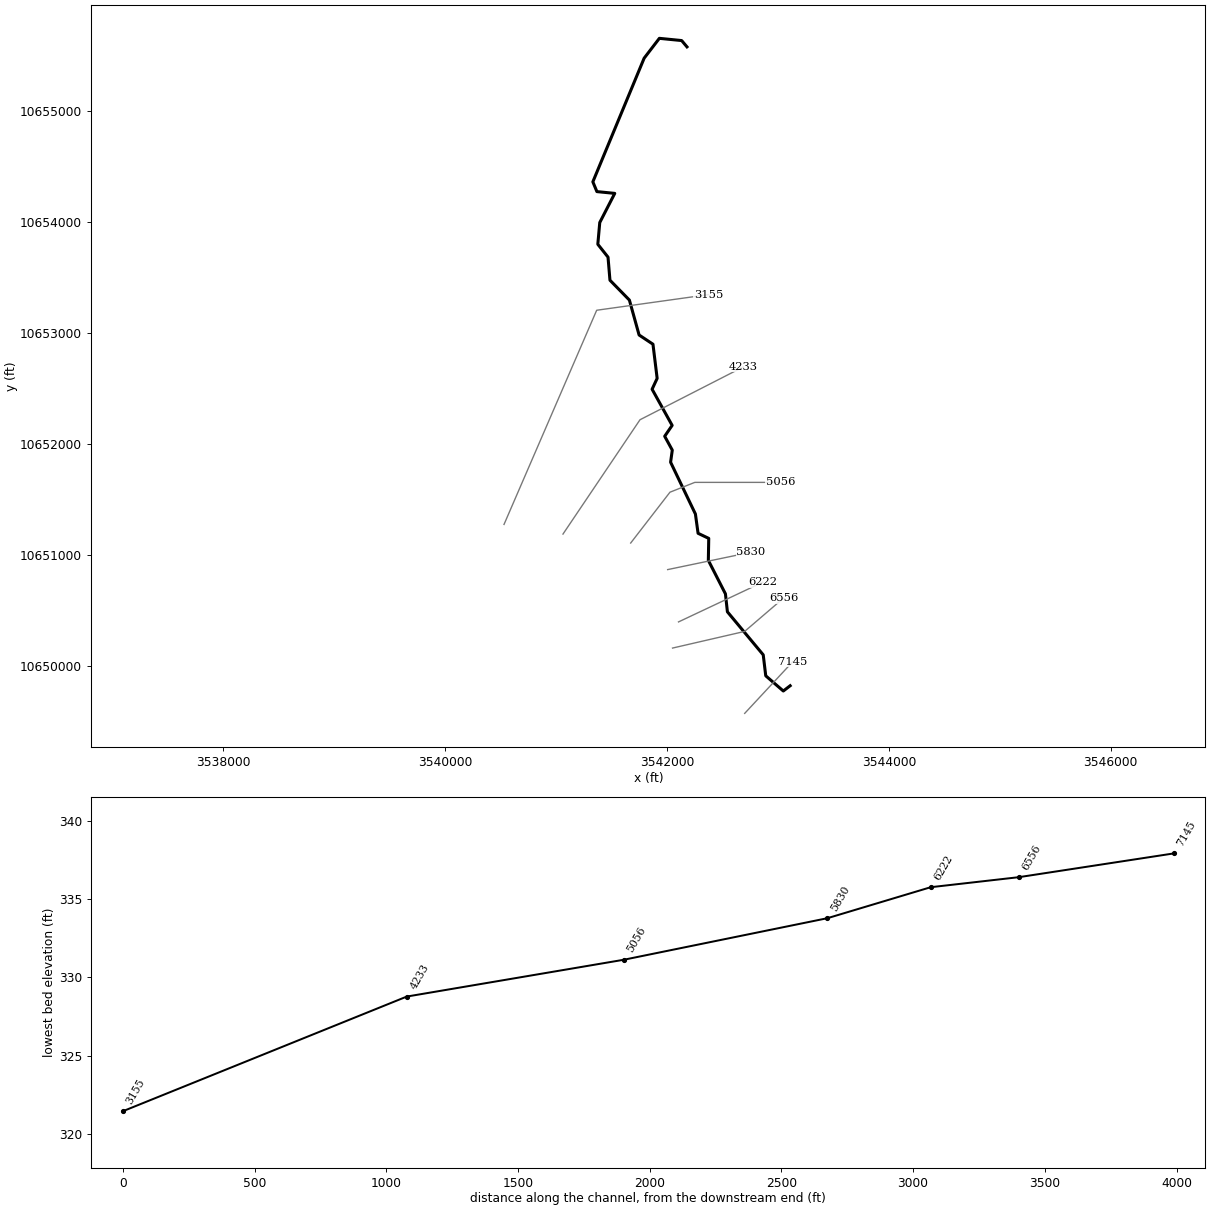
--- UNT101 IN CCTC.prj (project) ---

Proj Title=UNT101 IN CCTC Base Level Engineering
Current Plan=p01
Default Exp/Contr=0.3,0.1
English Units
Geom File=g01
Flow File=f01
Plan File=p01
Y Axis Title=Elevation
X Axis Title(PF)=Main Channel Distance
X Axis Title(XS)=Station
BEGIN DESCRIPTION:
UNT101 IN CCTC
END DESCRIPTION:
DSS Export Rating Curves= 0
DSS Export Rating Curve Sorted= 0
DSS Export Volume Flow Curves= 0
DXF OffsetX= 0
DXF OffsetY= 0
DXF ScaleX= 1
DXF ScaleY= 10

--- UNT101 IN CCTC.p01 (plan) ---

Plan Title=Multiple Run
Short Identifier=Multiple
Geom File=g01
Flow File=f01
Subcritical Flow
K Sum by GR= 0
Std Step Tol= 0.01
Critical Tol= 0.01
Num of Std Step Trials= 20
Max Error Tol= 0.3
Flow Tol Ratio= 0.001
Split Flow NTrial= 30
Split Flow Tol= 0.02
Split Flow Ratio= 0.02
Log Output Level= 0
Friction Slope Method= 1
Unsteady Friction Slope Method= 2
Unsteady Bridges Friction Slope Method= 1
Parabolic Critical Depth
Global Vel Dist=  1 , 1 , 1
Global Log Level= 0
CheckData=True
Encroach Param= -1, 0, 0, 0
BEGIN DESCRIPTION:
Multiple Run
END DESCRIPTION:

--- UNT101 IN CCTC.f01 (steady flow) ---

Flow Title=Multiple
Number of Profiles=7
Profile Names=10-year,25-year,50-year,1pct_min,100-year,1pct_plu,500-year
River Rch & RM= UNT101 IN CCTC,Reach-1,7145
    1370    1883    2306    2061    2787    3770    4058
Boundary for River Rch & Prof#=UNT101 IN CCTC,Reach-1,1
Up Type=0
Dn Type=3
Dn Slope=0.005
Boundary for River Rch & Prof#=UNT101 IN CCTC,Reach-1,2
Up Type=0
Dn Type=3
Dn Slope=0.005
Boundary for River Rch & Prof#=UNT101 IN CCTC,Reach-1,3
Up Type=0
Dn Type=3
Dn Slope=0.005
Boundary for River Rch & Prof#=UNT101 IN CCTC,Reach-1,4
Up Type=0
Dn Type=3
Dn Slope=0.005
Boundary for River Rch & Prof#=UNT101 IN CCTC,Reach-1,5
Up Type=0
Dn Type=3
Dn Slope=0.005
Boundary for River Rch & Prof#=UNT101 IN CCTC,Reach-1,6
Up Type=0
Dn Type=3
Dn Slope=0.005
Boundary for River Rch & Prof#=UNT101 IN CCTC,Reach-1,7
Up Type=0
Dn Type=3
Dn Slope=0.005

--- UNT101 IN CCTC.g01 (geometry) ---

Geom Title=Existing Conditions
Program Version=4.10

River Reach=UNT101 IN CCTC  ,Reach-1
Reach XY= 30
      3543110.11     10649820.43      3543048.25       10649773.
        3542890.       10649910.      3542867.25       10650099.
      3542544.25       10650487.       3542526.5       10650649.
      3542372.25       10650951.        3542376.       10651149.
      3542279.75       10651195.      3542255.75       10651369.
        3542032.       10651836.      3542047.25       10651945.
      3541978.75       10652070.        3542046.       10652168.
      3541865.25       10652494.      3541910.75       10652592.
        3541873.       10652900.        3541748.       10652983.
       3541660.5       10653298.      3541485.25       10653477.
      3541467.75       10653685.      3541375.75       10653801.
      3541393.25       10653997.       3541528.5       10654260.
       3541367.5       10654276.        3541331.       10654364.
       3541793.5       10655479.      3541930.75       10655658.
      3542131.75       10655638.      3542179.75       10655581.

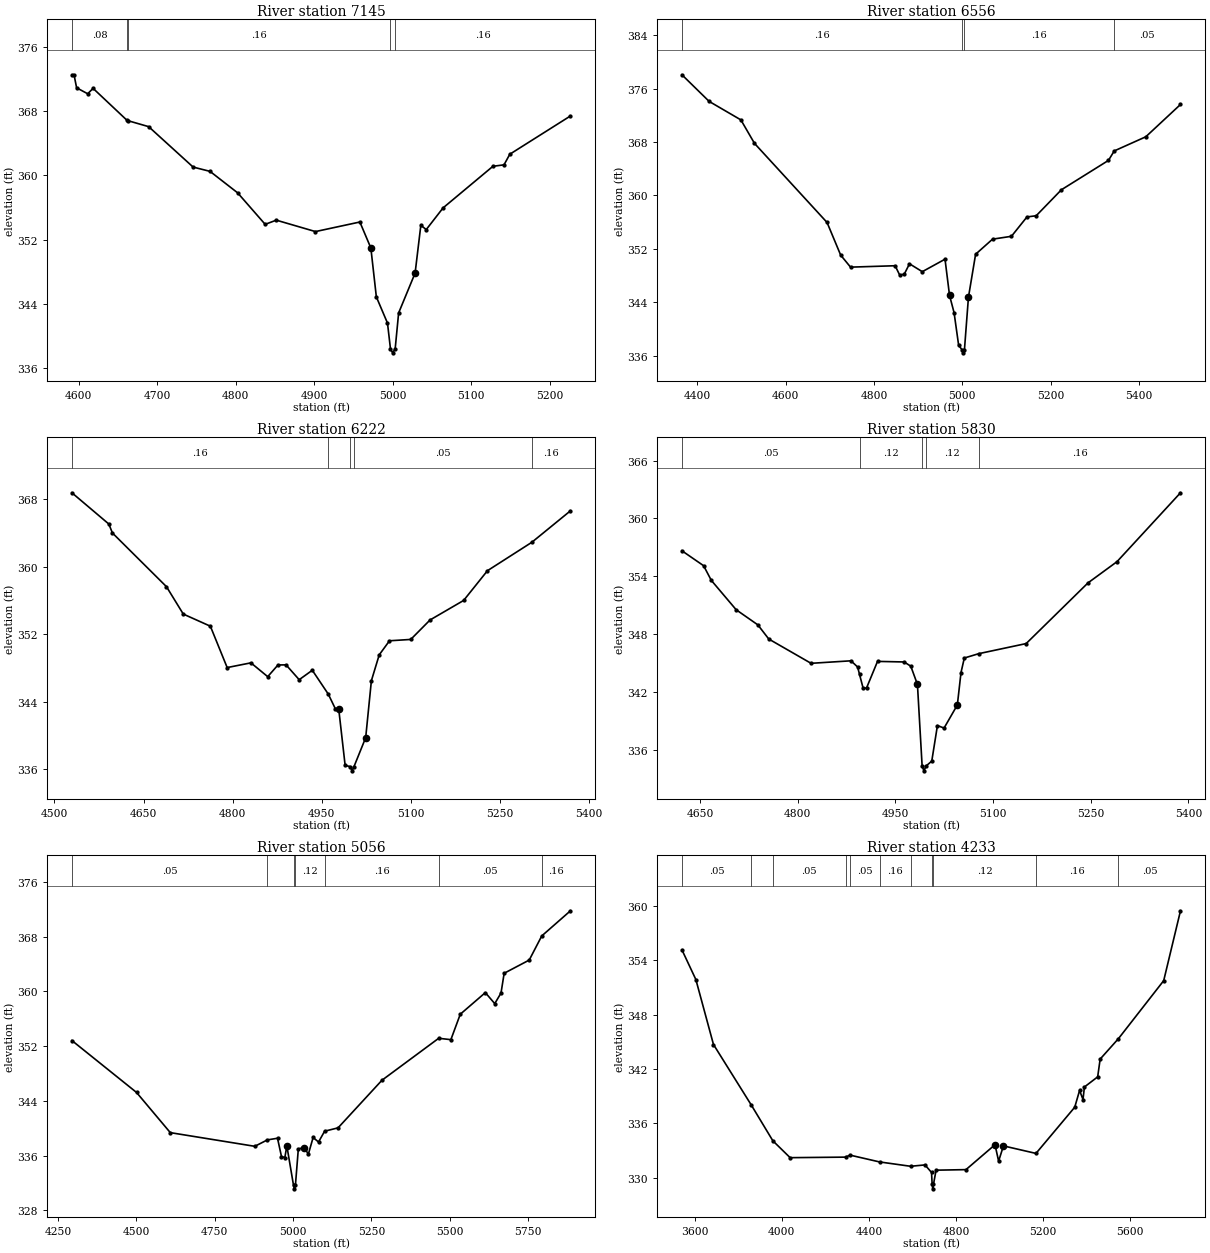
Type RM Length L Ch R = 1 ,7145    ,589,589,589
BEGIN DESCRIPTION:
UNT101 IN CCTC 7.0
END DESCRIPTION:
XS GIS Cut Line= 2
      3542700.13     10649571.25      3543132.91     10650036.49
#Sta/Elev= 30
  4591.3  372.51    4594  372.51  4597.3  370.89  4611.4  370.15  4618.3  370.82
  4661.6  366.84  4662.4  366.81  4689.1  366.06  4745.8  361.03  4767.3   360.5
  4802.5  357.83  4837.6  353.91  4851.8  354.43  4901.7  353.01  4958.3   354.2
  4972.3  350.97  4979.3  344.89  4993.5  341.63  4997.3  338.43  5000.1  337.93
  5003.3  338.43  5007.7  342.89  5028.7  347.85    5036  353.79  5042.9  353.26
  5064.4  355.96  5127.9  361.13    5142  361.31  5149.4  362.63  5226.7  367.39
#Mann= 5 ,-1 , 0
  4591.3     .08       0  4661.6     .05       0  4662.4     .16       0
  4997.3     .07       0  5003.3     .16       0
Bank Sta=4972.3,5028.7
XS Rating Curve= 0 ,0
Exp/Cntr=0.3,0.1

Type RM Length L Ch R = 1 ,6556    ,334,334,334
BEGIN DESCRIPTION:
UNT101 IN CCTC 6.0
END DESCRIPTION:
XS GIS Cut Line= 3
      3542049.59     10650160.18      3542699.61     10650310.19
      3543049.62      10650610.2
#Sta/Elev= 30
  4365.6  378.07  4427.2  374.08    4499  371.31  4529.8  367.79    4694  355.94
  4724.8  351.05  4747.1  349.25    4848  349.46  4858.2  348.08  4868.5  348.17
  4880.5  349.75  4909.5  348.57  4960.9  350.44  4971.1  345.02  4981.4  342.43
  4991.7  337.55  4998.9  336.91  5001.7  336.41  5004.9  336.91  5013.9  344.74
  5030.1  351.18  5068.4  353.44  5111.2  353.87  5146.3  356.77  5167.2  356.95
  5224.2  360.84  5330.7  365.24  5343.8  366.66  5415.2  368.78  5493.7  373.62
#Mann= 4 ,-1 , 0
  4365.6     .16       0  4998.9     .07       0  5004.9     .16       0
  5343.8     .05       0
Bank Sta=4971.1,5013.9
XS Rating Curve= 0 ,0
Exp/Cntr=0.3,0.1

Type RM Length L Ch R = 1 ,6222    ,392,392,392
BEGIN DESCRIPTION:
UNT101 IN CCTC 5.0
END DESCRIPTION:
XS GIS Cut Line= 2
      3542103.36      10650395.9      3542862.89     10650753.97
#Sta/Elev= 30
  4529.4  368.78  4591.6  365.07  4597.6  364.01  4688.7  357.63    4717  354.38
  4762.6  352.94  4790.9  348.03  4830.9  348.59  4859.2  346.95  4876.5  348.34
  4890.1  348.35  4912.2  346.59  4934.3  347.71  4961.1  344.89  4973.1  343.14
  4978.7  343.17  4989.6  336.41  4998.5  336.27  5001.2  335.77  5004.5  336.27
  5024.2  339.71  5033.8  346.47    5047  349.54  5064.3  351.21  5100.1  351.37
  5132.6  353.68  5189.2     356  5229.3  359.53  5304.2  362.91  5369.1  366.64
#Mann= 5 ,-1 , 0
  4529.4     .16       0  4961.1     .05       0  4998.5     .03       0
  5004.5     .05       0  5304.2     .16       0
Bank Sta=4978.7,5024.2
XS Rating Curve= 0 ,0
Exp/Cntr=0.3,0.1

Type RM Length L Ch R = 1 ,5830    ,774,774,774
BEGIN DESCRIPTION:
UNT101 IN CCTC 4.0
END DESCRIPTION:
XS GIS Cut Line= 2
       3542005.5     10650867.67      3542755.11     10651023.84
#Sta/Elev= 30
  4622.1  356.63  4655.4  355.08  4667.2  353.56  4705.4  350.51  4738.7  348.94
  4755.5  347.47  4820.4  344.95  4881.7  345.21  4891.9  344.57  4894.9  343.79
  4900.5  342.34  4905.7   342.4  4922.5  345.15  4963.4  345.09  4973.6  344.65
  4983.8  342.76    4991  334.29  4993.8  333.79    4997  334.29  5005.8   334.8
  5014.5  338.49  5024.7  338.23  5045.1  340.63  5050.7  343.99  5055.8   345.5
  5077.9  345.95  5150.8     347  5245.8   353.3  5290.3   355.5  5387.8  362.65
#Mann= 5 ,-1 , 0
  4622.1     .05       0  4894.9     .12       0    4991     .07       0
    4997     .12       0  5077.9     .16       0
Bank Sta=4983.8,5045.1
XS Rating Curve= 0 ,0
Exp/Cntr=0.3,0.1

Type RM Length L Ch R = 1 ,5056    ,823,823,823
BEGIN DESCRIPTION:
UNT101 IN CCTC 3.0
END DESCRIPTION:
XS GIS Cut Line= 4
      3541672.21     10651107.27      3542026.37     10651565.59
      3542250.33     10651654.13      3543021.19     10651654.13
#Sta/Elev= 30
  4294.5  352.82  4500.7  345.23  4608.5  339.35  4878.1  337.35  4918.3  338.29
  4950.6  338.53  4963.2  335.86    4974  335.71  4980.4  337.41  5001.7  331.63
  5004.5  331.13  5007.7  331.63    5017  336.97  5034.5  337.16  5049.2  336.23
  5064.2  338.64  5081.5  337.98  5100.9  339.56  5143.8  340.05  5283.8  347.01
  5464.9  353.15  5503.8  352.95  5533.8  356.67  5613.8  359.83  5643.8  358.22
  5663.8  359.77  5673.8  362.66  5753.8  364.59  5793.8  368.12  5885.4   371.8
#Mann= 7 ,-1 , 0
  4294.5     .05       0  4918.3     .12       0  5001.7     .07       0
  5007.7     .12       0  5100.9     .16       0  5464.9     .05       0
  5793.8     .16       0
Bank Sta=4980.4,5034.5
XS Rating Curve= 0 ,0
Exp/Cntr=0.3,0.1

Type RM Length L Ch R = 1 ,4233    ,1078,1078,1078
BEGIN DESCRIPTION:
UNT101 IN CCTC 2.0
END DESCRIPTION:
XS GIS Cut Line= 3
      3541061.67       10651188.      3541756.11     10652218.81
      3542688.28     10652695.73
#Sta/Elev= 30
  3541.5  355.16  3605.5  351.88  3686.4  344.71  3860.6  338.01  3959.2  334.08
  4038.5  332.22  4293.1  332.28  4313.9   332.5  4449.2  331.75  4591.8  331.27
    4658  331.42  4687.9  330.59  4690.9  329.28  4693.7  328.78  4696.9  329.28
  4708.9  330.84  4846.2   330.9  4979.5  333.65  4996.1  331.84  5018.3  333.52
  5167.7  332.69  5345.8  337.79    5368  339.64  5383.7  338.64  5390.2  340.02
  5451.1  341.14  5462.5   343.1  5546.6  345.36  5754.4  351.76  5831.5  359.47
#Mann= 11 ,-1 , 0
  3541.5     .05       0  3860.6     .16       0  3959.2     .05       0
  4293.1     .16       0  4313.9     .05       0  4449.2     .16       0
  4591.8     .12       0  4690.9     .07       0  4696.9     .12       0
  5167.7     .16       0  5546.6     .05       0
Bank Sta=4979.5,5018.3
XS Rating Curve= 0 ,0
Exp/Cntr=0.3,0.1

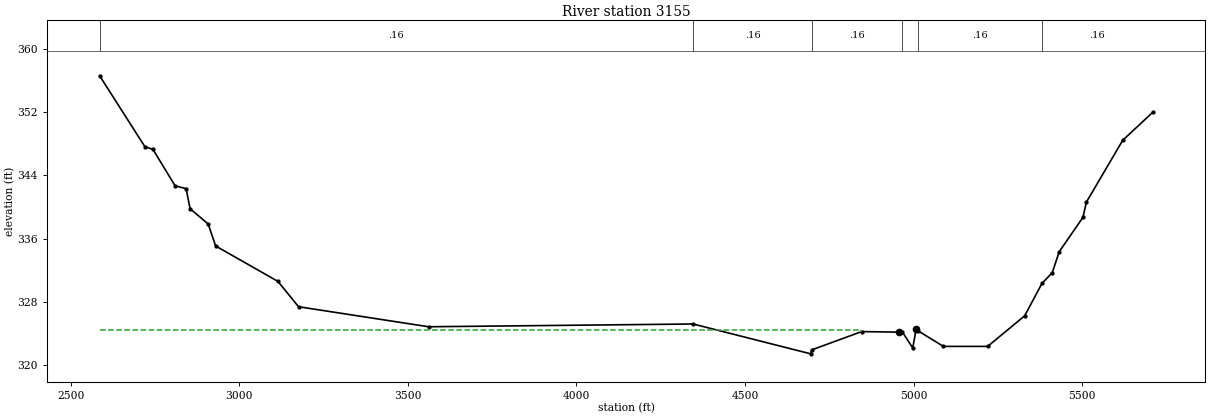
Type RM Length L Ch R = 1 ,3155    ,0,0,0
BEGIN DESCRIPTION:
UNT101 IN CCTC 1.0
END DESCRIPTION:
XS GIS Cut Line= 3
      3540529.98     10651274.79      3541365.48     10653206.22
      3542374.57     10653347.27
#Sta/Elev= 30
  2586.1  356.57  2720.5   347.6    2744  347.29  2809.9  342.67  2842.6  342.32
  2854.3  339.78    2908  337.85  2930.2  335.07    3115   330.6    3176   327.4
  3561.7  324.87  4346.2  325.22  4694.9  321.45  4698.1  321.95  4846.1  324.26
  4957.2  324.19  4967.1  324.19  4997.6  322.19  5007.7  324.57  5013.9  324.34
  5088.5  322.39  5219.7  322.39  5329.5  326.25  5380.8  330.34  5411.6  331.72
  5431.8  334.34  5502.4  338.69  5512.5  340.61  5620.3  348.42  5709.4  351.96
#Mann= 6 ,-1 , 0
  2586.1     .16       0  4346.2     .16       0  4698.1     .16       0
  4967.1     .07       0  5013.9     .16       0  5380.8     .16       0
#XS Ineff= 2 , 0
       0 4843.99   324.5               0
Permanent Ineff=
       F       F
Bank Sta=4957.2,5007.7
XS Rating Curve= 0 ,0
Exp/Cntr=0.3,0.1

Chan Stop Cuts=-1
Use User Specified Reach Order=0
Composite Channel Slope=5