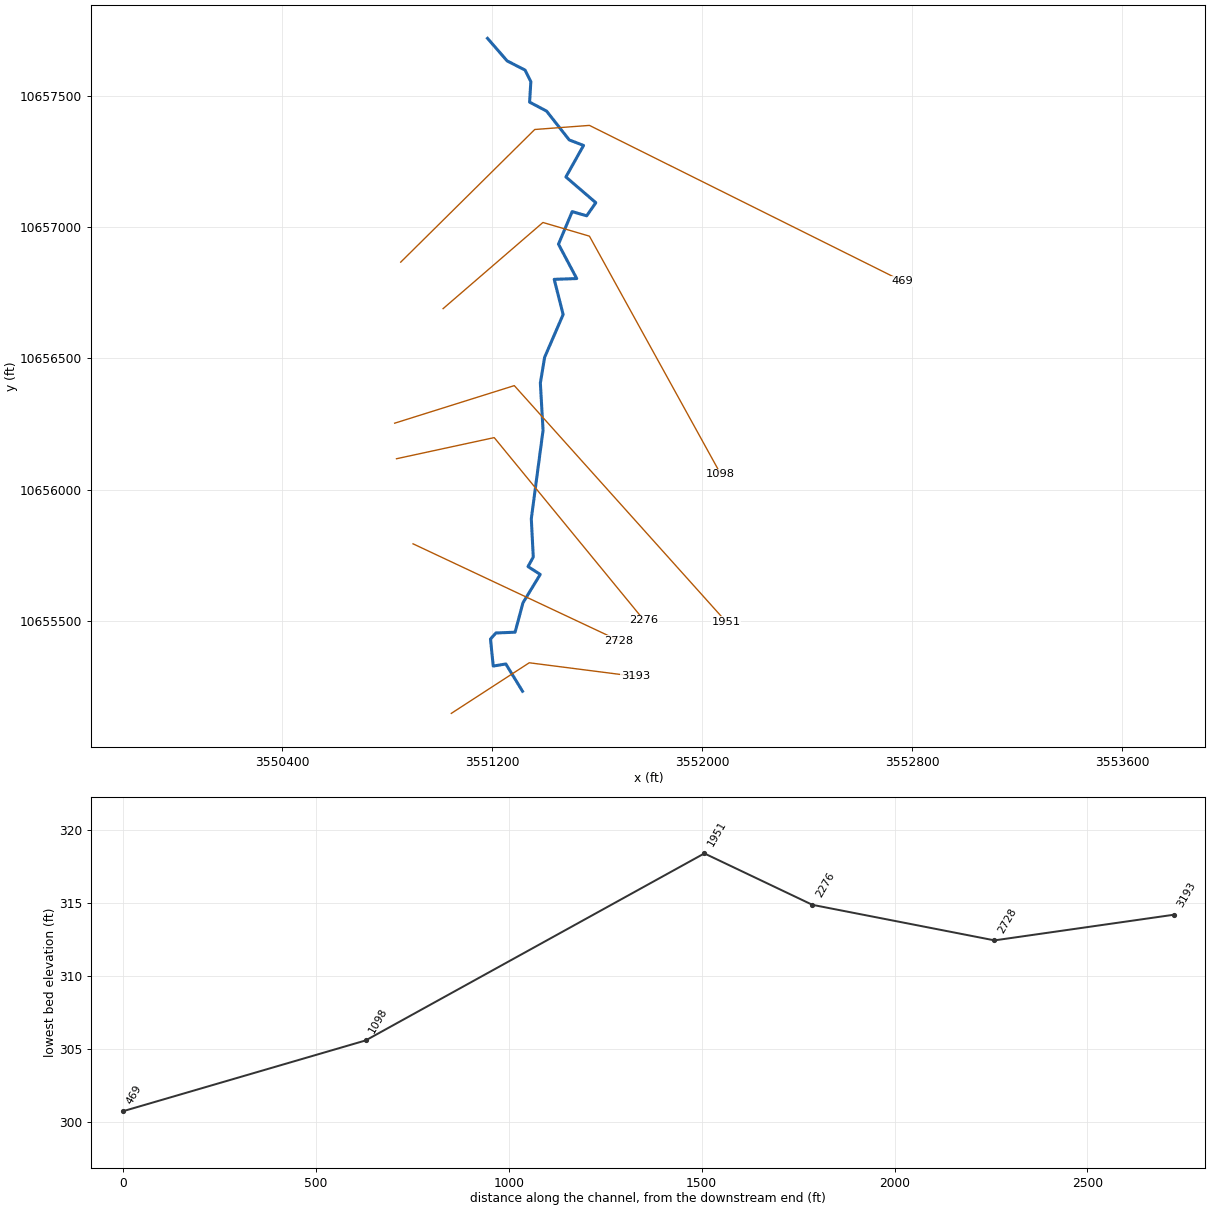
--- UNT104 IN CCTC.prj (project) ---

Proj Title=UNT104 IN CCTC Base Level Engineering
Current Plan=p01
Default Exp/Contr=0.3,0.1
English Units
Geom File=g01
Flow File=f01
Plan File=p01
Y Axis Title=Elevation
X Axis Title(PF)=Main Channel Distance
X Axis Title(XS)=Station
BEGIN DESCRIPTION:
UNT104 IN CCTC
END DESCRIPTION:
DSS Export Rating Curves= 0
DSS Export Rating Curve Sorted= 0
DSS Export Volume Flow Curves= 0
DXF OffsetX= 0
DXF OffsetY= 0
DXF ScaleX= 1
DXF ScaleY= 10

--- UNT104 IN CCTC.p01 (plan) ---

Plan Title=Multiple Run
Short Identifier=Multiple
Geom File=g01
Flow File=f01
Subcritical Flow
K Sum by GR= 0
Std Step Tol= 0.01
Critical Tol= 0.01
Num of Std Step Trials= 20
Max Error Tol= 0.3
Flow Tol Ratio= 0.001
Split Flow NTrial= 30
Split Flow Tol= 0.02
Split Flow Ratio= 0.02
Log Output Level= 0
Friction Slope Method= 1
Unsteady Friction Slope Method= 2
Unsteady Bridges Friction Slope Method= 1
Parabolic Critical Depth
Global Vel Dist=  1 , 1 , 1
Global Log Level= 0
CheckData=True
Encroach Param= -1, 0, 0, 0
BEGIN DESCRIPTION:
Multiple Run
END DESCRIPTION:

--- UNT104 IN CCTC.f01 (steady flow) ---

Flow Title=Multiple
Number of Profiles=7
Profile Names=10-year,25-year,50-year,1pct_min,100-year,1pct_plu,500-year
River Rch & RM= UNT104 IN CCTC,Reach-1,3193
    1251    1717    2102    1879    2542    3437    3703
Boundary for River Rch & Prof#=UNT104 IN CCTC,Reach-1,1
Up Type=0
Dn Type=3
Dn Slope=0.005
Boundary for River Rch & Prof#=UNT104 IN CCTC,Reach-1,2
Up Type=0
Dn Type=3
Dn Slope=0.005
Boundary for River Rch & Prof#=UNT104 IN CCTC,Reach-1,3
Up Type=0
Dn Type=3
Dn Slope=0.005
Boundary for River Rch & Prof#=UNT104 IN CCTC,Reach-1,4
Up Type=0
Dn Type=3
Dn Slope=0.005
Boundary for River Rch & Prof#=UNT104 IN CCTC,Reach-1,5
Up Type=0
Dn Type=3
Dn Slope=0.005
Boundary for River Rch & Prof#=UNT104 IN CCTC,Reach-1,6
Up Type=0
Dn Type=3
Dn Slope=0.005
Boundary for River Rch & Prof#=UNT104 IN CCTC,Reach-1,7
Up Type=0
Dn Type=3
Dn Slope=0.005

--- UNT104 IN CCTC.g01 (geometry) ---

Geom Title=Existing Conditions
Program Version=4.10

River Reach=UNT104 IN CCTC  ,Reach-1
Reach XY= 30
      3551315.52     10655232.08        3551252.       10655336.
        3551204.       10655328.       3551193.5       10655431.
      3551214.25       10655454.      3551287.25       10655457.
      3551317.25       10655569.        3551383.       10655677.
       3551336.5       10655707.       3551356.5       10655743.
        3551349.       10655889.      3551393.75       10656226.
       3551383.5       10656406.      3551399.75       10656504.
      3551470.25       10656667.      3551436.25       10656801.
        3551522.       10656804.       3551452.5       10656935.
      3551504.75       10657059.        3551560.       10657043.
      3551594.75       10657093.      3551480.75       10657191.
        3551548.       10657311.       3551493.5       10657332.
        3551407.       10657442.       3551342.5       10657476.
      3551347.25       10657554.      3551325.25       10657598.
        3551257.       10657633.      3551182.25       10657719.

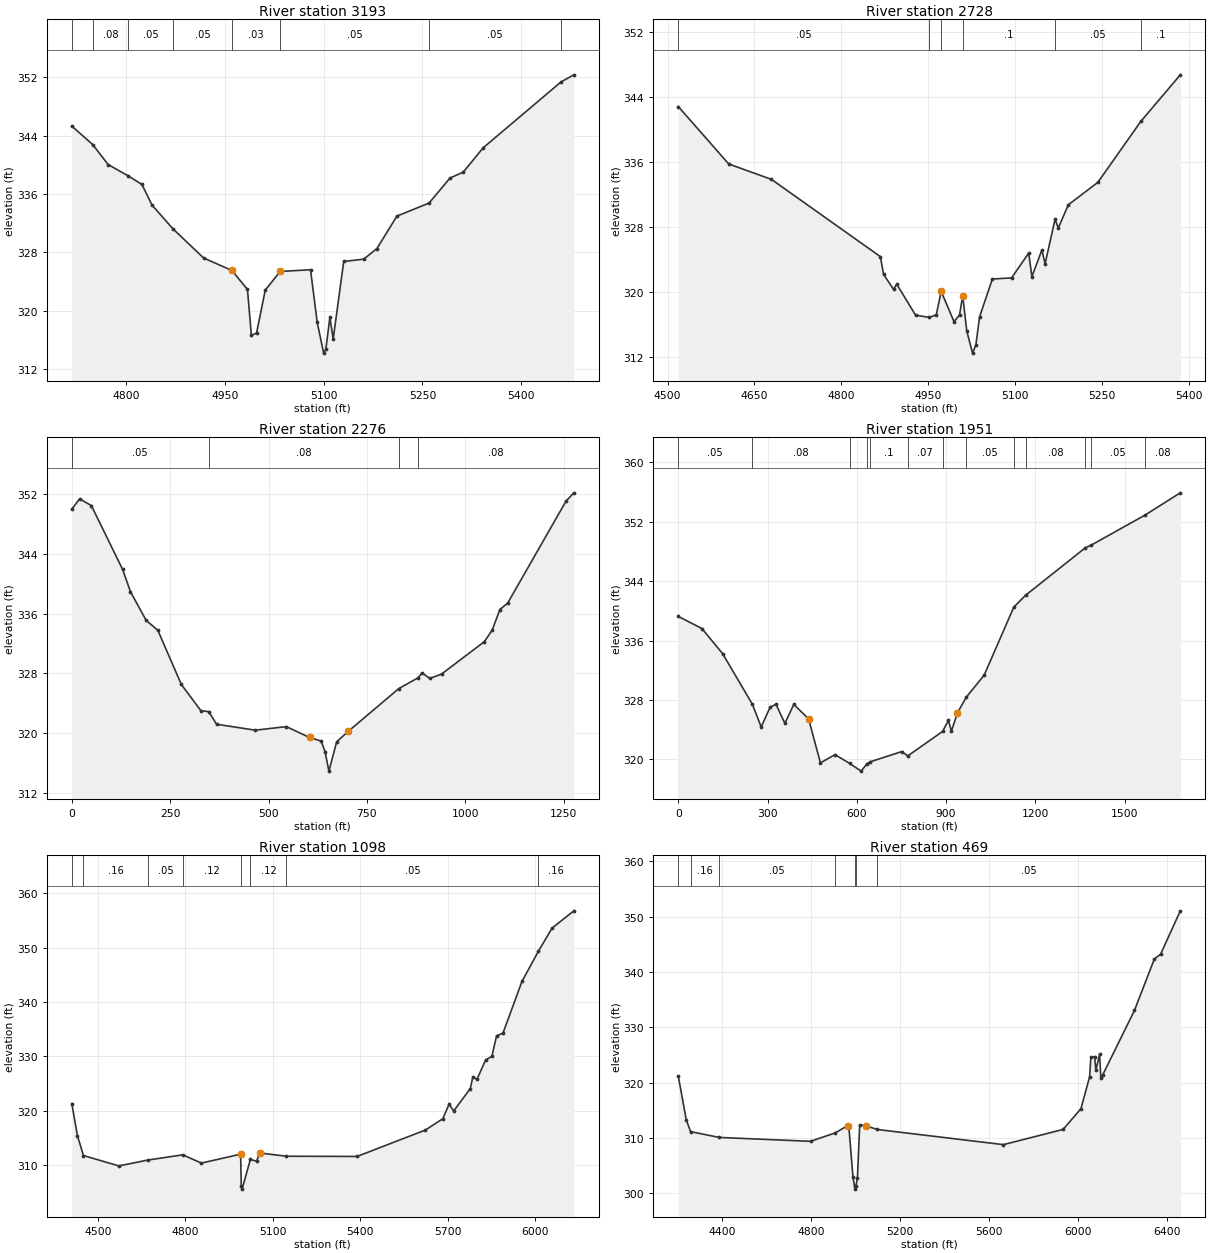
Type RM Length L Ch R = 1 ,3193    ,465,465,465
BEGIN DESCRIPTION:
UNT104 IN CCTC 6.0
END DESCRIPTION:
XS GIS Cut Line= 3
      3551044.33     10655147.79      3551341.24     10655340.53
      3551746.05     10655288.63
#Sta/Elev= 30
  4717.7  345.29  4749.6  342.75  4772.8  340.03  4803.2  338.48  4824.2   337.3
  4839.4  334.49  4871.2  331.23  4917.8  327.23  4960.8  325.52  4984.4  322.92
  4990.3  316.63  4998.2  316.96  5011.4  322.83    5034  325.38  5080.1  325.62
  5090.2  318.45    5100   314.2  5103.3   314.7  5109.5   319.1  5114.5  316.13
  5130.5  326.75  5160.8  327.07  5180.9  328.52  5211.2  332.96    5260  334.75
  5291.8  338.17    5312  338.99  5342.2  342.32  5460.5  351.35  5479.8  352.31
#Mann= 8 ,-1 , 0
  4717.7     .05       0  4749.6     .08       0  4803.2     .05       0
  4871.2     .05       0  4960.8     .03       0    5034     .05       0
    5260     .05       0  5460.5     .08       0
Bank Sta=4960.8,5034
XS Rating Curve= 0 ,0
Exp/Cntr=0.3,0.1

Type RM Length L Ch R = 1 ,2728    ,472,472,472
BEGIN DESCRIPTION:
UNT104 IN CCTC 5.0
END DESCRIPTION:
XS GIS Cut Line= 2
      3550898.56     10655793.64      3551683.42      10655424.6
#Sta/Elev= 30
  4518.4  342.79  4605.6  335.72  4679.5  333.82  4867.5  324.32  4873.2  322.12
  4890.3  320.29  4895.8  320.93  4928.4  317.11    4952  316.84  4964.2  317.16
  4972.6  320.04  4994.7  316.33  5004.3  317.12  5009.8  319.53  5016.8  315.17
  5026.8  312.44  5032.6  313.47  5038.9  316.89    5061  321.56  5094.2   321.7
  5123.8  324.75  5129.3  321.85  5146.6  325.13  5152.1  323.43  5169.4  328.93
  5174.9  327.83  5192.2  330.69  5243.3  333.46  5317.4  340.95  5385.7  346.69
#Mann= 6 ,-1 , 0
  4518.4     .05       0    4952     .05       0  4972.6     .03       0
  5009.8      .1       0  5169.4     .05       0  5317.4      .1       0
Bank Sta=4972.6,5009.8
XS Rating Curve= 0 ,0
Exp/Cntr=0.3,0.1

Type RM Length L Ch R = 1 ,2276    ,280,280,280
BEGIN DESCRIPTION:
UNT104 IN CCTC 4.0
END DESCRIPTION:
XS GIS Cut Line= 3
      3550835.51     10656117.69      3551207.79     10656198.17
      3551778.71     10655502.02
#Sta/Elev= 30
       0     350   19.89  351.39   49.72  350.49  129.26  341.92  149.15  338.94
  188.92   335.1  218.75  333.76  278.41   326.5  328.13  322.98  348.02  322.86
   367.9  321.17  466.42  320.37  545.15  320.85   604.2  319.39  633.73  318.91
  643.57  317.48  653.41  314.88  673.09  318.82  702.62  320.22  830.66  325.94
   880.1   327.4  889.99  328.05  909.77  327.31  939.44  327.89 1048.23  332.24
 1068.01  333.76 1087.79  336.55 1107.56  337.41 1255.91   351.1 1275.69   352.2
#Mann= 4 ,-1 , 0
       0     .05       0  348.02     .08       0  830.66     .05       0
   880.1     .08       0
Bank Sta=604.2,702.62
XS Rating Curve= 0 ,0
Exp/Cntr=0.3,0.1

Type RM Length L Ch R = 1 ,1951    ,878,878,878
BEGIN DESCRIPTION:
UNT104 IN CCTC 3.0
END DESCRIPTION:
XS GIS Cut Line= 3
      3550828.57     10656253.11      3551284.26     10656396.22
      3552091.22      10655496.8
#Sta/Elev= 30
       0  339.25   79.63  337.61  149.31  334.22  248.85  327.44  278.72  324.36
  308.58     327  328.49  327.41  358.35  324.84  388.21  327.39  437.98  325.46
   477.8  319.52  526.69  320.63  575.57  319.46  614.68  318.41  634.24   319.4
  644.01  319.65  751.56  321.05  771.12  320.45  888.45  323.76     908  325.24
  917.99  323.79  937.97  326.23  967.94  328.37 1027.87  331.32 1127.77  340.51
 1167.72  342.11 1367.51  348.47 1387.49  348.84  1567.3  352.86 1687.17  355.89
#Mann= 13 ,-1 , 0
       0     .05       0  248.85     .08       0  575.57     .07       0
  634.24     .08       0  644.01      .1       0  771.12     .07       0
  888.45     .05       0  967.94     .05       0 1127.77     .07       0
 1167.72     .08       0 1367.51      .1       0 1387.49     .05       0
  1567.3     .08       0
Bank Sta=437.98,937.97
XS Rating Curve= 0 ,0
Exp/Cntr=0.3,0.1

Type RM Length L Ch R = 1 ,1098    ,629,629,629
BEGIN DESCRIPTION:
UNT104 IN CCTC 2.0
END DESCRIPTION:
XS GIS Cut Line= 4
      3551013.09     10656689.46      3551393.33     10657017.61
      3551570.41     10656965.53      3552070.42     10656059.25
#Sta/Elev= 30
    4410  321.32  4429.6  315.37  4450.1  311.75  4571.2  309.84  4671.3  310.92
  4790.6  311.88  4854.5  310.36  4989.1     312  4991.4  306.07  4994.1  305.57
  5022.5  311.02  5043.9  310.71  5054.3  312.22  5146.3  311.62  5388.5  311.58
  5622.8  316.44  5682.4  318.51  5704.2  321.21  5719.7  319.94  5776.8  324.07
  5785.6  326.23  5799.6  325.75  5829.1  329.31  5850.9  329.99  5866.9  333.78
  5888.7  334.24    5954  343.78  6010.6  349.35  6057.2  353.58  6131.9  356.76
#Mann= 8 ,-1 , 0
    4410     .08       0  4450.1     .16       0  4671.3     .05       0
  4790.6     .12       0  4989.1     .07       0  5022.5     .12       0
  5146.3     .05       0  6010.6     .16       0
Bank Sta=4989.1,5054.3
XS Rating Curve= 0 ,0
Exp/Cntr=0.3,0.1

Type RM Length L Ch R = 1 ,469     ,0,0,0
BEGIN DESCRIPTION:
UNT104 IN CCTC 1.0
END DESCRIPTION:
XS GIS Cut Line= 4
      3550851.67     10656866.57      3551362.08     10657371.78
      3551570.41      10657387.4       3552761.6     10656794.41
#Sta/Elev= 30
  4201.2  321.19  4237.7  313.18  4256.9  311.11  4386.3  310.06  4796.3  309.36
  4906.5  310.87  4963.5   312.2  4968.5  311.97  4987.1  302.83  4994.1  301.21
  4996.9  300.71  5000.1  301.21  5007.1  302.78  5017.2  312.34  5047.2  312.15
  5095.6   311.5  5663.6  308.76  5931.7  311.51  6011.9  315.25  6051.1  321.03
  6056.7  324.54  6073.5  324.68  6079.1  322.19  6095.9   325.1  6101.5  320.89
  6110.4  321.41  6252.6  333.03  6342.2  342.35  6370.1   343.2  6458.9  351.06
#Mann= 7 ,-1 , 0
  4201.2     .08       0  4256.9     .16       0  4386.3     .05       0
  4906.5     .12       0  4994.1     .07       0  5000.1     .12       0
  5095.6     .05       0
Bank Sta=4963.5,5047.2
XS Rating Curve= 0 ,0
Exp/Cntr=0.3,0.1

Chan Stop Cuts=-1
Use User Specified Reach Order=0
Composite Channel Slope=5