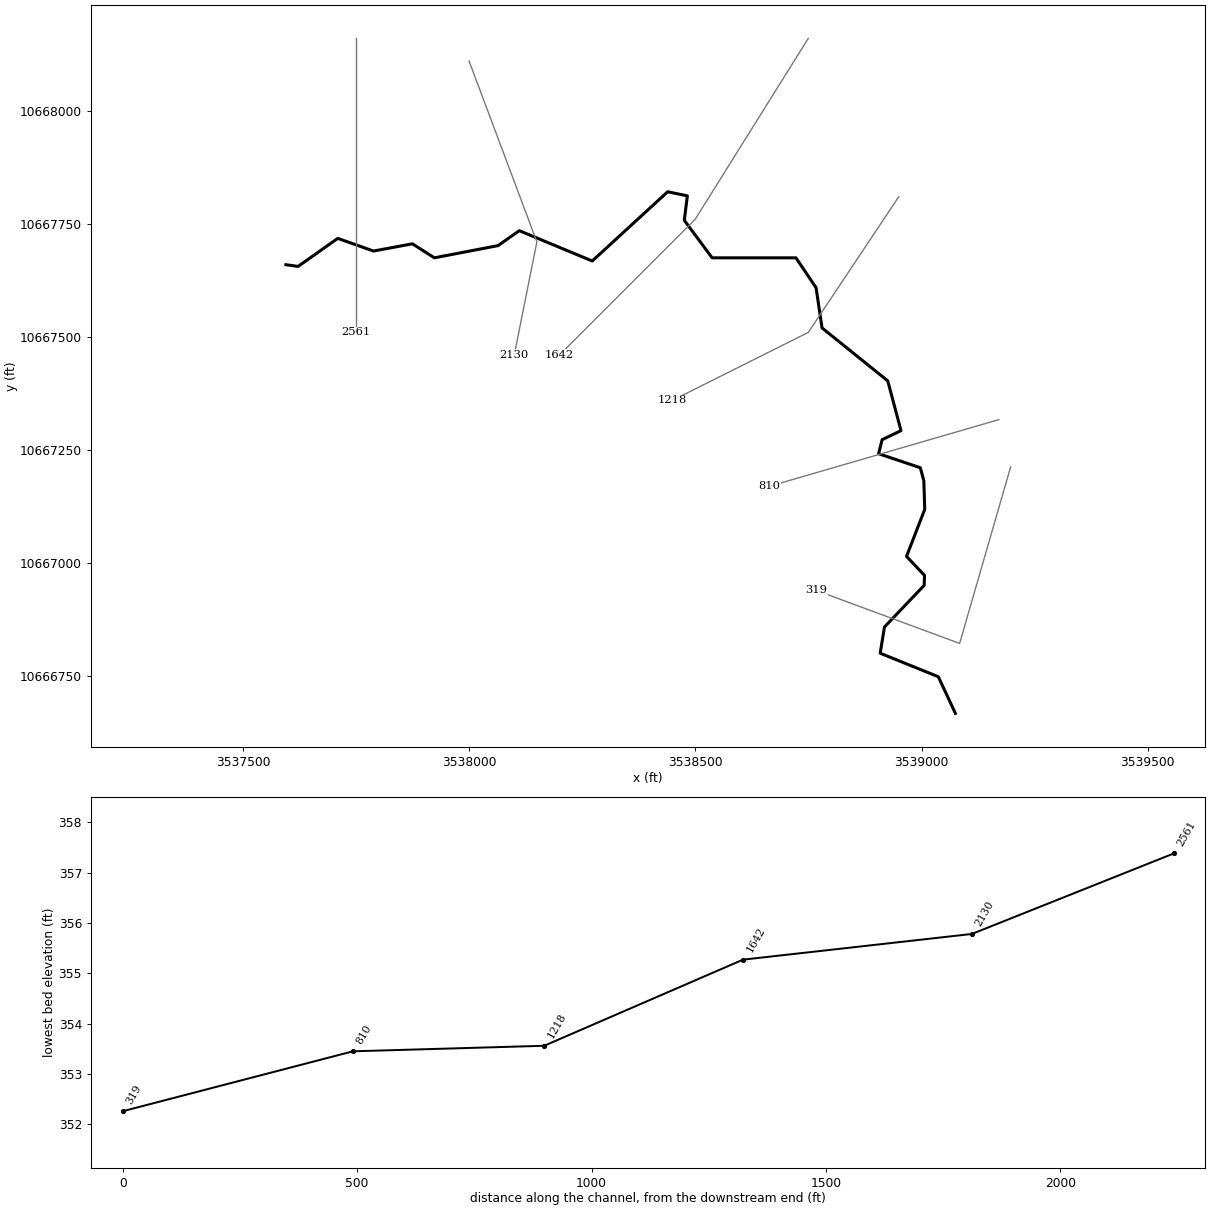
--- UNT107 IN CCTC.prj (project) ---

Proj Title=UNT107 IN CCTC Base Level Engineering
Current Plan=p01
Default Exp/Contr=0.3,0.1
English Units
Geom File=g01
Flow File=f01
Plan File=p01
BEGIN DESCRIPTION:
UNT107 IN CCTC
END DESCRIPTION:

--- UNT107 IN CCTC.p01 (plan) ---

Plan Title=Multiple Run
Short Identifier=Multiple
Geom File=g01
Flow File=f01
Subcritical Flow
K Sum by GR= 0
Std Step Tol= 0.01
Critical Tol= 0.01
Num of Std Step Trials= 20
Max Error Tol= 0.3
Flow Tol Ratio= 0.001
Split Flow NTrial= 30
Split Flow Tol= 0.02
Split Flow Ratio= 0.02
Log Output Level= 0
Friction Slope Method= 1
Unsteady Friction Slope Method= 2
Unsteady Bridges Friction Slope Method= 1
Parabolic Critical Depth
Global Vel Dist=  1 , 1 , 1
Global Log Level= 0
CheckData=True
Encroach Param= -1, 0, 0, 0
BEGIN DESCRIPTION:
Multiple Run
END DESCRIPTION:

--- UNT107 IN CCTC.f01 (steady flow) ---

Flow Title=Multiple
Number of Profiles=7
Profile Names=10-year,25-year,50-year,1pct_min,100-year,1pct_plu,500-year
River Rch & RM= UNT107 IN CCTC,Reach-1,2561
     834    1102    1313    1141    1544    2088    2127
Boundary for River Rch & Prof#=UNT107 IN CCTC,Reach-1,1
Up Type=0
Dn Type=3
Dn Slope=0.005
Boundary for River Rch & Prof#=UNT107 IN CCTC,Reach-1,2
Up Type=0
Dn Type=3
Dn Slope=0.005
Boundary for River Rch & Prof#=UNT107 IN CCTC,Reach-1,3
Up Type=0
Dn Type=3
Dn Slope=0.005
Boundary for River Rch & Prof#=UNT107 IN CCTC,Reach-1,4
Up Type=0
Dn Type=3
Dn Slope=0.005
Boundary for River Rch & Prof#=UNT107 IN CCTC,Reach-1,5
Up Type=0
Dn Type=3
Dn Slope=0.005
Boundary for River Rch & Prof#=UNT107 IN CCTC,Reach-1,6
Up Type=0
Dn Type=3
Dn Slope=0.005
Boundary for River Rch & Prof#=UNT107 IN CCTC,Reach-1,7
Up Type=0
Dn Type=3
Dn Slope=0.005

--- UNT107 IN CCTC.g01 (geometry) ---

Geom Title=Existing Conditions

River Reach=UNT107 IN CCTC,Reach-1
Reach XY= 30
      3537594.82     10667659.84      3537621.75     10667656.00
      3537709.50     10667718.00      3537788.50     10667690.00
      3537874.50     10667706.00      3537923.00     10667675.00
      3538063.75     10667702.00      3538110.75     10667735.00
      3538272.00     10667668.00      3538438.75     10667821.00
      3538482.25     10667812.00      3538475.50     10667758.00
      3538537.00     10667675.00      3538722.25     10667675.00
      3538766.75     10667609.00      3538780.00     10667520.00
      3538925.25     10667403.00      3538954.50     10667293.00
      3538912.75     10667273.00      3538905.00     10667242.00
      3538997.25     10667211.00      3539005.00     10667182.00
      3539007.00     10667119.00      3538966.75     10667015.00
      3539006.50     10666973.00      3539005.75     10666951.00
      3538918.00     10666859.00      3538908.50     10666801.00
      3539037.00     10666749.00      3539074.75     10666668.00

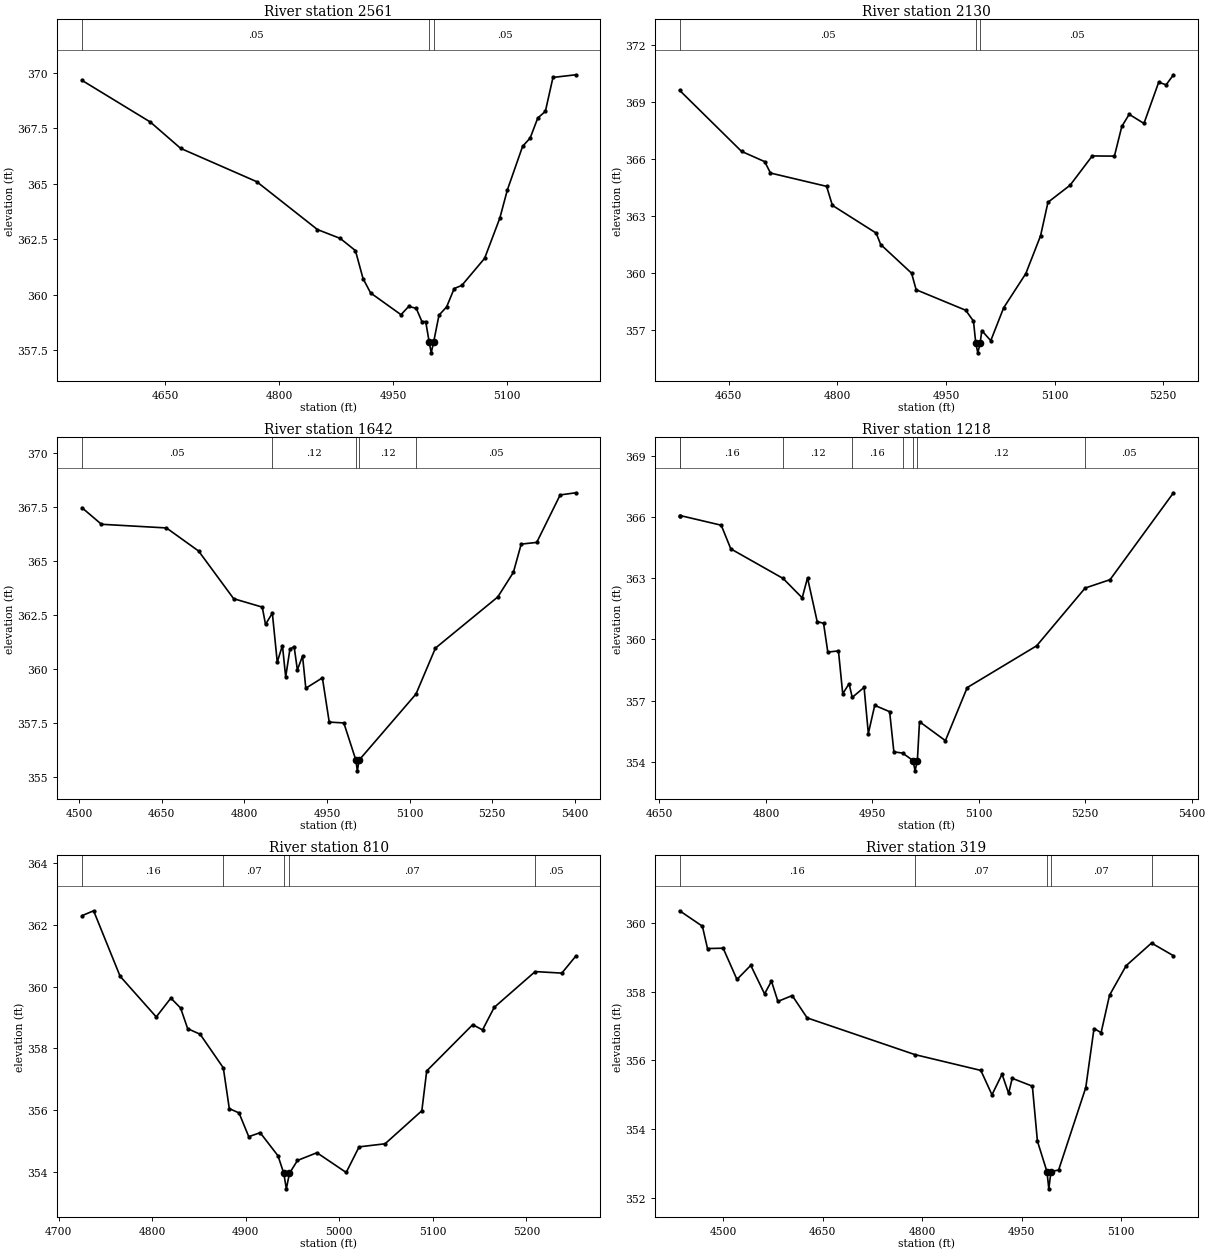
Type RM Length L Ch R = 1,2561,431,431,431
BEGIN DESCRIPTION:
UNT107 IN CCTC 5.0
END DESCRIPTION:
XS GIS Cut Line= 3
      3537749.61     10668160.19      3537749.61     10667710.19
      3537749.61     10667510.19
#Sta/Elev= 30
  4540.6  369.67  4630.6  367.79  4670.6  366.60  4770.6  365.10  4850.6  362.94
  4880.6  362.54  4900.6  361.99  4910.6  360.73  4920.6  360.08  4960.6  359.10
  4970.6  359.47  4980.6  359.39  4988.1  358.79  4993.1  358.79  4997.6  357.88
  5000.4  357.38  5003.6  357.88  5010.6  359.08  5020.6  359.45  5030.6  360.28
  5040.6  360.42  5070.6  361.64  5090.6  363.45  5100.6  364.73  5120.6  366.69
  5130.6  367.07  5140.6  367.97  5150.6  368.27  5160.6  369.80  5190.6  369.92
#Mann=3,-1,0
  4540.6    0.05       0  4997.6    0.03       0  5003.6    0.05       0
Bank Sta=4997.6,5003.6
Exp/Cntr=0.3,0.1

Type RM Length L Ch R = 1,2130,488,488,488
BEGIN DESCRIPTION:
UNT107 IN CCTC 4.0
END DESCRIPTION:
XS GIS Cut Line= 3
      3537999.60     10668110.23      3538149.61     10667710.19
      3538099.61     10667460.18
#Sta/Elev= 30
  4582.0  369.59  4667.5  366.38  4699.5  365.84  4707.5  365.24  4785.0  364.54
  4793.0  363.54  4853.5  362.08  4859.7  361.48  4902.4  359.97  4908.7  359.10
  4977.2  358.02  4987.9  357.45  4991.1  356.28  4993.9  355.78  4997.1  356.28
  4999.4  356.95  5011.8  356.42  5029.6  358.15  5060.2  359.95  5080.6  361.94
  5090.8  363.70  5121.4  364.60  5152.0  366.14  5182.6  366.13  5192.8  367.69
  5203.0  368.33  5223.4  367.85  5243.8  370.02  5254.0  369.88  5264.2  370.41
#Mann=3,-1,0
  4582.0    0.05       0  4991.1    0.03       0  4997.1    0.05       0
Bank Sta=4991.1,4997.1
Exp/Cntr=0.3,0.1

Type RM Length L Ch R = 1,1642,424,424,424
BEGIN DESCRIPTION:
UNT107 IN CCTC 3.0
END DESCRIPTION:
XS GIS Cut Line= 3
      3538749.61     10668160.18      3538499.61     10667760.19
      3538199.58     10667460.16
#Sta/Elev= 30
  4505.5  367.47  4540.9  366.70  4658.8  366.53  4717.2  365.46  4780.8  363.25
  4832.7  362.86  4838.6  362.06  4851.0  362.58  4859.9  360.31  4869.3  361.08
  4875.2  359.62  4882.9  360.91  4890.5  361.03  4896.4  359.95  4905.8  360.59
  4911.7  359.10  4941.8  359.58  4954.2  357.53  4980.7  357.49  5002.5  355.77
  5005.2  355.27  5008.5  355.77  5111.6  358.83  5146.9  360.96  5260.0  363.33
  5288.3  364.47  5302.5  365.78  5330.7  365.86  5373.2  368.06  5401.5  368.16
#Mann=5,-1,0
  4505.5    0.05       0  4851.0    0.12       0  5002.5    0.07       0
  5008.5    0.12       0  5111.6    0.05       0
Bank Sta=5002.5,5008.5
Exp/Cntr=0.3,0.1

Type RM Length L Ch R = 1,1218,408,408,408
BEGIN DESCRIPTION:
UNT107 IN CCTC 2.0
END DESCRIPTION:
XS GIS Cut Line= 3
      3538949.59     10667810.16      3538749.61     10667510.19
      3538449.63     10667360.20
#Sta/Elev= 30
  4678.4  366.07  4679.6  366.07  4737.0  365.60  4750.5  364.44  4824.2  362.99
  4851.1  362.04  4858.6  363.02  4872.2  360.88  4881.2  360.79  4887.2  359.38
  4902.2  359.44  4908.2  357.34  4917.2  357.83  4921.6  357.16  4938.3  357.65
  4944.3  355.39  4953.3  356.77  4974.3  356.46  4980.3  354.49  4992.6  354.43
  5007.4  354.06  5010.1  353.56  5013.4  354.06  5016.4  355.97  5052.9  355.04
  5083.6  357.64  5181.5  359.69  5249.8  362.52  5284.9  362.93  5374.3  367.19
#Mann=8,-1,0
  4678.4    0.05       0  4679.6    0.16       0  4824.2    0.12       0
  4921.6    0.16       0  4992.6    0.12       0  5007.4    0.07       0
  5013.4    0.12       0  5249.8    0.05       0
Bank Sta=5007.4,5013.4
Exp/Cntr=0.3,0.1

Type RM Length L Ch R = 1,810,491,491,491
BEGIN DESCRIPTION:
Mapping XS 7fa3b456
END DESCRIPTION:
XS GIS Cut Line= 2
      3539170.94     10667317.39      3538663.82     10667170.03
#Sta/Elev= 30
  4724.7  362.30  4737.2  362.46  4765.5  360.34  4804.2  359.02  4819.8  359.63
  4830.2  359.31  4837.8  358.64  4851.1  358.46  4875.9  357.37  4882.3  356.05
  4892.7  355.91  4903.1  355.14  4915.3  355.27  4934.4  354.52  4940.6  353.95
  4943.3  353.45  4946.6  353.95  4955.2  354.37  4976.0  354.62  5007.3  353.98
  5021.1  354.81  5048.9  354.91  5088.2  355.98  5093.4  357.27  5142.6  358.77
  5153.1  358.60  5165.6  359.33  5209.4  360.49  5237.9  360.44  5252.8  360.99
#Mann=5,-1,0
  4724.7    0.16       0  4875.9    0.07       0  4940.6    0.07       0
  4946.6    0.07       0  5209.4    0.05       0
Bank Sta=4940.6,4946.6
Exp/Cntr=0.3,0.1

Type RM Length L Ch R = 1,319,0,0,0
BEGIN DESCRIPTION:
UNT107 IN CCTC 1.0
END DESCRIPTION:
XS GIS Cut Line= 3
      3539196.97     10667213.18      3539084.13     10666822.60
      3538767.27     10666939.80
#Sta/Elev= 30
  4434.4  360.36  4468.7  359.91  4476.4  359.26  4500.0  359.27  4520.8  358.36
  4541.6  358.77  4562.4  357.94  4572.8  358.31  4582.5  357.72  4604.1  357.89
  4626.6  357.24  4789.1  356.17  4888.4  355.71  4905.2  355.00  4920.4  355.60
  4930.3  355.04  4935.7  355.48  4966.1  355.25  4973.7  353.65  4988.1  352.76
  4990.9  352.26  4994.1  352.76  5005.7  352.81  5046.6  355.21  5059.0  356.93
  5069.7  356.81  5082.4  357.90  5107.4  358.76  5145.7  359.42  5178.8  359.05
#Mann=5,-1,0
  4434.4    0.16       0  4789.1    0.07       0  4988.1    0.07       0
  4994.1    0.07       0  5145.7    0.05       0
Bank Sta=4988.1,4994.1
Exp/Cntr=0.3,0.1

Chan Stop Cuts=-1