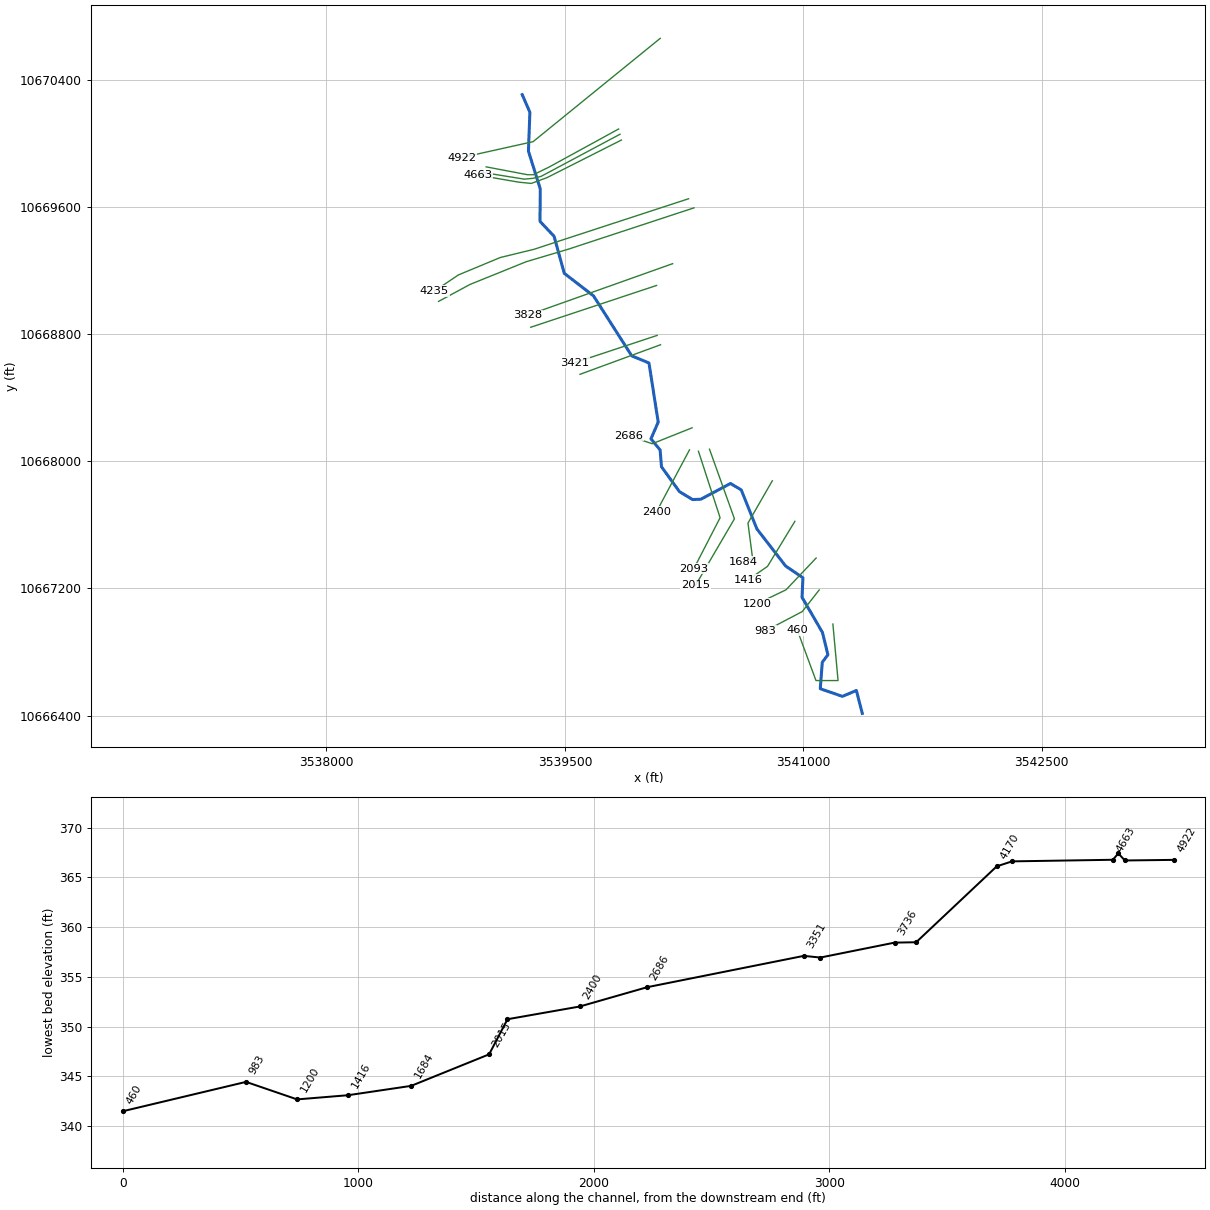
--- UNT108 IN CCTC.prj (project) ---

Proj Title=UNT108 IN CCTC Base Level Engineering
Current Plan=p01
Default Exp/Contr=0.3,0.1
English Units
Geom File=g01
Flow File=f01
Plan File=p01
Y Axis Title=Elevation
X Axis Title(PF)=Main Channel Distance
X Axis Title(XS)=Station
BEGIN DESCRIPTION:
UNT108 IN CCTC
END DESCRIPTION:
DSS Export Rating Curves= 0
DSS Export Rating Curve Sorted= 0
DSS Export Volume Flow Curves= 0
DXF OffsetX= 0
DXF OffsetY= 0
DXF ScaleX= 1
DXF ScaleY= 10

--- UNT108 IN CCTC.p01 (plan) ---

Plan Title=Multiple Run
Short Identifier=Multiple
Geom File=g01
Flow File=f01
Subcritical Flow
K Sum by GR= 0
Std Step Tol= 0.01
Critical Tol= 0.01
Num of Std Step Trials= 20
Max Error Tol= 0.3
Flow Tol Ratio= 0.001
Split Flow NTrial= 30
Split Flow Tol= 0.02
Split Flow Ratio= 0.02
Log Output Level= 0
Friction Slope Method= 1
Unsteady Friction Slope Method= 2
Unsteady Bridges Friction Slope Method= 1
Parabolic Critical Depth
Global Vel Dist=  1 , 1 , 1
Global Log Level= 0
CheckData=True
Encroach Param= -1, 0, 0, 0
BEGIN DESCRIPTION:
Multiple Run
END DESCRIPTION:

--- UNT108 IN CCTC.f01 (steady flow) ---

Flow Title=Multiple
Program Version=4.10
Number of Profiles= 7
Profile Names=10-year,25-year,50-year,1pct_min,100-year,1pct_plu,500-year
River Rch & RM=UNT108 IN CCTC,Reach-1         ,4922
     752     993    1183    1030    1393    1884    1923
Boundary for River Rch & Prof#=UNT108 IN CCTC,Reach-1         , 1
Up Type= 0
Dn Type= 3
Dn Slope=0.005
Boundary for River Rch & Prof#=UNT108 IN CCTC,Reach-1         , 2
Up Type= 0
Dn Type= 3
Dn Slope=0.005
Boundary for River Rch & Prof#=UNT108 IN CCTC,Reach-1         , 3
Up Type= 0
Dn Type= 3
Dn Slope=0.005
Boundary for River Rch & Prof#=UNT108 IN CCTC,Reach-1         , 4
Up Type= 0
Dn Type= 3
Dn Slope=0.005
Boundary for River Rch & Prof#=UNT108 IN CCTC,Reach-1         , 5
Up Type= 0
Dn Type= 3
Dn Slope=0.005
Boundary for River Rch & Prof#=UNT108 IN CCTC,Reach-1         , 6
Up Type= 0
Dn Type= 3
Dn Slope=0.005
Boundary for River Rch & Prof#=UNT108 IN CCTC,Reach-1         , 7
Up Type= 0
Dn Type= 3
Dn Slope=0.005
DSS Import GetInterval= 0
DSS Import GetPeak= 0
DSS Import FillOption= 0

--- UNT108 IN CCTC.g01 (geometry) ---

Geom Title=Existing Conditions
Program Version=4.10

River Reach=UNT108 IN CCTC  ,Reach-1
Reach XY= 30
      3539231.47     10670305.87      3539279.65      10670195.2
      3539270.53      10669950.4        3539345.       10669713.
      3539343.25       10669509.      3539431.75       10669415.
        3539496.       10669182.        3539680.       10669040.
      3539920.25       10668663.      3540028.75       10668618.
      3540086.75       10668246.      3540041.25       10668141.
      3540098.75       10668071.       3540107.5       10667965.
      3540220.25       10667809.      3540302.75       10667759.
      3540354.75       10667761.      3540541.25       10667860.
        3540609.       10667820.      3540707.75       10667574.
      3540888.25       10667341.      3540997.25       10667267.
       3540991.5       10667144.        3541120.       10666923.
      3541154.25       10666783.      3541118.75       10666735.
      3541106.25       10666569.      3541245.75       10666521.
      3541333.25       10666558.       3541370.5       10666414.

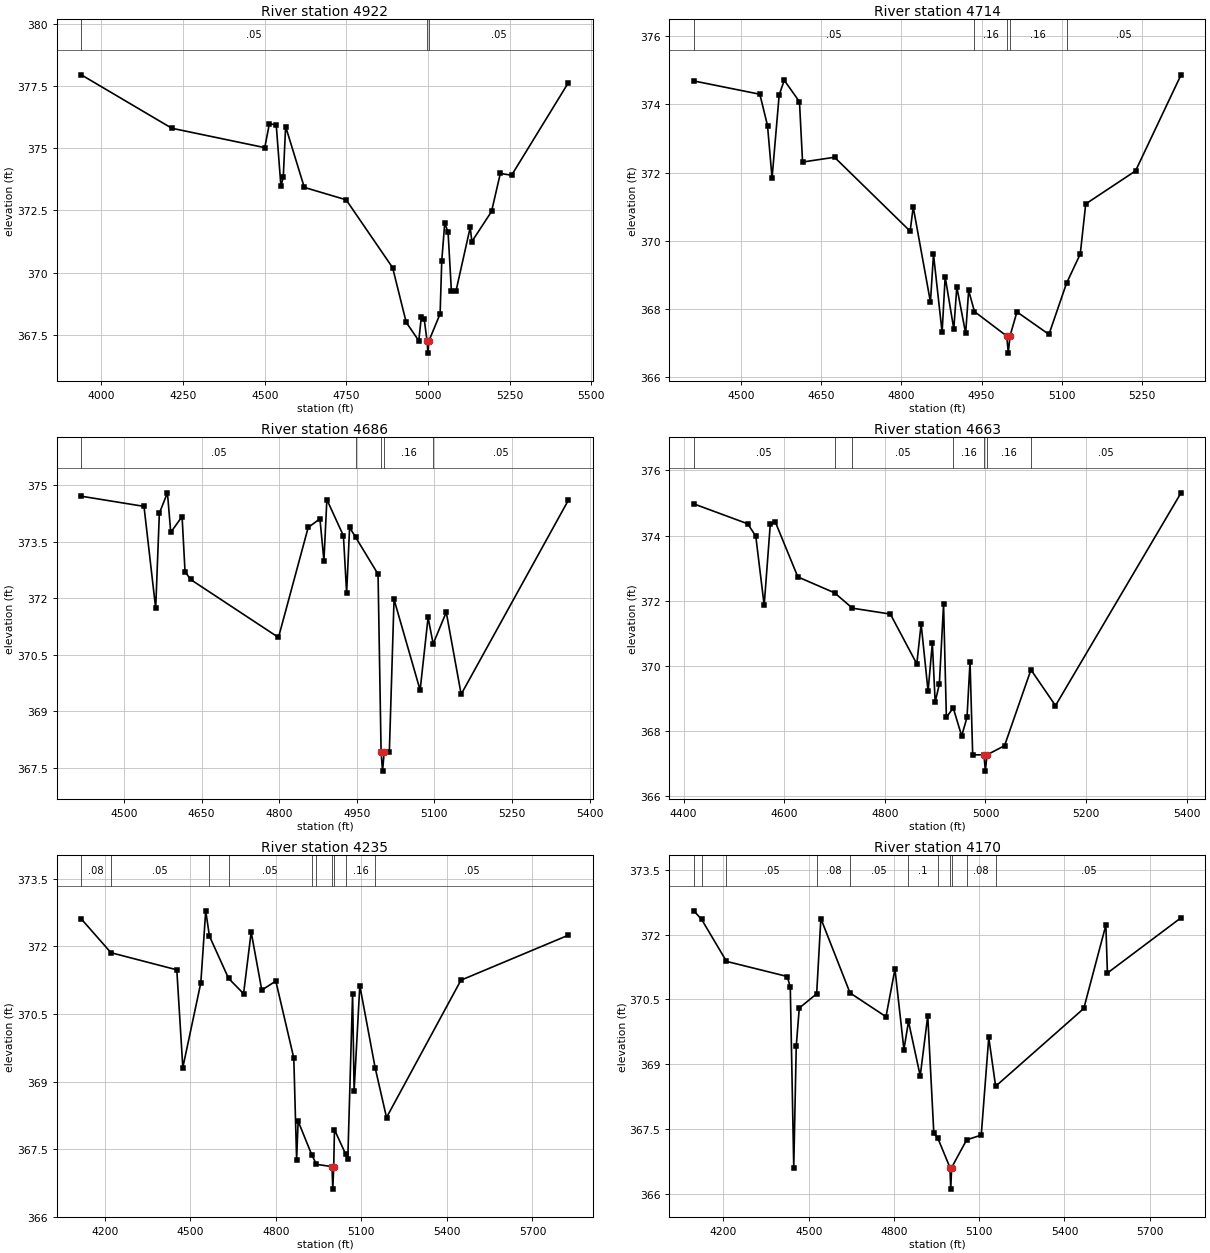
Type RM Length L Ch R = 1 ,4922    ,208,208,208
BEGIN DESCRIPTION:
UNT108 IN CCTC 8.0
END DESCRIPTION:
XS GIS Cut Line= 3
      3540099.65     10670660.22      3539299.61     10670010.19
      3538849.61     10669910.19
#Sta/Elev= 30
  3938.3  377.96  4215.6  375.81  4500.1  375.03  4514.4     376  4535.3  375.93
  4549.6  373.48  4556.8  373.84    4564  375.88  4621.2  373.43  4749.3  372.93
  4891.6   370.2  4933.2     368  4971.7  367.26  4979.4   368.2  4988.3  368.13
    4997  367.26  4999.8  366.76    5003  367.26    5037  368.34  5042.1  370.48
  5051.1  371.98  5061.3  371.65  5071.6  369.26  5085.7  369.26  5129.2  371.82
  5134.3  371.25  5194.5  372.46  5221.4  373.99    5256  373.92  5430.1  377.65
#Mann= 3 ,-1 , 0
  3938.3     .05       0    4997    .035       0    5003     .05       0
Bank Sta=4997,5003
XS Rating Curve= 0 ,0
Exp/Cntr=0.3,0.1

Type RM Length L Ch R = 1 ,4714    ,28,28,28
BEGIN DESCRIPTION:
Mapping XS a3ceb293
END DESCRIPTION:
XS GIS Cut Line= 5
       3539837.8     10670089.86      3539397.89     10669849.12
      3539301.54     10669802.24      3539265.08     10669802.24
      3539004.63     10669851.73
#Sta/Elev= 30
  4412.4  374.69  4535.7   374.3    4550  373.38  4558.5  371.84  4571.8  374.28
  4581.3  374.71  4609.7  374.08  4615.5  372.31  4675.2  372.45  4816.5  370.28
  4822.2  370.99  4854.4   368.2  4860.1   369.6  4876.2  367.31  4881.9  368.94
    4898  367.41  4903.7  368.64  4920.2  367.28  4925.8  368.54  4936.6  367.92
    4997   367.2  4999.8   366.7    5003   367.2    5016  367.91  5075.8  367.25
  5108.6  368.75  5134.3  369.61  5144.5  371.08  5237.6  372.05  5322.6  374.87
#Mann= 5 ,-1 , 0
  4412.4     .05       0  4936.6     .16       0    4997     .07       0
    5003     .16       0  5108.6     .05       0
Bank Sta=4997,5003
XS Rating Curve= 0 ,0
Exp/Cntr=0.3,0.1

Type RM Length L Ch R = 1 ,4686    ,23,23,23
BEGIN DESCRIPTION:
Mapping XS d6b5b4c1
END DESCRIPTION:
XS GIS Cut Line= 5
      3539846.51     10670056.89       3539349.8     10669791.83
      3539299.45     10669779.67       3539243.9     10669774.47
       3538976.5     10669817.87
#Sta/Elev= 30
  4417.6  374.71  4538.8  374.44  4561.4  371.73  4568.5  374.26  4584.1   374.8
  4590.5  373.75  4612.4  374.17  4618.1  372.71  4628.7   372.5  4798.7  370.96
  4856.1  373.88  4878.8  374.11  4886.5     373  4892.2  374.62  4924.2  373.66
  4930.4  372.13  4936.1  373.88  4947.8  373.62  4991.1  372.64    4997  367.91
  4999.8  367.41    5003  367.91  5012.9  367.91    5022  371.97  5072.4  369.56
  5087.8  371.49  5097.6  370.79  5122.9  371.63  5151.7  369.45  5359.1  374.61
#Mann= 5 ,-1 , 0
  4417.6     .05       0  4947.8     .16       0    4997     .07       0
    5003     .16       0  5097.6     .05       0
Bank Sta=4997,5003
XS Rating Curve= 0 ,0
Exp/Cntr=0.3,0.1

Type RM Length L Ch R = 1 ,4663    ,428,428,428
BEGIN DESCRIPTION:
UNT108 IN CCTC 7.0
END DESCRIPTION:
XS GIS Cut Line= 5
      3539855.13      10670020.4      3539387.47     10669784.02
      3539288.52     10669747.56      3539210.39     10669755.37
      3538953.63     10669799.46
#Sta/Elev= 30
  4420.3  374.97  4527.3  374.36  4543.4  373.98  4560.1  371.86  4572.2  374.34
  4582.4  374.41    4627  372.73  4700.2  372.24  4735.5  371.77  4810.9  371.59
  4863.5  370.06  4872.1  371.29  4885.9  369.22  4894.4   370.7    4900  368.89
  4908.3  369.44  4916.7  371.89  4922.3  368.42  4935.9  368.71  4952.7  367.85
  4963.3  368.42  4969.3  370.12  4974.6  367.27    4997  367.27  4999.8  366.77
    5003  367.27  5037.9  367.55  5090.4  369.88  5139.2  368.78  5388.8  375.31
#Mann= 7 ,-1 , 0
  4420.3     .05       0  4700.2     .08       0  4735.5     .05       0
  4935.9     .16       0    4997     .07       0    5003     .16       0
  5090.4     .05       0
Bank Sta=4997,5003
XS Rating Curve= 0 ,0
Exp/Cntr=0.3,0.1

Type RM Length L Ch R = 1 ,4235    ,65,65,65
BEGIN DESCRIPTION:
Mapping XS dc26430f
END DESCRIPTION:
XS GIS Cut Line= 6
      3540278.08      10669651.2      3539489.04     10669393.39
      3539306.74     10669333.49       3539093.2     10669281.41
      3538830.18     10669172.04      3538679.17     10669070.49
#Sta/Elev= 30
  4117.7  372.61  4221.8  371.86  4452.7  371.48  4473.8  369.31  4536.9  371.19
  4554.1  372.79  4567.1  372.23  4634.2  371.29  4686.9  370.95  4713.5  372.32
  4750.7  371.03  4799.9  371.23    4863  369.52  4872.9  367.26  4878.2  368.12
  4926.1  367.37  4942.6  367.16    4997  367.11  4999.8  366.61    5003  367.11
  5005.6  367.93  5045.4  367.38  5052.4  367.28  5069.2  370.95  5074.5  368.79
  5094.5  371.13  5148.1  369.31  5188.2   368.2  5449.2  371.25  5826.3  372.25
#Mann= 10 ,-1 , 0
  4117.7     .08       0  4221.8     .05       0  4567.1     .08       0
  4634.2     .05       0  4926.1      .1       0  4942.6     .05       0
    4997    .033       0    5003     .05       0  5045.4     .16       0
  5148.1     .05       0
Bank Sta=4997,5003
XS Rating Curve= 0 ,0
Exp/Cntr=0.3,0.1

Type RM Length L Ch R = 1 ,4170    ,342,342,342
BEGIN DESCRIPTION:
UNT108 IN CCTC 6.0
END DESCRIPTION:
XS GIS Cut Line= 5
      3540311.99     10669593.92      3539520.29     10669333.49
      3539257.27     10669255.37       3538903.1     10669112.14
      3538705.21     10669005.38
#Sta/Elev= 30
  4095.7  372.55  4123.1  372.35  4210.6  371.38  4424.6  371.03  4435.1  370.78
  4447.3  366.61  4456.1  369.42  4466.7   370.3  4527.9  370.63  4542.7  372.37
  4645.4  370.65  4771.9   370.1  4803.5   371.2  4835.1  369.34  4851.1  369.99
  4892.4  368.73  4918.9  370.12  4940.3   367.4  4953.7   367.3    4997  366.61
  4999.8  366.11    5003  366.61  5055.8  367.25  5107.2  367.36  5133.6  369.62
  5157.8  368.49    5468  370.29  5545.8  372.22  5551.2  371.11  5810.4  372.39
#Mann= 11 ,-1 , 0
  4095.7     .05       0  4123.1     .08       0  4210.6     .05       0
  4527.9     .08       0  4645.4     .05       0  4851.1      .1       0
  4953.7     .05       0    4997    .033       0    5003     .05       0
  5055.8     .08       0  5157.8     .05       0
Bank Sta=4997,5003
XS Rating Curve= 0 ,0
Exp/Cntr=0.3,0.1

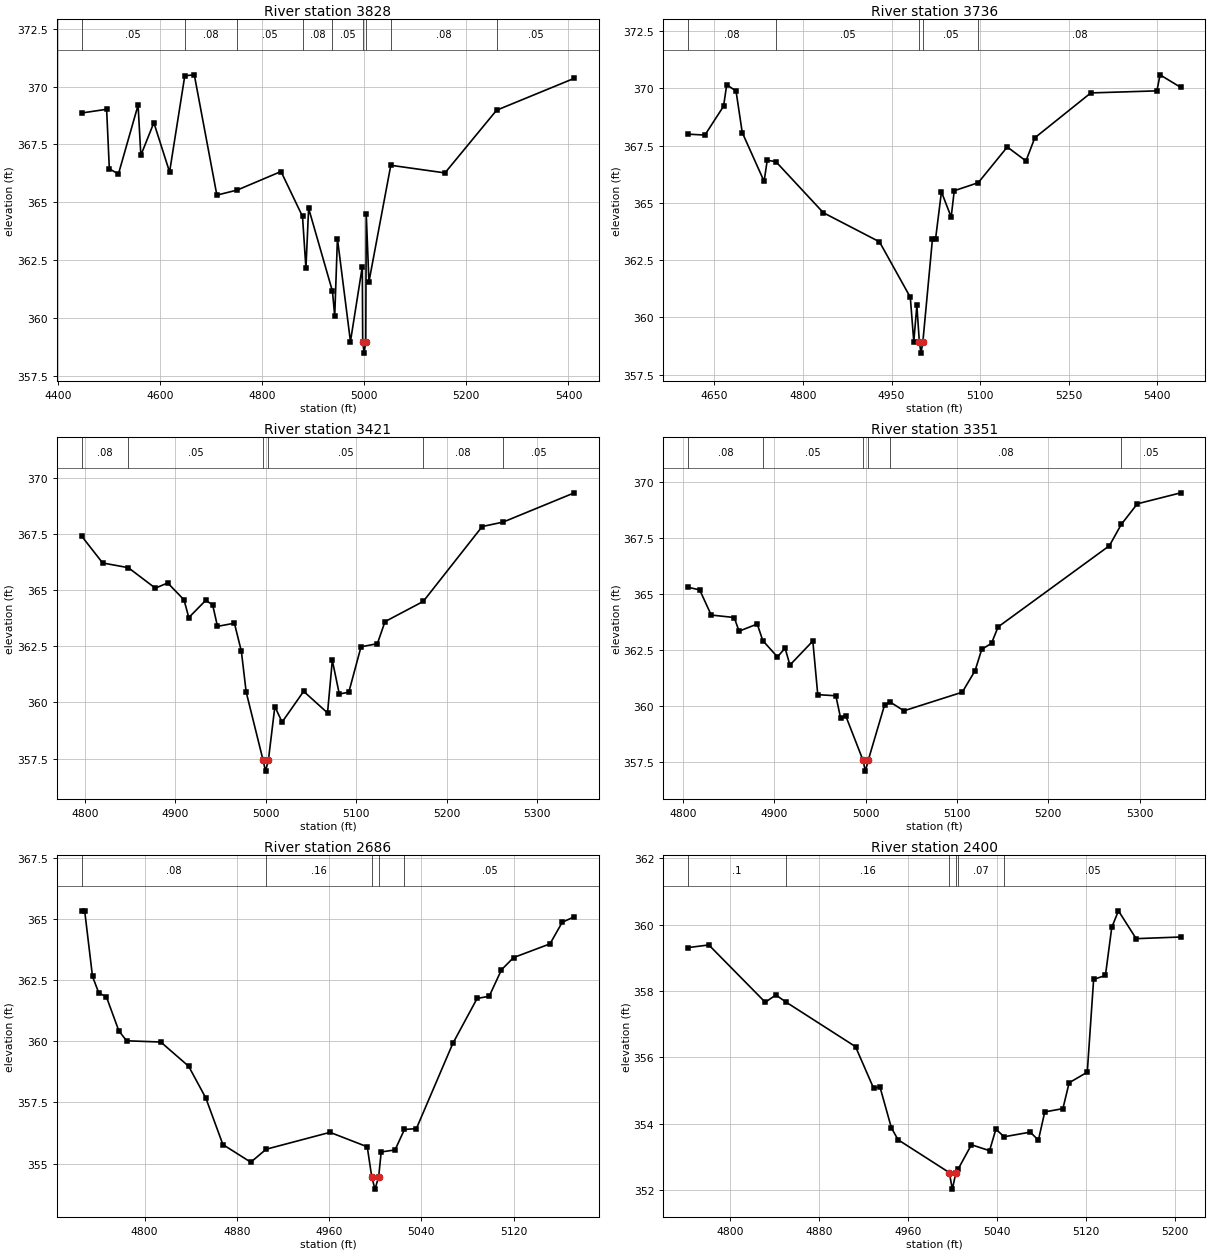
Type RM Length L Ch R = 1 ,3828    ,92,92,92
BEGIN DESCRIPTION:
UNT108 IN CCTC 5.0
END DESCRIPTION:
XS GIS Cut Line= 2
       3540177.6     10669242.77      3539268.38     10668919.45
#Sta/Elev= 30
  4446.4  368.86  4495.5  369.02  4500.8  366.45  4518.6  366.22  4557.1   369.2
  4562.5  367.03    4588  368.44  4618.8  366.31  4648.6  370.47  4667.2  370.51
  4711.4  365.31  4751.4  365.53    4837  366.33  4879.1  364.39  4885.8  362.15
  4891.1  364.74  4937.8  361.15  4942.2  360.08  4947.5  363.43    4973  358.98
  4996.2  362.22    4997  358.98  4999.8  358.48    5003  358.98  5003.9  364.51
  5009.2  361.56    5052   366.6  5158.1  366.27  5259.2  368.98  5411.4  370.36
#Mann= 9 ,-1 , 0
  4446.4     .05       0  4648.6     .08       0  4751.4     .05       0
  4879.1     .08       0  4937.8     .05       0    4997     .04       0
    5003     .05       0    5052     .08       0  5259.2     .05       0
Bank Sta=4997,5003
XS Rating Curve= 0 ,0
Exp/Cntr=0.3,0.1

Type RM Length L Ch R = 1 ,3736    ,315,315,315
BEGIN DESCRIPTION:
Mapping XS 585dcf00
END DESCRIPTION:
XS GIS Cut Line= 2
      3540076.73     10669105.85      3539285.08     10668842.84
#Sta/Elev= 30
  4605.4     368    4634  367.96  4665.6  369.22  4670.9  370.16  4686.7  369.88
  4697.2  368.07  4734.2  365.94  4739.5  366.86  4754.1   366.8  4834.5  364.57
  4929.5   363.3  4981.7  360.88  4987.6  358.94  4992.8  360.52    4997  358.94
  4999.8  358.44    5003  358.94  5019.2  363.42  5024.5  363.43  5034.4  365.48
  5050.9  364.38  5056.1  365.53  5096.7  365.88  5145.9  367.44  5177.5  366.83
  5192.5  367.84  5287.3   369.8  5399.2  369.89  5404.5  370.59  5439.6  370.04
#Mann= 5 ,-1 , 0
  4605.4     .08       0  4754.1     .05       0    4997     .04       0
    5003     .05       0  5096.7     .08       0
Bank Sta=4997,5003
XS Rating Curve= 0 ,0
Exp/Cntr=0.3,0.1

Type RM Length L Ch R = 1 ,3421    ,70,70,70
BEGIN DESCRIPTION:
Mapping XS ab4c8d5f
END DESCRIPTION:
XS GIS Cut Line= 2
      3540079.99      10668791.4        3539563.     10668620.51
#Sta/Elev= 30
  4796.5   367.4  4819.8   366.2  4848.2  365.99    4878  365.08  4891.7  365.31
  4909.7  364.56    4915  363.77  4933.8  364.54  4941.4  364.33  4946.7  363.38
  4965.4  363.52  4973.1  362.27  4978.4  360.46    4997  357.44  4999.8  356.94
    5003  357.44  5010.1  359.81  5018.1  359.12  5041.9  360.49  5068.3  359.53
  5073.6  361.87  5081.3  360.37  5091.8  360.45  5105.3  362.47  5123.4  362.61
  5131.8  363.59  5174.1  364.49  5239.2  367.82  5262.4  368.02    5341  369.32
#Mann= 6 ,-1 , 0
  4796.5     .08       0  4848.2     .05       0    4997     .04       0
    5003     .05       0  5174.1     .08       0  5262.4     .05       0
Bank Sta=4997,5003
XS Rating Curve= 0 ,0
Exp/Cntr=0.3,0.1

Type RM Length L Ch R = 1 ,3351    ,665,665,665
BEGIN DESCRIPTION:
UNT108 IN CCTC 4.0
END DESCRIPTION:
XS GIS Cut Line= 2
      3540101.63     10668732.79      3539594.96      10668546.9
#Sta/Elev= 30
  4805.5  365.31  4818.3  365.19  4830.9  364.07  4856.1  363.96  4861.4  363.35
  4881.3  363.67  4887.4  362.93  4903.5   362.2  4911.8   362.6  4917.1  361.84
  4942.2  362.91  4947.6  360.52  4967.4  360.47  4972.7  359.46  4978.1  359.59
    4997  357.61  4999.8  357.11    5003  357.61  5020.7  360.05  5026.9  360.19
    5042   359.8  5105.9  360.63  5119.9  361.59  5127.2  362.54  5137.9  362.81
  5145.1  363.54    5267  367.16    5280  368.11  5297.6  369.03  5345.2  369.52
#Mann= 6 ,-1 , 0
  4805.5     .08       0  4887.4     .05       0    4997     .04       0
    5003     .05       0  5026.9     .08       0    5280     .05       0
Bank Sta=4997,5003
XS Rating Curve= 0 ,0
Exp/Cntr=0.3,0.1

Type RM Length L Ch R = 1 ,2686    ,286,286,286
BEGIN DESCRIPTION:
UNT108 IN CCTC 3.0
END DESCRIPTION:
XS GIS Cut Line= 3
      3540299.65     10668210.21      3540049.61     10668110.19
      3539899.63     10668160.18
#Sta/Elev= 30
  4745.3  365.33    4748  365.33  4754.8  362.65  4760.2  361.98  4766.9  361.81
  4777.7  360.42  4784.4  360.02    4814  359.97  4838.2  358.98  4853.1  357.68
  4867.9  355.78  4892.1  355.06  4905.4  355.59  4960.8  356.28  4993.1  355.69
    4997  354.46  4999.8  353.96    5003  354.46  5005.2  355.48  5017.2  355.56
  5025.4   356.4  5035.7  356.43  5067.3  359.91  5088.4  361.75  5098.9  361.84
  5109.5  362.92    5120  363.42  5151.6  363.98  5162.2  364.86  5172.7  365.09
#Mann= 5 ,-1 , 0
  4745.3     .08       0  4905.4     .16       0    4997     .07       0
    5003     .16       0  5025.4     .05       0
Bank Sta=4997,5003
XS Rating Curve= 0 ,0
Exp/Cntr=0.3,0.1

Type RM Length L Ch R = 1 ,2400    ,307,307,307
BEGIN DESCRIPTION:
Mapping XS 039b8476
END DESCRIPTION:
XS GIS Cut Line= 2
      3540283.59      10668071.4      3540075.26     10667680.79
#Sta/Elev= 30
  4762.3  359.31    4781  359.39  4831.7  357.66  4841.2  357.88  4850.6  357.66
  4912.8  356.32  4929.1  355.06  4934.7  355.11    4945  353.87    4951  353.51
    4997  352.52  4999.8  352.02    5003  352.52  5004.9  352.62  5016.9  353.36
  5033.2  353.18  5038.9  353.83  5046.3   353.6  5069.7  353.74  5077.1   353.5
  5082.8  354.35  5099.1  354.45  5104.7  355.23    5121  355.55  5126.7  358.35
  5137.3  358.47    5143  359.92    5149  360.42  5164.9  359.58    5205  359.63
#Mann= 6 ,-1 , 0
  4762.3      .1       0  4850.6     .16       0    4997     .07       0
    5003     .16       0  5004.9     .07       0  5046.3     .05       0
Bank Sta=4997,5003
XS Rating Curve= 0 ,0
Exp/Cntr=0.3,0.1

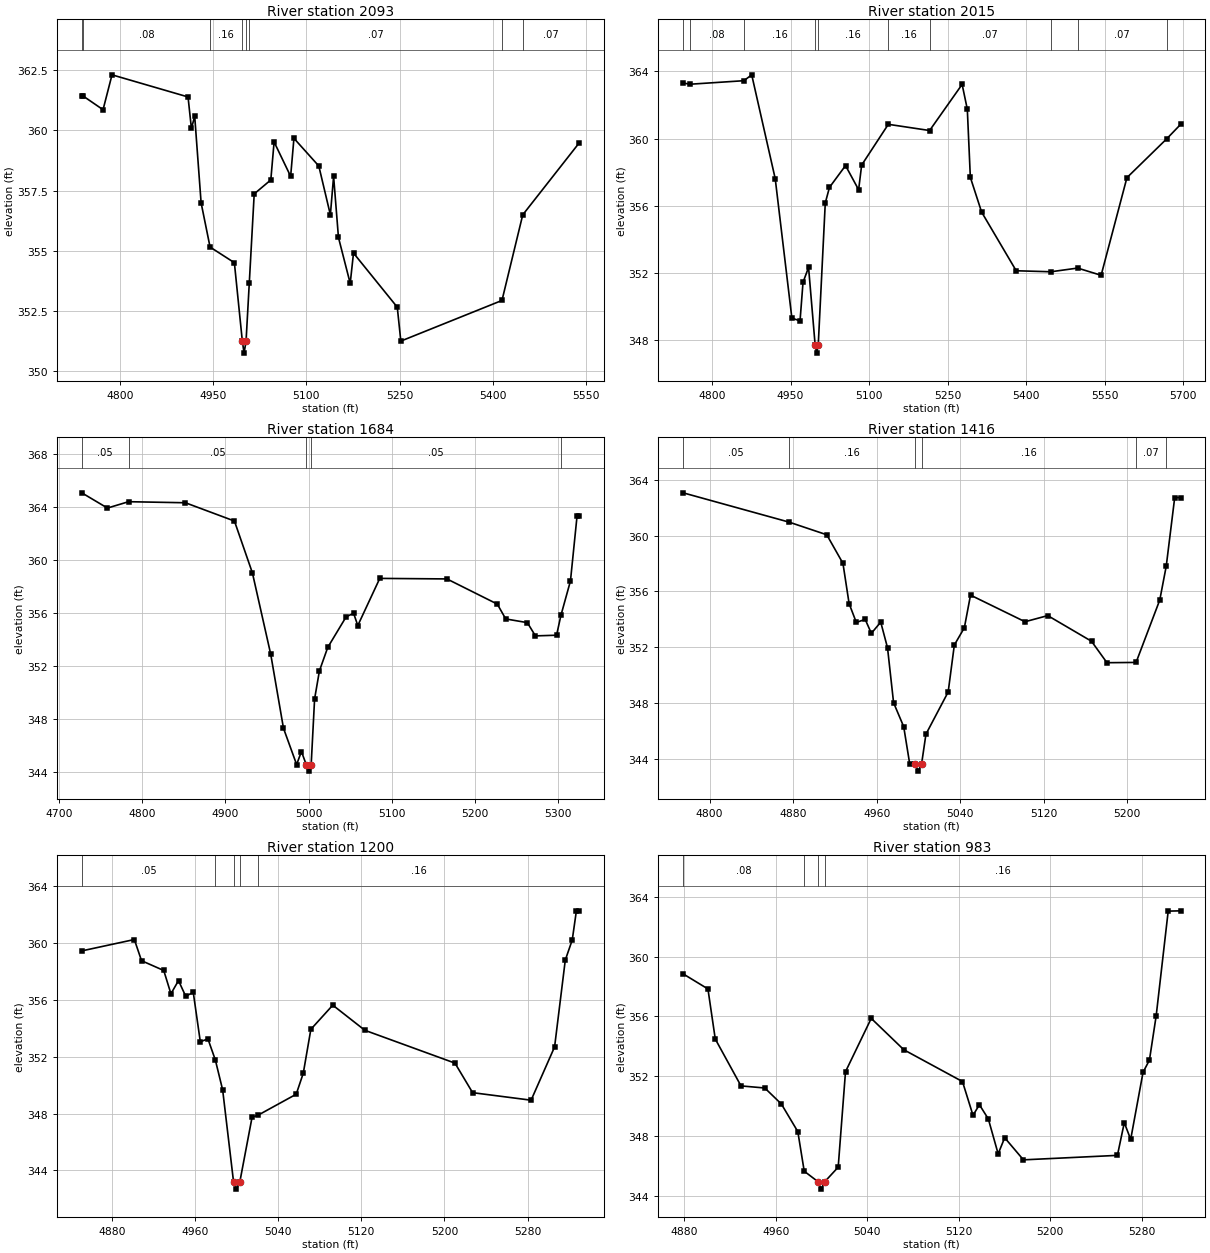
Type RM Length L Ch R = 1 ,2093    ,78,78,78
BEGIN DESCRIPTION:
Mapping XS c67242ac
END DESCRIPTION:
XS GIS Cut Line= 3
      3540339.99      10668062.7      3540476.09     10667644.67
      3540311.01     10667324.33
#Sta/Elev= 30
  4738.8  361.42  4741.4  361.42    4773  360.86  4787.4  362.31  4909.7  361.39
  4915.1  360.08  4920.4  360.59  4930.7  356.99  4945.1  355.15  4984.2   354.5
    4997  351.24  4999.8  350.74    5003  351.24  5008.2  353.66  5016.1  357.36
  5042.8  357.94  5048.1  359.52  5074.7  358.09    5080  359.67    5120  358.52
  5138.6  356.49  5143.8  358.09  5151.6  355.55  5170.5  353.64  5175.8   354.9
  5246.2  352.65  5251.9  351.24  5414.6  352.93    5448  356.49  5538.8  359.48
#Mann= 8 ,-1 , 0
  4738.8     .05       0  4741.4     .08       0  4945.1     .16       0
    4997     .07       0    5003     .16       0  5008.2     .07       0
  5414.6     .16       0    5448     .07       0
Bank Sta=4997,5003
XS Rating Curve= 0 ,0
Exp/Cntr=0.3,0.1

Type RM Length L Ch R = 1 ,2015    ,331,331,331
BEGIN DESCRIPTION:
Mapping XS 748c8b05
END DESCRIPTION:
XS GIS Cut Line= 3
      3540409.43     10668075.73      3540566.35     10667637.81
      3540321.53     10667219.24
#Sta/Elev= 30
  4744.9  363.31  4758.3  363.24    4861  363.45  4875.9   363.8  4920.8  357.61
  4952.6   349.3  4968.2  349.13  4973.9  351.43  4984.5  352.32    4997  347.71
  4999.8  347.21    5003  347.71  5016.4  356.16  5024.4  357.09  5055.1  358.39
  5080.1  356.95  5085.9  358.42  5136.8  360.85  5215.7  360.48  5277.8  363.23
  5287.7  361.75  5293.5  357.69    5315  355.62  5381.1  352.12  5447.4  352.06
  5498.4  352.28  5543.3  351.85  5592.6  357.67  5668.4  359.98    5695  360.84
#Mann= 10 ,-1 , 0
  4744.9     .05       0  4758.3     .08       0    4861     .16       0
    4997     .07       0    5003     .16       0  5136.8     .16       0
  5215.7     .07       0  5447.4     .16       0  5498.4     .07       0
  5668.4     .16       0
Bank Sta=4997,5003
XS Rating Curve= 0 ,0
Exp/Cntr=0.3,0.1

Type RM Length L Ch R = 1 ,1684    ,268,268,268
BEGIN DESCRIPTION:
Mapping XS adb0a783
END DESCRIPTION:
XS GIS Cut Line= 4
      3540804.51     10667876.92      3540651.54     10667611.11
      3540680.83      10667386.5      3540619.63     10667366.46
#Sta/Elev= 30
  4727.4  365.05  4758.2   363.9  4783.6  364.38  4851.9   364.3  4910.8  362.92
  4932.4     359  4954.4  352.86  4969.7  347.28  4985.5  344.54  4991.3  345.52
    4997  344.54  4999.8  344.04    5003  344.54  5007.1  349.49  5012.9  351.61
  5022.9  353.38  5045.1   355.7    5054  355.95    5059  355.03  5085.4  358.59
  5166.1  358.55  5226.6  356.65  5236.7  355.53  5262.7  355.25  5272.4  354.25
  5297.8   354.3    5303  355.79  5314.5   358.4  5322.4  363.29    5325  363.29
#Mann= 5 ,-1 , 0
  4727.4     .05       0  4783.6     .05       0    4997     .07       0
    5003     .05       0    5303     .07       0
Bank Sta=4997,5003
XS Rating Curve= 0 ,0
Exp/Cntr=0.3,0.1

Type RM Length L Ch R = 1 ,1416    ,216,216,216
BEGIN DESCRIPTION:
Mapping XS 1c58a83d
END DESCRIPTION:
XS GIS Cut Line= 3
      3540946.54     10667622.03      3540774.65     10667339.02
      3540655.46     10667255.78
#Sta/Elev= 30
  4774.6  363.07    4876  360.97  4912.2  360.06  4927.7  358.01  4933.6  355.12
  4940.5  353.77    4949  353.99  4954.9  352.99  4963.9  353.79  4970.4  351.95
  4976.2  348.01  4985.9  346.29  4991.7   343.6    4997   343.6  4999.8   343.1
    5003   343.6  5007.2  345.75  5028.5  348.78  5034.4  352.15    5044  353.39
  5049.9  355.73  5102.1  353.82  5123.9  354.26  5165.8  352.42  5180.6  350.88
  5208.5   350.9  5231.2  355.38  5237.4  357.81  5245.5  362.73  5251.1  362.73
#Mann= 6 ,-1 , 0
  4774.6     .05       0    4876     .16       0    4997     .07       0
    5003     .16       0  5208.5     .07       0  5237.4      .1       0
Bank Sta=4997,5003
XS Rating Curve= 0 ,0
Exp/Cntr=0.3,0.1

Type RM Length L Ch R = 1 ,1200    ,217,217,217
BEGIN DESCRIPTION:
Mapping XS e4d6c163
END DESCRIPTION:
XS GIS Cut Line= 3
      3541080.21     10667391.11      3540890.97     10667191.45
      3540707.57      10667102.8
#Sta/Elev= 30
  4850.9  359.45  4901.5  360.25  4908.4  358.76  4929.8  358.07  4936.7  356.43
    4944  357.36  4950.9  356.26  4958.2  356.53    4965  353.05  4972.3  353.26
  4979.5  351.76  4986.5  349.66    4997  343.18  4999.8  342.68    5003  343.18
  5014.8  347.74  5020.7  347.89  5057.3  349.36  5064.1  350.84  5071.4  353.93
  5092.5  355.63  5123.4  353.86  5210.1  351.55  5227.1  349.47  5283.4  348.94
    5306  352.69  5316.3   358.8    5323  360.22    5327  362.27  5329.7  362.27
#Mann= 5 ,-1 , 0
  4850.9     .05       0  4979.5     .08       0    4997     .07       0
    5003     .08       0  5020.7     .16       0
Bank Sta=4997,5003
XS Rating Curve= 0 ,0
Exp/Cntr=0.3,0.1

Type RM Length L Ch R = 1 ,983     ,523,523,523
BEGIN DESCRIPTION:
UNT108 IN CCTC 2.0
END DESCRIPTION:
XS GIS Cut Line= 3
      3541099.55     10667190.31       3540992.8     10667054.26
      3540760.76     10666932.45
#Sta/Elev= 30
  4879.1  358.85  4900.8  357.84  4907.2  354.49  4929.7  351.35  4950.5  351.21
    4965  350.14  4979.4  348.29    4985  345.64    4997  344.94  4999.8  344.44
    5003  344.94  5014.7  345.91  5021.1   352.3  5043.6  355.87  5072.1  353.77
  5123.4  351.64  5132.6  349.38  5138.2  350.09    5146  349.14  5154.6   346.8
  5160.3  347.88  5176.7   346.4  5258.9   346.7  5264.9  348.89  5270.5  347.77
  5281.3  352.26  5286.9  353.08  5292.8  356.05  5303.3  363.05  5314.1  363.07
#Mann= 4 ,-1 , 0
  4879.1     .08       0    4985     .16       0    4997     .07       0
    5003     .16       0
Bank Sta=4997,5003
XS Rating Curve= 0 ,0
Exp/Cntr=0.3,0.1

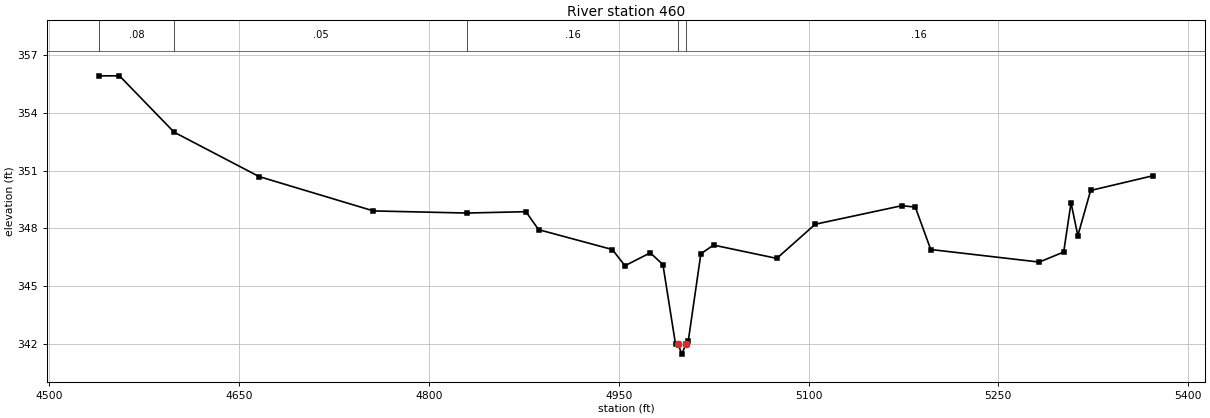
Type RM Length L Ch R = 1 ,460     ,0,0,0
BEGIN DESCRIPTION:
UNT108 IN CCTC 1.0
END DESCRIPTION:
XS GIS Cut Line= 4
      3541185.68     10666975.99       3541218.1     10666620.42
      3541079.21     10666620.42      3540962.39     10666936.26
#Sta/Elev= 30
  4539.4  355.91  4555.3  355.91  4598.5  352.99  4665.7  350.69  4756.1  348.91
  4829.8   348.8  4876.6  348.87  4886.6  347.94  4944.9  346.91  4954.9  346.07
  4974.9  346.74  4984.9  346.13  4994.9  341.99    4997  341.99  4999.8  341.49
    5003  341.99  5004.9  342.15  5014.9  346.69  5024.9  347.14  5074.9  346.45
  5105.3  348.22  5173.7  349.18  5184.4  349.11  5196.6  346.91  5282.4  346.26
  5301.7  346.78  5307.5  349.33  5312.9  347.63    5323  349.97  5372.1  350.73
#Mann= 5 ,-1 , 0
  4539.4     .08       0  4598.5     .05       0  4829.8     .16       0
    4997     .07       0    5003     .16       0
Bank Sta=4997,5003
XS Rating Curve= 0 ,0
Exp/Cntr=0.3,0.1

Chan Stop Cuts=-1
Use User Specified Reach Order=0
Composite Channel Slope=5