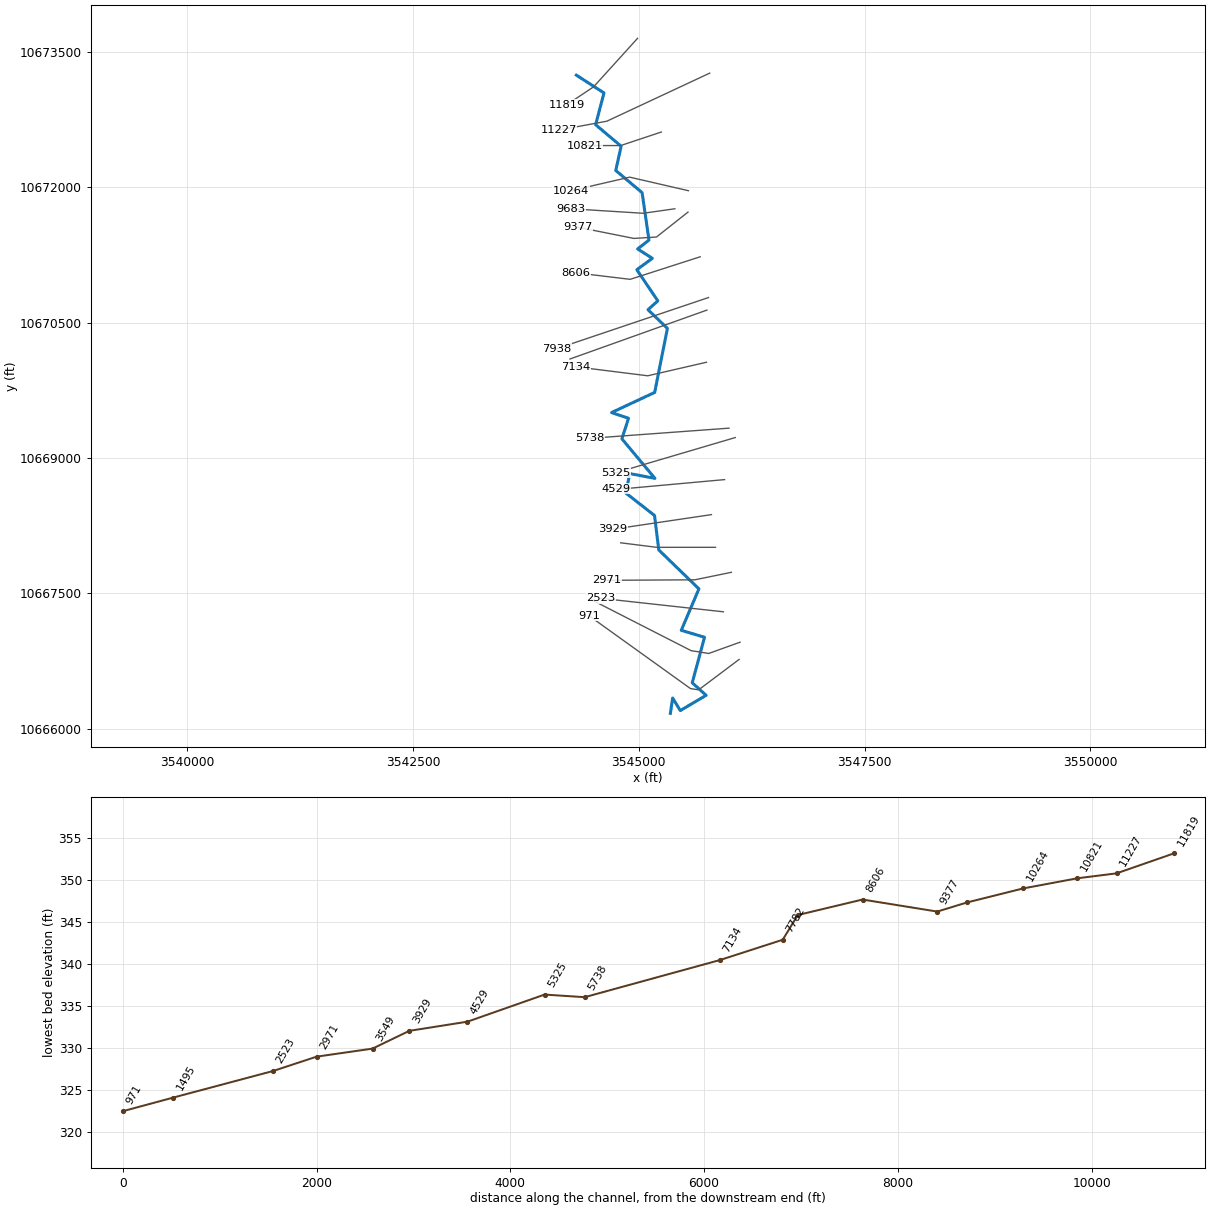
--- UNT109 IN CCTC.prj (project) ---

Proj Title=UNT109 IN CCTC Base Level Engineering
Current Plan=p01
Default Exp/Contr=0.3,0.1
English Units
Geom File=g01
Flow File=f01
Plan File=p01
BEGIN DESCRIPTION:
UNT109 IN CCTC
END DESCRIPTION:

--- UNT109 IN CCTC.p01 (plan) ---

Plan Title=Multiple Run
Short Identifier=Multiple
Geom File=g01
Flow File=f01
Subcritical Flow
K Sum by GR= 0
Std Step Tol= 0.01
Critical Tol= 0.01
Num of Std Step Trials= 20
Max Error Tol= 0.3
Flow Tol Ratio= 0.001
Split Flow NTrial= 30
Split Flow Tol= 0.02
Split Flow Ratio= 0.02
Log Output Level= 0
Friction Slope Method= 1
Unsteady Friction Slope Method= 2
Unsteady Bridges Friction Slope Method= 1
Parabolic Critical Depth
Global Vel Dist=  1 , 1 , 1
Global Log Level= 0
CheckData=True
Encroach Param= -1, 0, 0, 0
BEGIN DESCRIPTION:
Multiple Run
END DESCRIPTION:

--- UNT109 IN CCTC.f01 (steady flow) ---

Flow Title=Multiple
Number of Profiles=7
Profile Names=10-year,25-year,50-year,1pct_min,100-year,1pct_plu,500-year
River Rch & RM= UNT109 IN CCTC,Reach-1,11819
    1391    1907    2329    2074    2805    3793    4057
River Rch & RM= UNT109 IN CCTC,Reach-1,11227
    1961    2729    3368    3025    4091    5532    6024
Boundary for River Rch & Prof#=UNT109 IN CCTC,Reach-1,1
Up Type=0
Dn Type=3
Dn Slope=0.005
Boundary for River Rch & Prof#=UNT109 IN CCTC,Reach-1,2
Up Type=0
Dn Type=3
Dn Slope=0.005
Boundary for River Rch & Prof#=UNT109 IN CCTC,Reach-1,3
Up Type=0
Dn Type=3
Dn Slope=0.005
Boundary for River Rch & Prof#=UNT109 IN CCTC,Reach-1,4
Up Type=0
Dn Type=3
Dn Slope=0.005
Boundary for River Rch & Prof#=UNT109 IN CCTC,Reach-1,5
Up Type=0
Dn Type=3
Dn Slope=0.005
Boundary for River Rch & Prof#=UNT109 IN CCTC,Reach-1,6
Up Type=0
Dn Type=3
Dn Slope=0.005
Boundary for River Rch & Prof#=UNT109 IN CCTC,Reach-1,7
Up Type=0
Dn Type=3
Dn Slope=0.005

--- UNT109 IN CCTC.g01 (geometry) ---

Geom Title=Existing Conditions

River Reach=UNT109 IN CCTC,Reach-1
Reach XY= 30
      3544309.50     10673240.00      3544615.00     10673043.00
      3544522.50     10672691.00      3544804.75     10672453.00
      3544745.50     10672184.00      3545036.75     10671939.00
      3545113.00     10671414.00      3544988.00     10671315.00
      3545150.25     10671211.00      3544978.25     10671085.00
      3545211.00     10670740.00      3545102.00     10670642.00
      3545317.25     10670435.00      3545176.25     10669726.00
      3544699.25     10669503.00      3544886.50     10669439.00
      3544813.25     10669212.00      3545178.75     10668774.00
      3544901.00     10668827.00      3544855.25     10668613.00
      3545174.25     10668363.00      3545221.75     10667981.00
      3545665.75     10667550.00      3545470.50     10667091.00
      3545727.75     10667014.00      3545592.00     10666510.00
      3545745.25     10666371.00      3545459.50     10666202.00
      3545375.00     10666341.00      3545349.75     10666171.00

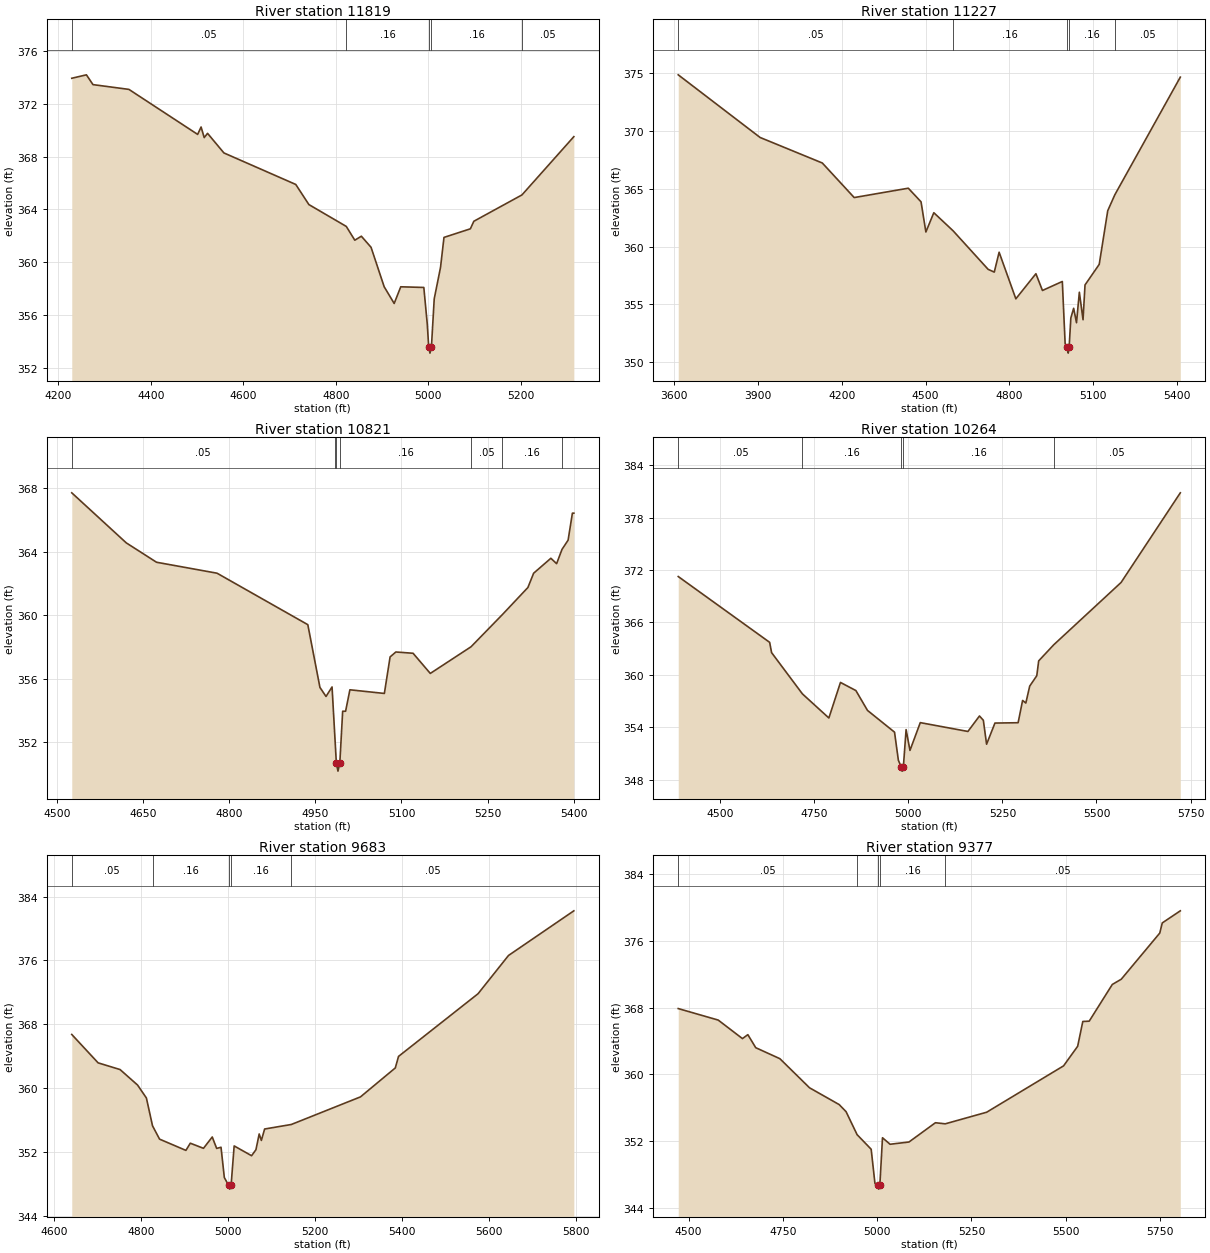
Type RM Length L Ch R = 1,11819,592,592,592
BEGIN DESCRIPTION:
UNT109 IN CCTC 18.0
END DESCRIPTION:
XS GIS Cut Line= 3
      3544986.65     10673647.84      3544499.61     10673110.19
      3544199.61     10672910.19
#Sta/Elev= 30
  4229.1  373.91  4260.8  374.17  4275.0  373.43  4352.7  373.07  4501.4  369.67
  4508.8  370.23  4515.6  369.43  4522.8  369.75  4558.2  368.27  4713.6  365.89
  4742.0  364.37  4822.9  362.72  4841.3  361.68  4855.5  361.98  4876.5  361.14
  4904.9  358.16  4926.5  356.90  4940.7  358.16  4990.6  358.11  4998.1  355.33
  5001.1  353.65  5003.9  353.15  5007.1  353.65  5013.1  357.25  5026.7  359.62
  5034.2  361.89  5091.3  362.54  5098.8  363.11  5202.9  365.10  5315.1  369.50
#Mann=5,-1,0
  4229.1    0.05       0  4822.9    0.16       0  5001.1    0.07       0
  5007.1    0.16       0  5202.9    0.05       0
Bank Sta=5001.1,5007.1
Exp/Cntr=0.3,0.1

Type RM Length L Ch R = 1,11227,406,406,406
BEGIN DESCRIPTION:
UNT109 IN CCTC 17.0
END DESCRIPTION:
XS GIS Cut Line= 3
      3545785.27     10673262.41      3544646.56     10672730.01
      3544113.94     10672631.37
#Sta/Elev= 30
  3614.1  374.86  3907.4  369.44  4130.3  367.23  4244.5  364.24  4438.3  365.05
  4484.0  363.87  4501.3  361.26  4529.7  362.93  4599.0  361.36  4724.3  358.03
  4746.3  357.79  4763.7  359.51  4823.6  355.48  4895.5  357.65  4918.9  356.20
  4990.1  356.98  5000.2  351.60  5008.5  351.28  5011.2  350.78  5014.5  351.28
  5020.6  353.82  5030.7  354.66  5040.9  353.41  5051.1  356.05  5064.3  353.67
  5071.4  356.68  5122.3  358.46  5152.8  363.10  5178.2  364.48  5412.8  374.66
#Mann=5,-1,0
  3614.1    0.05       0  4599.0    0.16       0  5008.5    0.07       0
  5014.5    0.16       0  5178.2    0.05       0
Bank Sta=5008.5,5014.5
Exp/Cntr=0.3,0.1

Type RM Length L Ch R = 1,10821,557,557,557
BEGIN DESCRIPTION:
UNT109 IN CCTC 16.0
END DESCRIPTION:
XS GIS Cut Line= 3
      3545249.66     10672610.20      3544799.61     10672460.19
      3544399.60     10672460.19
#Sta/Elev= 30
  4525.8  367.71  4620.7  364.56  4673.4  363.34  4778.8  362.65  4936.9  359.41
  4958.0  355.46  4968.6  354.89  4979.1  355.49  4983.7  352.55  4986.6  350.69
  4989.4  350.19  4992.6  350.69  4997.6  353.96  5002.7  353.96  5010.2  355.31
  5070.2  355.08  5080.2  357.38  5090.2  357.69  5120.2  357.61  5150.2  356.34
  5221.2  358.02  5275.9  360.05  5320.2  361.75  5330.2  362.65  5360.2  363.59
  5370.2  363.25  5379.6  364.15  5390.2  364.73  5397.7  366.43  5400.2  366.43
#Mann=7,-1,0
  4525.8    0.05       0  4983.7    0.16       0  4986.6    0.07       0
  4992.6    0.16       0  5221.2    0.05       0  5275.9    0.16       0
  5379.6    0.05       0
Bank Sta=4986.6,4992.6
Exp/Cntr=0.3,0.1

Type RM Length L Ch R = 1,10264,581,581,581
BEGIN DESCRIPTION:
UNT109 IN CCTC 15.0
END DESCRIPTION:
XS GIS Cut Line= 3
      3545549.65     10671960.18      3544899.61     10672110.19
      3544249.62     10671960.19
#Sta/Elev= 30
  4388.6  371.26  4631.5  363.73  4636.7  362.55  4718.6  357.83  4788.9  355.07
  4819.7  359.14  4860.7  358.21  4891.5  355.94  4963.4  353.45  4973.6  350.23
  4980.9  349.49  4983.6  348.99  4986.9  349.49  4994.1  353.74  5004.4  351.36
  5031.8  354.54  5158.4  353.53  5189.1  355.30  5199.4  354.81  5208.0  352.07
  5230.2  354.49  5291.8  354.53  5303.7  357.08  5312.3  356.78  5322.6  358.72
  5341.4  359.91  5346.5  361.61  5386.5  363.45  5565.4  370.58  5722.8  380.84
#Mann=5,-1,0
  4388.6    0.05       0  4718.6    0.16       0  4980.9    0.07       0
  4986.9    0.16       0  5386.5    0.05       0
Bank Sta=4980.9,4986.9
Exp/Cntr=0.3,0.1

Type RM Length L Ch R = 1,9683,306,306,306
BEGIN DESCRIPTION:
UNT109 IN CCTC 14.0
END DESCRIPTION:
XS GIS Cut Line= 3
      3545399.60     10671760.19      3545049.61     10671710.19
      3544249.62     10671760.19
#Sta/Elev= 30
  4639.9  366.72  4700.5  363.16  4751.0  362.32  4791.4  360.37  4811.6  358.75
  4825.7  355.26  4841.9  353.59  4902.5  352.18  4912.6  353.08  4942.9  352.44
  4963.1  353.86  4973.2  352.43  4983.3  352.57  4990.9  348.77  5000.5  347.82
  5003.2  347.32  5006.5  347.82  5013.5  352.74  5053.6  351.51  5063.6  352.26
  5071.1  354.24  5076.1  353.43  5083.6  354.86  5145.1  355.43  5304.1  358.89
  5384.2  362.52  5391.7  363.97  5574.6  371.83  5644.7  376.63  5795.0  382.23
#Mann=5,-1,0
  4639.9    0.05       0  4825.7    0.16       0  5000.5    0.07       0
  5006.5    0.16       0  5145.1    0.05       0
Bank Sta=5000.5,5006.5
Exp/Cntr=0.3,0.1

Type RM Length L Ch R = 1,9377,771,771,771
BEGIN DESCRIPTION:
UNT109 IN CCTC 13.0
END DESCRIPTION:
XS GIS Cut Line= 4
      3545544.97     10671723.20      3545196.03     10671447.18
      3544946.03     10671431.55      3544322.77     10671556.20
#Sta/Elev= 30
  4472.7  367.89  4578.7  366.51  4642.9  364.29  4657.3  364.76  4678.1  363.20
  4742.2  361.88  4820.8  358.39  4899.3  356.38  4917.6  355.53  4946.9  352.77
  4984.2  351.02  4994.2  346.92  5001.2  346.74  5004.0  346.24  5007.2  346.74
  5014.2  352.40  5034.3  351.62  5084.4  351.89  5154.5  354.20  5180.6  354.07
  5290.3  355.46  5494.2  361.02  5531.6  363.37  5545.2  366.34  5562.2  366.38
  5623.4  370.78  5647.2  371.41  5749.2  376.94  5755.9  378.16  5803.7  379.61
#Mann=5,-1,0
  4472.7    0.05       0  4946.9    0.16       0  5001.2    0.07       0
  5007.2    0.16       0  5180.6    0.05       0
Bank Sta=5001.2,5007.2
Exp/Cntr=0.3,0.1

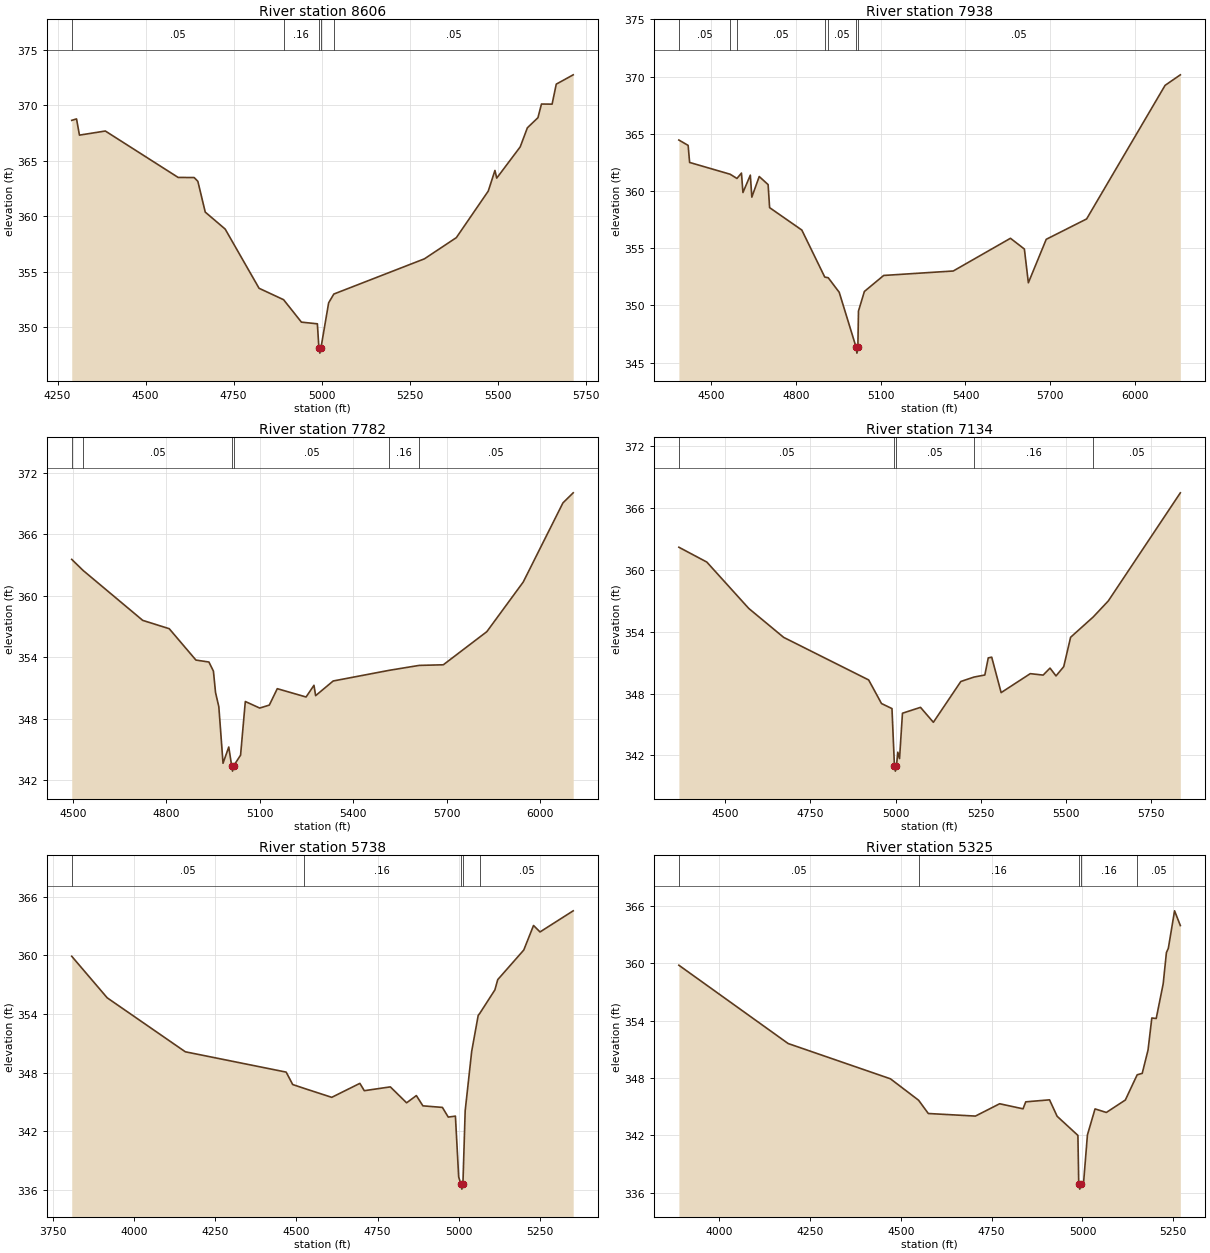
Type RM Length L Ch R = 1,8606,668,668,668
BEGIN DESCRIPTION:
UNT109 IN CCTC 12.0
END DESCRIPTION:
XS GIS Cut Line= 3
      3545680.43     10671228.43      3544904.37     10670978.43
      3544300.19     10671051.34
#Sta/Elev= 30
  4290.2  368.63  4303.8  368.76  4312.1  367.30  4385.6  367.67  4592.4  363.49
  4637.8  363.48  4648.3  363.14  4669.3  360.37  4725.9  358.84  4822.1  353.51
  4891.8  352.48  4942.4  350.46  4987.7  350.31  4992.0  348.17  4994.7  347.67
  4998.0  348.17  5019.7  352.20  5034.4  352.99  5291.6  356.16  5382.3  358.07
  5472.9  362.26  5491.9  364.12  5497.0  363.43  5563.6  366.24  5584.0  367.96
  5614.0  368.87  5624.0  370.10  5654.2  370.09  5666.0  371.89  5714.1  372.73
#Mann=5,-1,0
  4290.2    0.05       0  4891.8    0.16       0  4992.0    0.07       0
  4998.0    0.16       0  5034.4    0.05       0
Bank Sta=4992,4998
Exp/Cntr=0.3,0.1

Type RM Length L Ch R = 1,7938,156,156,156
BEGIN DESCRIPTION:
UNT109 IN CCTC 11.0
END DESCRIPTION:
XS GIS Cut Line= 2
      3545772.01     10670776.89      3544089.72     10670209.18
#Sta/Elev= 30
  4385.3  364.46  4418.1  363.99  4423.3  362.50  4566.8  361.47  4590.9  361.10
  4606.9  361.57  4612.1  359.87  4638.3  361.39  4643.6  359.47  4669.8  361.27
  4701.3  360.56  4706.5  358.55  4820.6  356.59  4901.8  352.48  4914.1  352.42
  4953.0  351.15  5013.0  346.33  5015.7  345.83  5019.0  346.33  5021.2  349.51
  5042.1  351.22  5110.4  352.62  5356.8  353.01  5559.3  355.87  5608.6  354.93
  5622.7  351.98  5686.0  355.78  5828.9  357.56  6106.8  369.24  6160.8  370.16
#Mann=7,-1,0
  4385.3    0.05       0  4566.8    0.08       0  4590.9    0.05       0
  4901.8    0.16       0  4914.1    0.05       0  5013.0    0.04       0
  5019.0    0.05       0
Bank Sta=5013,5019
Exp/Cntr=0.3,0.1

Type RM Length L Ch R = 1,7782,648,648,648
BEGIN DESCRIPTION:
UNT109 IN CCTC 10.0
END DESCRIPTION:
XS GIS Cut Line= 2
      3545754.21     10670637.78      3544238.60     10670096.12
#Sta/Elev= 30
  4495.9  363.54  4532.4  362.46  4723.8  357.59  4808.8  356.78  4894.5  353.72
  4936.2  353.53  4950.7  352.64  4957.4  350.56  4968.0  349.17  4981.5  343.66
  4999.9  345.24  5009.3  343.39  5012.0  342.89  5015.3  343.39  5037.8  344.45
  5053.0  349.68  5099.3  349.04  5130.1  349.33  5155.6  350.93  5248.0  350.12
  5273.4  351.26  5278.7  350.25  5335.0  351.68  5514.8  352.72  5610.8  353.20
  5688.5  353.26  5828.2  356.49  5945.0  361.33  6072.5  369.05  6105.4  370.03
#Mann=6,-1,0
  4495.9    0.08       0  4532.4    0.05       0  5009.3   0.035       0
  5015.3    0.05       0  5514.8    0.16       0  5610.8    0.05       0
Bank Sta=5009.3,5015.3
Exp/Cntr=0.3,0.1

Type RM Length L Ch R = 1,7134,1396,1396,1396
BEGIN DESCRIPTION:
UNT109 IN CCTC 9.0
END DESCRIPTION:
XS GIS Cut Line= 3
      3545749.64     10670060.20      3545099.61     10669910.19
      3544299.65     10670010.18
#Sta/Elev= 30
  4363.5  362.21  4445.6  360.77  4568.8  356.27  4671.4  353.46  4921.1  349.33
  4958.8  347.04  4989.6  346.55  4996.8  340.98  4999.6  340.48  5002.8  340.98
  5006.7  342.32  5011.8  341.70  5020.4  346.10  5073.4  346.67  5111.2  345.22
  5191.9  349.18  5230.7  349.61  5262.4  349.81  5272.5  351.47  5282.6  351.54
  5310.3  348.10  5395.9  349.94  5433.7  349.80  5453.9  350.48  5471.5  349.72
  5494.2  350.62  5514.4  353.47  5581.1  355.45  5625.2  357.00  5836.8  367.49
#Mann=5,-1,0
  4363.5    0.05       0  4996.8   0.035       0  5002.8    0.05       0
  5230.7    0.16       0  5581.1    0.05       0
Bank Sta=4996.8,5002.8
Exp/Cntr=0.3,0.1

Type RM Length L Ch R = 1,5738,413,413,413
BEGIN DESCRIPTION:
UNT109 IN CCTC 7.0
END DESCRIPTION:
XS GIS Cut Line= 2
      3545998.59     10669330.14      3544457.71     10669217.28
#Sta/Elev= 30
  3807.6  359.89  3916.9  355.64  4157.5  350.12  4468.3  348.04  4488.4  346.77
  4522.5  346.39  4608.7  345.46  4695.3  346.89  4709.0  346.14  4789.2  346.53
  4839.3  344.90  4869.4  345.64  4889.5  344.59  4949.6  344.43  4967.6  343.44
  4989.7  343.54  4999.8  337.31  5006.8  336.57  5009.5  336.07  5012.8  336.57
  5019.8  344.09  5039.9  350.17  5059.9  353.84  5064.8  354.05  5111.3  356.45
  5120.1  357.50  5200.3  360.53  5230.4  363.04  5250.4  362.38  5352.6  364.54
#Mann=5,-1,0
  3807.6    0.05       0  4522.5    0.16       0  5006.8    0.07       0
  5012.8    0.16       0  5064.8    0.05       0
Bank Sta=5006.8,5012.8
Exp/Cntr=0.3,0.1

Type RM Length L Ch R = 1,5325,796,796,796
BEGIN DESCRIPTION:
UNT109 IN CCTC 6.0
END DESCRIPTION:
XS GIS Cut Line= 2
      3546068.04     10669225.98      3544744.36     10668835.39
#Sta/Elev= 30
  3889.3  359.80  4190.0  351.61  4471.5  347.92  4549.0  345.68  4575.8  344.29
  4705.4  344.02  4772.1  345.31  4836.5  344.78  4843.9  345.51  4909.4  345.72
  4930.3  344.00  4987.5  342.00  4989.8  336.88  4992.6  336.38  4995.8  336.88
  5003.3  337.16  5013.7  342.05  5034.6  344.77  5065.8  344.40  5118.0  345.70
  5150.6  348.34  5164.5  348.49  5180.5  350.93  5190.9  354.28  5203.0  354.23
  5222.2  357.86  5231.1  361.13  5236.3  361.56  5253.5  365.49  5269.4  363.95
#Mann=5,-1,0
  3889.3    0.05       0  4549.0    0.16       0  4989.8    0.07       0
  4995.8    0.16       0  5150.6    0.05       0
Bank Sta=4989.8,4995.8
Exp/Cntr=0.3,0.1

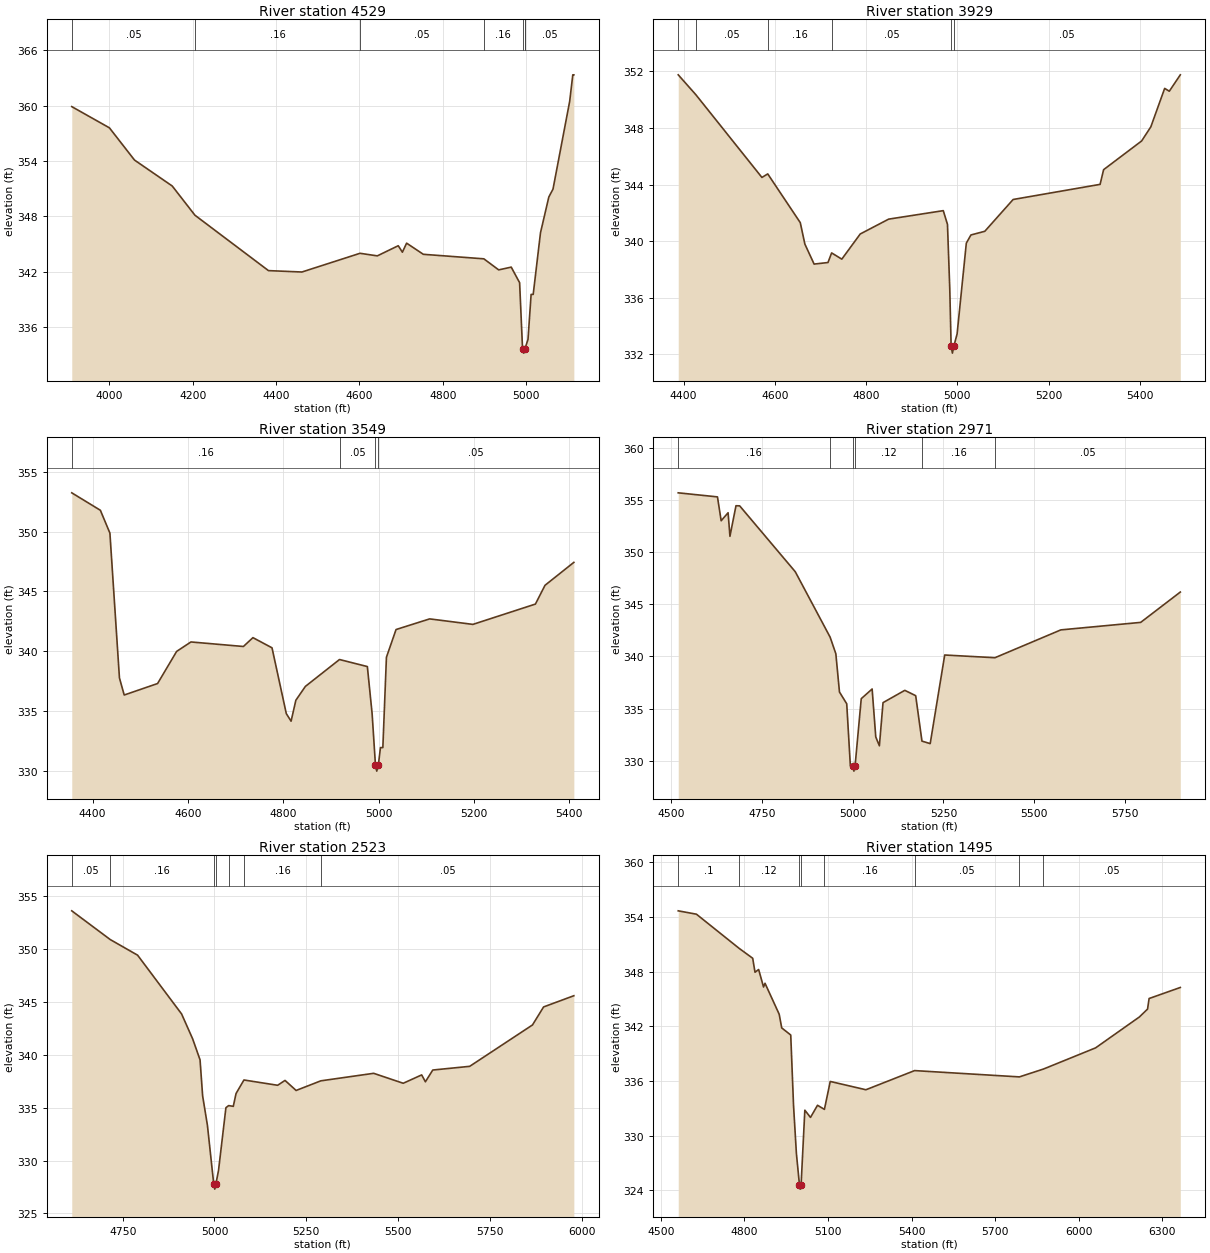
Type RM Length L Ch R = 1,4529,600,600,600
BEGIN DESCRIPTION:
UNT109 IN CCTC 5.0
END DESCRIPTION:
XS GIS Cut Line= 3
      3545949.58     10668760.19      3544849.61     10668660.19
      3544749.61     10668660.19
#Sta/Elev= 30
  3909.9  359.90  4000.2  357.60  4060.5  354.10  4150.9  351.29  4205.4  348.12
  4381.8  342.11  4462.1  341.96  4601.5  343.99  4642.9  343.71  4693.1  344.81
  4703.1  344.11  4713.2  345.09  4753.3  343.88  4898.5  343.39  4934.1  342.19
  4964.2  342.49  4984.3  340.80  4991.3  333.66  4994.1  333.16  4997.3  333.66
  4997.5  333.69  5004.4  334.64  5011.9  339.53  5016.9  339.53  5034.4  346.22
  5054.4  350.10  5064.4  350.95  5104.4  360.47  5111.9  363.35  5114.4  363.35
#Mann=7,-1,0
  3909.9    0.05       0  4205.4    0.16       0  4601.5    0.05       0
  4898.5    0.16       0  4991.3    0.03       0  4997.3    0.16       0
  4997.5    0.05       0
Bank Sta=4991.3,4997.3
Exp/Cntr=0.3,0.1

Type RM Length L Ch R = 1,3929,380,380,380
BEGIN DESCRIPTION:
UNT109 IN CCTC 4.0
END DESCRIPTION:
XS GIS Cut Line= 2
      3545804.21     10668372.37      3544715.72     10668210.92
#Sta/Elev= 30
  4388.2  351.76  4426.9  350.35  4571.6  344.50  4584.4  344.75  4655.7  341.30
  4665.8  339.78  4686.0  338.37  4716.4  338.48  4724.4  339.16  4746.7  338.72
  4787.1  340.50  4849.4  341.55  4969.1  342.15  4978.3  341.18  4983.3  336.64
  4986.3  332.57  4989.1  332.07  4992.3  332.57  4999.4  333.43  5019.6  339.85
  5029.7  340.43  5060.1  340.69  5122.2  342.94  5312.8  344.01  5320.5  345.05
  5403.8  347.08  5424.0  348.08  5454.3  350.80  5464.5  350.60  5488.6  351.76
#Mann=6,-1,0
  4388.2    0.16       0  4426.9    0.05       0  4584.4    0.16       0
  4724.4    0.05       0  4986.3   0.035       0  4992.3    0.05       0
Bank Sta=4986.3,4992.3
Exp/Cntr=0.3,0.1

Type RM Length L Ch R = 1,3549,578,578,578
BEGIN DESCRIPTION:
UNT109 IN CCTC 3.0
END DESCRIPTION:
XS GIS Cut Line= 3
      3545849.57     10668010.19      3545199.61     10668010.19
      3544799.59     10668060.19
#Sta/Elev= 30
  4356.5  353.25  4416.5  351.79  4436.5  349.88  4456.5  337.76  4466.5  336.33
  4536.5  337.29  4576.5  339.98  4606.5  340.77  4716.5  340.39  4736.5  341.13
  4776.5  340.28  4806.5  334.77  4816.5  334.14  4826.5  335.89  4846.5  337.05
  4918.1  339.30  4976.5  338.71  4986.5  334.76  4993.5  330.46  4996.2  329.96
  4999.5  330.46  5004.0  331.93  5009.0  331.93  5016.5  339.49  5036.7  341.81
  5107.2  342.70  5197.9  342.24  5329.0  343.94  5349.1  345.51  5409.6  347.43
#Mann=4,-1,0
  4356.5    0.16       0  4918.1    0.05       0  4993.5   0.035       0
  4999.5    0.05       0
Bank Sta=4993.5,4999.5
Exp/Cntr=0.3,0.1

Type RM Length L Ch R = 1,2971,448,448,448
BEGIN DESCRIPTION:
Mapping XS 0d66e117
END DESCRIPTION:
XS GIS Cut Line= 3
      3546025.48     10667733.57      3545619.21     10667650.23
      3544650.46     10667645.02
#Sta/Elev= 30
  4519.3  355.70  4627.4  355.31  4637.6  353.02  4656.7  353.79  4661.8  351.53
  4678.4  354.46  4688.6  354.45  4841.8  348.13  4937.9  341.85  4953.6  340.26
  4963.6  336.59  4983.6  335.46  4993.6  329.53  5000.6  329.50  5003.4  329.00
  5006.6  329.50  5023.6  335.95  5053.6  336.88  5063.6  332.28  5073.6  331.43
  5083.6  335.57  5143.6  336.75  5173.6  336.24  5190.9  331.88  5213.6  331.64
  5253.6  340.14  5392.0  339.88  5573.6  342.55  5793.6  343.27  5902.8  346.18
#Mann=6,-1,0
  4519.3    0.16       0  4937.9    0.12       0  5000.6    0.07       0
  5006.6    0.12       0  5190.9    0.16       0  5392.0    0.05       0
Bank Sta=5000.6,5006.6
Exp/Cntr=0.3,0.1

Type RM Length L Ch R = 1,2523,1028,1028,1028
BEGIN DESCRIPTION:
UNT109 IN CCTC 2.0
END DESCRIPTION:
XS GIS Cut Line= 2
      3545936.91     10667296.06      3544577.69     10667445.38
#Sta/Elev= 30
  4611.3  353.59  4715.9  350.88  4790.6  349.40  4910.4  343.85  4940.6  341.49
  4960.7  339.51  4967.7  336.11  4980.8  333.32  4997.9  327.80  5000.7  327.30
  5003.9  327.80  5011.0  329.07  5031.1  334.99  5038.5  335.19  5051.2  335.12
  5058.7  336.33  5080.2  337.61  5172.0  337.11  5192.1  337.57  5222.3  336.62
  5289.6  337.53  5433.5  338.24  5514.0  337.30  5564.3  338.09  5574.4  337.44
  5594.5  338.55  5695.1  338.90  5866.1  342.81  5896.3  344.51  5978.7  345.57
#Mann=7,-1,0
  4611.3    0.05       0  4715.9    0.16       0  4997.9    0.07       0
  5003.9    0.16       0  5038.5    0.12       0  5080.2    0.16       0
  5289.6    0.05       0
Bank Sta=4997.9,5003.9
Exp/Cntr=0.3,0.1

Type RM Length L Ch R = 1,1495,524,524,524
BEGIN DESCRIPTION:
Mapping XS dda2233a
END DESCRIPTION:
XS GIS Cut Line= 4
      3546121.15     10666959.44      3545773.95     10666834.45
      3545579.51     10666865.70      3544478.86     10667428.17
#Sta/Elev= 30
  4562.4  354.65  4627.8  354.28  4780.0  350.56  4829.7  349.45  4837.9  347.92
  4851.0  348.22  4868.6  346.30  4873.9  346.71  4924.7  343.32  4933.8  341.82
  4966.2  341.04  4976.3  333.28  4986.5  328.06  4997.4  324.65  5000.1  324.15
  5003.4  324.65  5016.8  332.80  5037.1  332.01  5062.3  333.34  5087.0  332.89
  5108.0  335.95  5236.0  335.04  5410.7  337.14  5786.8  336.45  5873.2  337.31
  6060.3  339.63  6217.6  343.02  6246.8  343.88  6252.4  345.04  6364.4  346.25
#Mann=8,-1,0
  4562.4     0.1       0  4780.0    0.12       0  4997.4    0.07       0
  5003.4    0.12       0  5087.0    0.16       0  5410.7    0.05       0
  5786.8    0.16       0  5873.2    0.05       0
Bank Sta=4997.4,5003.4
Exp/Cntr=0.3,0.1

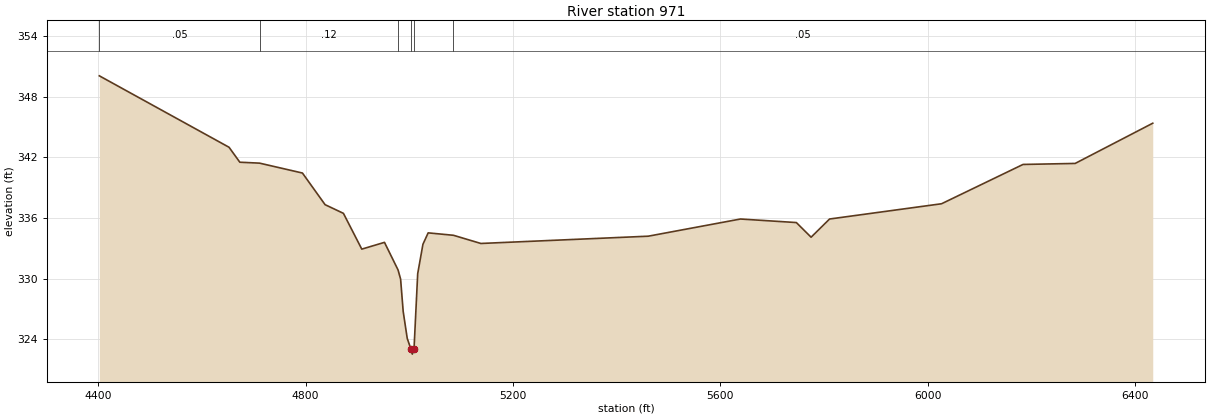
Type RM Length L Ch R = 1,971,0,0,0
BEGIN DESCRIPTION:
UNT109 IN CCTC 1.0
END DESCRIPTION:
XS GIS Cut Line= 4
      3546110.79     10666768.50      3545662.84     10666431.67
      3545572.56     10666445.56      3544451.07     10667251.09
#Sta/Elev= 30
  4402.0  350.06  4652.3  342.99  4673.1  341.51  4711.1  341.42  4793.9  340.44
  4837.6  337.31  4873.0  336.45  4908.4  332.91  4952.2  333.58  4978.4  330.85
  4983.3  329.95  4988.3  326.74  4996.1  324.08  5003.2  323.02  5005.9  322.52
  5009.2  323.02  5016.3  330.48  5026.4  333.39  5036.5  334.52  5085.3  334.28
  5138.2  333.47  5461.1  334.19  5639.1  335.89  5746.9  335.54  5775.4  334.09
  5811.0  335.89  6027.1  337.40  6184.3  341.29  6284.9  341.39  6434.6  345.37
#Mann=6,-1,0
  4402.0    0.05       0  4711.1    0.12       0  4978.4    0.16       0
  5003.2    0.07       0  5009.2    0.16       0  5085.3    0.05       0
Bank Sta=5003.2,5009.2
Exp/Cntr=0.3,0.1

Chan Stop Cuts=-1