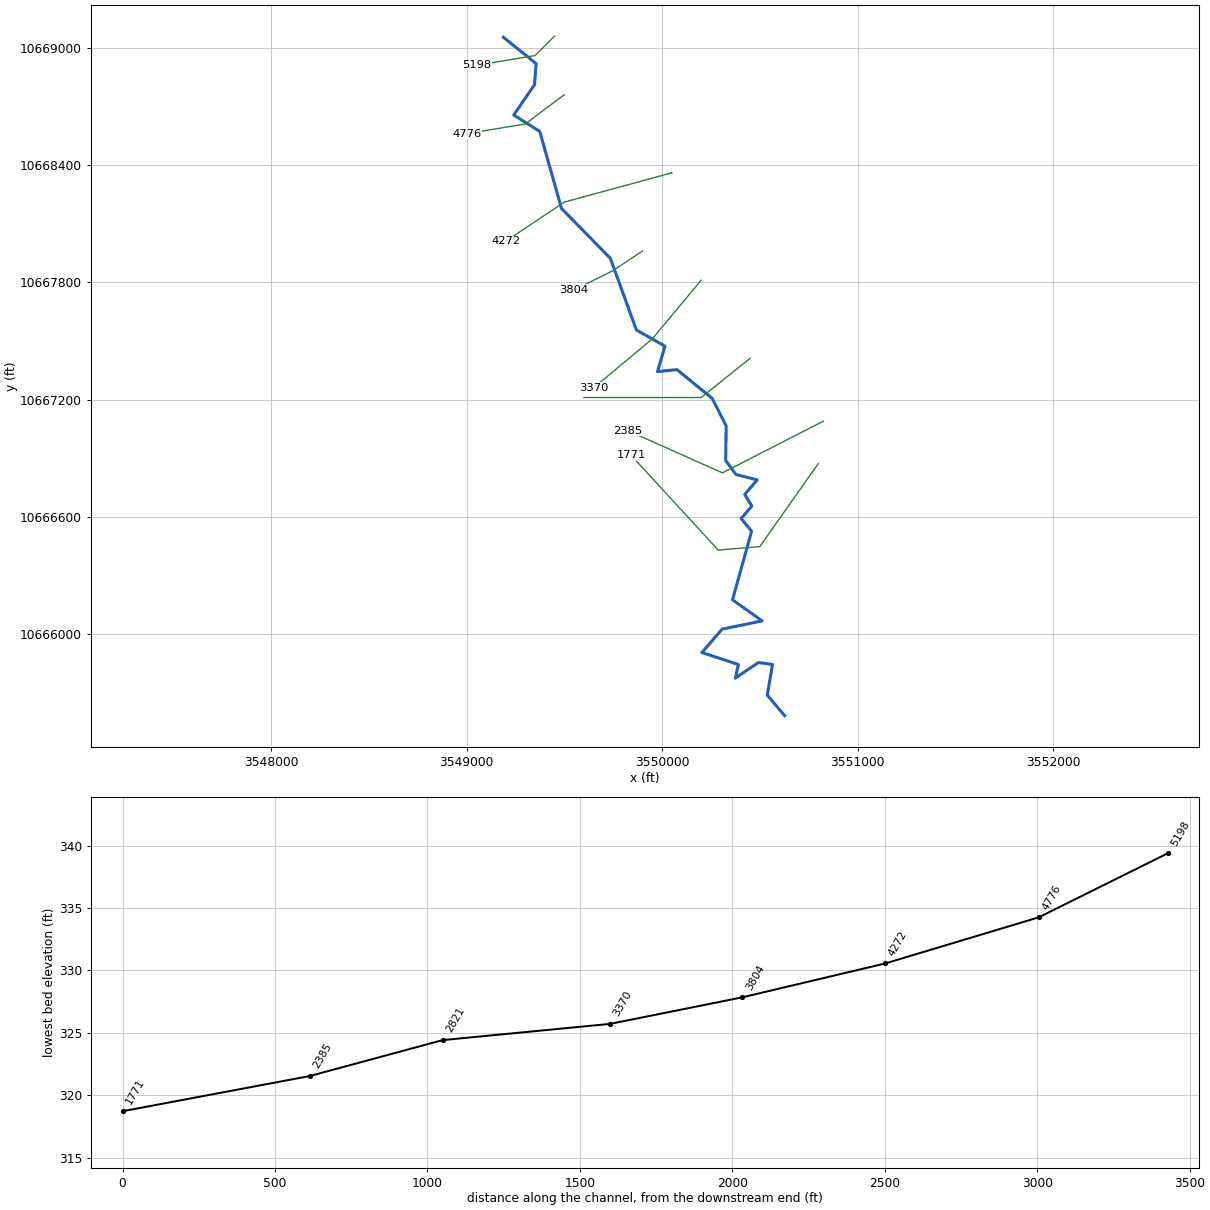
--- UNT110 IN CCTC.prj (project) ---

Proj Title=UNT110 IN CCTC Base Level Engineering
Current Plan=p01
Default Exp/Contr=0.3,0.1
English Units
Geom File=g01
Flow File=f01
Plan File=p01
Y Axis Title=Elevation
X Axis Title(PF)=Main Channel Distance
X Axis Title(XS)=Station
BEGIN DESCRIPTION:
UNT110 IN CCTC
END DESCRIPTION:
DSS Export Rating Curves= 0
DSS Export Rating Curve Sorted= 0
DSS Export Volume Flow Curves= 0
DXF OffsetX= 0
DXF OffsetY= 0
DXF ScaleX= 1
DXF ScaleY= 10

--- UNT110 IN CCTC.p01 (plan) ---

Plan Title=Multiple Run
Short Identifier=Multiple
Geom File=g01
Flow File=f01
Subcritical Flow
K Sum by GR= 0
Std Step Tol= 0.01
Critical Tol= 0.01
Num of Std Step Trials= 20
Max Error Tol= 0.3
Flow Tol Ratio= 0.001
Split Flow NTrial= 30
Split Flow Tol= 0.02
Split Flow Ratio= 0.02
Log Output Level= 0
Friction Slope Method= 1
Unsteady Friction Slope Method= 2
Unsteady Bridges Friction Slope Method= 1
Parabolic Critical Depth
Global Vel Dist=  1 , 1 , 1
Global Log Level= 0
CheckData=True
Encroach Param= -1, 0, 0, 0
BEGIN DESCRIPTION:
Multiple Run
END DESCRIPTION:

--- UNT110 IN CCTC.f01 (steady flow) ---

Flow Title=Multiple
Number of Profiles=7
Profile Names=10-year,25-year,50-year,1pct_min,100-year,1pct_plu,500-year
River Rch & RM= UNT110 IN CCTC,Reach-1,5198
    1145    1555    1888    1674    2263    3061    3242
Boundary for River Rch & Prof#=UNT110 IN CCTC,Reach-1,1
Up Type=0
Dn Type=3
Dn Slope=0.005
Boundary for River Rch & Prof#=UNT110 IN CCTC,Reach-1,2
Up Type=0
Dn Type=3
Dn Slope=0.005
Boundary for River Rch & Prof#=UNT110 IN CCTC,Reach-1,3
Up Type=0
Dn Type=3
Dn Slope=0.005
Boundary for River Rch & Prof#=UNT110 IN CCTC,Reach-1,4
Up Type=0
Dn Type=3
Dn Slope=0.005
Boundary for River Rch & Prof#=UNT110 IN CCTC,Reach-1,5
Up Type=0
Dn Type=3
Dn Slope=0.005
Boundary for River Rch & Prof#=UNT110 IN CCTC,Reach-1,6
Up Type=0
Dn Type=3
Dn Slope=0.005
Boundary for River Rch & Prof#=UNT110 IN CCTC,Reach-1,7
Up Type=0
Dn Type=3
Dn Slope=0.005

--- UNT110 IN CCTC.g01 (geometry) ---

Geom Title=Existing Conditions
Program Version=4.10

River Reach=UNT110 IN CCTC  ,Reach-1
Reach XY= 30
      3549187.86     10669053.82        3549355.       10668919.
        3549347.       10668811.      3549240.75       10668656.
      3549373.75       10668572.        3549485.       10668178.
      3549734.75       10667923.      3549868.25       10667556.
       3550014.5       10667473.       3549976.5       10667343.
        3550076.       10667353.        3550256.       10667206.
      3550327.75       10667065.      3550325.25       10666888.
      3550378.25       10666816.      3550486.75       10666789.
      3550422.75       10666714.      3550459.25       10666655.
       3550404.5       10666591.      3550457.75       10666526.
      3550360.25       10666175.        3550512.       10666067.
      3550307.25       10666025.      3550203.75       10665905.
      3550390.25       10665844.       3550374.5       10665774.
        3550493.       10665854.        3550565.       10665844.
        3550538.       10665687.      3550627.25       10665582.

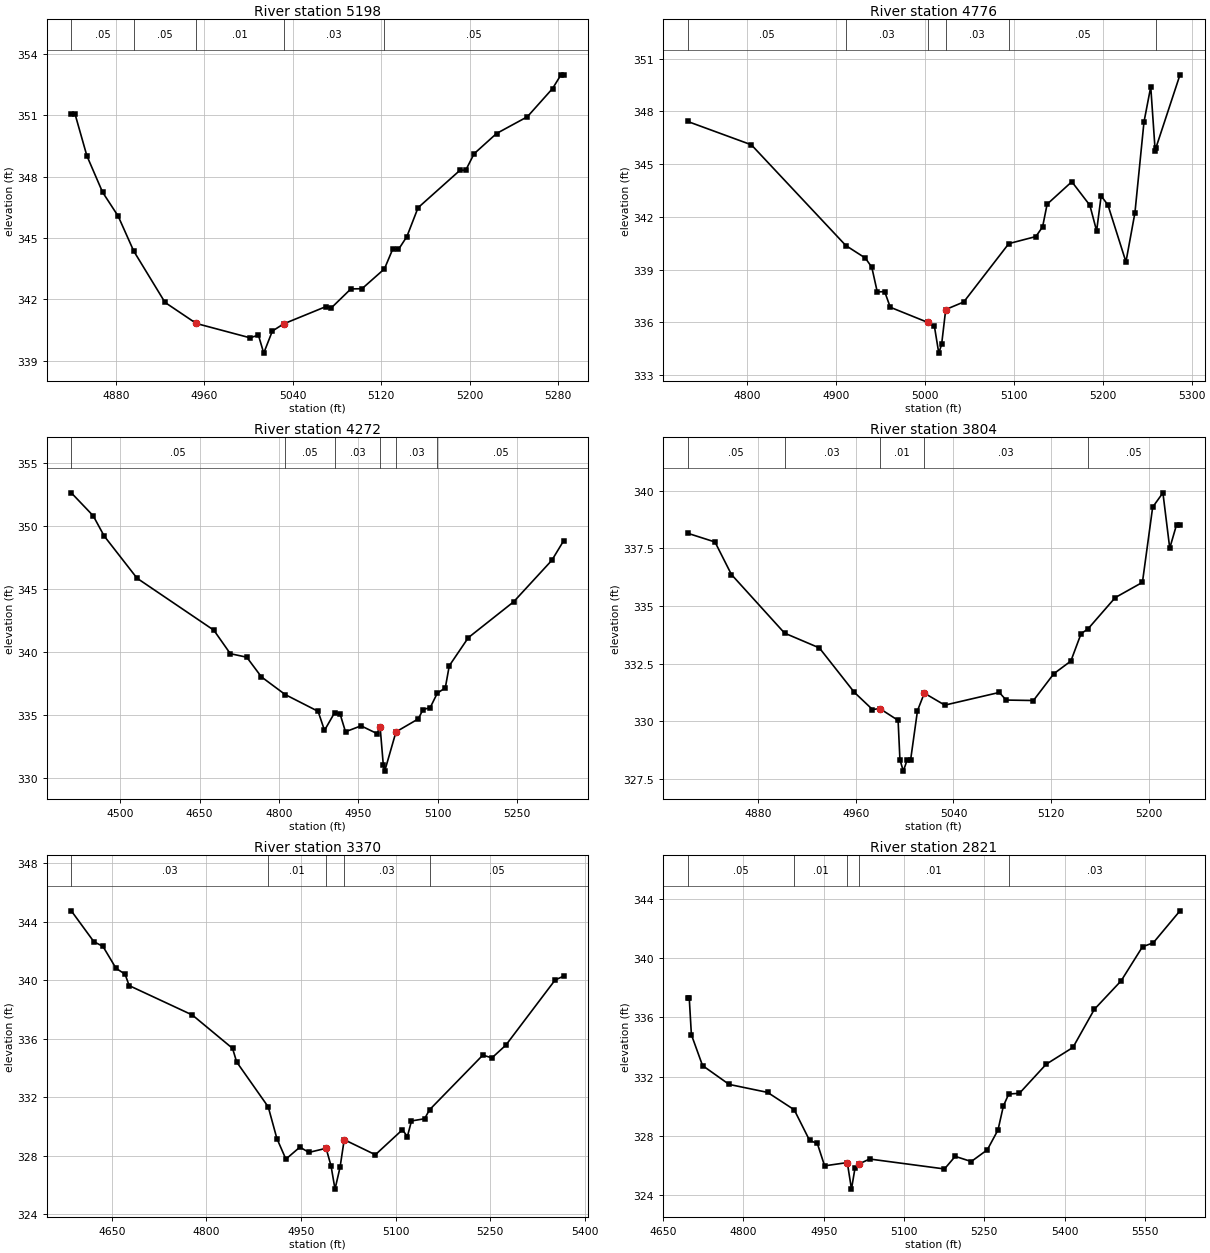
Type RM Length L Ch R = 1 ,5198    ,422,422,422
BEGIN DESCRIPTION:
UNT110 IN CCTC 7.0
END DESCRIPTION:
XS GIS Cut Line= 3
      3549449.59     10669060.17      3549349.61     10668960.19
      3549049.64     10668910.19
#Sta/Elev= 30
  4839.6  351.04  4843.1  351.04  4853.7  349.02  4867.9  347.24    4882  346.07
  4896.1  344.36  4924.4  341.85  4952.7  340.82  5001.3  340.12  5008.9  340.25
  5013.7  339.37  5021.5  340.45  5031.7   340.8  5069.7  341.64  5074.8  341.58
  5092.5  342.51  5102.6  342.52  5122.9  343.49  5130.5  344.47  5135.6  344.44
  5143.2  345.07  5153.3  346.48  5191.4  348.32  5196.4  348.31    5204  349.12
  5224.3  350.11  5252.2  350.93    5275  352.31  5282.6  352.98  5285.1  352.98
#Mann= 5 ,-1 , 0
  4839.6     .05       0  4896.1     .05       0  4952.7     .01       0
  5031.7     .03       0  5122.9     .05       0
Bank Sta=4952.7,5031.7
XS Rating Curve= 0 ,0
Exp/Cntr=0.3,0.1

Type RM Length L Ch R = 1 ,4776    ,504,504,504
BEGIN DESCRIPTION:
UNT110 IN CCTC 6.0
END DESCRIPTION:
XS GIS Cut Line= 3
      3549499.58     10668760.17      3549299.61     10668610.19
      3548999.61     10668560.19
#Sta/Elev= 30
  4732.8  347.43  4804.6   346.1  4910.9  340.37  4932.8  339.66  4940.1  339.14
  4946.3  337.73  4954.6  337.75  4960.9  336.86    5003     336  5010.6  335.77
  5015.5  334.25  5018.7  334.75  5023.3  336.73  5043.6  337.16  5094.3  340.48
  5124.7  340.88  5132.3  341.43  5137.4  342.72  5165.2     344  5185.5  342.66
  5193.1   341.2  5198.2  343.19  5205.8  342.68  5226.1  339.44  5236.2  342.23
  5246.4   347.4    5254   349.4    5259  345.75  5259.8  345.92  5286.9  350.08
#Mann= 6 ,-1 , 0
  4732.8     .05       0  4910.9     .03       0    5003     .01       0
  5023.3     .03       0  5094.3     .05       0  5259.8     .16       0
Bank Sta=5003,5023.3
XS Rating Curve= 0 ,0
Exp/Cntr=0.3,0.1

Type RM Length L Ch R = 1 ,4272    ,468,468,468
BEGIN DESCRIPTION:
UNT110 IN CCTC 5.0
END DESCRIPTION:
XS GIS Cut Line= 3
      3550049.56     10668360.18      3549499.61     10668210.19
       3549199.6     10668010.19
#Sta/Elev= 30
  4407.5  352.61  4448.9  350.79  4469.6  349.19  4531.8  345.84  4676.9  341.72
    4708  339.86  4739.1  339.58  4766.8  338.02  4811.7  336.62  4873.9  335.29
    4886  333.78    4905  335.17  4915.3   335.1  4925.7  333.67  4955.1  334.14
  4985.1  333.53  4991.1  334.06  4997.1  331.05  4999.8  330.55  5021.1  333.66
  5063.2  334.69  5072.2  335.43  5085.7  335.58  5099.2  336.73  5114.3  337.15
  5121.8   338.9  5157.8  341.13  5243.4  343.97  5315.6  347.26  5338.1  348.82
#Mann= 6 ,-1 , 0
  4407.5     .05       0  4811.7     .05       0    4905     .03       0
  4991.1     .01       0  5021.1     .03       0  5099.2     .05       0
Bank Sta=4991.1,5021.1
XS Rating Curve= 0 ,0
Exp/Cntr=0.3,0.1

Type RM Length L Ch R = 1 ,3804    ,434,434,434
BEGIN DESCRIPTION:
UNT110 IN CCTC 4.0
END DESCRIPTION:
XS GIS Cut Line= 3
      3549899.59     10667960.17      3549749.61     10667860.19
      3549549.57     10667760.17
#Sta/Elev= 30
  4821.9  338.15  4844.4  337.77  4857.9  336.36  4901.5  333.82    4930  333.18
  4958.6  331.26  4973.6  330.51  4979.6  330.55  4994.6  330.04  4996.1  328.34
  4998.9  327.84  5002.1  328.34  5004.9  328.34  5010.5  330.46  5016.1  331.22
  5032.9   330.7  5077.6  331.25  5083.2  330.92  5105.6   330.9  5122.3  332.06
  5136.3  332.61  5144.7   333.8  5150.3     334  5172.7  335.36    5195  336.02
  5203.4  339.28  5211.8   339.9  5217.4   337.5    5223  338.52  5225.8  338.52
#Mann= 5 ,-1 , 0
  4821.9     .05       0  4901.5     .03       0  4979.6     .01       0
  5016.1     .03       0  5150.3     .05       0
Bank Sta=4979.6,5016.1
XS Rating Curve= 0 ,0
Exp/Cntr=0.3,0.1

Type RM Length L Ch R = 1 ,3370    ,549,549,549
BEGIN DESCRIPTION:
UNT110 IN CCTC 3.0
END DESCRIPTION:
XS GIS Cut Line= 3
      3550199.63     10667810.22      3549949.61     10667510.19
      3549649.58     10667260.16
#Sta/Elev= 30
  4585.6  344.73  4621.4  342.62  4635.8   342.3  4656.6   340.8  4670.9   340.4
  4677.4  339.62  4777.6  337.61  4841.4  335.33  4847.9   334.4    4898  331.33
  4911.7  329.17    4926  327.76  4948.2  328.58  4962.5  328.22  4989.8   328.5
  4997.6   327.3  5003.9  325.71  5011.9   327.2  5018.5  329.09  5067.9  328.06
  5110.9  329.77  5118.7   329.3  5125.2  330.37    5146  330.52  5153.8  331.13
  5238.4  334.87  5252.8  334.68  5274.9  335.55    5353     340  5366.7  340.27
#Mann= 5 ,-1 , 0
  4585.6     .03       0    4898     .01       0  4989.8     .01       0
  5018.5     .03       0  5153.8     .05       0
Bank Sta=4989.8,5018.5
XS Rating Curve= 0 ,0
Exp/Cntr=0.3,0.1

Type RM Length L Ch R = 1 ,2821    ,436,436,436
BEGIN DESCRIPTION:
UNT110 IN CCTC 2.0
END DESCRIPTION:
XS GIS Cut Line= 3
      3550449.58     10667410.16      3550199.61     10667210.19
      3549599.62     10667210.19
#Sta/Elev= 30
  4695.6  337.29  4698.8  337.29  4702.8  334.82  4723.6  332.74  4773.2  331.47
  4845.2  330.93  4894.9  329.76  4923.7  327.69  4938.1  327.49  4951.7  325.98
  4994.1   326.2  5001.9  324.41  5008.5  325.83  5015.7   326.1  5035.7  326.44
  5175.7  325.77  5195.7  326.62  5225.7  326.27  5255.7  327.06  5275.7   328.4
  5285.7  330.01  5295.7  330.82  5315.7  330.87  5365.7  332.83  5415.7  333.96
  5455.7  336.53  5505.7  338.45  5545.7  340.75  5565.7  341.01  5615.7  343.17
#Mann= 5 ,-1 , 0
  4695.6     .05       0  4894.9     .01       0  4994.1     .01       0
  5015.7     .01       0  5295.7     .03       0
Bank Sta=4994.1,5015.7
XS Rating Curve= 0 ,0
Exp/Cntr=0.3,0.1

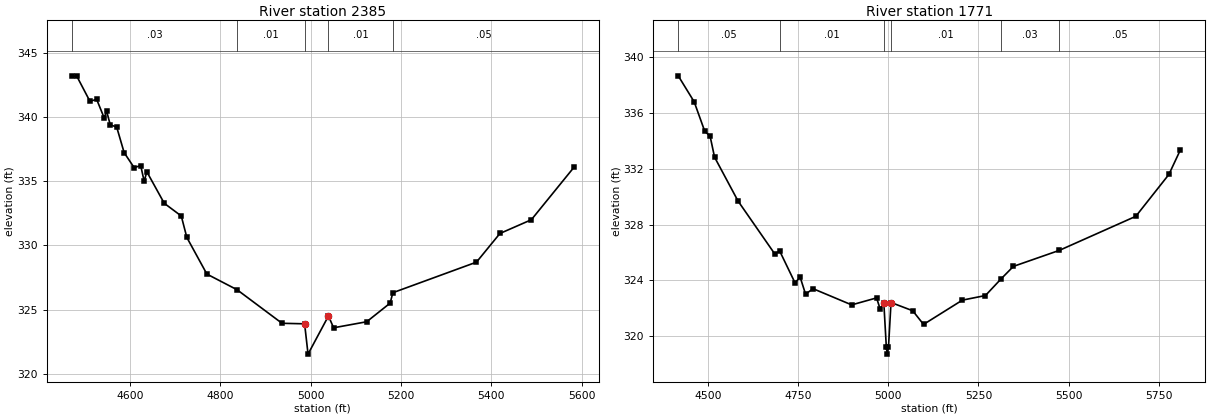
Type RM Length L Ch R = 1 ,2385    ,614,614,614
BEGIN DESCRIPTION:
Mapping XS bbd30dd0
END DESCRIPTION:
XS GIS Cut Line= 3
      3550825.39      10667089.4      3550308.85     10666824.62
      3549823.65     10667041.23
#Sta/Elev= 30
    4471  343.14  4481.7  343.19  4511.2  341.21  4526.1  341.36  4542.6  339.93
  4548.3  340.42  4556.2  339.38  4570.5   339.2    4587  337.21  4609.2  336.04
  4623.6  336.21  4631.4  334.97  4637.1  335.73  4675.8  333.27  4713.5  332.28
  4725.8  330.61  4770.2  327.76  4837.1  326.54  4936.6  323.93  4986.6  323.89
  4994.2  321.53  5039.4   324.5  5050.8  323.58  5124.1  324.05    5176   325.5
    5182  326.31  5367.2  328.69  5419.1  330.92  5488.7  331.99  5582.8  336.06
#Mann= 5 ,-1 , 0
    4471     .03       0  4837.1     .01       0  4986.6     .01       0
  5039.4     .01       0    5182     .05       0
Bank Sta=4986.6,5039.4
XS Rating Curve= 0 ,0
Exp/Cntr=0.3,0.1

Type RM Length L Ch R = 1 ,1771    ,0,0,0
BEGIN DESCRIPTION:
UNT110 IN CCTC 1.0
END DESCRIPTION:
XS GIS Cut Line= 4
       3550799.3     10666872.36      3550499.83     10666447.02
      3550287.15     10666429.66      3549840.37     10666915.47
#Sta/Elev= 30
  4416.6  338.66  4460.8   336.8  4490.4  334.67  4504.9  334.35  4517.4  332.83
  4582.7  329.68  4683.8  325.92  4698.6  326.08  4740.4  323.84  4755.2  324.21
    4770  323.01  4790.9   323.4    4898  322.24  4967.1  322.74  4977.1  321.94
  4987.2   322.4  4994.2  319.21    4997  318.71  5000.2  319.21  5007.2  322.41
  5067.4  321.82  5097.5  320.84  5205.2  322.58  5269.3  322.91  5311.8  324.08
  5346.9     325  5474.6  326.15  5686.7  328.59  5778.5  331.59  5810.2  333.34
#Mann= 6 ,-1 , 0
  4416.6     .05       0  4698.6     .01       0  4987.2     .01       0
  5007.2     .01       0  5311.8     .03       0  5474.6     .05       0
Bank Sta=4987.2,5007.2
XS Rating Curve= 0 ,0
Exp/Cntr=0.3,0.1

Chan Stop Cuts=-1
Use User Specified Reach Order=0
Composite Channel Slope=5