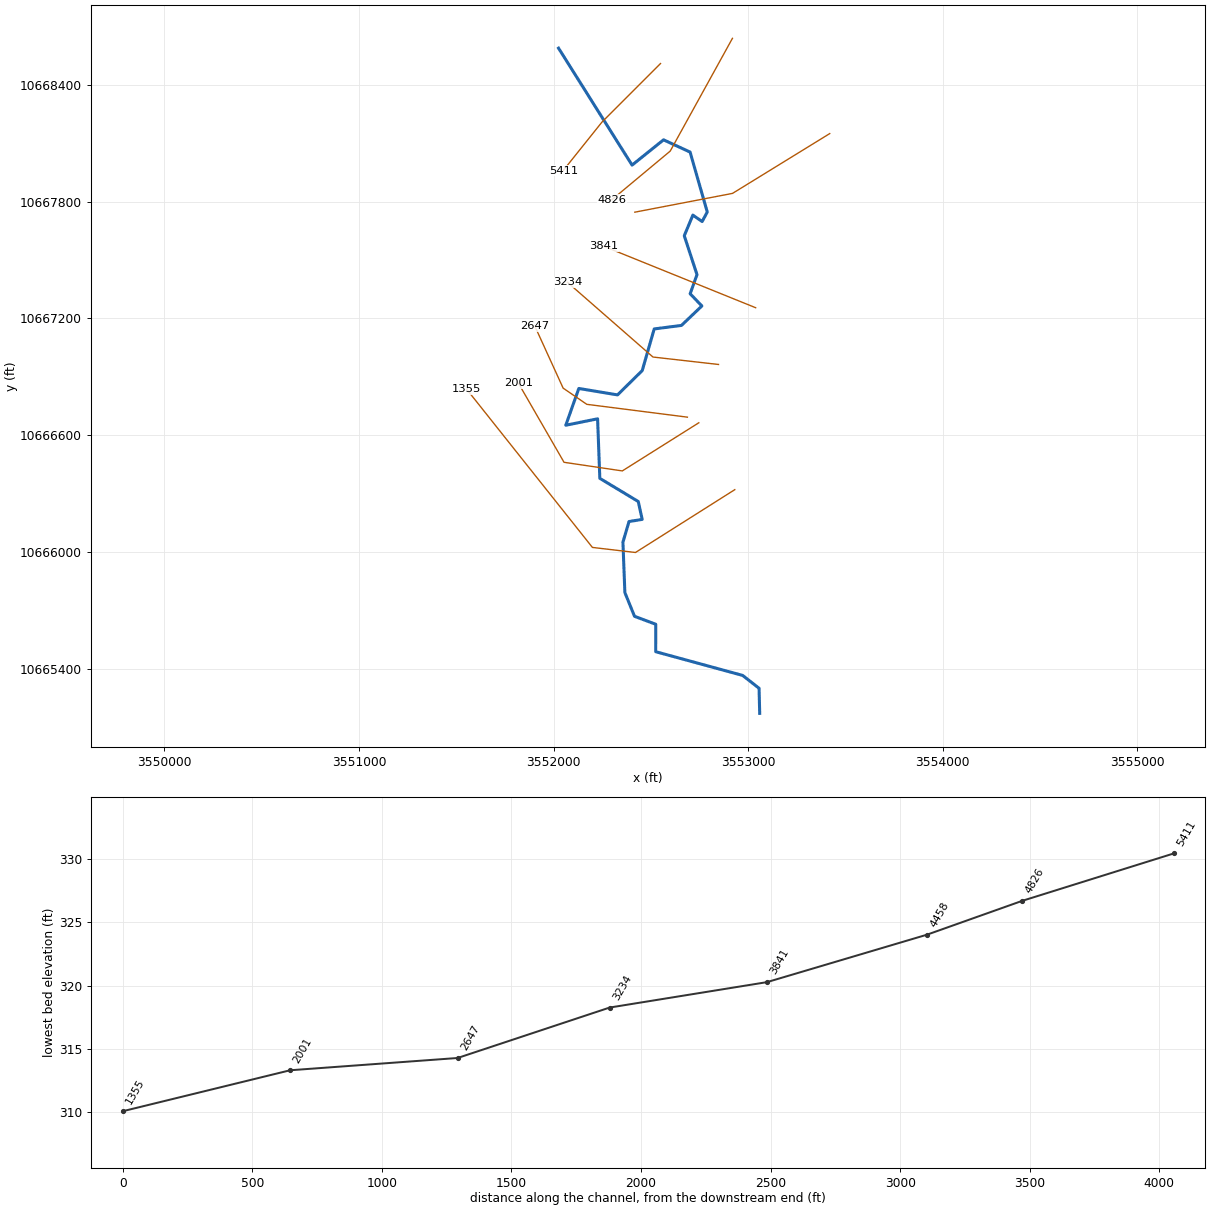
--- UNT112 IN CCTC.prj (project) ---

Proj Title=UNT112 IN CCTC Base Level Engineering
Current Plan=p01
Default Exp/Contr=0.3,0.1
English Units
Geom File=g01
Flow File=f01
Plan File=p01
BEGIN DESCRIPTION:
UNT112 IN CCTC
END DESCRIPTION:

--- UNT112 IN CCTC.p01 (plan) ---

Plan Title=Multiple Run
Short Identifier=Multiple
Geom File=g01
Flow File=f01
Subcritical Flow
K Sum by GR= 0
Std Step Tol= 0.01
Critical Tol= 0.01
Num of Std Step Trials= 20
Max Error Tol= 0.3
Flow Tol Ratio= 0.001
Split Flow NTrial= 30
Split Flow Tol= 0.02
Split Flow Ratio= 0.02
Log Output Level= 0
Friction Slope Method= 1
Unsteady Friction Slope Method= 2
Unsteady Bridges Friction Slope Method= 1
Parabolic Critical Depth
Global Vel Dist=  1 , 1 , 1
Global Log Level= 0
CheckData=True
Encroach Param= -1, 0, 0, 0
BEGIN DESCRIPTION:
Multiple Run
END DESCRIPTION:

--- UNT112 IN CCTC.f01 (steady flow) ---

Flow Title=Multiple
Number of Profiles=7
Profile Names=10-year,25-year,50-year,1pct_min,100-year,1pct_plu,500-year
River Rch & RM= UNT112 IN CCTC,Reach-1,5411
    1275    1745    2131    1899    2568    3473    3719
Boundary for River Rch & Prof#=UNT112 IN CCTC,Reach-1,1
Up Type=0
Dn Type=3
Dn Slope=0.005
Boundary for River Rch & Prof#=UNT112 IN CCTC,Reach-1,2
Up Type=0
Dn Type=3
Dn Slope=0.005
Boundary for River Rch & Prof#=UNT112 IN CCTC,Reach-1,3
Up Type=0
Dn Type=3
Dn Slope=0.005
Boundary for River Rch & Prof#=UNT112 IN CCTC,Reach-1,4
Up Type=0
Dn Type=3
Dn Slope=0.005
Boundary for River Rch & Prof#=UNT112 IN CCTC,Reach-1,5
Up Type=0
Dn Type=3
Dn Slope=0.005
Boundary for River Rch & Prof#=UNT112 IN CCTC,Reach-1,6
Up Type=0
Dn Type=3
Dn Slope=0.005
Boundary for River Rch & Prof#=UNT112 IN CCTC,Reach-1,7
Up Type=0
Dn Type=3
Dn Slope=0.005

--- UNT112 IN CCTC.g01 (geometry) ---

Geom Title=Existing Conditions

River Reach=UNT112 IN CCTC,Reach-1
Reach XY= 30
      3552025.53     10668589.12      3552403.50     10667988.00
      3552565.25     10668118.00      3552701.75     10668055.00
      3552790.00     10667747.00      3552763.75     10667698.00
      3552716.00     10667731.00      3552671.75     10667625.00
      3552737.25     10667425.00      3552702.00     10667327.00
      3552762.25     10667264.00      3552657.25     10667164.00
      3552517.25     10667146.00      3552455.75     10666932.00
      3552328.75     10666807.00      3552129.75     10666840.00
      3552062.75     10666651.00      3552226.25     10666684.00
      3552237.75     10666378.00      3552435.25     10666259.00
      3552455.50     10666167.00      3552387.75     10666156.00
      3552356.50     10666050.00      3552366.50     10665791.00
      3552416.00     10665669.00      3552525.25     10665628.00
      3552525.00     10665487.00      3552972.00     10665365.00
      3553056.25     10665299.00      3553059.50     10665170.00

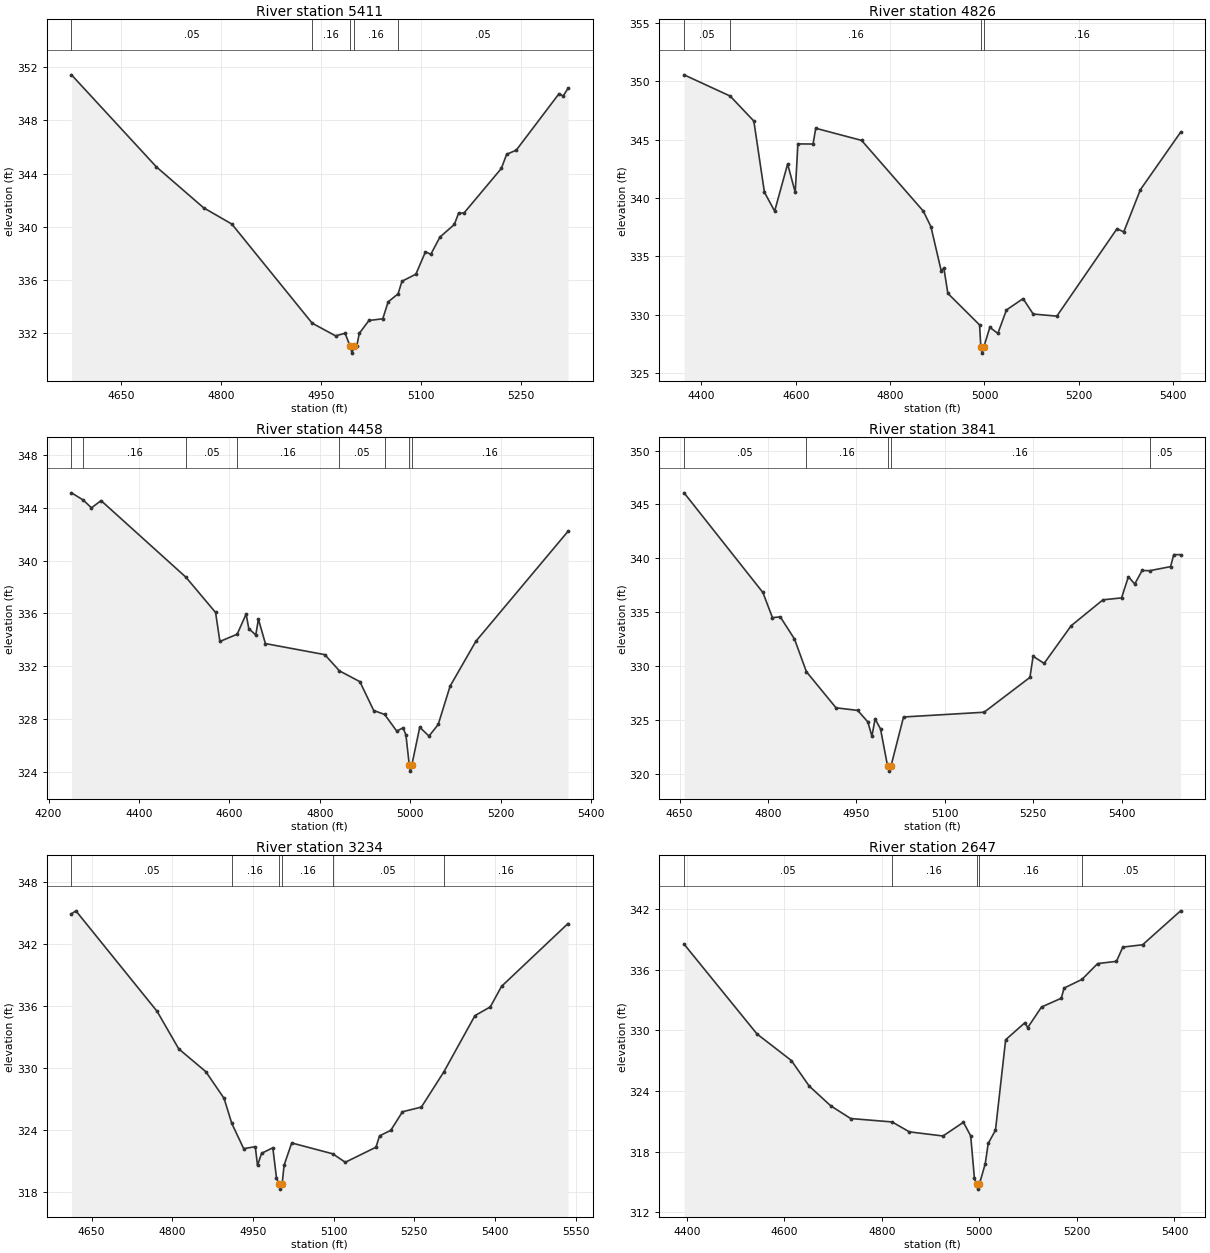
Type RM Length L Ch R = 1,5411,585,585,585
BEGIN DESCRIPTION:
UNT112 IN CCTC 7.0
END DESCRIPTION:
XS GIS Cut Line= 3
      3552549.63     10668510.21      3552249.61     10668210.19
      3552049.64     10667960.23
#Sta/Elev= 30
  4575.8  351.44  4703.1  344.50  4773.8  341.42  4816.2  340.19  4936.6  332.72
  4971.8  331.76  4986.0  331.96  4993.6  330.96  4996.3  330.46  4999.6  330.96
  5003.3  330.96  5007.3  331.95  5021.7  332.92  5042.5  333.05  5050.5  334.32
  5065.4  334.93  5071.3  335.88  5092.1  336.41  5106.5  338.10  5114.5  337.91
  5128.2  339.21  5149.8  340.16  5156.2  341.02  5164.2  341.02  5220.2  344.38
  5228.2  345.45  5242.6  345.76  5306.6  350.01  5313.0  349.85  5320.2  350.42
#Mann=5,-1,0
  4575.8    0.05       0  4936.6    0.16       0  4993.6    0.07       0
  4999.6    0.16       0  5065.4    0.05       0
Bank Sta=4993.6,4999.6
Exp/Cntr=0.3,0.1

Type RM Length L Ch R = 1,4826,368,368,368
BEGIN DESCRIPTION:
UNT112 IN CCTC 6.0
END DESCRIPTION:
XS GIS Cut Line= 3
      3552919.41     10668639.66      3552599.61     10668060.19
      3552299.59     10667810.17
#Sta/Elev= 30
  4363.3  350.56  4461.0  348.74  4511.2  346.60  4533.6  340.50  4555.3  338.88
  4582.8  342.92  4598.9  340.49  4604.6  344.64  4636.7  344.63  4642.4  345.98
  4739.6  344.94  4870.4  338.88  4886.5  337.55  4908.3  333.77  4914.0  333.99
  4922.4  331.83  4989.6  329.13  4992.4  327.21  4995.1  326.71  4998.4  327.21
  5011.4  328.92  5028.4  328.40  5046.6  330.41  5081.8  331.38  5103.3  330.06
  5153.4  329.88  5280.9  337.37  5295.3  337.10  5330.4  340.71  5415.7  345.64
#Mann=4,-1,0
  4363.3    0.05       0  4461.0    0.16       0  4992.4    0.07       0
  4998.4    0.16       0
Bank Sta=4992.4,4998.4
Exp/Cntr=0.3,0.1

Type RM Length L Ch R = 1,4458,617,617,617
BEGIN DESCRIPTION:
UNT112 IN CCTC 5.0
END DESCRIPTION:
XS GIS Cut Line= 3
      3553419.37     10668150.03      3552919.74     10667842.68
      3552417.74     10667746.14
#Sta/Elev= 30
  4250.7  345.15  4276.8  344.60  4294.8  344.01  4316.1  344.56  4503.6  338.75
  4569.3  336.07  4578.8  333.87  4617.0  334.42  4636.8  335.95  4642.7  334.85
  4658.1  334.36  4664.0  335.56  4679.4  333.71  4810.8  332.87  4843.1  331.64
  4888.3  330.82  4918.9  328.63  4943.1  328.33  4969.8  327.07  4984.0  327.32
  4990.2  326.76  4997.4  324.53  5000.1  324.03  5003.4  324.53  5020.7  327.36
  5041.1  326.69  5061.5  327.57  5087.8  330.48  5144.9  333.89  5348.5  342.23
#Mann=8,-1,0
  4250.7    0.05       0  4276.8    0.16       0  4503.6    0.05       0
  4617.0    0.16       0  4843.1    0.05       0  4943.1    0.16       0
  4997.4    0.07       0  5003.4    0.16       0
Bank Sta=4997.4,5003.4
Exp/Cntr=0.3,0.1

Type RM Length L Ch R = 1,3841,607,607,607
BEGIN DESCRIPTION:
UNT112 IN CCTC 4.0
END DESCRIPTION:
XS GIS Cut Line= 2
      3553038.68     10667255.05      3552257.46     10667571.01
#Sta/Elev= 30
  4657.5  346.08  4791.3  336.84  4807.5  334.51  4820.8  334.58  4844.9  332.53
  4865.1  329.50  4915.4  326.15  4952.2  325.91  4969.3  324.85  4976.3  323.52
  4981.7  325.12  4990.9  324.20  5002.8  320.78  5005.6  320.28  5008.8  320.78
  5030.0  325.30  5166.7  325.74  5244.5  328.97  5249.9  330.93  5268.6  330.27
  5314.5  333.76  5368.4  336.16  5400.0  336.34  5411.6  338.30  5422.4  337.63
  5434.9  338.88  5447.6  338.86  5483.2  339.24  5488.6  340.35  5500.2  340.35
#Mann=5,-1,0
  4657.5    0.05       0  4865.1    0.16       0  5002.8    0.07       0
  5008.8    0.16       0  5447.6    0.05       0
Bank Sta=5002.8,5008.8
Exp/Cntr=0.3,0.1

Type RM Length L Ch R = 1,3234,587,587,587
BEGIN DESCRIPTION:
UNT112 IN CCTC 3.0
END DESCRIPTION:
XS GIS Cut Line= 3
      3552847.77     10666963.37      3552510.92     10667001.57
      3552070.98     10667386.08
#Sta/Elev= 30
  4612.6  344.92  4620.8  345.21  4771.8  335.48  4812.0  331.85  4862.4  329.64
  4896.3  327.06  4910.7  324.63  4932.8  322.19  4954.4  322.38  4958.5  320.56
  4966.1  321.74  4987.0  322.27  4993.7  319.39  4998.3  318.77  5001.0  318.27
  5004.3  318.77  5007.9  320.58  5022.1  322.74  5098.3  321.69  5121.8  320.87
  5178.8  322.33  5185.4  323.43  5206.3  323.96  5228.1  325.76  5263.2  326.21
  5305.0  329.62  5362.9  335.07  5391.4  335.91  5412.3  337.90  5535.9  343.98
#Mann=6,-1,0
  4612.6    0.05       0  4910.7    0.16       0  4998.3    0.07       0
  5004.3    0.16       0  5098.3    0.05       0  5305.0    0.16       0
Bank Sta=4998.3,5004.3
Exp/Cntr=0.3,0.1

Type RM Length L Ch R = 1,2647,646,646,646
BEGIN DESCRIPTION:
UNT112 IN CCTC 2.0
END DESCRIPTION:
XS GIS Cut Line= 4
      3552687.97     10666692.55      3552170.64     10666758.52
      3552049.11     10666841.85      3551903.96     10667159.81
#Sta/Elev= 30
  4394.2  338.53  4543.8  329.64  4614.3  327.01  4650.9  324.48  4695.0  322.53
  4735.8  321.27  4821.0  320.93  4856.3  319.95  4925.3  319.54  4967.2  320.90
  4982.1  319.55  4989.7  315.38  4994.0  314.78  4996.8  314.28  5000.0  314.78
  5011.9  316.79  5018.0  318.80  5032.9  320.11  5053.8  329.07  5093.4  330.76
  5098.9  330.26  5127.4  332.31  5168.0  333.18  5173.5  334.18  5210.3  335.04
  5242.5  336.61  5281.1  336.83  5294.1  338.24  5334.7  338.47  5412.6  341.83
#Mann=5,-1,0
  4394.2    0.05       0  4821.0    0.16       0  4994.0    0.07       0
  5000.0    0.16       0  5210.3    0.05       0
Bank Sta=4994,5000
Exp/Cntr=0.3,0.1

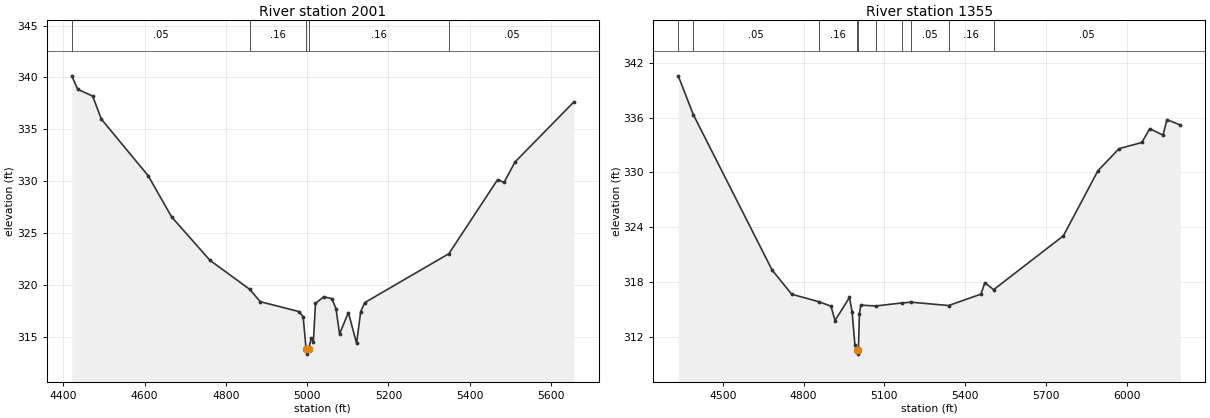
Type RM Length L Ch R = 1,2001,646,646,646
BEGIN DESCRIPTION:
Mapping XS c14cfc17
END DESCRIPTION:
XS GIS Cut Line= 4
      3552746.52     10666663.62      3552353.31     10666416.23
      3552053.83     10666460.50      3551819.90     10666865.97
#Sta/Elev= 30
  4420.8  340.15  4435.7  338.84  4472.2  338.20  4493.5  335.98  4608.9  330.51
  4666.6  326.54  4760.8  322.36  4858.6  319.56  4884.6  318.37  4980.1  317.41
  4990.2  316.91  4997.3  313.81  5000.0  313.31  5003.3  313.81  5010.2  314.85
  5015.2  314.47  5020.5  318.21  5040.7  318.84  5060.9  318.66  5071.1  317.67
  5079.7  315.25  5101.4  317.32  5121.6  314.35  5131.7  317.41  5141.8  318.28
  5348.8  323.00  5468.6  330.14  5484.4  329.87  5511.7  331.85  5656.2  337.63
#Mann=5,-1,0
  4420.8    0.05       0  4858.6    0.16       0  4997.3    0.07       0
  5003.3    0.16       0  5348.8    0.05       0
Bank Sta=4997.3,5003.3
Exp/Cntr=0.3,0.1

Type RM Length L Ch R = 1,1355,0,0,0
BEGIN DESCRIPTION:
UNT112 IN CCTC 1.0
END DESCRIPTION:
XS GIS Cut Line= 4
      3552931.47     10666319.90      3552421.02     10665996.96
      3552199.66     10666023.00      3551554.34     10666834.86
#Sta/Elev= 30
  4334.6  340.60  4390.8  336.33  4683.0  319.30  4755.9  316.64  4856.9  315.82
  4901.7  315.33  4916.6  313.75  4970.3  316.29  4980.3  314.66  4990.4  311.12
  4997.5  310.57  5000.2  310.07  5003.5  310.57  5007.3  314.51  5012.3  315.45
  5067.0  315.35  5164.2  315.68  5199.2  315.77  5338.2  315.40  5458.5  316.65
  5472.9  317.91  5505.5  317.14  5764.5  323.05  5892.6  330.18  5971.1  332.61
  6056.0  333.29  6084.9  334.80  6134.5  334.10  6148.9  335.79  6198.6  335.21
#Mann=10,-1,0
  4334.6    0.16       0  4390.8    0.05       0  4856.9    0.16       0
  4997.5    0.07       0  5003.5    0.16       0  5067.0    0.05       0
  5164.2    0.12       0  5199.2    0.05       0  5338.2    0.16       0
  5505.5    0.05       0
Bank Sta=4997.5,5003.5
Exp/Cntr=0.3,0.1

Chan Stop Cuts=-1