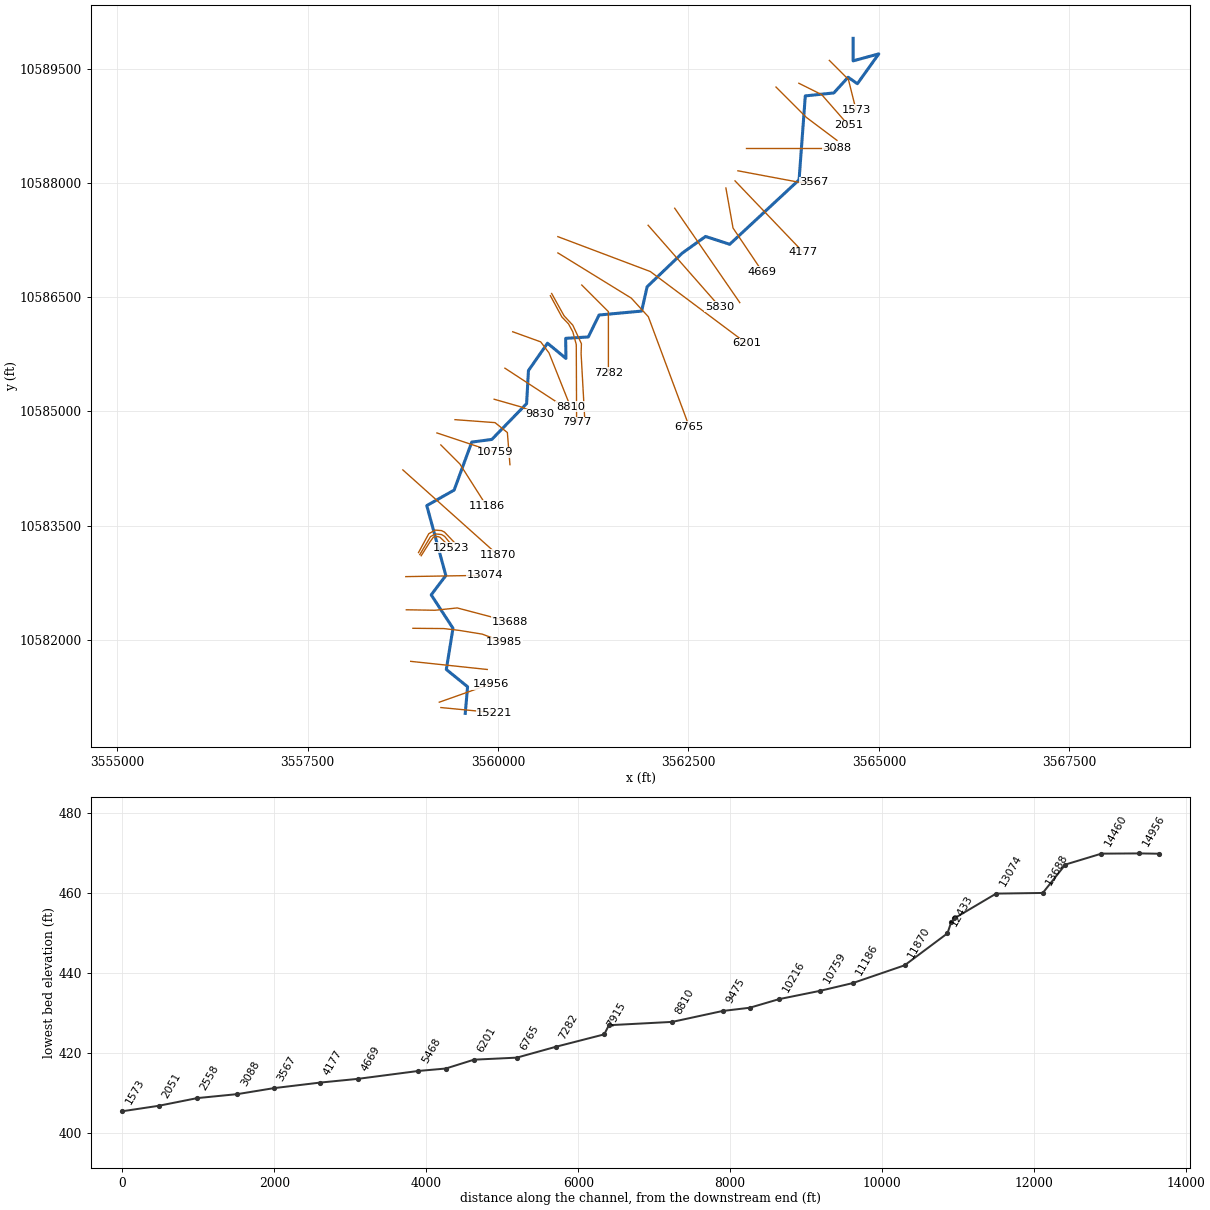
--- UNT117 IN CCTC.prj (project) ---

Proj Title=UNT117 IN CCTC Base Level Engineering
Current Plan=p01
Default Exp/Contr=0.3,0.1
English Units
Geom File=g01
Flow File=f01
Plan File=p01
BEGIN DESCRIPTION:
UNT117 IN CCTC
END DESCRIPTION:

--- UNT117 IN CCTC.p01 (plan) ---

Plan Title=Multiple Run
Short Identifier=Multiple
Geom File=g01
Flow File=f01
Subcritical Flow
K Sum by GR= 0
Std Step Tol= 0.01
Critical Tol= 0.01
Num of Std Step Trials= 20
Max Error Tol= 0.3
Flow Tol Ratio= 0.001
Split Flow NTrial= 30
Split Flow Tol= 0.02
Split Flow Ratio= 0.02
Log Output Level= 0
Friction Slope Method= 1
Unsteady Friction Slope Method= 2
Unsteady Bridges Friction Slope Method= 1
Parabolic Critical Depth
Global Vel Dist=  1 , 1 , 1
Global Log Level= 0
CheckData=True
Encroach Param= -1, 0, 0, 0
BEGIN DESCRIPTION:
Multiple Run
END DESCRIPTION:

--- UNT117 IN CCTC.f01 (steady flow) ---

Flow Title=Multiple
Number of Profiles=7
Profile Names=10-year,25-year,50-year,1pct_min,100-year,1pct_plu,500-year
River Rch & RM= UNT117 IN CCTC,Reach-1,15221
    1268    1735    2118    1887    2552    3452    3695
River Rch & RM= UNT117 IN CCTC,Reach-1,9830
    2054    2885    3585    3246    4390    5937    6566
River Rch & RM= UNT117 IN CCTC,Reach-1,5830
    2304    3240    4028    3646    4931    6669    7371
Boundary for River Rch & Prof#=UNT117 IN CCTC,Reach-1,1
Up Type=0
Dn Type=3
Dn Slope=0.005
Boundary for River Rch & Prof#=UNT117 IN CCTC,Reach-1,2
Up Type=0
Dn Type=3
Dn Slope=0.005
Boundary for River Rch & Prof#=UNT117 IN CCTC,Reach-1,3
Up Type=0
Dn Type=3
Dn Slope=0.005
Boundary for River Rch & Prof#=UNT117 IN CCTC,Reach-1,4
Up Type=0
Dn Type=3
Dn Slope=0.005
Boundary for River Rch & Prof#=UNT117 IN CCTC,Reach-1,5
Up Type=0
Dn Type=3
Dn Slope=0.005
Boundary for River Rch & Prof#=UNT117 IN CCTC,Reach-1,6
Up Type=0
Dn Type=3
Dn Slope=0.005
Boundary for River Rch & Prof#=UNT117 IN CCTC,Reach-1,7
Up Type=0
Dn Type=3
Dn Slope=0.005

--- UNT117 IN CCTC.g01 (geometry) ---

Geom Title=Existing Conditions

River Reach=UNT117 IN CCTC,Reach-1
Reach XY= 30
      3559570.65     10581034.28      3559601.00     10581384.00
      3559322.00     10581611.00      3559409.50     10582152.00
      3559123.50     10582591.00      3559316.00     10582845.00
      3559065.50     10583763.00      3559424.75     10583967.00
      3559655.75     10584597.00      3559919.00     10584632.00
      3560375.75     10585102.00      3560400.25     10585537.00
      3560650.25     10585896.00      3560892.25     10585696.00
      3560888.25     10585960.00      3561185.75     10585978.00
      3561326.75     10586266.00      3561885.75     10586318.00
      3561957.50     10586637.00      3562419.75     10587080.00
      3562725.00     10587298.00      3563041.75     10587195.00
      3563952.25     10588042.00      3564034.00     10589144.00
      3564408.50     10589183.00      3564595.50     10589389.00
      3564717.50     10589304.00      3564998.75     10589696.00
      3564661.50     10589604.00      3564662.00     10589900.00

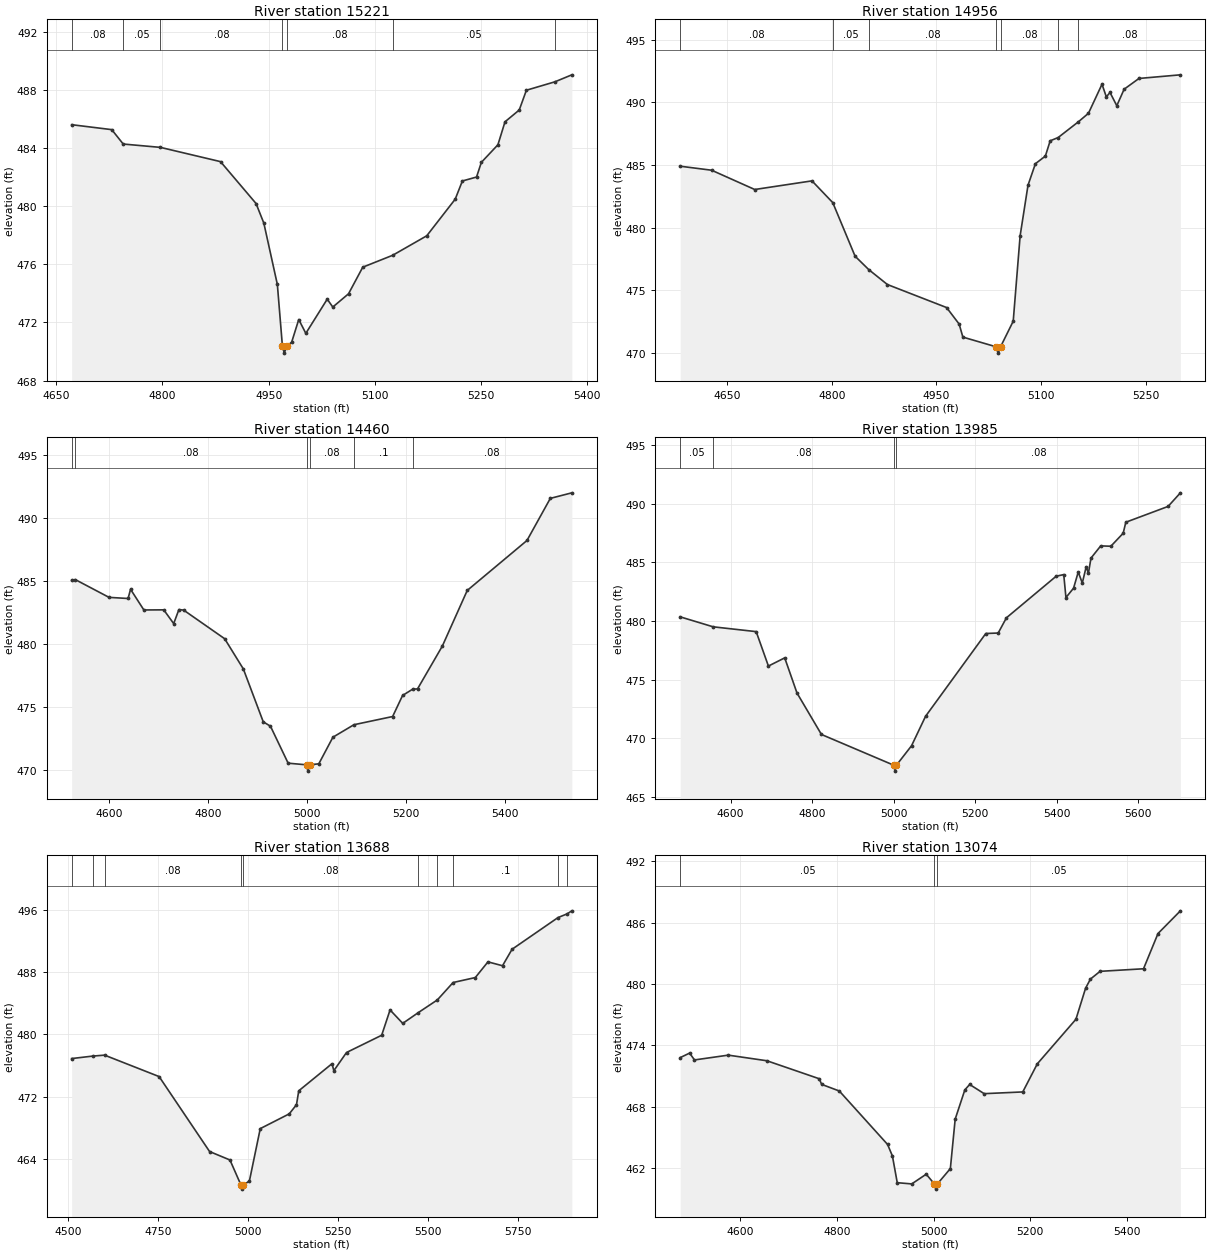
Type RM Length L Ch R = 1,15221,265,265,265
BEGIN DESCRIPTION:
UNT117 IN CCTC 29.0
END DESCRIPTION:
XS GIS Cut Line= 2
      3559250.40     10581110.81      3559953.55     10581043.10
#Sta/Elev= 30
  4671.8  485.60  4728.4  485.26  4744.6  484.27  4797.2  484.04  4882.0  483.06
  4932.2  480.18  4943.2  478.83  4962.3  474.61  4969.4  470.39  4972.1  469.89
  4975.4  470.39  4982.4  470.63  4992.5  472.20  5002.5  471.25  5032.7  473.60
  5040.6  473.06  5062.8  473.97  5082.9  475.80  5125.2  476.62  5173.3  477.96
  5213.5  480.48  5223.6  481.73  5243.6  482.00  5250.4  483.01  5273.8  484.22
  5283.8  485.80  5303.9  486.61  5314.0  487.97  5354.3  488.55  5378.2  489.03
#Mann=7,-1,0
  4671.8    0.08       0  4744.6    0.05       0  4797.2    0.08       0
  4969.4    0.07       0  4975.4    0.08       0  5125.2    0.05       0
  5354.3    0.08       0
Bank Sta=4969.4,4975.4
Exp/Cntr=0.3,0.1

Type RM Length L Ch R = 1,14956,496,496,496
BEGIN DESCRIPTION:
Mapping XS d02b4cef
END DESCRIPTION:
XS GIS Cut Line= 2
      3559229.57     10581181.13      3559905.60     10581420.34
#Sta/Elev= 30
  4582.8  484.90  4627.8  484.58  4689.6  483.04  4771.7  483.73  4801.5  481.99
  4833.5  477.71  4853.1  476.64  4879.8  475.45  4964.7  473.61  4982.7  472.29
  4988.0  471.25  5036.0  470.47  5038.7  469.97  5042.0  470.47  5060.2  472.52
  5070.1  479.34  5081.4  483.38  5092.0  485.10  5106.3  485.71  5113.2  486.93
  5124.6  487.19  5153.7  488.45  5168.1  489.13  5187.5  491.45  5193.7  490.44
  5199.0  490.79  5208.7  489.73  5219.2  491.05  5240.5  491.91  5299.9  492.20
#Mann=7,-1,0
  4582.8    0.08       0  4801.5    0.05       0  4853.1    0.08       0
  5036.0    0.07       0  5042.0    0.08       0  5124.6    0.05       0
  5153.7    0.08       0
Bank Sta=5036,5042
Exp/Cntr=0.3,0.1

Type RM Length L Ch R = 1,14460,475,475,475
BEGIN DESCRIPTION:
UNT117 IN CCTC 28.0
END DESCRIPTION:
XS GIS Cut Line= 2
      3558854.56     10581717.58      3559859.81     10581610.81
#Sta/Elev= 30
  4523.6  485.03  4530.9  485.10  4599.1  483.69  4637.6  483.60  4642.6  484.33
  4669.5  482.69  4709.7  482.70  4729.8  481.61  4740.3  482.72  4749.9  482.68
  4832.8  480.41  4870.6  478.01  4910.8  473.82  4925.4  473.47  4961.1  470.54
  4998.3  470.41  5001.1  469.91  5004.3  470.41  5023.1  470.49  5051.6  472.60
  5094.1  473.59  5172.3  474.24  5192.4  475.91  5212.8  476.41  5222.6  476.43
  5272.8  479.83  5323.1  484.24  5443.8  488.20  5491.0  491.54  5534.5  491.98
#Mann=6,-1,0
  4523.6     0.1       0  4530.9    0.08       0  4998.3    0.07       0
  5004.3    0.08       0  5094.1     0.1       0  5212.8    0.08       0
Bank Sta=4998.3,5004.3
Exp/Cntr=0.3,0.1

Type RM Length L Ch R = 1,13985,297,297,297
BEGIN DESCRIPTION:
UNT117 IN CCTC 27.0
END DESCRIPTION:
XS GIS Cut Line= 5
      3558883.27     10582151.59      3559289.48     10582148.12
      3559494.34     10582123.81      3559792.95     10582075.20
      3560084.88     10581965.30
#Sta/Elev= 30
  4476.7  480.35  4557.5  479.50  4663.0  479.09  4693.0  476.15  4733.0  476.85
  4763.1  473.85  4823.1  470.31  5000.9  467.68  5003.6  467.18  5006.9  467.68
  5044.2  469.35  5078.5  471.86  5226.3  478.93  5256.7  478.97  5276.9  480.27
  5398.9  483.82  5417.5  483.96  5422.9  482.00  5441.6  482.80  5453.1  484.18
  5463.0  483.24  5472.6  484.63  5478.0  484.08  5484.4  485.37  5508.2  486.41
  5533.1  486.38  5563.3  487.49  5569.8  488.43  5673.5  489.78  5703.7  490.94
#Mann=4,-1,0
  4476.7    0.05       0  4557.5    0.08       0  5000.9    0.07       0
  5006.9    0.08       0
Bank Sta=5000.9,5006.9
Exp/Cntr=0.3,0.1

Type RM Length L Ch R = 1,13688,614,614,614
BEGIN DESCRIPTION:
UNT117 IN CCTC 26.0
END DESCRIPTION:
XS GIS Cut Line= 4
      3558796.84     10582394.84      3559174.46     10582388.57
      3559464.81     10582419.15      3560160.16     10582235.98
#Sta/Elev= 30
  4510.8  476.90  4569.5  477.22  4602.2  477.34  4753.6  474.58  4893.7  464.93
  4950.3  463.84  4981.1  460.59  4983.9  460.09  4987.1  460.59  5004.3  461.15
  5034.4  467.88  5114.9  469.78  5135.0  470.96  5141.3  472.75  5233.6  476.24
  5238.7  475.34  5273.9  477.68  5371.5  479.90  5394.8  483.16  5430.0  481.43
  5473.0  482.81  5526.1  484.45  5569.8  486.69  5631.5  487.33  5666.6  489.35
  5707.0  488.85  5733.5  490.97  5861.0  495.05  5886.4  495.53  5899.5  495.92
#Mann=10,-1,0
  4510.8    0.08       0  4569.5    0.05       0  4602.2    0.08       0
  4981.1    0.07       0  4987.1    0.08       0  5473.0    0.05       0
  5526.1    0.08       0  5569.8     0.1       0  5861.0    0.08       0
  5886.4    0.15       0
Bank Sta=4981.1,4987.1
Exp/Cntr=0.3,0.1

Type RM Length L Ch R = 1,13074,551,551,551
BEGIN DESCRIPTION:
UNT117 IN CCTC 25.0
END DESCRIPTION:
XS GIS Cut Line= 2
      3558790.16     10582830.31      3559826.02     10582847.65
#Sta/Elev= 30
  4475.3  472.80  4494.7  473.24  4504.8  472.57  4574.8  473.04  4654.8  472.49
  4763.2  470.73  4768.2  470.18  4804.8  469.53  4904.8  464.30  4914.8  463.17
  4924.8  460.56  4954.8  460.44  4984.8  461.39  5001.8  460.43  5004.6  459.93
  5007.8  460.43  5034.8  461.94  5044.8  466.78  5064.8  469.64  5074.8  470.17
  5104.8  469.27  5184.8  469.44  5214.9  472.19  5294.9  476.55  5314.9  479.59
  5324.9  480.48  5344.9  481.24  5434.9  481.49  5464.9  484.94  5511.3  487.16
#Mann=3,-1,0
  4475.3    0.05       0  5001.8    0.03       0  5007.8    0.05       0
Bank Sta=5001.8,5007.8
Exp/Cntr=0.3,0.1

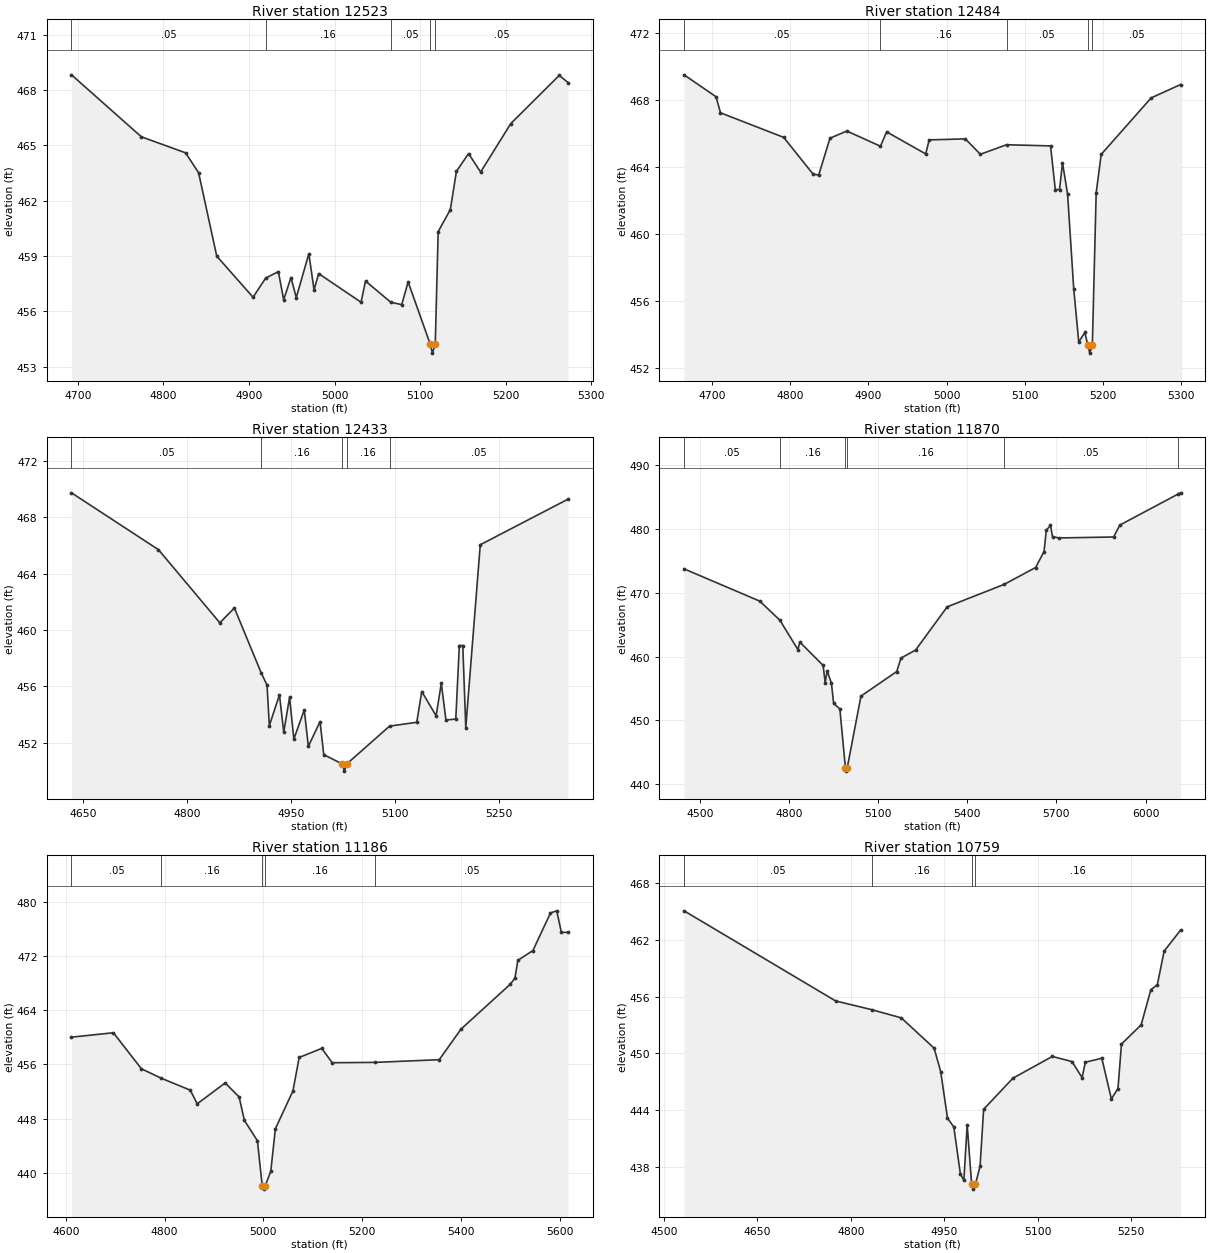
Type RM Length L Ch R = 1,12523,39,39,39
BEGIN DESCRIPTION:
UNT117 IN CCTC 24.0
END DESCRIPTION:
XS GIS Cut Line= 6
      3558992.02     10583104.58      3559109.18     10583289.44
      3559150.85     10583346.73      3559210.74     10583357.15
      3559239.39     10583346.73      3559382.62     10583208.71
#Sta/Elev= 30
  4692.7  468.83  4774.3  465.47  4826.0  464.60  4841.2  463.52  4862.4  459.00
  4904.8  456.77  4919.6  457.81  4934.4  458.16  4940.6  456.63  4949.1  457.84
  4955.3  456.75  4970.0  459.13  4976.1  457.17  4981.5  458.05  5031.0  456.50
  5036.2  457.65  5065.7  456.50  5078.5  456.37  5086.0  457.60  5111.7  454.24
  5114.4  453.74  5117.7  454.24  5121.1  460.33  5135.3  461.52  5142.4  463.59
  5156.6  464.56  5170.7  463.56  5206.0  466.19  5262.6  468.80  5272.8  468.41
#Mann=5,-1,0
  4692.7    0.05       0  4919.6    0.16       0  5065.7    0.05       0
  5111.7    0.07       0  5117.7    0.05       0
Bank Sta=5111.7,5117.7
Exp/Cntr=0.3,0.1

Type RM Length L Ch R = 1,12484,51,51,51
BEGIN DESCRIPTION:
UNT117 IN CCTC 23.0
END DESCRIPTION:
XS GIS Cut Line= 6
      3558974.20     10583120.16      3559115.26     10583356.71
      3559180.36     10583391.44      3559260.66     10583382.75
      3559299.72     10583358.88      3559399.57     10583237.33
#Sta/Elev= 30
  4664.2  469.50  4705.1  468.19  4710.8  467.23  4791.7  465.76  4829.3  463.56
  4836.5  463.51  4850.9  465.71  4872.5  466.14  4915.5  465.23  4923.4  466.09
  4973.4  464.77  4977.8  465.61  5024.1  465.67  5043.3  464.75  5076.8  465.32
  5133.1  465.25  5139.2  462.64  5144.6  462.64  5148.4  464.23  5154.9  462.38
  5162.8  456.69  5169.2  453.53  5177.1  454.10  5180.6  453.36  5183.3  452.86
  5186.6  453.36  5191.5  462.44  5197.9  464.74  5261.8  468.12  5299.5  468.92
#Mann=5,-1,0
  4664.2    0.05       0  4915.5    0.16       0  5076.8    0.05       0
  5180.6    0.07       0  5186.6    0.05       0
Bank Sta=5180.6,5186.6
Exp/Cntr=0.3,0.1

Type RM Length L Ch R = 1,12433,563,563,563
BEGIN DESCRIPTION:
Mapping XS a1879152
END DESCRIPTION:
XS GIS Cut Line= 6
      3558956.84     10583146.22      3559091.39     10583393.61
      3559176.02     10583441.35      3559258.49     10583434.84
      3559297.55     10583415.31      3559442.17     10583264.26
#Sta/Elev= 30
  4632.9  469.72  4758.4  465.69  4846.9  460.51  4867.9  461.56  4906.5  456.97
  4915.0  456.09  4918.3  453.22  4932.9  455.41  4939.1  452.76  4947.5  455.23
  4953.7  452.27  4968.7  454.34  4974.6  451.76  4991.5  453.51  4996.8  451.17
  5023.8  450.50  5026.5  450.00  5029.8  450.50  5091.8  453.19  5131.0  453.46
  5138.2  455.64  5158.9  453.92  5166.4  456.22  5173.1  453.62  5187.3  453.69
  5192.4  458.90  5197.4  458.90  5201.7  453.08  5222.6  466.04  5349.2  469.27
#Mann=5,-1,0
  4632.9    0.05       0  4906.5    0.16       0  5023.8    0.07       0
  5029.8    0.16       0  5091.8    0.05       0
Bank Sta=5023.8,5029.8
Exp/Cntr=0.3,0.1

Type RM Length L Ch R = 1,11870,684,684,684
BEGIN DESCRIPTION:
UNT117 IN CCTC 22.0
END DESCRIPTION:
XS GIS Cut Line= 2
      3558751.14     10584232.20      3559995.69     10583117.75
#Sta/Elev= 30
  4447.2  473.76  4702.2  468.69  4769.8  465.69  4830.1  461.10  4836.8  462.27
  4915.0  458.61  4922.0  455.92  4928.8  457.76  4943.0  455.82  4950.5  452.64
  4971.4  451.79  4990.1  442.52  4992.8  442.02  4996.1  442.52  5042.4  453.79
  5162.8  457.65  5177.0  459.76  5226.3  461.02  5332.5  467.80  5524.9  471.34
  5630.0  473.97  5658.4  476.48  5665.9  479.81  5680.1  480.58  5686.9  478.83
  5707.8  478.61  5892.5  478.76  5913.4  480.63  6109.5  485.50  6117.8  485.69
#Mann=6,-1,0
  4447.2    0.05       0  4769.8    0.16       0  4990.1    0.07       0
  4996.1    0.16       0  5524.9    0.05       0  6109.5    0.16       0
Bank Sta=4990.1,4996.1
Exp/Cntr=0.3,0.1

Type RM Length L Ch R = 1,11186,427,427,427
BEGIN DESCRIPTION:
UNT117 IN CCTC 21.0
END DESCRIPTION:
XS GIS Cut Line= 3
      3559249.58     10584560.22      3559499.61     10584310.19
      3559849.60     10583760.20
#Sta/Elev= 30
  4611.6  460.03  4696.5  460.68  4753.1  455.36  4793.3  453.96  4852.1  452.20
  4866.2  450.18  4922.8  453.26  4951.0  451.20  4961.7  447.73  4988.1  444.72
  4997.8  438.07  5000.5  437.57  5003.8  438.07  5015.1  440.18  5024.5  446.49
  5060.0  452.08  5072.7  457.03  5118.4  458.37  5139.6  456.25  5225.8  456.30
  5356.3  456.70  5400.4  461.22  5500.3  467.86  5509.6  468.76  5515.5  471.38
  5546.0  472.83  5581.6  478.39  5594.3  478.70  5603.6  475.52  5617.1  475.52
#Mann=5,-1,0
  4611.6    0.05       0  4793.3    0.16       0  4997.8    0.07       0
  5003.8    0.16       0  5225.8    0.05       0
Bank Sta=4997.8,5003.8
Exp/Cntr=0.3,0.1

Type RM Length L Ch R = 1,10759,543,543,543
BEGIN DESCRIPTION:
UNT117 IN CCTC 20.0
END DESCRIPTION:
XS GIS Cut Line= 2
      3559198.77     10584717.36      3559954.97     10584465.30
#Sta/Elev= 30
  4532.5  465.08  4775.8  455.55  4833.6  454.63  4881.2  453.76  4933.9  450.56
  4944.5  448.08  4955.4  443.16  4965.6  442.21  4976.1  437.25  4981.7  436.58
  4987.0  442.44  4994.2  436.15  4996.9  435.65  5000.2  436.15  5007.7  438.07
  5013.4  444.09  5060.4  447.38  5123.7  449.68  5155.3  449.14  5171.5  447.44
  5176.7  449.07  5203.1  449.49  5218.5  445.19  5229.1  446.29  5234.7  450.99
  5266.3  453.02  5281.8  456.73  5292.3  457.27  5303.2  460.82  5329.6  463.04
#Mann=4,-1,0
  4532.5    0.05       0  4833.6    0.16       0  4994.2    0.07       0
  5000.2    0.16       0
Bank Sta=4994.2,5000.2
Exp/Cntr=0.3,0.1

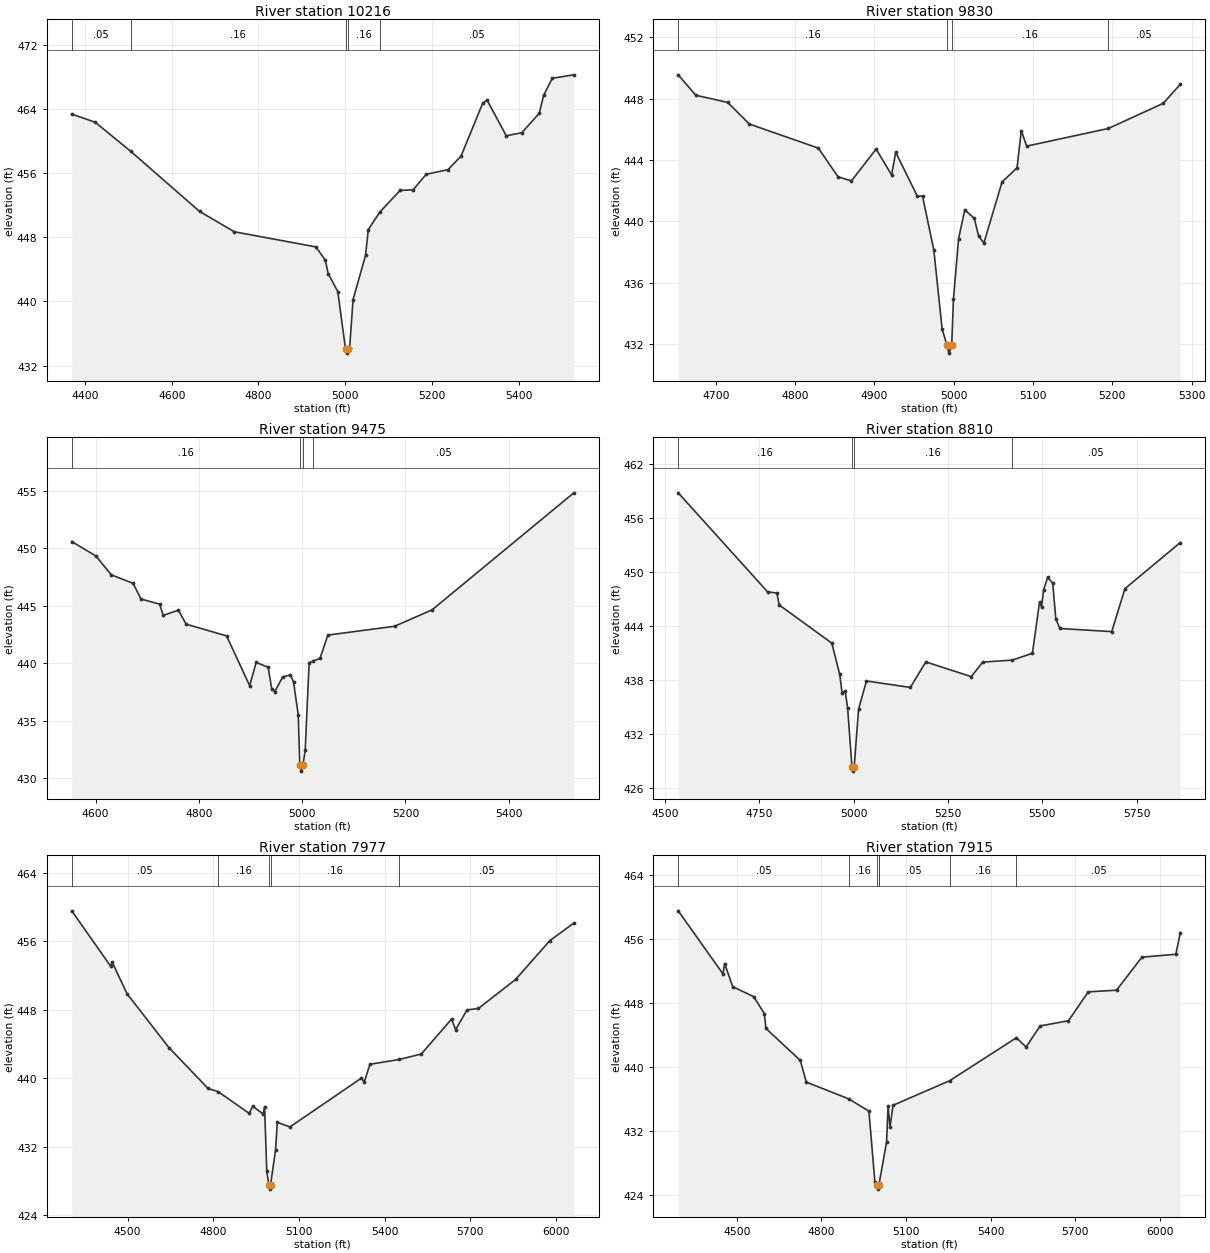
Type RM Length L Ch R = 1,10216,386,386,386
BEGIN DESCRIPTION:
UNT117 IN CCTC 19.0
END DESCRIPTION:
XS GIS Cut Line= 4
      3559435.74     10584891.83      3559961.83     10584852.77
      3560123.28     10584722.56      3560157.14     10584300.67
#Sta/Elev= 30
  4369.3  463.35  4423.3  462.34  4504.8  458.74  4664.0  451.23  4744.2  448.69
  4932.5  446.80  4954.3  445.14  4960.7  443.48  4983.0  441.23  5000.8  434.06
  5003.6  433.56  5006.8  434.06  5010.3  434.20  5018.2  440.24  5047.0  445.75
  5053.4  448.97  5080.2  451.16  5126.7  453.84  5156.8  453.92  5186.9  455.85
  5237.1  456.43  5267.2  458.10  5317.3  464.72  5327.3  465.10  5371.7  460.65
  5407.6  461.04  5447.7  463.45  5457.8  465.69  5477.8  467.82  5527.5  468.25
#Mann=5,-1,0
  4369.3    0.05       0  4504.8    0.16       0  5000.8    0.07       0
  5006.8    0.16       0  5080.2    0.05       0
Bank Sta=5000.8,5006.8
Exp/Cntr=0.3,0.1

Type RM Length L Ch R = 1,9830,355,355,355
BEGIN DESCRIPTION:
UNT117 IN CCTC 18.0
END DESCRIPTION:
XS GIS Cut Line= 3
      3559949.62     10585160.18      3560299.61     10585060.19
      3560549.56     10584960.21
#Sta/Elev= 30
  4652.5  449.56  4674.6  448.23  4714.9  447.76  4742.2  446.35  4829.3  444.78
  4854.0  442.91  4870.9  442.64  4902.1  444.72  4921.6  443.03  4926.8  444.51
  4954.1  441.64  4960.6  441.65  4974.9  438.12  4985.3  433.00  4991.4  431.91
  4994.1  431.41  4997.4  431.91  4999.6  434.93  5006.1  438.87  5013.9  440.75
  5025.9  440.20  5031.3  439.05  5038.0  438.59  5060.9  442.57  5079.8  443.50
  5085.2  445.92  5091.9  444.91  5194.9  446.06  5264.2  447.70  5285.7  448.94
#Mann=4,-1,0
  4652.5    0.16       0  4991.4    0.07       0  4997.4    0.16       0
  5194.9    0.05       0
Bank Sta=4991.4,4997.4
Exp/Cntr=0.3,0.1

Type RM Length L Ch R = 1,9475,665,665,665
BEGIN DESCRIPTION:
UNT117 IN CCTC 17.0
END DESCRIPTION:
XS GIS Cut Line= 2
      3560091.33     10585567.79      3560904.96     10585035.47
#Sta/Elev= 30
  4553.7  450.59  4600.2  449.34  4630.4  447.69  4672.6  446.95  4687.7  445.59
  4723.9  445.14  4730.9  444.16  4760.1  444.62  4775.2  443.40  4853.5  442.38
  4898.2  438.05  4910.8  440.07  4934.0  439.65  4941.0  437.75  4947.0  437.53
  4962.1  438.81  4977.2  438.98  4983.2  438.36  4992.3  435.51  4995.3  431.11
  4998.0  430.61  5001.3  431.11  5005.7  432.41  5013.4  440.05  5020.7  440.18
  5034.5  440.43  5049.6  442.45  5179.2  443.22  5251.6  444.65  5526.0  454.83
#Mann=4,-1,0
  4553.7    0.16       0  4995.3    0.07       0  5001.3    0.16       0
  5020.7    0.05       0
Bank Sta=4995.3,5001.3
Exp/Cntr=0.3,0.1

Type RM Length L Ch R = 1,8810,833,833,833
BEGIN DESCRIPTION:
UNT117 IN CCTC 16.0
END DESCRIPTION:
XS GIS Cut Line= 4
      3560193.60     10586046.34      3560560.78     10585913.53
      3560670.16     10585767.70      3560950.76     10585063.61
#Sta/Elev= 30
  4534.9  458.84  4771.7  447.83  4796.5  447.69  4802.4  446.37  4942.0  442.12
  4962.9  438.63  4969.2  436.58  4977.5  436.76  4983.8  434.94  4995.3  428.38
  4998.1  427.88  5001.3  428.38  5012.9  434.77  5033.8  437.91  5150.1  437.19
  5191.1  440.03  5311.8  438.39  5341.8  440.01  5420.2  440.23  5473.6  440.99
  5492.5  446.67  5497.9  446.16  5503.3  448.04  5514.0  449.44  5527.5  448.79
  5535.6  444.85  5546.3  443.75  5683.9  443.40  5718.9  448.18  5865.6  453.31
#Mann=4,-1,0
  4534.9    0.16       0  4995.3    0.07       0  5001.3    0.16       0
  5420.2    0.05       0
Bank Sta=4995.3,5001.3
Exp/Cntr=0.3,0.1

Type RM Length L Ch R = 1,7977,62,62,62
BEGIN DESCRIPTION:
UNT117 IN CCTC 15.0
END DESCRIPTION:
XS GIS Cut Line= 6
      3560687.52     10586520.30      3560838.56     10586240.79
      3560925.37     10586150.51      3560982.66     10586044.61
      3561027.80     10585877.94      3561032.14     10584856.22
#Sta/Elev= 30
  4304.3  459.57  4440.3  453.10  4446.0  453.57  4497.7  449.89  4644.5  443.59
  4781.8  438.81  4817.2  438.44  4925.2  435.91  4938.4  436.74  4974.5  435.82
  4979.6  436.68  4987.3  429.16  4994.5  427.55  4997.3  427.05  5000.5  427.55
  5018.0  431.64  5024.2  434.85  5068.5  434.32  5318.6  440.02  5328.6  439.55
  5348.6  441.64  5451.2  442.20  5528.6  442.84  5634.4  446.92  5648.7  445.70
  5688.7  447.99  5728.7  448.17  5858.7  451.55  5978.7  456.09  6062.7  458.14
#Mann=5,-1,0
  4304.3    0.05       0  4817.2    0.16       0  4994.5    0.07       0
  5000.5    0.16       0  5451.2    0.05       0
Bank Sta=4994.5,5000.5
Exp/Cntr=0.3,0.1

Type RM Length L Ch R = 1,7915,633,633,633
BEGIN DESCRIPTION:
UNT117 IN CCTC 14.0
END DESCRIPTION:
XS GIS Cut Line= 6
      3560704.76     10586548.91      3560867.50     10586255.98
      3560982.51     10586132.28      3561095.36     10585889.23
      3561091.02     10585759.02      3561139.75     10584884.56
#Sta/Elev= 30
  4292.7  459.55  4451.4  451.66  4457.1  452.96  4485.7  450.07  4560.1  448.82
  4597.8  446.70  4603.5  444.85  4725.4  440.84  4746.4  438.14  4896.4  436.05
  4968.3  434.51  4989.6  425.62  4997.3  425.26  5000.0  424.76  5003.3  425.26
  5003.6  425.27  5030.9  430.66  5036.2  435.14  5043.0  432.51  5053.7  435.24
  5254.2  438.31  5490.7  443.68  5525.0  442.53  5575.1  445.16  5675.3  445.81
  5745.4  449.42  5845.5  449.63  5935.7  453.76  6055.8  454.12  6071.5  456.83
#Mann=7,-1,0
  4292.7    0.05       0  4896.4    0.16       0  4997.3    0.07       0
  5003.3    0.16       0  5003.6    0.05       0  5254.2    0.16       0
  5490.7    0.05       0
Bank Sta=4997.3,5003.3
Exp/Cntr=0.3,0.1

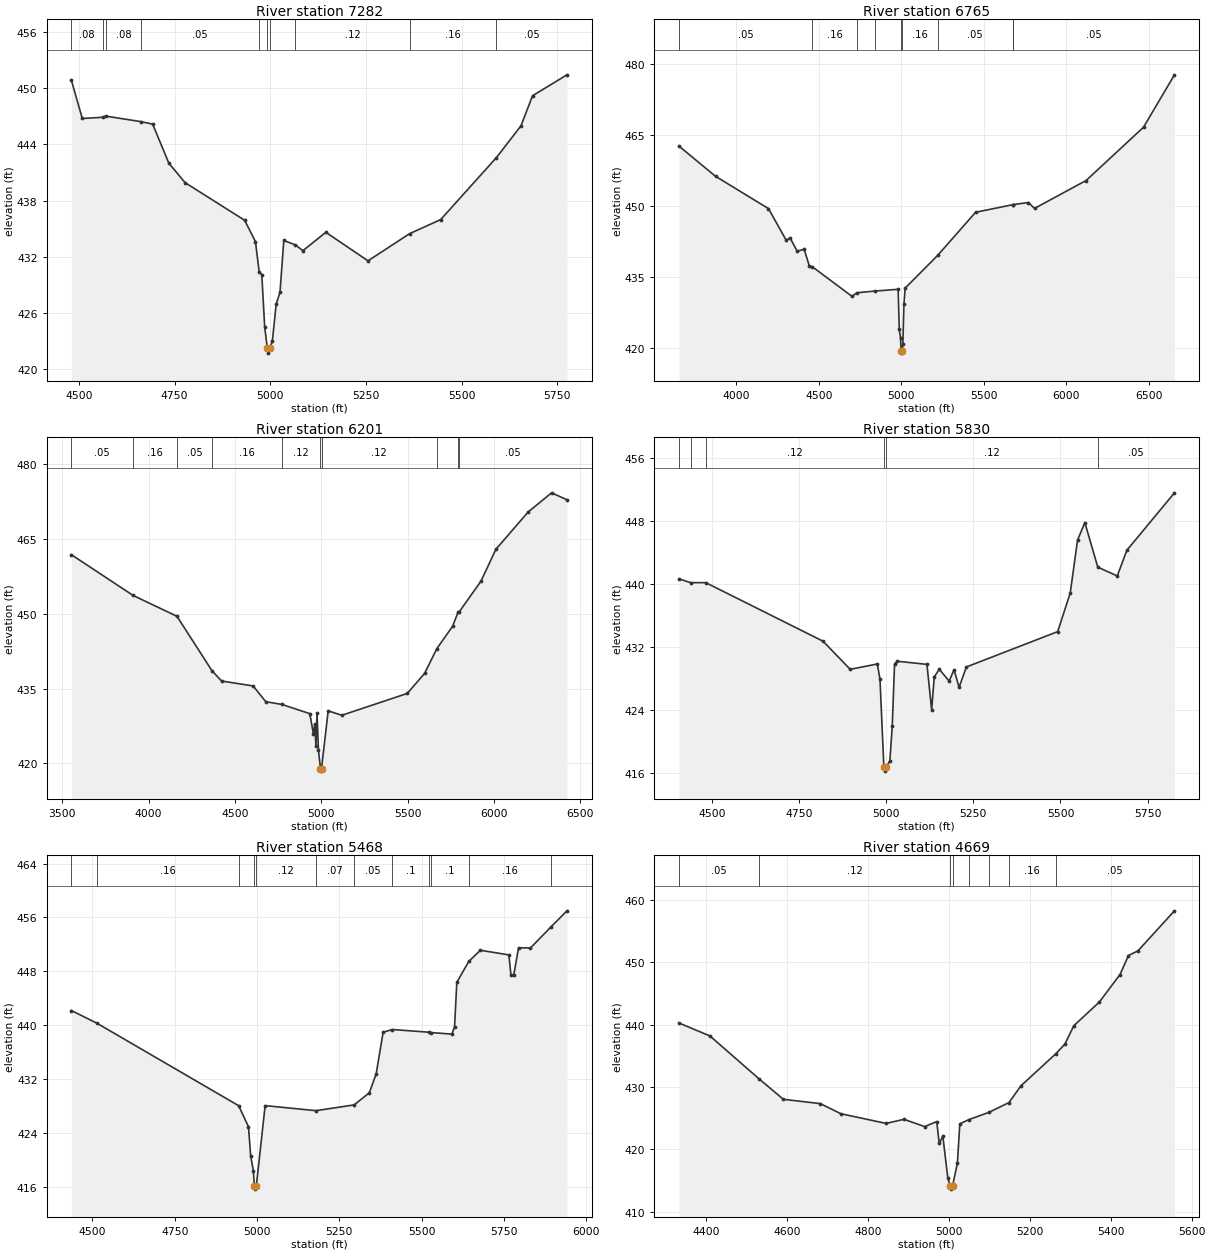
Type RM Length L Ch R = 1,7282,517,517,517
BEGIN DESCRIPTION:
UNT117 IN CCTC 13.0
END DESCRIPTION:
XS GIS Cut Line= 3
      3561099.57     10586660.22      3561449.61     10586310.19
      3561449.61     10585510.21
#Sta/Elev= 30
  4480.2  450.84  4508.5  446.77  4562.3  446.90  4569.4  447.03  4662.4  446.43
  4692.4  446.17  4734.8  441.99  4777.2  439.91  4932.8  435.89  4961.1  433.60
  4970.9  430.35  4977.7  430.08  4985.2  424.51  4992.2  422.18  4995.0  421.68
  4998.2  422.18  5005.2  422.94  5015.2  426.91  5025.2  428.17  5035.2  433.73
  5065.4  433.25  5085.2  432.64  5145.2  434.60  5255.2  431.55  5364.2  434.46
  5445.2  435.96  5590.9  442.59  5655.2  446.00  5685.2  449.20  5775.2  451.44
#Mann=10,-1,0
  4480.2    0.08       0  4562.3     0.1       0  4569.4    0.08       0
  4662.4    0.05       0  4970.9    0.16       0  4992.2    0.07       0
  4998.2    0.16       0  5065.4    0.12       0  5364.2    0.16       0
  5590.9    0.05       0
Bank Sta=4992.2,4998.2
Exp/Cntr=0.3,0.1

Type RM Length L Ch R = 1,6765,564,564,564
BEGIN DESCRIPTION:
UNT117 IN CCTC 12.0
END DESCRIPTION:
XS GIS Cut Line= 4
      3560786.36     10587081.92      3561749.88     10586488.19
      3561973.83     10586243.39      3562510.30     10584800.65
#Sta/Elev= 30
  3652.0  462.70  3873.8  456.31  4194.4  449.49  4301.9  442.81  4325.3  443.30
  4368.3  440.50  4410.8  440.89  4441.6  437.44  4460.3  437.20  4701.2  430.93
  4730.7  431.71  4842.7  432.07  4980.5  432.44  4987.2  423.98  4994.7  422.16
  4998.4  419.45  5001.2  418.95  5004.4  419.45  5008.8  420.84  5015.6  429.39
  5023.0  432.69  5220.2  439.61  5449.7  448.71  5673.5  450.30  5674.6  450.32
  5769.8  450.77  5806.7  449.52  6119.3  455.42  6467.4  466.68  6654.8  477.75
#Mann=9,-1,0
  3652.0    0.05       0  4460.3    0.16       0  4730.7    0.12       0
  4842.7    0.16       0  4998.4    0.07       0  5004.4    0.16       0
  5220.2    0.05       0  5673.5    0.12       0  5674.6    0.05       0
Bank Sta=4998.4,5004.4
Exp/Cntr=0.3,0.1

Type RM Length L Ch R = 1,6201,371,371,371
BEGIN DESCRIPTION:
UNT117 IN CCTC 11.0
END DESCRIPTION:
XS GIS Cut Line= 3
      3560786.29     10587295.49      3561999.88     10586837.14
      3563259.80     10585894.80
#Sta/Elev= 30
  3553.0  461.83  3909.5  453.68  4164.4  449.48  4366.8  438.59  4422.4  436.51
  4605.3  435.52  4678.9  432.36  4772.4  431.81  4934.0  429.96  4954.9  425.84
  4962.3  427.91  4969.5  423.44  4975.7  430.12  4984.1  422.61  4995.7  418.94
  4998.4  418.44  5001.7  418.94  5040.3  430.53  5119.5  429.64  5498.8  434.02
  5598.9  438.04  5669.8  443.00  5761.5  447.50  5792.6  450.30  5797.1  450.26
  5926.1  456.56  6011.5  462.90  6198.6  470.39  6334.6  474.24  6423.6  472.85
#Mann=10,-1,0
  3553.0    0.05       0  3909.5    0.16       0  4164.4    0.05       0
  4366.8    0.16       0  4772.4    0.12       0  4995.7    0.07       0
  5001.7    0.12       0  5669.8    0.16       0  5792.6    0.12       0
  5797.1    0.05       0
Bank Sta=4995.7,5001.7
Exp/Cntr=0.3,0.1

Type RM Length L Ch R = 1,5830,362,362,362
BEGIN DESCRIPTION:
UNT117 IN CCTC 10.0
END DESCRIPTION:
XS GIS Cut Line= 2
      3561970.98     10587444.68      3562908.49     10586376.96
#Sta/Elev= 30
  4406.0  440.65  4439.2  440.17  4482.9  440.17  4819.3  432.73  4897.1  429.16
  4974.9  429.84  4982.5  427.91  4993.7  416.73  4996.5  416.23  4999.7  416.73
  5010.8  417.52  5017.6  421.93  5024.3  429.82  5031.8  430.19  5117.2  429.79
  5130.6  424.01  5138.1  428.18  5152.4  429.18  5180.8  427.67  5195.0  429.11
  5209.3  426.87  5230.2  429.46  5492.1  433.95  5528.1  438.86  5549.0  445.57
  5569.9  447.80  5607.1  442.14  5662.9  441.02  5690.4  444.28  5826.9  451.58
#Mann=6,-1,0
  4406.0    0.05       0  4439.2    0.16       0  4482.9    0.12       0
  4993.7    0.07       0  4999.7    0.12       0  5607.1    0.05       0
Bank Sta=4993.7,4999.7
Exp/Cntr=0.3,0.1

Type RM Length L Ch R = 1,5468,799,799,799
BEGIN DESCRIPTION:
UNT117 IN CCTC 9.0
END DESCRIPTION:
XS GIS Cut Line= 2
      3562319.92     10587668.66      3563174.10     10586429.06
#Sta/Elev= 30
  4436.1  442.16  4513.4  440.28  4944.1  428.02  4973.9  424.90  4980.7  420.52
  4988.8  418.37  4991.8  416.12  4994.6  415.62  4997.8  416.12  5024.6  428.03
  5179.1  427.28  5295.1  428.14  5341.1  429.94  5362.0  432.77  5383.0  438.94
  5411.0  439.34  5521.9  438.94  5527.0  438.89  5592.0  438.66  5600.1  439.77
  5606.9  446.35  5643.0  449.45  5678.5  451.12  5765.1  450.43  5771.2  447.50
  5780.0  447.47  5794.4  451.48  5830.7  451.47  5894.2  454.65  5941.5  456.98
#Mann=12,-1,0
  4436.1    0.12       0  4513.4    0.16       0  4944.1    0.12       0
  4991.8    0.07       0  4997.8    0.12       0  5179.1    0.07       0
  5295.1    0.05       0  5411.0     0.1       0  5521.9    0.15       0
  5527.0     0.1       0  5643.0    0.16       0  5894.2    0.05       0
Bank Sta=4991.8,4997.8
Exp/Cntr=0.3,0.1

Type RM Length L Ch R = 1,4669,492,492,492
BEGIN DESCRIPTION:
UNT117 IN CCTC 8.0
END DESCRIPTION:
XS GIS Cut Line= 3
      3562991.80     10587934.28      3563085.55     10587408.24
      3563470.95     10586835.34
#Sta/Elev= 30
  4332.7  440.26  4409.4  438.18  4530.0  431.35  4590.8  428.03  4682.2  427.34
  4733.0  425.72  4844.7  424.17  4889.0  424.83  4940.0  423.66  4970.0  424.46
  4976.0  420.96  4985.0  422.12  4997.3  415.46  5003.0  414.14  5005.7  413.64
  5009.0  414.14  5021.0  417.80  5027.0  424.10  5049.0  424.77  5099.7  425.96
  5148.5  427.51  5178.0  430.19  5263.7  435.30  5286.5  436.86  5308.9  439.83
  5371.9  443.62  5422.9  448.02  5443.9  451.07  5467.3  451.82  5557.5  458.23
#Mann=8,-1,0
  4332.7    0.05       0  4530.0    0.12       0  5003.0    0.07       0
  5009.0    0.12       0  5049.0    0.16       0  5099.7    0.12       0
  5148.5    0.16       0  5263.7    0.05       0
Bank Sta=5003,5009
Exp/Cntr=0.3,0.1

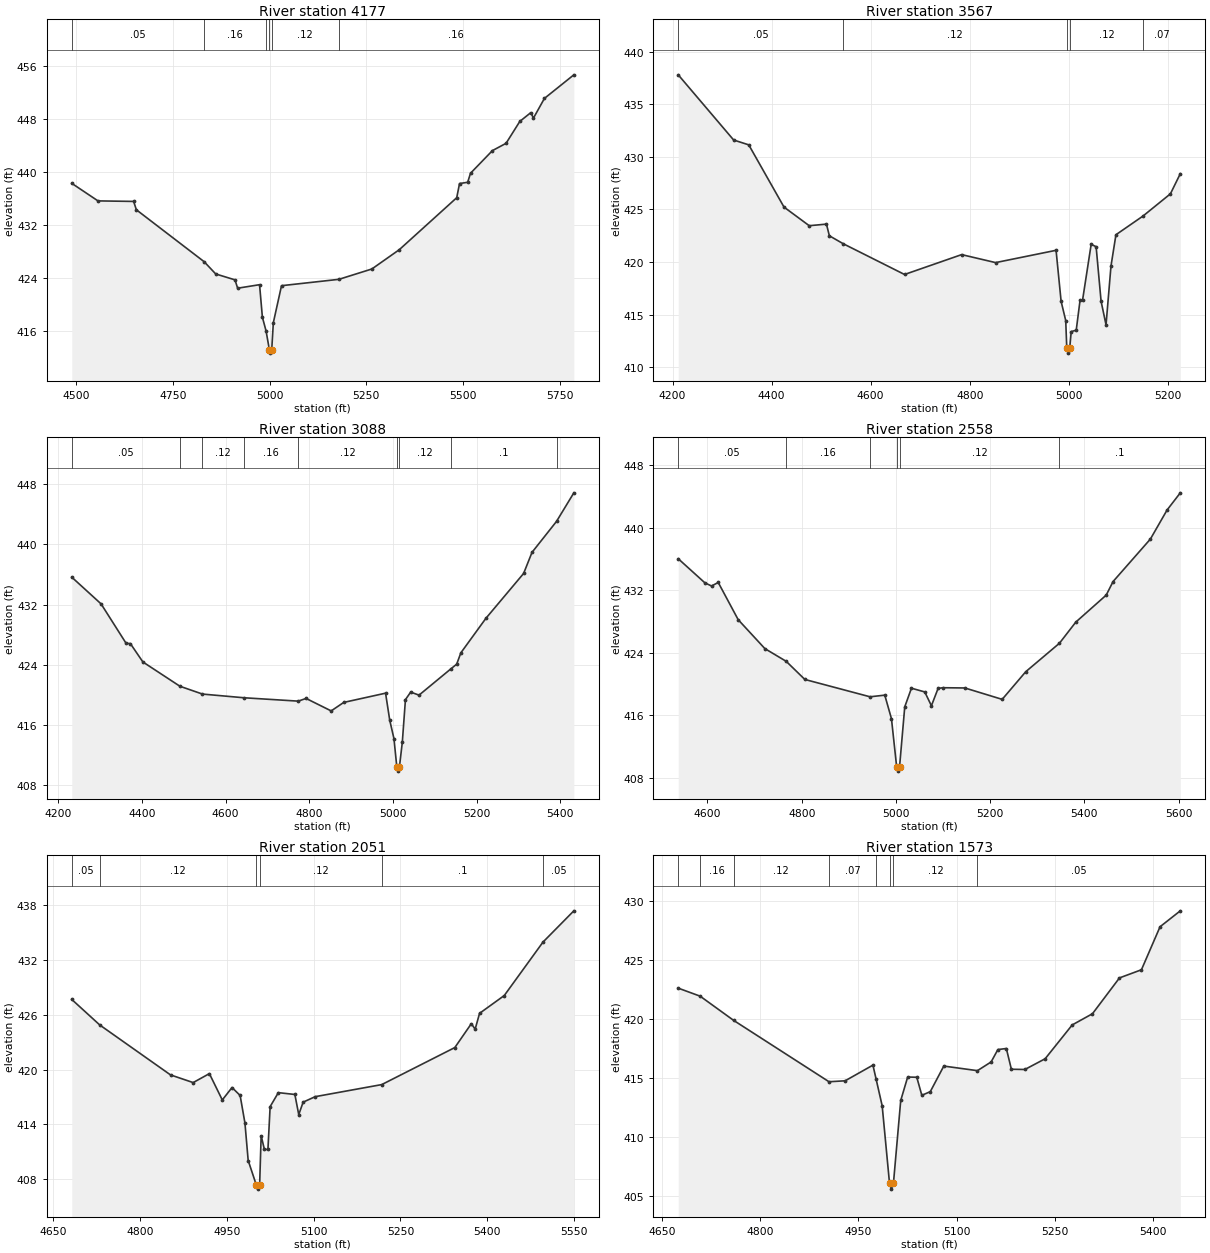
Type RM Length L Ch R = 1,4177,610,610,610
BEGIN DESCRIPTION:
UNT117 IN CCTC 6.0
END DESCRIPTION:
XS GIS Cut Line= 2
      3563111.58     10588028.04      3564007.42     10587090.54
#Sta/Elev= 30
  4489.2  438.35  4556.9  435.70  4649.0  435.62  4656.0  434.36  4831.1  426.52
  4861.0  424.67  4910.7  423.78  4917.6  422.52  4974.2  423.05  4981.5  418.14
  4991.0  416.07  4999.6  413.22  5002.3  412.72  5005.6  413.22  5009.8  417.32
  5030.9  422.90  5179.1  423.86  5264.2  425.42  5335.0  428.33  5483.4  436.18
  5490.7  438.32  5511.7  438.51  5519.0  439.87  5575.6  443.29  5610.8  444.39
  5646.4  447.70  5674.7  449.02  5681.6  448.20  5709.9  451.17  5785.9  454.73
#Mann=6,-1,0
  4489.2    0.05       0  4831.1    0.16       0  4991.0    0.12       0
  4999.6    0.07       0  5005.6    0.12       0  5179.1    0.16       0
Bank Sta=4999.6,5005.6
Exp/Cntr=0.3,0.1

Type RM Length L Ch R = 1,3567,479,479,479
BEGIN DESCRIPTION:
UNT117 IN CCTC 5.0
END DESCRIPTION:
XS GIS Cut Line= 3
      3563149.64     10588160.18      3563949.61     10588010.19
      3564149.60     10588010.19
#Sta/Elev= 30
  4211.4  437.80  4323.3  431.60  4353.8  431.14  4425.0  425.22  4475.9  423.45
  4510.7  423.60  4516.6  422.49  4544.8  421.73  4668.4  418.81  4783.7  420.70
  4852.3  419.94  4974.4  421.11  4984.6  416.25  4993.9  414.43  4996.0  411.83
  4998.8  411.33  5002.0  411.83  5005.0  413.38  5015.1  413.51  5022.8  416.34
  5027.8  416.34  5045.3  421.68  5055.3  421.45  5065.3  416.27  5075.3  414.02
  5085.3  419.61  5095.3  422.59  5150.0  424.37  5205.3  426.48  5225.3  428.40
#Mann=5,-1,0
  4211.4    0.05       0  4544.8    0.12       0  4996.0    0.07       0
  5002.0    0.12       0  5150.0    0.07       0
Bank Sta=4996,5002
Exp/Cntr=0.3,0.1

Type RM Length L Ch R = 1,3088,530,530,530
BEGIN DESCRIPTION:
UNT117 IN CCTC 4.0
END DESCRIPTION:
XS GIS Cut Line= 3
      3563249.62     10588460.19      3564049.61     10588460.19
      3564449.62     10588460.19
#Sta/Elev= 30
  4232.5  435.64  4302.5  432.09  4362.5  426.83  4372.5  426.81  4402.5  424.36
  4491.0  421.13  4544.9  420.09  4643.8  419.60  4773.8  419.15  4792.5  419.51
  4852.5  417.85  4882.5  418.98  4982.5  420.21  4992.5  416.60  5002.5  414.18
  5009.5  410.34  5012.2  409.84  5015.5  410.34  5022.5  413.67  5030.0  419.35
  5042.5  420.35  5062.5  419.95  5138.3  423.43  5152.5  424.07  5162.5  425.58
  5222.5  430.18  5312.5  436.14  5332.5  438.94  5391.1  443.06  5432.5  446.86
#Mann=9,-1,0
  4232.5    0.05       0  4491.0    0.16       0  4544.9    0.12       0
  4643.8    0.16       0  4773.8    0.12       0  5009.5    0.07       0
  5015.5    0.12       0  5138.3     0.1       0  5391.1    0.05       0
Bank Sta=5009.5,5015.5
Exp/Cntr=0.3,0.1

Type RM Length L Ch R = 1,2558,507,507,507
BEGIN DESCRIPTION:
UNT117 IN CCTC 3.0
END DESCRIPTION:
XS GIS Cut Line= 3
      3563649.60     10589260.20      3564049.61     10588860.19
      3564449.61     10588560.19
#Sta/Elev= 30
  4537.9  436.04  4594.5  432.95  4608.6  432.55  4622.8  433.00  4665.2  428.23
  4721.8  424.53  4767.1  422.90  4806.6  420.58  4945.0  418.36  4976.3  418.57
  4990.5  415.55  5001.6  409.34  5004.4  408.84  5007.6  409.34  5018.7  417.07
  5032.9  419.46  5061.2  418.98  5075.3  417.21  5089.5  419.44  5100.1  419.52
  5146.3  419.49  5225.5  418.03  5275.5  421.57  5347.1  425.22  5381.7  427.92
  5446.3  431.38  5460.9  433.12  5540.1  438.56  5575.5  442.28  5603.6  444.48
#Mann=6,-1,0
  4537.9    0.05       0  4767.1    0.16       0  4945.0    0.12       0
  5001.6    0.07       0  5007.6    0.12       0  5347.1     0.1       0
Bank Sta=5001.6,5007.6
Exp/Cntr=0.3,0.1

Type RM Length L Ch R = 1,2051,478,478,478
BEGIN DESCRIPTION:
UNT117 IN CCTC 2.0
END DESCRIPTION:
XS GIS Cut Line= 3
      3563949.63     10589310.18      3564249.61     10589160.19
      3564599.61     10588760.18
#Sta/Elev= 30
  4682.5  427.66  4730.8  424.87  4853.0  419.41  4892.1  418.57  4920.1  419.55
  4942.4  416.67  4959.2  418.03  4973.2  417.16  4981.5  414.15  4987.1  410.05
  5000.9  407.42  5003.7  406.92  5006.9  407.42  5009.5  412.76  5015.1  411.26
  5021.2  411.26  5025.0  415.94  5039.2  417.47  5067.7  417.27  5074.4  415.07
  5082.0  416.43  5102.8  417.03  5217.7  418.35  5343.9  422.40  5372.4  425.01
  5379.0  424.41  5386.6  426.14  5429.3  428.09  5496.1  433.93  5549.4  437.35
#Mann=6,-1,0
  4682.5    0.05       0  4730.8    0.12       0  5000.9    0.07       0
  5006.9    0.12       0  5217.7     0.1       0  5496.1    0.05       0
Bank Sta=5000.9,5006.9
Exp/Cntr=0.3,0.1

Type RM Length L Ch R = 1,1573,0,0,0
BEGIN DESCRIPTION:
UNT117 IN CCTC 1.0
END DESCRIPTION:
XS GIS Cut Line= 3
      3564349.60     10589610.20      3564599.61     10589360.19
      3564699.61     10588960.17
#Sta/Elev= 30
  4675.2  422.61  4708.6  421.93  4759.6  419.88  4905.2  414.67  4929.8  414.75
  4972.2  416.08  4976.9  414.93  4986.3  412.63  4997.5  406.06  5000.2  405.56
  5003.5  406.06  5014.6  413.08  5025.2  415.07  5039.1  415.05  5046.8  413.52
  5059.7  413.83  5080.3  416.00  5131.6  415.61  5152.5  416.35  5162.8  417.40
  5175.7  417.49  5183.4  415.73  5204.0  415.71  5234.9  416.62  5276.2  419.49
  5307.1  420.44  5348.3  423.48  5381.8  424.17  5410.2  427.82  5441.1  429.17
#Mann=8,-1,0
  4675.2    0.07       0  4708.6    0.16       0  4759.6    0.12       0
  4905.2    0.07       0  4976.9    0.12       0  4997.5    0.07       0
  5003.5    0.12       0  5131.6    0.05       0
Bank Sta=4997.5,5003.5
Exp/Cntr=0.3,0.1

Chan Stop Cuts=-1