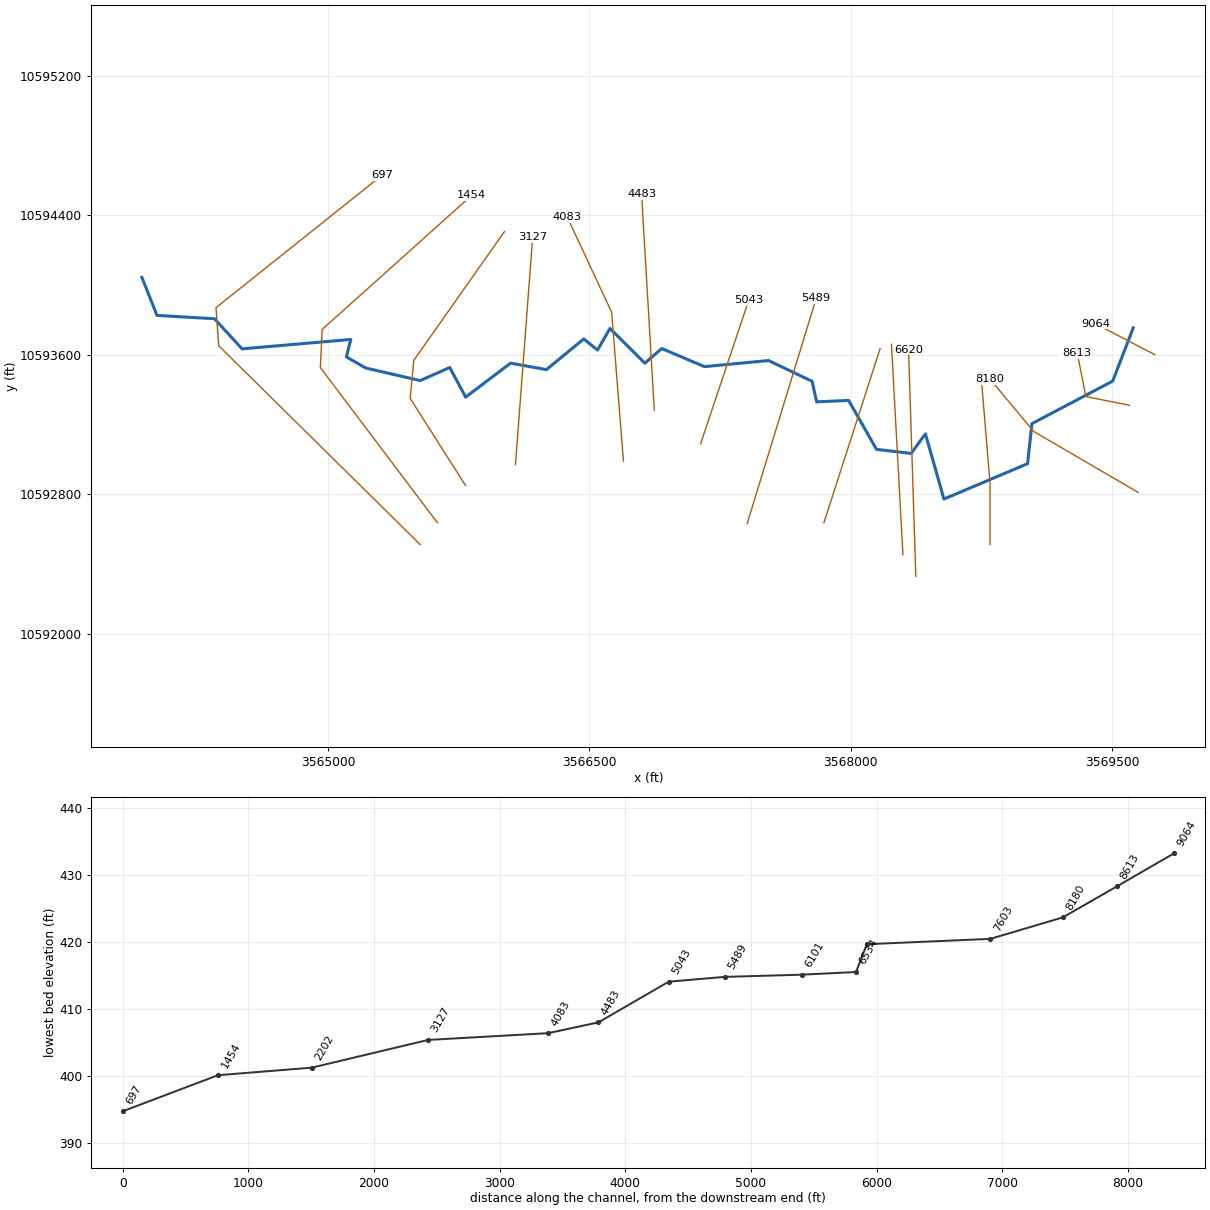
--- UNT121 IN CCTC.prj (project) ---

Proj Title=UNT121 IN CCTC Base Level Engineering
Current Plan=p01
Default Exp/Contr=0.3,0.1
English Units
Geom File=g01
Flow File=f01
Plan File=p01
BEGIN DESCRIPTION:
UNT121 IN CCTC
END DESCRIPTION:

--- UNT121 IN CCTC.p01 (plan) ---

Plan Title=Multiple Run
Short Identifier=Multiple
Geom File=g01
Flow File=f01
Subcritical Flow
K Sum by GR= 0
Std Step Tol= 0.01
Critical Tol= 0.01
Num of Std Step Trials= 20
Max Error Tol= 0.3
Flow Tol Ratio= 0.001
Split Flow NTrial= 30
Split Flow Tol= 0.02
Split Flow Ratio= 0.02
Log Output Level= 0
Friction Slope Method= 1
Unsteady Friction Slope Method= 2
Unsteady Bridges Friction Slope Method= 1
Parabolic Critical Depth
Global Vel Dist=  1 , 1 , 1
Global Log Level= 0
CheckData=True
Encroach Param= -1, 0, 0, 0
BEGIN DESCRIPTION:
Multiple Run
END DESCRIPTION:

--- UNT121 IN CCTC.f01 (steady flow) ---

Flow Title=Multiple
Number of Profiles=7
Profile Names=10-year,25-year,50-year,1pct_min,100-year,1pct_plu,500-year
River Rch & RM= UNT121 IN CCTC,Reach-1,9064
    1457    2016    2482    2231    3018    4081    4444
River Rch & RM= UNT121 IN CCTC,Reach-1,4483
    2015    2830    3516    3186    4309    5827    6449
Boundary for River Rch & Prof#=UNT121 IN CCTC,Reach-1,1
Up Type=0
Dn Type=3
Dn Slope=0.005
Boundary for River Rch & Prof#=UNT121 IN CCTC,Reach-1,2
Up Type=0
Dn Type=3
Dn Slope=0.005
Boundary for River Rch & Prof#=UNT121 IN CCTC,Reach-1,3
Up Type=0
Dn Type=3
Dn Slope=0.005
Boundary for River Rch & Prof#=UNT121 IN CCTC,Reach-1,4
Up Type=0
Dn Type=3
Dn Slope=0.005
Boundary for River Rch & Prof#=UNT121 IN CCTC,Reach-1,5
Up Type=0
Dn Type=3
Dn Slope=0.005
Boundary for River Rch & Prof#=UNT121 IN CCTC,Reach-1,6
Up Type=0
Dn Type=3
Dn Slope=0.005
Boundary for River Rch & Prof#=UNT121 IN CCTC,Reach-1,7
Up Type=0
Dn Type=3
Dn Slope=0.005

--- UNT121 IN CCTC.g01 (geometry) ---

Geom Title=Existing Conditions

River Reach=UNT121 IN CCTC,Reach-1
Reach XY= 30
      3569621.14     10593754.36      3569503.50     10593449.00
      3569040.00     10593205.00      3569014.75     10592975.00
      3568534.75     10592772.00      3568428.75     10593146.00
      3568346.25     10593034.00      3568148.00     10593057.00
      3567987.75     10593338.00      3567804.25     10593330.00
      3567778.00     10593448.00      3567528.25     10593567.00
      3567160.00     10593532.00      3566915.50     10593636.00
      3566818.00     10593552.00      3566618.00     10593751.00
      3566546.50     10593627.00      3566467.50     10593691.00
      3566253.50     10593515.00      3566047.25     10593552.00
      3565789.75     10593357.00      3565698.50     10593527.00
      3565529.00     10593452.00      3565216.50     10593524.00
      3565105.00     10593588.00      3565130.50     10593688.00
      3564506.50     10593634.00      3564348.00     10593807.00
      3564018.25     10593826.00      3563931.75     10594044.00

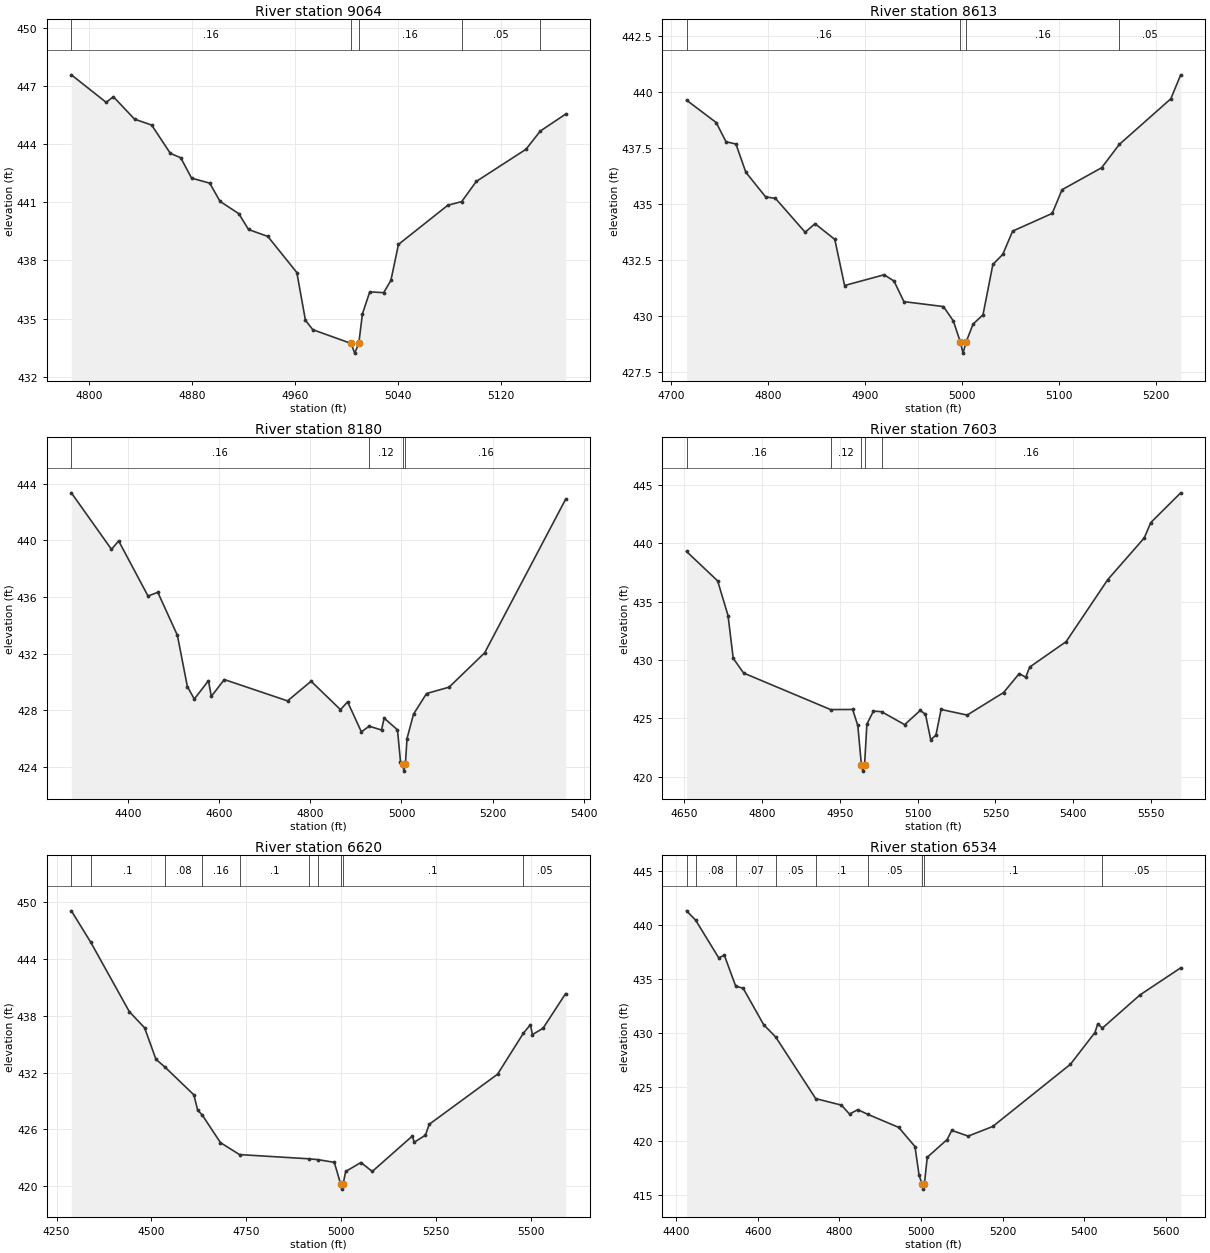
Type RM Length L Ch R = 1,9064,451,451,451
BEGIN DESCRIPTION:
UNT121 IN CCTC 16.0
END DESCRIPTION:
XS GIS Cut Line= 2
      3569744.88     10593600.81      3569404.60     10593777.90
#Sta/Elev= 30
  4786.4  447.58  4813.4  446.16  4819.0  446.45  4835.5  445.29  4848.7  444.99
  4863.2  443.53  4871.3  443.30  4879.7  442.25  4893.8  441.99  4901.8  441.05
  4916.3  440.42  4923.9  439.60  4938.9  439.24  4961.4  437.38  4968.1  434.91
  4973.8  434.43  5003.5  433.72  5006.3  433.22  5009.5  433.72  5012.3  435.24
  5018.0  436.38  5028.8  436.34  5034.4  436.97  5040.3  438.83  5078.6  440.85
  5089.4  441.04  5100.7  442.08  5139.3  443.74  5150.4  444.68  5170.0  445.55
#Mann=5,-1,0
  4786.4    0.16       0  5003.5    0.07       0  5009.5    0.16       0
  5089.4    0.05       0  5150.4    0.16       0
Bank Sta=5003.5,5009.5
Exp/Cntr=0.3,0.1

Type RM Length L Ch R = 1,8613,433,433,433
BEGIN DESCRIPTION:
UNT121 IN CCTC 15.0
END DESCRIPTION:
XS GIS Cut Line= 3
      3569599.59     10593310.19      3569349.61     10593360.19
      3569299.61     10593610.21
#Sta/Elev= 30
  4715.5  439.63  4746.1  438.63  4756.3  437.77  4766.5  437.67  4776.7  436.41
  4797.1  435.31  4807.3  435.24  4837.9  433.73  4848.1  434.11  4868.5  433.41
  4878.6  431.35  4919.4  431.83  4929.6  431.55  4939.8  430.63  4980.6  430.41
  4990.8  429.77  4998.0  428.83  5000.8  428.33  5004.0  428.83  5011.2  429.63
  5021.4  430.04  5031.6  432.29  5041.8  432.74  5052.0  433.78  5092.8  434.57
  5103.0  435.63  5143.8  436.61  5162.0  437.65  5215.2  439.69  5225.4  440.76
#Mann=4,-1,0
  4715.5    0.16       0  4998.0    0.07       0  5004.0    0.16       0
  5162.0    0.05       0
Bank Sta=4998,5004
Exp/Cntr=0.3,0.1

Type RM Length L Ch R = 1,8180,577,577,577
BEGIN DESCRIPTION:
UNT121 IN CCTC 14.0
END DESCRIPTION:
XS GIS Cut Line= 3
      3569649.65     10592810.17      3569049.61     10593160.19
      3568799.60     10593460.20
#Sta/Elev= 30
  4275.2  443.37  4363.3  439.37  4379.0  439.97  4443.5  436.07  4465.0  436.33
  4508.0  433.29  4529.9  429.66  4545.2  428.78  4576.2  430.08  4582.5  428.97
  4611.0  430.16  4749.9  428.65  4801.6  430.04  4866.1  428.03  4881.8  428.58
  4912.0  426.46  4929.3  426.86  4956.2  426.59  4962.0  427.43  4991.3  426.60
  4997.9  424.36  5002.7  424.18  5005.4  423.68  5008.7  424.18  5012.2  425.98
  5026.5  427.71  5055.1  429.17  5104.6  429.62  5182.7  432.05  5360.4  442.91
#Mann=4,-1,0
  4275.2    0.16       0  4929.3    0.12       0  5002.7    0.07       0
  5008.7    0.16       0
Bank Sta=5002.7,5008.7
Exp/Cntr=0.3,0.1

Type RM Length L Ch R = 1,7603,983,983,983
BEGIN DESCRIPTION:
UNT121 IN CCTC 13.0
END DESCRIPTION:
XS GIS Cut Line= 3
      3568799.61     10592510.15      3568799.61     10592860.19
      3568749.61     10593460.17
#Sta/Elev= 30
  4654.9  439.29  4714.9  436.77  4734.9  433.80  4744.9  430.14  4764.9  428.88
  4932.5  425.75  4974.9  425.76  4984.9  424.39  4991.9  420.98  4994.7  420.48
  4997.9  420.98  5002.4  424.50  5015.0  425.62  5030.6  425.57  5075.2  424.46
  5105.3  425.68  5115.3  425.34  5125.4  423.17  5135.4  423.56  5145.4  425.76
  5195.6  425.28  5265.8  427.21  5295.9  428.83  5308.5  428.52  5316.0  429.39
  5386.3  431.57  5466.5  436.88  5536.8  440.45  5549.3  441.76  5607.0  444.31
#Mann=5,-1,0
  4654.9    0.16       0  4932.5    0.12       0  4991.9    0.07       0
  4997.9    0.12       0  5030.6    0.16       0
Bank Sta=4991.9,4997.9
Exp/Cntr=0.3,0.1

Type RM Length L Ch R = 1,6620,86,86,86
BEGIN DESCRIPTION:
UNT121 IN CCTC 12.0
END DESCRIPTION:
XS GIS Cut Line= 2
      3568373.37     10592327.41      3568331.71     10593629.45
#Sta/Elev= 30
  4289.2  449.08  4340.4  445.75  4442.1  438.42  4482.1  436.73  4512.1  433.40
  4536.5  432.55  4612.1  429.64  4622.1  428.03  4634.5  427.49  4682.2  424.59
  4732.5  423.33  4916.8  422.88  4940.0  422.79  4982.3  422.51  4999.3  420.18
  5002.1  419.68  5005.3  420.18  5012.3  421.55  5052.4  422.49  5082.4  421.55
  5188.0  425.29  5193.0  424.63  5222.5  425.38  5232.5  426.53  5412.6  431.82
  5480.8  436.16  5499.4  437.06  5504.4  436.00  5532.6  436.68  5591.9  440.33
#Mann=10,-1,0
  4289.2    0.05       0  4340.4     0.1       0  4536.5    0.08       0
  4634.5    0.16       0  4732.5     0.1       0  4916.8    0.05       0
  4940.0     0.1       0  4999.3    0.07       0  5005.3     0.1       0
  5480.8    0.05       0
Bank Sta=4999.3,5005.3
Exp/Cntr=0.3,0.1

Type RM Length L Ch R = 1,6534,433,433,433
BEGIN DESCRIPTION:
UNT121 IN CCTC 11.0
END DESCRIPTION:
XS GIS Cut Line= 2
      3568299.59     10592451.54      3568233.62     10593659.84
#Sta/Elev= 30
  4425.7  441.31  4448.0  440.45  4504.5  436.96  4518.3  437.20  4546.0  434.35
  4564.6  434.13  4614.6  430.77  4644.0  429.63  4742.1  423.92  4804.9  423.32
  4824.9  422.49  4845.0  422.90  4869.4  422.47  4945.1  421.26  4985.2  419.48
  4995.2  416.82  5002.2  416.04  5005.0  415.54  5008.2  416.04  5015.2  418.49
  5063.8  420.13  5075.3  420.98  5115.4  420.45  5175.5  421.34  5365.7  427.10
  5425.8  430.04  5432.5  430.82  5444.3  430.46  5536.0  433.52  5635.8  436.03
#Mann=9,-1,0
  4425.7    0.05       0  4448.0    0.08       0  4546.0    0.07       0
  4644.0    0.05       0  4742.1     0.1       0  4869.4    0.05       0
  5002.2    0.03       0  5008.2     0.1       0  5444.3    0.05       0
Bank Sta=5002.2,5008.2
Exp/Cntr=0.3,0.1

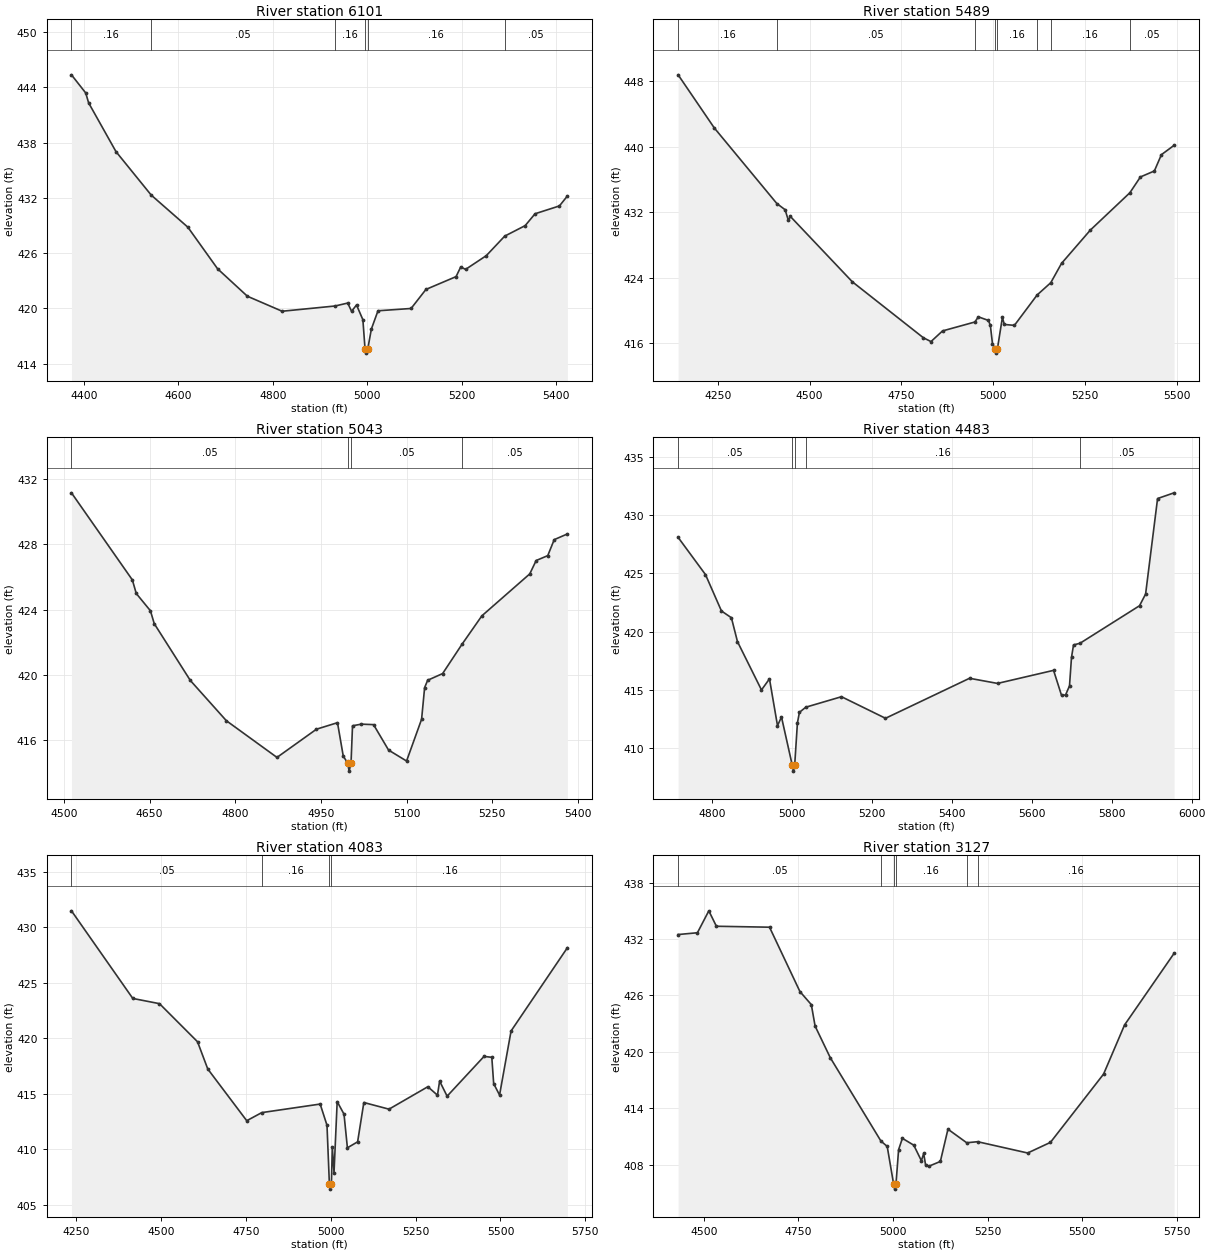
Type RM Length L Ch R = 1,6101,612,612,612
BEGIN DESCRIPTION:
UNT121 IN CCTC 10.0
END DESCRIPTION:
XS GIS Cut Line= 2
      3567845.60     10592635.52      3568168.47     10593635.39
#Sta/Elev= 30
  4373.3  445.37  4403.5  443.40  4409.7  442.32  4467.6  437.03  4542.2  432.31
  4619.9  428.82  4682.9  424.30  4746.0  421.32  4819.6  419.69  4931.9  420.26
  4958.6  420.58  4966.7  419.68  4977.2  420.37  4990.7  418.77  4995.2  415.64
  4998.0  415.14  5001.2  415.64  5008.7  417.76  5022.7  419.74  5092.8  419.99
  5124.3  422.06  5188.1  423.45  5197.9  424.49  5208.4  424.24  5252.2  425.73
  5291.2  427.85  5334.5  428.99  5355.5  430.28  5407.1  431.13  5424.0  432.21
#Mann=6,-1,0
  4373.3    0.16       0  4542.2    0.05       0  4931.9    0.16       0
  4995.2    0.07       0  5001.2    0.16       0  5291.2    0.05       0
Bank Sta=4995.2,5001.2
Exp/Cntr=0.3,0.1

Type RM Length L Ch R = 1,5489,446,446,446
BEGIN DESCRIPTION:
UNT121 IN CCTC 9.0
END DESCRIPTION:
XS GIS Cut Line= 2
      3567405.54     10592631.58      3567801.36     10593923.19
#Sta/Elev= 30
  4142.0  448.79  4240.6  442.30  4411.0  433.07  4433.4  432.32  4442.3  431.01
  4447.5  431.51  4616.5  423.52  4809.9  416.69  4830.8  416.22  4862.2  417.52
  4950.3  418.61  4959.8  419.24  4987.3  418.80  4992.5  418.19  4998.2  415.98
  5005.6  415.31  5008.4  414.81  5011.6  415.31  5025.3  419.17  5030.5  418.31
  5058.0  418.20  5119.9  421.91  5157.1  423.41  5186.4  425.77  5265.0  429.84
  5372.5  434.39  5401.2  436.32  5439.2  437.05  5458.4  439.04  5492.9  440.18
#Mann=8,-1,0
  4142.0    0.16       0  4411.0    0.05       0  4950.3    0.16       0
  5005.6    0.07       0  5011.6    0.16       0  5119.9    0.05       0
  5157.1    0.16       0  5372.5    0.05       0
Bank Sta=5005.6,5011.6
Exp/Cntr=0.3,0.1

Type RM Length L Ch R = 1,5043,560,560,560
BEGIN DESCRIPTION:
UNT121 IN CCTC 8.0
END DESCRIPTION:
XS GIS Cut Line= 2
      3567138.06     10593089.14      3567414.10     10593912.08
#Sta/Elev= 30
  4513.4  431.16  4620.0  425.82  4626.8  424.99  4651.6  423.93  4658.3  423.14
  4721.4  419.66  4784.5  417.19  4873.1  414.94  4942.2  416.67  4979.0  417.07
  4989.1  415.02  4996.7  414.60  4999.4  414.10  5002.7  414.60  5005.3  416.88
  5020.8  416.98  5042.1  416.95  5068.4  415.39  5099.9  414.72  5126.2  417.28
  5131.5  419.22  5136.8  419.67  5163.0  420.08  5196.8  421.87  5231.7  423.62
  5315.5  426.19  5326.7  427.01  5347.0  427.31  5358.3  428.29  5381.4  428.64
#Mann=4,-1,0
  4513.4    0.05       0  4996.7    0.07       0  5002.7    0.05       0
  5196.8    0.05       0
Bank Sta=4996.7,5002.7
Exp/Cntr=0.3,0.1

Type RM Length L Ch R = 1,4483,400,400,400
BEGIN DESCRIPTION:
UNT121 IN CCTC 7.0
END DESCRIPTION:
XS GIS Cut Line= 2
      3566872.44     10593281.86      3566799.52     10594521.41
#Sta/Elev= 30
  4714.3  428.07  4782.8  424.88  4822.8  421.76  4847.7  421.18  4862.9  419.13
  4923.0  414.99  4943.0  415.94  4963.1  411.93  4973.1  412.67  5000.1  408.53
  5002.9  408.03  5006.1  408.53  5013.0  412.17  5018.0  413.07  5033.9  413.51
  5123.3  414.41  5233.5  412.56  5443.9  415.99  5514.0  415.55  5654.3  416.67
  5674.3  414.52  5684.3  414.56  5694.2  415.34  5699.2  417.79  5704.3  418.85
  5720.4  418.99  5869.5  422.21  5884.7  423.21  5914.7  431.40  5956.0  431.89
#Mann=5,-1,0
  4714.3    0.05       0  5000.1    0.03       0  5006.1    0.05       0
  5033.9    0.16       0  5720.4    0.05       0
Bank Sta=5000.1,5006.1
Exp/Cntr=0.3,0.1

Type RM Length L Ch R = 1,4083,956,956,956
BEGIN DESCRIPTION:
UNT121 IN CCTC 6.0
END DESCRIPTION:
XS GIS Cut Line= 3
      3566695.35     10592990.19      3566627.64     10593844.36
      3566372.45     10594391.19
#Sta/Elev= 30
  4236.8  431.48  4417.4  423.59  4496.0  423.12  4608.0  419.69  4638.1  417.24
  4752.9  412.58  4797.1  413.31  4969.1  414.08  4989.2  412.17  4996.2  406.92
  4998.9  406.42  5002.2  406.92  5004.9  410.20  5009.9  407.91  5019.2  414.30
  5039.3  413.17  5049.3  410.14  5079.4  410.68  5097.7  414.22  5171.8  413.62
  5286.1  415.64  5314.5  414.88  5320.8  416.15  5342.9  414.79  5451.6  418.37
  5474.5  418.29  5480.0  415.92  5497.3  414.89  5531.2  420.66  5697.1  428.16
#Mann=4,-1,0
  4236.8    0.05       0  4797.1    0.16       0  4996.2    0.07       0
  5002.2    0.16       0
Bank Sta=4996.2,5002.2
Exp/Cntr=0.3,0.1

Type RM Length L Ch R = 1,3127,925,925,925
BEGIN DESCRIPTION:
UNT121 IN CCTC 5.0
END DESCRIPTION:
XS GIS Cut Line= 2
      3566075.56     10592969.34      3566174.46     10594275.90
#Sta/Elev= 30
  4432.2  432.47  4483.2  432.66  4513.3  434.99  4533.3  433.35  4673.7  433.25
  4754.0  426.41  4784.1  425.02  4794.1  422.74  4834.2  419.38  4968.0  410.52
  4984.6  409.95  5001.7  405.91  5004.4  405.41  5007.7  405.91  5014.7  409.60
  5024.7  410.81  5054.8  410.08  5074.9  408.43  5081.0  409.20  5086.0  407.98
  5094.9  407.85  5125.0  408.35  5145.1  411.78  5194.6  410.34  5223.5  410.45
  5355.7  409.25  5415.9  410.38  5556.3  417.64  5611.7  422.86  5742.5  430.47
#Mann=6,-1,0
  4432.2    0.05       0  4968.0    0.16       0  5001.7    0.07       0
  5007.7    0.16       0  5194.6    0.05       0  5223.5    0.16       0
Bank Sta=5001.7,5007.7
Exp/Cntr=0.3,0.1

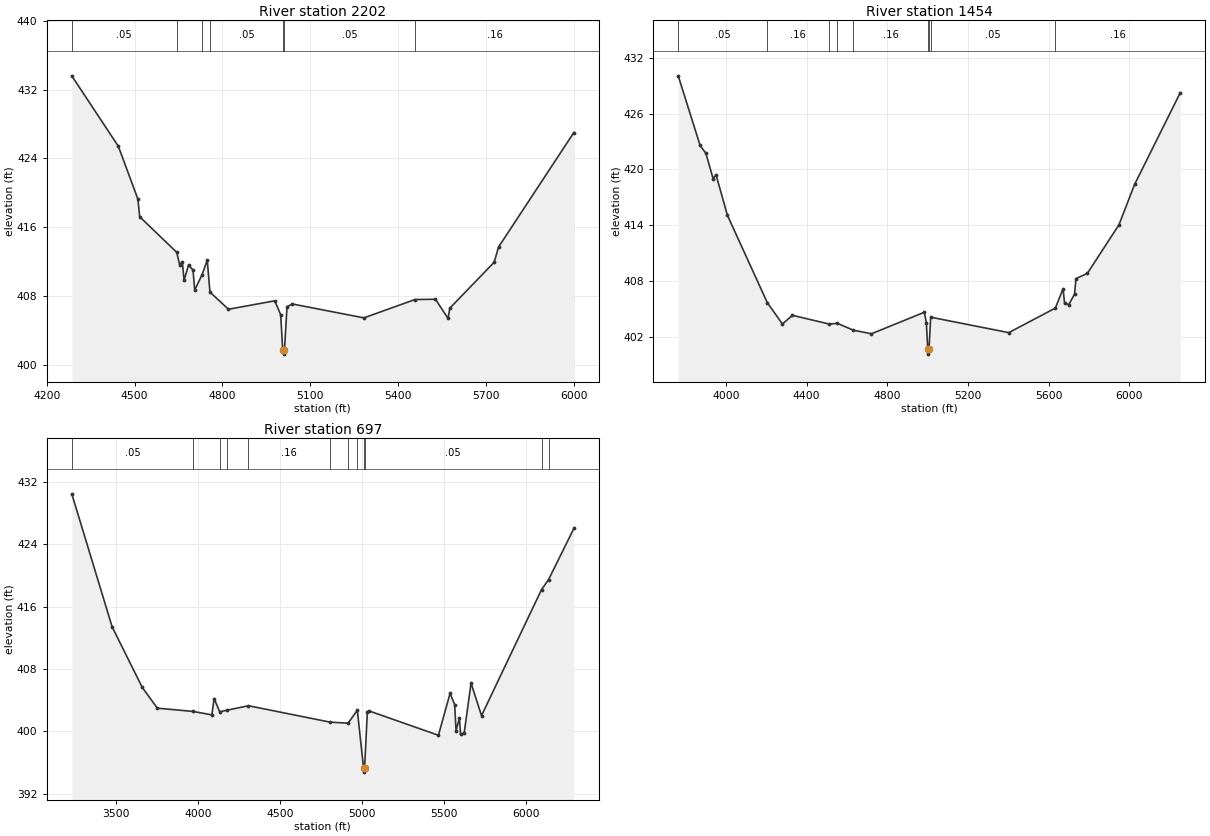
Type RM Length L Ch R = 1,2202,748,748,748
BEGIN DESCRIPTION:
UNT121 IN CCTC 3.0
END DESCRIPTION:
XS GIS Cut Line= 4
      3565789.12     10592849.54      3565471.39     10593349.57
      3565492.23     10593568.32      3566012.11     10594306.56
#Sta/Elev= 30
  4285.2  433.59  4444.3  425.41  4511.1  419.28  4517.2  417.23  4643.8  413.10
  4653.5  411.67  4662.9  411.98  4668.8  409.84  4684.0  411.62  4699.3  411.05
  4705.2  408.73  4730.4  410.50  4748.0  412.21  4757.2  408.48  4820.4  406.49
  4978.7  407.47  4998.8  405.86  5005.8  401.78  5008.6  401.28  5011.8  401.78
  5020.5  406.79  5039.0  407.10  5283.1  405.49  5457.7  407.62  5527.7  407.65
  5570.5  405.43  5576.7  406.62  5728.2  411.95  5743.0  413.71  6000.3  427.01
#Mann=7,-1,0
  4285.2    0.05       0  4643.8    0.08       0  4730.4    0.16       0
  4757.2    0.05       0  5005.8    0.03       0  5011.8    0.05       0
  5457.7    0.16       0
Bank Sta=5005.8,5011.8
Exp/Cntr=0.3,0.1

Type RM Length L Ch R = 1,1454,757,757,757
BEGIN DESCRIPTION:
UNT121 IN CCTC 2.0
END DESCRIPTION:
XS GIS Cut Line= 4
      3565627.65     10592636.02      3564955.77     10593526.65
      3564966.18     10593745.40      3565824.46     10594515.25
#Sta/Elev= 30
  3764.3  430.06  3872.5  422.59  3901.6  421.72  3937.0  419.01  3951.6  419.43
  4007.8  415.08  4205.6  405.68  4280.5  403.39  4330.4  404.32  4513.0  403.38
  4552.2  403.46  4632.4  402.72  4721.8  402.34  4983.6  404.65  4993.6  403.53
  5000.6  400.65  5003.4  400.15  5006.6  400.65  5015.1  404.12  5402.0  402.46
  5632.9  405.10  5671.1  407.18  5678.6  405.60  5699.5  405.48  5727.9  406.60
  5734.9  408.26  5791.4  408.83  5947.7  414.04  6025.4  418.39  6251.9  428.26
#Mann=9,-1,0
  3764.3    0.05       0  4205.6    0.16       0  4513.0    0.05       0
  4552.2    0.08       0  4632.4    0.16       0  5000.6    0.07       0
  5006.6    0.16       0  5015.1    0.05       0  5632.9    0.16       0
Bank Sta=5000.6,5006.6
Exp/Cntr=0.3,0.1

Type RM Length L Ch R = 1,697,0,0,0
BEGIN DESCRIPTION:
UNT121 IN CCTC 1.0
END DESCRIPTION:
XS GIS Cut Line= 4
      3565528.66     10592511.05      3564372.43     10593651.65
      3564356.81     10593870.40      3565309.90     10594630.79
#Sta/Elev= 30
  3230.5  430.50  3476.7  413.43  3660.6  405.65  3752.5  402.99  3970.5  402.57
  4084.9  402.13  4099.0  404.22  4132.9  402.52  4175.1  402.72  4308.5  403.30
  4805.2  401.20  4916.4  401.06  4972.4  402.73  5010.6  395.28  5013.3  394.78
  5016.6  395.28  5033.6  402.53  5043.7  402.64  5467.1  399.51  5538.1  404.89
  5566.4  403.45  5574.4  400.12  5595.2  401.73  5602.0  399.68  5624.0  399.75
  5666.0  406.21  5730.0  402.03  6096.3  418.22  6138.9  419.49  6293.2  426.05
#Mann=12,-1,0
  3230.5    0.05       0  3970.5     0.1       0  4132.9    0.15       0
  4175.1     0.1       0  4308.5    0.16       0  4805.2    0.05       0
  4916.4    0.16       0  4972.4    0.05       0  5010.6    0.03       0
  5016.6    0.05       0  6096.3    0.12       0  6138.9    0.16       0
Bank Sta=5010.6,5016.6
Exp/Cntr=0.3,0.1

Chan Stop Cuts=-1