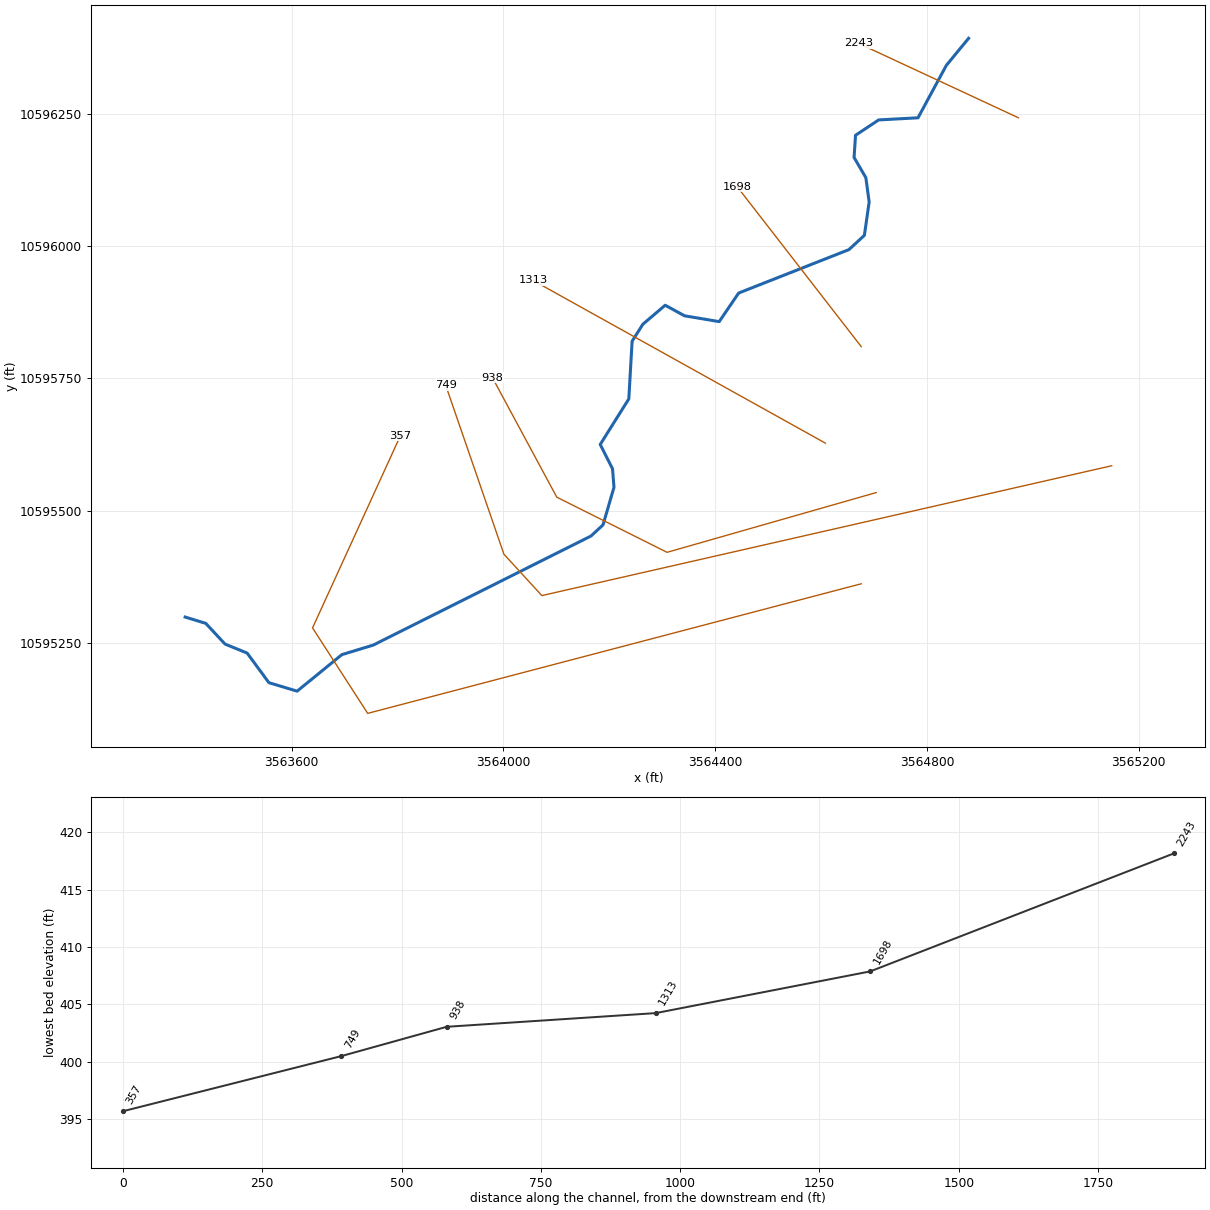
--- UNT124 IN CCTC.prj (project) ---

Proj Title=UNT124 IN CCTC Base Level Engineering
Current Plan=p01
Default Exp/Contr=0.3,0.1
English Units
Geom File=g01
Flow File=f01
Plan File=p01
Y Axis Title=Elevation
X Axis Title(PF)=Main Channel Distance
X Axis Title(XS)=Station
BEGIN DESCRIPTION:
UNT124 IN CCTC
END DESCRIPTION:
DSS Export Rating Curves= 0
DSS Export Rating Curve Sorted= 0
DSS Export Volume Flow Curves= 0
DXF OffsetX= 0
DXF OffsetY= 0
DXF ScaleX= 1
DXF ScaleY= 10

--- UNT124 IN CCTC.p01 (plan) ---

Plan Title=Multiple Run
Short Identifier=Multiple
Geom File=g01
Flow File=f01
Subcritical Flow
K Sum by GR= 0
Std Step Tol= 0.01
Critical Tol= 0.01
Num of Std Step Trials= 20
Max Error Tol= 0.3
Flow Tol Ratio= 0.001
Split Flow NTrial= 30
Split Flow Tol= 0.02
Split Flow Ratio= 0.02
Log Output Level= 0
Friction Slope Method= 1
Unsteady Friction Slope Method= 2
Unsteady Bridges Friction Slope Method= 1
Parabolic Critical Depth
Global Vel Dist=  1 , 1 , 1
Global Log Level= 0
CheckData=True
Encroach Param= -1, 0, 0, 0
BEGIN DESCRIPTION:
Multiple Run
END DESCRIPTION:

--- UNT124 IN CCTC.f01 (steady flow) ---

Flow Title=Multiple
Number of Profiles=7
Profile Names=10-year,25-year,50-year,1pct_min,100-year,1pct_plu,500-year
River Rch & RM= UNT124 IN CCTC,Reach-1,2243
     576     751     889     770    1042    1409    1423
Boundary for River Rch & Prof#=UNT124 IN CCTC,Reach-1,1
Up Type=0
Dn Type=3
Dn Slope=0.005
Boundary for River Rch & Prof#=UNT124 IN CCTC,Reach-1,2
Up Type=0
Dn Type=3
Dn Slope=0.005
Boundary for River Rch & Prof#=UNT124 IN CCTC,Reach-1,3
Up Type=0
Dn Type=3
Dn Slope=0.005
Boundary for River Rch & Prof#=UNT124 IN CCTC,Reach-1,4
Up Type=0
Dn Type=3
Dn Slope=0.005
Boundary for River Rch & Prof#=UNT124 IN CCTC,Reach-1,5
Up Type=0
Dn Type=3
Dn Slope=0.005
Boundary for River Rch & Prof#=UNT124 IN CCTC,Reach-1,6
Up Type=0
Dn Type=3
Dn Slope=0.005
Boundary for River Rch & Prof#=UNT124 IN CCTC,Reach-1,7
Up Type=0
Dn Type=3
Dn Slope=0.005

--- UNT124 IN CCTC.g01 (geometry) ---

Geom Title=Existing Conditions
Program Version=4.10

River Reach=UNT124 IN CCTC  ,Reach-1
Reach XY= 30
      3564878.54     10596392.11       3564836.5       10596341.
        3564783.       10596242.      3564708.75       10596238.
        3564665.       10596209.      3564662.25       10596167.
       3564684.5       10596129.      3564690.75       10596083.
      3564681.75       10596020.       3564652.5       10595993.
      3564444.25       10595911.       3564407.5       10595857.
        3564342.       10595868.       3564305.5       10595888.
      3564263.25       10595852.        3564243.       10595820.
      3564236.75       10595711.      3564182.75       10595625.
        3564206.       10595579.      3564208.75       10595544.
        3564188.       10595473.      3564165.25       10595452.
        3563754.       10595246.      3563694.75       10595228.
      3563610.25       10595159.        3563557.       10595175.
      3563515.75       10595231.        3563474.       10595248.
      3563437.75       10595287.      3563398.75       10595299.

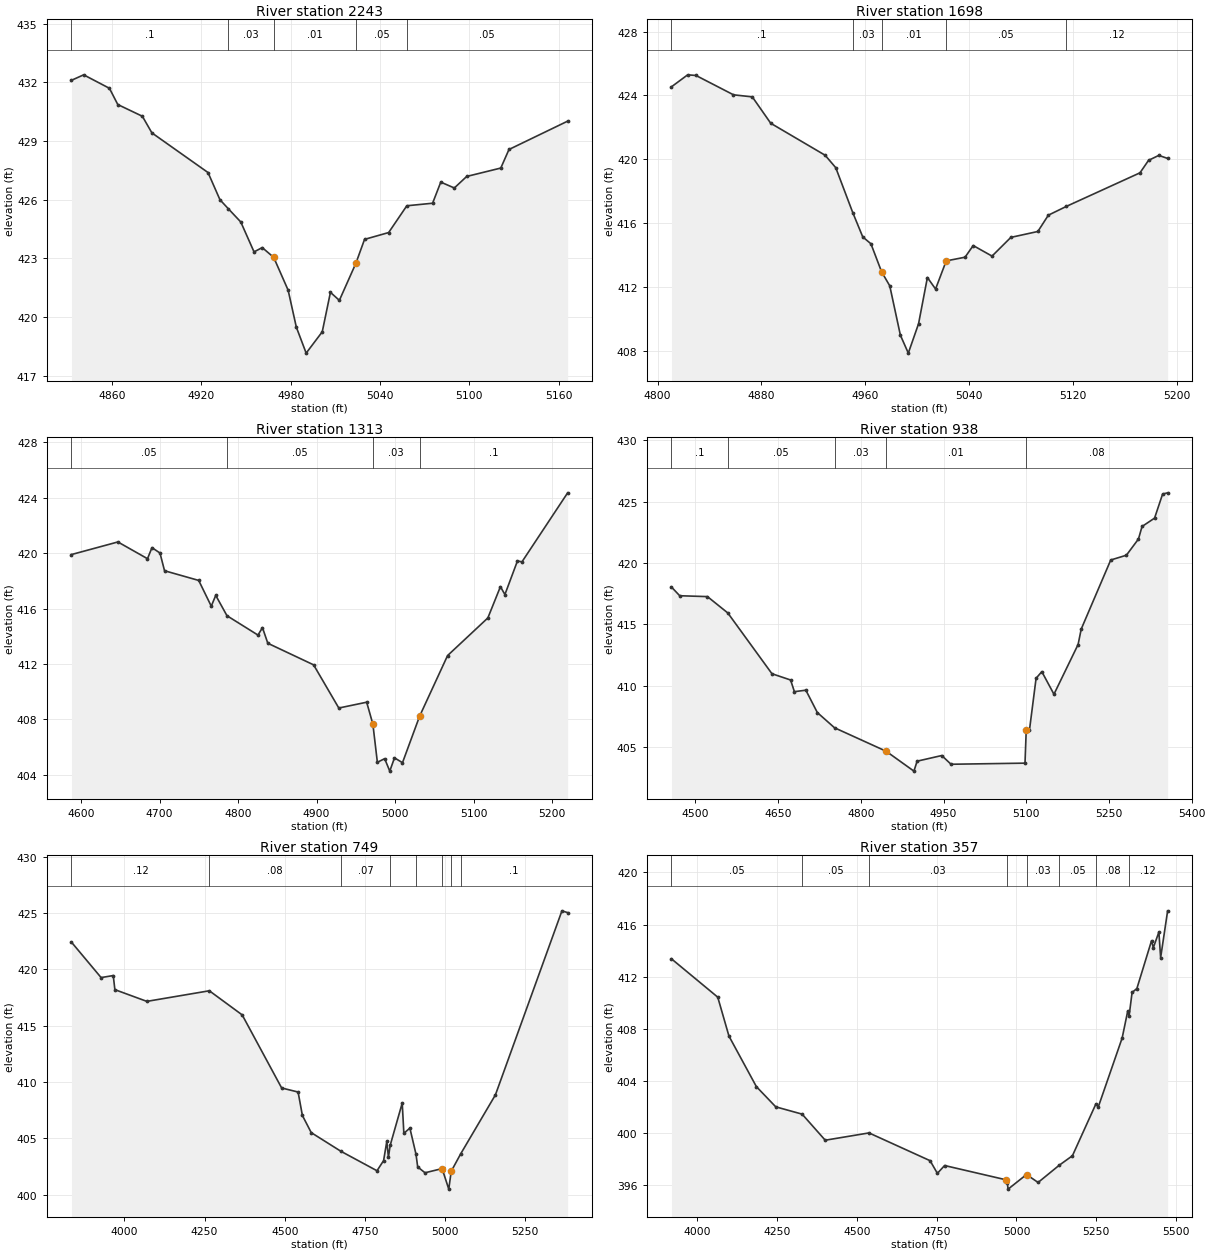
Type RM Length L Ch R = 1 ,2243    ,545,545,545
BEGIN DESCRIPTION:
UNT124 IN CCTC 4.0
END DESCRIPTION:
XS GIS Cut Line= 2
      3564972.73     10596242.02      3564670.65     10596382.65
#Sta/Elev= 30
  4832.8  432.11    4841  432.39  4858.3   431.7  4863.9  430.87  4880.4  430.27
  4886.8  429.42  4924.5  427.39  4932.5     426  4938.1  425.54  4946.5  424.86
  4955.4  423.33  4960.9  423.55  4968.6  423.05  4978.3  421.37  4983.8  419.48
  4990.4  418.15  5001.2  419.24  5006.7  421.26  5012.7  420.85  5023.8  422.75
  5029.6  423.97  5045.8  424.32    5058  425.69  5075.3  425.82  5080.8   426.9
  5089.9   426.6  5098.2  427.19  5121.1  427.62  5126.6  428.57    5166  430.02
#Mann= 5 ,-1 , 0
  4832.8      .1       0  4938.1     .03       0  4968.6     .01       0
  5023.8     .05       0    5058     .05       0
Bank Sta=4968.6,5023.8
XS Rating Curve= 0 ,0
Exp/Cntr=0.3,0.1

Type RM Length L Ch R = 1 ,1698    ,385,385,385
BEGIN DESCRIPTION:
Mapping XS 5ba80fa1
END DESCRIPTION:
XS GIS Cut Line= 2
      3564675.79     10595809.78      3564441.44     10596111.83
#Sta/Elev= 30
  4810.7  424.54  4823.2  425.29  4829.6  425.25  4858.5  424.04    4873  423.91
  4887.2  422.26  4929.1  420.26  4937.3  419.48  4950.4  416.67  4958.1  415.15
  4964.4  414.72  4972.6  412.97  4978.9  412.09  4987.1     409  4993.2  407.88
  5001.1  409.72  5007.9  412.61  5014.2  411.89  5022.4  413.65  5036.9  413.88
  5043.2  414.61  5057.7  413.95  5072.2  415.12    5093  415.49  5101.1  416.51
    5115  417.06  5171.7  419.16  5178.3  419.94  5186.2  420.25    5193  420.06
#Mann= 5 ,-1 , 0
  4810.7      .1       0  4950.4     .03       0  4972.6     .01       0
  5022.4     .05       0    5115     .12       0
Bank Sta=4972.6,5022.4
XS Rating Curve= 0 ,0
Exp/Cntr=0.3,0.1

Type RM Length L Ch R = 1 ,1313    ,375,375,375
BEGIN DESCRIPTION:
UNT124 IN CCTC 3.0
END DESCRIPTION:
XS GIS Cut Line= 2
      3564608.08     10595627.48      3564056.03     10595934.75
#Sta/Elev= 30
  4587.9   419.9    4647  420.81  4684.7   419.6  4690.4   420.4  4700.6  420.01
  4706.4  418.73  4749.9  418.03  4765.9  416.17  4771.6  416.95  4785.9  415.48
  4825.4  414.08  4831.1  414.62  4837.9  413.49  4896.2  411.93  4928.3  408.81
  4963.8  409.23  4971.7  407.64  4977.4  404.89  4986.7  405.15  4993.2  404.25
  4999.2  405.21  5009.4  404.86  5031.2  408.22  5066.8   412.6  5118.1  415.32
  5134.1  417.58  5139.8  417.01  5155.8  419.44  5161.5  419.37  5219.7  424.36
#Mann= 4 ,-1 , 0
  4587.9     .05       0  4785.9     .05       0  4971.7     .03       0
  5031.2      .1       0
Bank Sta=4971.7,5031.2
XS Rating Curve= 0 ,0
Exp/Cntr=0.3,0.1

Type RM Length L Ch R = 1 ,938     ,189,189,189
BEGIN DESCRIPTION:
UNT124 IN CCTC 2.0
END DESCRIPTION:
XS GIS Cut Line= 4
        3564704.     10595534.09      3564309.03     10595421.24
       3564100.7      10595525.4      3563979.19     10595751.07
#Sta/Elev= 30
  4456.4  418.05  4471.4  417.34  4521.7  417.27  4558.6  415.94  4638.7  410.99
  4672.5  410.48  4679.4  409.53  4700.2  409.65    4721  407.83  4752.2  406.59
  4845.8  404.68  4896.2  403.06    4902  403.87  4946.7  404.33  4963.5  403.62
  5097.7  403.71  5099.9  406.37  5105.7  406.37  5117.8  410.62  5128.2  411.16
  5150.2  409.32    5194  413.37  5199.7  414.63  5253.2  420.25  5281.6  420.64
  5303.5  421.96    5310  422.98  5332.7  423.66  5347.3  425.62  5356.4  425.72
#Mann= 5 ,-1 , 0
  4456.4      .1       0  4558.6     .05       0  4752.2     .03       0
  4845.8     .01       0  5099.9     .08       0
Bank Sta=4845.8,5099.9
XS Rating Curve= 0 ,0
Exp/Cntr=0.3,0.1

Type RM Length L Ch R = 1 ,749     ,392,392,392
BEGIN DESCRIPTION:
Mapping XS 5d9bdd78
END DESCRIPTION:
XS GIS Cut Line= 4
      3565148.84     10595584.75      3564072.49     10595339.53
      3564000.88     10595417.66      3563890.83     10595737.02
#Sta/Elev= 30
  3834.7  422.41  3927.1  419.27    3965  419.45  3970.1   418.2  4069.8  417.16
  4264.7   418.1  4367.2  415.96  4490.3  409.48  4541.6  409.12    4555  407.04
  4582.6  405.52  4674.9  403.87  4787.7  402.14  4808.3  403.04  4818.3  404.75
  4823.4  403.34  4828.8  404.39  4866.4  408.14  4871.5  405.46  4890.3  405.92
  4909.4   403.6  4914.6  402.48  4937.5  401.96  4990.8  402.33  5011.6  400.51
  5019.2  402.09  5048.6  403.63  5157.1  408.87  5364.6  425.19  5382.4  425.03
#Mann= 8 ,-1 , 0
  3834.7     .12       0  4264.7     .08       0  4674.9     .07       0
  4828.8     .05       0  4909.4     .03       0  4990.8     .01       0
  5019.2     .03       0  5048.6      .1       0
Bank Sta=4990.8,5019.2
XS Rating Curve= 0 ,0
Exp/Cntr=0.3,0.1

Type RM Length L Ch R = 1 ,357     ,0,0,0
BEGIN DESCRIPTION:
UNT124 IN CCTC 1.0
END DESCRIPTION:
XS GIS Cut Line= 4
       3564675.8     10595361.82      3563743.53     10595117.04
      3563639.36      10595278.5      3563805.33     10595641.55
#Sta/Elev= 30
  3918.6  413.37  4063.7  410.43  4098.9  407.44  4184.8  403.57  4245.5  402.02
  4328.2  401.46  4400.6  399.46  4537.8  400.02  4729.3  397.89  4752.1  396.92
  4774.8  397.52  4968.1  396.42  4971.1  396.21  4973.8  395.71  5031.5  396.83
  5067.8  396.22  5133.4  397.53  5175.4  398.27  5249.1  402.25  5256.7  402.03
  5331.3   407.3  5348.8  409.37  5353.1     409  5362.4  410.79  5377.4  411.09
  5423.4  414.76  5428.9  414.22  5446.4  415.42  5451.9  413.46  5473.8  417.05
#Mann= 8 ,-1 , 0
  3918.6     .05       0  4328.2     .05       0  4537.8     .03       0
  4971.1     .01       0  5031.5     .03       0  5133.4     .05       0
  5249.1     .08       0  5353.1     .12       0
Bank Sta=4968.1,5031.5
XS Rating Curve= 0 ,0
Exp/Cntr=0.3,0.1

Chan Stop Cuts=-1
Use User Specified Reach Order=0
Composite Channel Slope=5