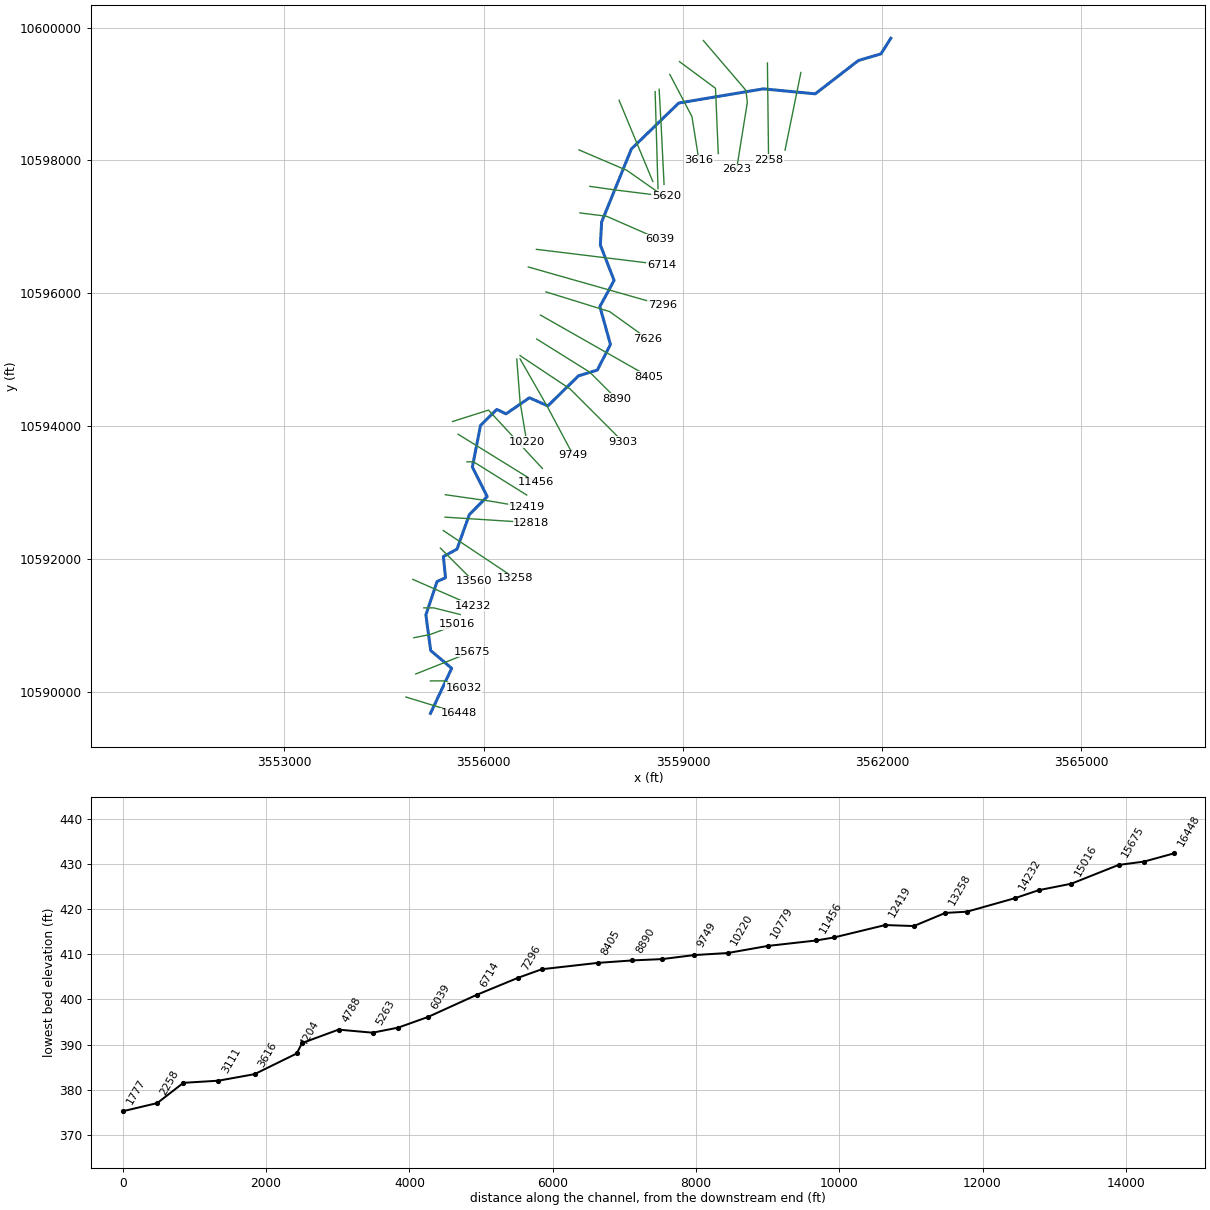
--- UNT125 IN CCTC.prj (project) ---

Proj Title=UNT125 IN CCTC Base Level Engineering
Current Plan=p01
Default Exp/Contr=0.3,0.1
English Units
Geom File=g01
Flow File=f01
Plan File=p01
Y Axis Title=Elevation
X Axis Title(PF)=Main Channel Distance
X Axis Title(XS)=Station
BEGIN DESCRIPTION:
UNT125 IN CCTC
END DESCRIPTION:
DSS Export Rating Curves= 0
DSS Export Rating Curve Sorted= 0
DSS Export Volume Flow Curves= 0
DXF OffsetX= 0
DXF OffsetY= 0
DXF ScaleX= 1
DXF ScaleY= 10

--- UNT125 IN CCTC.p01 (plan) ---

Plan Title=Multiple Run
Short Identifier=Multiple
Geom File=g01
Flow File=f01
Subcritical Flow
K Sum by GR= 0
Std Step Tol= 0.01
Critical Tol= 0.01
Num of Std Step Trials= 20
Max Error Tol= 0.3
Flow Tol Ratio= 0.001
Split Flow NTrial= 30
Split Flow Tol= 0.02
Split Flow Ratio= 0.02
Log Output Level= 0
Friction Slope Method= 1
Unsteady Friction Slope Method= 2
Unsteady Bridges Friction Slope Method= 1
Parabolic Critical Depth
Global Vel Dist=  1 , 1 , 1
Global Log Level= 0
CheckData=True
Encroach Param= -1, 0, 0, 0
BEGIN DESCRIPTION:
Multiple Run
END DESCRIPTION:

--- UNT125 IN CCTC.f01 (steady flow) ---

Flow Title=Multiple
Number of Profiles=7
Profile Names=10-year,25-year,50-year,1pct_min,100-year,1pct_plu,500-year
River Rch & RM= UNT125 IN CCTC,Reach-1,16448
    1341    1834    2237    1991    2692    3641    3887
River Rch & RM= UNT125 IN CCTC,Reach-1,10779
    2400    3386    4219    3828    5177    7001    7774
River Rch & RM= UNT125 IN CCTC,Reach-1,9749
    2977    4237    5311    4842    6549    8856    9935
River Rch & RM= UNT125 IN CCTC,Reach-1,4279
    3435    4919    6191    5666    7662   10362   11711
Boundary for River Rch & Prof#=UNT125 IN CCTC,Reach-1,1
Up Type=0
Dn Type=3
Dn Slope=0.005
Boundary for River Rch & Prof#=UNT125 IN CCTC,Reach-1,2
Up Type=0
Dn Type=3
Dn Slope=0.005
Boundary for River Rch & Prof#=UNT125 IN CCTC,Reach-1,3
Up Type=0
Dn Type=3
Dn Slope=0.005
Boundary for River Rch & Prof#=UNT125 IN CCTC,Reach-1,4
Up Type=0
Dn Type=3
Dn Slope=0.005
Boundary for River Rch & Prof#=UNT125 IN CCTC,Reach-1,5
Up Type=0
Dn Type=3
Dn Slope=0.005
Boundary for River Rch & Prof#=UNT125 IN CCTC,Reach-1,6
Up Type=0
Dn Type=3
Dn Slope=0.005
Boundary for River Rch & Prof#=UNT125 IN CCTC,Reach-1,7
Up Type=0
Dn Type=3
Dn Slope=0.005

--- UNT125 IN CCTC.g01 (geometry) ---

Geom Title=Existing Conditions
Program Version=4.10

River Reach=UNT125 IN CCTC  ,Reach-1
Reach XY= 30
      3555200.25       10589671.       3555519.5       10590350.
      3555203.75       10590618.       3555131.5       10591155.
      3555299.25       10591656.      3555426.75       10591715.
      3555394.75       10592033.       3555599.5       10592145.
        3555786.       10592666.        3556055.       10592937.
        3555831.       10593381.      3555953.75       10594009.
       3556198.5       10594250.        3556338.       10594183.
       3556689.5       10594425.        3556968.       10594303.
        3557427.       10594755.      3557712.25       10594843.
      3557909.75       10595228.       3557750.5       10595800.
       3557964.5       10596193.      3557757.75       10596726.
        3557777.       10597074.       3558224.5       10598173.
        3558937.       10598865.        3560210.       10599079.
      3560992.75       10599004.      3561642.25       10599506.
      3561981.75       10599606.       3562129.5       10599840.

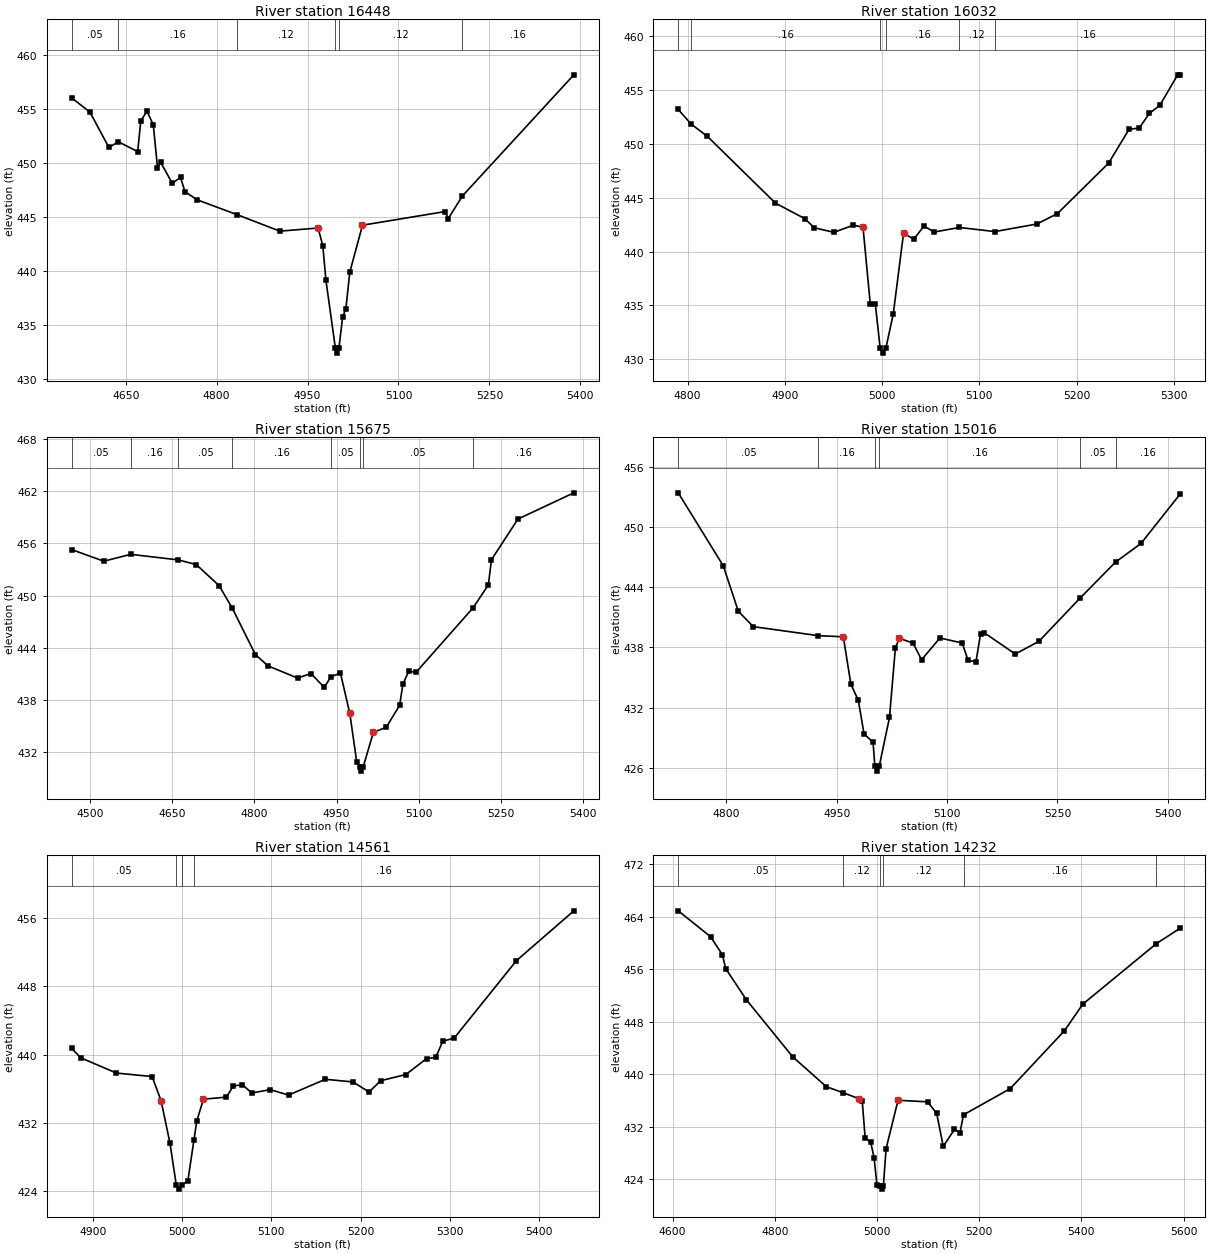
Type RM Length L Ch R = 1 ,16448   ,416,416,416
BEGIN DESCRIPTION:
UNT125 IN CCTC 32.0
END DESCRIPTION:
XS GIS Cut Line= 2
      3554831.01     10589917.08      3555623.06      10589674.7
#Sta/Elev= 30
    4561  456.02  4590.9  454.71  4622.3  451.43  4637.7  451.96  4669.7  451.05
  4674.9  453.89    4685  454.79  4695.5  453.53  4702.4  449.57  4707.7  450.05
  4726.9  448.11  4740.4  448.66  4747.8  447.33    4768  446.58  4833.1  445.22
  4904.3  443.68  4967.4  443.97  4975.1  442.34  4980.3  439.13  4995.8  432.88
  4998.5  432.38  5001.8  432.88  5007.9  435.75  5013.1  436.45  5019.7  439.88
  5040.6  444.23  5176.5  445.49  5182.2  444.85  5205.5  446.94  5389.3  458.16
#Mann= 6 ,-1 , 0
    4561     .05       0  4637.7     .16       0  4833.1     .12       0
  4995.8     .07       0  5001.8     .12       0  5205.5     .16       0
Bank Sta=4967.4,5040.6
XS Rating Curve= 0 ,0
Exp/Cntr=0.3,0.1

Type RM Length L Ch R = 1 ,16032   ,357,357,357
BEGIN DESCRIPTION:
UNT125 IN CCTC 31.0
END DESCRIPTION:
XS GIS Cut Line= 3
      3555199.58     10590160.19      3555399.61     10590160.19
      3555699.65     10590060.17
#Sta/Elev= 30
  4790.4   453.2  4803.9  451.83  4820.4   450.7  4890.4   444.5  4920.4  443.07
  4930.4  442.21  4950.4  441.79  4970.4  442.45  4980.4  442.27  4987.9  435.11
  4993.1  435.11    4998  431.07  5000.7  430.57    5004  431.07  5011.5  434.19
  5022.1  441.71  5032.6  441.15  5043.1  442.37  5053.7  441.82  5079.6  442.24
    5116  441.86  5159.1  442.56  5180.2  443.52  5232.9  448.21    5254  451.36
  5264.5  451.48    5275  452.85  5285.6  453.58    5304  456.42  5306.7  456.42
#Mann= 6 ,-1 , 0
  4790.4     .05       0  4803.9     .16       0    4998     .07       0
    5004     .16       0  5079.6     .12       0    5116     .16       0
Bank Sta=4980.4,5022.1
XS Rating Curve= 0 ,0
Exp/Cntr=0.3,0.1

Type RM Length L Ch R = 1 ,15675   ,659,659,659
BEGIN DESCRIPTION:
UNT125 IN CCTC 30.0
END DESCRIPTION:
XS GIS Cut Line= 2
      3554978.58      10590264.3      3555829.29     10590602.84
#Sta/Elev= 30
  4467.2  455.28  4525.6  453.95  4574.6  454.74  4661.6   454.1  4694.3  453.56
    4736  451.13    4760  448.54    4802  443.22    4825  441.92    4879  440.52
  4903.3  441.04  4927.6  439.45    4940  440.68  4957.2  441.08  4974.2  436.46
  4986.9  430.86  4992.7  430.32  4995.4  429.82  4998.7  430.32  5017.2  434.27
  5040.8  434.87  5065.1  437.39    5071   439.8  5081.8  441.32  5094.8  441.16
  5199.4  448.62    5227  451.24  5232.5  454.12  5280.9   458.8  5382.8  461.81
#Mann= 8 ,-1 , 0
  4467.2     .05       0  4574.6     .16       0  4661.6     .05       0
    4760     .16       0    4940     .05       0  4992.7     .03       0
  4998.7     .05       0  5199.4     .16       0
Bank Sta=4974.2,5017.2
XS Rating Curve= 0 ,0
Exp/Cntr=0.3,0.1

Type RM Length L Ch R = 1 ,15016   ,455,455,455
BEGIN DESCRIPTION:
UNT125 IN CCTC 29.0
END DESCRIPTION:
XS GIS Cut Line= 3
      3554949.62     10590810.19      3555199.61     10590860.19
      3555599.57     10591010.17
#Sta/Elev= 30
  4734.8  453.42    4796  446.14  4816.4  441.61  4836.8  440.07  4925.3  439.17
  4959.1  439.06  4969.3  434.34  4979.5  432.71  4987.2  429.37  4999.5  428.55
  5001.9  426.16  5004.6  425.66  5007.9  426.16  5021.8  431.01  5029.8  437.95
  5035.1  438.91  5053.8  438.43  5065.4  436.77  5090.3  438.94  5120.6  438.44
  5128.6   436.7  5139.3  436.57  5145.5  439.34  5150.8  439.45  5192.7  437.34
  5224.7   438.6  5280.6  442.91  5328.9  446.51  5363.5  448.37  5416.9  453.32
#Mann= 6 ,-1 , 0
  4734.8     .05       0  4925.3     .16       0  5001.9     .07       0
  5007.9     .16       0  5280.6     .05       0  5328.9     .16       0
Bank Sta=4959.1,5035.1
XS Rating Curve= 0 ,0
Exp/Cntr=0.3,0.1

Type RM Length L Ch R = 1 ,14561   ,329,329,329
BEGIN DESCRIPTION:
UNT125 IN CCTC 28.0
END DESCRIPTION:
XS GIS Cut Line= 3
      3555099.59     10591260.19      3555249.61     10591260.19
      3555649.58     10591160.19
#Sta/Elev= 30
  4876.4  440.71  4886.4  439.62  4926.4  437.83  4966.4  437.42  4976.4  434.59
  4986.4  429.62  4993.4  424.73  4996.2  424.23  4999.4  424.73  5006.4  425.18
  5013.3  430.04  5016.4  432.22  5023.9  434.77  5049.6  435.01  5057.3  436.32
  5067.6  436.46    5078  435.49  5098.6  435.89  5119.2  435.25  5160.4   437.1
  5191.3  436.79  5209.4  435.61  5222.3  436.93  5250.6  437.66  5273.8  439.53
  5284.1  439.66  5291.8  441.56  5304.7  441.93  5374.3  450.99  5438.7  456.84
#Mann= 4 ,-1 , 0
  4876.4     .05       0  4993.4     .03       0  4999.4     .05       0
  5013.3     .16       0
Bank Sta=4976.4,5023.9
XS Rating Curve= 0 ,0
Exp/Cntr=0.3,0.1

Type RM Length L Ch R = 1 ,14232   ,672,672,672
BEGIN DESCRIPTION:
UNT125 IN CCTC 27.0
END DESCRIPTION:
XS GIS Cut Line= 2
      3554934.64     10591689.63      3555834.44      10591295.1
#Sta/Elev= 30
  4611.1  464.92  4674.3  460.98  4697.6  458.21  4703.9  456.12  4744.4  451.36
  4834.9  442.67    4901  438.09  4933.7  437.18  4965.6  436.24  4971.1  435.97
  4976.9  430.25  4987.8  429.61  4994.5  427.19  4999.9  423.13  5006.6  422.97
  5009.4  422.47  5012.6  422.97  5017.8  428.63  5041.2  436.02  5098.9  435.79
  5116.8  434.03  5129.7     429  5151.6  431.57  5162.5   431.1  5169.4  433.81
  5260.8   437.8  5366.9  446.63  5402.7  450.68  5546.9  459.93  5593.6  462.28
#Mann= 6 ,-1 , 0
  4611.1     .05       0  4933.7     .12       0  5006.6     .07       0
  5012.6     .12       0  5169.4     .16       0  5546.9     .12       0
Bank Sta=4965.6,5041.2
XS Rating Curve= 0 ,0
Exp/Cntr=0.3,0.1

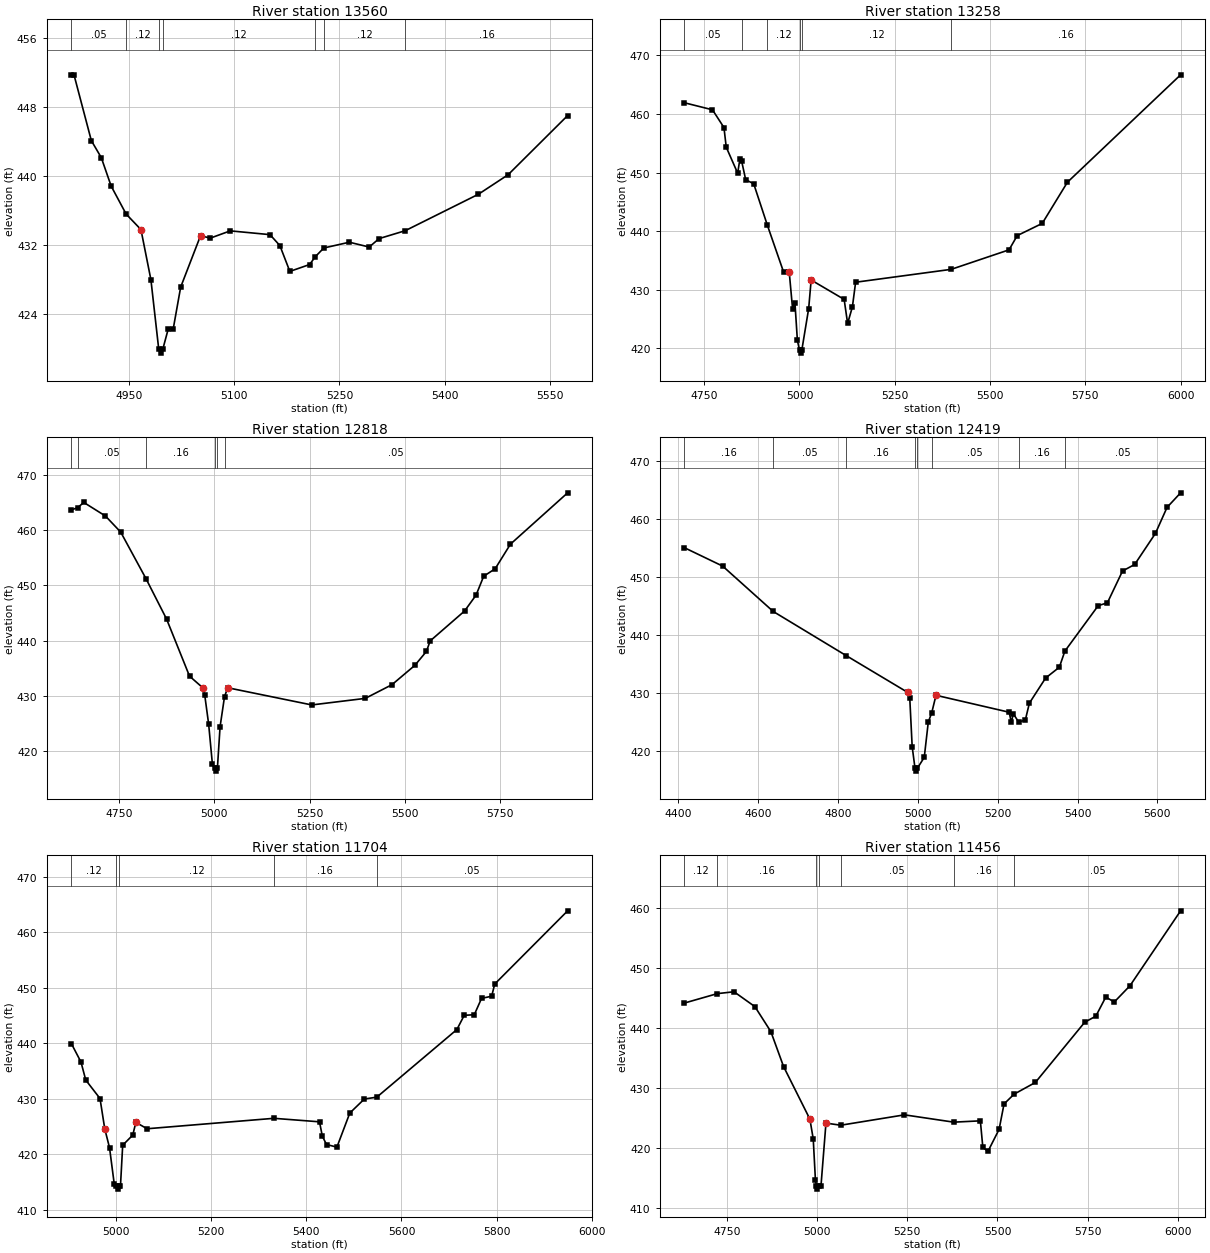
Type RM Length L Ch R = 1 ,13560   ,302,302,302
BEGIN DESCRIPTION:
UNT125 IN CCTC 26.0
END DESCRIPTION:
XS GIS Cut Line= 3
      3555349.59     10592160.21      3555449.61     10592060.19
      3555849.58     10591660.21
#Sta/Elev= 30
  4868.2  451.78  4871.8  451.78  4896.5  444.14  4910.7  442.16  4924.8  438.85
  4946.1  435.61  4967.2  433.81  4981.4  427.99  4992.5  419.96  4995.3  419.46
  4998.5  419.96  5006.1  422.27  5013.2  422.27  5023.8  427.12  5052.1  433.09
  5066.2  432.82  5094.5  433.66  5151.1  433.22  5165.2  431.95  5179.4  428.95
  5207.6  429.75  5215.7  430.66  5227.8  431.67  5264.2  432.34  5292.5  431.78
  5306.6  432.76  5343.9  433.68  5448.1  437.91  5490.5  440.18  5575.3  447.05
#Mann= 7 ,-1 , 0
  4868.2     .05       0  4946.1     .12       0  4992.5     .07       0
  4998.5     .12       0  5215.7     .16       0  5227.8     .12       0
  5343.9     .16       0
Bank Sta=4967.2,5052.1
XS Rating Curve= 0 ,0
Exp/Cntr=0.3,0.1

Type RM Length L Ch R = 1 ,13258   ,440,440,440
BEGIN DESCRIPTION:
UNT125 IN CCTC 25.0
END DESCRIPTION:
XS GIS Cut Line= 2
      3555392.95     10592425.74      3556476.28     10591703.52
#Sta/Elev= 30
  4698.1  461.92  4771.7  460.72  4801.8  457.69  4807.8  454.34  4837.8   449.9
  4843.8   452.4  4848.1  451.99  4858.8  448.79  4879.9  448.09  4915.7  441.02
  4958.5  432.99    4973  433.08    4982  426.65    4988  427.83  4994.5  421.35
  5000.1  419.69  5002.8  419.19  5006.1  419.69  5024.1   426.8  5030.6  431.67
  5117.2  428.36  5126.3  424.25  5138.8  427.08  5147.3  431.29  5398.1  433.49
  5549.9  436.82  5571.4  439.25    5637  441.33  5703.1  448.36  6000.1  466.69
#Mann= 6 ,-1 , 0
  4698.1     .05       0  4848.1     .16       0  4915.7     .12       0
  5000.1     .07       0  5006.1     .12       0  5398.1     .16       0
Bank Sta=4973,5030.6
XS Rating Curve= 0 ,0
Exp/Cntr=0.3,0.1

Type RM Length L Ch R = 1 ,12818   ,399,399,399
BEGIN DESCRIPTION:
UNT125 IN CCTC 24.0
END DESCRIPTION:
XS GIS Cut Line= 2
      3555420.69     10592627.14      3556719.32     10592543.81
#Sta/Elev= 30
  4625.1  463.72  4641.7  464.14  4657.3  465.08  4714.2  462.61  4754.3  459.68
  4820.4  451.25  4874.5   443.9  4934.7  433.53  4968.8  431.46  4974.7  430.04
  4984.8  424.86  4994.8  417.49  5001.8  416.78  5004.5  416.28  5007.8  416.78
  5014.8  424.32  5026.5  429.81  5034.9  431.42  5255.3   428.3  5395.6  429.49
  5465.7  431.98  5525.9   435.5  5555.9  438.01  5565.9  439.93  5656.1  445.36
  5686.2  448.24  5706.2  451.67  5736.3  453.03  5776.4   457.5  5926.4  466.82
#Mann= 6 ,-1 , 0
  4625.1     .16       0  4641.7     .05       0  4820.4     .16       0
  5001.8     .07       0  5007.8     .16       0  5026.5     .05       0
Bank Sta=4968.8,5034.9
XS Rating Curve= 0 ,0
Exp/Cntr=0.3,0.1

Type RM Length L Ch R = 1 ,12419   ,715,715,715
BEGIN DESCRIPTION:
UNT125 IN CCTC 23.0
END DESCRIPTION:
XS GIS Cut Line= 3
      3555424.75     10592964.92       3556093.2     10592869.42
      3556653.08     10592773.94
#Sta/Elev= 30
  4414.9     455  4510.7  451.83  4637.2  444.02  4819.9  436.42  4974.5  430.06
  4979.5  429.06  4985.5  420.73  4992.6     417  4995.3   416.5  4998.6     417
  5015.8  418.88  5025.9  424.97  5034.4  426.53  5045.2  429.57  5228.5  426.65
  5233.9  424.91    5239  426.38  5252.5  424.94  5269.1  425.33  5279.2  428.22
  5319.8  432.54  5354.3  434.41  5368.1  437.18  5451.7  445.02  5474.6   445.5
  5512.6  450.99    5543  452.11    5595  457.47  5624.1  461.95  5658.1  464.46
#Mann= 8 ,-1 , 0
  4414.9     .16       0  4637.2     .05       0  4819.9     .16       0
  4992.6     .07       0  4998.6     .16       0  5034.4     .05       0
  5252.5     .16       0  5368.1     .05       0
Bank Sta=4974.5,5045.2
XS Rating Curve= 0 ,0
Exp/Cntr=0.3,0.1

Type RM Length L Ch R = 1 ,11704   ,248,248,248
BEGIN DESCRIPTION:
UNT125 IN CCTC 22.0
END DESCRIPTION:
XS GIS Cut Line= 3
      3555749.58     10593460.19      3555849.61     10593460.19
      3556649.59      10592960.2
#Sta/Elev= 30
    4906  439.94    4926  436.65    4936  433.41    4966  430.08    4976  424.61
    4986  421.22    4996  414.64  5000.5  414.25  5003.3  413.75  5006.5  414.25
    5009  414.25  5013.7  421.66  5034.9  423.49  5041.4  425.78    5065  424.63
  5331.7  426.51  5427.6  425.88  5433.5   423.3  5442.3  421.79  5464.2  421.32
  5491.3  427.46  5521.9  429.99  5548.1  430.32  5716.5  442.51  5731.9  445.07
  5753.1  445.18  5768.4  448.13  5789.6  448.51  5796.1  450.71  5949.4   463.9
#Mann= 5 ,-1 , 0
    4906     .12       0  5000.5     .07       0  5006.5     .12       0
  5331.7     .16       0  5548.1     .05       0
Bank Sta=4976,5041.4
XS Rating Curve= 0 ,0
Exp/Cntr=0.3,0.1

Type RM Length L Ch R = 1 ,11456   ,677,677,677
BEGIN DESCRIPTION:
UNT125 IN CCTC 21.0
END DESCRIPTION:
XS GIS Cut Line= 2
      3555615.79     10593876.36      3556786.11     10593152.49
#Sta/Elev= 30
  4631.8  444.12  4723.1  445.69  4769.3     446  4827.2  443.52  4871.5  439.35
  4906.7  433.53  4979.7  424.76    4989  421.46  4995.1  414.58    4998  413.58
  5000.7  413.08    5004  413.58  5010.5  413.63  5024.3  424.09  5065.4  423.74
  5242.1  425.47  5378.7  424.25  5452.5  424.47  5459.4  420.03  5473.7  419.39
  5504.5  423.05  5518.2  427.29  5546.1  428.92    5605  430.87    5742  440.92
  5772.8  441.93  5800.4  445.12  5823.9  444.29  5867.4     447  6007.9   459.5
#Mann= 7 ,-1 , 0
  4631.8     .12       0  4723.1     .16       0    4998     .07       0
    5004     .16       0  5065.4     .05       0  5378.7     .16       0
  5546.1     .05       0
Bank Sta=4979.7,5024.3
XS Rating Curve= 0 ,0
Exp/Cntr=0.3,0.1

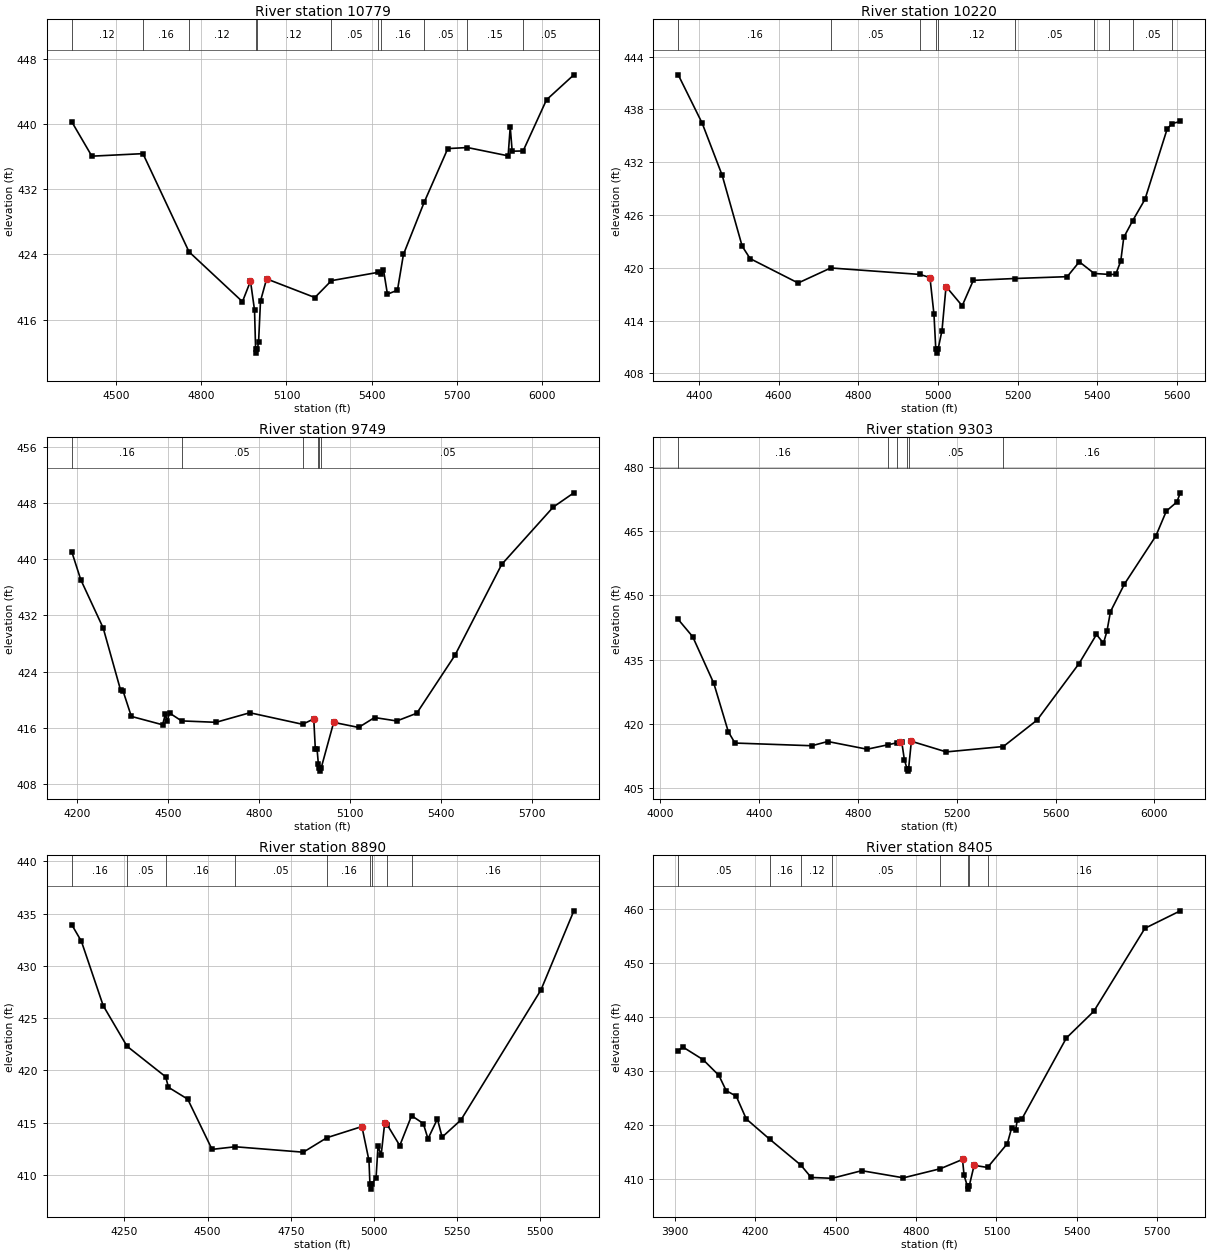
Type RM Length L Ch R = 1 ,10779   ,559,559,559
BEGIN DESCRIPTION:
UNT125 IN CCTC 20.0
END DESCRIPTION:
XS GIS Cut Line= 3
      3555532.33     10594067.43      3556073.96     10594239.29
      3556885.56     10593360.06
#Sta/Elev= 30
  4345.4  440.28    4416  436.06  4595.6  436.37  4757.6  424.31  4945.3  418.19
  4973.6  420.71  4987.8  417.16  4991.6  412.37  4994.3  411.87  4997.6  412.37
    5002   413.2  5008.8  418.27  5030.3  420.99  5199.9   418.7    5258  420.77
  5420.4  421.78  5431.6  421.58  5440.9  422.14    5455  419.11  5490.2   419.6
  5511.2  423.99    5584  430.39  5667.1  436.99  5736.3  437.12  5879.2   436.1
  5886.6  439.66  5893.4  436.67  5931.9   436.7  6014.1  442.98  6110.2  446.05
#Mann= 11 ,-1 , 0
  4345.4     .12       0  4595.6     .16       0  4757.6     .12       0
  4991.6     .07       0  4997.6     .12       0    5258     .05       0
  5420.4     .08       0  5431.6     .16       0    5584     .05       0
  5736.3     .15       0  5931.9     .05       0
Bank Sta=4973.6,5030.3
XS Rating Curve= 0 ,0
Exp/Cntr=0.3,0.1

Type RM Length L Ch R = 1 ,10220   ,471,471,471
BEGIN DESCRIPTION:
UNT125 IN CCTC 19.0
END DESCRIPTION:
XS GIS Cut Line= 3
      3556499.61     10595010.18      3556549.61     10594360.19
      3556649.61     10593760.17
#Sta/Elev= 30
  4347.9  441.93  4408.1  436.42  4458.2  430.51  4508.4  422.45  4528.4  421.04
  4648.8  418.27  4730.7  419.98  4955.3  419.24  4979.7  418.88  4989.8  414.71
  4994.3   410.8  4997.1   410.3  5000.3   410.8  5009.9  412.86  5020.1  417.87
  5060.6  415.68  5088.5  418.57  5192.2  418.78  5324.2  418.99  5354.6  420.68
    5392  419.35  5428.1  419.25  5445.9  419.24  5458.6  420.76  5466.2  423.46
  5488.5  425.35  5519.4  427.78  5575.1  435.78  5587.3  436.39  5608.1  436.63
#Mann= 10 ,-1 , 0
  4347.9     .16       0  4730.7     .05       0  4955.3     .12       0
  4994.3     .07       0  5000.3     .12       0  5192.2     .05       0
    5392     .16       0  5428.1     .08       0  5488.5     .05       0
  5587.3     .15       0
Bank Sta=4979.7,5020.1
XS Rating Curve= 0 ,0
Exp/Cntr=0.3,0.1

Type RM Length L Ch R = 1 ,9749    ,446,446,446
BEGIN DESCRIPTION:
UNT125 IN CCTC 18.0
END DESCRIPTION:
XS GIS Cut Line= 3
      3556549.59     10595010.22      3556949.61     10594310.19
      3557349.63     10593560.15
#Sta/Elev= 30
  4182.2  441.07  4211.7  437.11  4285.9  430.21  4343.5  421.33  4351.4  421.25
  4378.7  417.63  4481.7  416.44    4491  417.93  4496.8  416.95  4504.7  418.11
  4544.4  416.99    4658  416.79  4769.6  418.15  4943.4  416.51  4980.5  417.27
  4985.6  413.02  4991.3  413.02  4995.7  410.86  4999.3  410.34    5002  409.84
  5005.3  410.34  5046.2  416.78  5128.4  416.06  5181.1  417.47  5254.4  416.98
  5320.3  418.08  5446.4  426.34  5600.5  439.27  5770.5  447.43  5838.5  449.46
#Mann= 6 ,-1 , 0
  4182.2     .16       0  4544.4     .05       0  4943.4     .12       0
  4995.7     .05       0  4999.3     .03       0  5005.3     .05       0
Bank Sta=4980.5,5046.2
XS Rating Curve= 0 ,0
Exp/Cntr=0.3,0.1

Type RM Length L Ch R = 1 ,9303    ,413,413,413
BEGIN DESCRIPTION:
UNT125 IN CCTC 17.0
END DESCRIPTION:
XS GIS Cut Line= 3
      3556549.64     10595060.17      3557299.61     10594560.19
      3558099.59      10593760.2
#Sta/Elev= 30
  4072.4  444.38    4131  440.35  4216.6  429.43  4275.2  418.13  4302.2  415.51
  4613.2  414.88  4677.8  415.87    4837  414.07  4921.2   415.1  4959.3  415.59
  4970.7  415.77  4977.3  415.77  4987.9  411.62    4999  409.45  5001.8  408.95
    5005  409.45  5016.2  415.93  5157.6  413.44  5388.7   414.7  5525.3  420.88
    5695  434.07  5765.7  440.87    5794  438.82  5808.1  441.65  5822.3   446.2
  5878.8  452.64  6006.1  463.88  6048.6   469.7    6091  471.81  6105.1  473.96
#Mann= 6 ,-1 , 0
  4072.4     .16       0  4921.2     .12       0  4959.3     .05       0
    4999     .03       0    5005     .05       0  5388.7     .16       0
Bank Sta=4970.7,5016.2
XS Rating Curve= 0 ,0
Exp/Cntr=0.3,0.1

Type RM Length L Ch R = 1 ,8890    ,485,485,485
BEGIN DESCRIPTION:
UNT125 IN CCTC 16.0
END DESCRIPTION:
XS GIS Cut Line= 3
      3556799.57     10595310.21      3557599.61     10594810.19
      3557999.59     10594410.21
#Sta/Elev= 30
  4091.6  433.93  4120.5  432.35    4186   426.2  4257.6  422.32  4373.7   419.4
  4382.3  418.39  4440.1  417.26  4513.2  412.46  4582.8  412.71  4787.4  412.19
  4858.8  413.58  4963.7  414.64  4984.9   411.4  4987.8  409.16  4990.6  408.66
  4993.8  409.16  5006.2  409.74  5012.1  412.77  5021.5  411.91  5032.1  414.95
  5040.5  414.77  5077.5  412.82    5113  415.68  5148.2  414.93  5162.3  413.47
  5190.6  415.37  5204.8  413.63  5261.3  415.27  5501.7  427.69  5600.7  435.26
#Mann= 9 ,-1 , 0
  4091.6     .16       0  4257.6     .05       0  4373.7     .16       0
  4582.8     .05       0  4858.8     .16       0  4987.8     .07       0
  4993.8     .16       0  5040.5     .05       0    5113     .16       0
Bank Sta=4963.7,5032.1
XS Rating Curve= 0 ,0
Exp/Cntr=0.3,0.1

Type RM Length L Ch R = 1 ,8405    ,779,779,779
BEGIN DESCRIPTION:
UNT125 IN CCTC 15.0
END DESCRIPTION:
XS GIS Cut Line= 2
      3556855.24     10595671.57      3558484.42     10594745.07
#Sta/Elev= 30
  3912.1  433.73  3929.7  434.38  4004.7  432.06  4063.8  429.15  4091.1  426.32
  4128.6   425.3  4166.1  421.09  4253.3  417.35  4369.7  412.56  4408.3  410.27
  4486.1  410.11  4597.1  411.52  4752.8   410.2  4890.3  411.88  4973.3   413.6
  4979.1  410.64  4991.9  408.61  4994.7  408.11  4997.9  408.61  5016.6  412.51
  5066.8  412.12  5140.5  416.52  5156.4  419.39  5171.1  418.97    5178  420.94
  5193.9     421  5361.1  436.07  5463.4     441  5654.2  456.35  5786.3  459.58
#Mann= 8 ,-1 , 0
  3912.1     .05       0  4253.3     .16       0  4369.7     .12       0
  4486.1     .05       0  4890.3     .12       0  4991.9     .07       0
  4997.9     .12       0  5066.8     .16       0
Bank Sta=4973.3,5016.6
XS Rating Curve= 0 ,0
Exp/Cntr=0.3,0.1

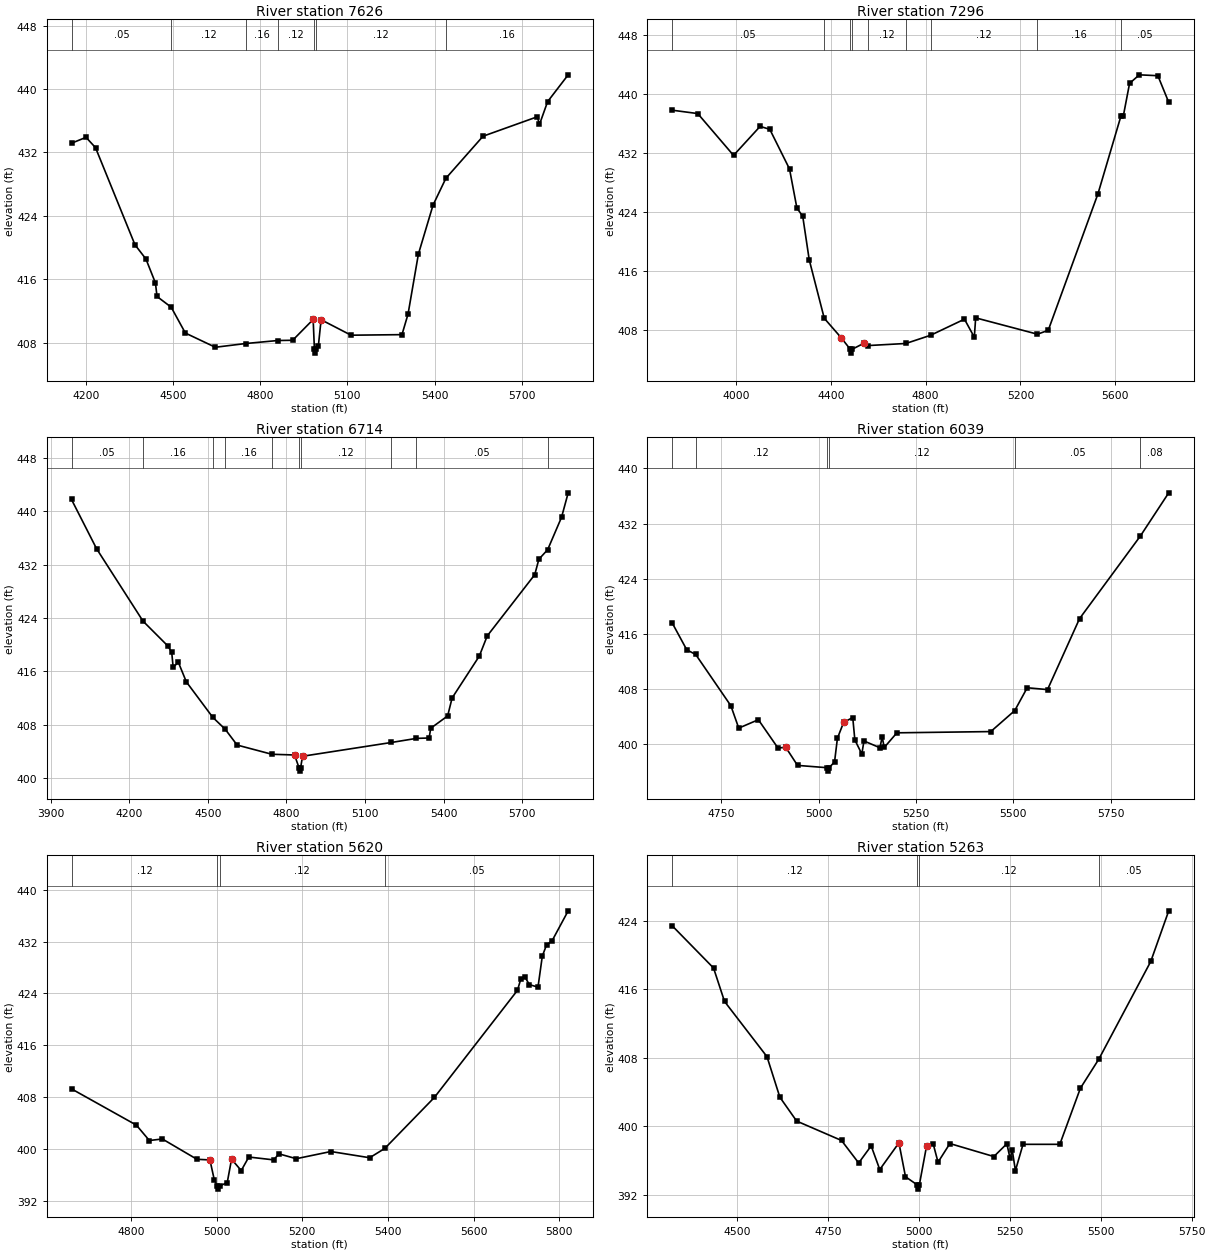
Type RM Length L Ch R = 1 ,7626    ,330,330,330
BEGIN DESCRIPTION:
UNT125 IN CCTC 13.0
END DESCRIPTION:
XS GIS Cut Line= 3
      3556938.56     10596020.54      3557896.88     10595723.67
      3558469.79     10595312.21
#Sta/Elev= 30
  4150.8  433.17  4200.8  433.91  4233.4  432.61  4369.1  420.37  4406.9  418.57
  4439.5  415.56    4445  413.85  4493.7   412.5  4542.5  409.24  4645.6  407.45
  4749.8  407.92  4860.6   408.3  4911.6  408.33  4982.1  410.95  4986.4  407.21
  4989.2  406.71  4992.4  407.21  4999.9  407.58  5009.4  410.92  5112.5  408.97
  5287.6  409.04  5308.5  411.63  5344.1  419.19  5394.5  425.37  5438.7  428.75
  5566.4  434.05    5753   436.5  5760.7  435.54  5788.6  438.41  5859.4  441.79
#Mann= 7 ,-1 , 0
  4150.8     .05       0  4493.7     .12       0  4749.8     .16       0
  4860.6     .12       0  4986.4     .07       0  4992.4     .12       0
  5438.7     .16       0
Bank Sta=4982.1,5009.4
XS Rating Curve= 0 ,0
Exp/Cntr=0.3,0.1

Type RM Length L Ch R = 1 ,7296    ,582,582,582
BEGIN DESCRIPTION:
UNT125 IN CCTC 12.0
END DESCRIPTION:
XS GIS Cut Line= 2
       3556672.9     10596395.55      3558688.56     10595822.62
#Sta/Elev= 30
  3730.2  437.81  3838.6  437.35  3989.7  431.67  4101.8  435.61  4142.6  435.21
  4225.8  429.83    4257  424.52  4281.6   423.4    4309  417.49  4372.4  409.55
  4444.1   406.9  4482.7  405.32  4485.4  404.82  4488.7  405.32  4539.5  406.16
  4558.5  405.85  4716.7  406.13  4820.7  407.24  4963.9  409.43  5005.5  406.98
  5011.2  409.61    5272  407.39  5317.4  407.92  5527.1  426.45  5623.7  436.97
  5633.9  436.98  5660.5  441.45  5701.7  442.61  5779.9  442.49  5825.7  438.88
#Mann= 9 ,-1 , 0
  3730.2     .05       0  4372.4     .16       0  4482.7     .07       0
  4488.7     .16       0  4558.5     .12       0  4716.7     .16       0
  4820.7     .12       0    5272     .16       0  5623.7     .05       0
Bank Sta=4444.1,4539.5
XS Rating Curve= 0 ,0
Exp/Cntr=0.3,0.1

Type RM Length L Ch R = 1 ,6714    ,675,675,675
BEGIN DESCRIPTION:
UNT125 IN CCTC 11.0
END DESCRIPTION:
XS GIS Cut Line= 2
      3556794.54     10596661.51      3558676.36      10596431.7
#Sta/Elev= 30
    3980  441.75  4075.8  434.36  4252.9  423.51  4347.8  419.78  4362.5  418.84
  4367.9  416.62  4388.1  417.31  4418.3   414.4  4519.2  409.08  4566.7  407.29
  4612.2  404.92  4744.6  403.54  4831.3  403.43  4848.5  401.51  4851.2  401.01
  4854.5  401.51  4861.8  403.24  5201.3  405.31  5296.7  405.92  5345.1  405.98
  5351.1  407.44  5415.7  409.29  5432.7  411.98  5536.5  418.26  5566.8  421.29
  5748.1  430.47  5763.9  432.79  5797.4  434.22  5850.5  439.09  5875.8  442.75
#Mann= 10 ,-1 , 0
    3980     .05       0  4252.9     .16       0  4519.2     .12       0
  4566.7     .16       0  4744.6     .12       0  4848.5     .07       0
  4854.5     .12       0  5201.3     .16       0  5296.7     .05       0
  5797.4     .08       0
Bank Sta=4831.3,4861.8
XS Rating Curve= 0 ,0
Exp/Cntr=0.3,0.1

Type RM Length L Ch R = 1 ,6039    ,419,419,419
BEGIN DESCRIPTION:
UNT125 IN CCTC 10.0
END DESCRIPTION:
XS GIS Cut Line= 3
      3557449.57     10597210.19      3557849.61     10597160.19
      3558649.64     10596810.18
#Sta/Elev= 30
  4623.2  417.65    4661  413.72    4684  413.04  4774.4  405.61  4794.6  402.37
    4845  403.59  4895.3   399.5  4915.5  399.58  4945.7  396.97  5020.8  396.64
  5023.6  396.14  5026.8  396.64  5040.8  397.47  5048.2   400.9  5064.2  403.21
  5087.6   403.9    5093  400.66  5110.9  398.62  5116.4  400.51  5157.3  399.53
  5163.2  401.07  5168.6  399.57    5201  401.69  5442.3  401.87  5503.9  404.91
  5535.9  408.22  5588.1  407.95  5670.4  418.23  5826.7   430.2  5899.6  436.46
#Mann= 6 ,-1 , 0
  4623.2     .16       0    4684     .12       0  5020.8     .07       0
  5026.8     .12       0  5503.9     .05       0  5826.7     .08       0
Bank Sta=4915.5,5064.2
XS Rating Curve= 0 ,0
Exp/Cntr=0.3,0.1

Type RM Length L Ch R = 1 ,5620    ,357,357,357
BEGIN DESCRIPTION:
UNT125 IN CCTC 9.0
END DESCRIPTION:
XS GIS Cut Line= 3
      3557599.65     10597610.18      3557949.61     10597560.19
      3558749.58     10597460.19
#Sta/Elev= 30
  4661.3  409.25  4812.8  403.65  4843.1  401.27  4873.4  401.51  4954.2  398.37
  4984.5  398.27  4994.6  395.22  5001.7  394.26  5004.5  393.76  5007.7  394.26
  5024.9  394.77    5035  398.38  5057.6  396.63  5075.3  398.72  5133.2  398.28
  5145.8  399.21  5186.1  398.46  5266.8  399.57  5357.5  398.61  5392.8  400.05
  5508.6  407.93  5702.6  424.48  5710.2  426.19  5720.3  426.51  5730.3  425.36
  5750.5  424.97  5760.6  429.77  5770.6  431.51  5783.2  432.11    5821  436.76
#Mann= 4 ,-1 , 0
  4661.3     .12       0  5001.7     .07       0  5007.7     .12       0
  5392.8     .05       0
Bank Sta=4984.5,5035
XS Rating Curve= 0 ,0
Exp/Cntr=0.3,0.1

Type RM Length L Ch R = 1 ,5263    ,475,475,475
BEGIN DESCRIPTION:
UNT125 IN CCTC 8.0
END DESCRIPTION:
XS GIS Cut Line= 3
      3557436.88     10598158.91      3558157.37     10597850.75
      3558634.72      10597516.6
#Sta/Elev= 30
  4320.6  423.46  4434.8   418.5    4465  414.59  4581.8  408.13  4617.2  403.39
  4663.4   400.6  4786.8  398.33    4834   395.7  4868.4   397.7    4892  394.93
  4944.7  398.05  4962.8  394.09  4994.9  393.14  4997.6  392.64  5000.9  393.14
  5020.9  397.71    5039  397.93  5052.3  395.79  5084.9  397.97  5205.9  396.45
  5241.7  397.95  5250.4  396.23  5256.5  397.18  5265.2  394.81  5286.1  397.88
  5387.3  397.88  5443.9  404.44  5494.7  407.85  5637.5  419.27  5686.9  425.19
#Mann= 4 ,-1 , 0
  4320.6     .12       0  4994.9     .07       0  5000.9     .12       0
  5494.7     .05       0
Bank Sta=4944.7,5020.9
XS Rating Curve= 0 ,0
Exp/Cntr=0.3,0.1

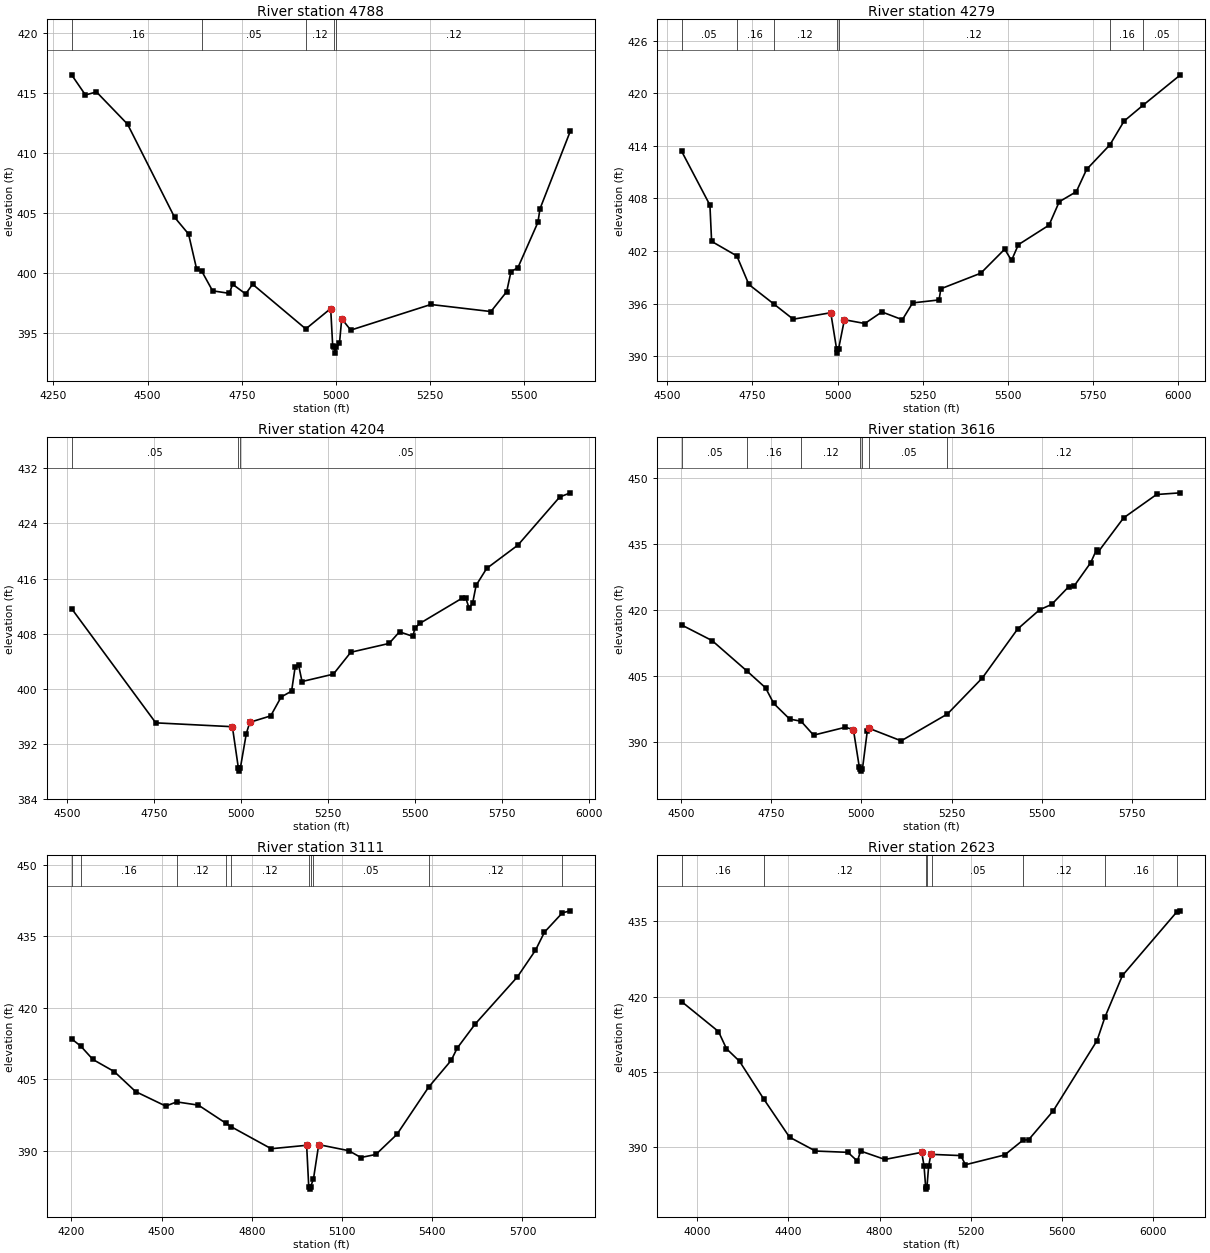
Type RM Length L Ch R = 1 ,4788    ,509,509,509
BEGIN DESCRIPTION:
Mapping XS 318af0c1
END DESCRIPTION:
XS GIS Cut Line= 2
       3558039.6     10598906.89      3558546.95     10597684.06
#Sta/Elev= 30
  4298.4  416.55  4335.1  414.87  4364.4  415.12  4446.9  412.43  4571.7  404.66
  4608.8  403.26  4630.4  400.32  4643.5  400.18  4672.6  398.52  4717.1  398.31
  4725.7  399.07  4760.4  398.26  4778.9  399.07    4920  395.34  4986.1  397.04
  4991.5  393.88  4995.5  393.82  4998.3  393.32  5001.5  393.82  5009.4  394.13
  5015.4  396.19  5039.3  395.24  5251.9  397.38  5411.4  396.79  5453.3  398.45
  5464.6  400.12    5483  400.45  5536.2  404.24  5541.6  405.36  5622.3  411.86
#Mann= 5 ,-1 , 0
  4298.4     .16       0  4643.5     .05       0    4920     .12       0
  4995.5     .07       0  5001.5     .12       0
Bank Sta=4986.1,5015.4
XS Rating Curve= 0 ,0
Exp/Cntr=0.3,0.1

Type RM Length L Ch R = 1 ,4279    ,75,75,75
BEGIN DESCRIPTION:
UNT125 IN CCTC 7.0
END DESCRIPTION:
XS GIS Cut Line= 2
      3558582.13     10599037.15      3558625.53     10597574.79
#Sta/Elev= 30
  4542.9  413.35  4625.6  407.23  4630.6  403.09  4704.6  401.43  4739.9  398.17
  4812.6  395.96    4870  394.21  4980.1  394.95  4997.1  390.84  4999.8  390.34
  5003.1  390.84  5020.1  394.15  5080.1  393.72  5130.1  395.04  5190.1  394.15
  5220.2  396.07  5297.9  396.41  5302.9  397.68  5420.2  399.46  5490.3   402.2
  5510.3  400.91  5530.3  402.71  5620.3  404.94  5650.3  407.61  5700.4  408.76
  5730.4  411.29    5799  414.11  5840.4  416.81    5897  418.65  6005.9  422.09
#Mann= 7 ,-1 , 0
  4542.9     .05       0  4704.6     .16       0  4812.6     .12       0
  4997.1     .07       0  5003.1     .12       0    5799     .16       0
    5897     .05       0
Bank Sta=4980.1,5020.1
XS Rating Curve= 0 ,0
Exp/Cntr=0.3,0.1

Type RM Length L Ch R = 1 ,4204    ,588,588,588
BEGIN DESCRIPTION:
UNT125 IN CCTC 6.0
END DESCRIPTION:
XS GIS Cut Line= 3
       3558642.9     10599071.83      3558673.28     10598520.61
      3558716.68     10597639.53
#Sta/Elev= 30
  4512.7  411.63  4754.7  395.04    4975  394.48  4992.1  388.53  4994.8  388.03
  4998.1  388.53  5015.1  393.49  5025.1  395.12  5085.2  396.05  5115.2  398.79
  5145.3  399.65  5155.3  403.08  5165.3  403.45  5175.3  401.04  5265.4  402.11
  5315.5  405.29  5425.6  406.57  5455.6  408.26  5494.5  407.59  5499.5  408.81
  5515.7  409.53  5635.9  413.15  5645.9  413.19  5655.9  411.68  5665.9  412.44
  5675.9  415.01  5706.2  417.46  5796.1  420.85  5916.2  427.83  5946.9  428.44
#Mann= 3 ,-1 , 0
  4512.7     .05       0  4992.1     .04       0  4998.1     .05       0
Bank Sta=4975,5025.1
XS Rating Curve= 0 ,0
Exp/Cntr=0.3,0.1

Type RM Length L Ch R = 1 ,3616    ,505,505,505
BEGIN DESCRIPTION:
UNT125 IN CCTC 5.0
END DESCRIPTION:
XS GIS Cut Line= 3
      3558803.42     10599295.84      3559136.75     10598660.43
      3559240.84     10598004.68
#Sta/Elev= 30
  4502.5  416.64  4586.7   413.1  4684.6  406.09  4734.7  402.38  4757.3  398.83
  4801.6  395.27    4833  394.79  4867.8  391.62    4956  393.42  4978.1  392.86
  4994.5  384.31  4997.1  383.95  4999.9  383.45  5003.1  383.95  5016.5  392.54
  5022.2  393.15  5110.4  390.33  5238.5  396.43  5335.3  404.63  5432.9  415.73
  5493.7   420.1  5527.2  421.32  5574.7  425.37  5589.5  425.51  5635.4  430.81
  5651.7  433.79  5656.8  433.33  5726.5  440.98  5817.7  446.29    5884  446.67
#Mann= 7 ,-1 , 0
  4502.5     .05       0  4684.6     .16       0    4833     .12       0
  4997.1     .07       0  5003.1     .12       0  5022.2     .05       0
  5238.5     .12       0
Bank Sta=4978.1,5022.2
XS Rating Curve= 0 ,0
Exp/Cntr=0.3,0.1

Type RM Length L Ch R = 1 ,3111    ,488,488,488
BEGIN DESCRIPTION:
UNT125 IN CCTC 4.0
END DESCRIPTION:
XS GIS Cut Line= 3
      3558949.22     10599488.58      3559490.92     10599087.51
      3559532.54      10598104.2
#Sta/Elev= 30
  4201.1   413.5  4231.6  411.98    4272  409.18    4343  406.64  4413.9  402.45
  4514.1  399.41  4550.4  400.29  4622.7  399.61  4713.2  395.85  4731.3  395.09
  4864.7  390.47  4982.5  391.19  4989.5   382.5  4992.3     382  4995.5   382.5
  5005.2  384.13  5022.6  391.33  5122.7  390.06  5162.7  388.63  5212.7  389.27
  5282.8  393.49    5388  403.38    5463  408.99    5483  411.56    5543  416.63
  5683.2   426.5  5743.2  432.07  5773.2  435.88  5832.8  439.93  5859.3  440.35
#Mann= 10 ,-1 , 0
  4201.1     .12       0  4231.6     .16       0  4550.4     .12       0
  4713.2     .16       0  4731.3     .12       0  4989.5     .07       0
  4995.5     .12       0  5005.2     .05       0    5388     .12       0
  5832.8     .16       0
Bank Sta=4982.5,5022.6
XS Rating Curve= 0 ,0
Exp/Cntr=0.3,0.1

Type RM Length L Ch R = 1 ,2623    ,365,365,365
BEGIN DESCRIPTION:
UNT125 IN CCTC 3.0
END DESCRIPTION:
XS GIS Cut Line= 4
       3559308.6     10599806.29      3559949.25     10599056.26
      3559970.09     10598873.97      3559808.62     10597868.73
#Sta/Elev= 30
  3931.7  418.98  4092.9  413.02  4128.1  409.58  4185.2  407.08  4292.6  399.46
  4404.7  391.91  4518.4  389.14  4660.5  388.88  4702.5  387.13  4716.5  389.14
    4823  387.46  4984.6  388.88  4994.7  386.19  5001.7  382.03  5004.5  381.53
  5007.7  382.03  5014.8  386.06  5024.9  388.55  5030.4  388.47  5156.1  388.23
  5176.3   386.4  5348.5  388.36  5429.4  391.34  5453.1  391.37  5561.2  397.15
  5753.6   411.2  5788.2  415.88    5865  424.21  6102.6  436.86  6119.7  437.13
#Mann= 8 ,-1 , 0
  3931.7     .16       0  4292.6     .12       0  5001.7     .07       0
  5007.7     .12       0  5030.4     .05       0  5429.4     .12       0
  5788.2     .16       0  6102.6     .12       0
Bank Sta=4984.6,5024.9
XS Rating Curve= 0 ,0
Exp/Cntr=0.3,0.1

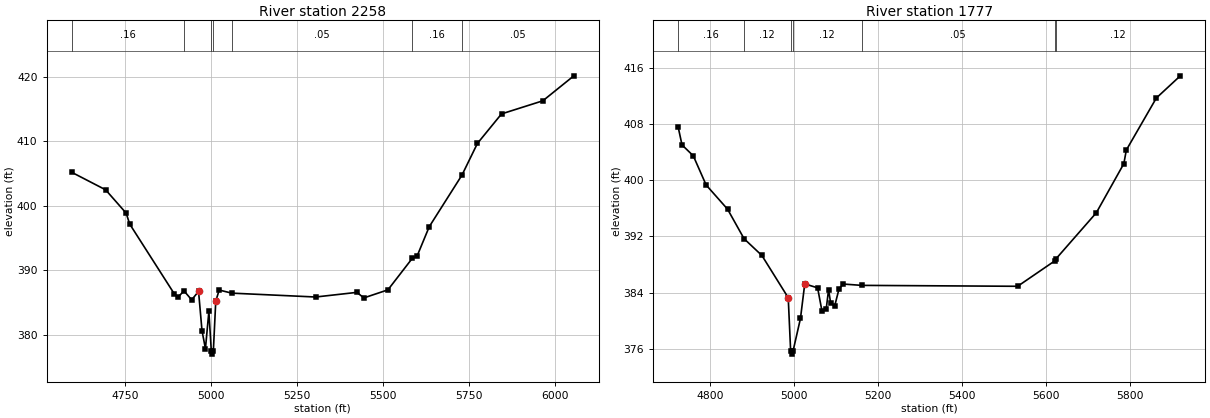
Type RM Length L Ch R = 1 ,2258    ,481,481,481
BEGIN DESCRIPTION:
UNT125 IN CCTC 2.0
END DESCRIPTION:
XS GIS Cut Line= 2
      3560272.68     10599468.48      3560290.04     10598010.09
#Sta/Elev= 30
  4595.4  405.21  4693.7   402.5  4753.3  398.89  4763.7  397.19  4893.7  386.34
  4903.7  385.85  4921.4  386.84  4943.7  385.45  4963.7  386.76  4973.7  380.68
  4983.7  377.88  4993.7  383.67  5000.7  377.54  5003.5  377.04  5006.7  377.54
  5013.7  385.26  5023.7  386.97  5060.1  386.49  5303.7  385.89  5423.8  386.61
  5443.8  385.75  5513.8     387  5584.7  391.89  5598.3   392.2  5633.8  396.78
    5729  404.79  5773.8  409.69  5843.8  414.26  5963.8  416.29  6053.9  420.16
#Mann= 7 ,-1 , 0
  4595.4     .16       0  4921.4     .12       0  5000.7     .07       0
  5006.7     .12       0  5060.1     .05       0  5584.7     .16       0
    5729     .05       0
Bank Sta=4963.7,5013.7
XS Rating Curve= 0 ,0
Exp/Cntr=0.3,0.1

Type RM Length L Ch R = 1 ,1777    ,0,0,0
BEGIN DESCRIPTION:
UNT125 IN CCTC 1.0
END DESCRIPTION:
XS GIS Cut Line= 2
      3560776.16     10599325.25      3560537.63     10598154.29
#Sta/Elev= 30
  4724.9  407.55  4733.9  405.05  4760.7   403.5  4791.3  399.34  4842.3  395.89
  4881.6  391.68    4924  389.29  4986.7  383.27  4992.4  375.73  4995.2  375.23
  4998.4  375.73  5015.8  380.31    5026  385.24  5056.6  384.68  5066.8  381.44
    5077  381.61  5082.7  384.41  5087.8  382.47  5097.5  382.15  5107.7  384.55
  5117.9  385.22  5161.3  385.03  5532.7   384.9  5620.6   388.5  5623.5  388.78
    5720  395.38  5785.5  402.38  5791.4  404.32  5862.9  411.74  5919.9   414.9
#Mann= 7 ,-1 , 0
  4724.9     .16       0  4881.6     .12       0  4992.4     .07       0
  4998.4     .12       0  5161.3     .05       0  5620.6     .16       0
  5623.5     .12       0
Bank Sta=4986.7,5026
XS Rating Curve= 0 ,0
Exp/Cntr=0.3,0.1