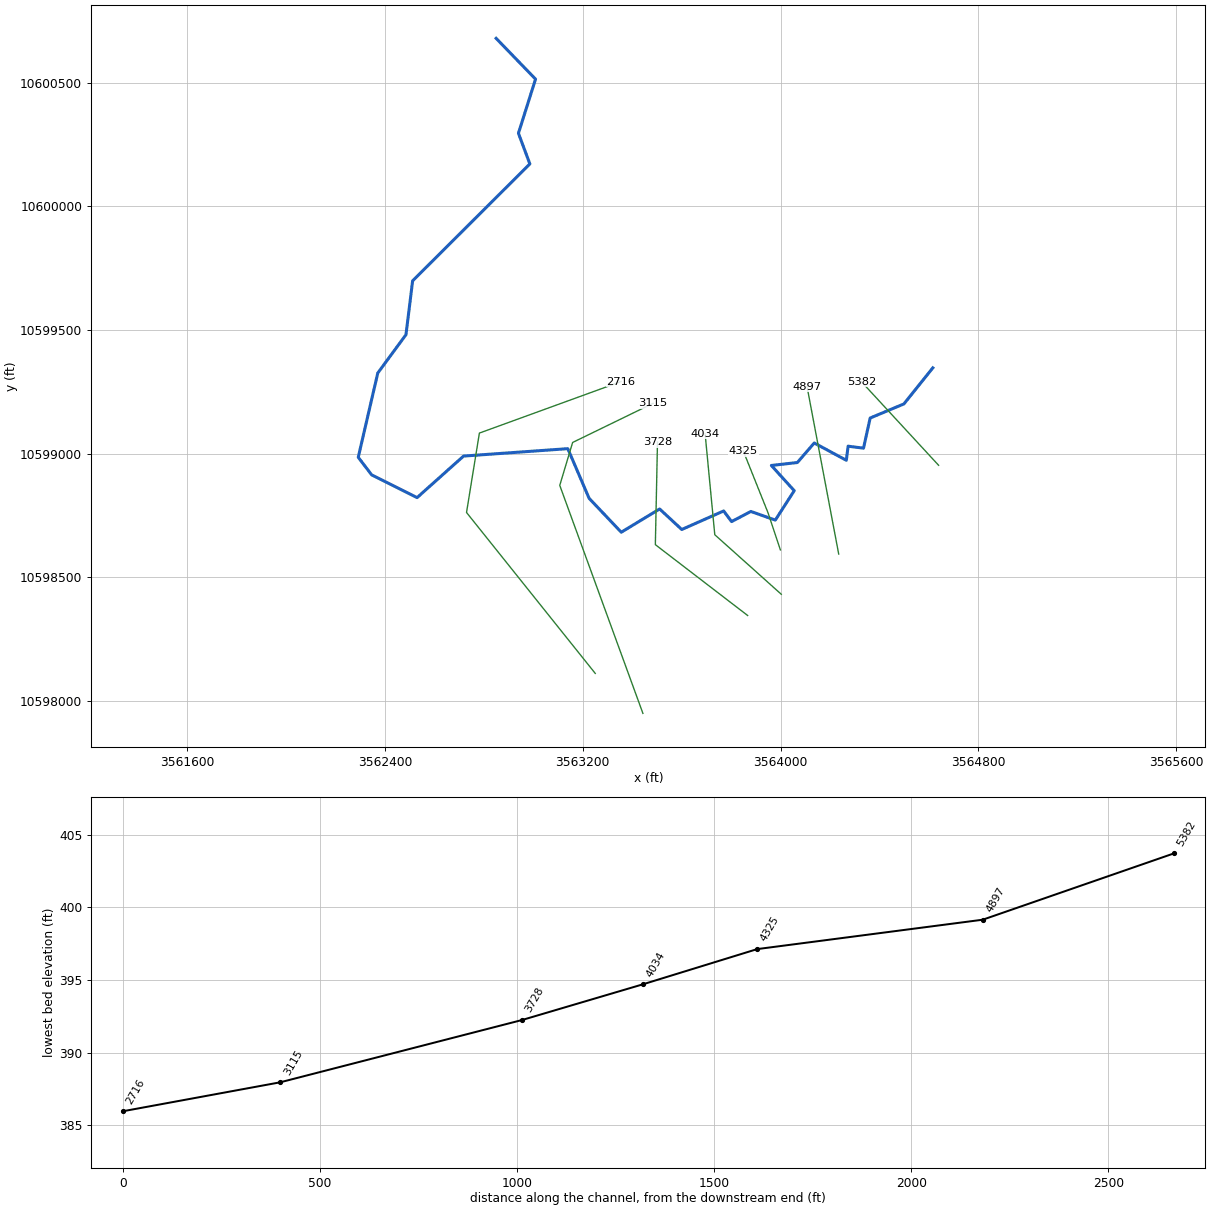
--- UNT129 IN CCTC.prj (project) ---

Proj Title=UNT129 IN CCTC Base Level Engineering
Current Plan=p01
Default Exp/Contr=0.3,0.1
English Units
Geom File=g01
Flow File=f01
Plan File=p01
BEGIN DESCRIPTION:
UNT129 IN CCTC
END DESCRIPTION:

--- UNT129 IN CCTC.p01 (plan) ---

Plan Title=Multiple Run
Short Identifier=Multiple
Geom File=g01
Flow File=f01
Subcritical Flow
K Sum by GR= 0
Std Step Tol= 0.01
Critical Tol= 0.01
Num of Std Step Trials= 20
Max Error Tol= 0.3
Flow Tol Ratio= 0.001
Split Flow NTrial= 30
Split Flow Tol= 0.02
Split Flow Ratio= 0.02
Log Output Level= 0
Friction Slope Method= 1
Unsteady Friction Slope Method= 2
Unsteady Bridges Friction Slope Method= 1
Parabolic Critical Depth
Global Vel Dist=  1 , 1 , 1
Global Log Level= 0
CheckData=True
Encroach Param= -1, 0, 0, 0
BEGIN DESCRIPTION:
Multiple Run
END DESCRIPTION:

--- UNT129 IN CCTC.f01 (steady flow) ---

Flow Title=Multiple
Number of Profiles=7
Profile Names=10-year,25-year,50-year,1pct_min,100-year,1pct_plu,500-year
River Rch & RM= UNT129 IN CCTC,Reach-1,5382
     908    1219    1471    1297    1755    2373    2486
Boundary for River Rch & Prof#=UNT129 IN CCTC,Reach-1,1
Up Type=0
Dn Type=3
Dn Slope=0.005
Boundary for River Rch & Prof#=UNT129 IN CCTC,Reach-1,2
Up Type=0
Dn Type=3
Dn Slope=0.005
Boundary for River Rch & Prof#=UNT129 IN CCTC,Reach-1,3
Up Type=0
Dn Type=3
Dn Slope=0.005
Boundary for River Rch & Prof#=UNT129 IN CCTC,Reach-1,4
Up Type=0
Dn Type=3
Dn Slope=0.005
Boundary for River Rch & Prof#=UNT129 IN CCTC,Reach-1,5
Up Type=0
Dn Type=3
Dn Slope=0.005
Boundary for River Rch & Prof#=UNT129 IN CCTC,Reach-1,6
Up Type=0
Dn Type=3
Dn Slope=0.005
Boundary for River Rch & Prof#=UNT129 IN CCTC,Reach-1,7
Up Type=0
Dn Type=3
Dn Slope=0.005

--- UNT129 IN CCTC.g01 (geometry) ---

Geom Title=Existing Conditions

River Reach=UNT129 IN CCTC,Reach-1
Reach XY= 30
      3564616.25     10599347.00      3564499.25     10599201.00
      3564362.75     10599144.00      3564335.75     10599022.00
      3564273.50     10599030.00      3564266.25     10598973.00
      3564136.50     10599043.00      3564068.25     10598964.00
      3563963.00     10598952.00      3564055.50     10598850.00
      3563979.00     10598731.00      3563880.00     10598766.00
      3563802.00     10598725.00      3563770.00     10598768.00
      3563600.50     10598693.00      3563511.00     10598776.00
      3563355.75     10598682.00      3563225.75     10598819.00
      3563139.50     10599020.00      3562717.75     10598990.00
      3562529.75     10598822.00      3562346.00     10598914.00
      3562291.75     10598985.00      3562370.75     10599326.00
      3562484.75     10599481.00      3562511.75     10599699.00
      3562986.00     10600172.00      3562939.75     10600296.00
      3563009.00     10600515.00      3562849.50     10600680.00

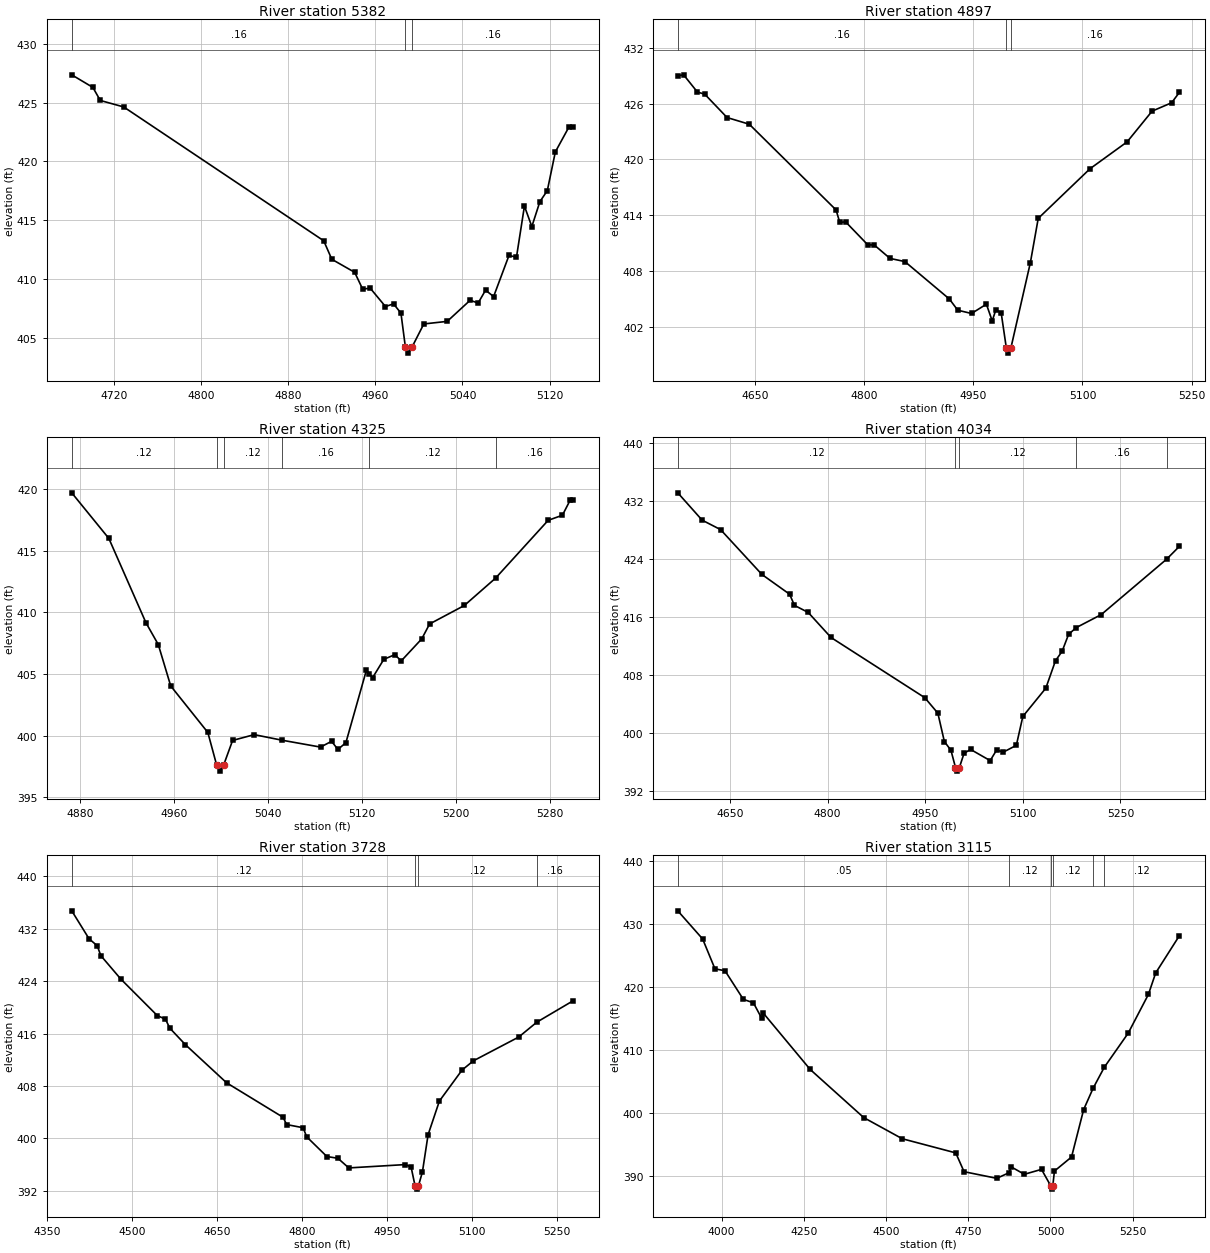
Type RM Length L Ch R = 1,5382,485,485,485
BEGIN DESCRIPTION:
UNT129 IN CCTC 4.0
END DESCRIPTION:
XS GIS Cut Line= 2
      3564639.48     10598952.85      3564327.00     10599291.37
#Sta/Elev= 30
  4681.2  427.36  4700.6  426.29  4707.4  425.18  4728.9  424.63  4912.6  413.25
  4920.0  411.68  4941.0  410.57  4948.4  409.13  4955.2  409.23  4969.3  407.66
  4976.7  407.89  4983.5  407.10  4987.6  404.20  4990.3  403.70  4993.6  404.20
  5004.5  406.18  5026.0  406.40  5047.0  408.19  5054.4  407.96  5061.2  409.05
  5068.6  408.51  5082.7  412.00  5089.6  411.86  5096.9  416.20  5103.7  414.46
  5111.1  416.58  5117.9  417.51  5125.3  420.81  5137.7  422.91  5141.9  422.91
#Mann=3,-1,0
  4681.2    0.16       0  4987.6    0.07       0  4993.6    0.16       0
Bank Sta=4987.6,4993.6
Exp/Cntr=0.3,0.1

Type RM Length L Ch R = 1,4897,572,572,572
BEGIN DESCRIPTION:
Mapping XS 0eef0615
END DESCRIPTION:
XS GIS Cut Line= 2
      3564235.41     10598593.72      3564107.37     10599270.82
#Sta/Elev= 30
  4544.1  429.02  4552.1  429.11  4571.0  427.26  4581.2  427.02  4611.8  424.51
  4642.3  423.79  4761.5  414.56  4766.6  413.21  4774.6  413.28  4805.1  410.80
  4813.9  410.79  4835.6  409.34  4856.0  409.00  4917.1  404.97  4928.7  403.76
  4947.6  403.41  4968.0  404.41  4976.0  402.61  4981.1  403.83  4988.3  403.48
  4995.5  399.64  4998.2  399.14  5001.5  399.64  5028.4  408.88  5039.2  413.65
  5110.4  419.00  5161.3  421.89  5195.6  425.20  5222.4  426.10  5233.2  427.23
#Mann=3,-1,0
  4544.1    0.16       0  4995.5    0.07       0  5001.5    0.16       0
Bank Sta=4995.5,5001.5
Exp/Cntr=0.3,0.1

Type RM Length L Ch R = 1,4325,291,291,291
BEGIN DESCRIPTION:
UNT129 IN CCTC 3.0
END DESCRIPTION:
XS GIS Cut Line= 3
      3563999.59     10598610.23      3563949.61     10598760.19
      3563849.62     10599010.16
#Sta/Elev= 30
  4872.7  419.70  4904.3  416.00  4935.9  409.16  4946.4  407.39  4957.0  404.03
  4988.6  400.26  4996.1  397.62  4998.9  397.12  5002.1  397.62  5009.7  399.61
  5028.1  400.08  5051.7  399.63  5084.6  399.07  5094.0  399.54  5099.4  398.88
  5106.2  399.43  5123.7  405.32  5126.3  405.02  5129.0  404.71  5138.5  406.19
  5147.9  406.57  5153.3  406.06  5170.8  407.85  5177.5  409.06  5207.1  410.56
  5233.7  412.78  5278.5  417.47  5290.6  417.88  5297.3  419.12  5300.0  419.12
#Mann=6,-1,0
  4872.7    0.12       0  4996.1    0.07       0  5002.1    0.12       0
  5051.7    0.16       0  5126.3    0.12       0  5233.7    0.16       0
Bank Sta=4996.1,5002.1
Exp/Cntr=0.3,0.1

Type RM Length L Ch R = 1,4034,306,306,306
BEGIN DESCRIPTION:
Mapping XS 032d9631
END DESCRIPTION:
XS GIS Cut Line= 3
      3564003.21     10598430.94      3563734.12     10598671.82
      3563695.06     10599079.80
#Sta/Elev= 30
  4569.8  433.11  4607.2  429.34  4635.6  428.03  4699.1  421.84  4741.7  419.11
  4749.1  417.57  4770.2  416.60  4805.3  413.14  4949.4  404.83  4969.5  402.69
  4979.5  398.77  4989.6  397.57  4996.6  395.19  4999.4  394.69  5002.6  395.19
  5009.7  397.14  5019.7  397.69  5049.9  396.14  5059.9  397.62  5070.0  397.31
  5090.1  398.25  5100.1  402.24  5135.4  406.14  5150.3  409.94  5160.4  411.22
  5170.4  413.57  5182.1  414.50  5220.6  416.30  5321.2  423.96  5340.8  425.73
#Mann=5,-1,0
  4569.8    0.12       0  4996.6    0.07       0  5002.6    0.12       0
  5182.1    0.16       0  5321.2    0.05       0
Bank Sta=4996.6,5002.6
Exp/Cntr=0.3,0.1

Type RM Length L Ch R = 1,3728,613,613,613
BEGIN DESCRIPTION:
UNT129 IN CCTC 2.0
END DESCRIPTION:
XS GIS Cut Line= 3
      3563866.92     10598345.20      3563493.65     10598631.66
      3563502.30     10599046.75
#Sta/Elev= 30
  4393.2  434.75  4423.7  430.49  4438.2  429.41  4444.5  427.91  4479.8  424.33
  4544.2  418.75  4558.7  418.19  4566.3  416.83  4594.0  414.29  4666.6  408.48
  4766.3  403.21  4772.6  402.10  4801.6  401.62  4808.0  400.23  4843.6  397.22
  4863.1  396.95  4882.3  395.48  4982.3  395.99  4992.3  395.62  4999.3  392.74
  5002.0  392.24  5005.3  392.74  5012.3  394.87  5022.3  400.55  5042.3  405.70
  5082.3  410.43  5102.3  411.84  5182.3  415.47  5214.4  417.75  5278.9  421.04
#Mann=4,-1,0
  4393.2    0.12       0  4999.3    0.07       0  5005.3    0.12       0
  5214.4    0.16       0
Bank Sta=4999.3,5005.3
Exp/Cntr=0.3,0.1

Type RM Length L Ch R = 1,3115,399,399,399
BEGIN DESCRIPTION:
Mapping XS ccd8c4cc
END DESCRIPTION:
XS GIS Cut Line= 4
      3563443.33     10597949.12      3563106.95     10598871.47
      3563159.03     10599045.08      3563484.59     10599203.52
#Sta/Elev= 30
  3867.1  432.04  3942.7  427.58  3980.1  422.85  4010.6  422.55  4066.4  418.02
  4097.0  417.47  4122.2  415.02  4127.5  415.81  4269.7  406.91  4432.4  399.29
  4549.5  395.94  4712.1  393.70  4737.4  390.72  4836.9  389.67  4875.0  390.58
  4879.8  391.51  4920.6  390.31  4972.8  391.09  5001.1  388.46  5003.9  387.96
  5007.1  388.46  5012.1  390.82  5064.1  393.05  5101.0  400.57  5129.7  403.94
  5163.8  407.27  5236.3  412.66  5297.7  418.79  5319.9  422.20  5392.2  428.12
#Mann=6,-1,0
  3867.1    0.05       0  4875.0    0.12       0  5001.1    0.07       0
  5007.1    0.12       0  5129.7    0.05       0  5163.8    0.12       0
Bank Sta=5001.1,5007.1
Exp/Cntr=0.3,0.1

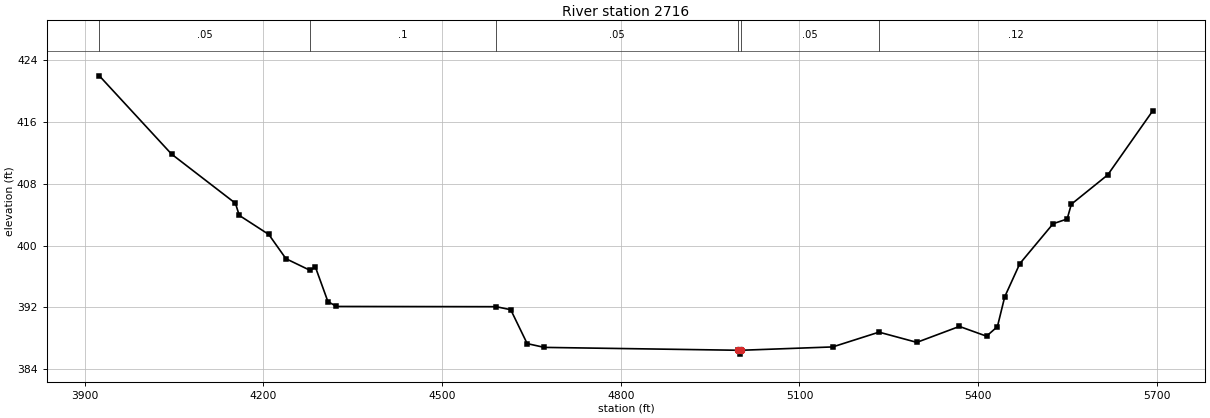
Type RM Length L Ch R = 1,2716,0,0,0
BEGIN DESCRIPTION:
UNT129 IN CCTC 1.0
END DESCRIPTION:
XS GIS Cut Line= 4
      3563250.57     10598110.86      3562729.76     10598761.87
      3562781.85     10599083.05      3563354.67     10599291.35
#Sta/Elev= 30
  3924.5  421.93  4045.7  411.82  4153.0  405.46  4159.4  403.90  4209.0  401.43
  4237.8  398.30  4277.7  396.82  4287.4  397.19  4308.2  392.77  4322.6  392.13
  4590.7  392.10  4615.2  391.71  4642.8  387.33  4671.6  386.84  4996.6  386.47
  4999.4  385.97  5002.6  386.47  5155.7  386.90  5233.5  388.81  5297.0  387.49
  5368.5  389.55  5414.0  388.29  5432.3  389.52  5444.6  393.38  5469.9  397.66
  5525.8  402.82  5549.4  403.43  5556.4  405.34  5617.5  409.13  5693.1  417.41
#Mann=6,-1,0
  3924.5    0.05       0  4277.7     0.1       0  4590.7    0.05       0
  4996.6    0.03       0  5002.6    0.05       0  5233.5    0.12       0
Bank Sta=4996.6,5002.6
Exp/Cntr=0.3,0.1

Chan Stop Cuts=-1