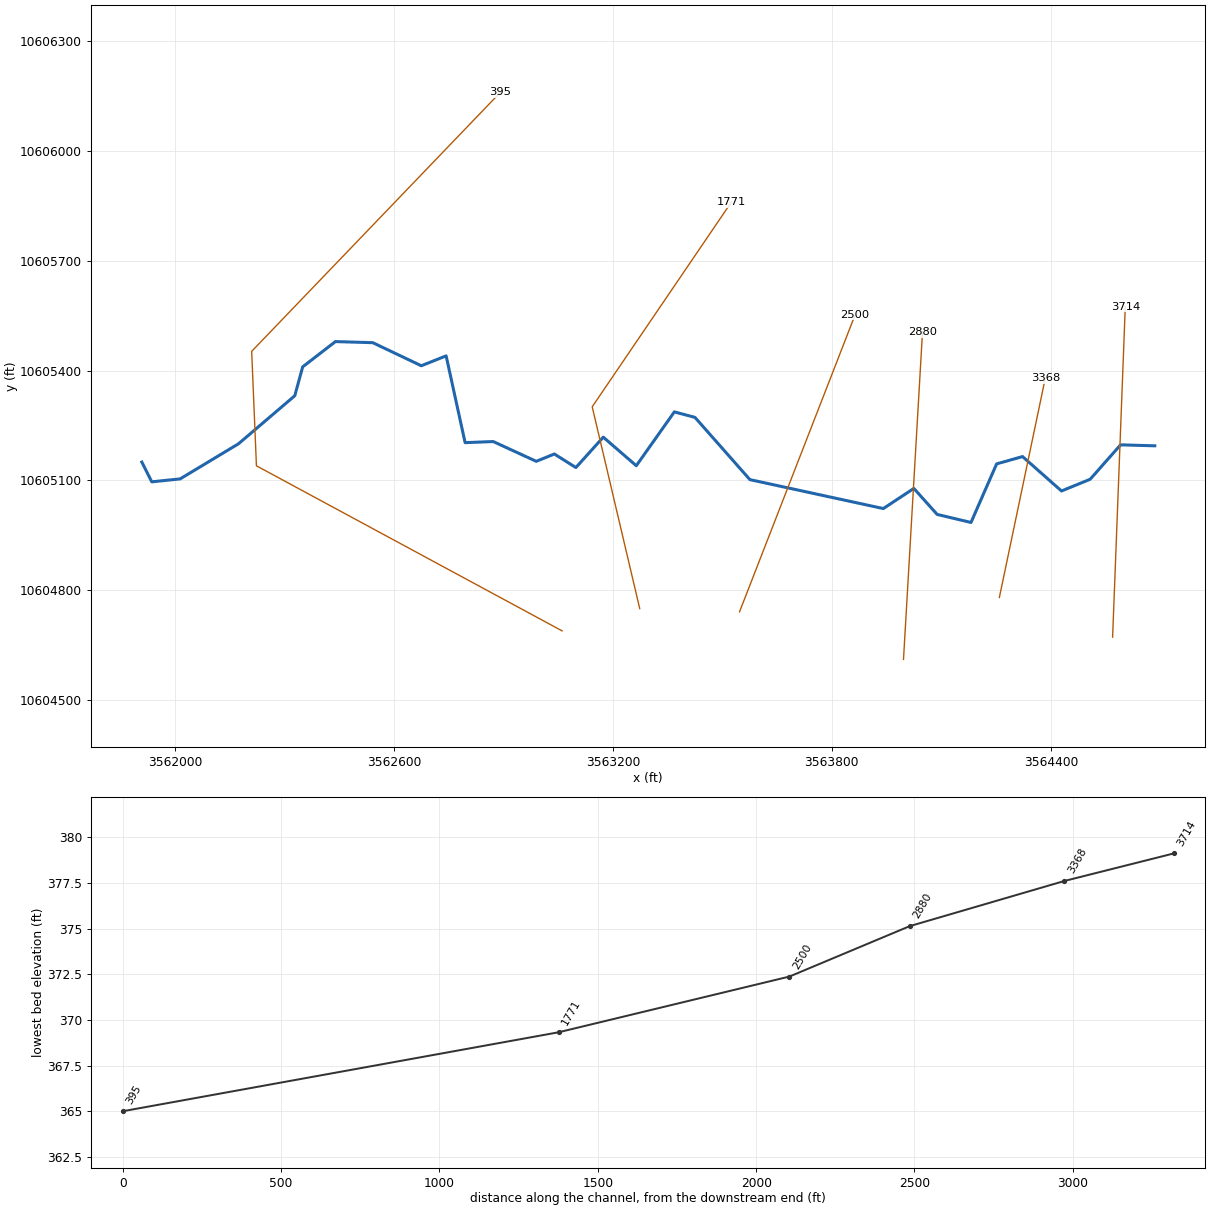
--- UNT130 IN CCTC.prj (project) ---

Proj Title=UNT130 IN CCTC Base Level Engineering
Current Plan=p01
Default Exp/Contr=0.3,0.1
English Units
Geom File=g01
Flow File=f01
Plan File=p01
BEGIN DESCRIPTION:
UNT130 IN CCTC
END DESCRIPTION:

--- UNT130 IN CCTC.p01 (plan) ---

Plan Title=Multiple Run
Short Identifier=Multiple
Geom File=g01
Flow File=f01
Subcritical Flow
K Sum by GR= 0
Std Step Tol= 0.01
Critical Tol= 0.01
Num of Std Step Trials= 20
Max Error Tol= 0.3
Flow Tol Ratio= 0.001
Split Flow NTrial= 30
Split Flow Tol= 0.02
Split Flow Ratio= 0.02
Log Output Level= 0
Friction Slope Method= 1
Unsteady Friction Slope Method= 2
Unsteady Bridges Friction Slope Method= 1
Parabolic Critical Depth
Global Vel Dist=  1 , 1 , 1
Global Log Level= 0
CheckData=True
Encroach Param= -1, 0, 0, 0
BEGIN DESCRIPTION:
Multiple Run
END DESCRIPTION:

--- UNT130 IN CCTC.f01 (steady flow) ---

Flow Title=Multiple
Number of Profiles=7
Profile Names=10-year,25-year,50-year,1pct_min,100-year,1pct_plu,500-year
River Rch & RM= UNT130 IN CCTC,Reach-1,3714
    1354    1855    2267    2023    2736    3701    3970
Boundary for River Rch & Prof#=UNT130 IN CCTC,Reach-1,1
Up Type=0
Dn Type=3
Dn Slope=0.005
Boundary for River Rch & Prof#=UNT130 IN CCTC,Reach-1,2
Up Type=0
Dn Type=3
Dn Slope=0.005
Boundary for River Rch & Prof#=UNT130 IN CCTC,Reach-1,3
Up Type=0
Dn Type=3
Dn Slope=0.005
Boundary for River Rch & Prof#=UNT130 IN CCTC,Reach-1,4
Up Type=0
Dn Type=3
Dn Slope=0.005
Boundary for River Rch & Prof#=UNT130 IN CCTC,Reach-1,5
Up Type=0
Dn Type=3
Dn Slope=0.005
Boundary for River Rch & Prof#=UNT130 IN CCTC,Reach-1,6
Up Type=0
Dn Type=3
Dn Slope=0.005
Boundary for River Rch & Prof#=UNT130 IN CCTC,Reach-1,7
Up Type=0
Dn Type=3
Dn Slope=0.005

--- UNT130 IN CCTC.g01 (geometry) ---

Geom Title=Existing Conditions

River Reach=UNT130 IN CCTC,Reach-1
Reach XY= 30
      3564684.75     10605194.36      3564591.00     10605197.00
      3564507.75     10605103.00      3564429.25     10605071.00
      3564322.50     10605165.00      3564251.50     10605145.00
      3564181.25     10604985.00      3564088.50     10605007.00
      3564024.75     10605078.00      3563941.00     10605023.00
      3563575.50     10605102.00      3563425.00     10605272.00
      3563368.50     10605287.00      3563264.25     10605140.00
      3563173.75     10605218.00      3563098.75     10605135.00
      3563039.75     10605172.00      3562990.25     10605152.00
      3562872.25     10605206.00      3562795.25     10605203.00
      3562743.25     10605440.00      3562675.25     10605413.00
      3562542.25     10605476.00      3562440.00     10605479.00
      3562350.25     10605410.00      3562328.50     10605331.00
      3562174.50     10605200.00      3562014.50     10605104.00
      3561936.75     10605096.00      3561909.50     10605150.00

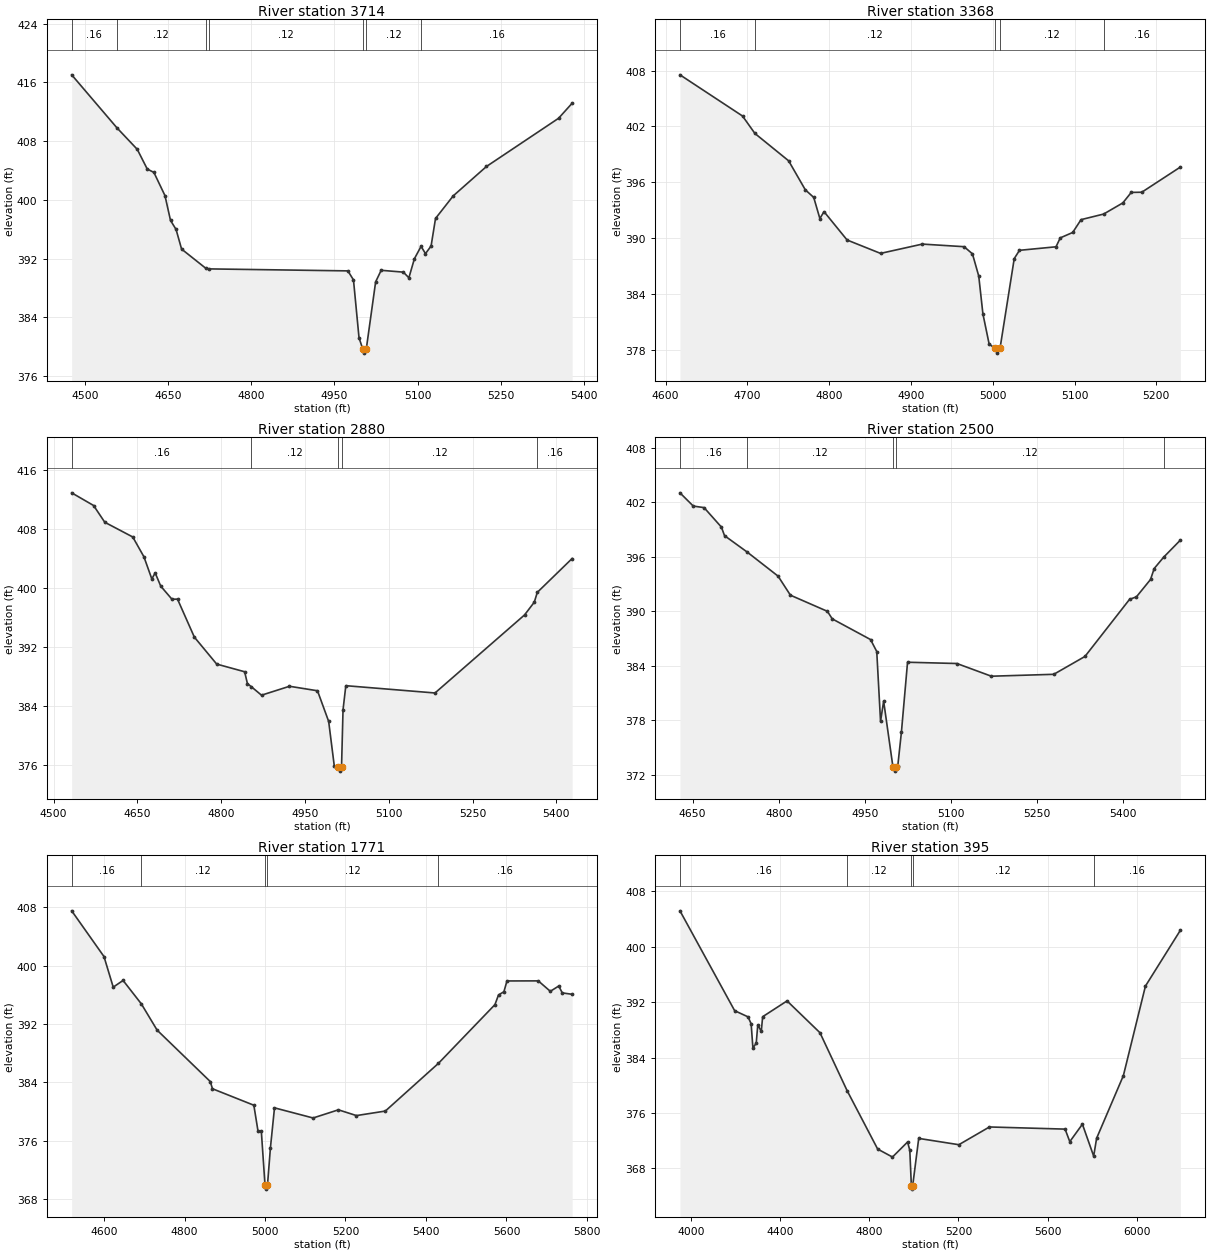
Type RM Length L Ch R = 1,3714,346,346,346
BEGIN DESCRIPTION:
UNT130 IN CCTC 6.0
END DESCRIPTION:
XS GIS Cut Line= 2
      3564569.25     10604671.91      3564603.97     10605574.65
#Sta/Elev= 30
  4475.6  417.02  4557.3  409.80  4594.0  406.87  4612.0  404.19  4624.0  403.73
  4644.0  400.57  4654.0  397.19  4664.0  395.97  4674.0  393.29  4717.6  390.68
  4724.3  390.59  4974.2  390.32  4984.3  389.09  4994.3  381.21  5001.3  379.62
  5004.0  379.12  5007.3  379.62  5024.3  388.83  5034.3  390.40  5074.3  390.15
  5084.3  389.38  5094.3  391.98  5106.3  393.66  5114.3  392.67  5124.4  393.71
  5132.4  397.46  5164.4  400.54  5224.4  404.54  5354.5  411.10  5379.0  413.15
#Mann=7,-1,0
  4475.6    0.16       0  4557.3    0.12       0  4717.6    0.16       0
  4724.3    0.12       0  5001.3    0.07       0  5007.3    0.12       0
  5106.3    0.16       0
Bank Sta=5001.3,5007.3
Exp/Cntr=0.3,0.1

Type RM Length L Ch R = 1,3368,488,488,488
BEGIN DESCRIPTION:
UNT130 IN CCTC 5.0
END DESCRIPTION:
XS GIS Cut Line= 2
      3564258.94     10604780.13      3564384.80     10605379.05
#Sta/Elev= 30
  4617.5  407.55  4694.0  403.12  4709.2  401.24  4750.4  398.30  4770.8  395.18
  4781.1  394.36  4788.6  392.09  4793.7  392.83  4821.9  389.78  4862.8  388.34
  4913.9  389.34  4965.0  389.06  4975.2  388.29  4982.9  385.90  4988.0  381.83
  4995.6  378.59  5002.9  378.11  5005.6  377.61  5008.9  378.11  5026.3  387.78
  5032.7  388.67  5077.4  389.05  5082.6  390.01  5097.8  390.59  5108.0  391.97
  5135.6  392.57  5159.1  393.77  5169.4  394.90  5182.3  394.92  5229.5  397.63
#Mann=5,-1,0
  4617.5    0.16       0  4709.2    0.12       0  5002.9    0.07       0
  5008.9    0.12       0  5135.6    0.16       0
Bank Sta=5002.9,5008.9
Exp/Cntr=0.3,0.1

Type RM Length L Ch R = 1,2880,380,380,380
BEGIN DESCRIPTION:
UNT130 IN CCTC 4.0
END DESCRIPTION:
XS GIS Cut Line= 2
      3563996.33     10604611.08      3564048.41     10605505.16
#Sta/Elev= 30
  4532.5  412.89  4571.7  411.17  4591.7  408.90  4641.8  406.90  4661.8  404.21
  4675.9  401.21  4681.9  402.03  4691.9  400.23  4711.9  398.46  4721.9  398.47
  4752.0  393.32  4792.0  389.66  4842.0  388.62  4847.0  387.01  4854.0  386.59
  4872.2  385.44  4922.3  386.65  4972.4  386.04  4992.4  381.88  5002.4  375.87
  5009.4  375.64  5012.2  375.14  5015.4  375.64  5018.1  383.45  5023.1  386.73
  5182.7  385.74  5343.0  396.33  5360.4  398.06  5365.8  399.39  5428.1  403.98
#Mann=5,-1,0
  4532.5    0.16       0  4854.0    0.12       0  5009.4    0.07       0
  5015.4    0.12       0  5365.8    0.16       0
Bank Sta=5009.4,5015.4
Exp/Cntr=0.3,0.1

Type RM Length L Ch R = 1,2500,729,729,729
BEGIN DESCRIPTION:
UNT130 IN CCTC 3.0
END DESCRIPTION:
XS GIS Cut Line= 2
      3563547.14     10604741.07      3563863.95     10605552.62
#Sta/Elev= 30
  4628.1  403.05  4651.3  401.59  4670.1  401.42  4700.3  399.27  4705.7  398.33
  4745.2  396.52  4798.9  393.87  4820.4  391.77  4884.8  389.99  4893.2  389.16
  4959.9  386.88  4970.7  385.56  4977.3  377.87  4982.7  380.09  4998.8  372.88
  5001.6  372.38  5004.8  372.88  5007.2  372.90  5013.6  376.65  5024.3  384.38
  5110.2  384.24  5170.2  382.84  5278.9  383.05  5333.2  385.02  5410.8  391.31
  5422.8  391.59  5447.3  393.50  5453.7  394.71  5470.2  395.96  5499.3  397.84
#Mann=5,-1,0
  4628.1    0.16       0  4745.2    0.12       0  4998.8    0.07       0
  5004.8    0.12       0  5470.2    0.16       0
Bank Sta=4998.8,5004.8
Exp/Cntr=0.3,0.1

Type RM Length L Ch R = 1,1771,1376,1376,1376
BEGIN DESCRIPTION:
UNT130 IN CCTC 2.0
END DESCRIPTION:
XS GIS Cut Line= 3
      3563273.68     10604749.74      3563143.48     10605300.93
      3563525.01     10605860.23
#Sta/Elev= 30
  4519.7  407.51  4599.9  401.24  4622.9  397.04  4647.4  397.96  4692.7  394.75
  4732.0  391.14  4864.0  384.09  4869.5  383.10  4972.3  380.84  4982.5  377.34
  4990.9  377.25  5000.1  369.83  5002.8  369.33  5006.1  369.83  5013.4  374.95
  5023.6  380.48  5119.5  379.09  5182.4  380.21  5227.2  379.42  5299.0  380.04
  5431.0  386.59  5571.3  394.64  5580.2  395.97  5593.6  396.41  5601.2  397.89
  5679.0  397.90  5708.9  396.47  5729.8  397.19  5738.7  396.25  5763.1  396.06
#Mann=5,-1,0
  4519.7    0.16       0  4692.7    0.12       0  5000.1    0.07       0
  5006.1    0.12       0  5431.0    0.16       0
Bank Sta=5000.1,5006.1
Exp/Cntr=0.3,0.1

Type RM Length L Ch R = 1,395,0,0,0
BEGIN DESCRIPTION:
UNT130 IN CCTC 1.0
END DESCRIPTION:
XS GIS Cut Line= 4
      3563060.98     10604688.97      3562223.52     10605139.77
      3562210.50     10605452.27      3562891.92     10606159.72
#Sta/Elev= 30
  3950.3  405.17  4195.8  390.76  4255.8  389.87  4269.8  388.87  4277.7  385.38
  4292.6  386.06  4299.6  388.71  4315.3  387.78  4321.5  389.89  4431.0  392.17
  4578.7  387.58  4700.4  379.23  4837.7  370.79  4904.1  369.64  4971.9  371.81
  4981.9  370.61  4988.9  365.51  4991.6  365.01  4994.9  365.51  5021.9  372.33
  5202.1  371.42  5339.3  373.98  5678.9  373.67  5700.0  371.86  5756.6  374.38
  5807.2  369.77  5820.4  372.35  5940.5  381.39  6039.5  394.31  6196.4  402.37
#Mann=5,-1,0
  3950.3    0.16       0  4700.4    0.12       0  4988.9    0.07       0
  4994.9    0.12       0  5807.2    0.16       0
Bank Sta=4988.9,4994.9
Exp/Cntr=0.3,0.1

Chan Stop Cuts=-1