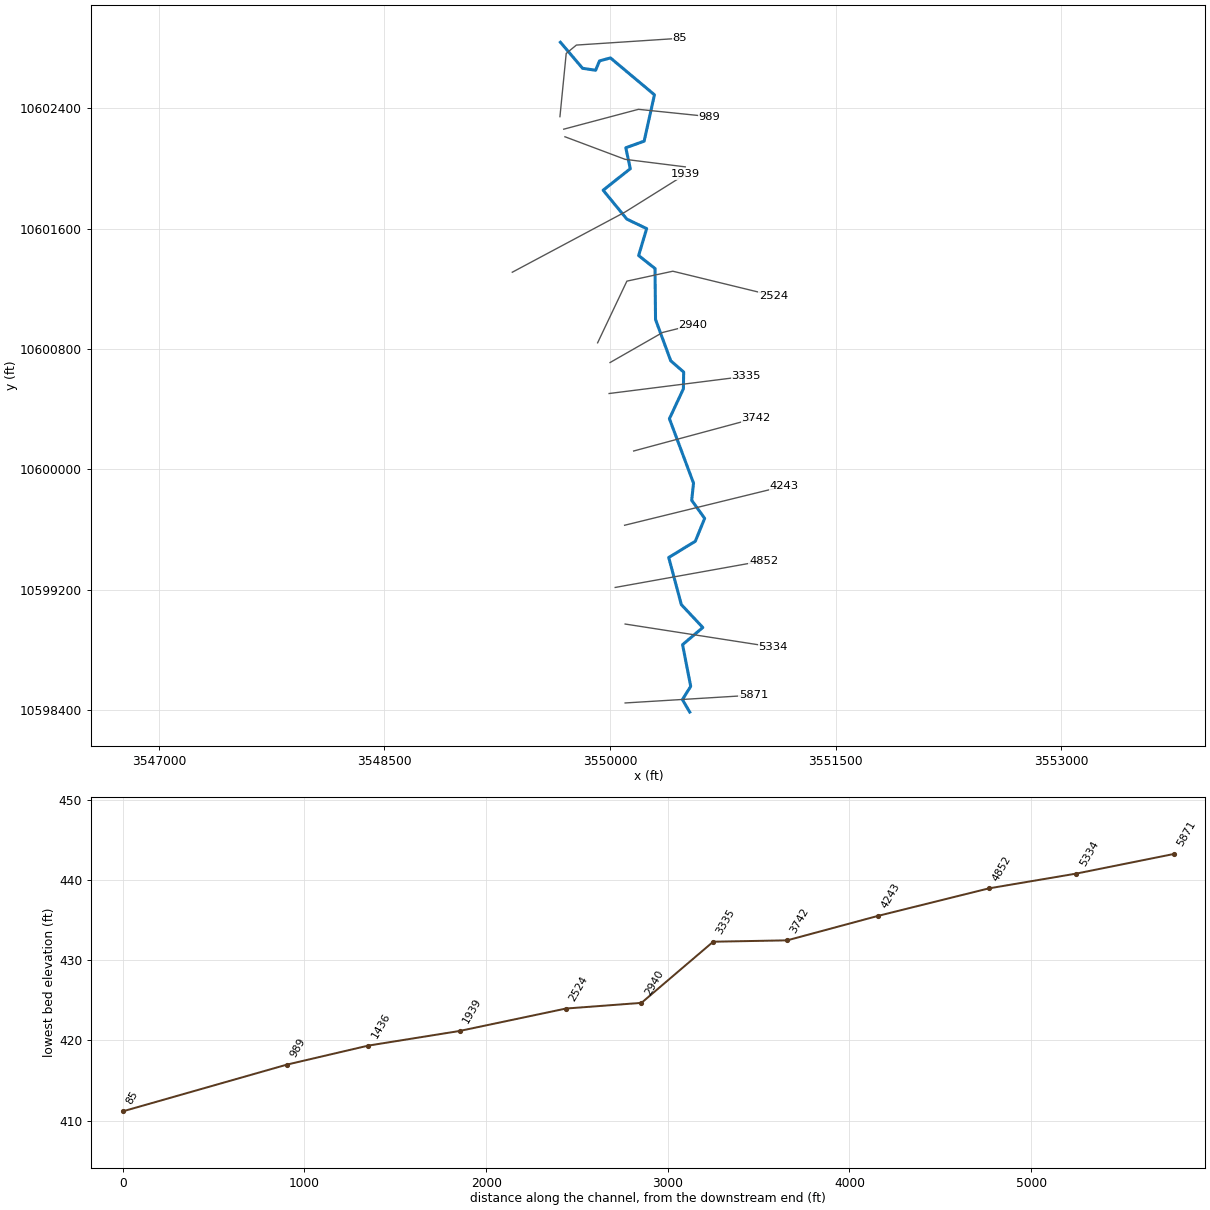
--- UNT132 IN CCTC.prj (project) ---

Proj Title=UNT132 IN CCTC Base Level Engineering
Current Plan=p01
Default Exp/Contr=0.3,0.1
English Units
Geom File=g01
Flow File=f01
Plan File=p01
BEGIN DESCRIPTION:
UNT132 IN CCTC
END DESCRIPTION:

--- UNT132 IN CCTC.p01 (plan) ---

Plan Title=Multiple Run
Short Identifier=Multiple
Geom File=g01
Flow File=f01
Subcritical Flow
K Sum by GR= 0
Std Step Tol= 0.01
Critical Tol= 0.01
Num of Std Step Trials= 20
Max Error Tol= 0.3
Flow Tol Ratio= 0.001
Split Flow NTrial= 30
Split Flow Tol= 0.02
Split Flow Ratio= 0.02
Log Output Level= 0
Friction Slope Method= 1
Unsteady Friction Slope Method= 2
Unsteady Bridges Friction Slope Method= 1
Parabolic Critical Depth
Global Vel Dist=  1 , 1 , 1
Global Log Level= 0
CheckData=True
Encroach Param= -1, 0, 0, 0
BEGIN DESCRIPTION:
Multiple Run
END DESCRIPTION:

--- UNT132 IN CCTC.f01 (steady flow) ---

Flow Title=Multiple
Number of Profiles=7
Profile Names=10-year,25-year,50-year,1pct_min,100-year,1pct_plu,500-year
River Rch & RM= UNT132 IN CCTC,Reach-1,5871
    1195    1624    1974    1751    2368    3203    3396
River Rch & RM= UNT132 IN CCTC,Reach-1,2940
    1636    2264    2785    2498    3378    4568    4955
Boundary for River Rch & Prof#=UNT132 IN CCTC,Reach-1,1
Up Type=0
Dn Type=3
Dn Slope=0.005
Boundary for River Rch & Prof#=UNT132 IN CCTC,Reach-1,2
Up Type=0
Dn Type=3
Dn Slope=0.005
Boundary for River Rch & Prof#=UNT132 IN CCTC,Reach-1,3
Up Type=0
Dn Type=3
Dn Slope=0.005
Boundary for River Rch & Prof#=UNT132 IN CCTC,Reach-1,4
Up Type=0
Dn Type=3
Dn Slope=0.005
Boundary for River Rch & Prof#=UNT132 IN CCTC,Reach-1,5
Up Type=0
Dn Type=3
Dn Slope=0.005
Boundary for River Rch & Prof#=UNT132 IN CCTC,Reach-1,6
Up Type=0
Dn Type=3
Dn Slope=0.005
Boundary for River Rch & Prof#=UNT132 IN CCTC,Reach-1,7
Up Type=0
Dn Type=3
Dn Slope=0.005

--- UNT132 IN CCTC.g01 (geometry) ---

Geom Title=Existing Conditions

River Reach=UNT132 IN CCTC,Reach-1
Reach XY= 30
      3550529.50     10598388.00      3550480.50     10598471.00
      3550535.75     10598559.00      3550481.75     10598836.00
      3550616.25     10598950.00      3550473.50     10599102.00
      3550389.75     10599415.00      3550566.50     10599523.00
      3550628.50     10599675.00      3550542.25     10599795.00
      3550554.50     10599909.00      3550394.25     10600337.00
      3550487.25     10600536.00      3550489.00     10600647.00
      3550403.00     10600722.00      3550302.00     10600996.00
      3550298.50     10601335.00      3550189.50     10601421.00
      3550243.00     10601600.00      3550111.25     10601663.00
      3549953.75     10601855.00      3550134.25     10601998.00
      3550104.25     10602137.00      3550226.25     10602181.00
      3550294.75     10602489.00      3550002.25     10602734.00
      3549929.50     10602714.00      3549903.50     10602652.00
      3549816.75     10602665.00      3549669.75     10602838.00

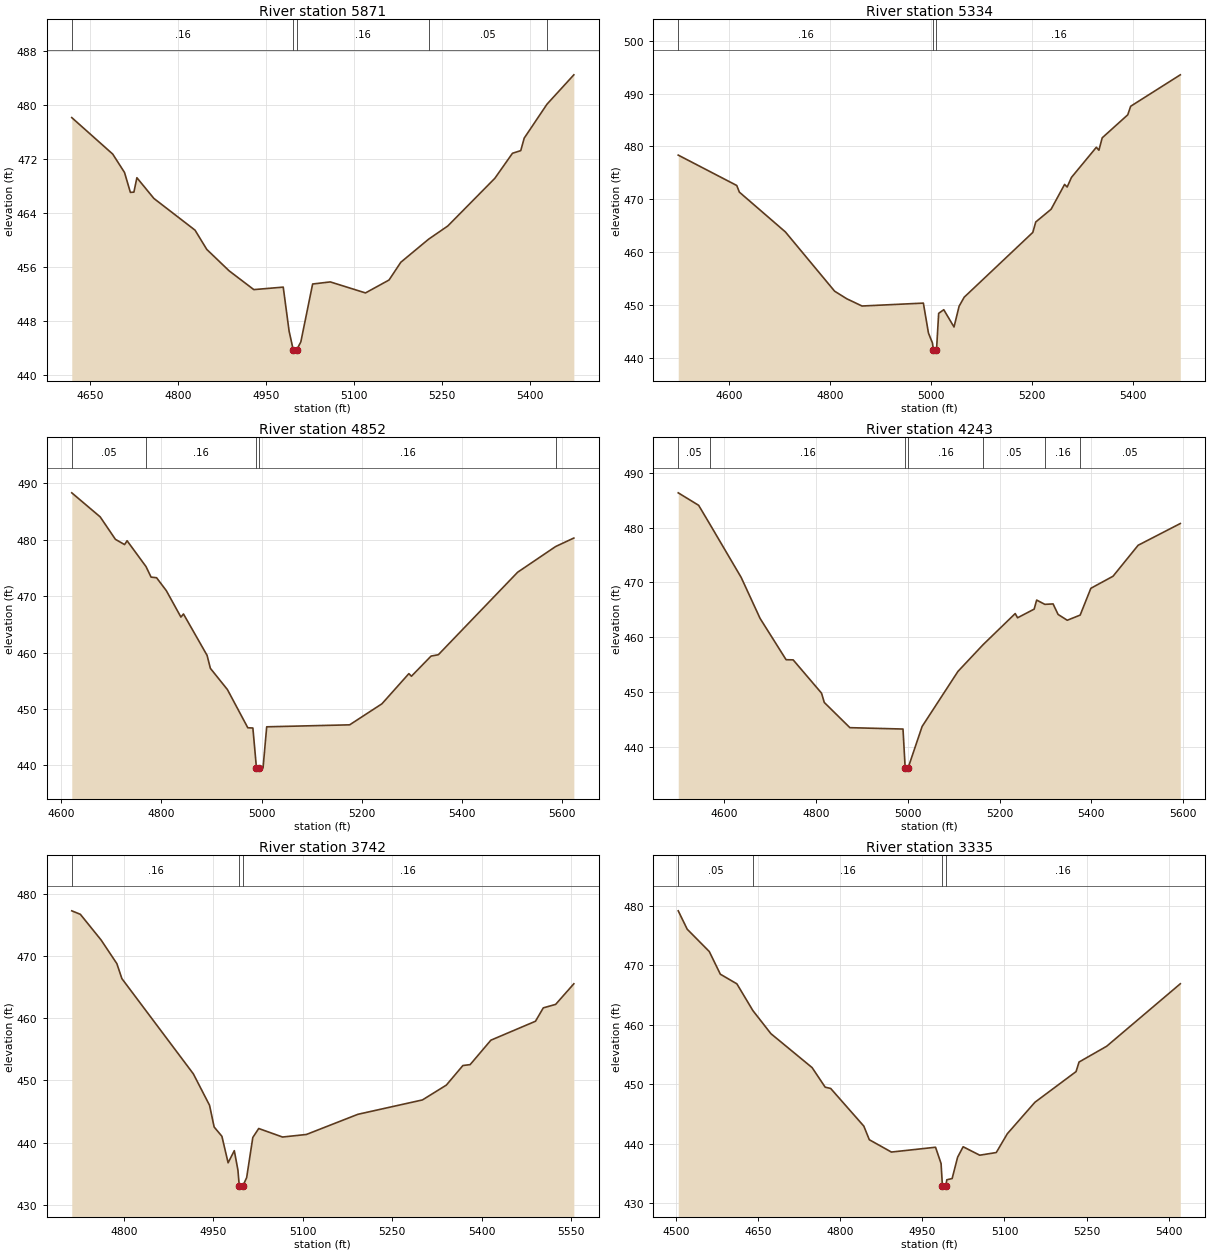
Type RM Length L Ch R = 1,5871,537,537,537
BEGIN DESCRIPTION:
UNT132 IN CCTC 11.0
END DESCRIPTION:
XS GIS Cut Line= 2
      3550099.89     10598448.68      3550954.01     10598500.76
#Sta/Elev= 30
  4618.6  478.16  4688.4  472.76  4708.5  470.04  4718.5  467.09  4724.5  467.13
  4729.6  469.26  4758.6  466.19  4828.7  461.50  4848.7  458.65  4886.8  455.48
  4928.9  452.70  4979.0  453.07  4989.0  446.56  4996.0  443.80  4998.8  443.30
  5002.0  443.80  5009.0  444.96  5029.1  453.53  5059.2  453.84  5119.2  452.21
  5159.3  454.12  5179.4  456.75  5226.7  460.16  5259.5  462.12  5339.7  469.18
  5369.7  472.88  5383.8  473.27  5389.7  475.12  5428.5  480.14  5474.3  484.49
#Mann=5,-1,0
  4618.6    0.16       0  4996.0    0.07       0  5002.0    0.16       0
  5226.7    0.05       0  5428.5    0.16       0
Bank Sta=4996,5002
Exp/Cntr=0.3,0.1

Type RM Length L Ch R = 1,5334,482,482,482
BEGIN DESCRIPTION:
UNT132 IN CCTC 10.0
END DESCRIPTION:
XS GIS Cut Line= 2
      3550099.92     10598972.97      3551082.52     10598820.20
#Sta/Elev= 30
  4499.7  478.34  4615.6  472.59  4620.8  471.33  4711.9  463.80  4809.4  452.58
  4833.3  451.15  4863.7  449.77  4985.2  450.32  4995.3  444.65  5003.2  442.77
  5005.2  441.35  5008.0  440.85  5011.2  441.35  5015.5  448.38  5025.6  449.07
  5045.9  445.80  5056.0  449.74  5066.1  451.44  5202.0  463.71  5207.8  465.68
  5238.2  468.09  5264.9  472.79  5270.0  472.30  5278.6  474.13  5327.8  479.82
  5332.9  479.27  5339.4  481.61  5390.0  485.97  5395.8  487.59  5494.1  493.54
#Mann=3,-1,0
  4499.7    0.16       0  5005.2    0.07       0  5011.2    0.16       0
Bank Sta=5005.2,5011.2
Exp/Cntr=0.3,0.1

Type RM Length L Ch R = 1,4852,609,609,609
BEGIN DESCRIPTION:
Mapping XS 02442ce2
END DESCRIPTION:
XS GIS Cut Line= 2
      3550033.88     10599216.03      3551020.01     10599393.12
#Sta/Elev= 30
  4621.0  488.30  4677.7  484.04  4708.1  480.06  4726.4  479.13  4731.4  479.81
  4769.2  475.23  4779.2  473.37  4790.2  473.26  4809.7  470.97  4838.8  466.29
  4843.9  466.84  4891.0  459.51  4897.6  457.21  4931.6  453.45  4972.3  446.68
  4982.4  446.64  4989.6  439.50  4992.3  439.00  4995.6  439.50  5002.7  439.57
  5010.0  446.85  5175.5  447.20  5240.0  450.93  5293.7  456.27  5298.8  455.81
  5338.0  459.38  5352.5  459.62  5510.7  474.23  5586.6  478.79  5622.9  480.29
#Mann=5,-1,0
  4621.0    0.05       0  4769.2    0.16       0  4989.6    0.07       0
  4995.6    0.16       0  5586.6    0.12       0
Bank Sta=4989.6,4995.6
Exp/Cntr=0.3,0.1

Type RM Length L Ch R = 1,4243,501,501,501
BEGIN DESCRIPTION:
UNT132 IN CCTC 9.0
END DESCRIPTION:
XS GIS Cut Line= 2
      3550096.41     10599629.23      3551158.86     10599889.64
#Sta/Elev= 30
  4500.0  486.35  4544.5  484.07  4568.7  480.66  4637.1  470.92  4678.3  463.44
  4735.0  455.90  4750.4  455.87  4812.2  449.80  4818.2  448.10  4874.0  443.50
  4989.7  443.25  4994.5  436.07  4997.3  435.57  5000.5  436.07  5031.3  443.71
  5109.4  453.76  5164.4  458.66  5234.2  464.32  5239.3  463.55  5275.5  465.13
  5280.9  466.78  5298.8  466.00  5316.7  466.08  5327.6  464.16  5347.6  463.10
  5375.7  464.04  5399.0  468.93  5447.3  471.13  5502.0  476.78  5593.9  480.75
#Mann=7,-1,0
  4500.0    0.05       0  4568.7    0.16       0  4994.5    0.07       0
  5000.5    0.16       0  5164.4    0.05       0  5298.8    0.16       0
  5375.7    0.05       0
Bank Sta=4994.5,5000.5
Exp/Cntr=0.3,0.1

Type RM Length L Ch R = 1,3742,407,407,407
BEGIN DESCRIPTION:
UNT132 IN CCTC 8.0
END DESCRIPTION:
XS GIS Cut Line= 2
      3550156.61     10600122.53      3550969.08     10600341.27
#Sta/Elev= 30
  4712.9  477.22  4727.3  476.66  4762.1  472.53  4788.5  468.73  4796.9  466.33
  4916.7  451.02  4943.8  445.98  4951.5  442.49  4964.5  441.00  4974.9  436.74
  4985.3  438.69  4991.4  435.54  4993.6  433.01  4996.3  432.51  4999.6  433.01
  5006.0  434.37  5016.3  440.81  5026.2  442.25  5066.1  440.88  5106.1  441.29
  5192.4  444.53  5300.6  446.84  5340.6  449.22  5368.4  452.37  5380.5  452.51
  5415.3  456.44  5490.0  459.48  5503.1  461.63  5523.8  462.19  5554.3  465.50
#Mann=3,-1,0
  4712.9    0.16       0  4993.6    0.07       0  4999.6    0.16       0
Bank Sta=4993.6,4999.6
Exp/Cntr=0.3,0.1

Type RM Length L Ch R = 1,3335,395,395,395
BEGIN DESCRIPTION:
UNT132 IN CCTC 7.0
END DESCRIPTION:
XS GIS Cut Line= 2
      3549993.36     10600504.46      3550903.07     10600619.04
#Sta/Elev= 30
  4504.2  479.11  4520.6  476.02  4560.9  472.27  4581.1  468.46  4611.3  466.84
  4640.5  462.35  4673.4  458.47  4748.7  452.76  4772.6  449.47  4782.6  449.26
  4843.1  442.93  4853.2  440.64  4893.5  438.57  4974.1  439.38  4984.2  436.64
  4986.7  432.84  4989.5  432.34  4992.7  432.84  4994.7  433.91  5004.4  434.12
  5014.4  437.70  5024.5  439.46  5054.8  438.04  5085.0  438.49  5105.2  441.65
  5155.6  446.94  5230.7  452.09  5236.2  453.70  5286.6  456.35  5421.1  466.85
#Mann=4,-1,0
  4504.2    0.05       0  4640.5    0.16       0  4986.7    0.07       0
  4992.7    0.16       0
Bank Sta=4986.7,4992.7
Exp/Cntr=0.3,0.1

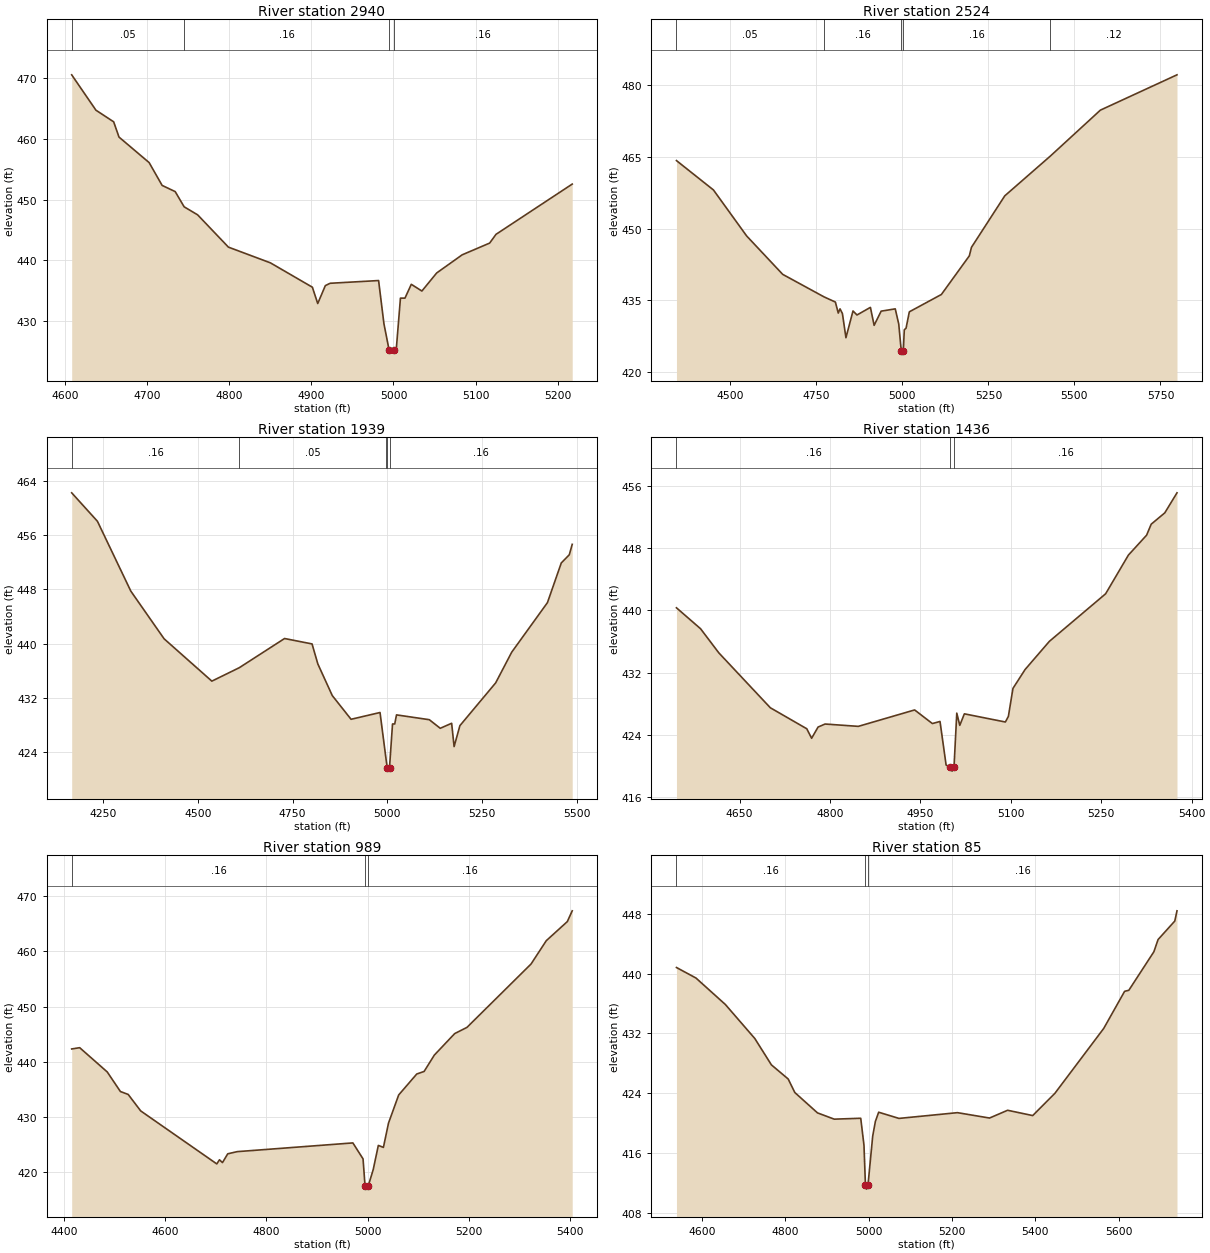
Type RM Length L Ch R = 1,2940,416,416,416
BEGIN DESCRIPTION:
UNT132 IN CCTC 6.0
END DESCRIPTION:
XS GIS Cut Line= 3
      3549999.61     10600710.19      3550349.61     10600910.19
      3550549.64     10600960.20
#Sta/Elev= 30
  4608.3  470.60  4637.8  464.77  4659.4  462.85  4665.9  460.33  4702.6  456.12
  4718.4  452.36  4734.3  451.34  4745.2  448.83  4761.6  447.51  4799.1  442.18
  4850.2  439.59  4901.3  435.57  4907.8  432.88  4917.1  435.84  4922.9  436.22
  4981.9  436.67  4988.4  429.54  4994.7  425.20  4997.5  424.70  5000.7  425.20
  5003.5  425.46  5008.5  433.77  5014.0  433.77  5021.7  436.05  5034.6  434.94
  5052.6  437.92  5083.6  440.91  5117.1  442.85  5124.8  444.29  5217.6  452.58
#Mann=4,-1,0
  4608.3    0.05       0  4745.2    0.16       0  4994.7    0.07       0
  5000.7    0.16       0
Bank Sta=4994.7,5000.7
Exp/Cntr=0.3,0.1

Type RM Length L Ch R = 1,2524,585,585,585
BEGIN DESCRIPTION:
UNT132 IN CCTC 5.0
END DESCRIPTION:
XS GIS Cut Line= 4
      3549917.02     10600841.29      3550111.45     10601250.99
      3550417.01     10601316.96      3551085.87     10601154.08
#Sta/Elev= 30
  4343.6  464.22  4451.1  458.08  4547.5  448.48  4652.3  440.45  4772.0  435.76
  4805.4  434.66  4813.8  432.36  4818.9  433.24  4825.9  432.25  4836.1  427.21
  4856.6  432.80  4868.2  431.96  4907.2  433.55  4918.0  429.80  4938.4  432.76
  4979.4  433.24  4989.6  430.05  4996.8  424.49  4999.6  423.99  5002.8  424.49
  5005.7  428.87  5010.8  429.20  5020.3  432.62  5113.4  436.24  5194.7  444.32
  5200.8  446.09  5297.6  456.85  5430.5  465.19  5575.5  474.76  5798.1  482.14
#Mann=5,-1,0
  4343.6    0.05       0  4772.0    0.16       0  4996.8    0.07       0
  5002.8    0.16       0  5430.5    0.12       0
Bank Sta=4996.8,5002.8
Exp/Cntr=0.3,0.1

Type RM Length L Ch R = 1,1939,503,503,503
BEGIN DESCRIPTION:
UNT132 IN CCTC 4.0
END DESCRIPTION:
XS GIS Cut Line= 3
      3549349.61     10601310.19      3550099.61     10601710.19
      3550499.61     10601960.19
#Sta/Elev= 30
  4166.9  462.26  4234.9  458.06  4323.1  447.75  4410.9  440.72  4537.0  434.47
  4609.4  436.45  4729.0  440.76  4801.6  439.96  4816.8  437.02  4855.0  432.34
  4904.6  428.84  4981.1  429.84  4997.0  422.96  5000.1  421.69  5002.8  421.19
  5006.1  421.69  5014.1  428.15  5019.9  428.15  5024.6  429.49  5111.2  428.78
  5140.1  427.51  5170.2  428.25  5176.7  424.81  5192.0  427.90  5286.4  434.21
  5328.8  438.74  5423.2  446.06  5459.7  451.91  5480.9  453.12  5488.6  454.66
#Mann=5,-1,0
  4166.9    0.16       0  4609.4    0.05       0  4997.0    0.16       0
  5000.1    0.07       0  5006.1    0.16       0
Bank Sta=5000.1,5006.1
Exp/Cntr=0.3,0.1

Type RM Length L Ch R = 1,1436,447,447,447
BEGIN DESCRIPTION:
UNT132 IN CCTC 3.0
END DESCRIPTION:
XS GIS Cut Line= 3
      3549699.64     10602210.18      3550099.61     10602060.19
      3550499.63     10602010.19
#Sta/Elev= 30
  4545.4  440.34  4585.4  437.65  4615.7  434.55  4701.1  427.50  4761.6  424.80
  4769.6  423.58  4780.3  425.02  4791.9  425.41  4847.1  425.11  4940.5  427.22
  4969.9  425.47  4982.6  425.74  4992.7  420.14  4999.8  419.86  5002.6  419.36
  5005.8  419.86  5010.4  426.81  5015.4  425.24  5023.0  426.72  5091.0  425.67
  5096.0  426.39  5103.6  429.99  5123.7  432.41  5164.0  436.03  5257.3  442.14
  5295.1  447.11  5325.3  449.67  5332.9  451.08  5355.5  452.54  5375.7  455.11
#Mann=3,-1,0
  4545.4    0.16       0  4999.8    0.07       0  5005.8    0.16       0
Bank Sta=4999.8,5005.8
Exp/Cntr=0.3,0.1

Type RM Length L Ch R = 1,989,904,904,904
BEGIN DESCRIPTION:
UNT132 IN CCTC 2.0
END DESCRIPTION:
XS GIS Cut Line= 3
      3549691.75     10602260.48      3550188.30     10602392.43
      3550660.53     10602343.81
#Sta/Elev= 30
  4415.7  442.35  4431.5  442.58  4485.9  438.19  4511.9  434.65  4527.3  434.12
  4552.0  431.14  4702.3  421.55  4707.5  422.30  4713.5  421.79  4723.9  423.38
  4742.5  423.77  4971.0  425.35  4991.1  422.46  4995.1  417.49  4997.9  416.99
  5001.1  417.49  5011.2  420.53  5021.3  424.90  5031.3  424.54  5041.4  428.94
  5061.5  434.03  5097.2  437.82  5111.7  438.28  5131.9  441.24  5172.1  445.13
  5196.3  446.25  5322.9  457.72  5353.0  461.94  5394.5  465.39  5404.2  467.34
#Mann=3,-1,0
  4415.7    0.16       0  4995.1    0.07       0  5001.1    0.16       0
Bank Sta=4995.1,5001.1
Exp/Cntr=0.3,0.1

Type RM Length L Ch R = 1,85,0,0,0
BEGIN DESCRIPTION:
UNT132 IN CCTC 1.0
END DESCRIPTION:
XS GIS Cut Line= 4
      3549666.51     10602343.60      3549708.18     10602763.77
      3549775.89     10602819.32      3550464.91     10602864.45
#Sta/Elev= 30
  4539.3  440.83  4586.1  439.42  4656.5  435.88  4727.2  431.32  4767.0  427.79
  4807.2  425.90  4823.1  424.09  4877.5  421.36  4917.7  420.52  4981.2  420.64
  4989.0  417.02  4992.5  411.65  4995.3  411.15  4998.5  411.65  5009.9  418.25
  5016.3  420.21  5024.2  421.45  5072.9  420.62  5213.2  421.39  5290.1  420.67
  5333.4  421.71  5393.6  421.00  5446.8  423.98  5563.9  432.67  5614.0  437.64
  5624.1  437.78  5684.2  442.94  5694.2  444.57  5734.3  447.05  5739.6  448.42
#Mann=3,-1,0
  4539.3    0.16       0  4992.5    0.07       0  4998.5    0.16       0
Bank Sta=4992.5,4998.5
Exp/Cntr=0.3,0.1

Chan Stop Cuts=-1