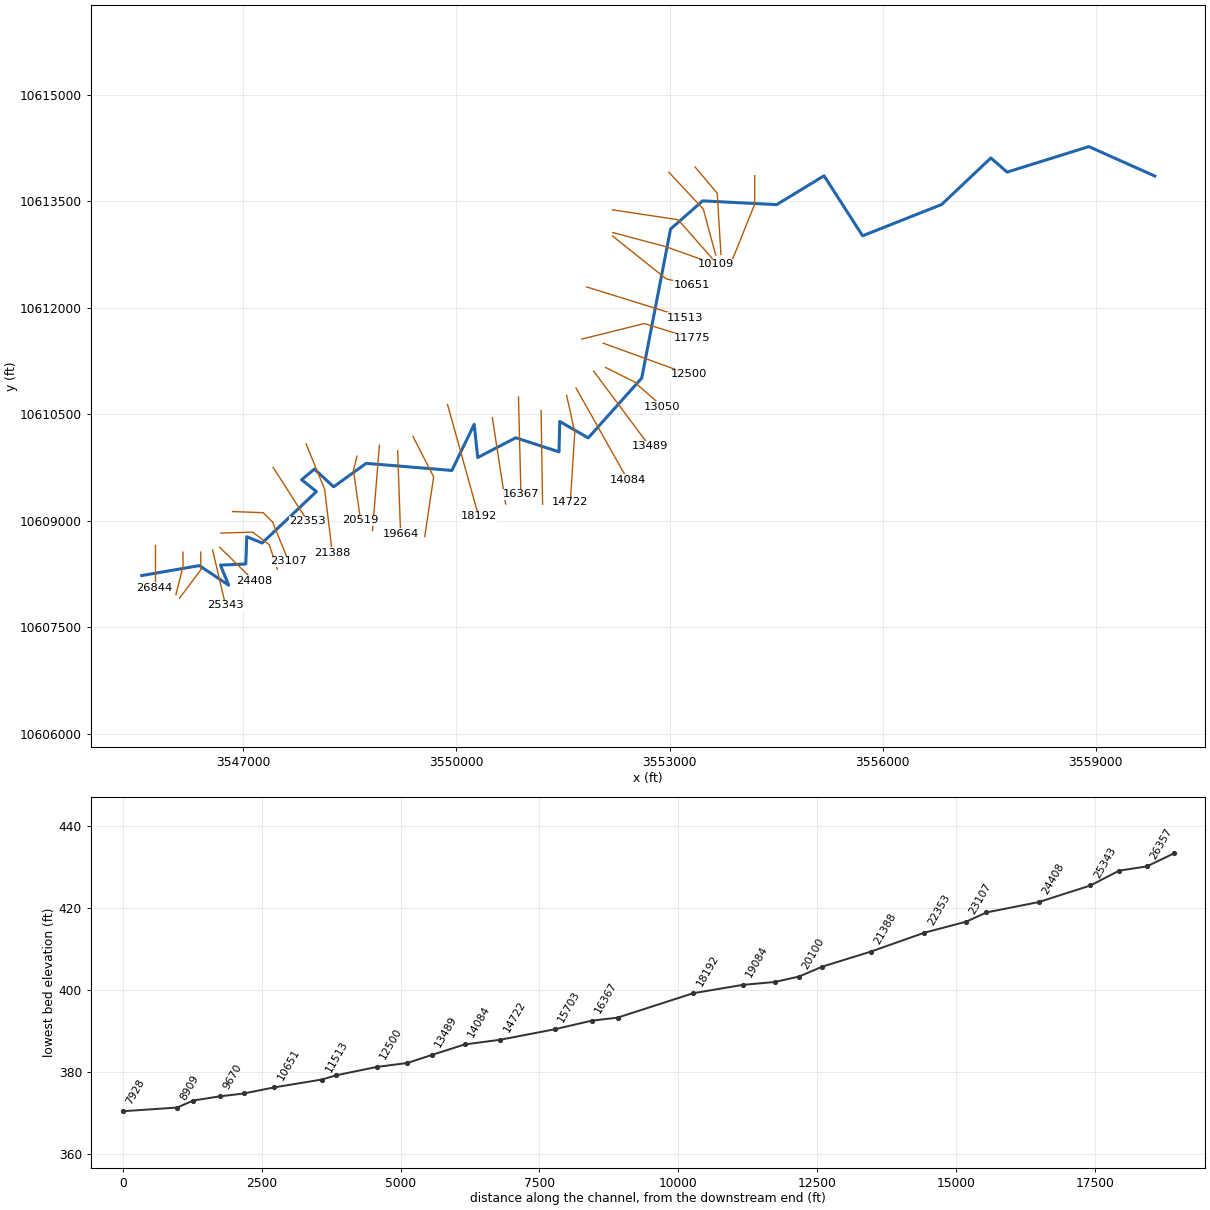
--- UNT133 IN CCTC.prj (project) ---

Proj Title=UNT133 IN CCTC Base Level Engineering
Current Plan=p01
Default Exp/Contr=0.3,0.1
English Units
Geom File=g01
Flow File=f01
Plan File=p01
BEGIN DESCRIPTION:
UNT133 IN CCTC
END DESCRIPTION:

--- UNT133 IN CCTC.p01 (plan) ---

Plan Title=Multiple Run
Short Identifier=Multiple
Geom File=g01
Flow File=f01
Subcritical Flow
K Sum by GR= 0
Std Step Tol= 0.01
Critical Tol= 0.01
Num of Std Step Trials= 20
Max Error Tol= 0.3
Flow Tol Ratio= 0.001
Split Flow NTrial= 30
Split Flow Tol= 0.02
Split Flow Ratio= 0.02
Log Output Level= 0
Friction Slope Method= 1
Unsteady Friction Slope Method= 2
Unsteady Bridges Friction Slope Method= 1
Parabolic Critical Depth
Global Vel Dist=  1 , 1 , 1
Global Log Level= 0
CheckData=True
Encroach Param= -1, 0, 0, 0
BEGIN DESCRIPTION:
Multiple Run
END DESCRIPTION:

--- UNT133 IN CCTC.f01 (steady flow) ---

Flow Title=Multiple
Number of Profiles=7
Profile Names=10-year,25-year,50-year,1pct_min,100-year,1pct_plu,500-year
River Rch & RM= UNT133 IN CCTC,Reach-1,26844
    2102    2966    3698    3360    4544    6146    6844
River Rch & RM= UNT133 IN CCTC,Reach-1,20519
    2721    3875    4859    4437    6000    8114    9125
River Rch & RM= UNT133 IN CCTC,Reach-1,12500
    2844    4048    5073    4627    6258    8463    9499
River Rch & RM= UNT133 IN CCTC,Reach-1,9198
    4235    6111    7731    7107    9611   12998   14821
Boundary for River Rch & Prof#=UNT133 IN CCTC,Reach-1,1
Up Type=0
Dn Type=3
Dn Slope=0.005
Boundary for River Rch & Prof#=UNT133 IN CCTC,Reach-1,2
Up Type=0
Dn Type=3
Dn Slope=0.005
Boundary for River Rch & Prof#=UNT133 IN CCTC,Reach-1,3
Up Type=0
Dn Type=3
Dn Slope=0.005
Boundary for River Rch & Prof#=UNT133 IN CCTC,Reach-1,4
Up Type=0
Dn Type=3
Dn Slope=0.005
Boundary for River Rch & Prof#=UNT133 IN CCTC,Reach-1,5
Up Type=0
Dn Type=3
Dn Slope=0.005
Boundary for River Rch & Prof#=UNT133 IN CCTC,Reach-1,6
Up Type=0
Dn Type=3
Dn Slope=0.005
Boundary for River Rch & Prof#=UNT133 IN CCTC,Reach-1,7
Up Type=0
Dn Type=3
Dn Slope=0.005

--- UNT133 IN CCTC.g01 (geometry) ---

Geom Title=Existing Conditions

River Reach=UNT133 IN CCTC,Reach-1
Reach XY= 30
      3545569.50     10608230.00      3546379.00     10608370.00
      3546792.00     10608095.00      3546677.25     10608377.00
      3547033.25     10608393.00      3547048.00     10608777.00
      3547264.00     10608688.00      3548028.50     10609413.00
      3547819.50     10609579.00      3548000.00     10609730.00
      3548269.50     10609480.00      3548729.25     10609810.00
      3549935.75     10609710.00      3550249.50     10610360.00
      3550299.50     10609892.00      3550834.75     10610170.00
      3551443.75     10609972.00      3551454.00     10610400.00
      3551855.25     10610168.00      3552608.75     10611011.00
      3553014.50     10613109.00      3553466.75     10613506.00
      3554508.50     10613453.00      3555176.00     10613859.00
      3555718.75     10613014.00      3556832.00     10613455.00
      3557524.75     10614110.00      3557753.50     10613911.00
      3558904.25     10614270.00      3559832.75     10613856.00

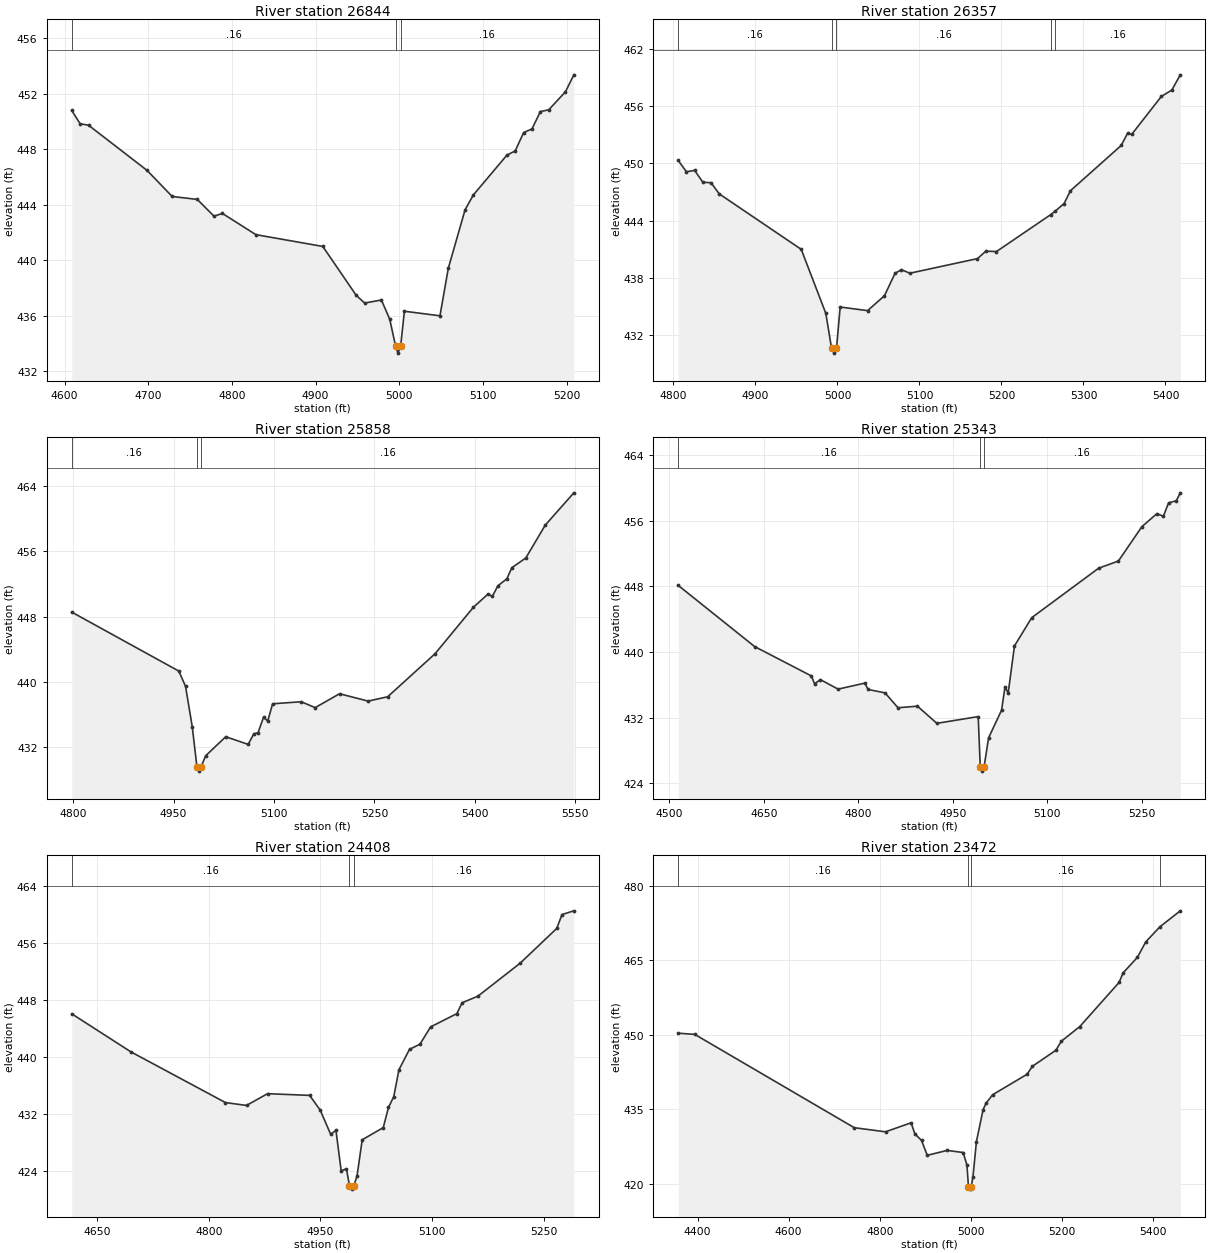
Type RM Length L Ch R = 1,26844,487,487,487
BEGIN DESCRIPTION:
UNT133 IN CCTC 48.0
END DESCRIPTION:
XS GIS Cut Line= 3
      3545749.61     10608660.21      3545749.61     10608260.19
      3545749.61     10608060.21
#Sta/Elev= 30
  4608.6  450.79  4618.6  449.83  4628.6  449.73  4698.6  446.47  4728.6  444.59
  4758.6  444.38  4778.6  443.17  4788.6  443.37  4828.6  441.84  4908.6  440.99
  4948.6  437.46  4958.6  436.91  4978.6  437.13  4988.6  435.74  4995.6  433.80
  4998.4  433.30  5001.6  433.80  5006.1  436.32  5048.6  435.99  5058.6  439.42
  5078.6  443.63  5088.6  444.71  5128.6  447.57  5138.6  447.88  5148.6  449.20
  5158.6  449.46  5168.6  450.71  5178.6  450.84  5198.6  452.14  5208.6  453.36
#Mann=3,-1,0
  4608.6    0.16       0  4995.6    0.07       0  5001.6    0.16       0
Bank Sta=4995.6,5001.6
Exp/Cntr=0.3,0.1

Type RM Length L Ch R = 1,26357,499,499,499
BEGIN DESCRIPTION:
UNT133 IN CCTC 47.0
END DESCRIPTION:
XS GIS Cut Line= 3
      3546149.61     10608560.19      3546149.61     10608360.19
      3546049.61     10607960.20
#Sta/Elev= 30
  4805.8  450.31  4815.8  449.13  4825.8  449.27  4835.8  448.03  4845.8  447.98
  4855.8  446.81  4955.8  441.00  4985.8  434.29  4992.8  430.63  4995.6  430.13
  4998.8  430.63  5003.3  434.96  5036.7  434.58  5057.3  436.14  5070.2  438.49
  5078.0  438.87  5088.3  438.50  5170.7  440.03  5181.0  440.81  5193.9  440.77
  5260.1  444.64  5265.4  444.99  5276.4  445.80  5284.1  447.14  5346.0  451.88
  5353.7  453.14  5358.8  453.04  5394.9  457.01  5407.8  457.69  5418.1  459.28
#Mann=5,-1,0
  4805.8    0.16       0  4992.8    0.07       0  4998.8    0.16       0
  5260.1    0.12       0  5265.4    0.16       0
Bank Sta=4992.8,4998.8
Exp/Cntr=0.3,0.1

Type RM Length L Ch R = 1,25858,515,515,515
BEGIN DESCRIPTION:
UNT133 IN CCTC 46.0
END DESCRIPTION:
XS GIS Cut Line= 3
      3546399.61     10608560.22      3546399.61     10608310.19
      3546099.63     10607910.21
#Sta/Elev= 30
  4797.9  448.55  4957.9  441.33  4967.9  439.45  4977.9  434.51  4984.9  429.59
  4987.7  429.09  4990.9  429.59  4997.9  430.97  5027.9  433.30  5061.5  432.36
  5069.8  433.66  5076.1  433.78  5084.4  435.69  5090.6  435.21  5097.9  437.33
  5140.6  437.58  5161.5  436.86  5197.9  438.56  5240.6  437.66  5269.8  438.19
  5340.6  443.46  5397.9  449.15  5419.8  450.77  5426.1  450.47  5434.4  451.77
  5447.9  452.63  5455.2  453.98  5476.1  455.17  5505.2  459.20  5547.9  463.15
#Mann=3,-1,0
  4797.9    0.16       0  4984.9    0.07       0  4990.9    0.16       0
Bank Sta=4984.9,4990.9
Exp/Cntr=0.3,0.1

Type RM Length L Ch R = 1,25343,935,935,935
BEGIN DESCRIPTION:
Mapping XS e64eeba4
END DESCRIPTION:
XS GIS Cut Line= 2
      3546566.10     10608589.81      3546748.13     10607813.98
#Sta/Elev= 30
  4514.1  448.13  4635.4  440.67  4725.4  437.09  4730.5  436.13  4739.7  436.64
  4767.8  435.48  4810.2  436.21  4815.4  435.44  4842.4  435.02  4862.9  433.21
  4893.8  433.40  4924.6  431.31  4990.2  432.13  4993.5  425.98  4996.2  425.48
  4999.5  425.98  5006.7  429.54  5027.3  432.91  5032.7  435.74  5037.8  435.01
  5047.8  440.75  5075.1  444.19  5181.4  450.23  5212.7  451.10  5250.0  455.29
  5273.8  456.88  5284.1  456.56  5292.4  458.20  5304.6  458.45  5311.0  459.42
#Mann=3,-1,0
  4514.1    0.16       0  4993.5    0.07       0  4999.5    0.16       0
Bank Sta=4993.5,4999.5
Exp/Cntr=0.3,0.1

Type RM Length L Ch R = 1,24408,936,936,936
BEGIN DESCRIPTION:
UNT133 IN CCTC 45.0
END DESCRIPTION:
XS GIS Cut Line= 2
      3546665.91     10608628.85      3547147.67     10608155.77
#Sta/Elev= 30
  4615.6  446.03  4695.0  440.70  4822.3  433.57  4850.6  433.17  4878.9  434.82
  4935.5  434.58  4949.6  432.53  4963.8  429.12  4970.9  429.67  4977.9  423.98
  4985.0  424.28  4989.0  421.92  4991.8  421.42  4995.0  421.92  4999.2  423.25
  5006.2  428.35  5034.5  430.06  5041.5  432.88  5048.6  434.40  5055.6  438.18
  5069.8  441.05  5083.9  441.77  5098.1  444.19  5133.5  446.06  5140.5  447.58
  5161.8  448.51  5218.4  453.12  5267.8  458.02  5274.9  459.97  5290.8  460.49
#Mann=3,-1,0
  4615.6    0.16       0  4989.0    0.07       0  4995.0    0.16       0
Bank Sta=4989,4995
Exp/Cntr=0.3,0.1

Type RM Length L Ch R = 1,23472,365,365,365
BEGIN DESCRIPTION:
UNT133 IN CCTC 44.0
END DESCRIPTION:
XS GIS Cut Line= 4
      3546683.28     10608828.48      3547130.34     10608841.50
      3547364.72     10608663.55      3547477.56     10608320.67
#Sta/Elev= 30
  4357.6  450.33  4393.9  450.09  4744.1  431.29  4812.8  430.46  4868.9  432.28
  4877.2  430.05  4891.8  428.73  4904.4  425.72  4948.0  426.71  4983.3  426.29
  4991.6  423.73  4994.9  419.41  4997.6  418.91  5000.9  419.41  5004.8  421.38
  5012.4  428.50  5027.0  434.91  5033.2  436.17  5047.8  437.92  5123.7  442.06
  5135.1  443.65  5186.9  446.89  5198.7  448.70  5239.5  451.68  5325.9  460.59
  5334.3  462.47  5365.9  465.62  5384.2  468.73  5415.4  471.78  5460.1  474.99
#Mann=4,-1,0
  4357.6    0.16       0  4994.9    0.07       0  5000.9    0.16       0
  5415.4    0.12       0
Bank Sta=4994.9,5000.9
Exp/Cntr=0.3,0.1

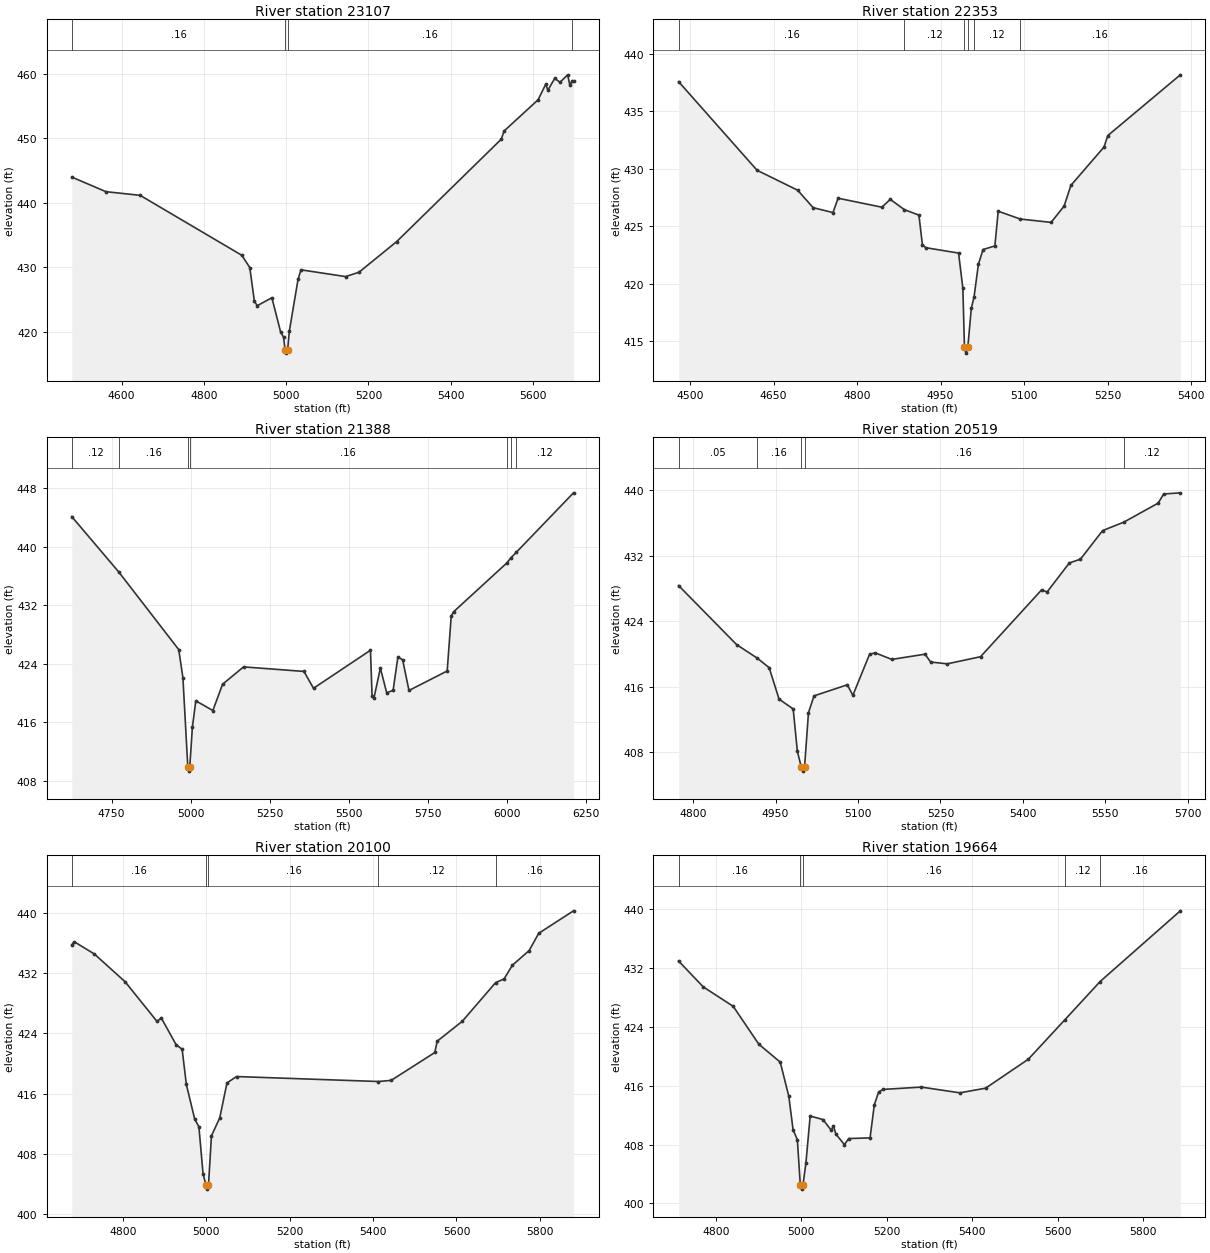
Type RM Length L Ch R = 1,23107,754,754,754
BEGIN DESCRIPTION:
UNT133 IN CCTC 43.0
END DESCRIPTION:
XS GIS Cut Line= 4
      3546846.69     10609131.13      3547278.98     10609115.50
      3547409.19     10608985.29      3547638.36     10608427.99
#Sta/Elev= 30
  4479.0  444.00  4562.0  441.73  4645.2  441.16  4892.2  431.85  4911.6  429.95
  4922.8  424.70  4929.9  424.02  4965.3  425.26  4986.5  419.95  4993.6  419.14
  4997.6  417.15  5000.4  416.65  5003.6  417.15  5007.7  420.05  5028.9  428.11
  5036.0  429.59  5144.5  428.54  5176.9  429.21  5268.3  433.96  5522.9  449.89
  5529.5  451.15  5612.2  456.00  5630.7  458.41  5636.1  457.50  5652.7  459.33
  5665.5  458.72  5684.1  459.88  5689.5  458.25  5695.1  458.93  5698.3  458.93
#Mann=4,-1,0
  4479.0    0.16       0  4997.6    0.07       0  5003.6    0.16       0
  5695.1    0.12       0
Bank Sta=4997.6,5003.6
Exp/Cntr=0.3,0.1

Type RM Length L Ch R = 1,22353,965,965,965
BEGIN DESCRIPTION:
UNT133 IN CCTC 42.0
END DESCRIPTION:
XS GIS Cut Line= 2
      3547418.44     10609753.76      3547904.23     10608994.70
#Sta/Elev= 30
  4479.5  437.57  4620.5  429.86  4693.3  428.13  4721.2  426.61  4756.8  426.18
  4766.0  427.43  4844.6  426.65  4859.8  427.33  4884.9  426.44  4911.2  425.96
  4917.4  423.40  4923.3  423.13  4982.4  422.66  4990.1  419.60  4993.0  414.46
  4995.8  413.96  4999.0  414.46  5005.3  417.87  5010.1  418.81  5018.0  421.68
  5026.4  422.97  5047.6  423.28  5053.6  426.30  5093.2  425.62  5148.6  425.33
  5171.9  426.74  5184.2  428.55  5243.6  431.88  5250.5  432.88  5380.7  438.16
#Mann=6,-1,0
  4479.5    0.16       0  4884.9    0.12       0  4993.0    0.07       0
  4999.0    0.12       0  5010.1    0.12       0  5093.2    0.16       0
Bank Sta=4993,4999
Exp/Cntr=0.3,0.1

Type RM Length L Ch R = 1,21388,869,869,869
BEGIN DESCRIPTION:
UNT133 IN CCTC 41.0
END DESCRIPTION:
XS GIS Cut Line= 3
      3547882.82     10610083.67      3548143.25     10609445.62
      3548251.54     10608553.32
#Sta/Elev= 30
  4623.9  444.09  4773.5  436.48  4962.5  425.93  4975.7  422.10  4991.3  409.84
  4994.0  409.34  4997.3  409.84  5005.7  415.33  5016.5  418.94  5070.5  417.61
  5101.2  421.20  5167.7  423.57  5358.8  422.95  5389.0  420.65  5569.3  425.84
  5574.4  419.57  5580.4  419.33  5600.6  423.40  5620.7  420.04  5640.9  420.36
  5656.2  424.94  5671.1  424.53  5691.2  420.35  5812.1  423.01  5824.8  430.46
  5832.3  431.09  6000.7  437.75  6014.7  438.50  6030.4  439.19  6211.9  447.33
#Mann=7,-1,0
  4623.9    0.12       0  4773.5    0.16       0  4991.3    0.07       0
  4997.3    0.16       0  6000.7    0.12       0  6014.7    0.16       0
  6030.4    0.12       0
Bank Sta=4991.3,4997.3
Exp/Cntr=0.3,0.1

Type RM Length L Ch R = 1,20519,419,419,419
BEGIN DESCRIPTION:
UNT133 IN CCTC 39.0
END DESCRIPTION:
XS GIS Cut Line= 3
      3548599.60     10609910.16      3548549.61     10609710.19
      3548649.60     10609010.22
#Sta/Elev= 30
  4773.5  428.36  4879.1  421.15  4916.8  419.49  4938.4  418.33  4956.4  414.49
  4982.1  413.29  4989.7  408.12  4996.8  406.20  4999.6  405.70  5002.8  406.20
  5009.9  412.83  5020.0  414.89  5080.6  416.24  5090.7  414.95  5121.0  419.95
  5131.1  420.15  5161.5  419.34  5222.1  419.98  5232.2  419.02  5262.5  418.80
  5323.1  419.67  5434.2  427.83  5444.3  427.58  5484.7  431.12  5504.9  431.58
  5545.3  435.07  5583.9  436.10  5646.3  438.42  5656.4  439.54  5686.7  439.68
#Mann=5,-1,0
  4773.5    0.05       0  4916.8    0.16       0  4996.8    0.07       0
  5002.8    0.16       0  5583.9    0.12       0
Bank Sta=4996.8,5002.8
Exp/Cntr=0.3,0.1

Type RM Length L Ch R = 1,20100,436,436,436
BEGIN DESCRIPTION:
UNT133 IN CCTC 38.0
END DESCRIPTION:
XS GIS Cut Line= 2
      3548914.83     10610064.26      3548817.71     10608864.08
#Sta/Elev= 30
  4676.8  435.78  4682.7  436.20  4731.0  434.57  4804.9  430.87  4881.5  425.59
  4891.6  426.06  4927.1  422.51  4941.7  421.89  4951.8  417.21  4971.8  412.60
  4981.9  411.59  4991.9  405.34  4998.9  403.78  5001.7  403.28  5004.9  403.78
  5012.0  410.36  5032.0  412.77  5049.3  417.41  5072.2  418.26  5412.4  417.60
  5443.4  417.75  5548.1  421.46  5553.7  422.96  5613.9  425.61  5694.0  430.76
  5714.3  431.25  5734.3  433.08  5774.4  435.02  5797.4  437.32  5880.9  440.31
#Mann=5,-1,0
  4676.8    0.16       0  4998.9    0.07       0  5004.9    0.16       0
  5412.4    0.12       0  5694.0    0.16       0
Bank Sta=4998.9,5004.9
Exp/Cntr=0.3,0.1

Type RM Length L Ch R = 1,19664,580,580,580
BEGIN DESCRIPTION:
UNT133 IN CCTC 37.0
END DESCRIPTION:
XS GIS Cut Line= 2
      3549171.78     10609987.90      3549213.43     10608814.73
#Sta/Elev= 30
  4712.9  432.94  4770.6  429.42  4840.7  426.78  4900.7  421.63  4950.8  419.20
  4970.8  414.56  4980.8  410.02  4990.8  408.67  4997.8  402.45  5000.5  401.95
  5003.8  402.45  5010.8  405.48  5020.8  411.88  5050.8  411.40  5070.2  409.94
  5075.2  410.57  5080.8  409.43  5100.9  408.00  5110.9  408.82  5160.9  408.91
  5170.9  413.41  5180.9  415.13  5190.9  415.49  5281.0  415.81  5371.0  415.03
  5431.1  415.66  5531.1  419.59  5616.6  424.95  5699.2  430.15  5886.8  439.75
#Mann=5,-1,0
  4712.9    0.16       0  4997.8    0.07       0  5003.8    0.16       0
  5616.6    0.12       0  5699.2    0.16       0
Bank Sta=4997.8,5003.8
Exp/Cntr=0.3,0.1

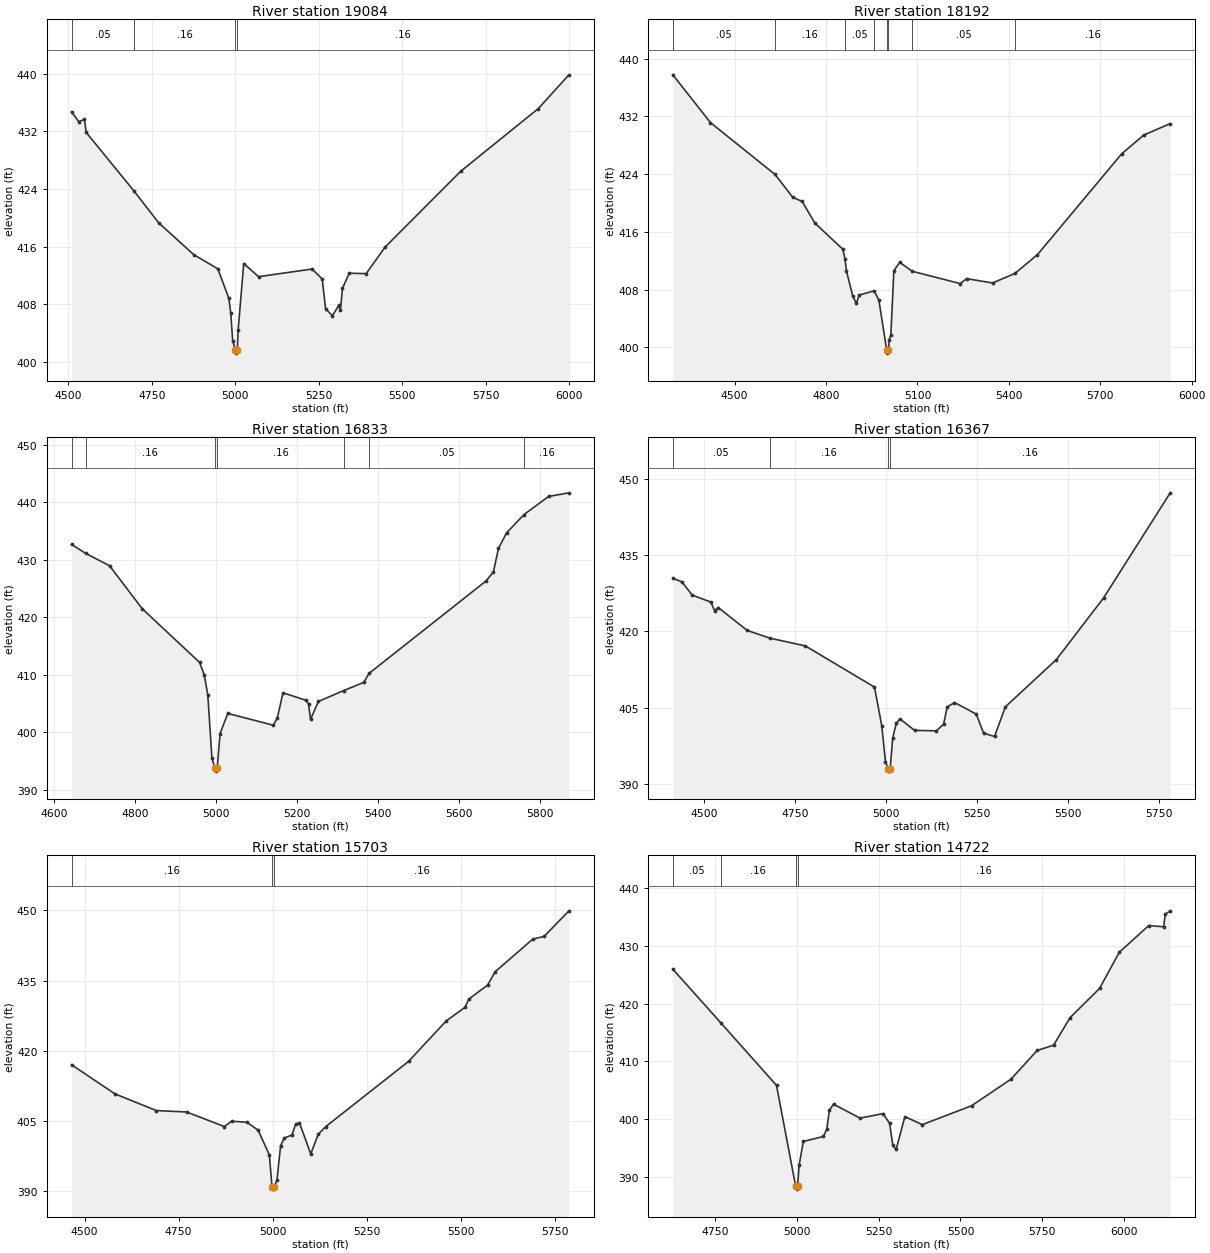
Type RM Length L Ch R = 1,19084,892,892,892
BEGIN DESCRIPTION:
UNT133 IN CCTC 36.0
END DESCRIPTION:
XS GIS Cut Line= 3
      3549387.07     10610189.27      3549678.72     10609619.84
      3549553.72     10608779.56
#Sta/Elev= 30
  4509.5  434.73  4531.3  433.35  4547.9  433.69  4553.5  431.86  4697.1  423.71
  4769.9  419.35  4875.3  414.91  4947.5  412.94  4980.4  408.86  4986.3  406.79
  4992.0  402.95  4999.8  401.74  5002.6  401.24  5005.8  401.74  5008.5  404.51
  5025.1  413.67  5069.5  411.85  5229.8  412.91  5260.1  411.53  5270.2  407.42
  5290.5  406.42  5309.4  407.85  5314.5  407.16  5320.8  410.24  5341.0  412.33
  5391.6  412.27  5448.1  415.94  5674.6  426.47  5907.2  435.18  5998.8  439.86
#Mann=4,-1,0
  4509.5    0.05       0  4697.1    0.16       0  4999.8    0.07       0
  5005.8    0.16       0
Bank Sta=4999.8,5005.8
Exp/Cntr=0.3,0.1

Type RM Length L Ch R = 1,18192,1359,1359,1359
BEGIN DESCRIPTION:
UNT133 IN CCTC 35.0
END DESCRIPTION:
XS GIS Cut Line= 2
      3549874.16     10610639.19      3550311.65     10609066.30
#Sta/Elev= 30
  4297.1  437.76  4420.6  431.14  4632.7  423.95  4690.5  420.80  4721.6  420.21
  4763.1  417.23  4855.0  413.59  4862.1  412.26  4866.9  410.58  4887.7  407.08
  4899.6  406.10  4908.5  407.24  4957.6  407.83  4973.2  406.55  4998.9  399.70
  5001.6  399.20  5004.9  399.70  5007.4  401.08  5012.6  401.72  5022.6  410.63
  5041.7  411.78  5082.9  410.54  5240.6  408.83  5261.4  409.52  5346.6  408.92
  5420.4  410.25  5493.9  412.85  5770.0  426.80  5842.6  429.41  5929.7  431.00
#Mann=8,-1,0
  4297.1    0.05       0  4632.7    0.16       0  4862.1    0.05       0
  4957.6    0.16       0  4998.9    0.07       0  5004.9    0.16       0
  5082.9    0.05       0  5420.4    0.16       0
Bank Sta=4998.9,5004.9
Exp/Cntr=0.3,0.1

Type RM Length L Ch R = 1,16833,466,466,466
BEGIN DESCRIPTION:
UNT133 IN CCTC 33.0
END DESCRIPTION:
XS GIS Cut Line= 2
      3550505.12     10610453.13      3550692.61     10609237.91
#Sta/Elev= 30
  4642.9  432.65  4678.1  431.10  4736.9  428.95  4817.9  421.46  4959.5  412.15
  4971.1  409.95  4979.8  406.48  4989.9  395.59  4997.0  393.75  4999.8  393.25
  5003.0  393.75  5010.1  399.79  5029.2  403.28  5141.7  401.23  5151.8  402.54
  5165.6  406.87  5222.6  405.56  5228.7  404.94  5233.8  402.24  5253.0  405.36
  5315.5  407.25  5365.1  408.67  5378.7  410.26  5667.8  426.32  5685.9  427.88
  5698.2  431.96  5718.4  434.68  5761.6  437.86  5822.3  441.00  5872.5  441.63
#Mann=7,-1,0
  4642.9    0.05       0  4678.1    0.16       0  4997.0    0.07       0
  5003.0    0.16       0  5315.5     0.1       0  5378.7    0.05       0
  5761.6    0.16       0
Bank Sta=4997,5003
Exp/Cntr=0.3,0.1

Type RM Length L Ch R = 1,16367,664,664,664
BEGIN DESCRIPTION:
UNT133 IN CCTC 32.0
END DESCRIPTION:
XS GIS Cut Line= 2
      3550873.17     10610744.86      3550907.89     10609376.80
#Sta/Elev= 30
  4413.1  430.41  4437.8  429.75  4466.3  427.13  4517.8  425.74  4527.8  424.08
  4537.8  424.68  4617.8  420.17  4679.3  418.68  4777.9  417.12  4967.9  409.03
  4988.0  401.39  4998.0  394.40  5005.0  393.01  5007.7  392.51  5011.0  393.01
  5018.0  399.05  5028.0  401.96  5038.0  402.78  5078.0  400.53  5138.0  400.43
  5158.0  401.73  5168.0  405.14  5188.0  406.00  5248.0  403.72  5268.0  399.97
  5298.1  399.32  5328.1  405.16  5468.1  414.43  5598.1  426.56  5781.6  447.23
#Mann=4,-1,0
  4413.1    0.05       0  4679.3    0.16       0  5005.0    0.07       0
  5011.0    0.16       0
Bank Sta=5005,5011
Exp/Cntr=0.3,0.1

Type RM Length L Ch R = 1,15703,981,981,981
BEGIN DESCRIPTION:
UNT133 IN CCTC 31.0
END DESCRIPTION:
XS GIS Cut Line= 2
      3551191.86     10610555.90      3551212.68     10609234.06
#Sta/Elev= 30
  4465.3  417.00  4581.0  410.76  4691.0  407.20  4771.0  406.91  4871.1  403.80
  4891.1  404.93  4931.1  404.72  4961.1  403.04  4991.1  397.73  4998.1  390.92
  5000.8  390.42  5004.1  390.92  5011.1  392.33  5021.1  399.73  5031.1  401.34
  5051.1  402.00  5061.1  404.31  5071.1  404.58  5101.1  397.94  5121.1  402.16
  5141.1  403.79  5361.1  417.72  5461.1  426.36  5511.1  429.27  5521.1  431.02
  5571.1  434.02  5591.1  436.86  5691.2  443.85  5721.2  444.41  5787.3  449.89
#Mann=3,-1,0
  4465.3    0.16       0  4998.1    0.07       0  5004.1    0.16       0
Bank Sta=4998.1,5004.1
Exp/Cntr=0.3,0.1

Type RM Length L Ch R = 1,14722,638,638,638
BEGIN DESCRIPTION:
UNT133 IN CCTC 30.0
END DESCRIPTION:
XS GIS Cut Line= 3
      3551551.24     10610769.41      3551665.82     10610248.57
      3551603.35     10609264.65
#Sta/Elev= 30
  4621.5  425.95  4767.9  416.67  4938.1  405.83  4996.6  388.36  4999.3  387.86
  5002.6  388.36  5007.1  391.98  5020.0  396.11  5081.5  396.98  5091.7  398.25
  5099.7  401.55  5112.2  402.57  5193.3  400.16  5263.4  400.94  5283.4  399.27
  5293.5  395.42  5303.5  394.73  5330.1  400.42  5383.6  399.03  5533.9  402.30
  5654.2  406.90  5734.3  411.88  5784.4  412.79  5834.5  417.55  5924.7  422.61
  5984.8  428.86  6075.0  433.51  6120.5  433.30  6125.5  435.48  6140.7  436.06
#Mann=4,-1,0
  4621.5    0.05       0  4767.9    0.16       0  4996.6    0.07       0
  5002.6    0.16       0
Bank Sta=4996.6,5002.6
Exp/Cntr=0.3,0.1

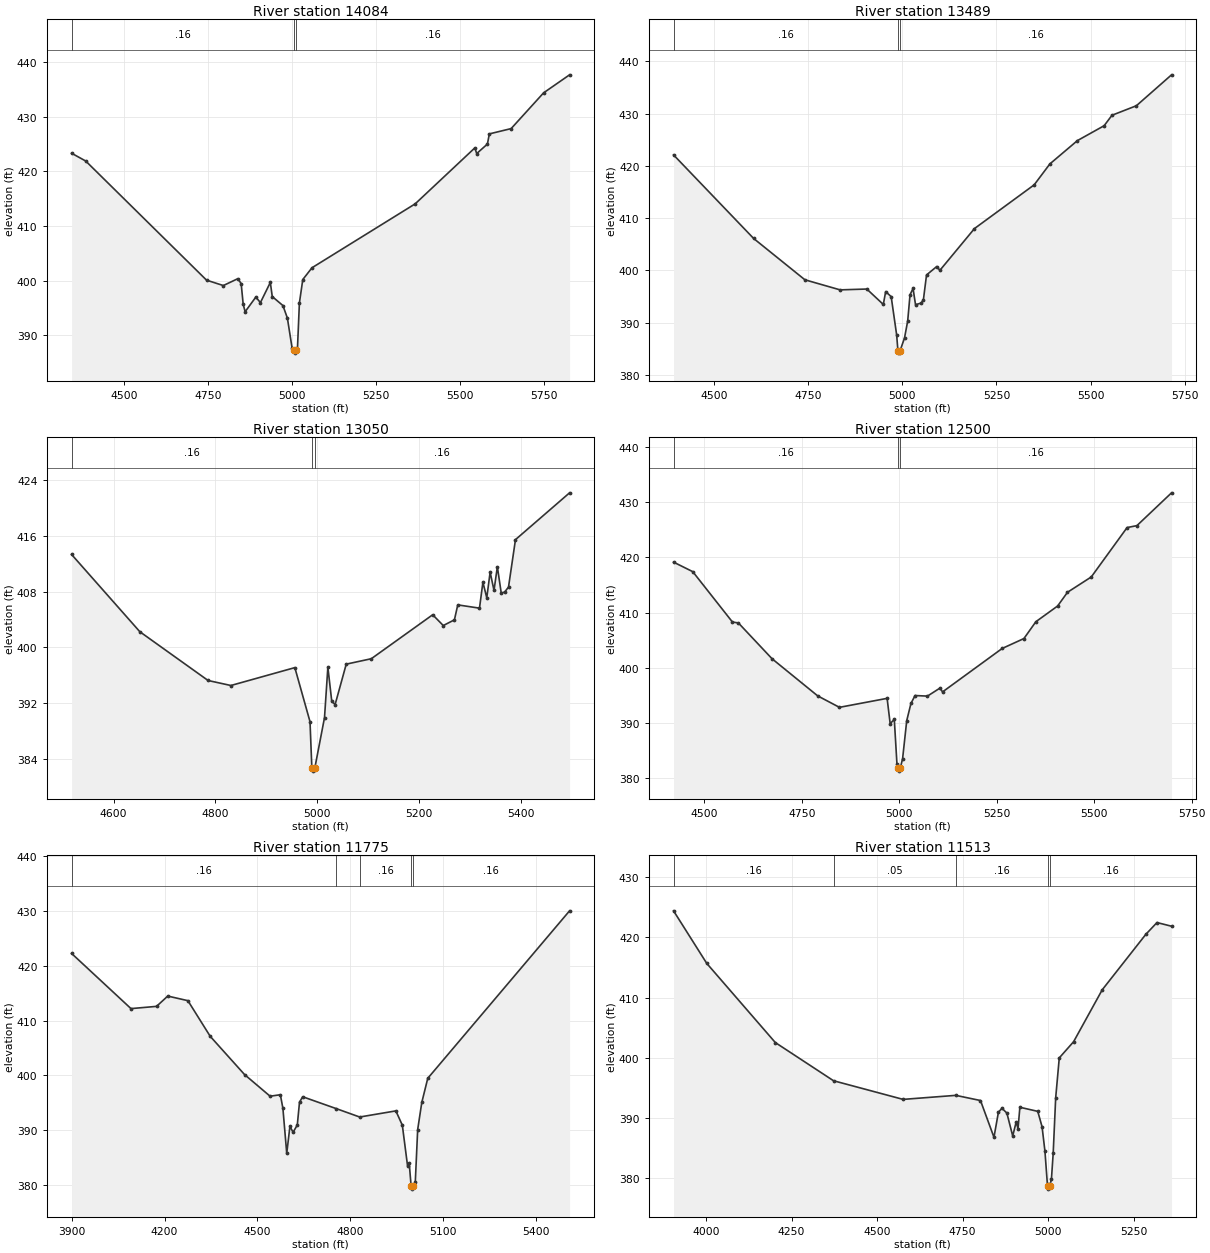
Type RM Length L Ch R = 1,14084,595,595,595
BEGIN DESCRIPTION:
UNT133 IN CCTC 28.0
END DESCRIPTION:
XS GIS Cut Line= 2
      3551683.17     10610870.72      3552412.35     10609577.30
#Sta/Elev= 30
  4342.4  423.34  4384.6  421.91  4744.8  400.09  4794.9  399.10  4838.2  400.36
  4848.1  399.45  4854.1  395.67  4859.9  394.30  4891.7  396.98  4905.5  395.98
  4935.0  399.67  4940.8  397.08  4972.6  395.43  4985.9  393.13  5000.0  387.62
  5005.8  387.22  5008.6  386.72  5011.8  387.22  5015.9  387.54  5021.7  395.91
  5031.8  400.20  5059.3  402.36  5367.0  414.07  5544.7  424.31  5550.4  423.28
  5582.3  425.02  5588.0  426.88  5653.0  427.85  5749.8  434.40  5827.2  437.70
#Mann=3,-1,0
  4342.4    0.16       0  5005.8    0.07       0  5011.8    0.16       0
Bank Sta=5005.8,5011.8
Exp/Cntr=0.3,0.1

Type RM Length L Ch R = 1,13489,439,439,439
BEGIN DESCRIPTION:
UNT133 IN CCTC 27.0
END DESCRIPTION:
XS GIS Cut Line= 2
      3551930.53     10611109.50      3552720.47     10610050.46
#Sta/Elev= 30
  4393.3  422.10  4605.8  406.10  4741.8  398.19  4835.2  396.26  4906.0  396.42
  4949.8  393.47  4956.1  395.93  4970.7  394.96  4985.3  387.59  4988.5  384.65
  4991.3  384.15  4994.5  384.65  5006.1  387.06  5014.5  390.30  5020.7  395.32
  5028.7  396.53  5035.3  393.42  5049.9  393.73  5056.1  394.33  5064.5  399.12
  5091.6  400.73  5099.9  400.00  5191.7  408.00  5350.1  416.37  5391.8  420.38
  5464.8  424.84  5535.7  427.69  5556.5  429.69  5621.2  431.51  5714.5  437.43
#Mann=3,-1,0
  4393.3    0.16       0  4988.5    0.07       0  4994.5    0.16       0
Bank Sta=4988.5,4994.5
Exp/Cntr=0.3,0.1

Type RM Length L Ch R = 1,13050,550,550,550
BEGIN DESCRIPTION:
UNT133 IN CCTC 26.0
END DESCRIPTION:
XS GIS Cut Line= 3
      3552099.60     10611160.19      3552499.61     10610960.19
      3552899.58     10610610.21
#Sta/Elev= 30
  4517.3  413.34  4651.5  402.23  4785.6  395.22  4830.4  394.50  4956.1  397.07
  4985.9  389.30  4989.5  382.69  4992.3  382.19  4995.5  382.69  5014.4  389.88
  5021.0  397.14  5028.6  392.26  5035.2  391.75  5057.1  397.57  5106.4  398.35
  5227.0  404.67  5247.8  403.12  5269.7  403.94  5276.3  406.09  5319.0  405.62
  5325.7  409.35  5333.3  407.11  5339.9  410.80  5347.5  408.17  5354.1  411.57
  5361.7  407.80  5368.4  407.93  5376.0  408.65  5389.7  415.47  5496.0  422.20
#Mann=3,-1,0
  4517.3    0.16       0  4989.5    0.07       0  4995.5    0.16       0
Bank Sta=4989.5,4995.5
Exp/Cntr=0.3,0.1

Type RM Length L Ch R = 1,12500,725,725,725
BEGIN DESCRIPTION:
UNT133 IN CCTC 25.0
END DESCRIPTION:
XS GIS Cut Line= 2
      3552067.59     10611501.79      3553267.78     10611064.73
#Sta/Elev= 30
  4421.1  419.14  4470.4  417.41  4572.2  408.27  4587.4  408.11  4673.8  401.61
  4790.8  394.88  4846.6  392.80  4968.9  394.43  4976.7  389.84  4987.3  390.62
  4994.1  382.55  4996.5  381.73  4999.2  381.23  5002.5  381.73  5008.6  383.49
  5019.2  390.39  5030.0  393.50  5040.5  394.94  5072.4  394.84  5104.4  396.29
  5111.1  395.60  5264.0  403.48  5319.8  405.28  5350.4  408.33  5406.2  411.18
  5431.5  413.67  5492.5  416.45  5584.4  425.41  5609.6  425.76  5698.4  431.71
#Mann=3,-1,0
  4421.1    0.16       0  4996.5    0.07       0  5002.5    0.16       0
Bank Sta=4996.5,5002.5
Exp/Cntr=0.3,0.1

Type RM Length L Ch R = 1,11775,262,262,262
BEGIN DESCRIPTION:
UNT133 IN CCTC 24.0
END DESCRIPTION:
XS GIS Cut Line= 3
      3551764.80     10611559.77      3552644.99     10611778.52
      3553315.72     10611570.54
#Sta/Elev= 30
  3899.4  422.26  4091.4  412.18  4174.0  412.59  4210.2  414.47  4275.3  413.63
  4347.4  407.12  4458.3  400.14  4540.9  396.18  4574.1  396.45  4582.3  393.97
  4594.7  385.74  4605.0  390.67  4615.3  389.59  4628.8  390.93  4636.0  395.10
  4646.3  396.08  4755.4  393.90  4830.4  392.38  4947.3  393.50  4968.2  390.89
  4985.2  383.42  4990.4  383.98  4996.7  379.71  4999.4  379.21  5002.7  379.71
  5010.1  380.49  5017.8  390.08  5031.1  395.04  5050.4  399.45  5508.6  430.04
#Mann=5,-1,0
  3899.4    0.16       0  4755.4    0.05       0  4830.4    0.16       0
  4996.7    0.07       0  5002.7    0.16       0
Bank Sta=4996.7,5002.7
Exp/Cntr=0.3,0.1

Type RM Length L Ch R = 1,11513,862,862,862
BEGIN DESCRIPTION:
UNT133 IN CCTC 23.0
END DESCRIPTION:
XS GIS Cut Line= 2
      3551832.47     10612294.15      3553223.13     10611861.84
#Sta/Elev= 30
  3904.9  424.43  4001.9  415.70  4202.5  402.53  4372.7  396.18  4576.2  393.08
  4730.3  393.75  4802.5  392.89  4841.9  386.78  4854.9  390.94  4865.3  391.61
  4879.7  390.80  4896.7  387.00  4907.0  389.35  4912.2  388.21  4917.7  391.77
  4970.0  391.09  4982.6  388.52  4991.0  384.46  4998.5  378.66  5001.2  378.16
  5004.5  378.66  5009.9  379.77  5015.1  384.12  5022.4  393.35  5032.9  399.98
  5074.8  402.67  5158.5  411.30  5286.0  420.52  5318.6  422.48  5361.2  421.87
#Mann=5,-1,0
  3904.9    0.16       0  4372.7    0.05       0  4730.3    0.16       0
  4998.5    0.07       0  5004.5    0.16       0
Bank Sta=4998.5,5004.5
Exp/Cntr=0.3,0.1

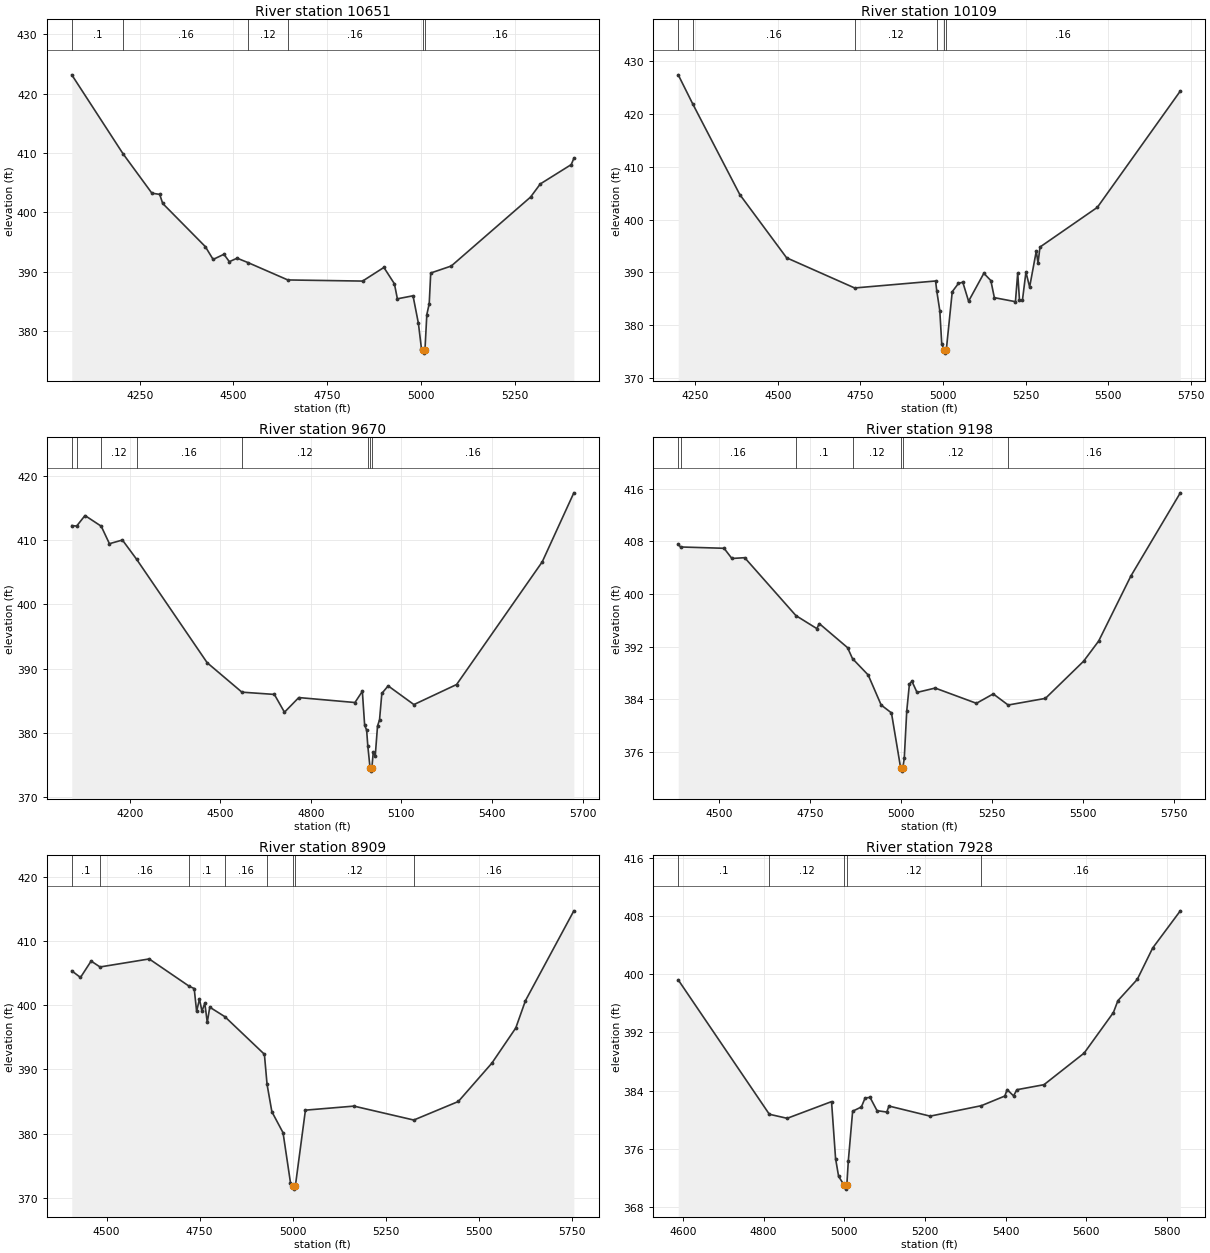
Type RM Length L Ch R = 1,10651,542,542,542
BEGIN DESCRIPTION:
UNT133 IN CCTC 22.0
END DESCRIPTION:
XS GIS Cut Line= 3
      3552199.60     10613010.20      3552949.61     10612410.19
      3553316.37     10612316.59
#Sta/Elev= 30
  4068.8  423.17  4205.5  409.86  4282.5  403.21  4303.3  403.01  4311.3  401.48
  4425.0  394.20  4445.8  392.04  4474.6  392.91  4489.0  391.66  4509.8  392.25
  4538.3  391.52  4645.0  388.58  4844.4  388.39  4901.2  390.69  4929.2  387.94
  4937.2  385.40  4978.9  385.91  4993.3  381.25  5001.3  377.02  5004.7  376.74
  5007.4  376.24  5010.7  376.74  5015.7  382.73  5022.1  384.58  5026.1  389.75
  5080.9  390.93  5292.3  402.55  5318.3  404.77  5400.8  408.03  5407.8  409.09
#Mann=6,-1,0
  4068.8     0.1       0  4205.5    0.16       0  4538.3    0.12       0
  4645.0    0.16       0  5004.7    0.07       0  5010.7    0.16       0
Bank Sta=5004.7,5010.7
Exp/Cntr=0.3,0.1

Type RM Length L Ch R = 1,10109,439,439,439
BEGIN DESCRIPTION:
UNT133 IN CCTC 21.0
END DESCRIPTION:
XS GIS Cut Line= 3
      3552199.59     10613060.19      3552949.61     10612860.19
      3553649.58     10612610.20
#Sta/Elev= 30
  4199.0  427.34  4242.6  421.88  4385.3  404.72  4527.0  392.77  4732.9  387.07
  4977.9  388.39  4981.4  386.52  4990.6  382.78  4996.5  376.52  5004.1  375.26
  5006.8  374.76  5010.1  375.26  5028.3  386.37  5046.9  387.92  5060.2  388.16
  5077.7  384.57  5123.9  389.84  5145.1  388.47  5155.7  385.24  5219.5  384.48
  5226.4  389.90  5231.7  384.85  5240.7  384.75  5251.3  390.07  5262.5  387.25
  5282.6  394.04  5287.9  391.78  5293.8  394.80  5467.4  402.30  5718.5  424.28
#Mann=6,-1,0
  4199.0     0.1       0  4242.6    0.16       0  4732.9    0.12       0
  4981.4    0.16       0  5004.1    0.07       0  5010.1    0.16       0
Bank Sta=5004.1,5010.1
Exp/Cntr=0.3,0.1

Type RM Length L Ch R = 1,9670,472,472,472
BEGIN DESCRIPTION:
UNT133 IN CCTC 20.0
END DESCRIPTION:
XS GIS Cut Line= 3
      3552196.27     10613379.79      3553120.13     10613240.65
      3553601.98     10612694.64
#Sta/Elev= 30
  4008.4  412.23  4024.6  412.16  4052.2  413.80  4105.9  412.14  4133.1  409.42
  4176.1  409.99  4222.9  407.01  4456.7  390.91  4571.8  386.33  4679.2  385.98
  4712.7  383.21  4760.1  385.49  4946.1  384.72  4970.6  386.47  4978.2  381.19
  4984.8  380.42  4988.6  378.00  4996.1  374.55  4998.8  374.05  5002.1  374.55
  5006.6  376.95  5013.3  376.42  5020.8  381.05  5027.5  382.03  5035.1  386.13
  5056.0  387.31  5141.3  384.40  5282.7  387.52  5566.3  406.60  5670.9  417.33
#Mann=8,-1,0
  4008.4    0.16       0  4024.6     0.1       0  4105.9    0.12       0
  4222.9    0.16       0  4571.8    0.12       0  4988.6    0.16       0
  4996.1    0.07       0  5002.1    0.16       0
Bank Sta=4996.1,5002.1
Exp/Cntr=0.3,0.1

Type RM Length L Ch R = 1,9198,289,289,289
BEGIN DESCRIPTION:
UNT133 IN CCTC 19.0
END DESCRIPTION:
XS GIS Cut Line= 3
      3552990.53     10613909.32      3553476.66     10613388.47
      3553649.81     10612743.48
#Sta/Elev= 30
  4387.8  407.53  4394.2  407.15  4513.8  406.95  4535.3  405.40  4570.5  405.52
  4711.3  396.71  4768.8  394.73  4775.6  395.49  4853.3  391.83  4866.9  390.16
  4910.0  387.67  4945.7  383.10  4974.0  381.90  4999.2  373.54  5001.9  373.04
  5005.2  373.54  5009.2  374.98  5016.0  382.18  5023.3  386.26  5030.2  386.72
  5044.3  385.02  5094.2  385.68  5207.6  383.36  5253.8  384.79  5294.8  383.10
  5397.2  384.11  5502.3  389.77  5543.7  392.84  5632.0  402.71  5768.1  415.39
#Mann=7,-1,0
  4387.8     0.1       0  4394.2    0.16       0  4711.3     0.1       0
  4866.9    0.12       0  4999.2    0.07       0  5005.2    0.12       0
  5294.8    0.16       0
Bank Sta=4999.2,5005.2
Exp/Cntr=0.3,0.1

Type RM Length L Ch R = 1,8909,981,981,981
BEGIN DESCRIPTION:
UNT133 IN CCTC 18.0
END DESCRIPTION:
XS GIS Cut Line= 3
      3553359.48     10613983.08      3553671.97     10613614.16
      3553724.06     10612750.41
#Sta/Elev= 30
  4406.7  405.36  4430.1  404.32  4458.7  406.88  4482.6  405.96  4614.7  407.21
  4722.8  402.93  4735.6  402.60  4742.1  399.04  4749.8  400.96  4756.4  399.06
  4764.1  400.31  4770.7  397.31  4777.4  399.69  4818.0  398.21  4924.2  392.35
  4931.3  387.67  4944.3  383.39  4974.3  380.12  4994.3  372.31  5001.4  371.83
  5004.1  371.33  5007.4  371.83  5034.4  383.64  5164.7  384.27  5325.5  382.10
  5445.2  384.99  5535.3  390.97  5599.5  396.45  5625.5  400.71  5755.5  414.71
#Mann=8,-1,0
  4406.7     0.1       0  4482.6    0.16       0  4722.8     0.1       0
  4818.0    0.16       0  4931.3    0.12       0  5001.4    0.07       0
  5007.4    0.12       0  5325.5    0.16       0
Bank Sta=5001.4,5007.4
Exp/Cntr=0.3,0.1

Type RM Length L Ch R = 1,7928,371,371,371
BEGIN DESCRIPTION:
UNT133 IN CCTC 17.0
END DESCRIPTION:
XS GIS Cut Line= 3
      3554199.61     10613860.20      3554199.61     10613460.19
      3553884.64     10612676.64
#Sta/Elev= 30
  4588.6  399.24  4814.4  380.74  4858.6  380.18  4968.6  382.48  4978.6  374.63
  4986.1  372.19  5000.4  370.93  5003.2  370.43  5006.4  370.93  5010.2  374.33
  5020.9  381.16  5042.5  381.74  5051.8  382.98  5064.1  383.06  5081.3  381.24
  5105.5  381.04  5110.9  381.87  5213.0  380.48  5340.0  381.92  5398.2  383.25
  5403.9  384.14  5419.7  383.27  5428.1  384.12  5495.2  384.81  5594.7  389.16
  5667.3  394.75  5678.4  396.38  5726.4  399.31  5764.6  403.63  5833.1  408.75
#Mann=5,-1,0
  4588.6     0.1       0  4814.4    0.12       0  5000.4    0.07       0
  5006.4    0.12       0  5340.0    0.16       0
Bank Sta=5000.4,5006.4
Exp/Cntr=0.3,0.1