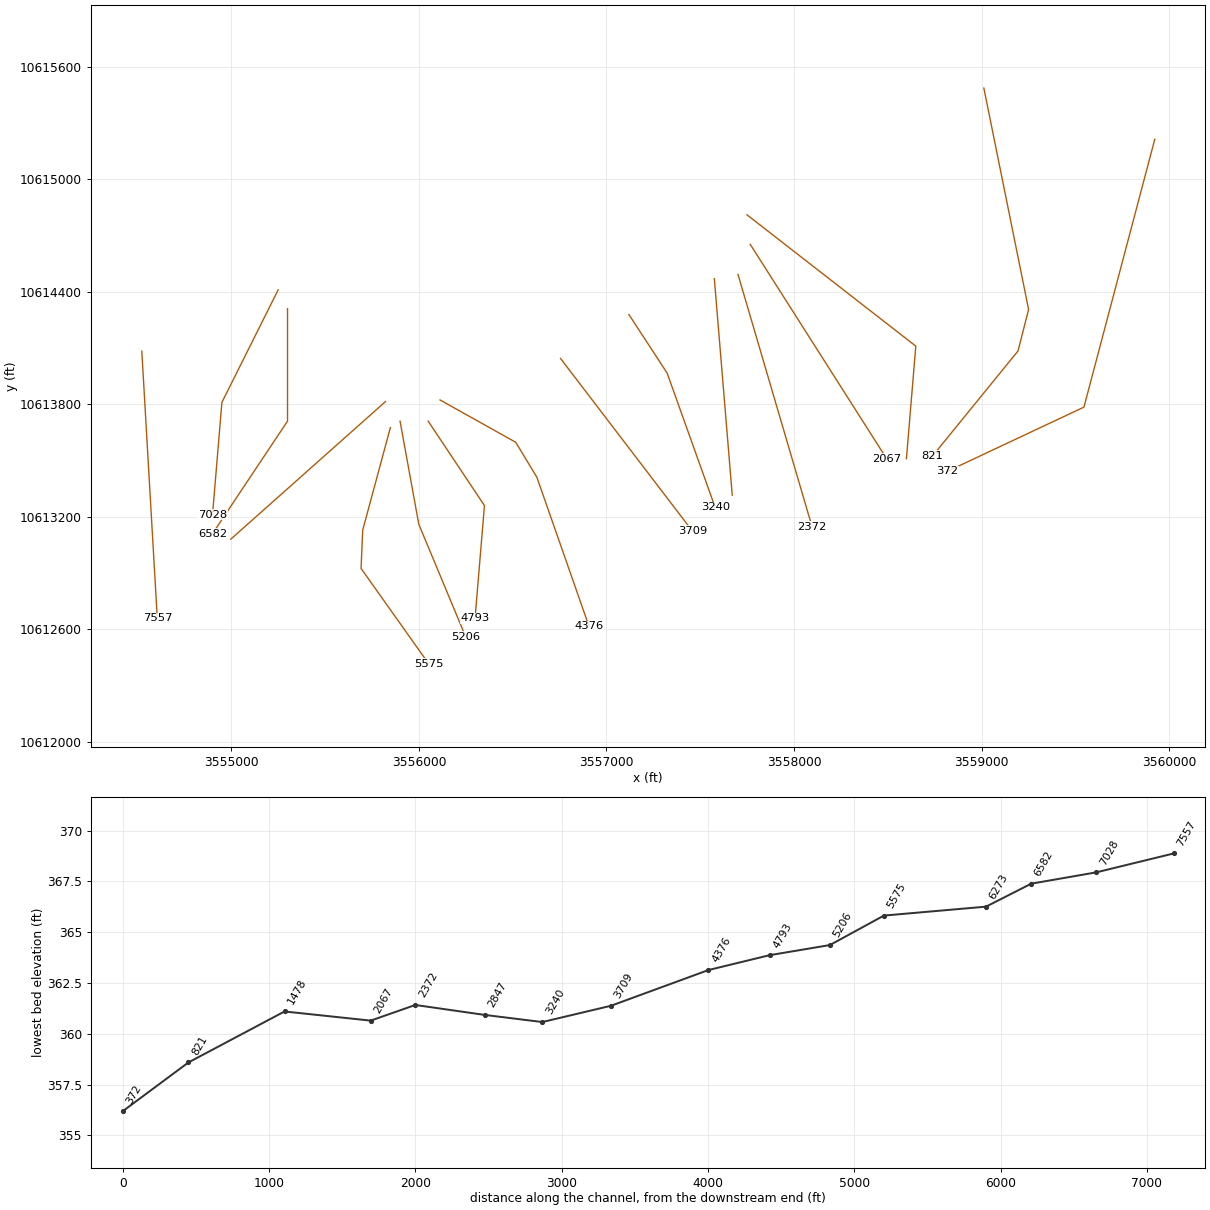
HEC-RAS study UNT133 IN CCTC.prj: UNT133 IN CCTC Base Level Engineering

--- UNT133 IN CCTC.g01 (geometry) --- (continued)

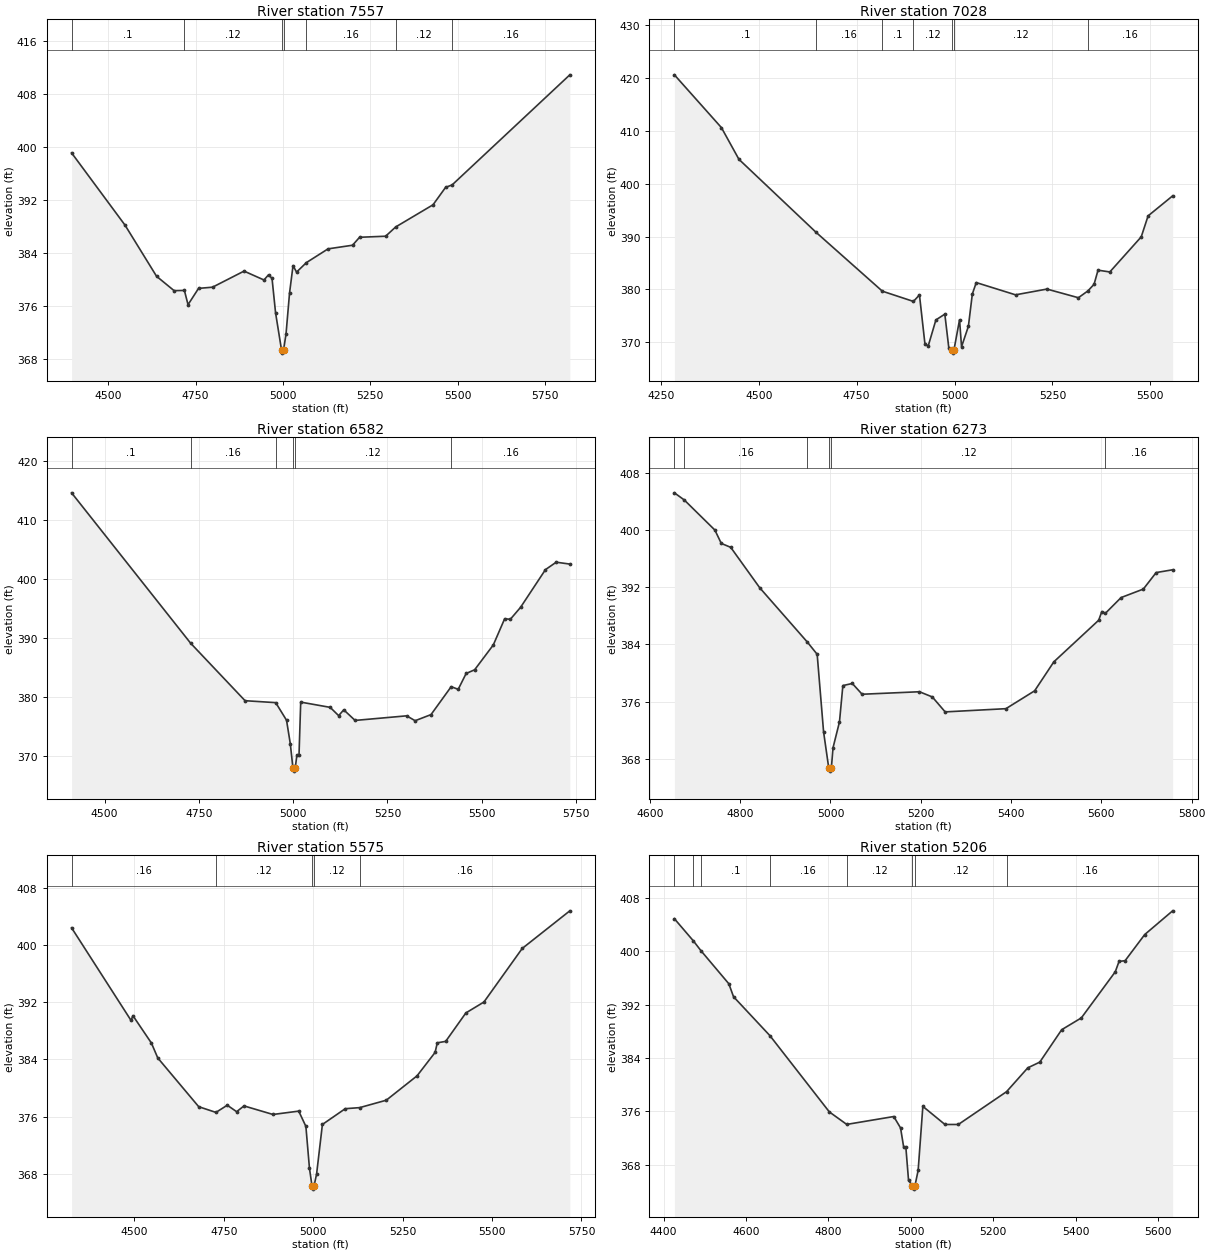
Type RM Length L Ch R = 1,7557,529,529,529
BEGIN DESCRIPTION:
UNT133 IN CCTC 16.0
END DESCRIPTION:
XS GIS Cut Line= 2
      3554522.66     10614082.96      3554605.13     10612659.35
#Sta/Elev= 30
  4395.2  399.13  4548.2  388.21  4638.4  380.49  4688.5  378.32  4718.1  378.35
  4728.5  376.20  4758.6  378.66  4798.6  378.84  4888.8  381.27  4945.8  379.93
  4958.9  380.71  4968.9  380.17  4979.0  374.98  4996.0  369.38  4998.7  368.88
  5002.0  369.38  5009.0  371.80  5019.0  377.95  5029.0  382.10  5039.1  381.12
  5067.4  382.56  5129.2  384.63  5199.3  385.18  5219.4  386.38  5294.0  386.54
  5322.8  387.94  5429.7  391.29  5465.6  393.92  5484.3  394.29  5821.2  410.92
#Mann=7,-1,0
  4395.2     0.1       0  4718.1    0.12       0  4996.0    0.07       0
  5002.0    0.12       0  5067.4    0.16       0  5322.8    0.12       0
  5484.3    0.16       0
Bank Sta=4996,5002
Exp/Cntr=0.3,0.1

Type RM Length L Ch R = 1,7028,446,446,446
BEGIN DESCRIPTION:
UNT133 IN CCTC 15.0
END DESCRIPTION:
XS GIS Cut Line= 3
      3555249.62     10614410.21      3554949.61     10613810.19
      3554899.61     10613210.22
#Sta/Elev= 30
  4284.3  420.65  4404.5  410.65  4449.2  404.65  4646.5  390.81  4815.6  379.68
  4895.0  377.74  4910.4  378.97  4924.4  369.70  4932.8  369.31  4952.4  374.24
  4975.2  375.33  4985.3  368.99  4992.3  368.45  4995.0  367.95  4998.3  368.45
  5012.8  374.27  5017.9  369.16  5035.4  373.02  5045.5  379.15  5055.5  381.31
  5155.8  378.99  5236.1  380.08  5316.4  378.44  5340.7  379.73  5356.5  380.99
  5366.6  383.66  5396.7  383.32  5477.0  389.97  5494.5  393.94  5557.2  397.73
#Mann=7,-1,0
  4284.3     0.1       0  4646.5    0.16       0  4815.6     0.1       0
  4895.0    0.12       0  4992.3    0.07       0  4998.3    0.12       0
  5340.7    0.16       0
Bank Sta=4992.3,4998.3
Exp/Cntr=0.3,0.1

Type RM Length L Ch R = 1,6582,309,309,309
BEGIN DESCRIPTION:
UNT133 IN CCTC 14.0
END DESCRIPTION:
XS GIS Cut Line= 3
      3555299.61     10614310.23      3555299.61     10613710.19
      3554899.58     10613110.15
#Sta/Elev= 30
  4412.3  414.65  4727.9  389.12  4872.3  379.35  4953.6  379.02  4982.3  376.03
  4992.3  372.04  4999.3  367.89  5002.1  367.39  5005.3  367.89  5009.8  370.13
  5015.4  370.13  5019.9  379.11  5098.0  378.22  5120.5  376.81  5134.0  377.80
  5164.1  376.00  5300.8  376.78  5323.3  375.95  5365.4  376.99  5418.9  381.73
  5437.5  381.28  5458.5  383.97  5481.1  384.60  5530.6  388.82  5560.7  393.27
  5575.7  393.17  5602.8  395.20  5668.9  401.61  5697.4  402.87  5733.5  402.55
#Mann=6,-1,0
  4412.3     0.1       0  4727.9    0.16       0  4953.6    0.12       0
  4999.3    0.07       0  5005.3    0.12       0  5418.9    0.16       0
Bank Sta=4999.3,5005.3
Exp/Cntr=0.3,0.1

Type RM Length L Ch R = 1,6273,698,698,698
BEGIN DESCRIPTION:
UNT133 IN CCTC 13.0
END DESCRIPTION:
XS GIS Cut Line= 2
      3555821.92     10613814.57      3554997.24     10613081.04
#Sta/Elev= 30
  4654.2  405.21  4676.1  404.21  4743.9  400.00  4758.1  398.13  4779.0  397.58
  4843.4  391.91  4948.6  384.33  4970.5  382.61  4984.7  371.75  4996.0  366.76
  4998.7  366.26  5002.0  366.76  5005.6  369.53  5019.9  373.15  5027.4  378.23
  5048.3  378.53  5070.0  377.02  5197.1  377.37  5225.6  376.64  5254.0  374.55
  5388.6  375.00  5452.2  377.50  5494.8  381.56  5594.1  387.38  5601.0  388.59
  5609.1  388.36  5643.7  390.55  5693.0  391.74  5721.4  394.05  5757.9  394.44
#Mann=6,-1,0
  4654.2     0.1       0  4676.1    0.16       0  4948.6    0.12       0
  4996.0    0.07       0  5002.0    0.12       0  5609.1    0.16       0
Bank Sta=4996,5002
Exp/Cntr=0.3,0.1

Type RM Length L Ch R = 1,5575,369,369,369
BEGIN DESCRIPTION:
UNT133 IN CCTC 12.0
END DESCRIPTION:
XS GIS Cut Line= 4
      3555847.97     10613675.72      3555700.39     10613128.81
      3555691.71     10612924.81      3556051.97     10612416.98
#Sta/Elev= 30
  4324.1  402.47  4490.5  389.47  4495.6  390.15  4547.3  386.31  4565.1  384.22
  4679.6  377.38  4727.8  376.58  4759.5  377.59  4785.6  376.68  4806.3  377.49
  4887.3  376.29  4959.3  376.76  4979.3  374.62  4989.3  368.75  4996.3  366.32
  4999.0  365.82  5002.3  366.32  5009.3  367.95  5025.5  374.89  5089.4  377.10
  5129.7  377.25  5204.1  378.29  5290.2  381.71  5340.6  384.99  5346.8  386.34
  5370.2  386.54  5426.7  390.53  5477.2  392.06  5584.2  399.57  5717.4  404.85
#Mann=5,-1,0
  4324.1    0.16       0  4727.8    0.12       0  4996.3    0.07       0
  5002.3    0.12       0  5129.7    0.16       0
Bank Sta=4996.3,5002.3
Exp/Cntr=0.3,0.1

Type RM Length L Ch R = 1,5206,413,413,413
BEGIN DESCRIPTION:
UNT133 IN CCTC 11.0
END DESCRIPTION:
XS GIS Cut Line= 3
      3555899.61     10613710.17      3555999.61     10613160.19
      3556249.61     10612560.19
#Sta/Elev= 30
  4426.3  404.86  4472.5  401.53  4490.9  400.06  4558.4  395.12  4569.8  393.18
  4658.1  387.35  4802.3  375.93  4844.5  374.06  4958.6  375.24  4975.1  373.53
  4982.8  370.61  4988.0  370.61  4994.5  365.67  5004.0  364.87  5006.7  364.37
  5010.0  364.87  5017.8  367.18  5029.2  376.76  5082.8  374.05  5115.3  374.05
  5232.3  378.96  5283.8  382.53  5313.0  383.39  5366.1  388.24  5413.8  390.01
  5496.1  396.91  5505.3  398.47  5519.9  398.57  5567.6  402.49  5635.3  406.04
#Mann=8,-1,0
  4426.3     0.1       0  4472.5    0.16       0  4490.9     0.1       0
  4658.1    0.16       0  4844.5    0.12       0  5004.0    0.07       0
  5010.0    0.12       0  5232.3    0.16       0
Bank Sta=5004,5010
Exp/Cntr=0.3,0.1

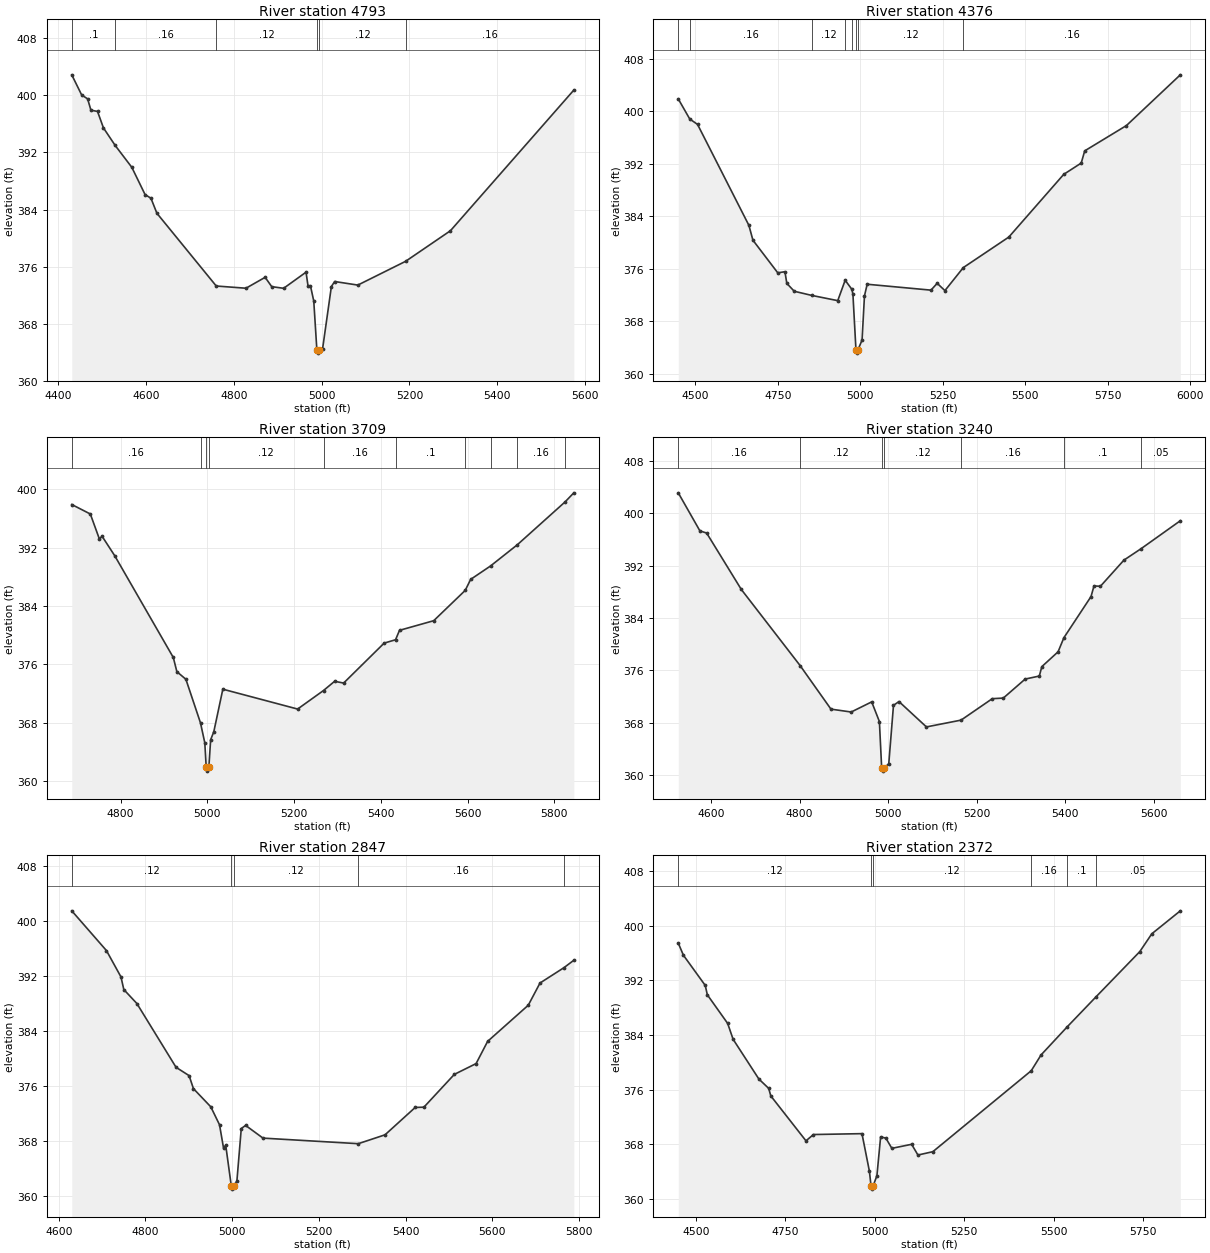
Type RM Length L Ch R = 1,4793,417,417,417
BEGIN DESCRIPTION:
UNT133 IN CCTC 10.0
END DESCRIPTION:
XS GIS Cut Line= 3
      3556049.60     10613710.20      3556349.61     10613260.19
      3556299.61     10612660.21
#Sta/Elev= 30
  4431.3  402.89  4453.8  400.07  4467.4  399.52  4474.9  397.93  4489.9  397.76
  4503.4  395.45  4530.1  392.99  4568.0  389.92  4598.1  386.11  4611.6  385.58
  4625.1  383.48  4760.2  373.28  4827.9  372.97  4871.5  374.50  4886.5  373.19
  4913.6  372.96  4964.6  375.22  4969.1  373.30  4974.7  373.30  4982.2  371.17
  4989.2  364.37  4992.0  363.87  4995.2  364.37  5002.2  364.44  5022.3  373.21
  5029.8  373.91  5082.5  373.41  5191.2  376.74  5293.3  381.03  5574.2  400.75
#Mann=6,-1,0
  4431.3     0.1       0  4530.1    0.16       0  4760.2    0.12       0
  4989.2    0.07       0  4995.2    0.12       0  5191.2    0.16       0
Bank Sta=4989.2,4995.2
Exp/Cntr=0.3,0.1

Type RM Length L Ch R = 1,4376,667,667,667
BEGIN DESCRIPTION:
UNT133 IN CCTC 9.0
END DESCRIPTION:
XS GIS Cut Line= 4
      3556112.73     10613823.24      3556516.36     10613597.56
      3556629.21     10613410.93      3556907.00     10612616.64
#Sta/Elev= 30
  4447.9  401.89  4482.7  398.83  4506.4  398.00  4662.0  382.62  4674.3  380.35
  4749.6  375.38  4771.3  375.55  4777.0  373.77  4799.5  372.57  4852.3  371.94
  4931.4  371.14  4953.9  374.25  4974.0  372.88  4977.4  372.13  4986.6  363.64
  4989.3  363.14  4992.6  363.64  5005.1  365.12  5012.4  371.86  5020.6  373.64
  5214.0  372.74  5232.8  373.78  5256.3  372.67  5312.1  376.18  5450.0  380.83
  5616.5  390.39  5669.5  392.11  5680.1  393.97  5806.6  397.83  5969.9  405.56
#Mann=8,-1,0
  4447.9     0.1       0  4482.7    0.16       0  4852.3    0.12       0
  4953.9    0.16       0  4974.0    0.12       0  4986.6    0.07       0
  4992.6    0.12       0  5312.1    0.16       0
Bank Sta=4986.6,4992.6
Exp/Cntr=0.3,0.1

Type RM Length L Ch R = 1,3709,469,469,469
BEGIN DESCRIPTION:
UNT133 IN CCTC 8.0
END DESCRIPTION:
XS GIS Cut Line= 2
      3556755.10     10614044.58      3557457.90     10613124.86
#Sta/Elev= 30
  4687.4  397.89  4730.2  396.59  4751.0  393.18  4757.3  393.54  4786.4  390.88
  4921.5  376.94  4929.7  375.00  4950.5  373.96  4984.2  367.98  4994.1  365.26
  4997.4  361.88  5000.1  361.38  5003.4  361.88  5007.6  365.68  5014.9  366.78
  5035.7  372.60  5208.1  369.88  5267.8  372.42  5293.4  373.68  5314.2  373.44
  5407.6  378.91  5433.9  379.37  5443.0  380.66  5521.9  381.98  5594.5  386.13
  5607.1  387.64  5652.8  389.47  5714.3  392.36  5824.6  398.24  5844.9  399.49
#Mann=10,-1,0
  4687.4    0.16       0  4984.2    0.12       0  4997.4    0.07       0
  5003.4    0.12       0  5267.8    0.16       0  5433.9     0.1       0
  5594.5    0.16       0  5652.8     0.1       0  5714.3    0.16       0
  5824.6    0.05       0
Bank Sta=4997.4,5003.4
Exp/Cntr=0.3,0.1

Type RM Length L Ch R = 1,3240,393,393,393
BEGIN DESCRIPTION:
UNT133 IN CCTC 7.0
END DESCRIPTION:
XS GIS Cut Line= 3
      3557119.68     10614278.95      3557323.66     10613966.48
      3557579.73     10613250.34
#Sta/Elev= 30
  4526.1  403.14  4575.0  397.32  4590.2  396.99  4668.5  388.36  4801.3  376.72
  4870.9  370.06  4916.6  369.62  4962.9  371.17  4980.3  368.16  4985.4  361.08
  4988.1  360.58  4991.4  361.08  5001.5  361.73  5012.1  370.64  5024.5  371.22
  5086.5  367.34  5164.7  368.38  5235.2  371.66  5260.1  371.75  5309.5  374.66
  5341.4  375.12  5347.1  376.56  5383.8  378.83  5396.9  380.98  5458.2  387.28
  5464.9  388.90  5479.4  388.85  5532.5  392.85  5571.5  394.61  5659.8  398.87
#Mann=7,-1,0
  4526.1    0.16       0  4801.3    0.12       0  4985.4    0.07       0
  4991.4    0.12       0  5164.7    0.16       0  5396.9     0.1       0
  5571.5    0.05       0
Bank Sta=4985.4,4991.4
Exp/Cntr=0.3,0.1

Type RM Length L Ch R = 1,2847,475,475,475
BEGIN DESCRIPTION:
UNT133 IN CCTC 6.0
END DESCRIPTION:
XS GIS Cut Line= 2
      3557575.40     10614469.92      3557670.88     10613315.47
#Sta/Elev= 30
  4629.9  401.41  4709.9  395.63  4743.4  391.80  4750.0  389.96  4780.1  387.93
  4870.5  378.65  4900.6  377.44  4910.6  375.55  4950.7  372.90  4970.8  370.29
  4980.1  366.90  4985.1  367.32  4997.9  361.43  5000.6  360.93  5003.9  361.43
  5010.9  362.10  5021.0  369.74  5031.0  370.20  5071.1  368.35  5291.0  367.54
  5352.7  368.83  5422.3  372.81  5442.4  372.85  5512.6  377.62  5562.8  379.19
  5589.4  382.42  5683.2  387.68  5710.3  390.91  5765.5  393.14  5788.3  394.22
#Mann=5,-1,0
  4629.9    0.12       0  4997.9    0.07       0  5003.9    0.12       0
  5291.0    0.16       0  5765.5    0.05       0
Bank Sta=4997.9,5003.9
Exp/Cntr=0.3,0.1

Type RM Length L Ch R = 1,2372,305,305,305
BEGIN DESCRIPTION:
UNT133 IN CCTC 5.0
END DESCRIPTION:
XS GIS Cut Line= 2
      3557701.56     10614492.49      3558096.51     10613147.06
#Sta/Elev= 30
  4451.0  397.43  4465.4  395.65  4526.4  391.23  4532.2  389.86  4588.9  385.68
  4604.2  383.35  4676.2  377.53  4703.5  376.17  4709.5  375.06  4807.7  368.49
  4828.6  369.41  4964.1  369.54  4984.9  364.03  4989.3  361.92  4992.0  361.42
  4995.3  361.92  5005.8  363.37  5016.2  369.07  5030.9  368.88  5047.5  367.39
  5102.8  367.98  5120.4  366.41  5162.1  366.90  5436.9  378.75  5464.3  381.06
  5538.0  385.21  5616.8  389.51  5740.2  396.19  5773.6  398.79  5853.2  402.15
#Mann=6,-1,0
  4451.0    0.12       0  4989.3    0.07       0  4995.3    0.12       0
  5436.9    0.16       0  5538.0     0.1       0  5616.8    0.05       0
Bank Sta=4989.3,4995.3
Exp/Cntr=0.3,0.1

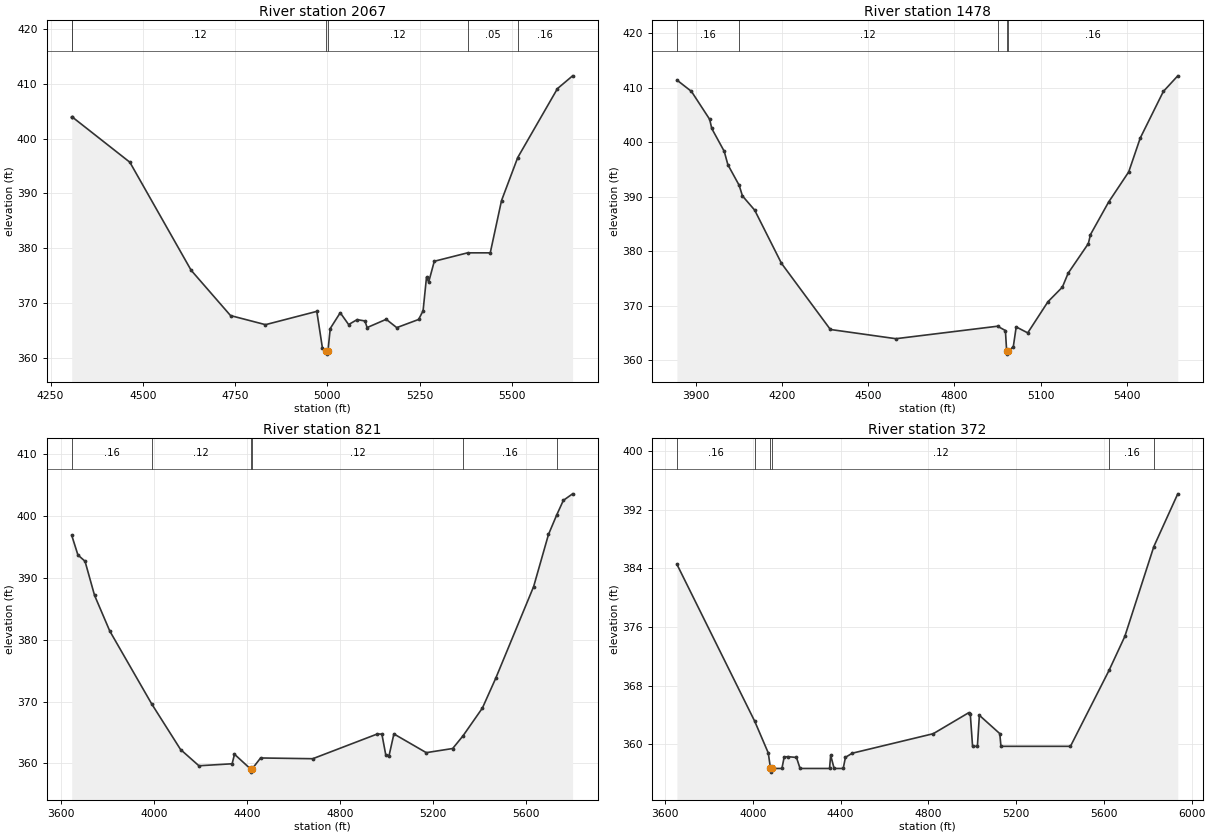
Type RM Length L Ch R = 1,2067,589,589,589
BEGIN DESCRIPTION:
UNT133 IN CCTC 4.0
END DESCRIPTION:
XS GIS Cut Line= 2
      3557766.67     10614653.10      3558495.21     10613508.25
#Sta/Elev= 30
  4307.2  403.97  4308.5  403.97  4464.7  395.70  4630.7  375.97  4737.5  367.69
  4832.2  366.03  4971.2  368.46  4986.3  361.82  4995.3  361.15  4998.0  360.65
  5001.3  361.15  5007.6  365.33  5034.7  368.21  5057.4  366.05  5080.4  366.95
  5101.6  366.71  5107.5  365.50  5159.2  367.01  5187.8  365.49  5247.0  366.98
  5259.1  368.56  5268.4  374.70  5274.3  373.82  5289.5  377.61  5379.6  379.15
  5441.1  379.15  5471.6  388.69  5515.5  396.55  5623.1  409.14  5664.2  411.48
#Mann=6,-1,0
  4307.2    0.16       0  4308.5    0.12       0  4995.3    0.07       0
  5001.3    0.12       0  5379.6    0.05       0  5515.5    0.16       0
Bank Sta=4995.3,5001.3
Exp/Cntr=0.3,0.1

Type RM Length L Ch R = 1,1478,657,657,657
BEGIN DESCRIPTION:
UNT133 IN CCTC 3.0
END DESCRIPTION:
XS GIS Cut Line= 3
      3557749.61     10614810.19      3558649.61     10614110.19
      3558599.60     10613510.14
#Sta/Elev= 30
  3834.5  411.39  3885.2  409.30  3948.5  404.18  3955.8  402.50  3999.2  398.31
  4011.9  395.85  4051.2  392.07  4062.5  390.13  4105.1  387.52  4198.3  377.76
  4368.4  365.62  4596.4  363.93  4949.8  366.22  4977.2  365.43  4981.7  361.60
  4984.5  361.10  4987.7  361.60  5004.8  362.49  5014.8  366.09  5054.9  365.00
  5125.2  370.71  5175.4  373.39  5195.4  375.94  5265.7  381.38  5273.2  383.04
  5335.9  388.97  5406.2  394.54  5446.3  400.75  5526.6  409.29  5576.8  412.16
#Mann=5,-1,0
  3834.5    0.16       0  4051.2    0.12       0  4949.8    0.16       0
  4981.7    0.07       0  4987.7    0.16       0
Bank Sta=4981.7,4987.7
Exp/Cntr=0.3,0.1

Type RM Length L Ch R = 1,821,449,449,449
BEGIN DESCRIPTION:
UNT133 IN CCTC 2.0
END DESCRIPTION:
XS GIS Cut Line= 4
      3559012.31     10615486.47      3559251.03     10614305.89
      3559194.61     10614084.54      3558739.08     10613524.89
#Sta/Elev= 30
  3646.6  396.90  3673.4  393.71  3703.8  392.71  3744.8  387.19  3810.4  381.41
  3990.2  369.65  4114.8  362.25  4193.7  359.62  4336.6  359.94  4346.8  361.48
  4416.2  359.09  4418.9  358.59  4422.2  359.09  4459.0  360.88  4683.4  360.76
  4961.7  364.77  4980.8  364.73  4997.4  361.39  5011.7  361.27  5032.4  364.77
  5171.7  361.74  5285.2  362.41  5329.5  364.45  5413.0  368.95  5470.5  373.78
  5633.5  388.61  5697.4  397.04  5732.5  400.17  5761.3  402.55  5801.1  403.61
#Mann=6,-1,0
  3646.6    0.16       0  3990.2    0.12       0  4416.2    0.07       0
  4422.2    0.12       0  5329.5    0.16       0  5732.5    0.05       0
Bank Sta=4416.2,4422.2
Exp/Cntr=0.3,0.1

Type RM Length L Ch R = 1,372,0,0,0
BEGIN DESCRIPTION:
UNT133 IN CCTC 1.0
END DESCRIPTION:
XS GIS Cut Line= 3
      3559923.76     10615212.97      3559546.17     10613785.06
      3558816.96     10613442.16
#Sta/Elev= 30
  3654.0  384.54  4009.0  363.11  4070.6  358.80  4080.6  356.69  4083.3  356.19
  4086.6  356.69  4132.7  356.69  4143.0  358.24  4158.9  358.30  4199.1  358.19
  4215.4  356.69  4349.8  356.69  4354.9  358.49  4370.6  356.69  4412.0  356.69
  4422.3  358.21  4453.3  358.77  4822.4  361.43  4983.3  364.28  4991.2  364.11
  5001.6  359.71  5023.6  359.71  5032.6  363.94  5125.7  361.44  5130.9  359.71
  5447.7  359.71  5623.3  370.05  5695.5  374.70  5827.7  386.95  5936.8  394.14
#Mann=6,-1,0
  3654.0    0.16       0  4009.0    0.12       0  4080.6    0.07       0
  4086.6    0.12       0  5623.3    0.16       0  5827.7    0.05       0
Bank Sta=4080.6,4086.6
Exp/Cntr=0.3,0.1

Chan Stop Cuts=-1