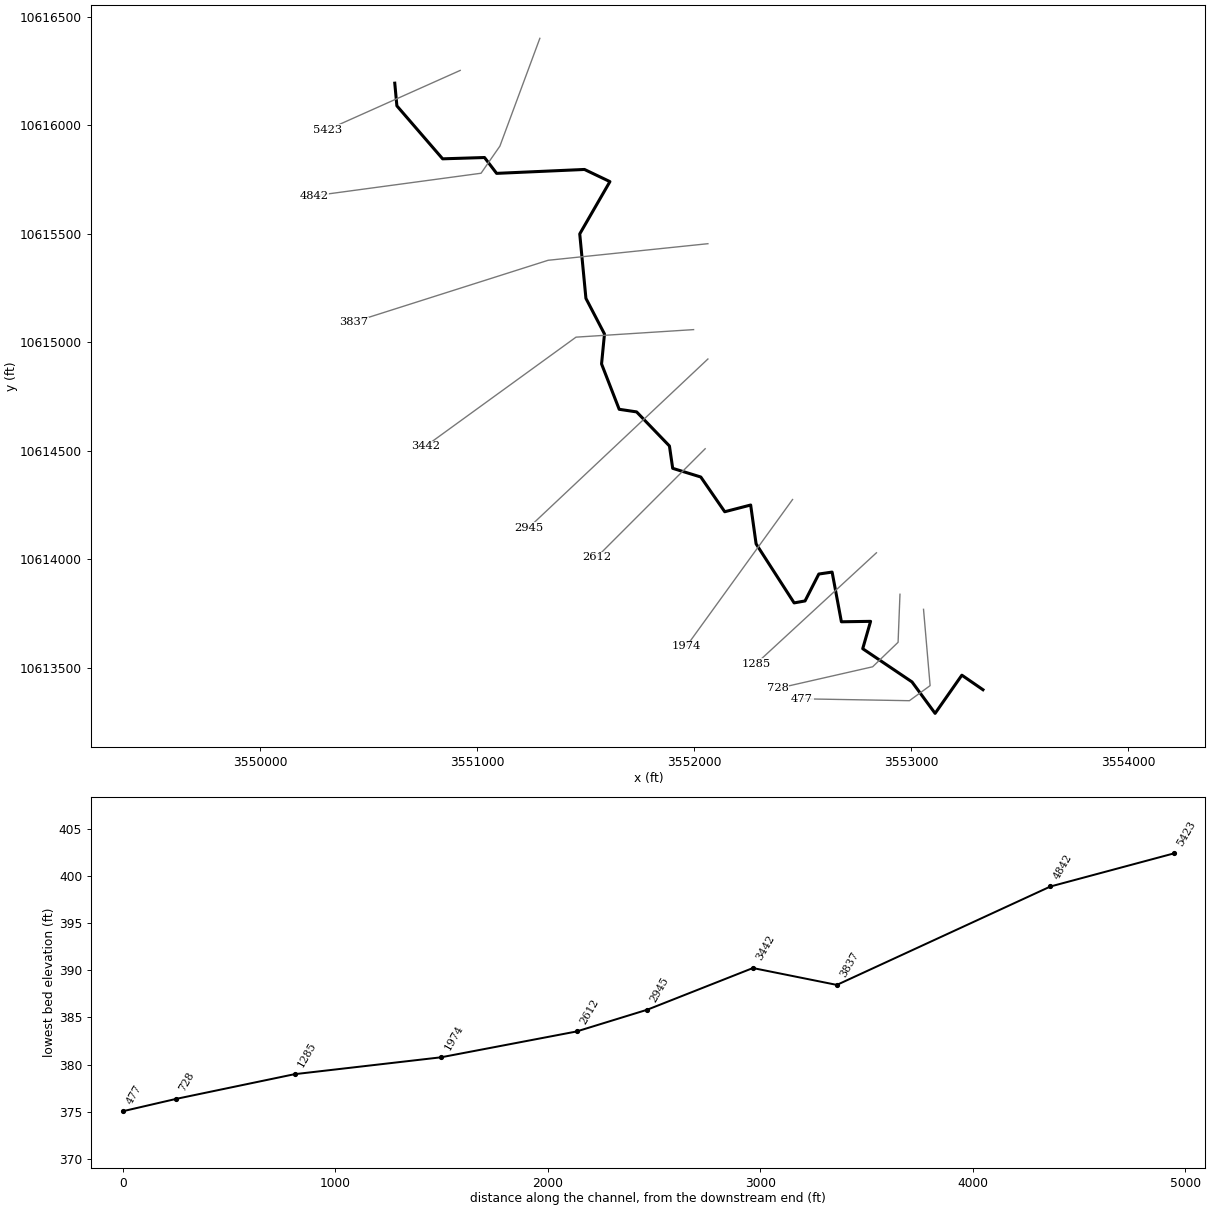
--- UNT134 IN CCTC.prj (project) ---

Proj Title=UNT134 IN CCTC Base Level Engineering
Current Plan=p01
Default Exp/Contr=0.3,0.1
English Units
Geom File=g01
Flow File=f01
Plan File=p01
BEGIN DESCRIPTION:
UNT134 IN CCTC
END DESCRIPTION:

--- UNT134 IN CCTC.p01 (plan) ---

Plan Title=Multiple Run
Short Identifier=Multiple
Geom File=g01
Flow File=f01
Subcritical Flow
K Sum by GR= 0
Std Step Tol= 0.01
Critical Tol= 0.01
Num of Std Step Trials= 20
Max Error Tol= 0.3
Flow Tol Ratio= 0.001
Split Flow NTrial= 30
Split Flow Tol= 0.02
Split Flow Ratio= 0.02
Log Output Level= 0
Friction Slope Method= 1
Unsteady Friction Slope Method= 2
Unsteady Bridges Friction Slope Method= 1
Parabolic Critical Depth
Global Vel Dist=  1 , 1 , 1
Global Log Level= 0
CheckData=True
Encroach Param= -1, 0, 0, 0
BEGIN DESCRIPTION:
Multiple Run
END DESCRIPTION:

--- UNT134 IN CCTC.f01 (steady flow) ---

Flow Title=Multiple
Number of Profiles=7
Profile Names=10-year,25-year,50-year,1pct_min,100-year,1pct_plu,500-year
River Rch & RM= UNT134 IN CCTC,Reach-1,5423
    1437    1983    2436    2185    2955    3997    4333
River Rch & RM= UNT134 IN CCTC,Reach-1,3442
    1901    2657    3293    2975    4023    5441    5986
Boundary for River Rch & Prof#=UNT134 IN CCTC,Reach-1,1
Up Type=0
Dn Type=3
Dn Slope=0.005
Boundary for River Rch & Prof#=UNT134 IN CCTC,Reach-1,2
Up Type=0
Dn Type=3
Dn Slope=0.005
Boundary for River Rch & Prof#=UNT134 IN CCTC,Reach-1,3
Up Type=0
Dn Type=3
Dn Slope=0.005
Boundary for River Rch & Prof#=UNT134 IN CCTC,Reach-1,4
Up Type=0
Dn Type=3
Dn Slope=0.005
Boundary for River Rch & Prof#=UNT134 IN CCTC,Reach-1,5
Up Type=0
Dn Type=3
Dn Slope=0.005
Boundary for River Rch & Prof#=UNT134 IN CCTC,Reach-1,6
Up Type=0
Dn Type=3
Dn Slope=0.005
Boundary for River Rch & Prof#=UNT134 IN CCTC,Reach-1,7
Up Type=0
Dn Type=3
Dn Slope=0.005

--- UNT134 IN CCTC.g01 (geometry) ---

Geom Title=Existing Conditions

River Reach=UNT134 IN CCTC,Reach-1
Reach XY= 30
      3550619.50     10616194.55      3550629.25     10616090.00
      3550840.00     10615846.00      3551033.00     10615852.00
      3551088.75     10615779.00      3551493.50     10615797.00
      3551610.75     10615741.00      3551471.75     10615500.00
      3551500.25     10615203.00      3551585.75     10615039.00
      3551572.25     10614901.00      3551653.50     10614692.00
      3551733.75     10614680.00      3551885.00     10614523.00
      3551900.00     10614420.00      3552029.50     10614380.00
      3552139.75     10614220.00      3552259.25     10614251.00
      3552284.25     10614072.00      3552459.50     10613800.00
      3552509.75     10613809.00      3552573.25     10613933.00
      3552634.50     10613942.00      3552677.25     10613713.00
      3552811.75     10613715.00      3552775.50     10613589.00
      3553002.50     10613436.00      3553109.00     10613291.00
      3553232.25     10613467.00      3553329.50     10613400.00

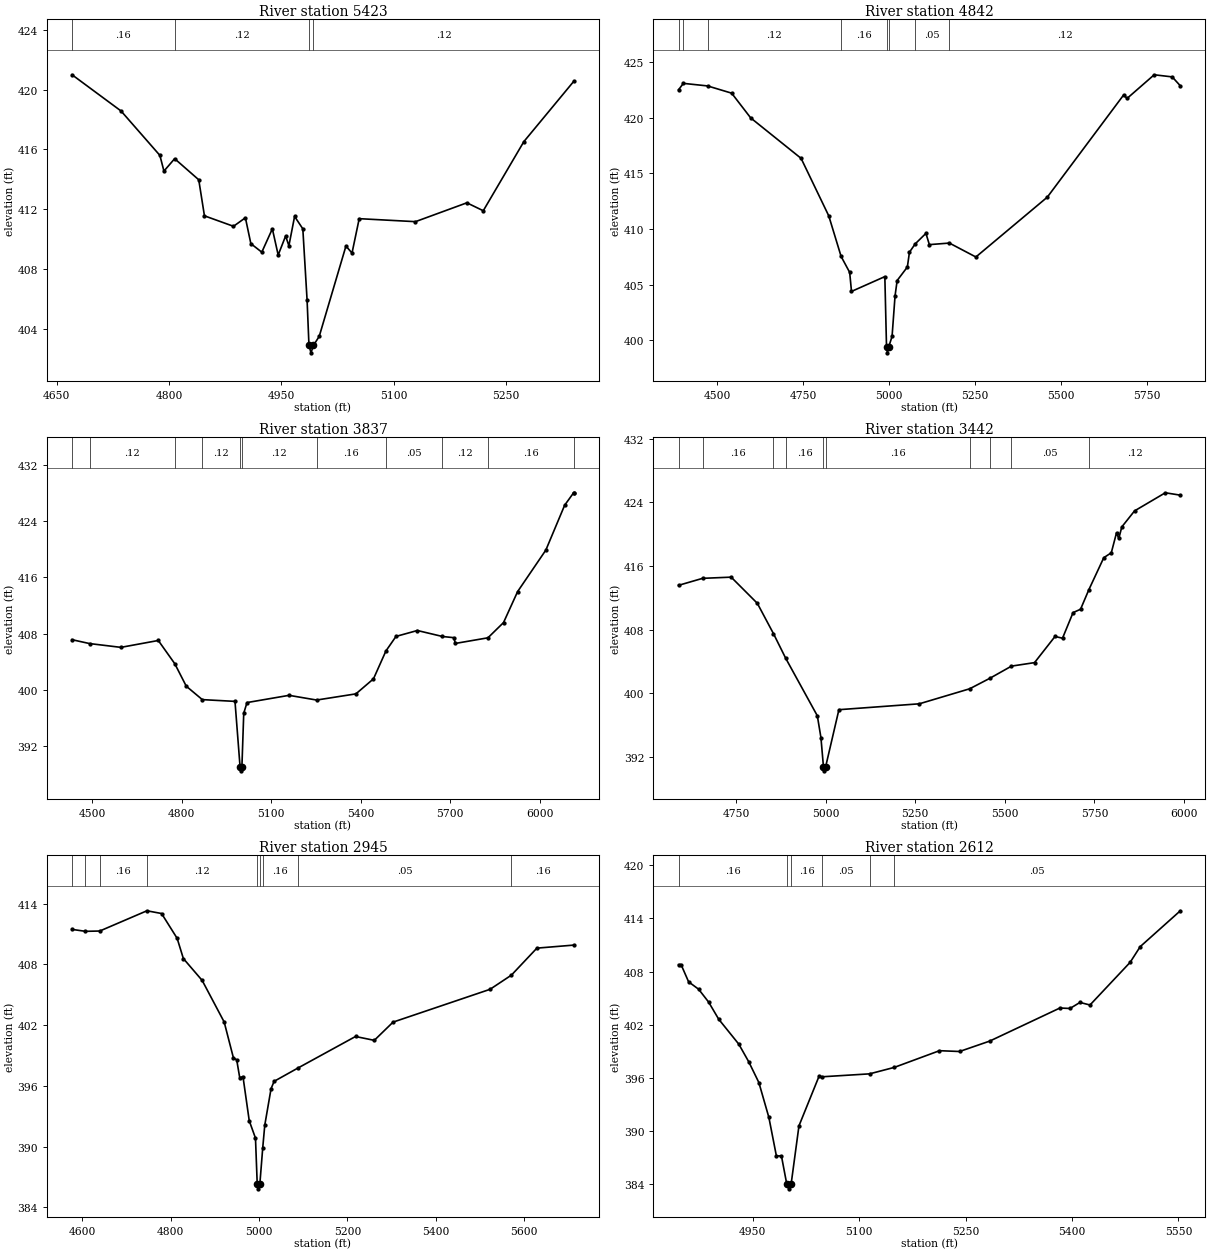
Type RM Length L Ch R = 1,5423,581,581,581
BEGIN DESCRIPTION:
UNT134 IN CCTC 9.0
END DESCRIPTION:
XS GIS Cut Line= 2
      3550920.99     10616253.33      3550309.10     10615979.92
#Sta/Elev= 30
  4670.3  420.99  4735.7  418.57  4787.6  415.60  4793.0  414.55  4807.3  415.38
  4839.5  413.97  4847.1  411.56  4885.9  410.86  4901.8  411.43  4909.1  409.70
  4923.7  409.13  4937.8  410.69  4945.6  408.94  4955.5  410.21  4959.9  409.56
  4967.5  411.52  4978.5  410.69  4984.2  405.92  4986.7  402.90  4989.4  402.40
  4992.7  402.90  5000.4  403.50  5036.1  409.54  5044.2  409.07  5053.8  411.37
  5128.9  411.17  5197.6  412.43  5219.5  411.90  5273.7  416.52  5340.5  420.56
#Mann=4,-1,0
  4670.3    0.16       0  4807.3    0.12       0  4986.7    0.07       0
  4992.7    0.12       0
Bank Sta=4986.7,4992.7
Exp/Cntr=0.3,0.1

Type RM Length L Ch R = 1,4842,1005,1005,1005
BEGIN DESCRIPTION:
UNT134 IN CCTC 8.0
END DESCRIPTION:
XS GIS Cut Line= 4
      3551287.91     10616401.14      3551103.88     10615904.60
      3551017.07     10615779.60      3550246.21     10615675.43
#Sta/Elev= 30
  4386.8  422.49  4400.8  423.07  4471.2  422.84  4541.3  422.19  4596.7  419.97
  4743.3  416.34  4823.8  411.18  4859.7  407.54  4884.6  406.11  4889.9  404.40
  4986.9  405.73  4991.8  399.39  4994.5  398.89  4997.8  399.39  5007.9  400.36
  5016.6  404.00  5022.7  405.38  5052.4  406.59  5058.5  407.92  5075.3  408.67
  5106.4  409.61  5116.4  408.60  5174.6  408.74  5251.7  407.49  5459.5  412.86
  5681.5  422.03  5691.6  421.72  5770.4  423.84  5822.8  423.65  5846.4  422.85
#Mann=8,-1,0
  4386.8    0.05       0  4400.8    0.16       0  4471.2    0.12       0
  4859.7    0.16       0  4991.8    0.07       0  4997.8    0.16       0
  5075.3    0.05       0  5174.6    0.12       0
Bank Sta=4991.8,4997.8
Exp/Cntr=0.3,0.1

Type RM Length L Ch R = 1,3837,395,395,395
BEGIN DESCRIPTION:
UNT134 IN CCTC 7.0
END DESCRIPTION:
XS GIS Cut Line= 3
      3552062.21     10615454.95      3551326.10     10615378.56
      3550430.22     10615093.82
#Sta/Elev= 30
  4433.5  407.12  4492.2  406.57  4597.0  406.03  4722.2  407.01  4777.3  403.71
  4815.9  400.50  4869.6  398.59  4979.0  398.34  4996.1  388.95  4998.9  388.45
  5002.1  388.95  5008.3  396.65  5019.2  398.17  5160.0  399.20  5252.3  398.53
  5383.9  399.41  5442.7  401.55  5484.4  405.52  5518.1  407.59  5589.6  408.43
  5673.6  407.58  5711.6  407.41  5716.8  406.59  5825.9  407.39  5878.1  409.56
  5925.4  413.98  6019.8  419.88  6082.8  426.27  6112.8  428.04  6113.6  428.04
#Mann=11,-1,0
  4433.5    0.16       0  4492.2    0.12       0  4777.3    0.16       0
  4869.6    0.12       0  4996.1    0.07       0  5002.1    0.12       0
  5252.3    0.16       0  5484.4    0.05       0  5673.6    0.12       0
  5825.9    0.16       0  6112.8    0.12       0
Bank Sta=4996.1,5002.1
Exp/Cntr=0.3,0.1

Type RM Length L Ch R = 1,3442,497,497,497
BEGIN DESCRIPTION:
UNT134 IN CCTC 6.0
END DESCRIPTION:
XS GIS Cut Line= 3
      3551996.24     10615059.11      3551454.57     10615024.39
      3550760.16     10614520.94
#Sta/Elev= 30
  4589.2  413.57  4656.4  414.45  4736.1  414.60  4809.1  411.31  4854.1  407.50
  4888.5  404.38  4976.6  397.16  4986.6  394.43  4993.7  390.74  4996.4  390.24
  4999.7  390.74  5036.8  397.93  5261.2  398.67  5401.8  400.56  5458.1  401.88
  5518.5  403.41  5582.8  403.85  5640.0  407.14  5660.9  406.92  5690.3  410.14
  5711.2  410.56  5734.6  413.04  5776.1  417.05  5797.0  417.66  5811.7  420.19
  5817.9  419.46  5826.4  420.92  5861.9  422.93  5947.8  425.21  5989.7  424.91
#Mann=10,-1,0
  4589.2    0.12       0  4656.4    0.16       0  4854.1    0.12       0
  4888.5    0.16       0  4993.7    0.07       0  4999.7    0.16       0
  5401.8    0.05       0  5458.1    0.16       0  5518.5    0.05       0
  5734.6    0.12       0
Bank Sta=4993.7,4999.7
Exp/Cntr=0.3,0.1

Type RM Length L Ch R = 1,2945,333,333,333
BEGIN DESCRIPTION:
UNT134 IN CCTC 5.0
END DESCRIPTION:
XS GIS Cut Line= 2
      3552062.21     10614923.70      3551235.85     10614145.94
#Sta/Elev= 30
  4577.3  411.45  4607.6  411.26  4639.9  411.29  4746.6  413.29  4779.7  413.02
  4814.9  410.57  4829.0  408.57  4871.5  406.41  4921.3  402.30  4942.3  398.74
  4949.6  398.57  4956.5  396.79  4963.8  396.91  4978.0  392.54  4992.1  390.83
  4996.0  386.32  4998.7  385.82  5002.0  386.32  5008.5  389.88  5013.1  392.11
  5027.3  395.71  5034.2  396.44  5087.9  397.75  5218.3  400.87  5260.8  400.49
  5303.2  402.29  5522.5  405.53  5570.8  406.93  5628.5  409.60  5712.1  409.90
#Mann=9,-1,0
  4577.3    0.16       0  4607.6    0.12       0  4639.9    0.16       0
  4746.6    0.12       0  4996.0    0.07       0  5002.0    0.12       0
  5008.5    0.16       0  5087.9    0.05       0  5570.8    0.16       0
Bank Sta=4996,5002
Exp/Cntr=0.3,0.1

Type RM Length L Ch R = 1,2612,638,638,638
BEGIN DESCRIPTION:
UNT134 IN CCTC 4.0
END DESCRIPTION:
XS GIS Cut Line= 3
      3552049.62     10614510.20      3551949.61     10614410.19
      3551549.63     10614010.21
#Sta/Elev= 30
  4845.5  408.78  4849.1  408.78  4859.7  406.84  4873.8  406.01  4887.9  404.56
  4902.1  402.63  4930.4  399.82  4944.5  397.82  4958.7  395.49  4972.8  391.56
  4983.4  387.22  4990.5  387.22  4998.1  384.01  5000.8  383.51  5004.1  384.01
  5015.2  390.61  5043.5  396.20  5047.9  396.14  5114.7  396.47  5149.6  397.20
  5213.2  399.08  5241.5  398.99  5283.9  400.16  5382.9  403.89  5397.1  403.84
  5411.2  404.52  5425.3  404.23  5481.9  409.04  5496.1  410.81  5552.6  414.85
#Mann=6,-1,0
  4845.5    0.16       0  4998.1    0.07       0  5004.1    0.16       0
  5047.9    0.05       0  5114.7    0.16       0  5149.6    0.05       0
Bank Sta=4998.1,5004.1
Exp/Cntr=0.3,0.1

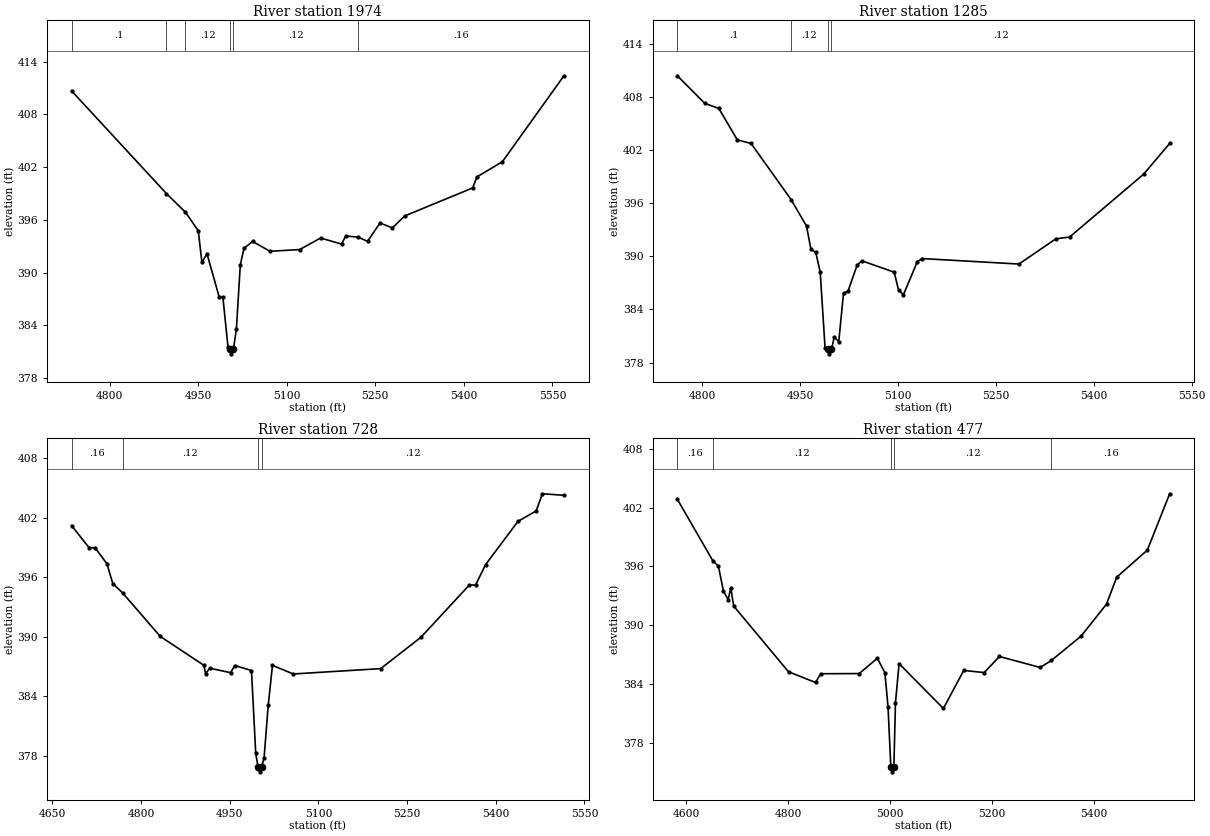
Type RM Length L Ch R = 1,1974,689,689,689
BEGIN DESCRIPTION:
Mapping XS d73cee8f
END DESCRIPTION:
XS GIS Cut Line= 2
      3552452.28     10614276.35      3551963.66     10613600.60
#Sta/Elev= 30
  4735.6  410.67  4896.3  398.99  4928.5  396.87  4950.2  394.76  4956.3  391.17
  4964.9  392.16  4985.7  387.20  4991.9  387.18  5000.4  381.60  5003.6  381.27
  5006.4  380.77  5009.6  381.27  5014.7  383.56  5021.3  390.84  5027.5  392.76
  5042.2  393.55  5071.6  392.43  5121.9  392.63  5157.4  393.94  5193.0  393.25
  5199.8  394.17  5221.1  394.04  5236.8  393.56  5258.0  395.65  5278.9  395.09
  5299.8  396.45  5415.0  399.64  5421.9  400.88  5465.3  402.62  5569.5  412.39
#Mann=6,-1,0
  4735.6     0.1       0  4896.3    0.16       0  4928.5    0.12       0
  5003.6    0.07       0  5009.6    0.12       0  5221.1    0.16       0
Bank Sta=5003.6,5009.6
Exp/Cntr=0.3,0.1

Type RM Length L Ch R = 1,1285,557,557,557
BEGIN DESCRIPTION:
UNT134 IN CCTC 3.0
END DESCRIPTION:
XS GIS Cut Line= 2
      3552838.66     10614030.85      3552283.85     10613519.38
#Sta/Elev= 30
  4761.7  410.41  4803.8  407.29  4825.3  406.72  4853.7  403.16  4874.7  402.76
  4936.3  396.39  4959.7  393.42  4966.5  390.78  4973.9  390.46  4980.7  388.20
  4988.1  379.69  4991.9  379.48  4994.6  378.98  4997.9  379.48  5002.3  380.89
  5009.1  380.34  5016.4  385.84  5023.2  386.05  5037.4  389.04  5044.8  389.49
  5094.1  388.21  5100.9  386.15  5108.3  385.67  5129.3  389.36  5136.7  389.75
  5285.2  389.13  5341.9  391.98  5362.9  392.18  5476.3  399.28  5516.3  402.76
#Mann=4,-1,0
  4761.7     0.1       0  4936.3    0.12       0  4991.9    0.07       0
  4997.9    0.12       0
Bank Sta=4991.9,4997.9
Exp/Cntr=0.3,0.1

Type RM Length L Ch R = 1,728,251,251,251
BEGIN DESCRIPTION:
UNT134 IN CCTC 2.0
END DESCRIPTION:
XS GIS Cut Line= 4
      3552947.15     10613839.87      3552938.46     10613618.50
      3552821.28     10613505.66      3552383.80     10613406.03
#Sta/Elev= 30
  4682.4  401.22  4712.1  398.98  4722.1  398.98  4742.1  397.37  4752.1  395.37
  4768.6  394.43  4832.2  390.04  4906.3  387.11  4909.0  386.27  4916.2  386.82
  4951.5  386.37  4958.4  387.09  4986.7  386.59  4993.9  378.22  4997.8  376.86
  5000.6  376.36  5003.8  376.86  5008.0  377.76  5015.0  383.06  5022.2  387.11
  5057.4  386.24  5205.3  386.78  5273.5  389.95  5355.5  395.24  5365.8  395.21
  5382.6  397.27  5437.5  401.64  5468.3  402.70  5478.9  404.43  5515.3  404.28
#Mann=4,-1,0
  4682.4    0.16       0  4768.6    0.12       0  4997.8    0.07       0
  5003.8    0.12       0
Bank Sta=4997.8,5003.8
Exp/Cntr=0.3,0.1

Type RM Length L Ch R = 1,477,0,0,0
BEGIN DESCRIPTION:
UNT134 IN CCTC 1.0
END DESCRIPTION:
XS GIS Cut Line= 4
      3553055.66     10613770.38      3553086.03     10613418.85
      3552990.55     10613349.41      3552495.73     10613358.09
#Sta/Elev= 30
  4582.8  402.84  4652.7  396.55  4663.3  396.04  4673.3  393.46  4682.6  392.60
  4687.6  393.81  4693.4  391.95  4800.9  385.25  4854.0  384.16  4864.0  385.05
  4939.6  385.07  4975.2  386.63  4989.9  385.16  4996.1  381.71  5001.6  375.55
  5004.3  375.05  5007.6  375.55  5010.7  382.08  5017.8  386.08  5104.7  381.51
  5144.7  385.39  5184.7  385.17  5214.7  386.81  5294.7  385.69  5316.6  386.41
  5374.7  388.88  5424.7  392.15  5444.7  394.90  5504.7  397.65  5548.6  403.40
#Mann=5,-1,0
  4582.8    0.16       0  4652.7    0.12       0  5001.6    0.07       0
  5007.6    0.12       0  5316.6    0.16       0
Bank Sta=5001.6,5007.6
Exp/Cntr=0.3,0.1

Chan Stop Cuts=-1