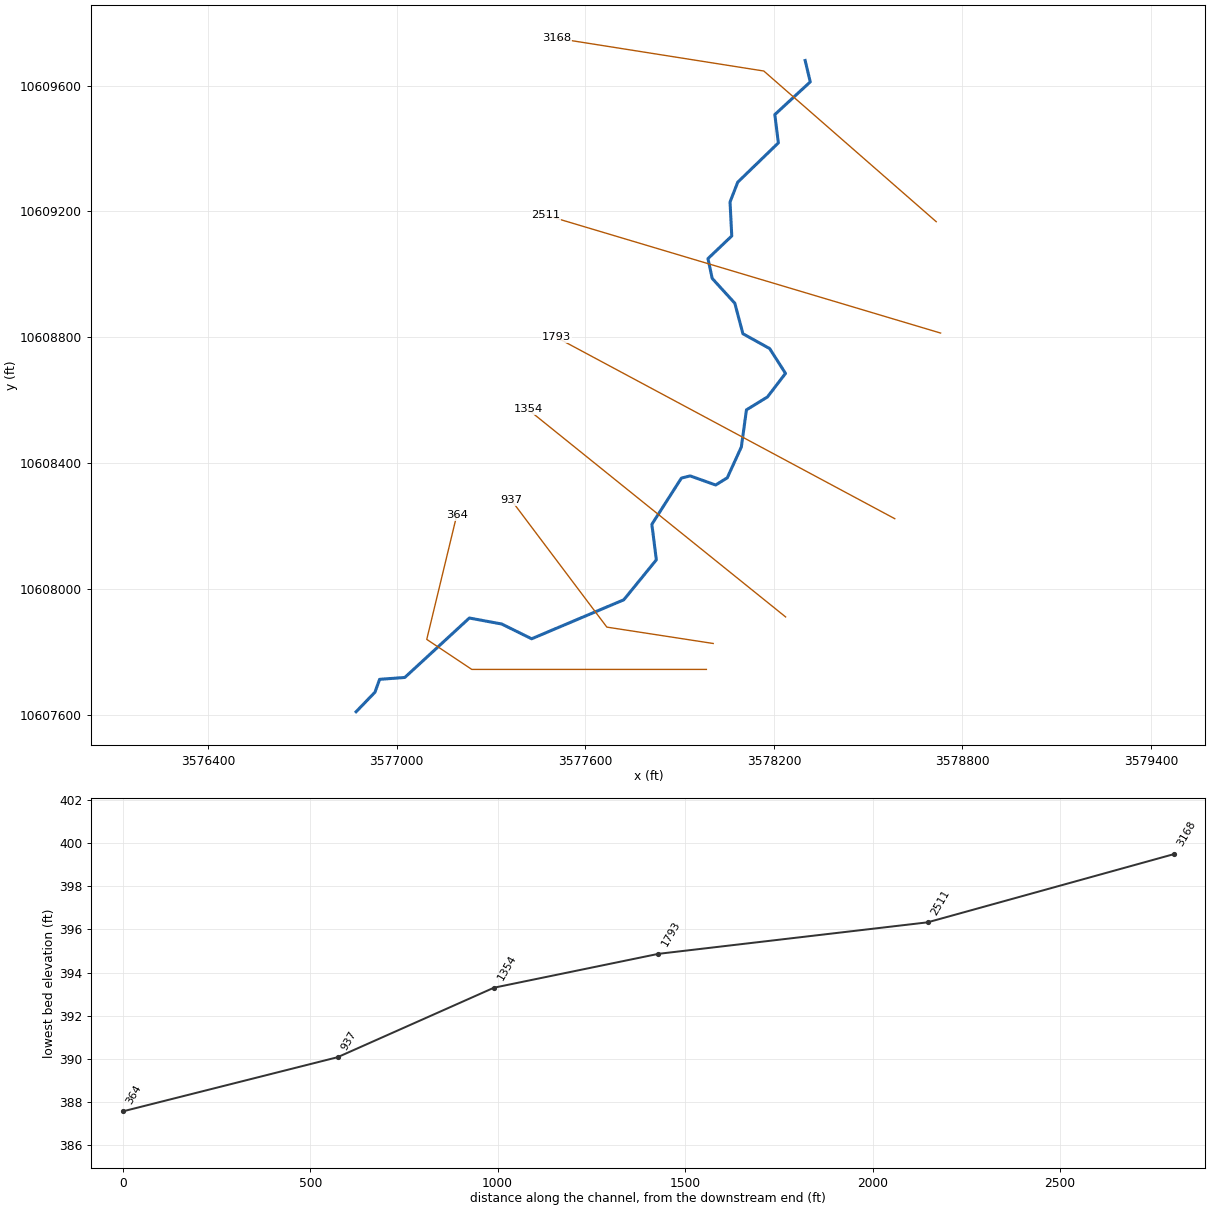
--- UNT137 IN CCTC.prj (project) ---

Proj Title=UNT137 IN CCTC Base Level Engineering
Current Plan=p01
Default Exp/Contr=0.3,0.1
English Units
Geom File=g01
Flow File=f01
Plan File=p01
BEGIN DESCRIPTION:
UNT137 IN CCTC
END DESCRIPTION:

--- UNT137 IN CCTC.p01 (plan) ---

Plan Title=Multiple Run
Short Identifier=Multiple
Geom File=g01
Flow File=f01
Subcritical Flow
K Sum by GR= 0
Std Step Tol= 0.01
Critical Tol= 0.01
Num of Std Step Trials= 20
Max Error Tol= 0.3
Flow Tol Ratio= 0.001
Split Flow NTrial= 30
Split Flow Tol= 0.02
Split Flow Ratio= 0.02
Log Output Level= 0
Friction Slope Method= 1
Unsteady Friction Slope Method= 2
Unsteady Bridges Friction Slope Method= 1
Parabolic Critical Depth
Global Vel Dist=  1 , 1 , 1
Global Log Level= 0
CheckData=True
Encroach Param= -1, 0, 0, 0
BEGIN DESCRIPTION:
Multiple Run
END DESCRIPTION:

--- UNT137 IN CCTC.f01 (steady flow) ---

Flow Title=Multiple
Number of Profiles=7
Profile Names=10-year,25-year,50-year,1pct_min,100-year,1pct_plu,500-year
River Rch & RM= UNT137 IN CCTC,Reach-1,3168
    1329    1817    2219    1978    2676    3618    3875
Boundary for River Rch & Prof#=UNT137 IN CCTC,Reach-1,1
Up Type=0
Dn Type=3
Dn Slope=0.005
Boundary for River Rch & Prof#=UNT137 IN CCTC,Reach-1,2
Up Type=0
Dn Type=3
Dn Slope=0.005
Boundary for River Rch & Prof#=UNT137 IN CCTC,Reach-1,3
Up Type=0
Dn Type=3
Dn Slope=0.005
Boundary for River Rch & Prof#=UNT137 IN CCTC,Reach-1,4
Up Type=0
Dn Type=3
Dn Slope=0.005
Boundary for River Rch & Prof#=UNT137 IN CCTC,Reach-1,5
Up Type=0
Dn Type=3
Dn Slope=0.005
Boundary for River Rch & Prof#=UNT137 IN CCTC,Reach-1,6
Up Type=0
Dn Type=3
Dn Slope=0.005
Boundary for River Rch & Prof#=UNT137 IN CCTC,Reach-1,7
Up Type=0
Dn Type=3
Dn Slope=0.005

--- UNT137 IN CCTC.g01 (geometry) ---

Geom Title=Existing Conditions

River Reach=UNT137 IN CCTC,Reach-1
Reach XY= 30
      3578299.50     10609680.00      3578315.75     10609612.00
      3578203.00     10609508.00      3578214.25     10609418.00
      3578085.00     10609293.00      3578060.50     10609230.00
      3578066.00     10609122.00      3577990.25     10609050.00
      3578003.75     10608987.00      3578075.75     10608908.00
      3578101.50     10608811.00      3578186.50     10608764.00
      3578237.00     10608685.00      3578179.50     10608610.00
      3578112.75     10608569.00      3578096.50     10608451.00
      3578051.75     10608353.00      3578014.75     10608330.00
      3577933.50     10608359.00      3577905.75     10608352.00
      3577811.75     10608205.00      3577826.00     10608092.00
      3577722.50     10607965.00      3577429.25     10607841.00
      3577334.00     10607888.00      3577231.00     10607907.00
      3577025.75     10607718.00      3576945.50     10607712.00
      3576930.75     10607671.00      3576870.75     10607609.00

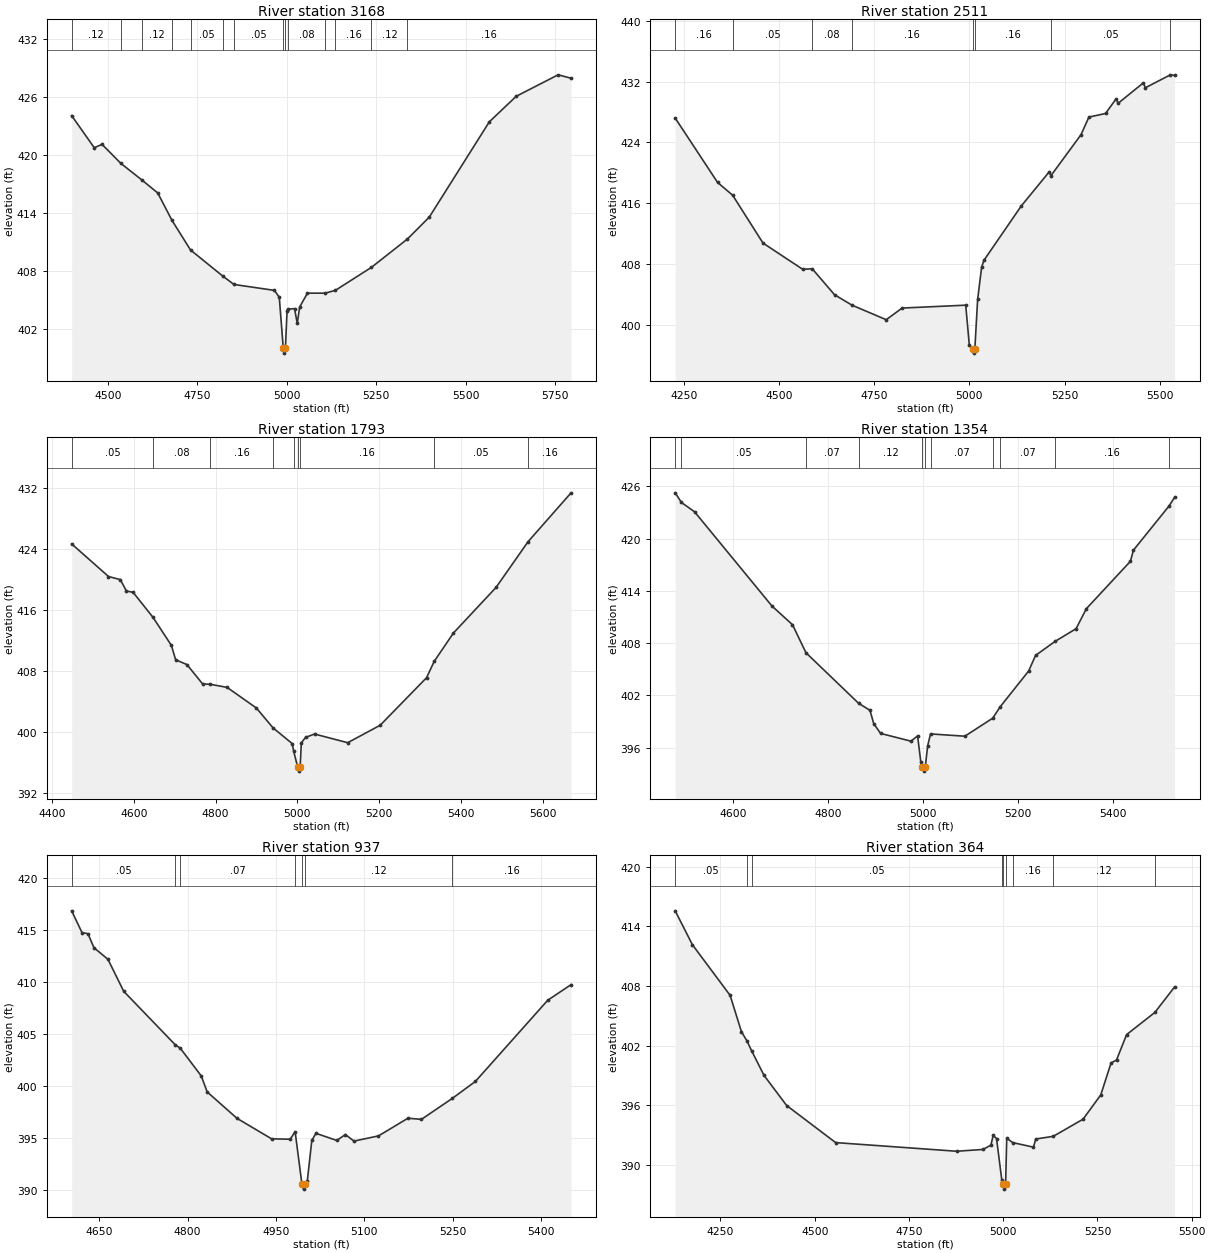
Type RM Length L Ch R = 1,3168,657,657,657
BEGIN DESCRIPTION:
UNT137 IN CCTC 5.0
END DESCRIPTION:
XS GIS Cut Line= 3
      3578716.51     10609167.41      3578167.92     10609646.56
      3577508.17     10609750.73
#Sta/Elev= 30
  4398.2  424.09  4461.4  420.76  4483.2  421.11  4536.1  419.13  4594.6  417.42
  4638.9  416.08  4678.7  413.24  4730.6  410.17  4821.4  407.45  4852.0  406.60
  4965.0  405.99  4978.7  405.28  4989.9  399.99  4992.7  399.49  4995.9  399.99
  5000.5  403.89  5002.6  404.04  5021.4  404.10  5029.0  402.56  5035.7  404.27
  5057.5  405.70  5106.8  405.70  5135.5  405.99  5236.3  408.37  5337.1  411.31
  5398.2  413.58  5565.9  423.44  5641.2  426.09  5758.3  428.31  5794.5  427.96
#Mann=14,-1,0
  4398.2    0.12       0  4536.1    0.16       0  4594.6    0.12       0
  4678.7    0.16       0  4730.6    0.05       0  4821.4    0.16       0
  4852.0    0.05       0  4989.9    0.03       0  4995.9    0.05       0
  5002.6    0.08       0  5106.8    0.05       0  5135.5    0.16       0
  5236.3    0.12       0  5337.1    0.16       0
Bank Sta=4989.9,4995.9
Exp/Cntr=0.3,0.1

Type RM Length L Ch R = 1,2511,718,718,718
BEGIN DESCRIPTION:
UNT137 IN CCTC 4.0
END DESCRIPTION:
XS GIS Cut Line= 2
      3578730.46     10608813.21      3577474.08     10609188.04
#Sta/Elev= 30
  4227.8  427.21  4339.0  418.76  4378.7  417.07  4458.3  410.79  4562.6  407.34
  4587.6  407.41  4646.1  404.00  4692.0  402.63  4781.8  400.72  4823.5  402.25
  4990.5  402.63  5000.0  397.36  5008.4  396.83  5011.1  396.33  5014.4  396.83
  5021.8  403.39  5032.2  407.59  5038.3  408.52  5136.6  415.68  5209.3  420.12
  5214.3  419.65  5293.1  425.02  5313.9  427.34  5357.5  427.81  5385.4  429.74
  5390.6  429.15  5456.9  431.84  5462.1  431.19  5527.7  432.89  5538.9  432.81
#Mann=8,-1,0
  4227.8    0.16       0  4378.7    0.05       0  4587.6    0.08       0
  4692.0    0.16       0  5008.4    0.07       0  5014.4    0.16       0
  5214.3    0.05       0  5527.7    0.16       0
Bank Sta=5008.4,5014.4
Exp/Cntr=0.3,0.1

Type RM Length L Ch R = 1,1793,439,439,439
BEGIN DESCRIPTION:
UNT137 IN CCTC 3.0
END DESCRIPTION:
XS GIS Cut Line= 2
      3578584.59     10608222.94      3577508.20     10608799.33
#Sta/Elev= 30
  4448.2  424.69  4538.3  420.41  4567.3  420.00  4582.2  418.50  4598.4  418.34
  4647.1  415.05  4692.1  411.37  4702.4  409.49  4730.1  408.85  4768.3  406.32
  4787.6  406.26  4828.2  405.86  4899.9  403.15  4940.5  400.55  4987.6  398.48
  4991.0  397.50  5000.9  395.37  5003.6  394.87  5006.9  395.37  5009.7  398.59
  5020.1  399.30  5042.1  399.74  5123.1  398.60  5202.5  400.89  5315.9  407.13
  5334.8  409.29  5381.7  413.00  5485.7  418.97  5564.1  424.98  5669.2  431.39
#Mann=9,-1,0
  4448.2    0.05       0  4647.1    0.08       0  4787.6    0.16       0
  4940.5    0.12       0  4991.0    0.16       0  5000.9    0.07       0
  5006.9    0.16       0  5334.8    0.05       0  5564.1    0.16       0
Bank Sta=5000.9,5006.9
Exp/Cntr=0.3,0.1

Type RM Length L Ch R = 1,1354,417,417,417
BEGIN DESCRIPTION:
UNT137 IN CCTC 2.0
END DESCRIPTION:
XS GIS Cut Line= 2
      3578237.34     10607910.46      3577417.90     10608570.18
#Sta/Elev= 30
  4478.2  425.25  4491.4  424.14  4518.9  423.08  4682.1  412.25  4725.3  410.11
  4753.7  406.89  4864.5  401.09  4888.5  400.28  4896.4  398.76  4910.8  397.63
  4974.8  396.74  4988.8  397.34  4995.6  394.35  4999.0  393.80  5001.8  393.30
  5005.0  393.80  5010.0  396.20  5016.0  397.57  5088.4  397.31  5147.1  399.38
  5162.7  400.68  5222.8  404.80  5237.2  406.58  5278.3  408.19  5322.6  409.65
  5344.3  411.95  5437.1  417.39  5443.5  418.67  5518.2  423.72  5530.2  424.74
#Mann=11,-1,0
  4478.2    0.08       0  4491.4    0.05       0  4753.7    0.07       0
  4864.5    0.12       0  4999.0    0.07       0  5005.0    0.12       0
  5016.0    0.07       0  5147.1    0.05       0  5162.7    0.07       0
  5278.3    0.16       0  5518.2     0.1       0
Bank Sta=4999,5005
Exp/Cntr=0.3,0.1

Type RM Length L Ch R = 1,937,573,573,573
BEGIN DESCRIPTION:
Mapping XS a5a69cec
END DESCRIPTION:
XS GIS Cut Line= 3
      3578007.03     10607826.05      3577668.47     10607878.14
      3577364.62     10608281.83
#Sta/Elev= 30
  4603.3  416.85  4620.9  414.76  4631.0  414.65  4641.2  413.30  4664.9  412.19
  4691.7  409.11  4779.1  403.97  4787.8  403.63  4823.3  400.97  4833.4  399.43
  4884.0  396.89  4942.7  394.92  4974.3  394.88  4982.7  395.60  4994.2  390.58
  4996.9  390.08  5000.2  390.58  5003.4  390.88  5011.0  394.76  5018.0  395.45
  5053.4  394.76  5068.0  395.33  5082.6  394.70  5124.2  395.20  5174.2  396.90
  5197.1  396.79  5249.3  398.80  5288.7  400.44  5411.5  408.25  5451.1  409.75
#Mann=7,-1,0
  4603.3    0.05       0  4779.1    0.12       0  4787.8    0.07       0
  4982.7    0.12       0  4994.2    0.07       0  5000.2    0.12       0
  5249.3    0.16       0
Bank Sta=4994.2,5000.2
Exp/Cntr=0.3,0.1

Type RM Length L Ch R = 1,364,0,0,0
BEGIN DESCRIPTION:
UNT137 IN CCTC 1.0
END DESCRIPTION:
XS GIS Cut Line= 4
      3577985.28     10607743.59      3577238.78     10607743.59
      3577095.55     10607839.08      3577191.04     10608234.06
#Sta/Elev= 30
  4129.8  415.56  4175.5  412.15  4275.5  407.06  4305.5  403.41  4319.9  402.49
  4332.9  401.46  4365.5  399.01  4425.5  395.98  4555.5  392.25  4876.3  391.38
  4946.3  391.56  4967.4  391.99  4973.4  392.97  4982.4  392.66  4996.4  388.45
  5000.4  388.07  5003.2  387.57  5006.4  388.07  5009.4  392.69  5025.3  392.25
  5080.4  391.79  5086.3  392.61  5132.8  392.88  5211.8  394.60  5258.8  397.04
  5286.2  400.26  5300.7  400.56  5327.4  403.11  5402.4  405.34  5454.8  407.91
#Mann=9,-1,0
  4129.8    0.05       0  4319.9    0.12       0  4332.9    0.05       0
  4996.4    0.12       0  5000.4    0.07       0  5006.4    0.12       0
  5025.3    0.16       0  5132.8    0.12       0  5402.4    0.16       0
Bank Sta=5000.4,5006.4
Exp/Cntr=0.3,0.1

Chan Stop Cuts=-1