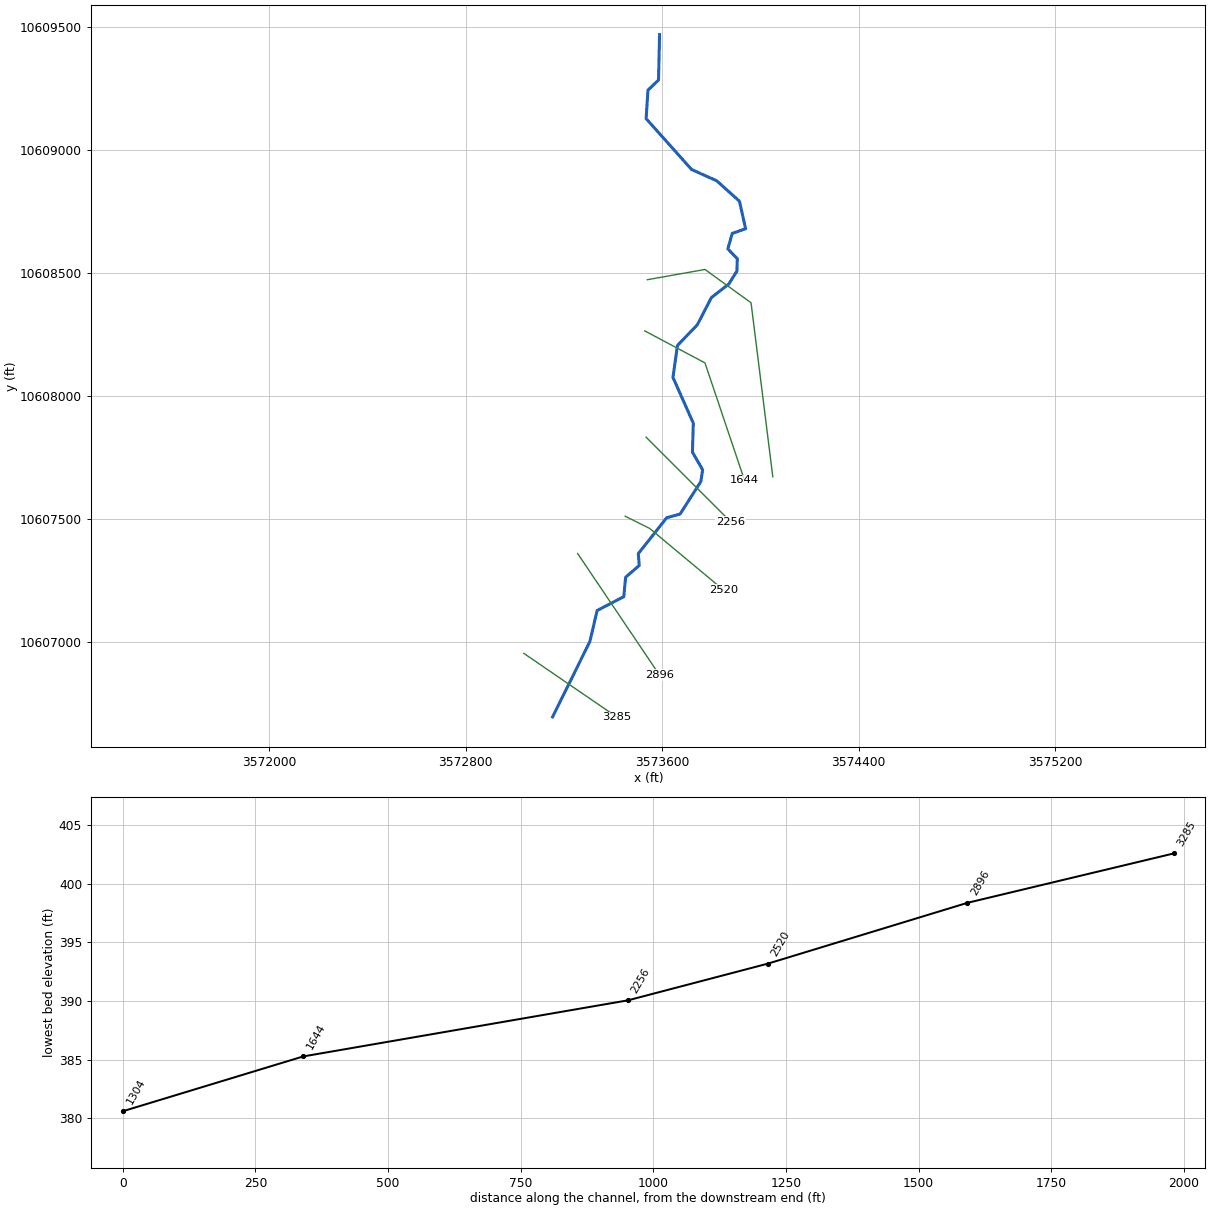
--- UNT138 IN CCTC.prj (project) ---

Proj Title=UNT138 IN CCTC Base Level Engineering
Current Plan=p01
Default Exp/Contr=0.3,0.1
English Units
Geom File=g01
Flow File=f01
Plan File=p01
BEGIN DESCRIPTION:
UNT138 IN CCTC
END DESCRIPTION:

--- UNT138 IN CCTC.p01 (plan) ---

Plan Title=Multiple Run
Short Identifier=Multiple
Geom File=g01
Flow File=f01
Subcritical Flow
K Sum by GR= 0
Std Step Tol= 0.01
Critical Tol= 0.01
Num of Std Step Trials= 20
Max Error Tol= 0.3
Flow Tol Ratio= 0.001
Split Flow NTrial= 30
Split Flow Tol= 0.02
Split Flow Ratio= 0.02
Log Output Level= 0
Friction Slope Method= 1
Unsteady Friction Slope Method= 2
Unsteady Bridges Friction Slope Method= 1
Parabolic Critical Depth
Global Vel Dist=  1 , 1 , 1
Global Log Level= 0
CheckData=True
Encroach Param= -1, 0, 0, 0
BEGIN DESCRIPTION:
Multiple Run
END DESCRIPTION:

--- UNT138 IN CCTC.f01 (steady flow) ---

Flow Title=Multiple
Number of Profiles=7
Profile Names=10-year,25-year,50-year,1pct_min,100-year,1pct_plu,500-year
River Rch & RM= UNT138 IN CCTC,Reach-1,3285
     838    1112    1332    1167    1578    2134    2202
Boundary for River Rch & Prof#=UNT138 IN CCTC,Reach-1,1
Up Type=0
Dn Type=3
Dn Slope=0.005
Boundary for River Rch & Prof#=UNT138 IN CCTC,Reach-1,2
Up Type=0
Dn Type=3
Dn Slope=0.005
Boundary for River Rch & Prof#=UNT138 IN CCTC,Reach-1,3
Up Type=0
Dn Type=3
Dn Slope=0.005
Boundary for River Rch & Prof#=UNT138 IN CCTC,Reach-1,4
Up Type=0
Dn Type=3
Dn Slope=0.005
Boundary for River Rch & Prof#=UNT138 IN CCTC,Reach-1,5
Up Type=0
Dn Type=3
Dn Slope=0.005
Boundary for River Rch & Prof#=UNT138 IN CCTC,Reach-1,6
Up Type=0
Dn Type=3
Dn Slope=0.005
Boundary for River Rch & Prof#=UNT138 IN CCTC,Reach-1,7
Up Type=0
Dn Type=3
Dn Slope=0.005

--- UNT138 IN CCTC.g01 (geometry) ---

Geom Title=Existing Conditions

River Reach=UNT138 IN CCTC,Reach-1
Reach XY= 30
      3573154.12     10606693.45      3573306.03     10607000.53
      3573335.32     10607126.39      3573443.83     10607182.82
      3573451.42     10607262.03      3573506.76     10607309.77
      3573503.00     10607358.00      3573618.50     10607504.00
      3573673.00     10607519.00      3573757.25     10607651.00
      3573764.75     10607699.00      3573723.25     10607771.00
      3573726.75     10607889.00      3573644.00     10608075.00
      3573662.25     10608205.00      3573743.00     10608289.00
      3573800.50     10608400.00      3573871.25     10608455.00
      3573904.25     10608508.00      3573905.75     10608558.00
      3573867.25     10608598.00      3573885.25     10608661.00
      3573939.50     10608680.00      3573914.50     10608792.00
      3573822.00     10608875.00      3573719.75     10608921.00
      3573534.75     10609128.00      3573542.25     10609244.00
      3573585.25     10609285.00      3573589.50     10609470.00

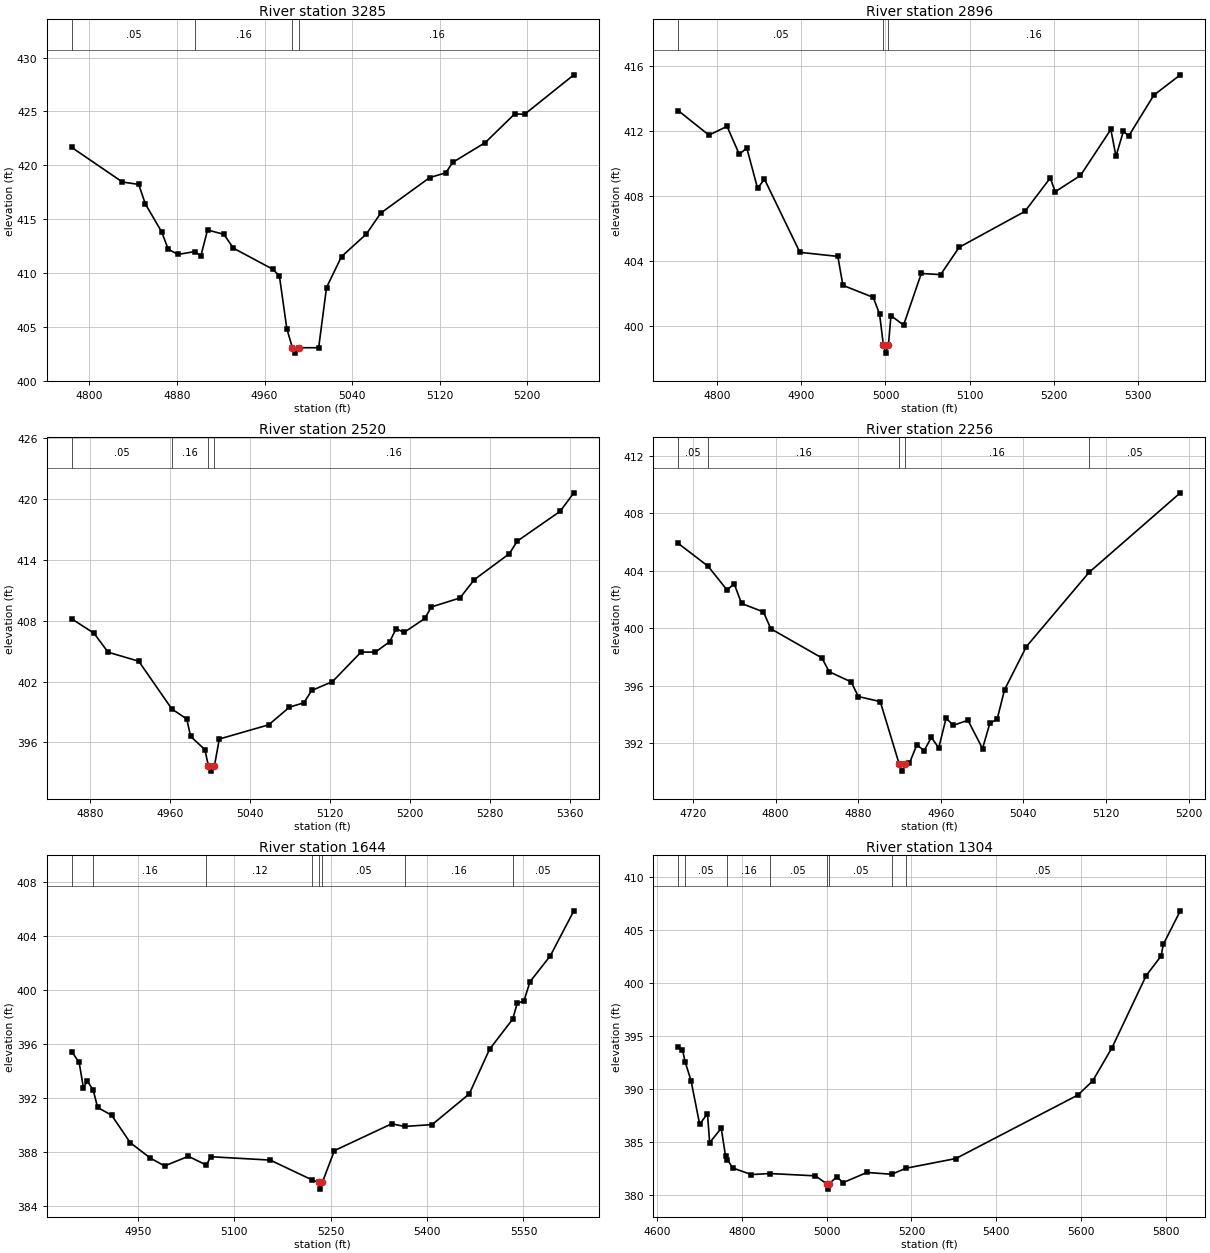
Type RM Length L Ch R = 1,3285,389,389,389
BEGIN DESCRIPTION:
UNT138 IN CCTC 3.0
END DESCRIPTION:
XS GIS Cut Line= 2
      3573037.44     10606952.03      3573416.13     10606692.65
#Sta/Elev= 30
  4783.8  421.66  4830.1  418.45  4845.0  418.23  4851.0  416.43  4866.0  413.82
  4872.0  412.21  4880.9  411.73  4896.5  412.00  4901.8  411.58  4907.9  414.00
  4922.8  413.60  4931.6  412.31  4967.5  410.36  4973.6  409.74  4980.4  404.84
  4985.5  403.07  4988.2  402.57  4991.5  403.07  5009.5  403.07  5016.7  408.66
  5030.4  411.53  5053.1  413.62  5066.3  415.57  5111.0  418.86  5125.8  419.31
  5132.0  420.27  5161.8  422.11  5188.8  424.78  5197.7  424.73  5242.8  428.40
#Mann=4,-1,0
  4783.8    0.05       0  4896.5    0.16       0  4985.5    0.07       0
  4991.5    0.16       0
Bank Sta=4985.5,4991.5
Exp/Cntr=0.3,0.1

Type RM Length L Ch R = 1,2896,376,376,376
BEGIN DESCRIPTION:
Mapping XS 3948bd33
END DESCRIPTION:
XS GIS Cut Line= 2
      3573256.22     10607358.24      3573588.94     10606864.36
#Sta/Elev= 30
  4754.2  413.28  4790.6  411.77  4812.1  412.31  4826.6  410.59  4835.5  410.98
  4848.3  408.50  4856.5  409.06  4898.5  404.56  4943.5  404.31  4949.5  402.53
  4985.5  401.79  4993.0  400.76  4997.5  398.86  5000.2  398.36  5003.5  398.86
  5006.5  400.66  5021.5  400.09  5042.5  403.26  5065.4  403.19  5087.4  404.87
  5165.4  407.08  5195.4  409.13  5201.4  408.29  5231.3  409.29  5267.3  412.12
  5273.4  410.47  5282.3  412.03  5288.3  411.70  5318.3  414.23  5349.7  415.48
#Mann=3,-1,0
  4754.2    0.05       0  4997.5    0.07       0  5003.5    0.16       0
Bank Sta=4997.5,5003.5
Exp/Cntr=0.3,0.1

Type RM Length L Ch R = 1,2520,264,264,264
BEGIN DESCRIPTION:
UNT138 IN CCTC 2.0
END DESCRIPTION:
XS GIS Cut Line= 3
      3573449.65     10607510.17      3573549.61     10607460.19
      3573849.63     10607210.17
#Sta/Elev= 30
  4862.0  408.17  4884.3  406.75  4898.3  404.89  4929.0  404.00  4962.2  399.29
  4977.0  398.32  4980.9  396.60  4995.2  395.30  4998.7  393.68  5001.5  393.18
  5004.7  393.68  5009.6  396.34  5059.0  397.74  5079.8  399.48  5094.2  399.91
  5102.0  401.12  5122.8  401.99  5151.4  404.90  5165.8  404.90  5180.1  405.93
  5186.6  407.21  5194.4  406.83  5215.2  408.21  5221.7  409.34  5250.4  410.23
  5264.7  412.03  5299.8  414.59  5307.6  415.82  5350.6  418.76  5364.3  420.58
#Mann=4,-1,0
  4862.0    0.05       0  4962.2    0.16       0  4998.7    0.07       0
  5004.7    0.16       0
Bank Sta=4998.7,5004.7
Exp/Cntr=0.3,0.1

Type RM Length L Ch R = 1,2256,612,612,612
BEGIN DESCRIPTION:
Mapping XS 38410bb4
END DESCRIPTION:
XS GIS Cut Line= 2
      3573534.65     10607831.92      3573878.38     10607488.19
#Sta/Elev= 30
  4705.8  405.90  4734.7  404.31  4753.0  402.66  4760.0  403.08  4767.1  401.72
  4788.3  401.13  4795.4  399.96  4844.9  397.93  4851.9  396.97  4873.2  396.26
  4880.2  395.24  4901.4  394.89  4919.7  390.55  4922.4  390.05  4925.7  390.55
  4929.7  390.61  4936.8  391.88  4943.9  391.48  4950.9  392.40  4958.0  391.66
  4965.1  393.73  4972.2  393.24  4986.3  393.59  5000.4  391.62  5007.5  393.38
  5014.6  393.67  5021.7  395.71  5042.9  398.72  5103.5  403.88  5191.9  409.42
#Mann=5,-1,0
  4705.8    0.05       0  4734.7    0.16       0  4919.7    0.07       0
  4925.7    0.16       0  5103.5    0.05       0
Bank Sta=4919.7,4925.7
Exp/Cntr=0.3,0.1

Type RM Length L Ch R = 1,1644,340,340,340
BEGIN DESCRIPTION:
Mapping XS 62be1c79
END DESCRIPTION:
XS GIS Cut Line= 3
      3573529.45     10608264.22      3573774.21     10608134.02
      3573935.07     10607656.63
#Sta/Elev= 30
  4847.4  395.45  4858.9  394.65  4865.6  392.75  4871.3  393.29  4880.7  392.61
  4887.6  391.32  4909.5  390.74  4938.2  388.72  4969.8  387.56  4991.8  386.99
  5028.8  387.70  5056.8  387.05  5063.4  387.67  5156.1  387.42  5221.7  385.94
  5231.2  385.77  5234.0  385.27  5237.2  385.77  5255.9  388.12  5345.1  390.11
  5365.0  389.91  5408.0  390.05  5465.7  392.32  5497.2  395.62  5533.3  397.86
  5540.2  399.02  5550.8  399.21  5560.2  400.63  5591.7  402.54  5628.4  405.88
#Mann=8,-1,0
  4847.4    0.05       0  4880.7    0.16       0  5056.8    0.12       0
  5221.7    0.05       0  5231.2    0.07       0  5237.2    0.05       0
  5365.0    0.16       0  5533.3    0.05       0
Bank Sta=5231.2,5237.2
Exp/Cntr=0.3,0.1

Type RM Length L Ch R = 1,1304,0,0,0
BEGIN DESCRIPTION:
UNT138 IN CCTC 1.0
END DESCRIPTION:
XS GIS Cut Line= 4
      3573539.87     10608472.57      3573774.21     10608514.23
      3573961.71     10608378.81      3574050.26     10607670.43
#Sta/Elev= 30
  4650.3  393.95  4660.2  393.74  4666.6  392.59  4680.5  390.81  4700.8  386.70
  4719.2  387.72  4724.3  384.97  4751.6  386.34  4761.8  383.70  4766.3  383.39
  4778.3  382.60  4822.7  381.97  4866.1  382.07  4973.6  381.85  5000.0  381.10
  5002.8  380.60  5006.0  381.10  5023.9  381.76  5038.6  381.21  5095.1  382.17
  5153.3  382.00  5187.1  382.57  5304.4  383.48  5591.9  389.46  5626.9  390.79
  5672.5  393.92  5753.1  400.72  5788.2  402.56  5793.4  403.66  5833.5  406.82
#Mann=8,-1,0
  4650.3    0.08       0  4666.6    0.05       0  4766.3    0.16       0
  4866.1    0.05       0  5000.0    0.03       0  5006.0    0.05       0
  5153.3    0.12       0  5187.1    0.05       0
Bank Sta=5000,5006
Exp/Cntr=0.3,0.1

Chan Stop Cuts=-1