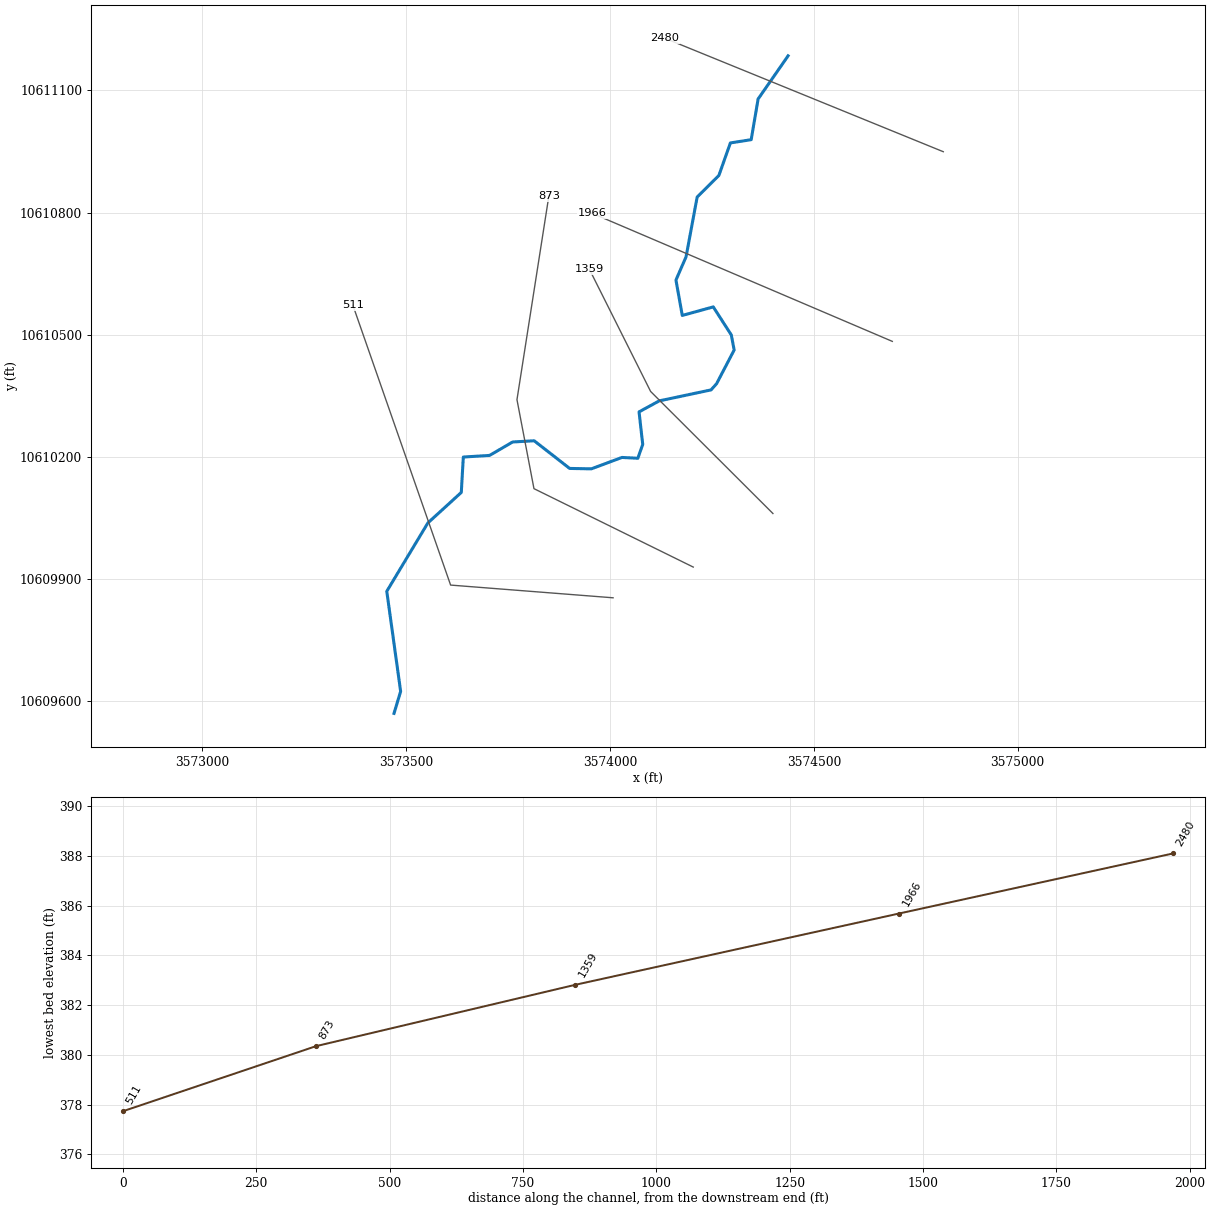
--- UNT139 IN CCTC.prj (project) ---

Proj Title=UNT139 IN CCTC Base Level Engineering
Current Plan=p01
Default Exp/Contr=0.3,0.1
English Units
Geom File=g01
Flow File=f01
Plan File=p01
Y Axis Title=Elevation
X Axis Title(PF)=Main Channel Distance
X Axis Title(XS)=Station
BEGIN DESCRIPTION:
UNT139 IN CCTC
END DESCRIPTION:
DSS Export Rating Curves= 0
DSS Export Rating Curve Sorted= 0
DSS Export Volume Flow Curves= 0
DXF OffsetX= 0
DXF OffsetY= 0
DXF ScaleX= 1
DXF ScaleY= 10

--- UNT139 IN CCTC.p01 (plan) ---

Plan Title=Multiple Run
Short Identifier=Multiple
Geom File=g01
Flow File=f01
Subcritical Flow
K Sum by GR= 0
Std Step Tol= 0.01
Critical Tol= 0.01
Num of Std Step Trials= 20
Max Error Tol= 0.3
Flow Tol Ratio= 0.001
Split Flow NTrial= 30
Split Flow Tol= 0.02
Split Flow Ratio= 0.02
Log Output Level= 0
Friction Slope Method= 1
Unsteady Friction Slope Method= 2
Unsteady Bridges Friction Slope Method= 1
Parabolic Critical Depth
Global Vel Dist=  1 , 1 , 1
Global Log Level= 0
CheckData=True
Encroach Param= -1, 0, 0, 0
BEGIN DESCRIPTION:
Multiple Run
END DESCRIPTION:

--- UNT139 IN CCTC.f01 (steady flow) ---

Flow Title=Multiple
Number of Profiles=7
Profile Names=10-year,25-year,50-year,1pct_min,100-year,1pct_plu,500-year
River Rch & RM= UNT139 IN CCTC,Reach-1,2480
     854    1126    1341    1167    1578    2134    2175
Boundary for River Rch & Prof#=UNT139 IN CCTC,Reach-1,1
Up Type=0
Dn Type=3
Dn Slope=0.005
Boundary for River Rch & Prof#=UNT139 IN CCTC,Reach-1,2
Up Type=0
Dn Type=3
Dn Slope=0.005
Boundary for River Rch & Prof#=UNT139 IN CCTC,Reach-1,3
Up Type=0
Dn Type=3
Dn Slope=0.005
Boundary for River Rch & Prof#=UNT139 IN CCTC,Reach-1,4
Up Type=0
Dn Type=3
Dn Slope=0.005
Boundary for River Rch & Prof#=UNT139 IN CCTC,Reach-1,5
Up Type=0
Dn Type=3
Dn Slope=0.005
Boundary for River Rch & Prof#=UNT139 IN CCTC,Reach-1,6
Up Type=0
Dn Type=3
Dn Slope=0.005
Boundary for River Rch & Prof#=UNT139 IN CCTC,Reach-1,7
Up Type=0
Dn Type=3
Dn Slope=0.005

--- UNT139 IN CCTC.g01 (geometry) ---

Geom Title=Existing Conditions
Program Version=4.10

River Reach=UNT139 IN CCTC  ,Reach-1
Reach XY= 30
      3574436.75       10611185.      3574363.25       10611079.
      3574346.25       10610979.      3574295.25       10610971.
        3574267.       10610891.      3574213.75       10610838.
       3574186.5       10610691.      3574161.75       10610634.
      3574177.25       10610547.      3574253.25       10610568.
       3574297.5       10610499.       3574304.5       10610462.
      3574261.25       10610379.      3574247.75       10610364.
      3574120.75       10610337.      3574071.25       10610310.
      3574080.25       10610230.      3574068.25       10610196.
      3574029.25       10610198.      3573954.25       10610170.
        3573901.       10610171.        3573814.       10610239.
      3573761.25       10610236.      3573704.75       10610203.
      3573640.25       10610199.      3573635.25       10610112.
      3573553.25       10610037.       3573452.5       10609869.
       3573486.5       10609623.      3573470.25       10609569.

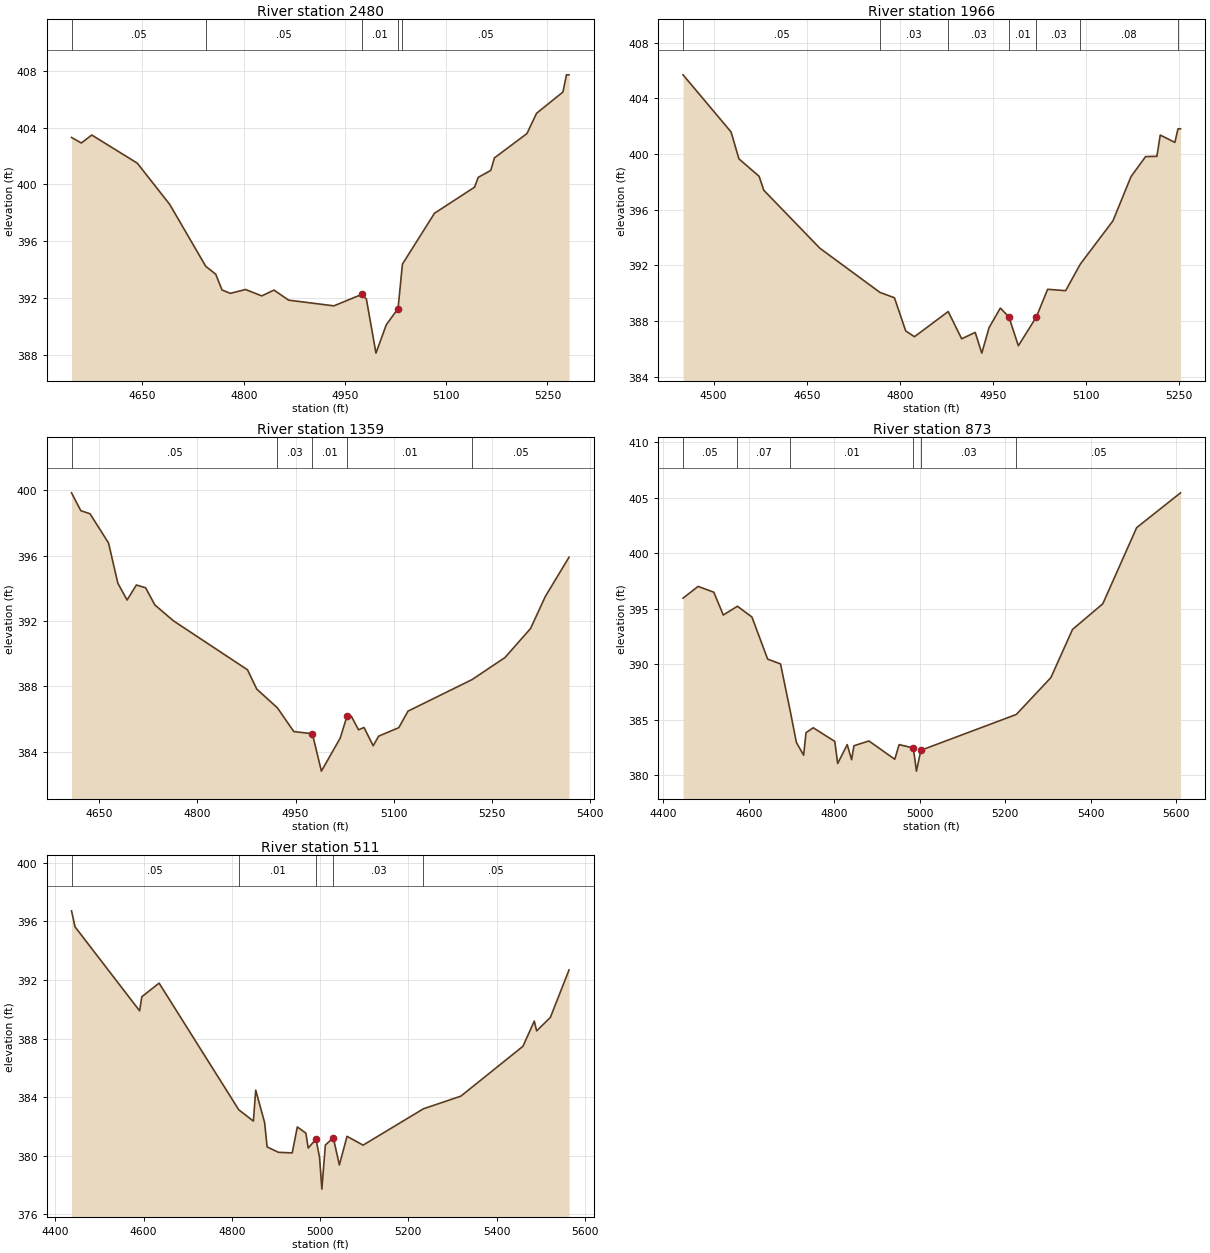
Type RM Length L Ch R = 1 ,2480    ,514,514,514
BEGIN DESCRIPTION:
UNT139 IN CCTC 5.0
END DESCRIPTION:
XS GIS Cut Line= 2
      3574817.38     10610949.42      3574135.09     10611228.07
#Sta/Elev= 30
  4544.9   403.3  4559.4  402.91  4574.9  403.47  4642.3  401.49  4690.4  398.58
  4743.8  394.22  4758.5  393.67  4767.8  392.56  4780.1  392.32  4802.7  392.59
  4826.7  392.14  4844.9  392.55  4866.5  391.84  4933.6  391.44  4974.6  392.24
  4981.7  391.92  4995.9  388.11  5011.1   390.1  5028.6  391.25  5035.1  394.38
  5082.6  397.96    5142   399.8  5147.4  400.49    5166  400.98  5171.4  401.86
  5219.5  403.57  5233.8     405  5272.9   406.5  5278.1  407.71  5281.9  407.71
#Mann= 5 ,-1 , 0
  4544.9     .05       0  4743.8     .05       0  4974.6     .01       0
  5028.6     .03       0  5035.1     .05       0
Bank Sta=4974.6,5028.6
XS Rating Curve= 0 ,0
Exp/Cntr=0.3,0.1

Type RM Length L Ch R = 1 ,1966    ,607,607,607
BEGIN DESCRIPTION:
UNT139 IN CCTC 4.0
END DESCRIPTION:
XS GIS Cut Line= 2
      3574692.37     10610483.28       3573955.4     10610798.38
#Sta/Elev= 30
  4450.8   405.7  4528.2  401.59  4540.8  399.66  4573.4   398.4  4580.9   397.4
  4671.3  393.23  4767.9  390.06  4791.4  389.67  4809.5  387.29  4823.6  386.87
    4878  388.68  4899.7  386.72  4921.5  387.18  4932.1  385.69  4943.8  387.52
    4962  388.93  4975.8  388.29    4991  386.22    5020  388.29  5038.2  390.28
  5067.2  390.18  5090.8  392.09  5143.4   395.2  5172.5  398.38    5196  399.82
  5214.2  399.84  5219.6  401.37  5243.2  400.84  5248.2  401.82  5252.3  401.82
#Mann= 7 ,-1 , 0
  4450.8     .05       0  4767.9     .03       0    4878     .03       0
  4975.8     .01       0    5020     .03       0  5090.8     .08       0
  5248.2     .05       0
Bank Sta=4975.8,5020
XS Rating Curve= 0 ,0
Exp/Cntr=0.3,0.1

Type RM Length L Ch R = 1 ,1359    ,486,486,486
BEGIN DESCRIPTION:
UNT139 IN CCTC 3.0
END DESCRIPTION:
XS GIS Cut Line= 3
      3574399.58     10610060.22      3574099.61     10610360.19
      3573949.62     10610660.16
#Sta/Elev= 30
    4608  399.85  4622.1  398.76  4636.2  398.57  4664.5  396.78  4678.7  394.32
  4692.8  393.29    4707  394.21  4721.1  394.04  4735.2  392.99  4763.5  392.02
  4876.7  389.02  4890.8  387.84  4922.4  386.69  4947.4  385.24  4975.7  385.11
  4989.5  382.82  5018.1  384.83  5028.7  386.19    5035  386.19  5046.2  385.35
  5054.6  385.49  5068.6  384.37  5076.9  384.96  5107.7  385.48  5121.7  386.49
  5219.5  388.42  5269.8  389.77  5308.9  391.55  5331.3   393.5  5367.6  395.91
#Mann= 5 ,-1 , 0
    4608     .05       0  4922.4     .03       0  4975.7     .01       0
  5028.7     .01       0  5219.5     .05       0
Bank Sta=4975.7,5028.7
XS Rating Curve= 0 ,0
Exp/Cntr=0.3,0.1

Type RM Length L Ch R = 1 ,873     ,362,362,362
BEGIN DESCRIPTION:
UNT139 IN CCTC 2.0
END DESCRIPTION:
XS GIS Cut Line= 4
      3574204.13     10609928.58      3573813.49      10610121.3
      3573771.82     10610340.05      3573849.94       10610840.
#Sta/Elev= 30
  4445.9  395.95  4481.1  397.01  4517.8  396.49  4540.1  394.43  4573.1  395.22
  4607.1  394.25  4643.9  390.45    4674  390.02  4696.3  385.86  4711.2  382.93
  4728.1  381.79  4733.7  383.82  4750.6  384.26    4801  383.03  4807.8  381.04
  4830.1  382.74  4840.4  381.38  4845.9  382.64  4880.9  383.07  4941.4  381.42
  4951.6  382.74  4984.8  382.44  4992.1  380.35  5002.5  382.23  5225.8  385.46
  5306.7  388.78  5357.4  393.13  5428.2  395.44  5507.5  402.31  5610.2  405.45
#Mann= 6 ,-1 , 0
  4445.9     .05       0  4573.1     .07       0  4696.3     .01       0
  4984.8     .01       0  5002.5     .03       0  5225.8     .05       0
Bank Sta=4984.8,5002.5
XS Rating Curve= 0 ,0
Exp/Cntr=0.3,0.1

Type RM Length L Ch R = 1 ,511     ,0,0,0
BEGIN DESCRIPTION:
UNT139 IN CCTC 1.0
END DESCRIPTION:
XS GIS Cut Line= 3
      3574007.53     10609853.06      3573609.07     10609884.31
       3573369.5     10610571.77
#Sta/Elev= 30
  4436.7  396.71  4444.6  395.62    4591  389.89    4596  390.85  4635.2  391.78
  4815.8  383.14  4848.9  382.37  4854.2  384.48  4874.4  382.27    4880  380.61
  4905.8  380.24  4936.9   380.2  4948.5  381.97  4967.9  381.55  4973.2  380.53
  4990.9  381.14    4999  379.88  5004.1  377.73  5012.1  380.74  5030.1  381.23
  5043.8  379.38  5061.2  381.33  5097.6  380.73  5234.4  383.21  5319.2  384.07
  5459.9  387.47  5485.7  389.19    5491  388.52  5522.1  389.44  5564.4  392.68
#Mann= 5 ,-1 , 0
  4436.7     .05       0  4815.8     .01       0  4990.9     .01       0
  5030.1     .03       0  5234.4     .05       0
Bank Sta=4990.9,5030.1
XS Rating Curve= 0 ,0
Exp/Cntr=0.3,0.1

Chan Stop Cuts=-1
Use User Specified Reach Order=0
Composite Channel Slope=5