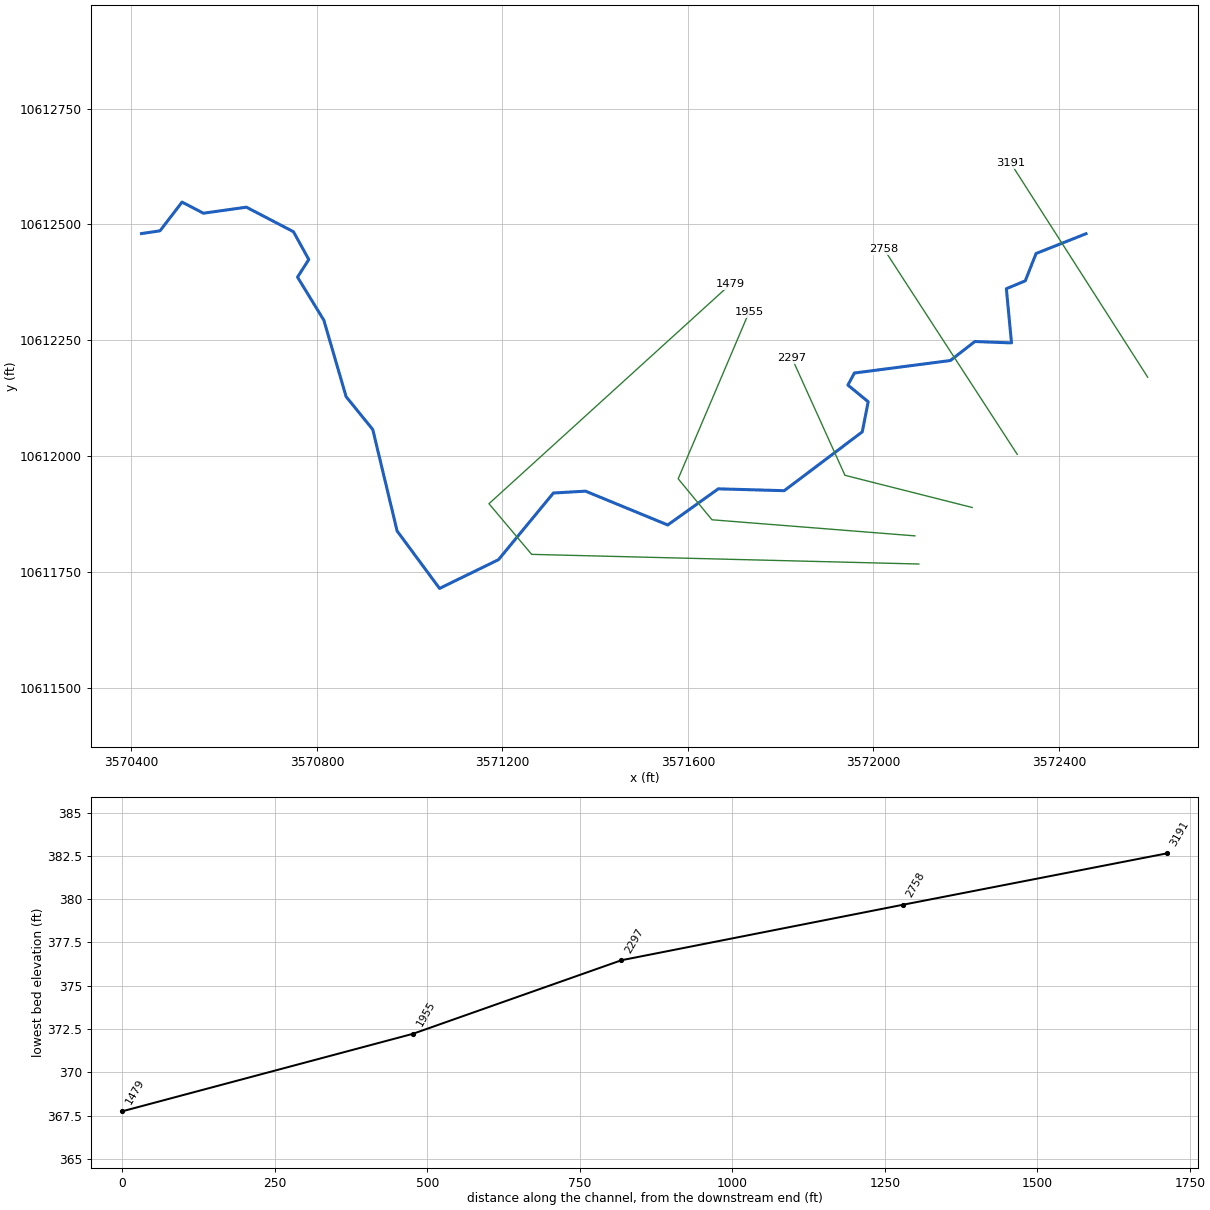
--- UNT140 IN CCTC.prj (project) ---

Proj Title=UNT140 IN CCTC Base Level Engineering
Current Plan=p01
Default Exp/Contr=0.3,0.1
English Units
Geom File=g01
Flow File=f01
Plan File=p01
Y Axis Title=Elevation
X Axis Title(PF)=Main Channel Distance
X Axis Title(XS)=Station
BEGIN DESCRIPTION:
UNT140 IN CCTC
END DESCRIPTION:
DSS Export Rating Curves= 0
DSS Export Rating Curve Sorted= 0
DSS Export Volume Flow Curves= 0
DXF OffsetX= 0
DXF OffsetY= 0
DXF ScaleX= 1
DXF ScaleY= 10

--- UNT140 IN CCTC.p01 (plan) ---

Plan Title=Multiple Run
Short Identifier=Multiple
Geom File=g01
Flow File=f01
Subcritical Flow
K Sum by GR= 0
Std Step Tol= 0.01
Critical Tol= 0.01
Num of Std Step Trials= 20
Max Error Tol= 0.3
Flow Tol Ratio= 0.001
Split Flow NTrial= 30
Split Flow Tol= 0.02
Split Flow Ratio= 0.02
Log Output Level= 0
Friction Slope Method= 1
Unsteady Friction Slope Method= 2
Unsteady Bridges Friction Slope Method= 1
Parabolic Critical Depth
Global Vel Dist=  1 , 1 , 1
Global Log Level= 0
CheckData=True
Encroach Param= -1, 0, 0, 0
BEGIN DESCRIPTION:
Multiple Run
END DESCRIPTION:

--- UNT140 IN CCTC.f01 (steady flow) ---

Flow Title=Multiple
Number of Profiles=7
Profile Names=10-year,25-year,50-year,1pct_min,100-year,1pct_plu,500-year
River Rch & RM= UNT140 IN CCTC,Reach-1,3191
     638     834     988     858    1161    1570    1590
Boundary for River Rch & Prof#=UNT140 IN CCTC,Reach-1,1
Up Type=0
Dn Type=3
Dn Slope=0.005
Boundary for River Rch & Prof#=UNT140 IN CCTC,Reach-1,2
Up Type=0
Dn Type=3
Dn Slope=0.005
Boundary for River Rch & Prof#=UNT140 IN CCTC,Reach-1,3
Up Type=0
Dn Type=3
Dn Slope=0.005
Boundary for River Rch & Prof#=UNT140 IN CCTC,Reach-1,4
Up Type=0
Dn Type=3
Dn Slope=0.005
Boundary for River Rch & Prof#=UNT140 IN CCTC,Reach-1,5
Up Type=0
Dn Type=3
Dn Slope=0.005
Boundary for River Rch & Prof#=UNT140 IN CCTC,Reach-1,6
Up Type=0
Dn Type=3
Dn Slope=0.005
Boundary for River Rch & Prof#=UNT140 IN CCTC,Reach-1,7
Up Type=0
Dn Type=3
Dn Slope=0.005

--- UNT140 IN CCTC.g01 (geometry) ---

Geom Title=Existing Conditions
Program Version=4.10

River Reach=UNT140 IN CCTC  ,Reach-1
Reach XY= 30
      3572458.44      10612479.7      3572350.75       10612437.
       3572327.5       10612378.      3572286.75       10612361.
      3572297.75       10612244.      3572218.75       10612247.
        3572166.       10612206.        3571959.       10612179.
        3571945.       10612153.      3571988.75       10612117.
        3571976.       10612052.      3571807.75       10611925.
       3571665.5       10611929.       3571556.5       10611851.
      3571379.25       10611924.        3571310.       10611920.
       3571191.5       10611776.       3571064.5       10611714.
        3570973.       10611838.       3570920.5       10612057.
        3570863.       10612128.        3570815.       10612293.
      3570758.25       10612386.       3570782.5       10612424.
       3570749.5       10612484.        3570648.       10612537.
      3570555.25       10612524.      3570509.25       10612548.
      3570461.75       10612486.      3570421.75       10612480.

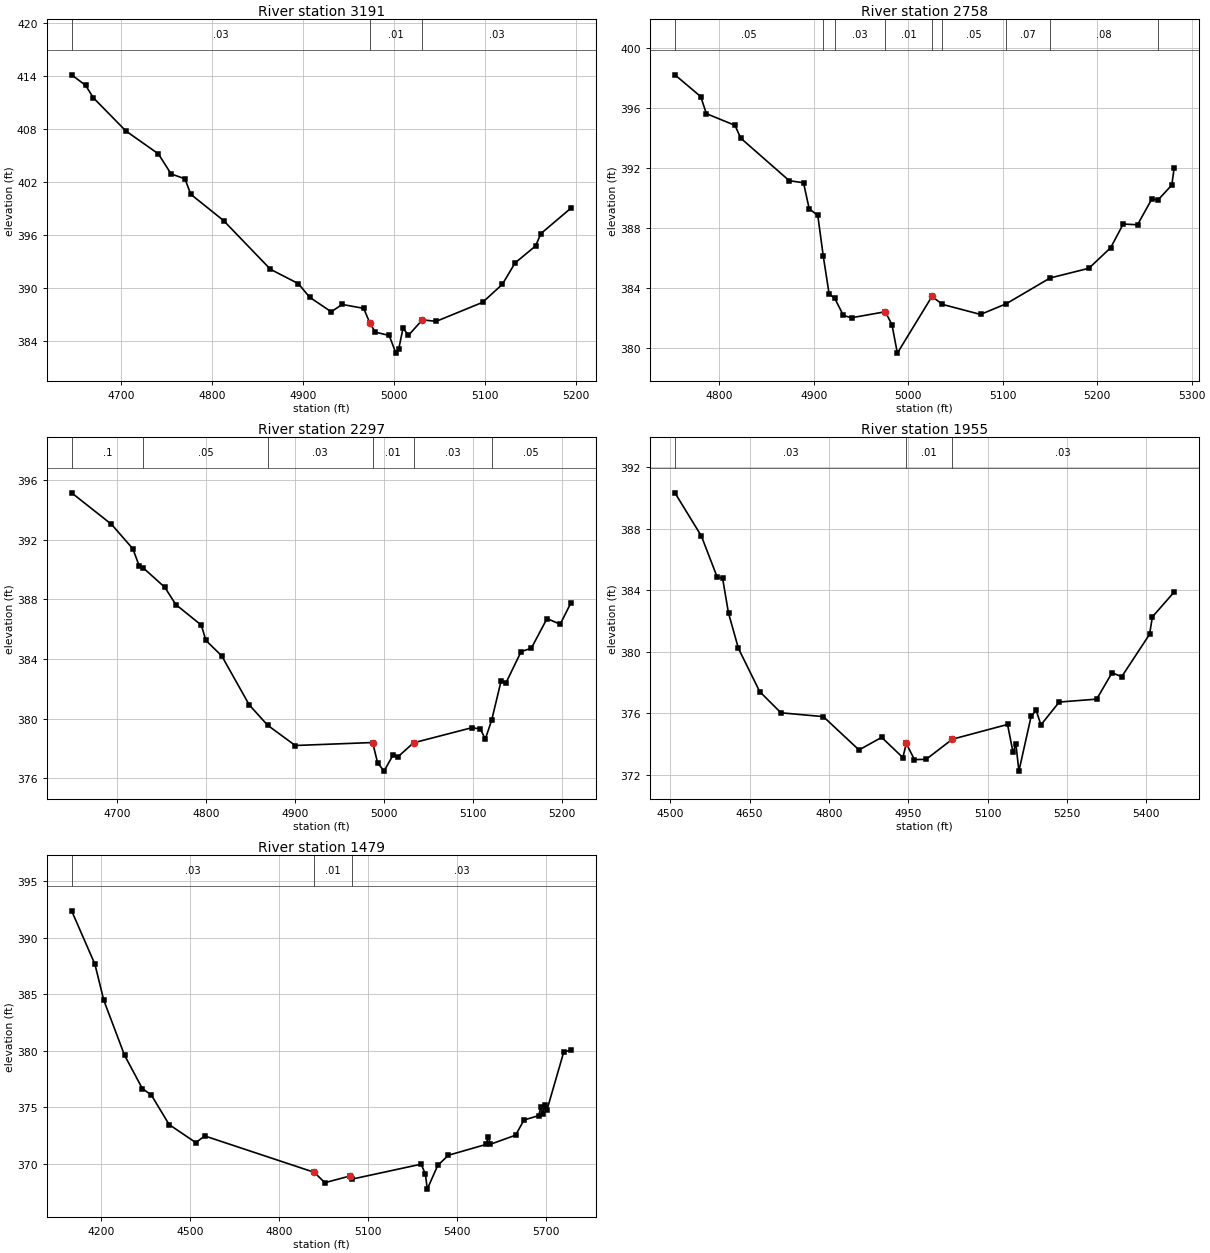
Type RM Length L Ch R = 1 ,3191    ,433,433,433
BEGIN DESCRIPTION:
UNT140 IN CCTC 2.0
END DESCRIPTION:
XS GIS Cut Line= 2
      3572591.43     10612170.01      3572296.32     10612631.77
#Sta/Elev= 30
  4646.1  414.09  4661.4   412.9    4670  411.49  4705.6  407.75  4741.3  405.16
  4755.3  402.89  4770.5  402.34  4776.9  400.59  4812.9  397.62  4864.4  392.11
  4894.9   390.5  4907.4  388.96  4931.1  387.31  4943.1  388.14  4966.7   387.7
  4973.6  386.02  4979.5  385.01  4994.7  384.64  5002.1  382.64  5005.3  383.14
  5009.9  385.47  5015.9  384.65  5031.1   386.4  5046.3  386.23  5097.3  388.38
    5119  390.42  5132.9  392.83  5155.4  394.75  5161.3  396.15  5194.1  399.01
#Mann= 3 , 0 , 0
  4646.1     .03       0  4973.6     .01       0  5031.1     .03       0
Bank Sta=4973.6,5031.1
XS Rating Curve= 0 ,0
Exp/Cntr=0.3,0.1

Type RM Length L Ch R = 1 ,2758    ,461,461,461
BEGIN DESCRIPTION:
Mapping XS 8d0f4a16
END DESCRIPTION:
XS GIS Cut Line= 2
      3572310.19     10612003.33      3572022.81     10612446.51
#Sta/Elev= 30
  4753.2  398.23  4780.5  396.78  4786.5  395.64  4816.8  394.86  4822.8  394.01
  4874.2  391.17  4889.3  391.03  4895.3   389.3  4904.4  388.85  4910.1  386.18
  4916.4  383.61  4922.3  383.33  4931.5  382.18  4940.1  382.03  4975.9  382.43
  4982.9  381.56  4988.6  379.67  5025.2  383.45  5036.3  382.92  5076.6  382.25
  5103.7  382.96  5150.2  384.68  5191.3  385.33  5214.3   386.7  5227.6  388.28
  5242.7  388.23  5257.9  389.95  5264.2  389.87    5279  390.88  5281.4  391.99
#Mann= 9 ,-1 , 0
  4753.2     .05       0  4910.1     .07       0  4922.3     .03       0
  4975.9     .01       0  5025.2     .03       0  5036.3     .05       0
  5103.7     .07       0  5150.2     .08       0  5264.2     .07       0
Bank Sta=4975.9,5025.2
XS Rating Curve= 0 ,0
Exp/Cntr=0.3,0.1

Type RM Length L Ch R = 1 ,2297    ,342,342,342
BEGIN DESCRIPTION:
Mapping XS e35bfc2b
END DESCRIPTION:
XS GIS Cut Line= 3
      3572212.98     10611888.74      3571938.67     10611958.18
      3571824.35     10612211.07
#Sta/Elev= 30
  4649.4  395.15  4694.1  393.04  4718.2  391.39  4725.1  390.27    4730   390.1
    4754  388.81  4766.4  387.65    4795  386.27  4800.2  385.24  4817.9  384.21
  4848.9  380.91  4869.5  379.55  4900.5  378.19  4987.4  378.39  4992.9  377.04
  5000.2  376.47  5010.5  377.57    5016  377.44  5033.3  378.37  5099.2  379.39
  5108.4  379.29  5113.9  378.62  5121.1   379.9  5131.5  382.49    5137  382.38
  5154.1  384.49  5165.6  384.72  5183.2  386.71    5198  386.33  5209.9  387.75
#Mann= 6 ,-1 , 0
  4649.4      .1       0    4730     .05       0  4869.5     .03       0
  4987.4     .01       0  5033.3     .03       0  5121.1     .05       0
Bank Sta=4987.4,5033.3
XS Rating Curve= 0 ,0
Exp/Cntr=0.3,0.1

Type RM Length L Ch R = 1 ,1955    ,476,476,476
BEGIN DESCRIPTION:
Mapping XS f5eff750
END DESCRIPTION:
XS GIS Cut Line= 4
      3572089.47     10611827.47      3571651.95     10611862.19
      3571579.03     10611950.73      3571731.81     10612310.11
#Sta/Elev= 30
  4508.6  390.35  4558.6  387.54  4588.7  384.85  4598.7   384.8    4610  382.51
  4628.8  380.21    4669   377.4  4709.1  376.02  4789.3  375.77  4856.8   373.6
  4899.7  374.42  4939.8   373.1  4946.2  374.02  4961.7  372.97  4983.8  372.99
  5033.4   374.3  5137.7  375.26  5148.1  373.45  5153.6  373.97  5159.2  372.22
  5182.6  375.83    5192  376.17  5200.8  375.23  5235.5  376.72  5306.3  376.91
  5335.4  378.63  5353.6  378.37  5406.3  381.13  5411.7  382.27  5452.7  383.88
#Mann= 3 , 0 , 0
  4508.6     .03       0  4946.2     .01       0  5033.4     .03       0
Bank Sta=4946.2,5033.4
XS Rating Curve= 0 ,0
Exp/Cntr=0.3,0.1

Type RM Length L Ch R = 1 ,1479    ,0,0,0
BEGIN DESCRIPTION:
UNT140 IN CCTC 1.0
END DESCRIPTION:
XS GIS Cut Line= 4
      3572098.08     10611766.71      3571263.06     10611787.54
      3571171.04     10611896.91      3571691.86     10612370.86
#Sta/Elev= 30
  4100.7   392.4  4179.2  387.67  4209.2  384.47  4279.2   379.6  4339.2  376.65
  4369.3  376.09  4429.3  373.47  4519.3  371.87  4549.3  372.46 4918.41  369.24
  4954.1  368.32  5039.9  368.92  5046.4  368.64  5278.7  369.96  5292.9   369.1
  5299.4  367.75  5334.8  369.86  5370.6  370.75  5497.6  371.71  5505.1   372.4
  5511.8  371.72    5597  372.53  5625.3  373.87  5674.7  374.26  5682.1     375
  5688.9  374.44  5696.3  375.22    5703  374.78  5759.8  379.94  5783.1  380.03
#Mann= 3 ,-1 , 0
  4100.7     .03       0 4918.41     .01       0  5046.4     .03       0
Bank Sta=4918.41,5039.9
XS Rating Curve= 0 ,0
Exp/Cntr=0.3,0.1

Chan Stop Cuts=-1
Use User Specified Reach Order=0
Composite Channel Slope=5