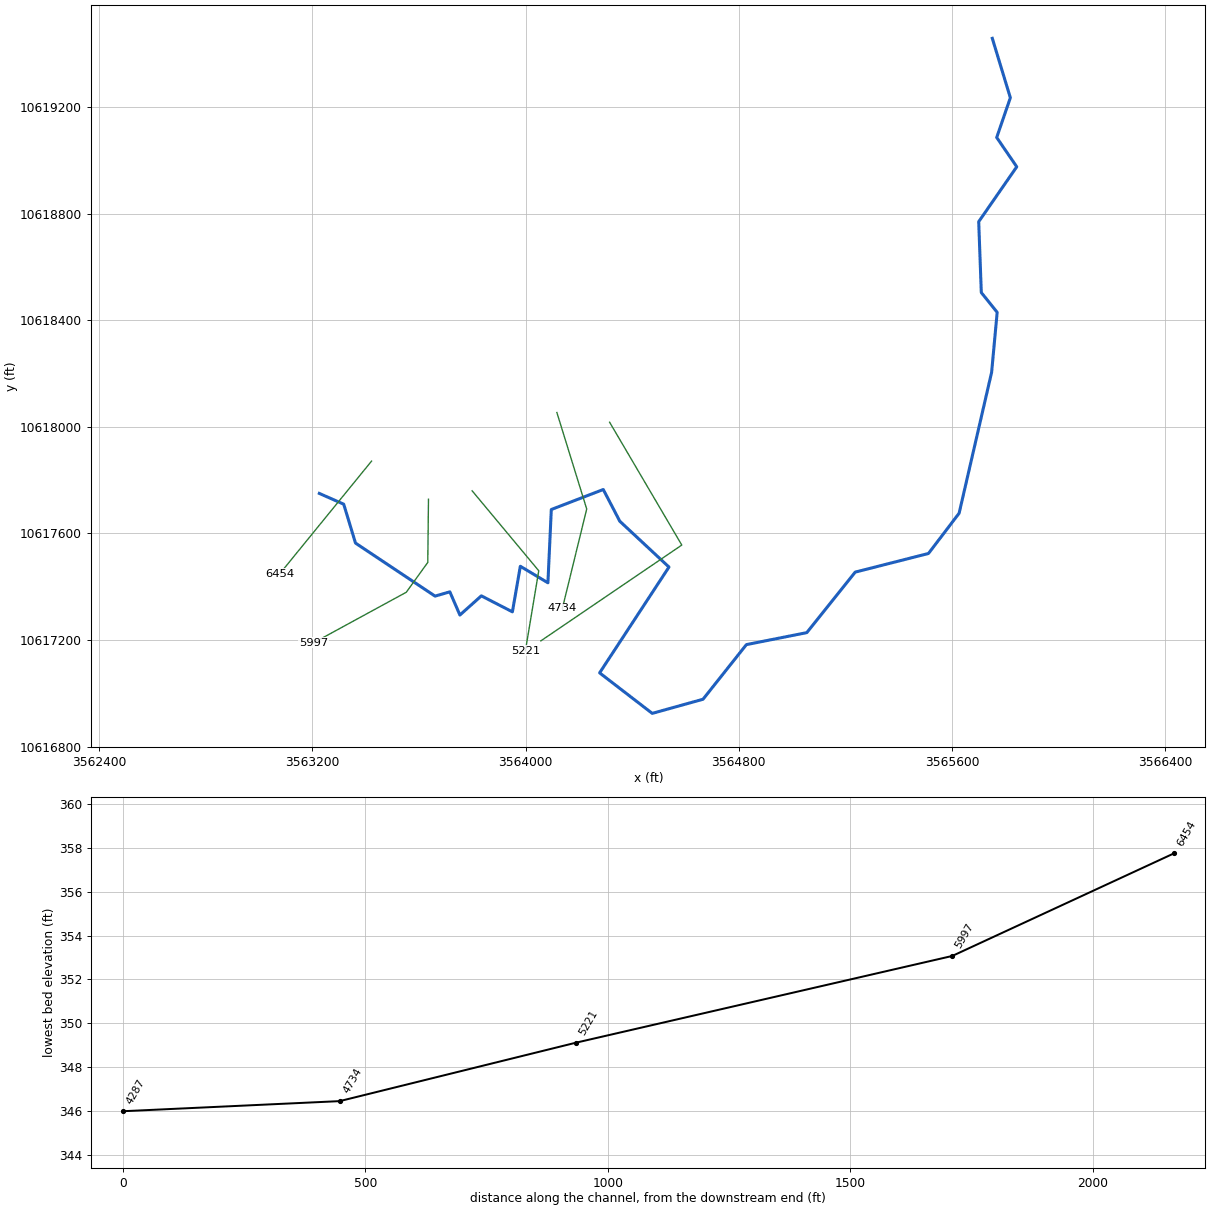
--- UNT145 IN CCTC.prj (project) ---

Proj Title=UNT145 IN CCTC Base Level Engineering
Current Plan=p01
Default Exp/Contr=0.3,0.1
English Units
Geom File=g01
Flow File=f01
Plan File=p01
BEGIN DESCRIPTION:
UNT145 IN CCTC
END DESCRIPTION:

--- UNT145 IN CCTC.p01 (plan) ---

Plan Title=Multiple Run
Short Identifier=Multiple
Geom File=g01
Flow File=f01
Subcritical Flow
K Sum by GR= 0
Std Step Tol= 0.01
Critical Tol= 0.01
Num of Std Step Trials= 20
Max Error Tol= 0.3
Flow Tol Ratio= 0.001
Split Flow NTrial= 30
Split Flow Tol= 0.02
Split Flow Ratio= 0.02
Log Output Level= 0
Friction Slope Method= 1
Unsteady Friction Slope Method= 2
Unsteady Bridges Friction Slope Method= 1
Parabolic Critical Depth
Global Vel Dist=  1 , 1 , 1
Global Log Level= 0
CheckData=True
Encroach Param= -1, 0, 0, 0
BEGIN DESCRIPTION:
Multiple Run
END DESCRIPTION:

--- UNT145 IN CCTC.f01 (steady flow) ---

Flow Title=Multiple
Number of Profiles=7
Profile Names=10-year,25-year,50-year,1pct_min,100-year,1pct_plu,500-year
River Rch & RM= UNT145 IN CCTC,Reach-1,6454
    1325    1809    2206    1963    2655    3590    3831
Boundary for River Rch & Prof#=UNT145 IN CCTC,Reach-1,1
Up Type=0
Dn Type=3
Dn Slope=0.005
Boundary for River Rch & Prof#=UNT145 IN CCTC,Reach-1,2
Up Type=0
Dn Type=3
Dn Slope=0.005
Boundary for River Rch & Prof#=UNT145 IN CCTC,Reach-1,3
Up Type=0
Dn Type=3
Dn Slope=0.005
Boundary for River Rch & Prof#=UNT145 IN CCTC,Reach-1,4
Up Type=0
Dn Type=3
Dn Slope=0.005
Boundary for River Rch & Prof#=UNT145 IN CCTC,Reach-1,5
Up Type=0
Dn Type=3
Dn Slope=0.005
Boundary for River Rch & Prof#=UNT145 IN CCTC,Reach-1,6
Up Type=0
Dn Type=3
Dn Slope=0.005
Boundary for River Rch & Prof#=UNT145 IN CCTC,Reach-1,7
Up Type=0
Dn Type=3
Dn Slope=0.005

--- UNT145 IN CCTC.g01 (geometry) ---

Geom Title=Existing Conditions

River Reach=UNT145 IN CCTC,Reach-1
Reach XY= 30
      3563226.20     10617750.36      3563317.75     10617710.00
      3563362.00     10617564.00      3563660.50     10617365.00
      3563716.00     10617381.00      3563753.75     10617294.00
      3563834.25     10617366.00      3563950.75     10617306.00
      3563980.50     10617477.00      3564084.00     10617415.00
      3564096.75     10617690.00      3564291.75     10617765.00
      3564353.75     10617646.00      3564538.25     10617474.00
      3564278.00     10617077.00      3564475.50     10616925.00
      3564666.00     10616978.00      3564828.75     10617183.00
      3565055.50     10617228.00      3565237.00     10617455.00
      3565512.00     10617525.00      3565627.00     10617676.00
      3565749.00     10618205.00      3565769.75     10618430.00
      3565710.25     10618504.00      3565700.50     10618770.00
      3565843.25     10618976.00      3565768.00     10619086.00
      3565819.25     10619235.00      3565751.50     10619458.00

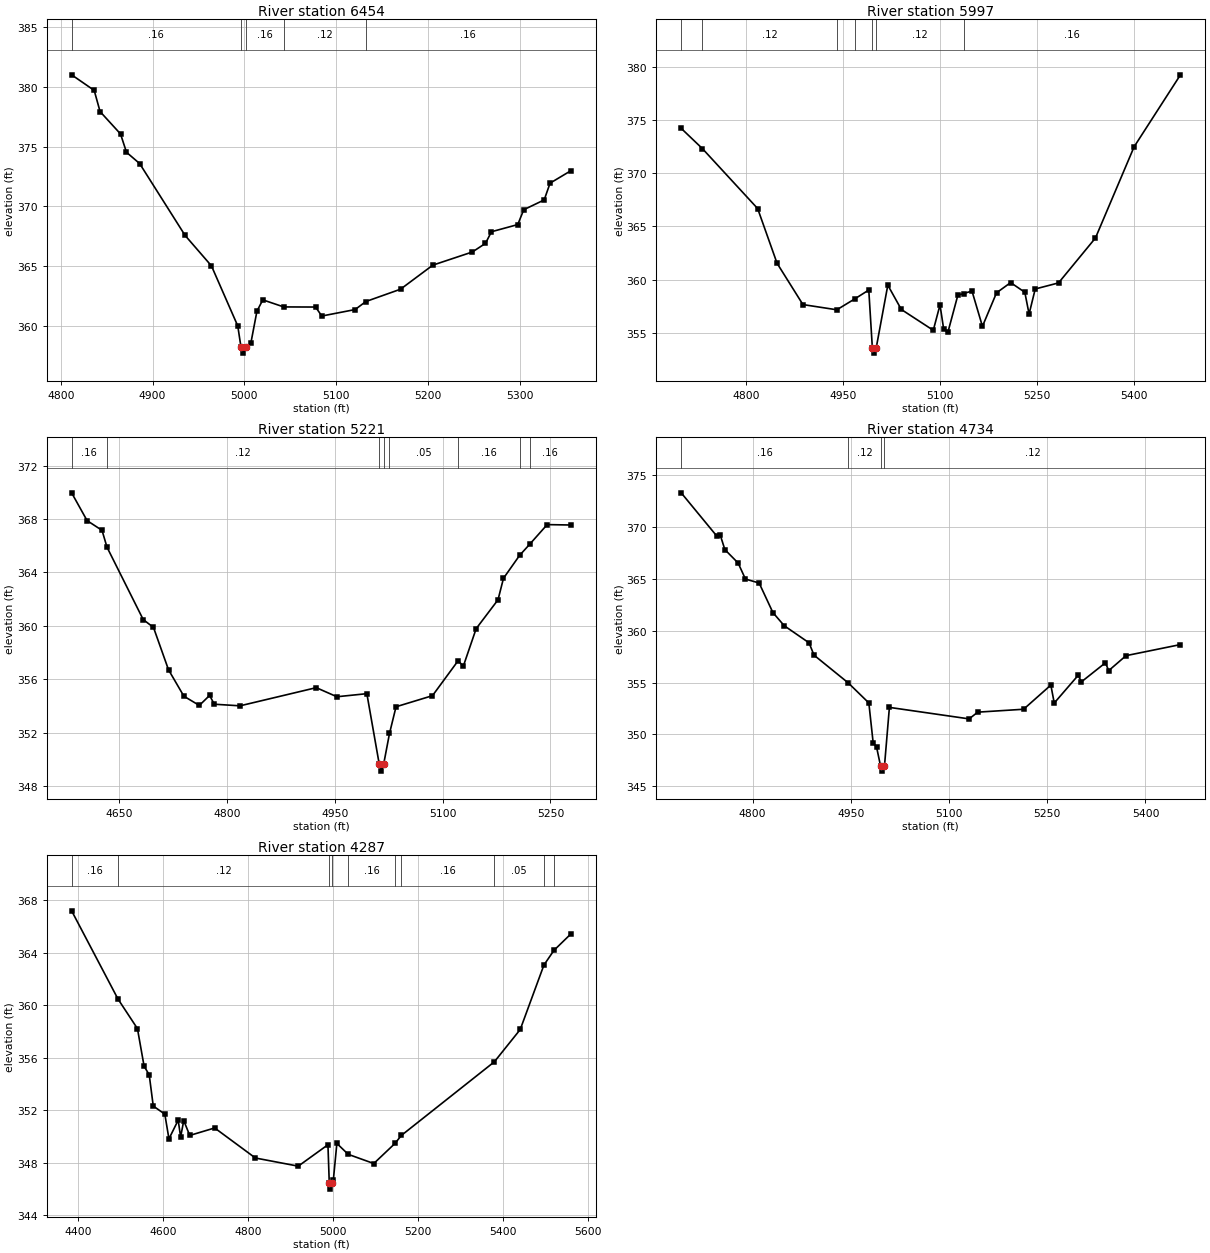
Type RM Length L Ch R = 1,6454,457,457,457
BEGIN DESCRIPTION:
UNT145 IN CCTC 4.0
END DESCRIPTION:
XS GIS Cut Line= 2
      3563422.28     10617871.63      3563078.52     10617449.75
#Sta/Elev= 30
  4811.8  380.99  4836.4  379.69  4842.8  377.92  4865.1  376.05  4871.6  374.52
  4885.9  373.58  4935.5  367.57  4964.2  365.03  4992.9  360.01  4996.4  358.24
  4999.1  357.74  5002.4  358.24  5007.1  358.55  5013.8  361.25  5020.2  362.19
  5043.0  361.60  5077.7  361.59  5084.5  360.84  5120.8  361.38  5132.5  362.05
  5170.3  363.08  5205.5  365.09  5248.6  366.19  5262.9  366.91  5269.4  367.88
  5298.1  368.48  5304.6  369.72  5326.9  370.54  5333.3  371.94  5356.0  372.98
#Mann=5,-1,0
  4811.8    0.16       0  4996.4    0.07       0  5002.4    0.16       0
  5043.0    0.12       0  5132.5    0.16       0
Bank Sta=4996.4,5002.4
Exp/Cntr=0.3,0.1

Type RM Length L Ch R = 1,5997,776,776,776
BEGIN DESCRIPTION:
UNT145 IN CCTC 3.0
END DESCRIPTION:
XS GIS Cut Line= 4
      3563635.83     10617728.41      3563633.23     10617491.44
      3563552.50     10617379.46      3563204.08     10617189.65
#Sta/Elev= 30
  4699.4  374.23  4732.1  372.33  4817.6  366.68  4847.6  361.53  4887.6  357.64
  4940.0  357.15  4968.1  358.19  4989.4  359.01  4994.9  353.57  4997.7  353.07
  5000.9  353.57  5018.8  359.47  5039.7  357.18  5089.1  355.22  5099.5  357.61
  5105.2  355.32  5111.9  355.08  5127.1  358.53  5136.3  358.68  5148.9  358.92
  5165.1  355.59  5186.9  358.75  5208.7  359.71  5230.6  358.80  5237.2  356.75
  5246.7  359.11  5282.7  359.68  5339.8  363.91  5399.6  372.50  5471.2  379.27
#Mann=7,-1,0
  4699.4    0.16       0  4732.1    0.12       0  4940.0    0.05       0
  4968.1    0.12       0  4994.9    0.07       0  5000.9    0.12       0
  5136.3    0.16       0
Bank Sta=4994.9,5000.9
Exp/Cntr=0.3,0.1

Type RM Length L Ch R = 1,5221,487,487,487
BEGIN DESCRIPTION:
UNT145 IN CCTC 2.0
END DESCRIPTION:
XS GIS Cut Line= 3
      3563799.59     10617760.21      3564049.61     10617460.19
      3563999.61     10617160.17
#Sta/Elev= 30
  4583.8  369.96  4605.3  367.88  4626.1  367.15  4633.0  365.89  4683.4  360.47
  4697.7  359.88  4718.6  356.71  4740.0  354.73  4761.5  354.04  4775.8  354.79
  4782.3  354.13  4818.1  354.01  4924.2  355.37  4952.9  354.69  4994.6  354.92
  5011.9  349.62  5014.6  349.12  5017.9  349.62  5026.1  351.94  5035.2  353.94
  5085.9  354.77  5121.5  357.38  5128.9  356.99  5146.7  359.79  5177.1  361.95
  5184.7  363.56  5207.2  365.28  5221.2  366.11  5245.5  367.58  5278.5  367.55
#Mann=8,-1,0
  4583.8    0.16       0  4633.0    0.12       0  5011.9    0.07       0
  5017.9    0.12       0  5026.1    0.05       0  5121.5    0.16       0
  5207.2    0.12       0  5221.2    0.16       0
Bank Sta=5011.9,5017.9
Exp/Cntr=0.3,0.1

Type RM Length L Ch R = 1,4734,447,447,447
BEGIN DESCRIPTION:
Mapping XS 8db1bcd3
END DESCRIPTION:
XS GIS Cut Line= 3
      3564117.62     10618053.90      3564229.58     10617691.96
      3564138.43     10617319.52
#Sta/Elev= 30
  4691.1  373.31  4745.3  369.15  4750.6  369.26  4757.8  367.83  4778.0  366.54
  4789.2  364.99  4810.1  364.61  4831.1  361.76  4848.4  360.49  4886.3  358.84
  4893.9  357.65  4946.2  354.97  4977.6  353.04  4984.2  349.20  4989.4  348.78
  4995.5  346.96  4998.3  346.46  5001.5  346.96  5009.0  352.61  5130.7  351.50
  5143.9  352.15  5213.9  352.43  5255.5  354.76  5260.7  353.03  5297.2  355.70
  5302.3  355.08  5338.8  356.91  5343.9  356.16  5370.3  357.60  5453.4  358.67
#Mann=4,-1,0
  4691.1    0.16       0  4946.2    0.12       0  4995.5    0.07       0
  5001.5    0.12       0
Bank Sta=4995.5,5001.5
Exp/Cntr=0.3,0.1

Type RM Length L Ch R = 1,4287,0,0,0
BEGIN DESCRIPTION:
UNT145 IN CCTC 1.0
END DESCRIPTION:
XS GIS Cut Line= 4
      3564315.54     10618017.44      3564586.35     10617556.54
      3564448.33     10617462.79      3564057.71     10617197.17
#Sta/Elev= 30
  4385.3  367.20  4494.3  360.48  4540.0  358.23  4555.7  355.36  4567.7  354.71
  4577.2  352.33  4604.4  351.71  4614.1  349.83  4635.8  351.25  4641.6  349.98
  4648.9  351.22  4663.0  350.09  4721.6  350.66  4817.4  348.37  4918.1  347.75
  4987.9  349.38  4991.0  346.50  4993.7  346.00  4997.0  346.50  5000.6  346.69
  5008.9  349.48  5035.6  348.65  5095.7  347.95  5145.5  349.48  5160.5  350.09
  5379.2  355.70  5440.0  358.16  5495.7  363.07  5519.3  364.19  5559.1  365.44
#Mann=10,-1,0
  4385.3    0.16       0  4494.3    0.12       0  4991.0    0.07       0
  4997.0    0.12       0  5035.6    0.16       0  5145.5    0.12       0
  5160.5    0.16       0  5379.2    0.05       0  5495.7    0.16       0
  5519.3    0.05       0
Bank Sta=4991,4997
Exp/Cntr=0.3,0.1

Chan Stop Cuts=-1