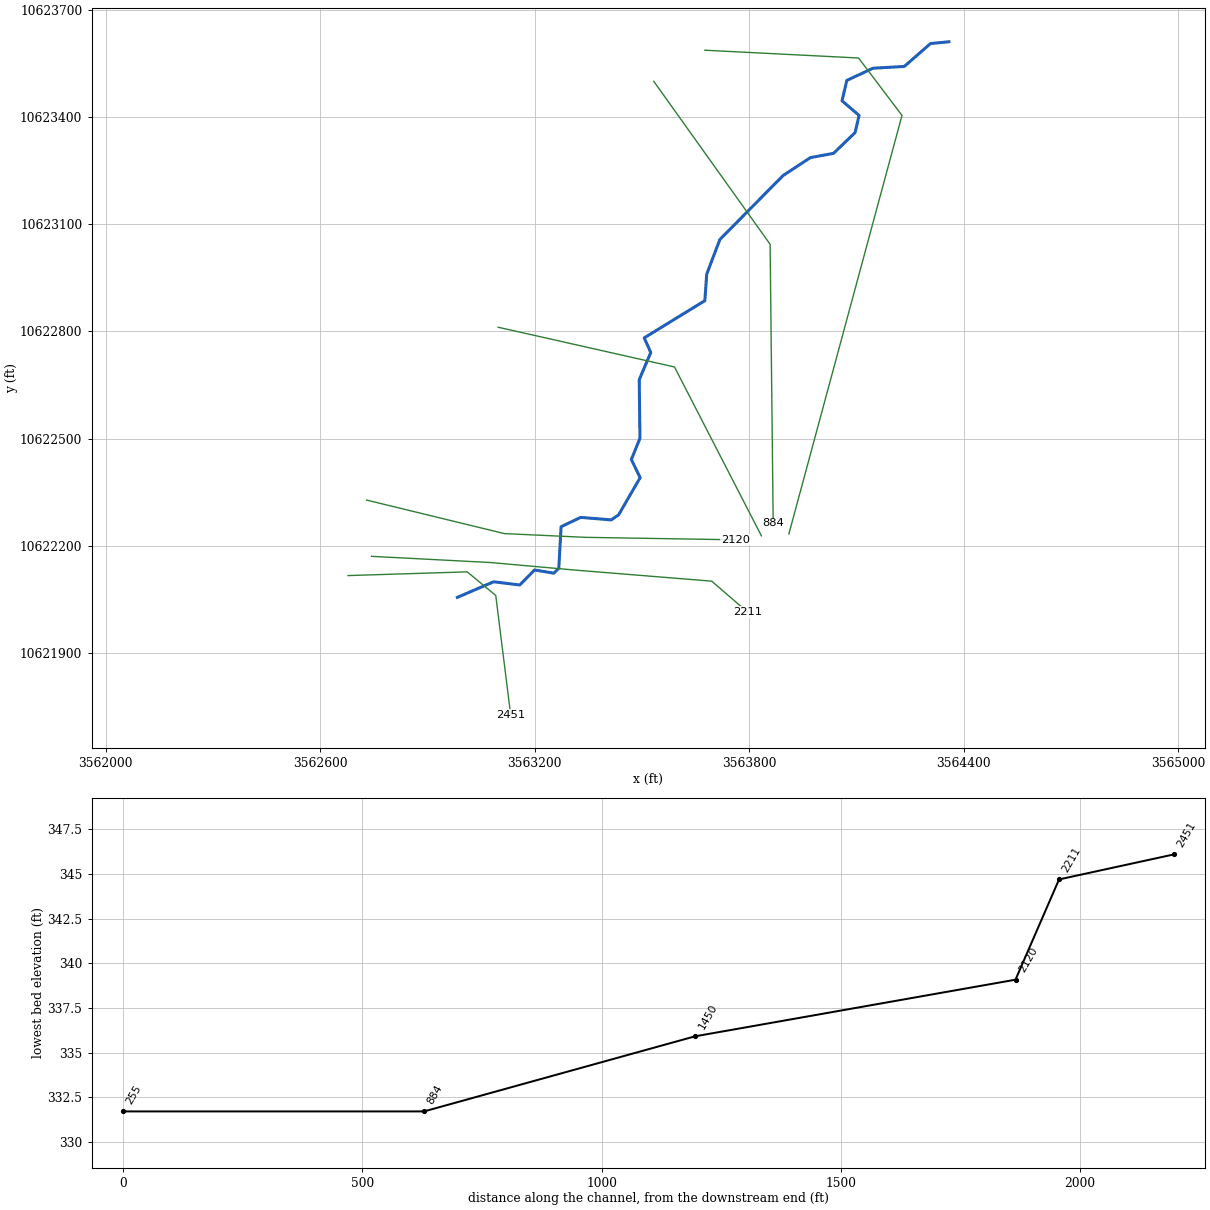
--- UNT146 IN CCTC.prj (project) ---

Proj Title=UNT146 IN CCTC Base Level Engineering
Current Plan=p01
Default Exp/Contr=0.3,0.1
English Units
Geom File=g01
Flow File=f01
Plan File=p01
Y Axis Title=Elevation
X Axis Title(PF)=Main Channel Distance
X Axis Title(XS)=Station
BEGIN DESCRIPTION:
UNT146 IN CCTC
END DESCRIPTION:
DSS Export Rating Curves= 0
DSS Export Rating Curve Sorted= 0
DSS Export Volume Flow Curves= 0
DXF OffsetX= 0
DXF OffsetY= 0
DXF ScaleX= 1
DXF ScaleY= 10

--- UNT146 IN CCTC.p01 (plan) ---

Plan Title=Multiple Run
Short Identifier=Multiple
Geom File=g01
Flow File=f01
Subcritical Flow
K Sum by GR= 0
Std Step Tol= 0.01
Critical Tol= 0.01
Num of Std Step Trials= 20
Max Error Tol= 0.3
Flow Tol Ratio= 0.001
Split Flow NTrial= 30
Split Flow Tol= 0.02
Split Flow Ratio= 0.02
Log Output Level= 0
Friction Slope Method= 1
Unsteady Friction Slope Method= 2
Unsteady Bridges Friction Slope Method= 1
Parabolic Critical Depth
Global Vel Dist=  1 , 1 , 1
Global Log Level= 0
CheckData=True
Encroach Param= -1, 0, 0, 0
BEGIN DESCRIPTION:
Multiple Run
END DESCRIPTION:

--- UNT146 IN CCTC.f01 (steady flow) ---

Flow Title=Multiple
Number of Profiles=7
Profile Names=10-year,25-year,50-year,1pct_min,100-year,1pct_plu,500-year
River Rch & RM= UNT146 IN CCTC,Reach-1,2451
    1009    1374    1674    1493    2019    2730    2921
Boundary for River Rch & Prof#=UNT146 IN CCTC,Reach-1,1
Up Type=0
Dn Type=3
Dn Slope=0.005
Boundary for River Rch & Prof#=UNT146 IN CCTC,Reach-1,2
Up Type=0
Dn Type=3
Dn Slope=0.005
Boundary for River Rch & Prof#=UNT146 IN CCTC,Reach-1,3
Up Type=0
Dn Type=3
Dn Slope=0.005
Boundary for River Rch & Prof#=UNT146 IN CCTC,Reach-1,4
Up Type=0
Dn Type=3
Dn Slope=0.005
Boundary for River Rch & Prof#=UNT146 IN CCTC,Reach-1,5
Up Type=0
Dn Type=3
Dn Slope=0.005
Boundary for River Rch & Prof#=UNT146 IN CCTC,Reach-1,6
Up Type=0
Dn Type=3
Dn Slope=0.005
Boundary for River Rch & Prof#=UNT146 IN CCTC,Reach-1,7
Up Type=0
Dn Type=3
Dn Slope=0.005

--- UNT146 IN CCTC.g01 (geometry) ---

Geom Title=Existing Conditions

River Reach=UNT146 IN CCTC,Reach-1
Reach XY= 30
      3562983.88     10622056.42      3563085.25     10622100.00
      3563158.25     10622091.00      3563199.75     10622133.00
      3563253.75     10622124.00      3563267.50     10622138.00
      3563274.00     10622254.00      3563328.75     10622280.00
      3563414.25     10622273.00      3563434.75     10622287.00
      3563495.00     10622391.00      3563470.50     10622442.00
      3563494.50     10622501.00      3563492.50     10622665.00
      3563524.75     10622741.00      3563506.50     10622782.00
      3563676.00     10622886.00      3563681.25     10622960.00
      3563718.00     10623057.00      3563895.00     10623236.00
      3563971.25     10623286.00      3564036.00     10623298.00
      3564096.25     10623356.00      3564107.50     10623404.00
      3564059.75     10623445.00      3564073.25     10623502.00
      3564146.50     10623536.00      3564234.00     10623541.00
      3564307.25     10623605.00      3564358.75     10623610.00

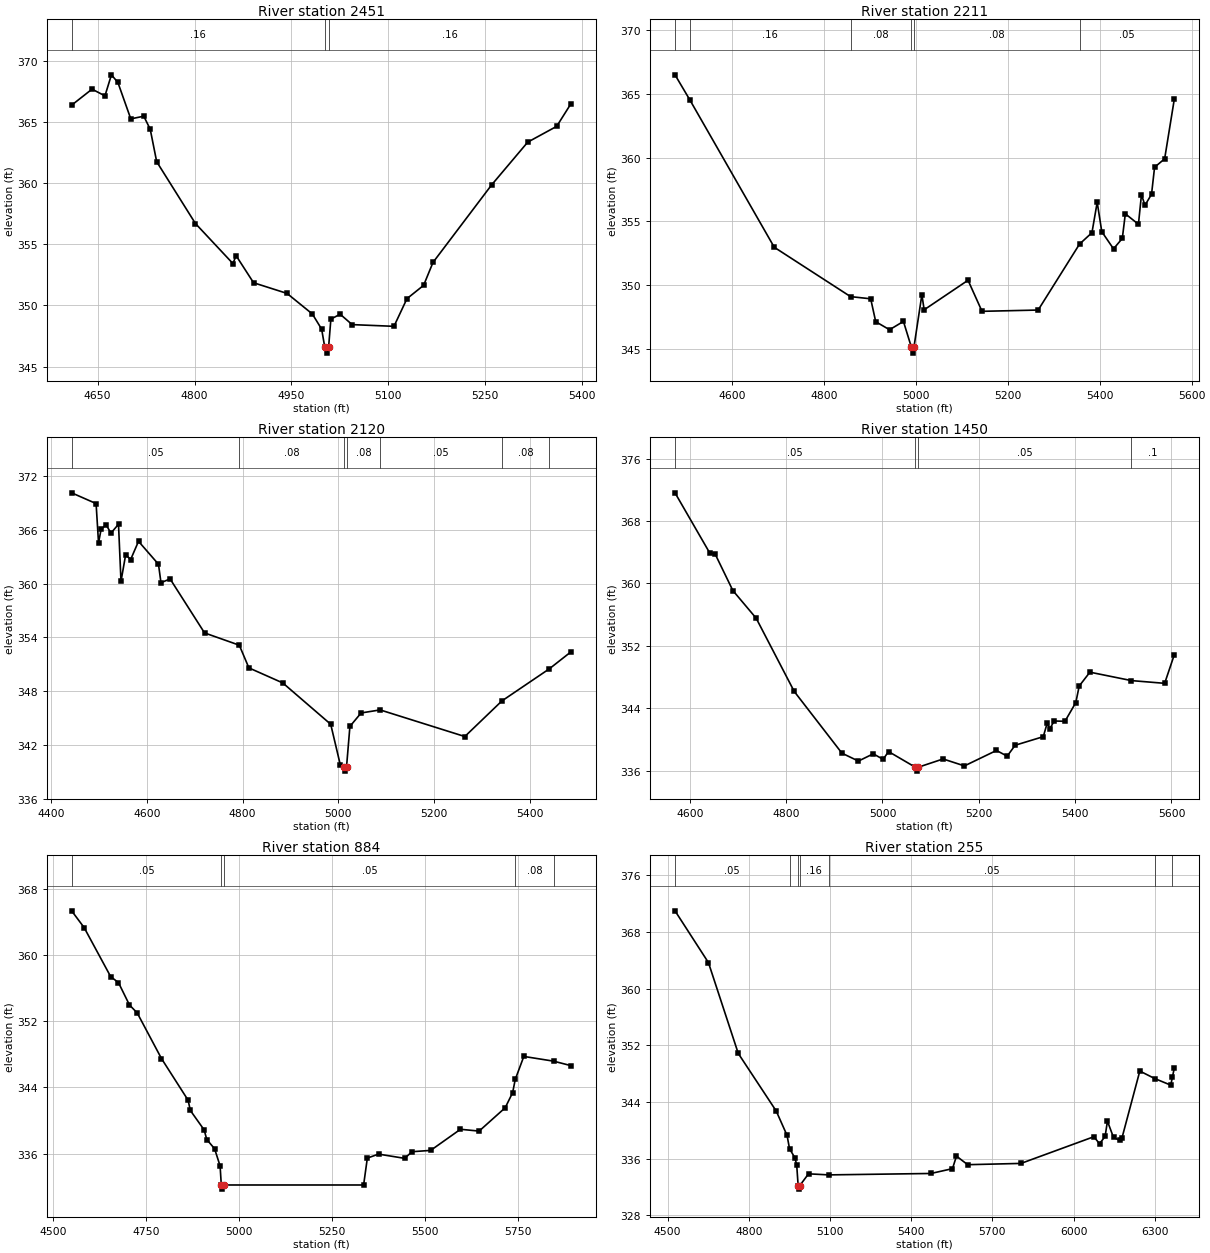
Type RM Length L Ch R = 1,2451,240,240,240
BEGIN DESCRIPTION:
UNT146 IN CCTC 4.0
END DESCRIPTION:
XS GIS Cut Line= 4
      3562678.01     10622117.30      3563011.30     10622127.71
      3563091.16     10622061.74      3563132.83     10621728.38
#Sta/Elev= 30
  4609.7  366.36  4641.3  367.67  4661.3  367.12  4671.3  368.84  4681.3  368.22
  4701.3  365.24  4721.4  365.46  4731.4  364.39  4741.4  361.74  4801.4  356.69
  4859.4  353.42  4864.4  354.06  4891.4  351.85  4943.2  350.98  4982.4  349.30
  4996.8  348.06  5001.6  346.60  5004.4  346.10  5007.6  346.60  5011.1  348.88
  5025.5  349.28  5044.0  348.43  5108.8  348.29  5128.9  350.55  5154.7  351.64
  5169.2  353.51  5259.9  359.84  5315.9  363.34  5360.7  364.63  5382.7  366.47
#Mann=3,-1,0
  4609.7    0.16       0  5001.6    0.07       0  5007.6    0.16       0
Bank Sta=5001.6,5007.6
Exp/Cntr=0.3,0.1

Type RM Length L Ch R = 1,2211,91,91,91
BEGIN DESCRIPTION:
Mapping XS 745536f2
END DESCRIPTION:
XS GIS Cut Line= 5
      3562743.95     10622171.11      3563077.27     10622153.75
      3563309.91     10622132.92      3563695.32     10622101.67
      3563795.14     10622015.63
#Sta/Elev= 30
  4476.4  366.47  4509.3  364.47  4692.3  352.98  4858.2  349.12  4902.0  348.95
  4912.9  347.16  4943.0  346.53  4973.2  347.18  4990.2  345.20  4993.0  344.70
  4996.2  345.20  5013.3  349.27  5018.3  348.09  5113.7  350.40  5144.1  347.97
  5266.2  348.07  5356.2  353.23  5383.2  354.12  5394.6  356.50  5404.6  354.20
  5430.1  352.86  5449.2  353.67  5455.8  355.60  5484.3  354.78  5490.9  357.10
  5498.5  356.26  5512.8  357.13  5519.4  359.24  5541.3  359.90  5562.2  364.54
#Mann=6,-1,0
  4476.4    0.08       0  4509.3    0.16       0  4858.2    0.08       0
  4990.2    0.07       0  4996.2    0.08       0  5356.2    0.05       0
Bank Sta=4990.2,4996.2
Exp/Cntr=0.3,0.1

Type RM Length L Ch R = 1,2120,670,670,670
BEGIN DESCRIPTION:
UNT146 IN CCTC 3.0
END DESCRIPTION:
XS GIS Cut Line= 4
      3562729.88     10622328.44      3563115.25     10622234.70
      3563340.94     10622224.28      3563761.04     10622217.34
#Sta/Elev= 30
  4442.8  370.14  4493.9  368.94  4499.0  364.55  4504.3  366.05  4514.6  366.59
  4524.9  365.65  4540.7  366.63  4545.9  360.26  4555.7  363.25  4566.0  362.69
  4582.5  364.73  4624.2  362.17  4629.4  360.11  4648.4  360.54  4720.4  354.51
  4793.0  353.14  4813.0  350.61  4883.8  348.93  4983.9  344.32  5003.9  339.80
  5011.0  339.59  5013.7  339.09  5017.0  339.59  5024.0  344.08  5047.4  345.58
  5087.1  345.92  5264.0  342.95  5341.4  346.92  5440.4  350.50  5485.5  352.39
#Mann=7,-1,0
  4442.8    0.05       0  4793.0    0.08       0  5011.0    0.07       0
  5017.0    0.08       0  5087.1    0.05       0  5341.4    0.08       0
  5440.4     0.1       0
Bank Sta=5011,5017
Exp/Cntr=0.3,0.1

Type RM Length L Ch R = 1,1450,566,566,566
BEGIN DESCRIPTION:
UNT146 IN CCTC 2.0
END DESCRIPTION:
XS GIS Cut Line= 3
      3563098.12     10622811.74      3563591.16     10622700.63
      3563834.21     10622228.41
#Sta/Elev= 30
  4569.3  371.61  4641.0  363.94  4652.8  363.74  4689.4  359.08  4737.8  355.53
  4816.8  346.14  4915.9  338.22  4950.1  337.21  4980.9  338.14  5001.4  337.43
  5012.6  338.43  5068.3  336.42  5071.1  335.92  5074.3  336.42  5125.9  337.48
  5170.2  336.59  5236.7  338.57  5258.9  337.84  5275.5  339.24  5333.9  340.34
  5342.0  342.07  5347.6  341.35  5356.4  342.35  5378.9  342.31  5401.4  344.71
  5408.5  346.84  5430.7  348.61  5516.9  347.53  5585.9  347.18  5605.8  350.83
#Mann=4,-1,0
  4569.3    0.05       0  5068.3    0.03       0  5074.3    0.05       0
  5516.9     0.1       0
Bank Sta=5068.3,5074.3
Exp/Cntr=0.3,0.1

Type RM Length L Ch R = 1,884,629,629,629
BEGIN DESCRIPTION:
Mapping XS 57bc9603
END DESCRIPTION:
XS GIS Cut Line= 3
      3563533.05     10623499.53      3563858.58     10623043.80
      3563867.24     10622263.90
#Sta/Elev= 30
  4550.8  365.34  4584.3  363.32  4655.6  357.39  4676.5  356.67  4706.0  353.97
  4726.9  353.00  4792.0  347.49  4863.3  342.47  4869.5  341.22  4906.4  338.88
  4913.6  337.71  4934.5  336.60  4949.3  334.52  4952.5  332.22  4955.3  331.72
  4958.5  332.22  5334.5  332.22  5344.5  335.47  5374.5  335.95  5444.5  335.44
  5464.5  336.24  5514.5  336.40  5594.5  338.95  5644.5  338.73  5714.5  341.55
  5734.5  343.38  5741.5  344.97  5764.5  347.75  5844.3  347.18  5890.8  346.64
#Mann=5,-1,0
  4550.8    0.05       0  4952.5    0.03       0  4958.5    0.05       0
  5741.5    0.08       0  5844.3     0.1       0
Bank Sta=4952.5,4958.5
Exp/Cntr=0.3,0.1

Type RM Length L Ch R = 1,255,0,0,0
BEGIN DESCRIPTION:
UNT146 IN CCTC 1.0
END DESCRIPTION:
XS GIS Cut Line= 4
      3563676.31     10623586.33      3564105.97     10623564.63
      3564227.50     10623404.04      3563911.07     10622233.67
#Sta/Elev= 30
  4527.7  371.01  4651.2  363.70  4761.3  350.88  4901.5  342.75  4941.5  339.31
  4950.8  337.41  4971.0  336.12  4977.3  335.07  4982.5  332.22  4985.3  331.72
  4988.5  332.22  5020.9  333.88  5095.5  333.73  5472.9  333.93  5552.6  334.61
  5567.3  336.38  5608.7  335.17  5805.6  335.35  6074.9  339.12  6095.6  338.13
  6116.3  339.15  6124.9  341.32  6147.4  339.01  6169.9  338.62  6178.5  338.93
  6244.5  348.39  6299.6  347.33  6358.9  346.40  6364.7  347.52  6371.7  348.76
#Mann=7,-1,0
  4527.7    0.05       0  4950.8    0.16       0  4982.5    0.07       0
  4988.5    0.16       0  5095.5    0.05       0  6299.6    0.08       0
  6364.7     0.1       0
Bank Sta=4982.5,4988.5
Exp/Cntr=0.3,0.1

Chan Stop Cuts=-1