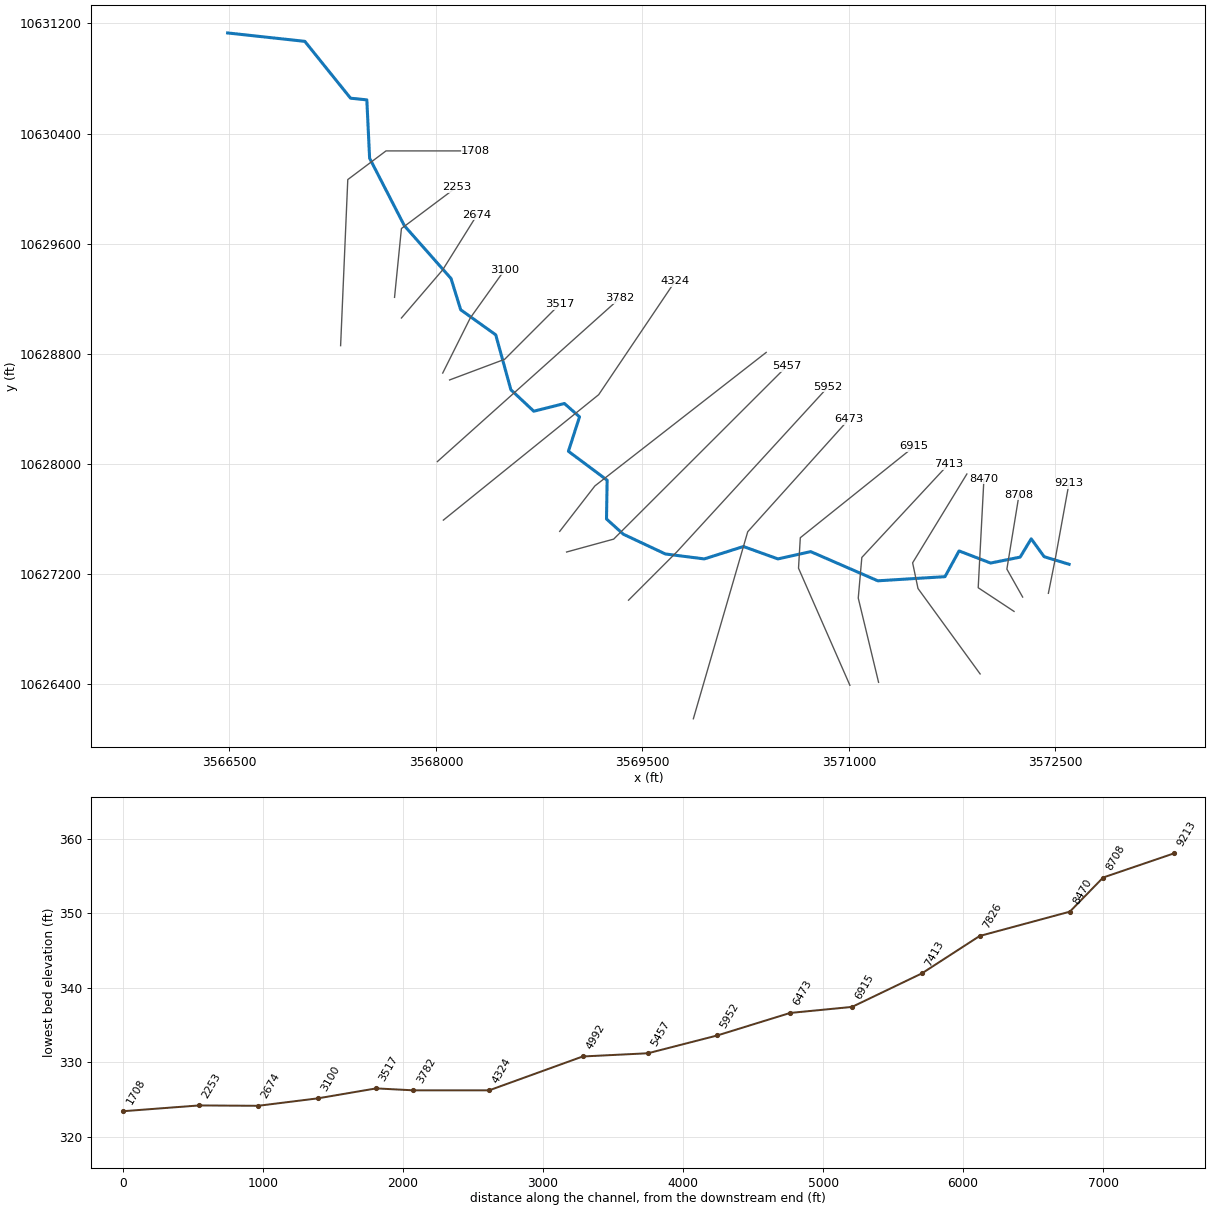
--- UNT149 IN CCTC.prj (project) ---

Proj Title=UNT149 IN CCTC Base Level Engineering
Current Plan=p01
Default Exp/Contr=0.3,0.1
English Units
Geom File=g01
Flow File=f01
Plan File=p01
BEGIN DESCRIPTION:
UNT149 IN CCTC
END DESCRIPTION:

--- UNT149 IN CCTC.p01 (plan) ---

Plan Title=Multiple Run
Short Identifier=Multiple
Geom File=g01
Flow File=f01
Subcritical Flow
K Sum by GR= 0
Std Step Tol= 0.01
Critical Tol= 0.01
Num of Std Step Trials= 20
Max Error Tol= 0.3
Flow Tol Ratio= 0.001
Split Flow NTrial= 30
Split Flow Tol= 0.02
Split Flow Ratio= 0.02
Log Output Level= 0
Friction Slope Method= 1
Unsteady Friction Slope Method= 2
Unsteady Bridges Friction Slope Method= 1
Parabolic Critical Depth
Global Vel Dist=  1 , 1 , 1
Global Log Level= 0
CheckData=True
Encroach Param= -1, 0, 0, 0
BEGIN DESCRIPTION:
Multiple Run
END DESCRIPTION:

--- UNT149 IN CCTC.f01 (steady flow) ---

Flow Title=Multiple
Number of Profiles=7
Profile Names=10-year,25-year,50-year,1pct_min,100-year,1pct_plu,500-year
River Rch & RM= UNT149 IN CCTC,Reach-1,9213
    1379    1889    2310    2063    2790    3773    4052
River Rch & RM= UNT149 IN CCTC,Reach-1,8470
    2304    3232    4014    3631    4910    6640    7324
Boundary for River Rch & Prof#=UNT149 IN CCTC,Reach-1,1
Up Type=0
Dn Type=3
Dn Slope=0.005
Boundary for River Rch & Prof#=UNT149 IN CCTC,Reach-1,2
Up Type=0
Dn Type=3
Dn Slope=0.005
Boundary for River Rch & Prof#=UNT149 IN CCTC,Reach-1,3
Up Type=0
Dn Type=3
Dn Slope=0.005
Boundary for River Rch & Prof#=UNT149 IN CCTC,Reach-1,4
Up Type=0
Dn Type=3
Dn Slope=0.005
Boundary for River Rch & Prof#=UNT149 IN CCTC,Reach-1,5
Up Type=0
Dn Type=3
Dn Slope=0.005
Boundary for River Rch & Prof#=UNT149 IN CCTC,Reach-1,6
Up Type=0
Dn Type=3
Dn Slope=0.005
Boundary for River Rch & Prof#=UNT149 IN CCTC,Reach-1,7
Up Type=0
Dn Type=3
Dn Slope=0.005

--- UNT149 IN CCTC.g01 (geometry) ---

Geom Title=Existing Conditions

River Reach=UNT149 IN CCTC,Reach-1
Reach XY= 30
      3572600.25     10627271.00      3572419.00     10627326.00
      3572324.75     10627456.00      3572244.50     10627323.00
      3572029.75     10627280.00      3571800.75     10627368.00
      3571698.50     10627181.00      3571210.25     10627151.00
      3570722.75     10627363.00      3570485.00     10627310.00
      3570234.25     10627400.00      3569949.75     10627310.00
      3569667.00     10627346.00      3569362.50     10627489.00
      3569239.50     10627600.00      3569244.00     10627882.00
      3568962.75     10628092.00      3569043.50     10628342.00
      3568933.75     10628439.00      3568711.25     10628383.00
      3568544.75     10628539.00      3568434.75     10628938.00
      3568180.25     10629120.00      3568110.00     10629347.00
      3567771.50     10629730.00      3567518.50     10630221.00
      3567498.25     10630645.00      3567380.00     10630657.00
      3567047.75     10631070.00      3566486.75     10631131.00

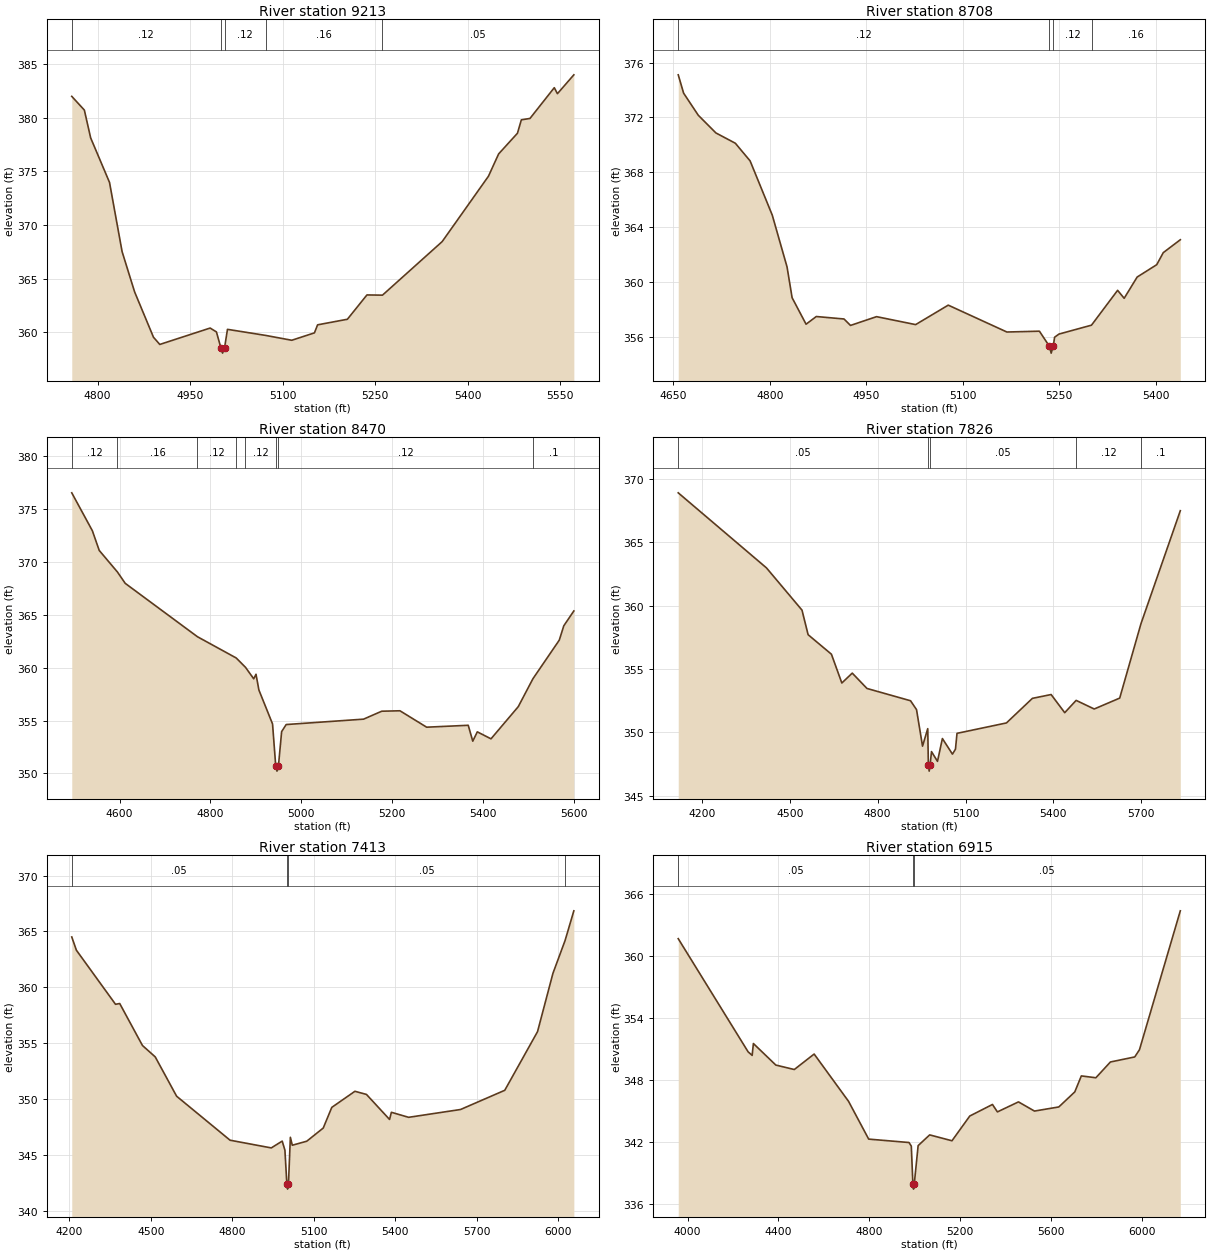
Type RM Length L Ch R = 1,9213,505,505,505
BEGIN DESCRIPTION:
UNT149 IN CCTC 17.0
END DESCRIPTION:
XS GIS Cut Line= 3
      3572449.62     10627060.22      3572499.61     10627310.19
      3572599.60     10627860.15
#Sta/Elev= 30
  4758.2  382.01  4778.6  380.73  4788.8  378.14  4819.4  373.98  4839.8  367.52
  4860.1  363.76  4890.7  359.53  4900.9  358.86  4982.5  360.39  4992.7  360.03
  4999.9  358.55  5002.7  358.05  5005.9  358.55  5010.6  360.27  5072.8  359.70
  5114.8  359.25  5151.6  359.94  5156.7  360.69  5205.0  361.21  5236.7  363.48
  5261.9  363.46  5358.7  368.46  5433.7  374.56  5450.2  376.64  5480.7  378.57
  5487.0  379.82  5501.0  379.95  5540.4  382.82  5545.5  382.26  5572.1  384.02
#Mann=5,-1,0
  4758.2    0.12       0  4999.9    0.07       0  5005.9    0.12       0
  5072.8    0.16       0  5261.9    0.05       0
Bank Sta=4999.9,5005.9
Exp/Cntr=0.3,0.1

Type RM Length L Ch R = 1,8708,238,238,238
BEGIN DESCRIPTION:
UNT149 IN CCTC 16.0
END DESCRIPTION:
XS GIS Cut Line= 3
      3572262.70     10627032.85      3572148.10     10627235.99
      3572236.44     10627776.38
#Sta/Elev= 30
  4657.5  375.11  4665.9  373.77  4688.7  372.16  4716.1  370.87  4746.3  370.12
  4769.3  368.83  4803.7  364.88  4826.7  361.10  4834.6  358.85  4856.3  356.92
  4872.2  357.48  4915.3  357.30  4925.4  356.83  4965.9  357.47  5026.7  356.89
  5077.4  358.31  5168.6  356.35  5219.2  356.41  5234.7  355.31  5237.5  354.81
  5240.7  355.31  5242.8  355.97  5249.6  356.20  5300.2  356.85  5340.8  359.39
  5351.0  358.81  5371.2  360.36  5401.6  361.26  5411.8  362.14  5438.3  363.08
#Mann=4,-1,0
  4657.5    0.12       0  5234.7    0.07       0  5240.7    0.12       0
  5300.2    0.16       0
Bank Sta=5234.7,5240.7
Exp/Cntr=0.3,0.1

Type RM Length L Ch R = 1,8470,644,644,644
BEGIN DESCRIPTION:
UNT149 IN CCTC 15.0
END DESCRIPTION:
XS GIS Cut Line= 3
      3572200.16     10626928.71      3571939.77     10627100.57
      3571981.44     10627892.28
#Sta/Elev= 30
  4494.8  376.51  4540.1  372.93  4555.2  371.07  4595.3  369.03  4612.4  367.96
  4771.2  362.92  4856.6  360.91  4877.0  360.03  4895.2  358.94  4900.2  359.37
  4906.6  357.88  4936.6  354.68  4943.6  350.72  4946.4  350.22  4949.6  350.72
  4956.6  353.95  4966.6  354.62  5136.9  355.13  5176.9  355.88  5217.0  355.92
  5275.7  354.37  5367.2  354.55  5377.2  353.05  5387.2  353.93  5417.3  353.27
  5477.3  356.31  5509.6  358.95  5567.5  362.59  5577.5  363.95  5599.6  365.35
#Mann=8,-1,0
  4494.8    0.12       0  4595.3    0.16       0  4771.2    0.12       0
  4856.6    0.16       0  4877.0    0.12       0  4943.6    0.07       0
  4949.6    0.12       0  5509.6     0.1       0
Bank Sta=4943.6,4949.6
Exp/Cntr=0.3,0.1

Type RM Length L Ch R = 1,7826,413,413,413
BEGIN DESCRIPTION:
UNT149 IN CCTC 14.0
END DESCRIPTION:
XS GIS Cut Line= 4
      3571953.78     10626474.40      3571502.42     10627095.03
      3571463.36     10627281.66      3571857.36     10627926.78
#Sta/Elev= 30
  4119.3  368.90  4420.5  362.98  4541.8  359.65  4562.7  357.71  4642.3  356.17
  4677.8  353.90  4713.4  354.68  4763.6  353.47  4912.4  352.50  4932.8  351.80
  4953.3  348.92  4971.1  350.30  4973.2  347.45  4976.0  346.95  4979.2  347.45
  4983.9  348.49  5004.4  347.72  5021.1  349.52  5055.4  348.29  5065.7  348.68
  5071.0  349.93  5239.7  350.75  5328.4  352.69  5392.3  352.99  5438.7  351.56
  5477.7  352.53  5539.4  351.85  5626.4  352.71  5698.9  358.57  5833.3  367.49
#Mann=5,-1,0
  4119.3    0.05       0  4973.2    0.03       0  4979.2    0.05       0
  5477.7    0.12       0  5698.9     0.1       0
Bank Sta=4973.2,4979.2
Exp/Cntr=0.3,0.1

Type RM Length L Ch R = 1,7413,498,498,498
BEGIN DESCRIPTION:
UNT149 IN CCTC 13.0
END DESCRIPTION:
XS GIS Cut Line= 4
      3571215.97     10626413.59      3571068.39     10627025.58
      3571094.44     10627320.72      3571722.54     10627996.47
#Sta/Elev= 30
  4208.7  364.50  4225.8  363.31  4369.8  358.47  4385.2  358.54  4469.0  354.78
  4516.0  353.76  4594.7  350.24  4791.5  346.30  4943.2  345.61  4983.4  346.22
  4993.4  345.41  5000.5  342.42  5003.2  341.92  5006.5  342.42  5013.5  346.56
  5020.6  345.85  5073.8  346.21  5134.5  347.39  5166.0  349.24  5251.1  350.68
  5293.6  350.40  5378.6  348.16  5385.4  348.80  5448.9  348.35  5640.0  349.05
  5802.8  350.77  5923.4  356.02  5980.1  361.24  6024.8  364.18  6057.1  366.84
#Mann=4,-1,0
  4208.7    0.05       0  5000.5    0.03       0  5006.5    0.05       0
  6024.8     0.1       0
Bank Sta=5000.5,5006.5
Exp/Cntr=0.3,0.1

Type RM Length L Ch R = 1,6915,442,442,442
BEGIN DESCRIPTION:
UNT149 IN CCTC 12.0
END DESCRIPTION:
XS GIS Cut Line= 4
      3571007.62     10626391.93      3570634.37     10627242.60
      3570647.39     10627463.95      3571475.48     10628127.29
#Sta/Elev= 30
  3958.9  361.71  4266.6  350.74  4284.5  350.39  4290.0  351.54  4388.9  349.45
  4470.2  349.02  4557.6  350.52  4709.0  345.94  4797.9  342.27  4975.6  341.94
  4985.6  341.59  4992.6  337.92  4995.4  337.42  4998.6  337.92  5015.7  341.64
  5066.5  342.68  5164.8  342.11  5243.2  344.51  5343.1  345.63  5364.9  344.91
  5457.7  345.88  5528.1  344.99  5635.4  345.39  5705.8  346.85  5734.6  348.40
  5798.6  348.22  5862.7  349.75  5969.9  350.24  5990.7  350.94  6170.6  364.41
#Mann=3,-1,0
  3958.9    0.05       0  4992.6    0.03       0  4998.6    0.05       0
Bank Sta=4992.6,4998.6
Exp/Cntr=0.3,0.1

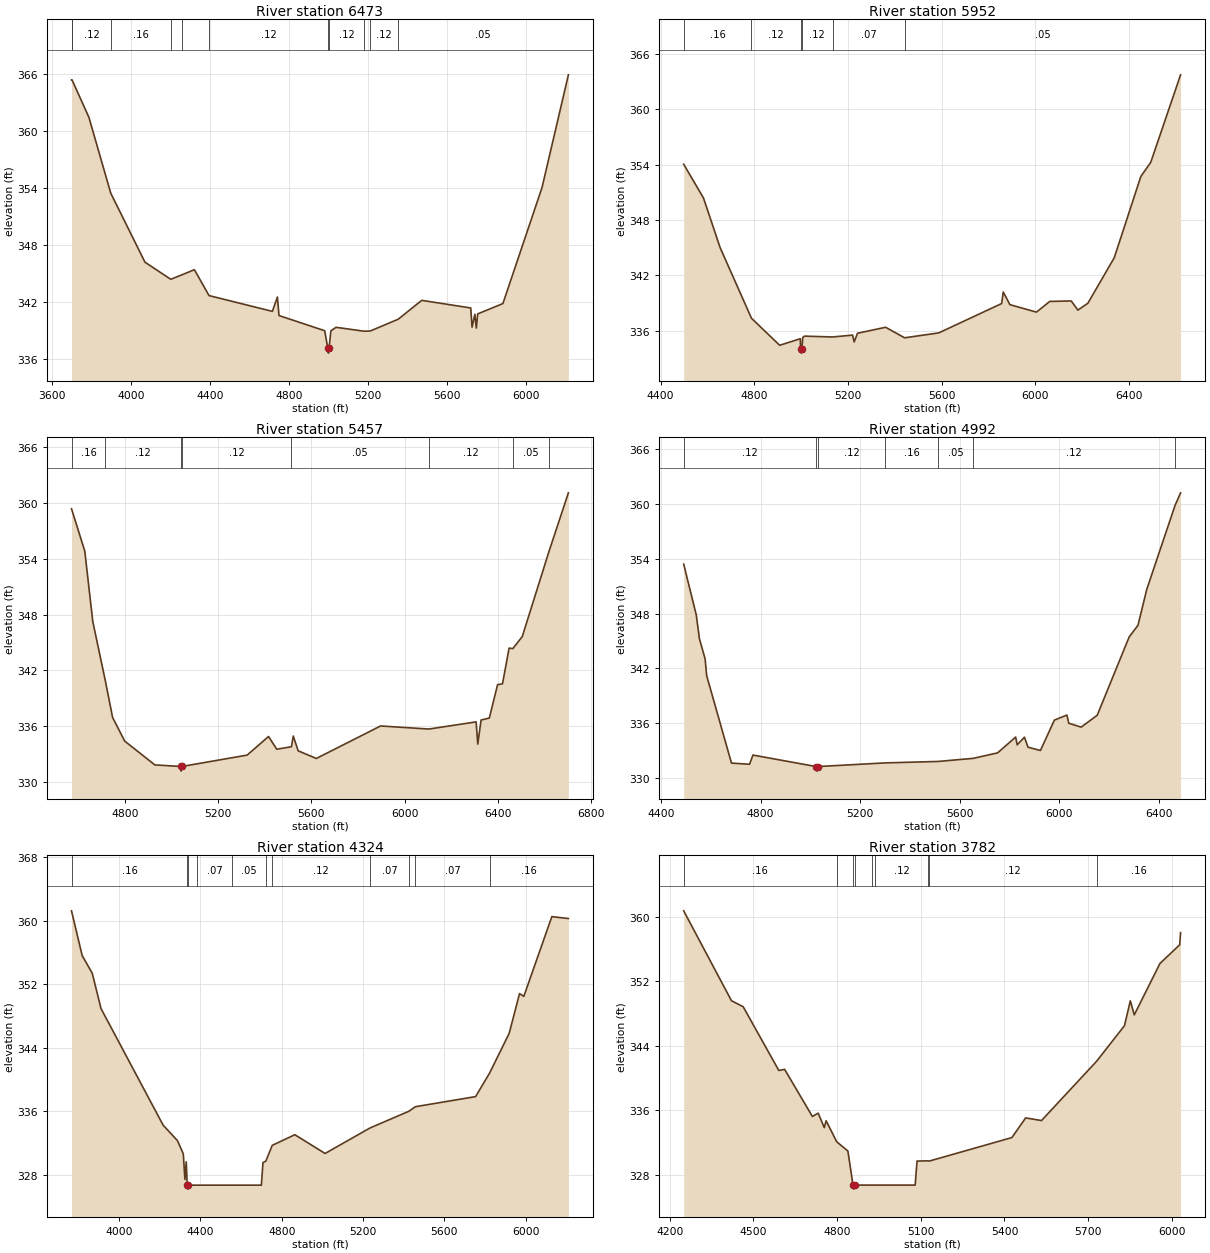
Type RM Length L Ch R = 1,6473,521,521,521
BEGIN DESCRIPTION:
UNT149 IN CCTC 11.0
END DESCRIPTION:
XS GIS Cut Line= 3
      3569870.47     10626148.80      3570265.44     10627507.35
      3571002.20     10628326.45
#Sta/Elev= 30
  3697.0  365.40  3699.6  365.40  3785.2  361.45  3895.8  353.46  4069.1  346.19
  4199.6  344.39  4256.2  344.86  4319.4  345.40  4393.6  342.67  4714.3  341.01
  4739.8  342.52  4747.8  340.57  4979.4  338.97  4995.2  337.11  4997.9  336.61
  5001.2  337.11  5010.6  338.96  5036.9  339.33  5178.4  338.92  5209.8  338.94
  5351.5  340.18  5470.7  342.17  5718.9  341.37  5725.6  339.35  5739.8  340.70
  5747.3  339.25  5754.0  340.74  5881.8  341.83  6079.9  354.05  6213.5  365.93
#Mann=11,-1,0
  3697.0    0.16       0  3699.6    0.12       0  3895.8    0.16       0
  4199.6    0.12       0  4256.2    0.16       0  4393.6    0.12       0
  4995.2    0.07       0  5001.2    0.12       0  5178.4    0.07       0
  5209.8    0.12       0  5351.5    0.05       0
Bank Sta=4995.2,5001.2
Exp/Cntr=0.3,0.1

Type RM Length L Ch R = 1,5952,495,495,495
BEGIN DESCRIPTION:
UNT149 IN CCTC 10.0
END DESCRIPTION:
XS GIS Cut Line= 3
      3569399.62     10627010.20      3569749.61     10627360.19
      3570849.58     10628560.16
#Sta/Elev= 30
  4498.3  354.04  4583.1  350.37  4653.8  345.02  4787.8  337.36  4908.4  334.43
  4996.7  335.14  4997.4  334.08  5000.1  333.58  5003.4  334.08  5007.1  335.28
  5014.5  335.42  5134.3  335.33  5219.9  335.53  5226.7  334.79  5240.8  335.73
  5361.1  336.38  5442.2  335.24  5588.0  335.77  5856.8  338.95  5863.6  340.20
  5892.0  338.83  6005.4  338.02  6062.2  339.18  6154.1  339.23  6182.4  338.24
  6225.0  338.98  6337.8  343.91  6451.3  352.71  6493.8  354.25  6621.1  363.72
#Mann=6,-1,0
  4498.3    0.16       0  4787.8    0.12       0  4997.4    0.07       0
  5003.4    0.12       0  5134.3    0.07       0  5442.2    0.05       0
Bank Sta=4997.4,5003.4
Exp/Cntr=0.3,0.1

Type RM Length L Ch R = 1,5457,465,465,465
BEGIN DESCRIPTION:
UNT149 IN CCTC 9.0
END DESCRIPTION:
XS GIS Cut Line= 3
      3568949.57     10627360.18      3569291.79     10627453.93
      3570549.58     10628710.15
#Sta/Elev= 30
  4570.9  359.37  4627.8  354.83  4662.3  347.25  4716.7  340.82  4747.2  336.96
  4799.0  334.42  4928.6  331.86  5038.7  331.69  5041.5  331.19  5044.7  331.69
  5324.6  332.91  5416.5  334.91  5451.9  333.54  5514.8  333.81  5522.6  334.96
  5543.8  333.37  5621.6  332.55  5897.4  336.04  6104.7  335.71  6307.5  336.48
  6314.5  334.09  6328.7  336.68  6364.0  336.89  6399.4  340.47  6420.6  340.57
  6448.9  344.40  6465.0  344.35  6505.5  345.65  6620.3  354.80  6703.4  361.08
#Mann=8,-1,0
  4570.9    0.16       0  4716.7    0.12       0  5038.7    0.07       0
  5044.7    0.12       0  5514.8    0.05       0  6104.7    0.12       0
  6465.0    0.05       0  6620.3    0.12       0
Bank Sta=5038.7,5044.7
Exp/Cntr=0.3,0.1

Type RM Length L Ch R = 1,4992,668,668,668
BEGIN DESCRIPTION:
UNT149 IN CCTC 8.0
END DESCRIPTION:
XS GIS Cut Line= 3
      3568899.64     10627510.22      3569155.07     10627840.21
      3570399.62     10628810.20
#Sta/Elev= 30
  4491.2  353.43  4541.7  347.88  4554.5  345.25  4577.2  343.06  4583.5  341.22
  4683.1  331.64  4755.6  331.51  4769.4  332.52  5023.2  331.26  5026.0  330.76
  5029.2  331.26  5300.1  331.66  5513.2  331.82  5654.0  332.16  5751.8  332.76
  5824.2  334.49  5830.5  333.64  5859.5  334.48  5873.9  333.38  5923.7  333.02
  5979.8  336.35  6030.0  336.90  6037.7  336.00  6087.4  335.58  6151.7  336.88
  6280.1  345.46  6315.4  346.73  6350.7  350.67  6464.1  359.85  6486.4  361.24
#Mann=7,-1,0
  4491.2    0.12       0  5023.2    0.07       0  5029.2    0.12       0
  5300.1    0.16       0  5513.2    0.05       0  5654.0    0.12       0
  6464.1    0.16       0
Bank Sta=5023.2,5029.2
Exp/Cntr=0.3,0.1

Type RM Length L Ch R = 1,4324,542,542,542
BEGIN DESCRIPTION:
UNT149 IN CCTC 7.0
END DESCRIPTION:
XS GIS Cut Line= 3
      3568054.34     10627591.88      3569182.82     10628503.35
      3569737.41     10629326.56
#Sta/Elev= 30
  3766.4  361.25  3818.8  355.62  3868.4  353.39  3911.5  348.94  4217.0  334.26
  4287.4  332.32  4316.1  330.65  4324.1  327.43  4330.5  329.65  4335.5  326.71
  4338.2  326.21  4341.5  326.71  4383.6  326.71  4557.8  326.71  4699.9  326.71
  4707.9  329.55  4721.8  329.73  4753.4  331.72  4864.6  333.06  5013.3  330.70
  5234.2  333.91  5424.2  336.00  5457.7  336.59  5753.4  337.86  5822.1  340.82
  5918.4  345.82  5969.4  350.83  5990.4  350.48  6128.3  360.52  6209.6  360.28
#Mann=11,-1,0
  3766.4    0.16       0  4335.5    0.07       0  4341.5    0.16       0
  4383.6    0.07       0  4557.8    0.05       0  4721.8    0.16       0
  4753.4    0.12       0  5234.2    0.07       0  5424.2    0.12       0
  5457.7    0.07       0  5822.1    0.16       0
Bank Sta=4335.5,4341.5
Exp/Cntr=0.3,0.1

Type RM Length L Ch R = 1,3782,265,265,265
BEGIN DESCRIPTION:
UNT149 IN CCTC 6.0
END DESCRIPTION:
XS GIS Cut Line= 2
      3568010.93     10628017.22      3569338.34     10629205.82
#Sta/Elev= 30
  4249.7  360.75  4421.1  349.59  4463.0  348.85  4590.8  340.94  4611.8  341.07
  4711.2  335.23  4732.1  335.64  4753.8  333.84  4760.5  334.70  4798.4  332.09
  4838.5  330.94  4857.0  326.71  4859.7  326.21  4863.0  326.71  4926.6  326.71
  4936.9  326.71  5079.8  326.71  5086.5  329.69  5125.0  329.72  5130.3  329.69
  5426.7  332.61  5476.0  335.05  5532.8  334.72  5731.2  342.11  5830.4  346.50
  5851.3  349.58  5865.5  347.84  5957.5  354.21  6028.5  356.54  6031.5  358.05
#Mann=9,-1,0
  4249.7    0.16       0  4798.4    0.08       0  4857.0    0.07       0
  4863.0    0.08       0  4926.6    0.07       0  4936.9    0.12       0
  5125.0    0.05       0  5130.3    0.12       0  5731.2    0.16       0
Bank Sta=4857,4863
Exp/Cntr=0.3,0.1

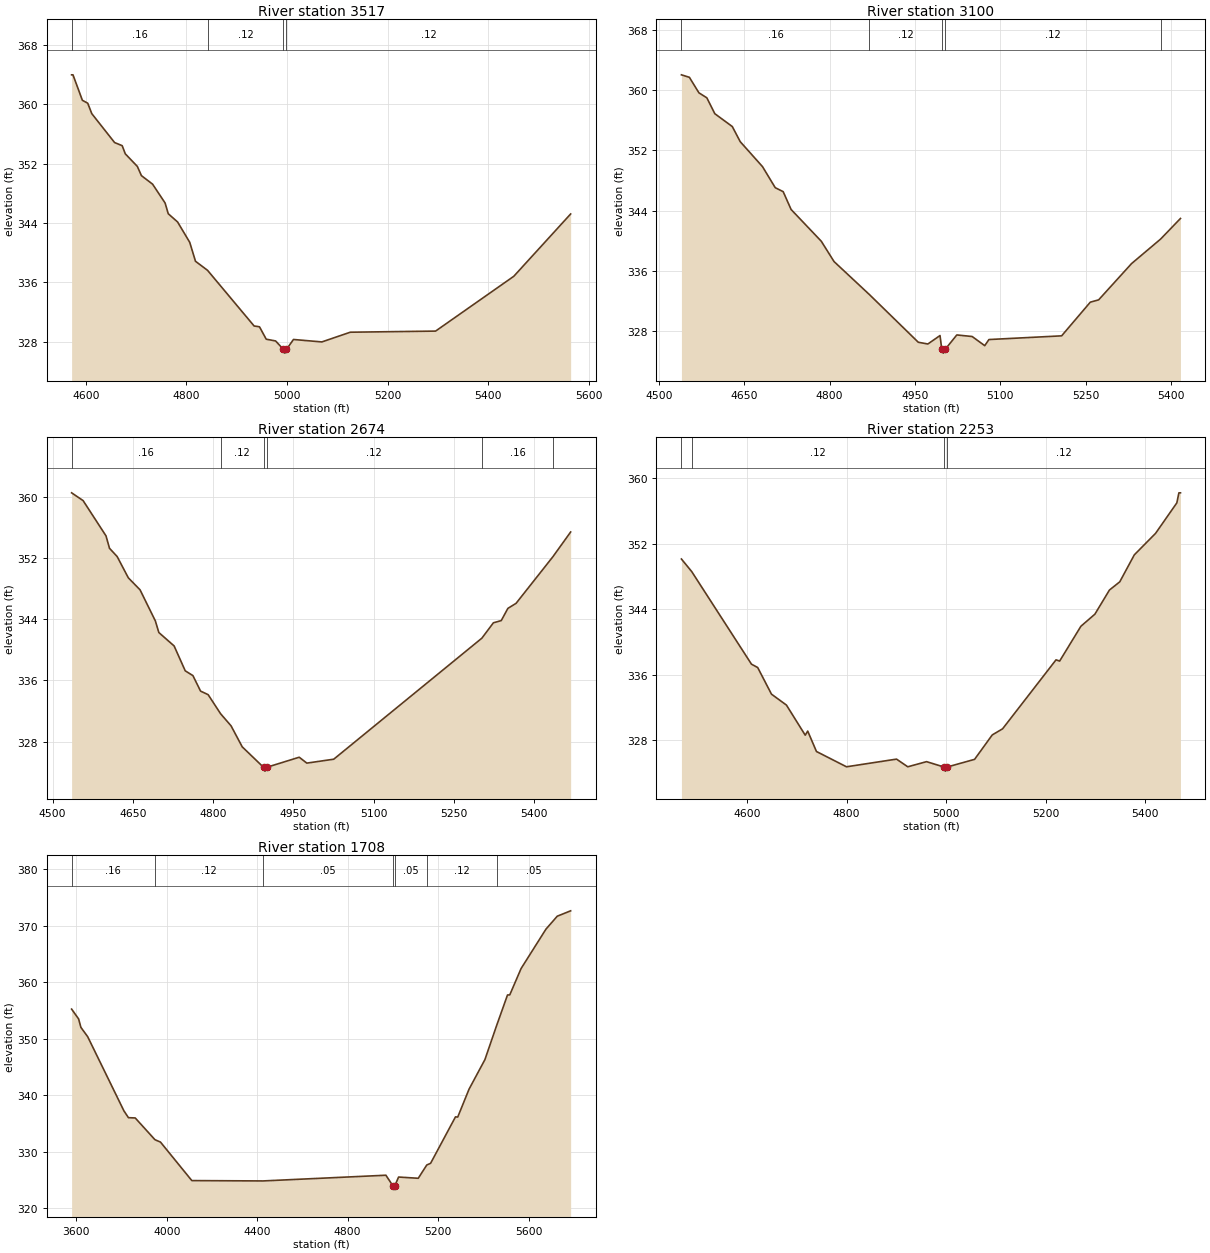
Type RM Length L Ch R = 1,3517,417,417,417
BEGIN DESCRIPTION:
UNT149 IN CCTC 5.0
END DESCRIPTION:
XS GIS Cut Line= 3
      3568099.59     10628610.18      3568499.61     10628760.19
      3568899.61     10629160.19
#Sta/Elev= 30
  4571.5  363.99  4574.2  363.99  4592.9  360.56  4603.6  360.16  4611.6  358.76
  4657.0  354.86  4672.1  354.44  4678.3  353.34  4702.3  351.64  4710.4  350.40
  4732.6  349.25  4757.5  346.71  4763.8  345.26  4782.4  344.15  4806.5  341.41
  4818.0  338.85  4842.0  337.63  4934.6  330.13  4945.3  330.02  4958.7  328.35
  4977.4  328.11  4993.0  326.97  4995.8  326.47  4999.0  326.97  5012.9  328.31
  5069.4  327.98  5126.0  329.29  5295.7  329.44  5451.3  336.83  5564.4  345.23
#Mann=4,-1,0
  4571.5    0.16       0  4842.0    0.12       0  4993.0    0.07       0
  4999.0    0.12       0
Bank Sta=4993,4999
Exp/Cntr=0.3,0.1

Type RM Length L Ch R = 1,3100,426,426,426
BEGIN DESCRIPTION:
UNT149 IN CCTC 4.0
END DESCRIPTION:
XS GIS Cut Line= 3
      3568049.62     10628660.21      3568249.61     10629060.19
      3568499.60     10629410.18
#Sta/Elev= 30
  4539.5  362.00  4553.5  361.67  4570.2  359.62  4584.2  358.95  4598.2  356.85
  4628.9  355.15  4642.9  353.14  4682.0  349.84  4704.4  347.05  4718.4  346.52
  4732.3  344.16  4785.4  339.95  4807.8  337.26  4869.8  332.90  4955.9  326.57
  4972.7  326.34  4994.1  327.46  4997.2  325.63  5000.0  325.13  5003.2  325.63
  5023.6  327.54  5050.6  327.33  5072.7  326.12  5080.1  326.93  5207.9  327.42
  5258.3  331.88  5273.0  332.19  5330.8  336.99  5381.9  340.24  5416.8  342.97
#Mann=5,-1,0
  4539.5    0.16       0  4869.8    0.12       0  4997.2    0.07       0
  5003.2    0.12       0  5381.9     0.1       0
Bank Sta=4997.2,5003.2
Exp/Cntr=0.3,0.1

Type RM Length L Ch R = 1,2674,421,421,421
BEGIN DESCRIPTION:
UNT149 IN CCTC 3.0
END DESCRIPTION:
XS GIS Cut Line= 3
      3567749.58     10629060.15      3568049.61     10629410.19
      3568299.60     10629810.17
#Sta/Elev= 30
  4535.6  360.57  4557.1  359.55  4599.9  354.93  4606.4  353.31  4620.7  352.23
  4641.6  349.44  4663.5  347.87  4692.1  343.80  4698.6  342.28  4727.2  340.52
  4748.0  337.26  4762.3  336.64  4776.6  334.61  4790.8  334.14  4814.0  331.65
  4833.6  330.06  4854.5  327.31  4894.3  324.63  4897.0  324.13  4900.3  324.63
  4961.0  325.95  4975.2  325.18  5025.5  325.69  5302.4  341.54  5323.9  343.55
  5338.6  343.84  5351.0  345.44  5366.3  346.10  5435.2  352.21  5468.3  355.44
#Mann=6,-1,0
  4535.6    0.16       0  4814.0    0.12       0  4894.3    0.07       0
  4900.3    0.12       0  5302.4    0.16       0  5435.2    0.12       0
Bank Sta=4894.3,4900.3
Exp/Cntr=0.3,0.1

Type RM Length L Ch R = 1,2253,545,545,545
BEGIN DESCRIPTION:
UNT149 IN CCTC 2.0
END DESCRIPTION:
XS GIS Cut Line= 3
      3567699.61     10629210.20      3567749.61     10629710.19
      3568149.63     10630010.20
#Sta/Elev= 30
  4468.1  350.14  4488.9  348.59  4608.8  337.27  4621.3  336.86  4649.0  333.60
  4679.1  332.26  4716.8  328.58  4721.8  329.08  4739.4  326.58  4799.7  324.71
  4900.2  325.65  4922.8  324.71  4960.5  325.34  4995.7  324.68  4998.5  324.18
  5001.7  324.68  5057.0  325.62  5092.5  328.61  5113.3  329.36  5220.6  337.80
  5227.9  337.65  5270.6  341.91  5298.7  343.39  5327.9  346.34  5348.7  347.35
  5377.9  350.65  5420.6  353.28  5463.3  357.01  5467.5  358.24  5470.6  358.24
#Mann=4,-1,0
  4468.1    0.16       0  4488.9    0.12       0  4995.7    0.07       0
  5001.7    0.12       0
Bank Sta=4995.7,5001.7
Exp/Cntr=0.3,0.1

Type RM Length L Ch R = 1,1708,0,0,0
BEGIN DESCRIPTION:
UNT149 IN CCTC 1.0
END DESCRIPTION:
XS GIS Cut Line= 4
      3567307.82     10628859.25      3567359.91     10630065.85
      3567637.69     10630274.18      3568288.74     10630274.18
#Sta/Elev= 30
  3579.7  355.27  3610.7  353.53  3620.7  352.04  3650.7  350.39  3810.9  337.26
  3830.9  336.05  3860.9  336.00  3948.1  332.15  3972.5  331.73  4111.1  324.91
  4425.4  324.85  4969.0  325.86  5001.4  323.90  5004.1  323.40  5007.4  323.90
  5025.2  325.54  5112.0  325.32  5149.7  327.67  5166.6  327.97  5276.6  336.19
  5286.6  336.16  5336.6  341.10  5406.6  346.32  5458.9  352.41  5506.6  357.77
  5516.6  357.79  5566.6  362.45  5676.6  369.43  5726.6  371.72  5785.7  372.67
#Mann=7,-1,0
  3579.7    0.16       0  3948.1    0.12       0  4425.4    0.05       0
  5001.4   0.035       0  5007.4    0.05       0  5149.7    0.12       0
  5458.9    0.05       0
Bank Sta=5001.4,5007.4
Exp/Cntr=0.3,0.1

Chan Stop Cuts=-1