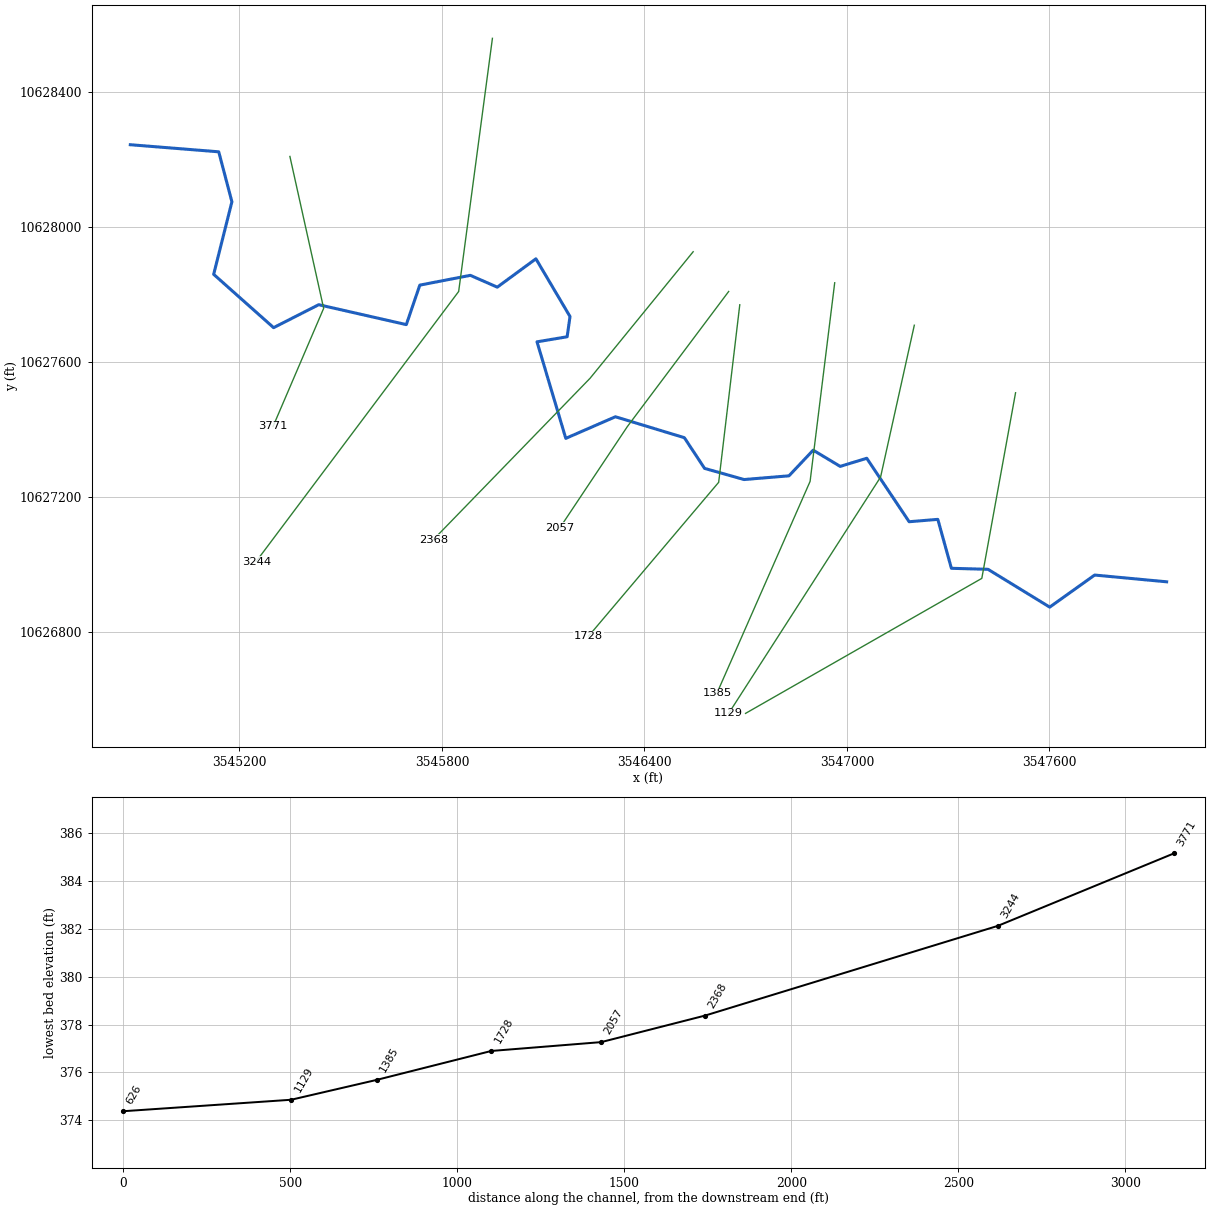
--- UNT155 IN CCTC.prj (project) ---

Proj Title=UNT155 IN CCTC Base Level Engineering
Current Plan=p01
Default Exp/Contr=0.3,0.1
English Units
Geom File=g01
Flow File=f01
Plan File=p01
BEGIN DESCRIPTION:
UNT155 IN CCTC
END DESCRIPTION:

--- UNT155 IN CCTC.p01 (plan) ---

Plan Title=Multiple Run
Short Identifier=Multiple
Geom File=g01
Flow File=f01
Subcritical Flow
K Sum by GR= 0
Std Step Tol= 0.01
Critical Tol= 0.01
Num of Std Step Trials= 20
Max Error Tol= 0.3
Flow Tol Ratio= 0.001
Split Flow NTrial= 30
Split Flow Tol= 0.02
Split Flow Ratio= 0.02
Log Output Level= 0
Friction Slope Method= 1
Unsteady Friction Slope Method= 2
Unsteady Bridges Friction Slope Method= 1
Parabolic Critical Depth
Global Vel Dist=  1 , 1 , 1
Global Log Level= 0
CheckData=True
Encroach Param= -1, 0, 0, 0
BEGIN DESCRIPTION:
Multiple Run
END DESCRIPTION:

--- UNT155 IN CCTC.f01 (steady flow) ---

Flow Title=Multiple
Number of Profiles=7
Profile Names=10-year,25-year,50-year,1pct_min,100-year,1pct_plu,500-year
River Rch & RM= UNT155 IN CCTC,Reach-1,3771
    1663    2310    2849    2562    3465    4686    5109
Boundary for River Rch & Prof#=UNT155 IN CCTC,Reach-1,1
Up Type=0
Dn Type=3
Dn Slope=0.005
Boundary for River Rch & Prof#=UNT155 IN CCTC,Reach-1,2
Up Type=0
Dn Type=3
Dn Slope=0.005
Boundary for River Rch & Prof#=UNT155 IN CCTC,Reach-1,3
Up Type=0
Dn Type=3
Dn Slope=0.005
Boundary for River Rch & Prof#=UNT155 IN CCTC,Reach-1,4
Up Type=0
Dn Type=3
Dn Slope=0.005
Boundary for River Rch & Prof#=UNT155 IN CCTC,Reach-1,5
Up Type=0
Dn Type=3
Dn Slope=0.005
Boundary for River Rch & Prof#=UNT155 IN CCTC,Reach-1,6
Up Type=0
Dn Type=3
Dn Slope=0.005
Boundary for River Rch & Prof#=UNT155 IN CCTC,Reach-1,7
Up Type=0
Dn Type=3
Dn Slope=0.005

--- UNT155 IN CCTC.g01 (geometry) ---

Geom Title=Existing Conditions

River Reach=UNT155 IN CCTC,Reach-1
Reach XY= 30
      3544876.75     10628245.00      3545138.75     10628224.00
      3545177.75     10628076.00      3545123.75     10627861.00
      3545301.25     10627703.00      3545435.00     10627771.00
      3545694.50     10627712.00      3545734.50     10627829.00
      3545884.25     10627858.00      3545964.00     10627823.00
      3546078.50     10627907.00      3546179.50     10627736.00
      3546171.00     10627676.00      3546081.75     10627661.00
      3546167.00     10627375.00      3546314.00     10627439.00
      3546518.25     10627377.00      3546578.25     10627286.00
      3546695.25     10627253.00      3546828.25     10627264.00
      3546900.00     10627340.00      3546980.00     10627292.00
      3547058.75     10627316.00      3547184.25     10627128.00
      3547269.25     10627135.00      3547309.50     10626990.00
      3547418.00     10626987.00      3547600.75     10626875.00
      3547734.00     10626970.00      3547947.25     10626950.00

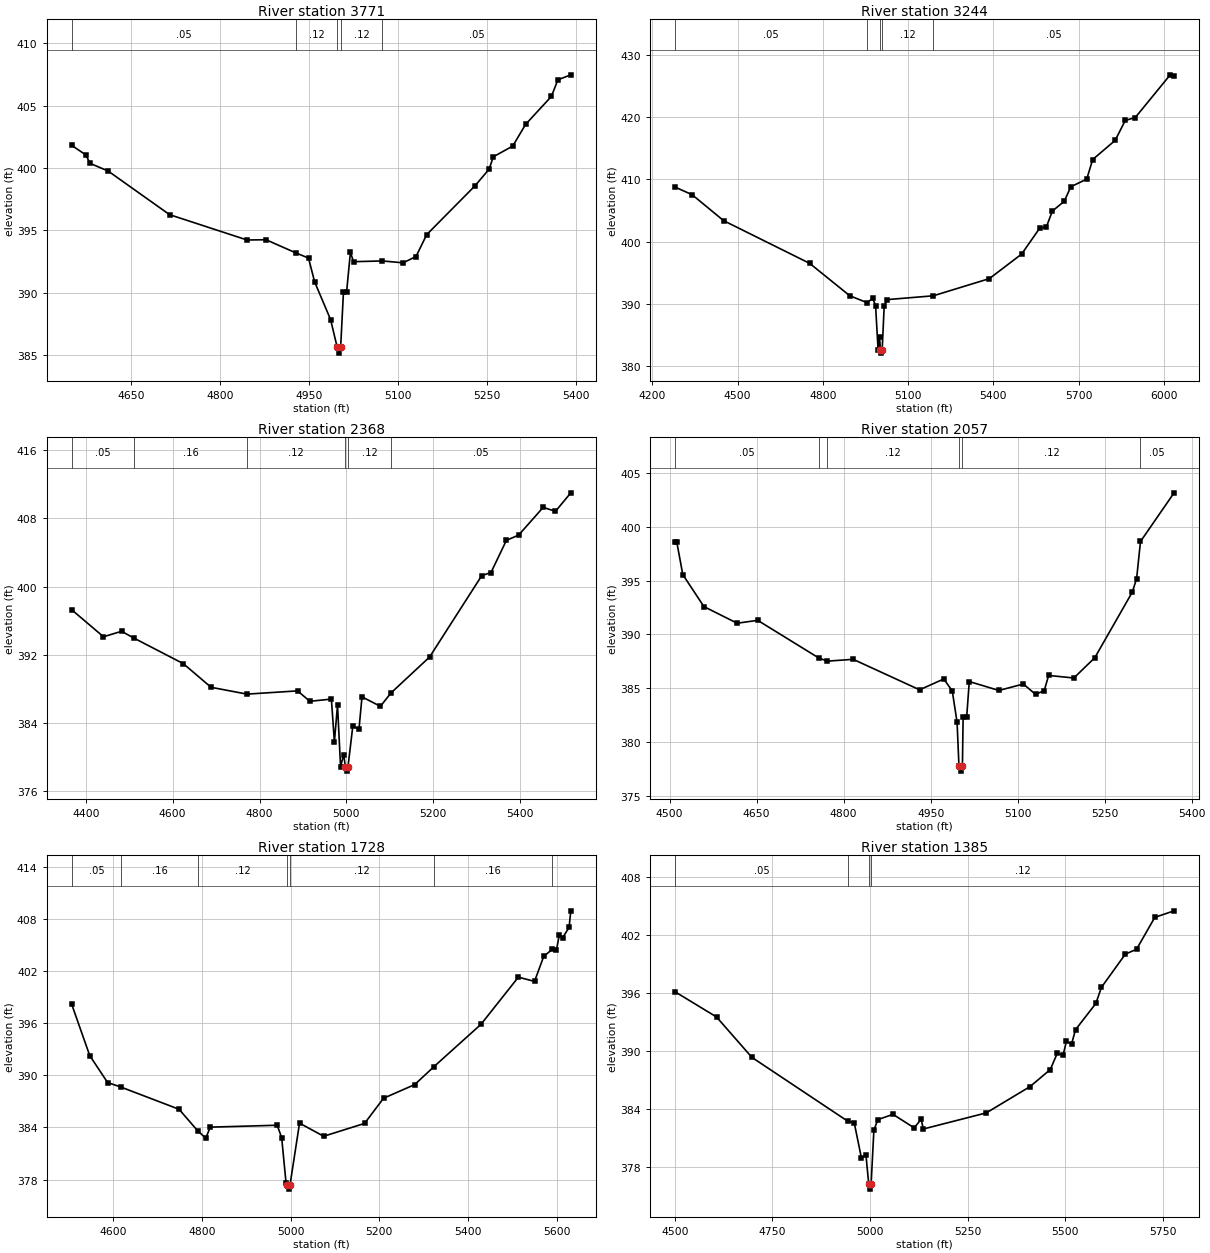
Type RM Length L Ch R = 1,3771,527,527,527
BEGIN DESCRIPTION:
UNT155 IN CCTC 7.0
END DESCRIPTION:
XS GIS Cut Line= 3
      3545349.61     10628210.20      3545449.61     10627760.19
      3545299.60     10627410.17
#Sta/Elev= 30
  4549.1  401.82  4573.4  401.04  4579.8  400.38  4610.6  399.76  4714.3  396.26
  4844.9  394.23  4876.9  394.25  4927.0  393.20  4948.6  392.78  4958.9  390.87
  4985.8  387.85  4996.8  385.66  4999.6  385.16  5002.8  385.66  5007.5  390.05
  5012.8  390.05  5019.2  393.23  5024.6  392.49  5073.1  392.55  5108.0  392.40
  5129.8  392.90  5147.9  394.66  5229.5  398.58  5253.1  399.91  5260.3  400.90
  5293.0  401.76  5314.7  403.50  5358.2  405.74  5369.1  407.07  5390.9  407.47
#Mann=5,-1,0
  4549.1    0.05       0  4927.0    0.12       0  4996.8    0.07       0
  5002.8    0.12       0  5073.1    0.05       0
Bank Sta=4996.8,5002.8
Exp/Cntr=0.3,0.1

Type RM Length L Ch R = 1,3244,876,876,876
BEGIN DESCRIPTION:
UNT155 IN CCTC 6.0
END DESCRIPTION:
XS GIS Cut Line= 3
      3545949.61     10628560.21      3545849.61     10627810.19
      3545249.59     10627010.16
#Sta/Elev= 30
  4279.2  408.79  4339.8  407.56  4450.7  403.39  4753.4  396.54  4894.6  391.34
  4955.0  390.24  4975.3  390.90  4985.4  389.77  4994.2  382.70  4999.3  384.70
  5002.6  382.63  5005.3  382.13  5008.6  382.63  5015.7  389.67  5025.8  390.72
  5188.4  391.33  5385.9  394.09  5499.4  398.03  5564.0  402.25  5585.9  402.33
  5607.7  404.94  5649.4  406.50  5672.3  408.82  5728.6  410.07  5749.4  413.20
  5828.6  416.28  5864.0  419.47  5899.4  419.95  6022.3  426.80  6035.9  426.59
#Mann=5,-1,0
  4279.2    0.05       0  4955.0    0.12       0  5002.6    0.07       0
  5008.6    0.12       0  5188.4    0.05       0
Bank Sta=5002.6,5008.6
Exp/Cntr=0.3,0.1

Type RM Length L Ch R = 1,2368,311,311,311
BEGIN DESCRIPTION:
UNT155 IN CCTC 5.0
END DESCRIPTION:
XS GIS Cut Line= 3
      3546544.41     10627927.94      3546238.87     10627552.96
      3545774.78     10627075.01
#Sta/Elev= 30
  4367.2  397.29  4440.6  394.12  4482.3  394.76  4510.4  393.97  4624.5  390.97
  4688.4  388.20  4771.2  387.40  4887.7  387.78  4916.0  386.56  4965.6  386.82
  4972.5  381.81  4979.7  386.11  4986.7  378.92  4993.9  380.32  4997.8  378.88
  5000.6  378.38  5003.8  378.88  5015.0  383.68  5029.1  383.26  5036.1  387.08
  5078.5  385.97  5103.1  387.55  5191.7  391.74  5312.1  401.29  5333.2  401.64
  5368.7  405.41  5397.0  406.03  5453.5  409.28  5481.8  408.81  5517.1  410.98
#Mann=6,-1,0
  4367.2    0.05       0  4510.4    0.16       0  4771.2    0.12       0
  4997.8    0.07       0  5003.8    0.12       0  5103.1    0.05       0
Bank Sta=4997.8,5003.8
Exp/Cntr=0.3,0.1

Type RM Length L Ch R = 1,2057,329,329,329
BEGIN DESCRIPTION:
UNT155 IN CCTC 4.0
END DESCRIPTION:
XS GIS Cut Line= 3
      3546649.63     10627810.22      3546349.61     10627410.19
      3546149.60     10627110.18
#Sta/Elev= 30
  4509.1  398.61  4512.3  398.61  4522.7  395.57  4559.1  392.59  4616.4  391.04
  4651.8  391.31  4757.0  387.81  4772.0  387.51  4816.4  387.68  4931.0  384.84
  4972.7  385.85  4987.3  384.73  4995.6  381.80  4998.8  377.77  5001.6  377.27
  5004.8  377.77  5006.0  382.28  5012.1  382.28  5016.6  385.61  5067.7  384.78
  5109.8  385.38  5130.8  384.42  5145.8  384.76  5153.4  386.18  5196.9  385.94
  5233.0  387.83  5297.6  393.93  5305.1  395.19  5311.8  398.65  5369.7  403.18
#Mann=6,-1,0
  4509.1    0.05       0  4757.0    0.16       0  4772.0    0.12       0
  4998.8    0.07       0  5004.8    0.12       0  5311.8    0.05       0
Bank Sta=4998.8,5004.8
Exp/Cntr=0.3,0.1

Type RM Length L Ch R = 1,1728,343,343,343
BEGIN DESCRIPTION:
Mapping XS f20dbeac
END DESCRIPTION:
XS GIS Cut Line= 3
      3546682.49     10627770.85      3546620.00     10627244.85
      3546234.61     10626789.16
#Sta/Elev= 30
  4505.7  398.22  4546.6  392.28  4586.9  389.18  4617.3  388.65  4748.1  386.10
  4790.7  383.59  4808.5  382.77  4818.5  384.04  4969.6  384.26  4979.7  382.83
  4989.7  377.55  4992.6  377.40  4995.3  376.90  4998.6  377.40  5020.0  384.50
  5074.5  382.99  5166.8  384.47  5209.6  387.37  5279.9  388.94  5323.6  391.02
  5429.4  395.88  5513.9  401.32  5550.3  400.83  5571.1  403.71  5590.7  404.54
  5599.7  404.45  5606.2  406.14  5614.0  405.88  5628.3  407.05  5632.2  408.96
#Mann=7,-1,0
  4505.7    0.05       0  4617.3    0.16       0  4790.7    0.12       0
  4992.6    0.07       0  4998.6    0.12       0  5323.6    0.16       0
  5590.7    0.12       0
Bank Sta=4992.6,4998.6
Exp/Cntr=0.3,0.1

Type RM Length L Ch R = 1,1385,256,256,256
BEGIN DESCRIPTION:
UNT155 IN CCTC 3.0
END DESCRIPTION:
XS GIS Cut Line= 3
      3546963.75     10627836.01      3546890.83     10627247.46
      3546614.78     10626619.83
#Sta/Elev= 30
  4500.2  396.15  4606.8  393.53  4697.5  389.34  4943.3  382.72  4959.5  382.58
  4977.9  378.94  4989.7  379.18  4996.8  376.19  4999.6  375.69  5002.8  376.19
  5009.9  381.79  5020.0  382.89  5058.9  383.44  5113.1  382.04  5131.0  382.93
  5136.5  381.92  5297.8  383.59  5409.7  386.31  5461.8  388.08  5479.7  389.77
  5494.5  389.56  5503.0  390.99  5516.3  390.73  5526.4  392.21  5578.5  394.93
  5592.8  396.60  5654.0  400.04  5682.8  400.55  5729.5  403.85  5778.9  404.53
#Mann=4,-1,0
  4500.2    0.05       0  4943.3    0.12       0  4996.8    0.07       0
  5002.8    0.12       0
Bank Sta=4996.8,5002.8
Exp/Cntr=0.3,0.1

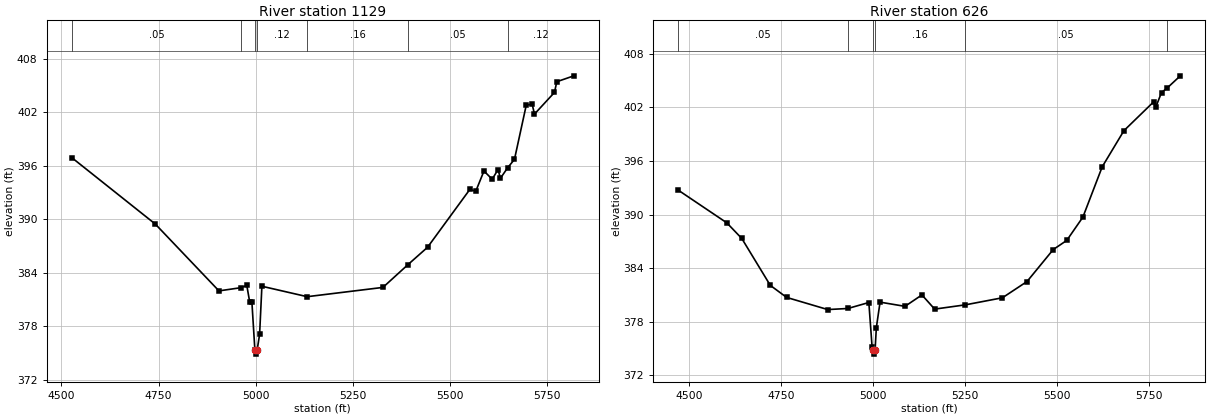
Type RM Length L Ch R = 1,1129,503,503,503
BEGIN DESCRIPTION:
UNT155 IN CCTC 2.0
END DESCRIPTION:
XS GIS Cut Line= 3
      3547199.62     10627710.23      3547099.61     10627260.19
      3546649.60     10626560.18
#Sta/Elev= 30
  4526.6  396.89  4741.8  389.44  4905.7  381.95  4962.5  382.31  4977.4  382.57
  4985.1  380.66  4990.6  380.66  4998.2  375.36  5000.9  374.86  5004.2  375.36
  5010.4  377.07  5016.3  382.47  5133.0  381.30  5328.1  382.34  5392.7  384.90
  5443.0  386.84  5552.0  393.33  5567.2  393.12  5588.3  395.39  5609.4  394.47
  5624.6  395.55  5630.6  394.57  5649.3  395.75  5666.9  396.70  5697.3  402.79
  5712.5  402.86  5718.4  401.77  5769.9  404.20  5775.9  405.40  5819.8  406.06
#Mann=7,-1,0
  4526.6    0.05       0  4962.5    0.12       0  4998.2    0.07       0
  5004.2    0.12       0  5133.0    0.16       0  5392.7    0.05       0
  5649.3    0.12       0
Bank Sta=4998.2,5004.2
Exp/Cntr=0.3,0.1

Type RM Length L Ch R = 1,626,0,0,0
BEGIN DESCRIPTION:
UNT155 IN CCTC 1.0
END DESCRIPTION:
XS GIS Cut Line= 3
      3547499.60     10627510.16      3547399.61     10626960.19
      3546699.62     10626560.19
#Sta/Elev= 30
  4471.2  392.74  4603.3  389.08  4644.0  387.33  4721.5  382.08  4765.9  380.73
  4877.7  379.37  4932.5  379.49  4989.5  380.16  4998.4  375.13  5000.5  374.88
  5003.3  374.38  5006.5  374.88  5009.9  377.36  5020.0  380.20  5087.8  379.73
  5133.8  381.01  5168.4  379.42  5252.2  379.90  5352.7  380.69  5419.6  382.51
  5490.9  386.09  5527.6  387.11  5571.5  389.72  5624.1  395.36  5683.1  399.40
  5763.7  402.62  5769.5  402.02  5785.3  403.67  5800.5  404.17  5836.4  405.54
#Mann=6,-1,0
  4471.2    0.05       0  4932.5    0.16       0  5000.5    0.07       0
  5006.5    0.16       0  5252.2    0.05       0  5800.5    0.12       0
Bank Sta=5000.5,5006.5
Exp/Cntr=0.3,0.1

Chan Stop Cuts=-1