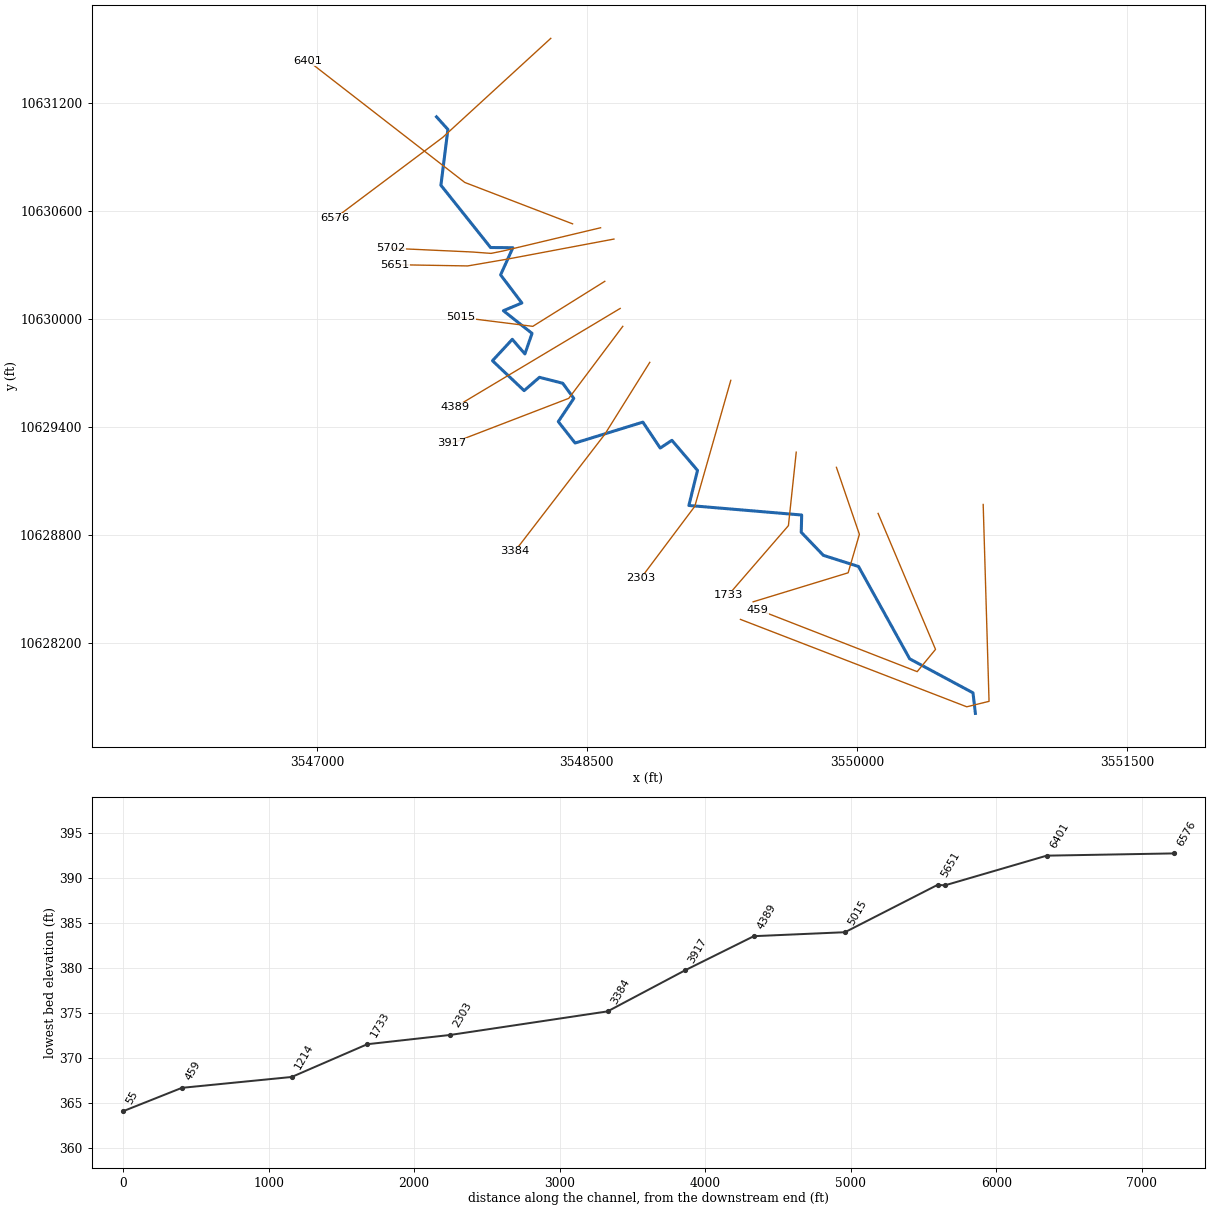
--- UNT156 IN CCTC.prj (project) ---

Proj Title=UNT156 IN CCTC Base Level Engineering
Current Plan=p01
Default Exp/Contr=0.3,0.1
English Units
Geom File=g01
Flow File=f01
Plan File=p01
Y Axis Title=Elevation
X Axis Title(PF)=Main Channel Distance
X Axis Title(XS)=Station
BEGIN DESCRIPTION:
UNT156 IN CCTC
END DESCRIPTION:
DSS Export Rating Curves= 0
DSS Export Rating Curve Sorted= 0
DSS Export Volume Flow Curves= 0
DXF OffsetX= 0
DXF OffsetY= 0
DXF ScaleX= 1
DXF ScaleY= 10

--- UNT156 IN CCTC.p01 (plan) ---

Plan Title=Multiple Run
Short Identifier=Multiple
Geom File=g01
Flow File=f01
Subcritical Flow
K Sum by GR= 0
Std Step Tol= 0.01
Critical Tol= 0.01
Num of Std Step Trials= 20
Max Error Tol= 0.3
Flow Tol Ratio= 0.001
Split Flow NTrial= 30
Split Flow Tol= 0.02
Split Flow Ratio= 0.02
Log Output Level= 0
Friction Slope Method= 1
Unsteady Friction Slope Method= 2
Unsteady Bridges Friction Slope Method= 1
Parabolic Critical Depth
Global Vel Dist=  1 , 1 , 1
Global Log Level= 0
CheckData=True
Encroach Param= -1, 0, 0, 0
BEGIN DESCRIPTION:
Multiple Run
END DESCRIPTION:

--- UNT156 IN CCTC.f01 (steady flow) ---

Flow Title=Multiple
Number of Profiles=7
Profile Names=10-year,25-year,50-year,1pct_min,100-year,1pct_plu,500-year
River Rch & RM= UNT156 IN CCTC,Reach-1,6576
    1476    2034    2496    2233    3021    4085    4410
Boundary for River Rch & Prof#=UNT156 IN CCTC,Reach-1,1
Up Type=0
Dn Type=3
Dn Slope=0.005
Boundary for River Rch & Prof#=UNT156 IN CCTC,Reach-1,2
Up Type=0
Dn Type=3
Dn Slope=0.005
Boundary for River Rch & Prof#=UNT156 IN CCTC,Reach-1,3
Up Type=0
Dn Type=3
Dn Slope=0.005
Boundary for River Rch & Prof#=UNT156 IN CCTC,Reach-1,4
Up Type=0
Dn Type=3
Dn Slope=0.005
Boundary for River Rch & Prof#=UNT156 IN CCTC,Reach-1,5
Up Type=0
Dn Type=3
Dn Slope=0.005
Boundary for River Rch & Prof#=UNT156 IN CCTC,Reach-1,6
Up Type=0
Dn Type=3
Dn Slope=0.005
Boundary for River Rch & Prof#=UNT156 IN CCTC,Reach-1,7
Up Type=0
Dn Type=3
Dn Slope=0.005

--- UNT156 IN CCTC.g01 (geometry) ---

Geom Title=Existing Conditions
Program Version=4.10

River Reach=UNT156 IN CCTC  ,Reach-1
Reach XY= 30
      3547664.66     10631124.15        3547728.       10631054.
      3547689.25       10630744.      3547965.25       10630398.
        3548089.       10630397.      3548020.75       10630246.
        3548139.       10630090.      3548036.25       10630047.
       3548195.5       10629921.      3548155.75       10629807.
      3548085.75       10629888.      3547975.75       10629769.
       3548151.5       10629603.      3548236.75       10629677.
        3548366.       10629644.       3548427.5       10629560.
      3548341.25       10629431.       3548434.5       10629312.
      3548811.25       10629428.       3548907.5       10629284.
       3548972.5       10629327.      3549114.75       10629160.
      3549066.75       10628965.       3549693.5       10628912.
        3549691.       10628816.        3549814.       10628688.
      3550009.25       10628626.       3550293.5       10628113.
      3550645.25       10627924.       3550658.5       10627810.

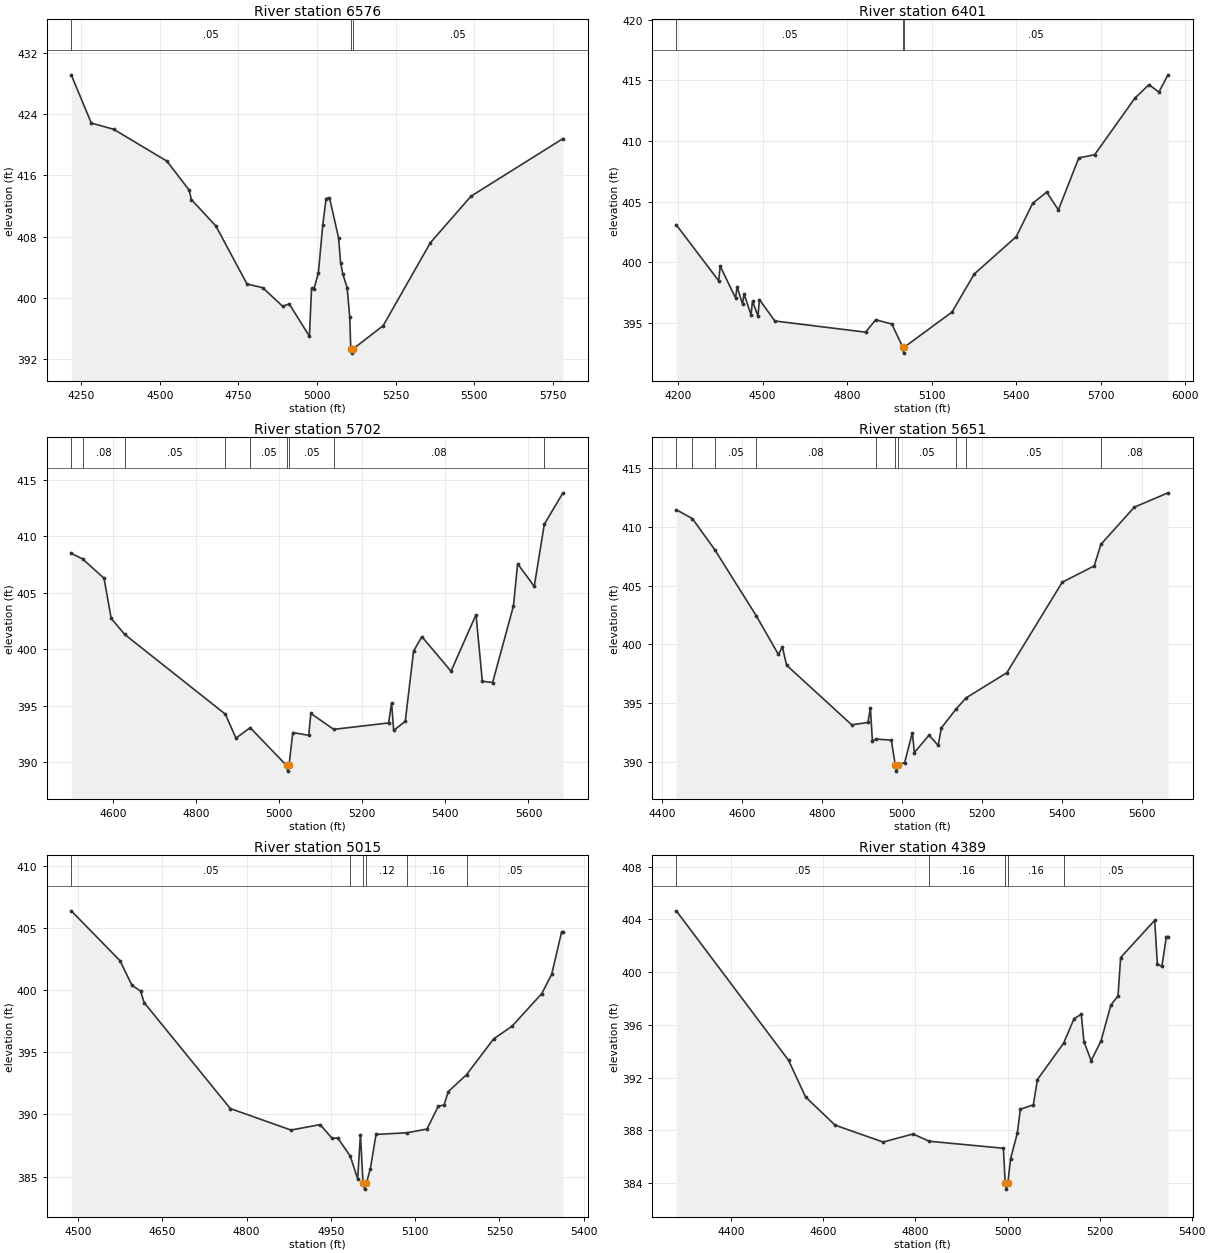
Type RM Length L Ch R = 1 ,6576    ,874,874,874
BEGIN DESCRIPTION:
UNT156 IN CCTC 10.0
END DESCRIPTION:
XS GIS Cut Line= 3
      3548299.63      10631560.2      3547699.61     10631010.19
      3547099.58     10630560.17
#Sta/Elev= 30
  4218.2  429.15    4282  422.84    4353  422.03  4522.5  417.86  4593.4  414.06
  4600.2  412.84  4678.5  409.36  4777.2  401.79  4827.1  401.31  4890.6  398.88
  4911.6  399.18  4975.7  394.96  4982.5  401.21  4989.9  401.13  5004.1  403.19
  5018.3  409.55  5028.8  412.97  5039.5  413.09  5068.6   407.8  5074.9  404.59
  5082.2  403.05  5095.7  401.32    5104  397.46  5107.3  393.25    5110  392.75
  5113.3  393.25  5210.3  396.34  5360.3  407.18  5489.5  413.27  5782.2  420.81
#Mann= 3 ,-1 , 0
  4218.2     .05       0  5107.3     .03       0  5113.3     .05       0
Bank Sta=5107.3,5113.3
XS Rating Curve= 0 ,0
Exp/Cntr=0.3,0.1

Type RM Length L Ch R = 1 ,6401    ,699,699,699
BEGIN DESCRIPTION:
UNT156 IN CCTC 10.0
END DESCRIPTION:
XS GIS Cut Line= 3
      3548420.71      10630529.6      3547821.73     10630759.64
      3546950.32     10631435.96
#Sta/Elev= 30
  4193.5  403.08  4343.9  398.47  4349.3  399.67  4403.9  397.05  4409.3  397.98
  4428.6  396.55    4434  397.38  4458.6  395.66    4464  396.79  4483.3  395.57
  4488.6  396.91  4543.3  395.15    4865  394.23  4901.1  395.25  4958.2   394.9
    4997     393  4999.8   392.5    5003     393  5171.8  395.89  5250.6  399.02
  5399.9  402.11  5457.9  404.85  5507.6  405.78  5549.3  404.31  5621.7   408.6
  5677.8  408.86  5820.8  413.53  5870.6  414.64  5905.9  414.03  5938.2  415.45
#Mann= 3 ,-1 , 0
  4193.5     .05       0    4997     .03       0    5003     .05       0
Bank Sta=4997,5003
XS Rating Curve= 0 ,0
Exp/Cntr=0.3,0.1

Type RM Length L Ch R = 1 ,5702    ,51,51,51
BEGIN DESCRIPTION:
UNT156 IN CCTC 9.0
END DESCRIPTION:
XS GIS Cut Line= 5
      3548576.35     10630507.85      3548032.96     10630378.51
      3547967.86     10630365.49      3547861.09      10630373.3
      3547410.59     10630394.14
#Sta/Elev= 30
    4500  408.49  4527.5  407.99  4578.9  406.28  4596.1  402.73  4628.2  401.32
  4870.6  394.25  4896.3  392.12  4930.5  393.05  5017.9   389.7  5020.7   389.2
  5023.9   389.7    5033  392.62  5071.3  392.37  5076.4  394.31  5131.5   392.9
  5263.5  393.47  5270.7  395.25  5275.7  392.81  5303.6  393.61  5323.6  399.84
  5343.6  401.11  5413.7  398.05  5473.8  403.06    5489  397.16  5513.8  397.05
  5563.9  403.84  5573.9  407.57  5613.9  405.56  5638.1  411.07    5683  413.85
#Mann= 9 ,-1 , 0
    4500      .1       0  4527.5     .08       0  4628.2     .05       0
  4870.6     .08       0  4930.5     .05       0  5017.9     .04       0
  5023.9     .05       0  5131.5     .08       0  5638.1     .05       0
Bank Sta=5017.9,5023.9
XS Rating Curve= 0 ,0
Exp/Cntr=0.3,0.1

Type RM Length L Ch R = 1 ,5651    ,636,636,636
BEGIN DESCRIPTION:
UNT156 IN CCTC 8.0
END DESCRIPTION:
XS GIS Cut Line= 4
      3548650.52     10630445.06      3548060.24     10630333.95
      3547838.01     10630295.76       3547435.2      10630302.7
#Sta/Elev= 30
    4436  411.44  4476.3  410.68  4532.4  408.03  4635.6  402.45  4691.3  399.15
    4701  399.81  4711.7  398.24  4874.5  393.18  4915.2  393.38  4921.1  394.63
  4926.1  391.84  4935.4  391.97  4973.5  391.88  4983.4  389.75  4986.2  389.25
  4989.4  389.75  5006.8  389.98    5026  392.51  5031.1  390.83  5067.7   392.3
  5090.7  391.43  5098.2   392.9    5135  394.51  5160.1  395.46  5262.1   397.6
  5400.6  405.28  5480.6  406.67  5497.2  408.49  5580.6  411.65    5665  412.87
#Mann= 10 ,-1 , 0
    4436      .1       0  4476.3     .08       0  4532.4     .05       0
  4635.6     .08       0  4935.4     .05       0  4983.4     .04       0
  4989.4     .05       0    5135     .08       0  5160.1     .05       0
  5497.2     .08       0
Bank Sta=4983.4,4989.4
XS Rating Curve= 0 ,0
Exp/Cntr=0.3,0.1

Type RM Length L Ch R = 1 ,5015    ,626,626,626
BEGIN DESCRIPTION:
UNT156 IN CCTC 7.0
END DESCRIPTION:
XS GIS Cut Line= 3
      3548599.61     10630210.19      3548199.61     10629960.19
      3547799.62     10630010.19
#Sta/Elev= 30
  4488.2  406.37  4574.9  402.36  4596.1  400.39  4611.4  399.92  4617.9  398.99
  4771.2  390.47  4879.1  388.74    4931  389.18  4952.2  388.08  4962.4   388.1
  4984.6  386.64  4997.7  384.82  5002.7  388.38  5007.3  384.49    5010  383.99
  5013.3  384.49  5020.4  385.64  5030.4  388.39  5084.8  388.52  5121.1  388.82
  5141.3  390.67  5151.4  390.75  5158.9  391.83  5191.4  393.19  5239.6  396.07
  5272.3  397.09  5325.2  399.71  5342.9  401.26  5360.5  404.66    5363  404.66
#Mann= 6 ,-1 , 0
  4488.2     .05       0  4984.6     .12       0  5007.3     .07       0
  5013.3     .12       0  5084.8     .16       0  5191.4     .05       0
Bank Sta=5007.3,5013.3
XS Rating Curve= 0 ,0
Exp/Cntr=0.3,0.1

Type RM Length L Ch R = 1 ,4389    ,472,472,472
BEGIN DESCRIPTION:
UNT156 IN CCTC 6.0
END DESCRIPTION:
XS GIS Cut Line= 2
      3548685.25     10630059.65      3547768.57     10629511.04
#Sta/Elev= 30
  4280.3  404.65  4524.2  393.32  4561.2  390.54  4625.3   388.4  4729.7  387.12
  4794.6  387.73  4829.7  387.18    4991  386.65  4994.8  384.05  4997.5  383.55
  5000.8  384.05  5006.5  385.84  5021.1  387.78  5027.9  389.61    5056  389.94
  5064.9  391.86  5121.7  394.61  5144.6  396.48  5160.2   396.8    5166  394.73
  5181.6  393.29    5203  394.78  5224.4   397.5  5239.9  398.19  5245.7  401.11
  5319.7  403.93  5325.5  400.61  5335.2  400.43  5345.1   402.7  5348.6   402.7
#Mann= 5 ,-1 , 0
  4280.3     .05       0  4829.7     .16       0  4994.8     .07       0
  5000.8     .16       0  5121.7     .05       0
Bank Sta=4994.8,5000.8
XS Rating Curve= 0 ,0
Exp/Cntr=0.3,0.1

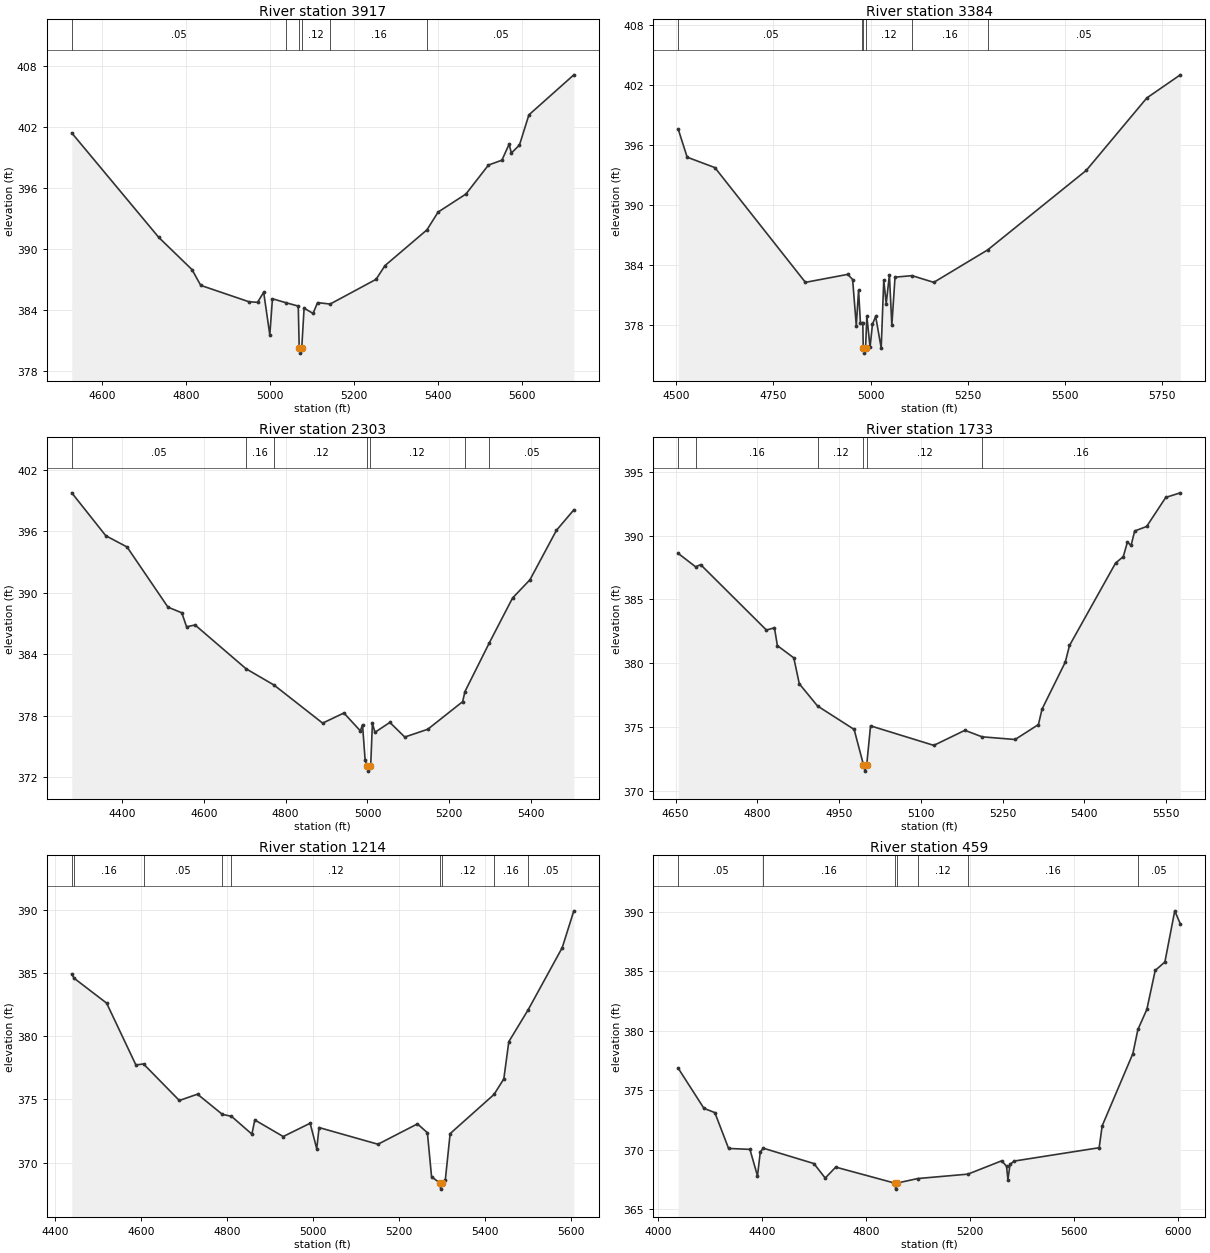
Type RM Length L Ch R = 1 ,3917    ,533,533,533
BEGIN DESCRIPTION:
UNT156 IN CCTC 5.0
END DESCRIPTION:
XS GIS Cut Line= 3
      3548699.62     10629960.21      3548399.61     10629560.19
      3547749.65      10629310.2
#Sta/Elev= 30
  4527.9  401.43  4735.2  391.15  4814.4  387.98  4835.2  386.43  4949.8  384.82
  4970.6  384.76  4985.2  385.75  4999.8  381.56  5006.1  385.11  5039.2  384.71
  5067.6  384.39  5069.9  380.26  5072.7  379.76  5075.9  380.26  5081.5  384.18
  5102.9  383.67  5113.6  384.73  5143.6  384.59  5252.9  387.02  5274.4  388.38
  5374.2  391.89  5400.8  393.64  5467.2  395.42  5520.8  398.27  5552.9  398.75
  5570.1  400.33  5575.4  399.45  5594.7  400.24  5617.2  403.21  5724.3  407.15
#Mann= 6 ,-1 , 0
  4527.9     .05       0  5039.2     .12       0  5069.9     .03       0
  5075.9     .12       0  5143.6     .16       0  5374.2     .05       0
Bank Sta=5069.9,5075.9
XS Rating Curve= 0 ,0
Exp/Cntr=0.3,0.1

Type RM Length L Ch R = 1 ,3384    ,1081,1081,1081
BEGIN DESCRIPTION:
UNT156 IN CCTC 4.0
END DESCRIPTION:
XS GIS Cut Line= 3
      3548849.61     10629760.19      3548599.61     10629360.19
      3548099.59     10628710.16
#Sta/Elev= 30
  4504.9  397.59  4527.9  394.79  4599.2  393.75  4832.1  382.27  4941.2  383.07
  4953.6  382.55    4963  377.95  4968.9  381.48  4973.7  378.19  4978.9  378.19
  4979.8  378.19  4980.9  375.69  4983.6  375.19  4986.9  375.69  4990.2   378.9
  4998.4  375.77  5004.7   378.1  5012.9  378.86  5027.1   375.7  5033.7  382.49
    5040  380.14  5048.2  383.01  5054.5  377.97  5062.7  382.79  5106.5  382.94
  5162.4  382.27  5301.2  385.52  5554.7  393.47  5710.6  400.72  5796.7  403.03
#Mann= 6 ,-1 , 0
  4504.9     .05       0  4978.9     .12       0  4980.9     .07       0
  4986.9     .12       0  5106.5     .16       0  5301.2     .05       0
Bank Sta=4980.9,4986.9
XS Rating Curve= 0 ,0
Exp/Cntr=0.3,0.1

Type RM Length L Ch R = 1 ,2303    ,570,570,570
BEGIN DESCRIPTION:
UNT156 IN CCTC 2.0
END DESCRIPTION:
XS GIS Cut Line= 3
      3549299.61     10629660.18      3549099.61     10628960.19
      3548799.61     10628560.19
#Sta/Elev= 30
  4276.8  399.76    4360  395.57    4412  394.47  4512.1  388.59  4545.9  388.04
  4557.6  386.67  4578.4  386.85  4703.1  382.57  4771.5  380.98  4890.4  377.26
  4942.4  378.25  4982.7   376.5  4987.9  377.11  4994.4  373.61  4999.2  373.07
    5002  372.57  5005.2  373.07  5007.9  373.07  5012.1  377.25  5018.3  376.36
  5054.8  377.33  5091.3   375.9  5147.5  376.66  5232.9  379.36  5238.4  380.34
  5297.9  385.09  5354.8  389.48  5397.5  391.27  5462.1  396.09  5504.8   398.1
#Mann= 7 ,-1 , 0
  4276.8     .05       0  4703.1     .16       0  4771.5     .12       0
  4999.2     .07       0  5005.2     .12       0  5238.4     .16       0
  5297.9     .05       0
Bank Sta=4999.2,5005.2
XS Rating Curve= 0 ,0
Exp/Cntr=0.3,0.1

Type RM Length L Ch R = 1 ,1733    ,519,519,519
BEGIN DESCRIPTION:
UNT156 IN CCTC 3.0
END DESCRIPTION:
XS GIS Cut Line= 3
      3549663.25     10629261.04      3549619.84     10628853.05
      3549285.63     10628466.75
#Sta/Elev= 30
  4654.8  388.61  4686.7  387.56  4695.9  387.73  4816.6   382.6  4831.3  382.78
  4836.7  381.38  4866.8  380.42  4876.9  378.39  4910.3  376.65  4977.5  374.81
  4994.6  372.04  4997.3  371.54  5000.6  372.04  5007.6  375.09  5123.7  373.56
  5180.7  374.74  5212.2  374.23  5272.8  374.02  5315.6  375.19  5322.2   376.4
  5364.9  380.09  5372.6  381.39  5457.1  387.85  5471.3  388.36  5478.8  389.49
  5485.6  389.24  5492.2  390.37  5514.1  390.72  5549.2     393  5575.9  393.36
#Mann= 6 ,-1 , 0
  4654.8     .05       0  4686.7     .16       0  4910.3     .12       0
  4994.6     .07       0  5000.6     .12       0  5212.2     .16       0
Bank Sta=4994.6,5000.6
XS Rating Curve= 0 ,0
Exp/Cntr=0.3,0.1

Type RM Length L Ch R = 1 ,1214    ,755,755,755
BEGIN DESCRIPTION:
Mapping XS e88f879d
END DESCRIPTION:
XS GIS Cut Line= 4
      3549886.48     10629176.92      3550014.08     10628804.53
      3549951.58     10628590.99      3549423.79     10628429.79
#Sta/Elev= 30
  4438.3  384.91  4443.7  384.58  4519.4  382.61  4587.5  377.72  4605.2   377.8
  4688.5  374.91  4730.8  375.41  4788.7  373.81  4809.8  373.66  4857.3  372.25
  4864.1  373.37  4930.2  372.06  4992.8  373.11  5008.2  371.09  5013.6  372.77
  5150.6  371.45  5242.5  373.06  5265.6  372.36  5275.3  368.88    5294   368.4
  5296.7   367.9    5300   368.4  5307.4  368.66  5318.5  372.29  5420.7  375.39
  5443.4  376.62    5455  379.56  5500.3   382.1  5579.3     387  5606.3  389.91
#Mann= 9 ,-1 , 0
  4438.3     .05       0  4443.7     .16       0  4605.2     .05       0
  4788.7     .16       0  4809.8     .12       0    5294     .07       0
    5300     .12       0  5420.7     .16       0  5500.3     .05       0
Bank Sta=5294,5300
XS Rating Curve= 0 ,0
Exp/Cntr=0.3,0.1

Type RM Length L Ch R = 1 ,459     ,404,404,404
BEGIN DESCRIPTION:
Mapping XS 0d27e1cd
END DESCRIPTION:
XS GIS Cut Line= 4
      3550118.07     10628920.71      3550437.08     10628165.51
      3550335.08     10628041.81      3549449.68     10628386.85
#Sta/Elev= 30
  4078.3  376.85  4177.1  373.48  4219.1  373.12  4271.9  370.11  4353.9  370.03
    4383   367.8  4393.7  369.81  4405.3  370.13  4599.9  368.84  4643.4  367.62
  4683.8  368.54  4911.6  367.19  4914.4  366.69  4917.6  367.19  4999.4  367.58
  5192.2  367.95  5321.9  369.07  5340.6  368.61  5345.9  367.48  5354.1  368.78
  5370.4  369.05  5696.7  370.17  5708.3  372.01  5826.3  378.08  5845.7  380.11
    5880  381.79  5912.2  385.07  5949.4  385.78  5987.3  390.08  6008.7  388.98
#Mann= 7 ,-1 , 0
  4078.3     .05       0  4405.3     .16       0  4911.6     .07       0
  4917.6     .16       0  4999.4     .12       0  5192.2     .16       0
  5845.7     .05       0
Bank Sta=4911.6,4917.6
XS Rating Curve= 0 ,0
Exp/Cntr=0.3,0.1

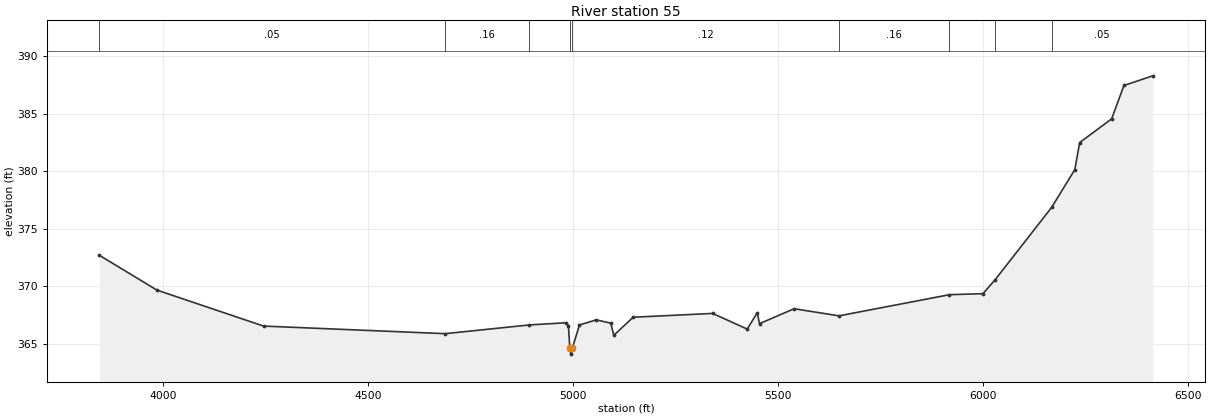
Type RM Length L Ch R = 1 ,55      ,0,0,0
BEGIN DESCRIPTION:
UNT156 IN CCTC 1.0
END DESCRIPTION:
XS GIS Cut Line= 4
      3550701.83     10628970.59      3550734.39     10627876.88
      3550610.69      10627846.5      3549353.27     10628332.12
#Sta/Elev= 30
  3844.8  372.69  3985.3  369.66  4245.4  366.53  4688.3  365.87    4894  366.63
    4984  366.82  4989.1  366.53  4992.4  364.59  4995.1  364.09  4998.4  364.59
    5016  366.63  5057.2  367.07  5092.4  366.78  5099.7  365.73    5147   367.3
  5340.6  367.63  5425.1  366.27  5449.7  367.69  5455.1  366.74  5539.6  368.04
  5648.8  367.42  5918.4  369.26  6000.2  369.35    6030  370.57  6167.8  376.86
  6224.2  380.14    6236  382.49  6314.1  384.56    6344  387.46  6414.3   388.3
#Mann= 9 ,-1 , 0
  3844.8     .05       0  4688.3     .16       0    4894     .12       0
  4992.4     .07       0  4998.4     .12       0  5648.8     .16       0
  5918.4     .12       0    6030     .16       0  6167.8     .05       0
Bank Sta=4992.4,4998.4
XS Rating Curve= 0 ,0
Exp/Cntr=0.3,0.1

Chan Stop Cuts=-1
Use User Specified Reach Order=0
Composite Channel Slope=5