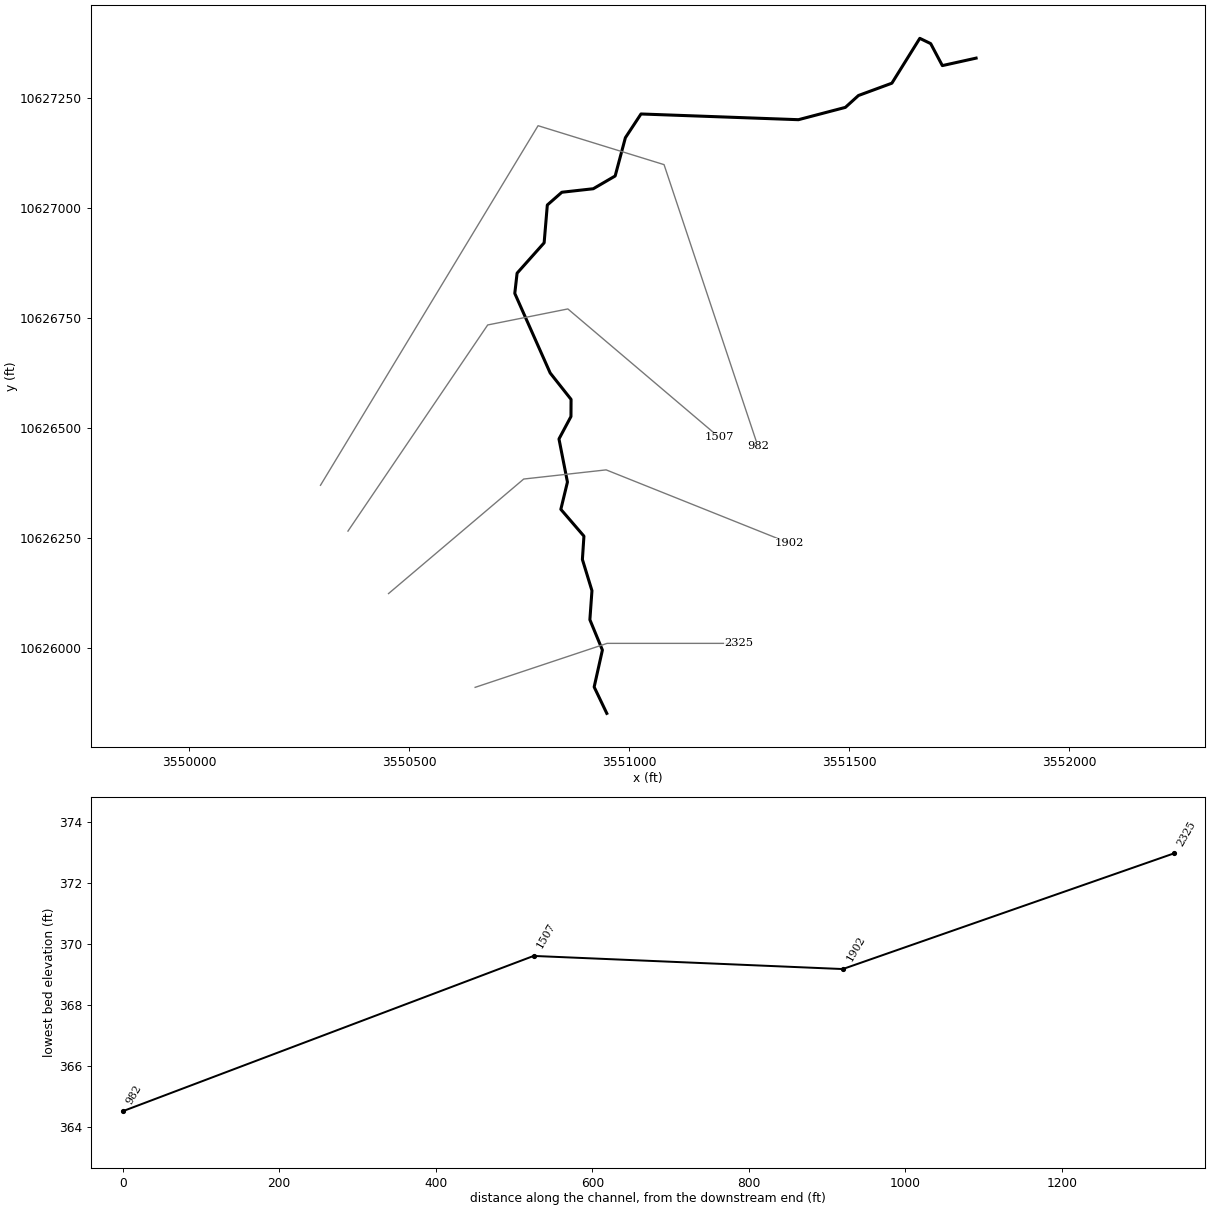
--- UNT157 IN CCTC.prj (project) ---

Proj Title=UNT157 IN CCTC Base Level Engineering
Current Plan=p01
Default Exp/Contr=0.3,0.1
English Units
Geom File=g01
Flow File=f01
Plan File=p01
Y Axis Title=Elevation
X Axis Title(PF)=Main Channel Distance
X Axis Title(XS)=Station
BEGIN DESCRIPTION:
UNT157 IN CCTC
END DESCRIPTION:
DSS Export Rating Curves= 0
DSS Export Rating Curve Sorted= 0
DSS Export Volume Flow Curves= 0
DXF OffsetX= 0
DXF OffsetY= 0
DXF ScaleX= 1
DXF ScaleY= 10

--- UNT157 IN CCTC.p01 (plan) ---

Plan Title=Multiple Run
Short Identifier=Multiple
Geom File=g01
Flow File=f01
Subcritical Flow
K Sum by GR= 0
Std Step Tol= 0.01
Critical Tol= 0.01
Num of Std Step Trials= 20
Max Error Tol= 0.3
Flow Tol Ratio= 0.001
Split Flow NTrial= 30
Split Flow Tol= 0.02
Split Flow Ratio= 0.02
Log Output Level= 0
Friction Slope Method= 1
Unsteady Friction Slope Method= 2
Unsteady Bridges Friction Slope Method= 1
Parabolic Critical Depth
Global Vel Dist=  1 , 1 , 1
Global Log Level= 0
CheckData=True
Encroach Param= -1, 0, 0, 0
BEGIN DESCRIPTION:
Multiple Run
END DESCRIPTION:

--- UNT157 IN CCTC.f01 (steady flow) ---

Flow Title=Multiple
Number of Profiles=7
Profile Names=10-year,25-year,50-year,1pct_min,100-year,1pct_plu,500-year
River Rch & RM= UNT157 IN CCTC,Reach-1,2325
    1143    1557    1897    1689    2285    3090    3298
Boundary for River Rch & Prof#=UNT157 IN CCTC,Reach-1,1
Up Type=0
Dn Type=3
Dn Slope=0.005
Boundary for River Rch & Prof#=UNT157 IN CCTC,Reach-1,2
Up Type=0
Dn Type=3
Dn Slope=0.005
Boundary for River Rch & Prof#=UNT157 IN CCTC,Reach-1,3
Up Type=0
Dn Type=3
Dn Slope=0.005
Boundary for River Rch & Prof#=UNT157 IN CCTC,Reach-1,4
Up Type=0
Dn Type=3
Dn Slope=0.005
Boundary for River Rch & Prof#=UNT157 IN CCTC,Reach-1,5
Up Type=0
Dn Type=3
Dn Slope=0.005
Boundary for River Rch & Prof#=UNT157 IN CCTC,Reach-1,6
Up Type=0
Dn Type=3
Dn Slope=0.005
Boundary for River Rch & Prof#=UNT157 IN CCTC,Reach-1,7
Up Type=0
Dn Type=3
Dn Slope=0.005

--- UNT157 IN CCTC.g01 (geometry) ---

Geom Title=Existing Conditions
Program Version=4.10

River Reach=UNT157 IN CCTC  ,Reach-1
Reach XY= 30
        3550949.       10625851.      3550920.25       10625911.
        3550939.       10625995.       3550910.5       10626064.
      3550915.25       10626130.       3550893.5       10626201.
        3550897.       10626254.       3550844.5       10626315.
       3550859.5       10626377.      3550840.25       10626475.
       3550867.5       10626526.      3550867.75       10626565.
      3550820.25       10626625.      3550739.75       10626806.
        3550745.       10626852.       3550806.5       10626921.
      3550813.75       10627007.      3550846.75       10627036.
      3550918.25       10627044.        3550968.       10627073.
      3550991.25       10627160.      3551026.75       10627214.
      3551384.75       10627201.       3551491.5       10627229.
      3551521.25       10627256.      3551597.25       10627284.
      3551660.75       10627386.       3551685.5       10627374.
        3551712.       10627324.      3551788.75       10627341.

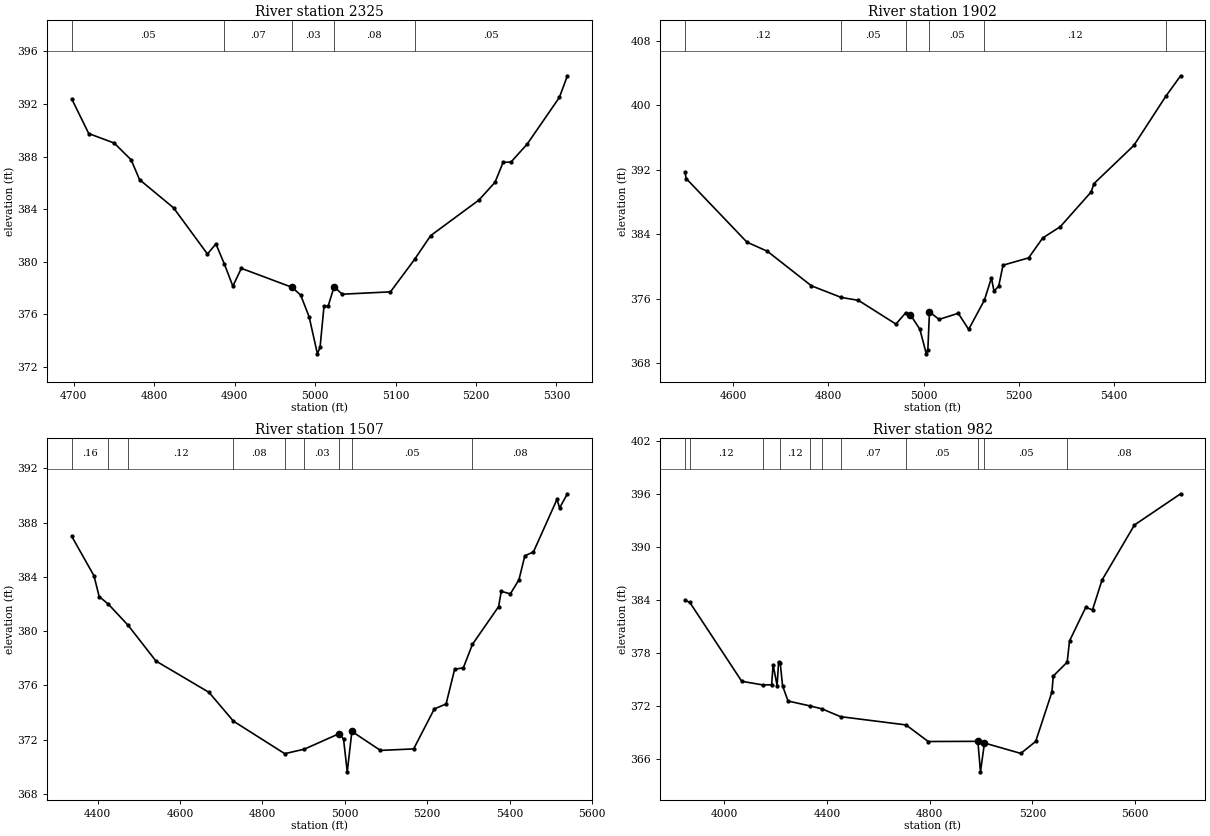
Type RM Length L Ch R = 1 ,2325    ,423,423,423
BEGIN DESCRIPTION:
UNT157 IN CCTC 3.0
END DESCRIPTION:
XS GIS Cut Line= 3
      3550649.61     10625910.19      3550949.61     10626010.19
      3551249.58     10626010.19
#Sta/Elev= 30
  4697.5  392.39  4718.6  389.75  4750.2  389.03  4771.3  387.75  4781.8  386.24
    4824   384.1  4866.2  380.58  4876.7  381.35  4887.2  379.82  4897.8  378.13
  4908.3  379.49  4971.6  378.04  4982.1  377.45  4992.6   375.8  5002.9  372.98
  5006.2  373.48  5011.1  376.61  5016.2  376.61  5023.7  378.09  5033.7  377.52
  5093.7   377.7  5123.7  380.17  5143.7  381.98  5203.7  384.69  5223.7  386.04
  5233.7  387.55  5243.7  387.59  5263.7  388.95  5303.7   392.5  5313.7  394.15
#Mann= 5 ,-1 , 0
  4697.5     .05       0  4887.2     .07       0  4971.6     .03       0
  5023.7     .08       0  5123.7     .05       0
Bank Sta=4971.6,5023.7
XS Rating Curve= 0 ,0
Exp/Cntr=0.3,0.1

Type RM Length L Ch R = 1 ,1902    ,395,395,395
BEGIN DESCRIPTION:
UNT157 IN CCTC 2.0
END DESCRIPTION:
XS GIS Cut Line= 4
       3550452.7     10626123.43      3550760.02     10626383.87
      3550947.52      10626404.7      3551364.14     10626238.06
#Sta/Elev= 30
  4499.3  391.68  4501.9  390.92  4629.3  383.04  4672.2  381.91  4764.5  377.63
    4827  376.19  4863.3  375.82    4942  372.88  4962.1  374.25  4972.1  374.06
  4992.3  372.23  5005.7  369.19    5009  369.69  5012.4  374.39  5032.5  373.46
  5072.8  374.22  5094.6  372.22  5127.7  375.85  5142.4  378.61  5147.8  376.97
  5157.7  377.58  5166.7  380.18  5220.5  381.09  5250.1  383.56  5286.9  384.95
  5351.5  389.25  5357.8  390.31  5441.3  395.03  5508.3  401.12  5539.5  403.67
#Mann= 6 ,-1 , 0
  4499.3     .12       0    4827     .05       0  4962.1     .03       0
  5012.4     .05       0  5127.7     .12       0  5508.3     .12       0
Bank Sta=4972.1,5012.4
XS Rating Curve= 0 ,0
Exp/Cntr=0.3,0.1

Type RM Length L Ch R = 1 ,1507    ,525,525,525
BEGIN DESCRIPTION:
Mapping XS e5819589
END DESCRIPTION:
XS GIS Cut Line= 4
      3550360.43     10626265.47      3550678.14     10626734.22
      3550860.43     10626770.68      3551204.19       10626479.
#Sta/Elev= 30
  4337.4  386.98  4391.4  384.07  4403.9  382.54    4426  381.99  4474.3  380.42
  4541.7  377.79  4670.5  375.48  4729.7  373.36  4854.3  370.96  4901.7  371.29
  4986.8  372.44    4997  372.04  5006.1  369.62  5017.3   372.6  5086.6   371.2
  5167.2  371.31  5217.4  374.26  5245.9  374.62  5266.8  377.19  5287.7  377.28
  5309.9  379.02  5373.4   381.8  5379.9  382.93  5401.9  382.74  5422.8  383.78
  5437.1  385.55  5457.9  385.83    5515   389.7  5521.6  389.08  5540.4  390.12
#Mann= 9 ,-1 , 0
  4337.4     .16       0    4426     .12       0  4474.3     .12       0
  4729.7     .08       0  4854.3     .07       0  4901.7     .03       0
  4986.8     .01       0  5017.3     .05       0  5309.9     .08       0
Bank Sta=4986.8,5017.3
XS Rating Curve= 0 ,0
Exp/Cntr=0.3,0.1

Type RM Length L Ch R = 1 ,982     ,0,0,0
BEGIN DESCRIPTION:
UNT157 IN CCTC 1.0
END DESCRIPTION:
XS GIS Cut Line= 4
      3550297.94     10626369.65      3550792.72     10627187.34
      3551079.18      10627098.8      3551292.71     10626458.22
#Sta/Elev= 30
  3846.9  383.99  3865.6  383.75    4068   374.8  4149.6  374.39  4184.4   374.4
  4190.2  376.67  4205.7  374.32  4211.6  376.98  4217.9  376.86  4227.1  374.27
  4248.4  372.56  4335.3     372  4380.9  371.67  4452.7  370.79  4708.2  369.85
  4794.3  367.97  4987.8  367.99    4998  364.53  5013.5   367.8  5155.1  366.62
  5213.1  367.98  5276.3  373.58  5281.6   375.4  5335.7  376.97  5344.9  379.38
  5408.1  383.19  5434.4   382.9  5471.3  386.27  5597.8  392.53  5777.7  396.07
#Mann= 11 ,-1 , 0
  3846.9     .16       0  3865.6     .12       0  4149.6     .16       0
  4217.9     .12       0  4335.3     .12       0  4380.9     .08       0
  4452.7     .07       0  4708.2     .05       0  4987.8     .03       0
  5013.5     .05       0  5335.7     .08       0
Bank Sta=4987.8,5013.5
XS Rating Curve= 0 ,0
Exp/Cntr=0.3,0.1

Chan Stop Cuts=-1
Use User Specified Reach Order=0
Composite Channel Slope=5