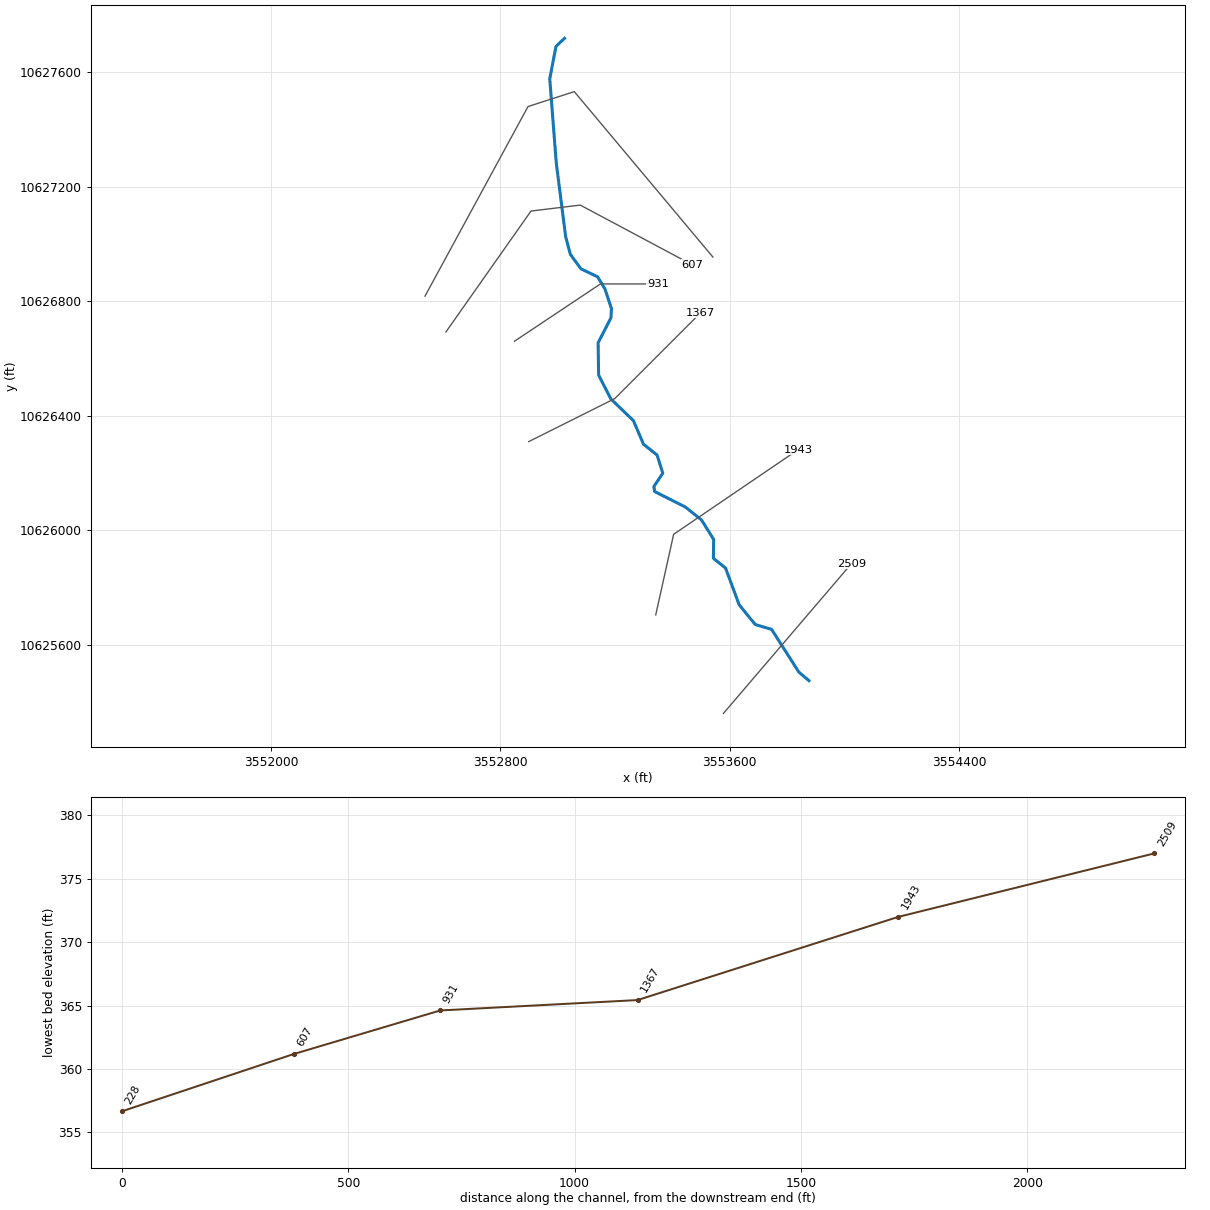
--- UNT158 IN CCTC.prj (project) ---

Proj Title=UNT158 IN CCTC Base Level Engineering
Current Plan=p01
Default Exp/Contr=0.3,0.1
English Units
Geom File=g01
Flow File=f01
Plan File=p01
Y Axis Title=Elevation
X Axis Title(PF)=Main Channel Distance
X Axis Title(XS)=Station
BEGIN DESCRIPTION:
UNT158 IN CCTC
END DESCRIPTION:
DSS Export Rating Curves= 0
DSS Export Rating Curve Sorted= 0
DSS Export Volume Flow Curves= 0
DXF OffsetX= 0
DXF OffsetY= 0
DXF ScaleX= 1
DXF ScaleY= 10

--- UNT158 IN CCTC.p01 (plan) ---

Plan Title=Multiple Run
Short Identifier=Multiple
Geom File=g01
Flow File=f01
Subcritical Flow
K Sum by GR= 0
Std Step Tol= 0.01
Critical Tol= 0.01
Num of Std Step Trials= 20
Max Error Tol= 0.3
Flow Tol Ratio= 0.001
Split Flow NTrial= 30
Split Flow Tol= 0.02
Split Flow Ratio= 0.02
Log Output Level= 0
Friction Slope Method= 1
Unsteady Friction Slope Method= 2
Unsteady Bridges Friction Slope Method= 1
Parabolic Critical Depth
Global Vel Dist=  1 , 1 , 1
Global Log Level= 0
CheckData=True
Encroach Param= -1, 0, 0, 0
BEGIN DESCRIPTION:
Multiple Run
END DESCRIPTION:

--- UNT158 IN CCTC.f01 (steady flow) ---

Flow Title=Multiple
Number of Profiles=7
Profile Names=10-year,25-year,50-year,1pct_min,100-year,1pct_plu,500-year
River Rch & RM= UNT158 IN CCTC,Reach-1,2509
    1156    1582    1933    1728    2337    3160    3398
Boundary for River Rch & Prof#=UNT158 IN CCTC,Reach-1,1
Up Type=0
Dn Type=3
Dn Slope=0.005
Boundary for River Rch & Prof#=UNT158 IN CCTC,Reach-1,2
Up Type=0
Dn Type=3
Dn Slope=0.005
Boundary for River Rch & Prof#=UNT158 IN CCTC,Reach-1,3
Up Type=0
Dn Type=3
Dn Slope=0.005
Boundary for River Rch & Prof#=UNT158 IN CCTC,Reach-1,4
Up Type=0
Dn Type=3
Dn Slope=0.005
Boundary for River Rch & Prof#=UNT158 IN CCTC,Reach-1,5
Up Type=0
Dn Type=3
Dn Slope=0.005
Boundary for River Rch & Prof#=UNT158 IN CCTC,Reach-1,6
Up Type=0
Dn Type=3
Dn Slope=0.005
Boundary for River Rch & Prof#=UNT158 IN CCTC,Reach-1,7
Up Type=0
Dn Type=3
Dn Slope=0.005

--- UNT158 IN CCTC.g01 (geometry) ---

Geom Title=Existing Conditions
Program Version=4.10

River Reach=UNT158 IN CCTC  ,Reach-1
Reach XY= 30
        3553877.       10625476.      3553841.75       10625506.
      3553746.75       10625655.       3553689.5       10625672.
       3553633.5       10625741.        3553586.       10625869.
      3553543.75       10625903.       3553544.5       10625969.
        3553502.       10626037.      3553445.75       10626082.
       3553338.5       10626136.        3553336.       10626153.
        3553367.       10626200.      3553347.25       10626263.
      3553299.75       10626301.      3553264.75       10626383.
        3553186.       10626459.      3553143.25       10626542.
       3553141.5       10626655.      3553186.25       10626742.
        3553188.       10626774.      3553165.25       10626843.
      3553139.75       10626885.       3553081.5       10626913.
      3553044.75       10626963.      3553028.25       10627025.
       3552995.5       10627282.      3552972.75       10627576.
       3552994.5       10627689.      3553024.25       10627717.

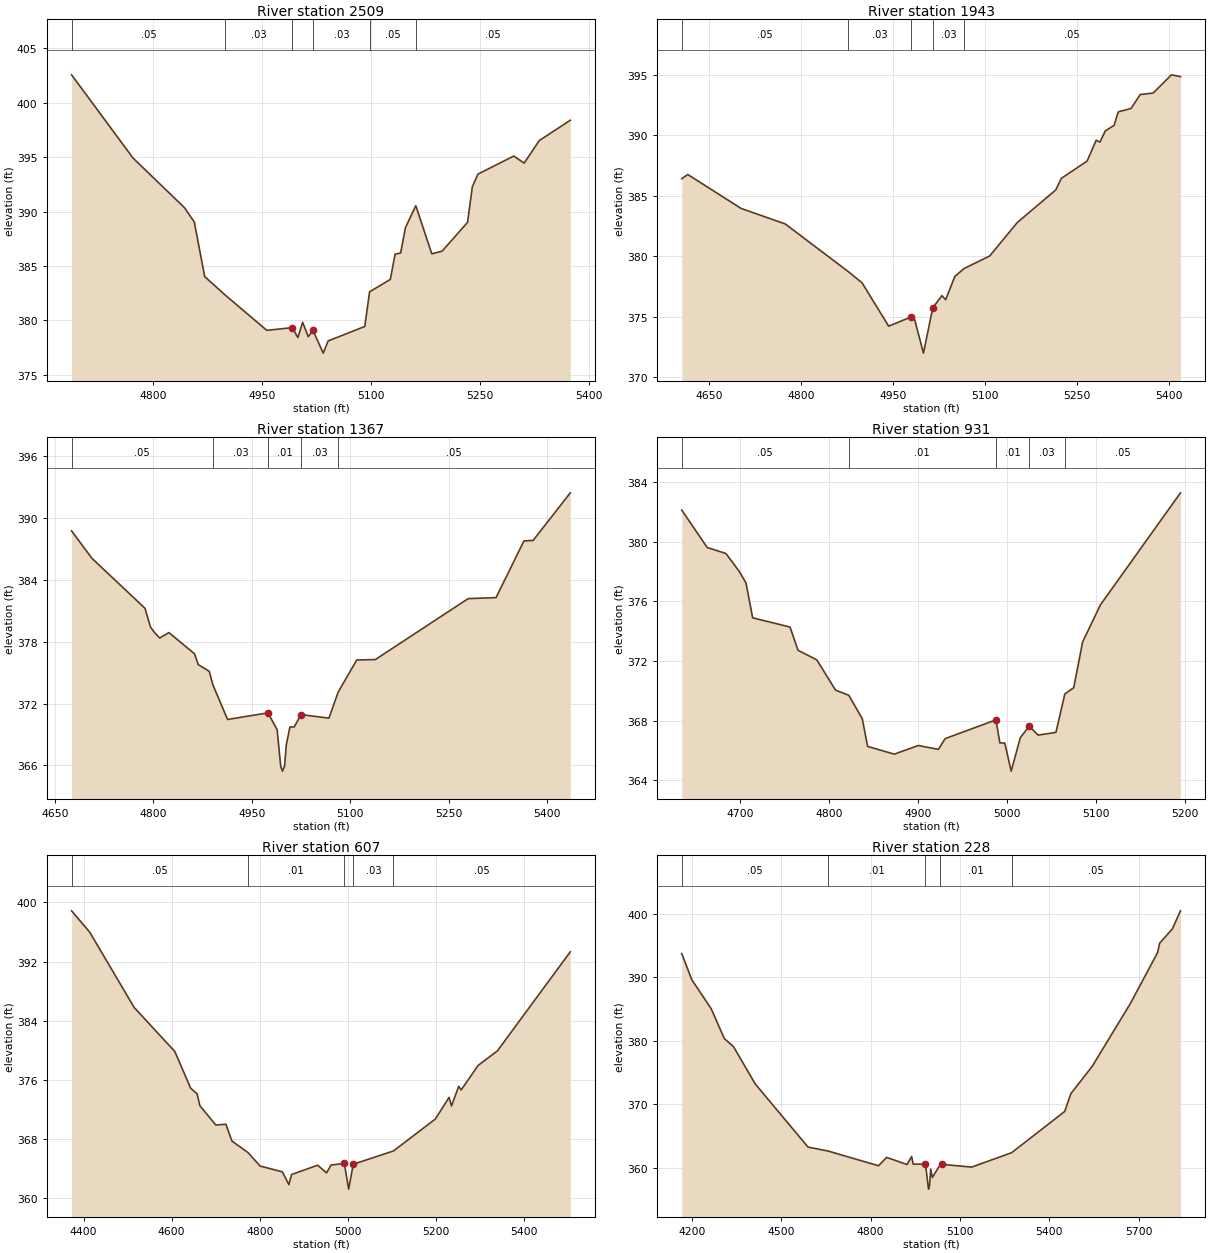
Type RM Length L Ch R = 1 ,2509    ,566,566,566
BEGIN DESCRIPTION:
UNT158 IN CCTC 4.0
END DESCRIPTION:
XS GIS Cut Line= 2
      3553578.72       10625362.      3554025.23     10625884.37
#Sta/Elev= 30
  4687.2  402.56  4771.8  394.92  4842.7  390.36  4856.3  389.04  4870.6  384.03
  4899.1  382.32  4956.2  379.09  4991.3  379.34    4999  378.43  5005.6  379.83
  5013.3  378.51  5019.9  379.08  5033.9     377  5040.7  378.12  5091.2  379.45
  5097.8  382.63  5126.4  383.77  5132.9  386.08  5140.6   386.2  5147.2  388.52
  5161.5  390.54  5183.5  386.12  5197.7  386.36  5232.8  389.01  5239.4  392.28
  5247.1  393.44  5296.5   395.1  5310.8  394.45  5331.6  396.52  5374.4  398.39
#Mann= 6 ,-1 , 0
  4687.2     .05       0  4899.1     .03       0  4991.3     .01       0
  5019.9     .03       0  5097.8     .05       0  5161.5     .05       0
Bank Sta=4991.3,5019.9
XS Rating Curve= 0 ,0
Exp/Cntr=0.3,0.1

Type RM Length L Ch R = 1 ,1943    ,576,576,576
BEGIN DESCRIPTION:
Mapping XS e620f343
END DESCRIPTION:
XS GIS Cut Line= 3
      3553342.49     10625705.51      3553404.98     10625986.74
      3553839.05      10626281.9
#Sta/Elev= 30
  4605.9  386.43  4615.7  386.77  4702.8  383.96  4774.6  382.68    4877  378.75
  4899.8  377.81  4943.2  374.22  4979.2  374.97  4985.2  374.83  4999.9  371.99
  5015.1  375.74    5030  376.75  5036.1  376.41    5051  378.33    5066  378.99
  5107.9  380.03  5152.7  382.79  5215.7   385.5  5224.6  386.45  5266.6  387.88
  5281.5  389.61  5287.5  389.45  5296.4  390.38  5310.7  390.84  5317.4  391.95
  5338.4  392.24  5353.3  393.39  5374.3  393.51  5404.2  395.02  5418.9  394.87
#Mann= 5 ,-1 , 0
  4605.9     .05       0    4877     .03       0  4979.2     .01       0
  5015.1     .03       0    5066     .05       0
Bank Sta=4979.2,5015.1
XS Rating Curve= 0 ,0
Exp/Cntr=0.3,0.1

Type RM Length L Ch R = 1 ,1367    ,436,436,436
BEGIN DESCRIPTION:
UNT158 IN CCTC 3.0
END DESCRIPTION:
XS GIS Cut Line= 3
      3552899.59     10626310.18      3553199.61     10626460.19
      3553499.61     10626760.19
#Sta/Elev= 30
  4675.5  388.77  4706.3  386.12  4787.3  381.25  4795.7  379.43  4801.3  378.94
  4809.7  378.36  4823.7  378.89  4862.8  376.83  4868.4  375.78  4885.2  375.13
  4890.7  373.82  4913.1  370.45  4974.6  371.09  4988.6  369.46    4994  365.93
  4996.7  365.43    5000  365.93  5002.5  367.97  5008.1  369.72  5014.5  369.72
  5025.1  370.92  5067.5  370.58  5081.6  373.11  5109.9  376.23  5138.2  376.27
  5279.6  382.19  5322.1  382.29  5364.5  387.79  5378.6  387.85  5435.2  392.47
#Mann= 5 ,-1 , 0
  4675.5     .05       0  4890.7     .03       0  4974.6     .01       0
  5025.1     .03       0  5081.6     .05       0
Bank Sta=4974.6,5025.1
XS Rating Curve= 0 ,0
Exp/Cntr=0.3,0.1

Type RM Length L Ch R = 1 ,931     ,324,324,324
BEGIN DESCRIPTION:
UNT158 IN CCTC 2.0
END DESCRIPTION:
XS GIS Cut Line= 3
      3552849.58     10626660.17      3553149.61     10626860.19
      3553349.61     10626860.19
#Sta/Elev= 30
  4634.2  382.13  4662.8  379.62  4683.8  379.22  4698.8  378.02  4706.4  377.24
  4713.9   374.9  4755.9  374.28  4764.9  372.72    4786  372.08    4807  370.05
    4822   369.7  4837.1  368.13  4843.1  366.27  4873.1  365.75  4900.1  366.33
  4922.7  366.07  4930.2  366.79  4987.3  368.05  4991.8   366.5  4997.3   366.5
  5004.5  364.61  5014.8  366.86  5024.8  367.62  5034.8  367.03  5054.8  367.21
  5064.8  369.79  5074.8  370.21  5084.8  373.28  5104.8  375.77  5194.8  383.29
#Mann= 5 ,-1 , 0
  4634.2     .05       0    4822     .01       0  4987.3     .01       0
  5024.8     .03       0  5064.8     .05       0
Bank Sta=4987.3,5024.8
XS Rating Curve= 0 ,0
Exp/Cntr=0.3,0.1

Type RM Length L Ch R = 1 ,607     ,379,379,379
BEGIN DESCRIPTION:
Mapping XS f770797e
END DESCRIPTION:
XS GIS Cut Line= 4
      3552610.43     10626692.55      3552907.31     10627114.43
      3553079.18     10627135.26      3553469.81     10626926.93
#Sta/Elev= 30
  4372.9  398.87  4413.9  395.99  4514.9  385.78  4607.3   379.8    4643  374.85
  4657.8  374.07  4663.9  372.48  4700.2  369.85  4723.1  369.96  4736.8  367.68
  4773.5  366.11  4800.6   364.3  4851.2  363.51    4866  361.78  4872.1  363.15
  4931.4  364.41  4951.5  363.37  4961.6  364.43  4991.8  364.65  5001.6  361.17
    5012  364.54  5103.3  366.34  5198.4  370.67  5229.4   373.6    5235  372.43
  5251.3   375.1    5257  374.61  5295.3  377.92  5339.2   379.9  5504.6  393.32
#Mann= 5 ,-1 , 0
  4372.9     .05       0  4773.5     .01       0  4991.8     .01       0
    5012     .03       0  5103.3     .05       0
Bank Sta=4991.8,5012
XS Rating Curve= 0 ,0
Exp/Cntr=0.3,0.1

Type RM Length L Ch R = 1 ,228     ,0,0,0
BEGIN DESCRIPTION:
UNT158 IN CCTC 1.0
END DESCRIPTION:
XS GIS Cut Line= 4
      3552537.53     10626817.58      3552896.89     10627479.01
      3553058.35     10627531.09      3553541.81     10626954.06
#Sta/Elev= 30
  4165.8  393.76  4199.4  389.65    4265  385.04  4308.7  380.37  4339.5  379.11
  4412.2  373.25  4589.9  363.28  4657.4  362.66  4826.6  360.34  4854.1  361.66
  4922.6  360.53  4937.9   361.8  4943.2   360.6  4984.4   360.6  4994.7  356.66
    4998  357.16    5002  359.82  5007.3  358.49  5034.1  360.51  5039.3  360.56
  5139.9  360.13  5273.9   362.4  5452.1  368.89  5472.9   371.7  5544.5     376
    5672  385.84  5764.4  393.93  5770.9  395.39  5813.8  397.65    5841  400.49
#Mann= 5 ,-1 , 0
  4165.8     .05       0  4657.4     .01       0  4984.4     .01       0
  5034.1     .01       0  5273.9     .05       0
Bank Sta=4984.4,5039.3
XS Rating Curve= 0 ,0
Exp/Cntr=0.3,0.1

Chan Stop Cuts=-1
Use User Specified Reach Order=0
Composite Channel Slope=5