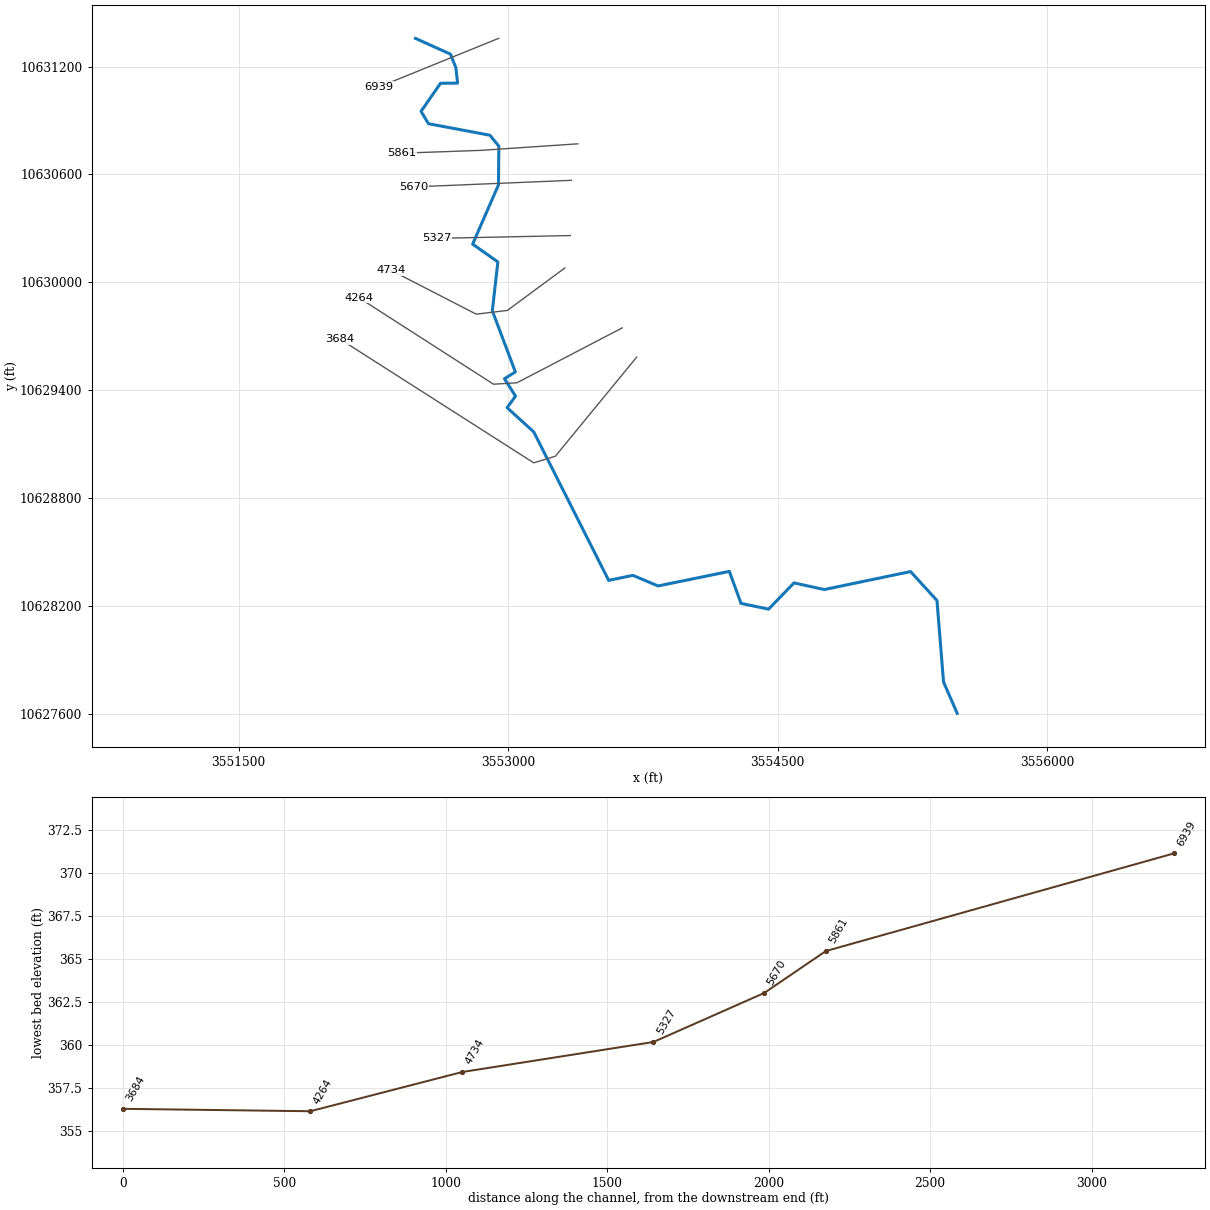
--- UNT159 IN CCTC.prj (project) ---

Proj Title=UNT159 IN CCTC Base Level Engineering
Current Plan=p01
Default Exp/Contr=0.3,0.1
English Units
Geom File=g01
Flow File=f01
Plan File=p01
BEGIN DESCRIPTION:
UNT159 IN CCTC
END DESCRIPTION:

--- UNT159 IN CCTC.p01 (plan) ---

Plan Title=Multiple Run
Short Identifier=Multiple
Geom File=g01
Flow File=f01
Subcritical Flow
K Sum by GR= 0
Std Step Tol= 0.01
Critical Tol= 0.01
Num of Std Step Trials= 20
Max Error Tol= 0.3
Flow Tol Ratio= 0.001
Split Flow NTrial= 30
Split Flow Tol= 0.02
Split Flow Ratio= 0.02
Log Output Level= 0
Friction Slope Method= 1
Unsteady Friction Slope Method= 2
Unsteady Bridges Friction Slope Method= 1
Parabolic Critical Depth
Global Vel Dist=  1 , 1 , 1
Global Log Level= 0
CheckData=True
Encroach Param= -1, 0, 0, 0
BEGIN DESCRIPTION:
Multiple Run
END DESCRIPTION:

--- UNT159 IN CCTC.f01 (steady flow) ---

Flow Title=Multiple
Number of Profiles=7
Profile Names=10-year,25-year,50-year,1pct_min,100-year,1pct_plu,500-year
River Rch & RM= UNT159 IN CCTC,Reach-1,6939
    1471    2016    2464    2196    2970    4017    4301
Boundary for River Rch & Prof#=UNT159 IN CCTC,Reach-1,1
Up Type=0
Dn Type=3
Dn Slope=0.005
Boundary for River Rch & Prof#=UNT159 IN CCTC,Reach-1,2
Up Type=0
Dn Type=3
Dn Slope=0.005
Boundary for River Rch & Prof#=UNT159 IN CCTC,Reach-1,3
Up Type=0
Dn Type=3
Dn Slope=0.005
Boundary for River Rch & Prof#=UNT159 IN CCTC,Reach-1,4
Up Type=0
Dn Type=3
Dn Slope=0.005
Boundary for River Rch & Prof#=UNT159 IN CCTC,Reach-1,5
Up Type=0
Dn Type=3
Dn Slope=0.005
Boundary for River Rch & Prof#=UNT159 IN CCTC,Reach-1,6
Up Type=0
Dn Type=3
Dn Slope=0.005
Boundary for River Rch & Prof#=UNT159 IN CCTC,Reach-1,7
Up Type=0
Dn Type=3
Dn Slope=0.005

--- UNT159 IN CCTC.g01 (geometry) ---

Geom Title=Existing Conditions

River Reach=UNT159 IN CCTC,Reach-1
Reach XY= 30
      3552484.55     10631356.76      3552679.50     10631269.00
      3552709.75     10631192.00      3552718.50     10631108.00
      3552624.00     10631107.00      3552515.50     10630951.00
      3552556.75     10630882.00      3552898.50     10630818.00
      3552948.50     10630757.00      3552946.25     10630541.00
      3552802.50     10630212.00      3552943.00     10630113.00
      3552912.25     10629841.00      3553040.25     10629501.00
      3552980.00     10629463.00      3553041.25     10629366.00
      3552994.25     10629302.00      3553142.75     10629167.00
      3553559.50     10628341.00      3553694.25     10628369.00
      3553834.25     10628310.00      3554231.00     10628391.00
      3554296.00     10628213.00      3554449.25     10628181.00
      3554590.75     10628327.00      3554759.50     10628290.00
      3555239.50     10628390.00      3555386.25     10628229.00
      3555422.75     10627776.00      3555498.75     10627601.00

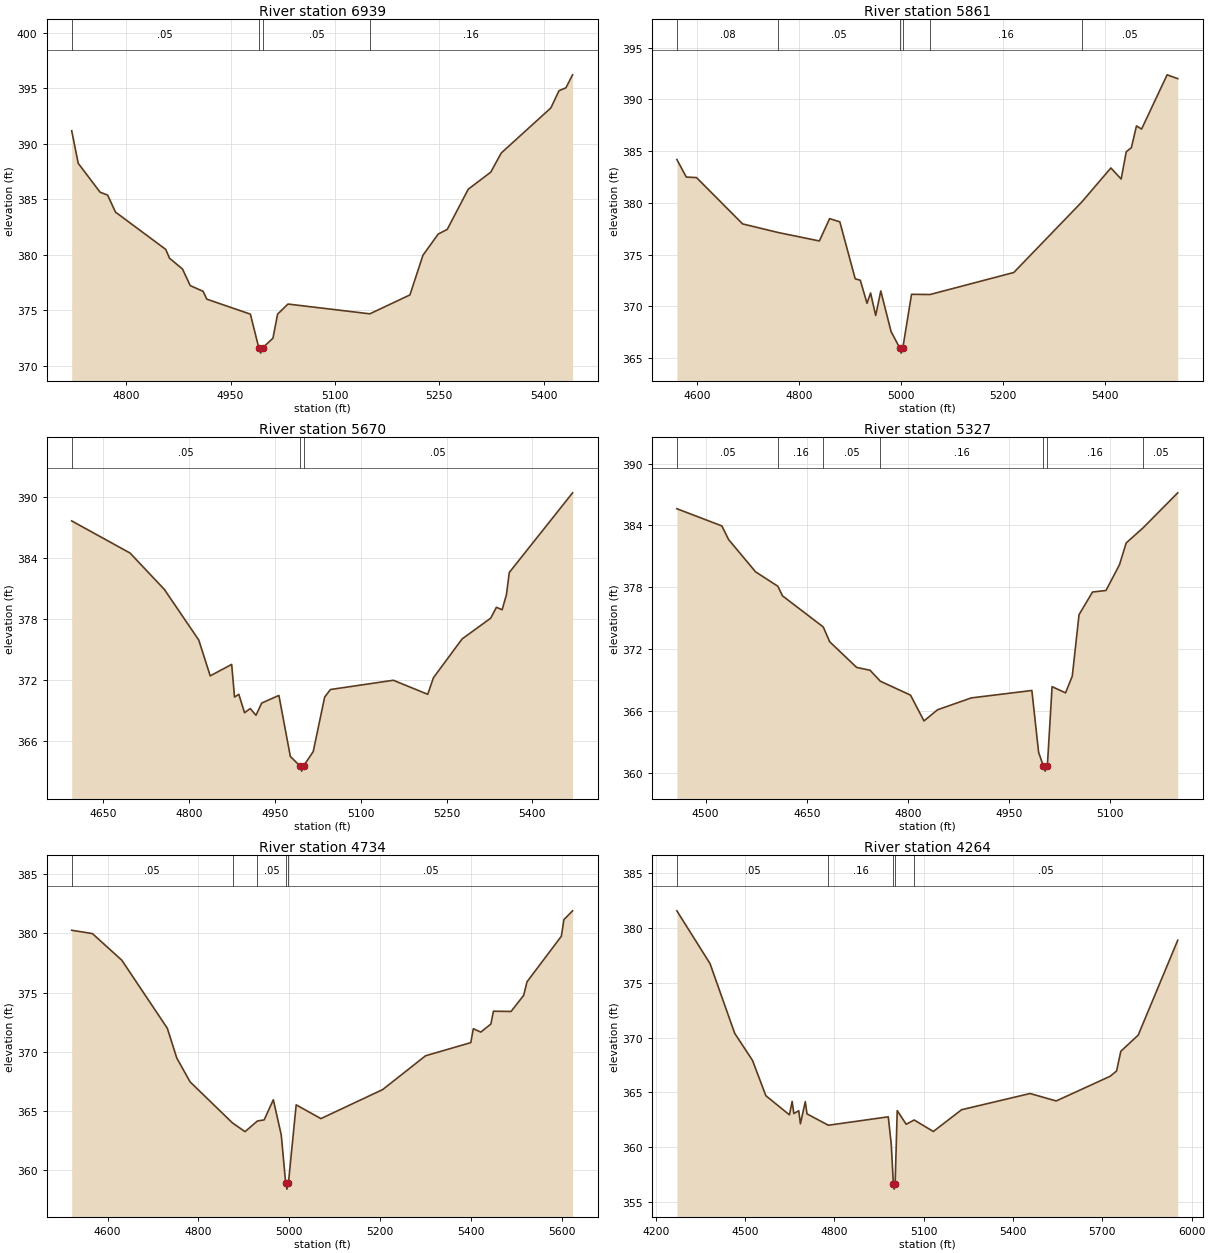
Type RM Length L Ch R = 1,6939,1078,1078,1078
BEGIN DESCRIPTION:
UNT159 IN CCTC 7.0
END DESCRIPTION:
XS GIS Cut Line= 2
      3552947.42     10631357.02      3552280.74     10631086.18
#Sta/Elev= 30
  4721.8  391.16  4731.2  388.23  4762.6  385.63  4773.4  385.37  4784.7  383.84
  4856.9  380.48  4862.3  379.69  4881.0  378.71  4892.1  377.22  4910.5  376.71
  4915.9  376.00  4978.5  374.65  4990.5  371.64  4993.3  371.14  4996.5  371.64
  5010.9  372.48  5017.6  374.65  5032.5  375.56  5150.1  374.68  5207.7  376.38
  5226.4  379.95  5248.3  381.86  5261.3  382.28  5291.5  385.90  5323.9  387.44
  5338.9  389.16  5410.2  393.22  5421.9  394.77  5431.8  395.03  5441.4  396.20
#Mann=4,-1,0
  4721.8    0.05       0  4990.5    0.03       0  4996.5    0.05       0
  5150.1    0.16       0
Bank Sta=4990.5,4996.5
Exp/Cntr=0.3,0.1

Type RM Length L Ch R = 1,5861,191,191,191
BEGIN DESCRIPTION:
UNT159 IN CCTC 6.0
END DESCRIPTION:
XS GIS Cut Line= 3
      3553388.03     10630770.06      3552846.36     10630733.60
      3552408.83     10630717.98
#Sta/Elev= 30
  4561.1  384.19  4579.6  382.49  4599.6  382.44  4689.8  377.96  4760.1  377.12
  4840.1  376.31  4860.2  378.47  4880.2  378.16  4910.3  372.65  4920.3  372.51
  4933.4  370.28  4940.4  371.28  4950.4  369.10  4960.4  371.47  4980.5  367.55
  4997.5  365.96  5000.3  365.46  5003.5  365.96  5020.6  371.15  5056.8  371.13
  5220.8  373.26  5353.4  380.05  5410.9  383.37  5431.0  382.30  5441.0  384.94
  5451.0  385.33  5461.0  387.44  5471.0  387.13  5521.0  392.38  5541.8  392.01
#Mann=6,-1,0
  4561.1    0.08       0  4760.1    0.05       0  4997.5   0.035       0
  5003.5    0.05       0  5056.8    0.16       0  5353.4    0.05       0
Bank Sta=4997.5,5003.5
Exp/Cntr=0.3,0.1

Type RM Length L Ch R = 1,5670,343,343,343
BEGIN DESCRIPTION:
UNT159 IN CCTC 5.0
END DESCRIPTION:
XS GIS Cut Line= 2
      3553351.57     10630566.94      3552476.53     10630530.48
#Sta/Elev= 30
  4594.6  387.61  4696.7  384.45  4756.7  380.87  4816.8  375.90  4836.8  372.38
  4874.3  373.51  4879.3  370.30  4886.8  370.57  4896.8  368.76  4906.8  369.17
  4916.8  368.51  4926.8  369.71  4956.9  370.46  4976.9  364.46  4993.9  363.52
  4996.7  363.02  4999.9  363.52  5016.9  364.94  5036.9  370.30  5047.0  371.04
  5157.0  371.95  5217.1  370.57  5227.1  372.20  5277.2  376.01  5327.2  378.05
  5337.2  379.12  5347.2  378.88  5354.7  380.35  5359.7  382.54  5470.4  390.37
#Mann=3,-1,0
  4594.6    0.05       0  4993.9    0.03       0  4999.9    0.05       0
Bank Sta=4993.9,4999.9
Exp/Cntr=0.3,0.1

Type RM Length L Ch R = 1,5327,593,593,593
BEGIN DESCRIPTION:
UNT159 IN CCTC 4.0
END DESCRIPTION:
XS GIS Cut Line= 2
      3553346.38     10630259.65      3552603.14     10630244.05
#Sta/Elev= 30
  4457.3  385.62  4524.1  383.95  4534.1  382.63  4574.1  379.50  4607.2  378.10
  4614.1  377.17  4674.6  374.15  4684.1  372.72  4724.1  370.23  4744.1  369.95
  4759.3  368.89  4804.1  367.54  4824.1  365.04  4844.2  366.12  4894.2  367.27
  4984.2  367.99  4994.2  362.00  5001.2  360.67  5003.9  360.17  5007.2  360.67
  5014.2  368.36  5034.2  367.76  5044.2  369.39  5054.2  375.34  5074.2  377.54
  5094.2  377.69  5114.2  380.18  5124.2  382.30  5149.2  383.76  5200.7  387.16
#Mann=7,-1,0
  4457.3    0.05       0  4607.2    0.16       0  4674.6    0.05       0
  4759.3    0.16       0  5001.2    0.07       0  5007.2    0.16       0
  5149.2    0.05       0
Bank Sta=5001.2,5007.2
Exp/Cntr=0.3,0.1

Type RM Length L Ch R = 1,4734,470,470,470
BEGIN DESCRIPTION:
UNT159 IN CCTC 3.0
END DESCRIPTION:
XS GIS Cut Line= 4
      3553315.47     10630079.23      3552996.06     10629843.15
      3552822.44     10629822.31      3552350.36     10630065.30
#Sta/Elev= 30
  4521.1  380.26  4566.7  379.98  4631.5  377.73  4731.7  371.99  4752.5  369.48
  4781.8  367.47  4875.3  364.00  4902.8  363.27  4930.1  364.17  4944.9  364.26
  4965.1  365.96  4982.6  362.98  4992.3  358.92  4995.0  358.42  4998.3  358.92
  5015.4  365.53  5069.9  364.37  5205.9  366.82  5300.3  369.67  5399.9  370.78
  5405.5  371.95  5422.0  371.67  5444.2  372.35  5449.8  373.43  5488.6  373.41
  5516.4  374.77  5523.7  375.91  5599.4  379.76  5605.0  381.16  5624.1  381.90
#Mann=5,-1,0
  4521.1    0.05       0  4875.3    0.16       0  4930.1    0.05       0
  4992.3    0.03       0  4998.3    0.05       0
Bank Sta=4992.3,4998.3
Exp/Cntr=0.3,0.1

Type RM Length L Ch R = 1,4264,580,580,580
BEGIN DESCRIPTION:
UNT159 IN CCTC 2.0
END DESCRIPTION:
XS GIS Cut Line= 4
      3553634.93     10629745.92      3553049.01     10629440.37
      3552918.80     10629432.55      3552168.76     10629914.35
#Sta/Elev= 30
  4270.6  381.58  4382.0  376.76  4464.8  370.39  4524.7  367.91  4569.6  364.68
  4648.8  362.93  4657.9  364.16  4663.6  363.04  4680.0  363.31  4685.7  362.11
  4702.1  364.14  4707.8  363.02  4779.5  361.98  4980.9  362.75  4990.9  360.24
  4997.9  356.64  5000.7  356.14  5003.9  356.64  5010.9  363.32  5041.0  362.07
  5067.8  362.46  5132.2  361.41  5227.3  363.40  5457.2  364.88  5545.0  364.20
  5726.5  366.46  5747.8  366.94  5762.1  368.74  5820.5  370.22  5953.3  378.89
#Mann=5,-1,0
  4270.6    0.05       0  4779.5    0.16       0  4997.9    0.07       0
  5003.9    0.16       0  5067.8    0.05       0
Bank Sta=4997.9,5003.9
Exp/Cntr=0.3,0.1

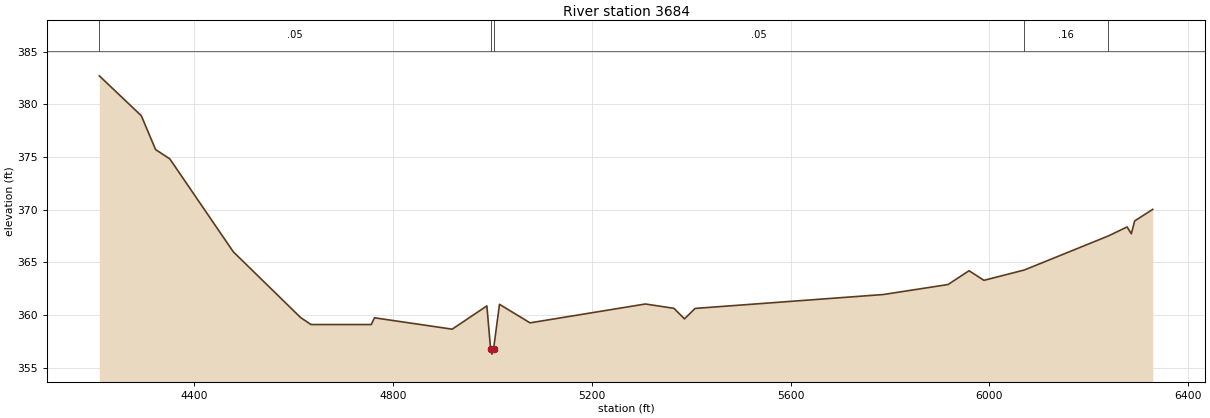
Type RM Length L Ch R = 1,3684,0,0,0
BEGIN DESCRIPTION:
UNT159 IN CCTC 1.0
END DESCRIPTION:
XS GIS Cut Line= 4
      3553715.67     10629583.59      3553262.55     10629031.51
      3553142.76     10628995.05      3552063.30     10629684.35
#Sta/Elev= 30
  4208.7  382.71  4293.2  378.92  4321.9  375.71  4350.6  374.82  4478.3  366.00
  4613.9  359.75  4634.8  359.09  4756.0  359.09  4762.5  359.73  4918.9  358.65
  4988.7  360.86  4996.2  356.78  4998.9  356.28  5002.2  356.78  5014.1  361.01
  5075.6  359.25  5307.7  361.04  5365.3  360.63  5386.4  359.63  5407.8  360.62
  5786.6  361.94  5916.9  362.89  5959.2  364.20  5989.2  363.29  6070.5  364.27
  6239.4  367.50  6277.3  368.36  6285.8  367.71  6292.5  368.93  6328.9  370.03
#Mann=5,-1,0
  4208.7    0.05       0  4996.2    0.03       0  5002.2    0.05       0
  6070.5    0.16       0  6239.4    0.12       0
Bank Sta=4996.2,5002.2
Exp/Cntr=0.3,0.1

Chan Stop Cuts=-1