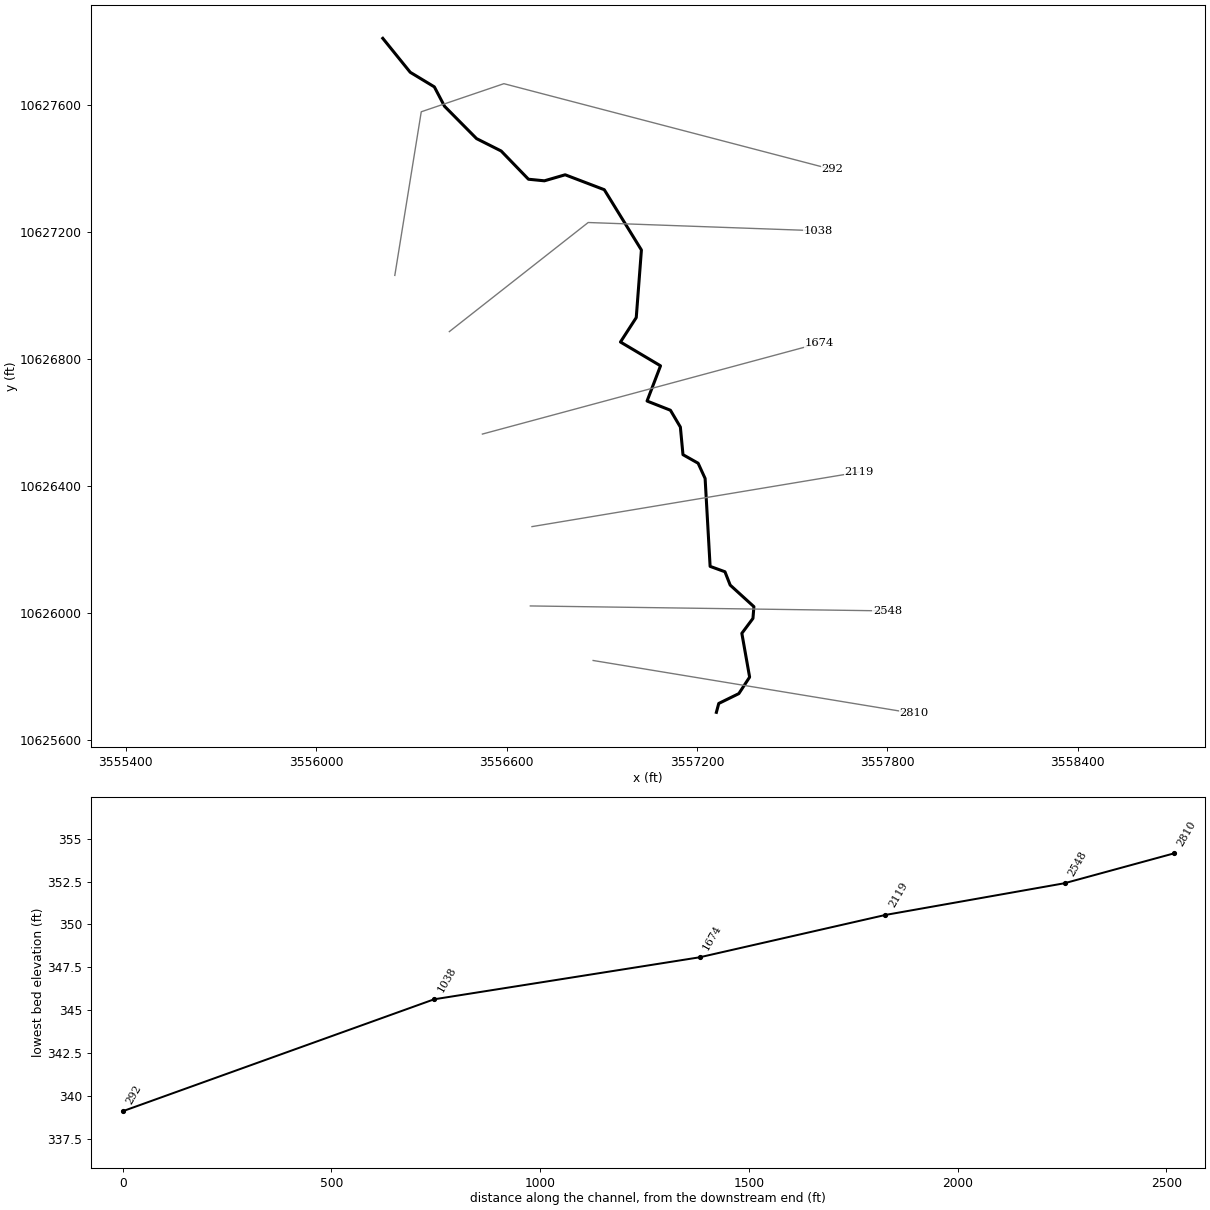
--- UNT160 IN CCTC.prj (project) ---

Proj Title=UNT160 IN CCTC Base Level Engineering
Current Plan=p01
Default Exp/Contr=0.3,0.1
English Units
Geom File=g01
Flow File=f01
Plan File=p01
Y Axis Title=Elevation
X Axis Title(PF)=Main Channel Distance
X Axis Title(XS)=Station
BEGIN DESCRIPTION:
UNT160 IN CCTC
END DESCRIPTION:
DSS Export Rating Curves= 0
DSS Export Rating Curve Sorted= 0
DSS Export Volume Flow Curves= 0
DXF OffsetX= 0
DXF OffsetY= 0
DXF ScaleX= 1
DXF ScaleY= 10

--- UNT160 IN CCTC.p01 (plan) ---

Plan Title=Multiple Run
Short Identifier=Multiple
Geom File=g01
Flow File=f01
Subcritical Flow
K Sum by GR= 0
Std Step Tol= 0.01
Critical Tol= 0.01
Num of Std Step Trials= 20
Max Error Tol= 0.3
Flow Tol Ratio= 0.001
Split Flow NTrial= 30
Split Flow Tol= 0.02
Split Flow Ratio= 0.02
Log Output Level= 0
Friction Slope Method= 1
Unsteady Friction Slope Method= 2
Unsteady Bridges Friction Slope Method= 1
Parabolic Critical Depth
Global Vel Dist=  1 , 1 , 1
Global Log Level= 0
CheckData=True
Encroach Param= -1, 0, 0, 0
BEGIN DESCRIPTION:
Multiple Run
END DESCRIPTION:

--- UNT160 IN CCTC.f01 (steady flow) ---

Flow Title=Multiple
Number of Profiles=7
Profile Names=10-year,25-year,50-year,1pct_min,100-year,1pct_plu,500-year
River Rch & RM= UNT160 IN CCTC,Reach-1,2810
    1396    1930    2373    2132    2884    3900    4240
Boundary for River Rch & Prof#=UNT160 IN CCTC,Reach-1,1
Up Type=0
Dn Type=3
Dn Slope=0.005
Boundary for River Rch & Prof#=UNT160 IN CCTC,Reach-1,2
Up Type=0
Dn Type=3
Dn Slope=0.005
Boundary for River Rch & Prof#=UNT160 IN CCTC,Reach-1,3
Up Type=0
Dn Type=3
Dn Slope=0.005
Boundary for River Rch & Prof#=UNT160 IN CCTC,Reach-1,4
Up Type=0
Dn Type=3
Dn Slope=0.005
Boundary for River Rch & Prof#=UNT160 IN CCTC,Reach-1,5
Up Type=0
Dn Type=3
Dn Slope=0.005
Boundary for River Rch & Prof#=UNT160 IN CCTC,Reach-1,6
Up Type=0
Dn Type=3
Dn Slope=0.005
Boundary for River Rch & Prof#=UNT160 IN CCTC,Reach-1,7
Up Type=0
Dn Type=3
Dn Slope=0.005

--- UNT160 IN CCTC.g01 (geometry) ---

Geom Title=Existing Conditions
Program Version=4.10

River Reach=UNT160 IN CCTC  ,Reach-1
Reach XY= 30
      3557260.75       10625686.      3557268.25       10625714.
       3557331.5       10625745.       3557365.5       10625797.
        3557341.       10625935.        3557376.       10625982.
        3557379.       10626019.      3557304.25       10626087.
      3557287.75       10626129.        3557241.       10626146.
      3557225.25       10626423.      3557203.25       10626471.
       3557155.5       10626498.      3557147.25       10626585.
        3557116.       10626638.      3557042.25       10626667.
      3557084.75       10626778.       3556958.5       10626853.
      3557008.25       10626930.       3557024.5       10627143.
       3556907.5       10627333.      3556784.25       10627380.
      3556718.75       10627361.       3556668.5       10627366.
       3556582.5       10627455.        3556505.       10627494.
        3556404.       10627596.        3556372.       10627657.
        3556296.       10627703.       3556209.5       10627810.

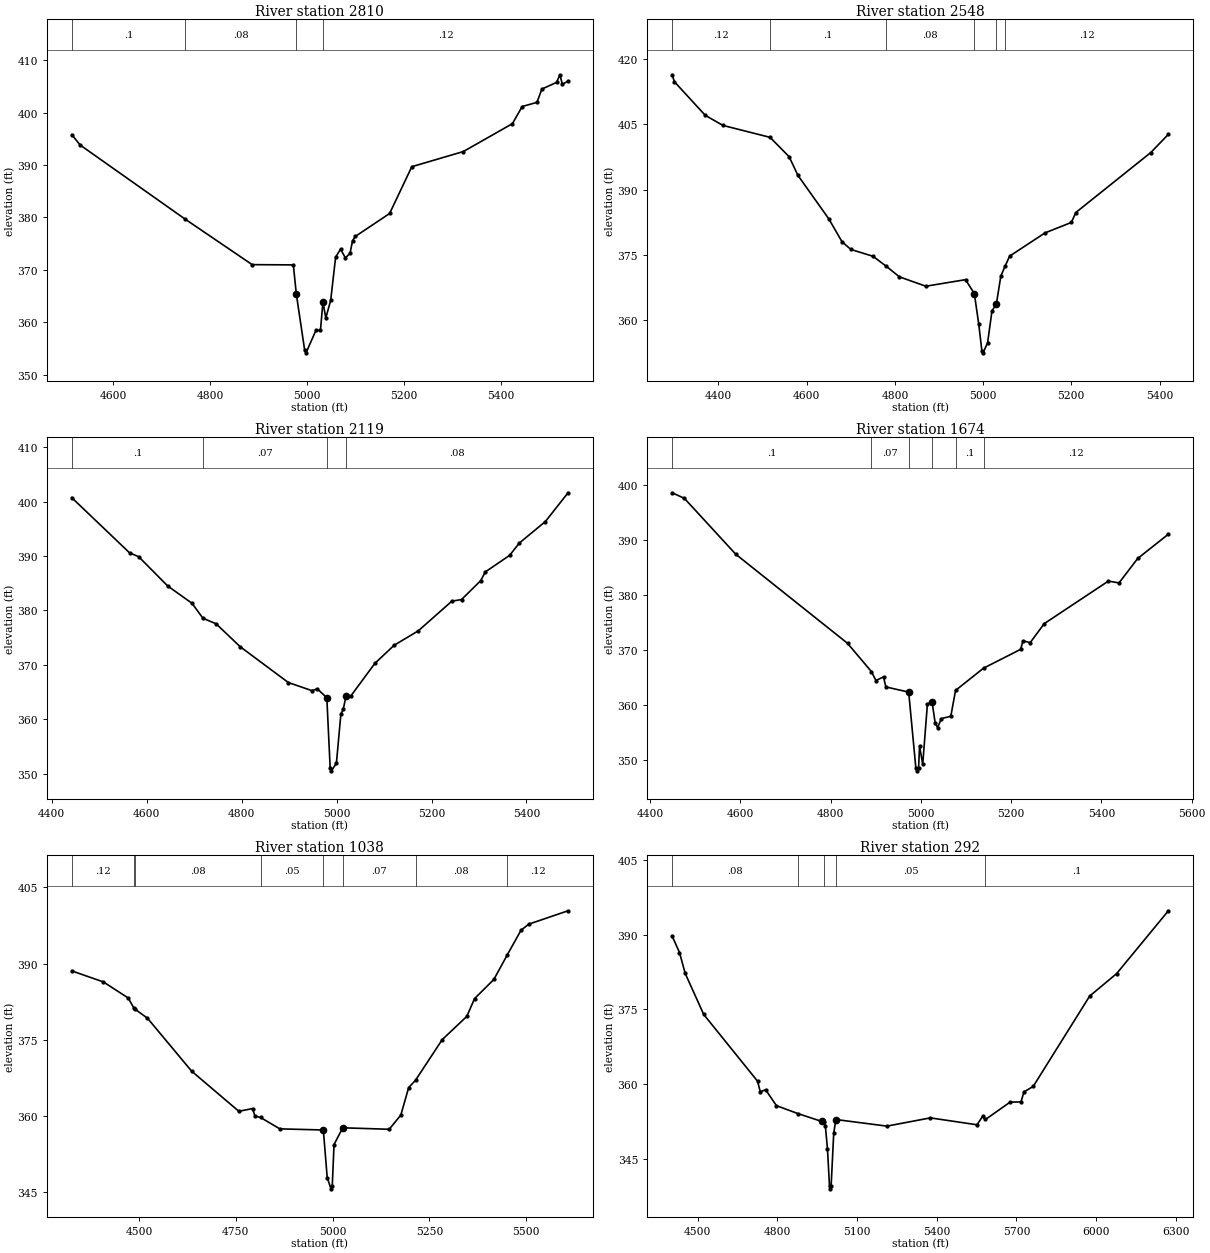
Type RM Length L Ch R = 1 ,2810    ,262,262,262
BEGIN DESCRIPTION:
UNT160 IN CCTC 4.0
END DESCRIPTION:
XS GIS Cut Line= 2
      3556872.41      10625849.4      3557882.86     10625682.73
#Sta/Elev= 30
  4514.9  395.82  4532.3  393.83  4749.2  379.66  4887.1  370.99  4972.1  370.94
  4978.3  365.35  4995.5  354.64  4998.3  354.14  5018.8  358.45  5028.1  358.45
  5033.2  363.88  5039.1  360.79  5049.2  364.17  5059.4  372.43  5069.5  373.94
  5079.6  372.28  5089.2  373.17  5094.3  375.55  5099.9  376.37  5170.8  380.76
  5216.6   389.7  5322.9  392.59  5424.2  397.92  5444.5   401.2  5474.9  401.99
    5485  404.53  5515.4  405.81  5522.2  407.26  5527.3  405.45    5539  406.04
#Mann= 4 ,-1 , 0
  4514.9      .1       0  4749.2     .08       0  4978.3     .05       0
  5033.2     .12       0
Bank Sta=4978.3,5033.2
XS Rating Curve= 0 ,0
Exp/Cntr=0.3,0.1

Type RM Length L Ch R = 1 ,2548    ,429,429,429
BEGIN DESCRIPTION:
Mapping XS 55c4a87a
END DESCRIPTION:
XS GIS Cut Line= 2
      3556674.46     10626021.28      3557799.45     10626005.65
#Sta/Elev= 30
    4295  416.43  4300.1  414.83  4370.2  407.08  4410.2  404.77    4517  402.02
  4560.2  397.57  4580.2  393.26  4650.2  383.25  4680.2  377.97  4700.2  376.21
  4750.2  374.64  4780.2  372.36  4810.2   369.9  4870.2  367.74  4960.2  369.25
  4980.2  366.03  4990.2  358.96  4997.2   352.9    5000   352.4  5010.2  354.71
  5020.2  362.08  5030.2  363.67  5040.2  370.08  5050.2  372.43  5060.2  374.67
  5140.2  380.01  5200.2  382.43  5210.2  384.71  5380.3  398.53  5420.1  402.72
#Mann= 6 ,-1 , 0
    4295     .12       0    4517      .1       0  4780.2     .08       0
  4980.2     .05       0  5030.2      .1       0  5050.2     .12       0
Bank Sta=4980.2,5030.2
XS Rating Curve= 0 ,0
Exp/Cntr=0.3,0.1

Type RM Length L Ch R = 1 ,2119    ,445,445,445
BEGIN DESCRIPTION:
Mapping XS c4f5c35e
END DESCRIPTION:
XS GIS Cut Line= 2
      3556679.66     10626271.27      3557710.94     10626443.15
#Sta/Elev= 30
  4442.1  400.71  4563.7  390.59  4583.2  389.86  4644.1   384.5  4695.5  381.31
  4718.4  378.57  4746.2  377.55  4796.9  373.34  4898.3  366.77  4948.2  365.27
  4959.1  365.62  4979.4  363.98  4986.5  351.05  4989.2  350.55  4999.6  351.95
    5009  360.94  5014.1  361.88  5019.9  364.32    5030   364.3  5080.7  370.29
  5121.3  373.61    5172  376.25  5242.9  381.71  5263.2     382  5303.8  385.49
  5313.2  387.07  5364.6  390.12  5384.9  392.37  5439.9  396.33  5487.6  401.61
#Mann= 4 ,-1 , 0
  4442.1      .1       0  4718.4     .07       0  4979.4     .05       0
  5019.9     .08       0
Bank Sta=4979.4,5019.9
XS Rating Curve= 0 ,0
Exp/Cntr=0.3,0.1

Type RM Length L Ch R = 1 ,1674    ,636,636,636
BEGIN DESCRIPTION:
UNT160 IN CCTC 3.0
END DESCRIPTION:
XS GIS Cut Line= 2
      3556523.44     10626562.94      3557585.23     10626849.21
#Sta/Elev= 30
  4448.7  398.52  4475.8  397.51  4589.7  387.37  4837.3  371.22  4890.1   366.1
  4900.4  364.46  4917.1  365.13  4922.3   363.3  4972.9  362.36  4988.8  348.58
  4991.6  348.08  4994.8  348.58    4997  352.55    5004  349.28  5014.4  360.21
  5024.7  360.57  5031.7  356.72  5036.9  355.93  5045.4  357.56  5066.2  357.98
  5076.8  362.67  5138.7   366.7    5221  370.12  5226.2  371.66  5242.2  371.34
  5273.3  374.78  5415.4   382.5    5439  382.17  5480.4   386.6  5548.4  391.01
#Mann= 6 ,-1 , 0
  4448.7      .1       0  4890.1     .07       0  4972.9     .05       0
  5024.7     .08       0  5076.8      .1       0  5138.7     .12       0
Bank Sta=4972.9,5024.7
XS Rating Curve= 0 ,0
Exp/Cntr=0.3,0.1

Type RM Length L Ch R = 1 ,1038    ,746,746,746
BEGIN DESCRIPTION:
UNT160 IN CCTC 2.0
END DESCRIPTION:
XS GIS Cut Line= 3
      3556419.25     10626885.84      3556856.78     10627229.61
      3557580.78     10627203.57
#Sta/Elev= 30
  4326.8  388.55  4408.3  386.38  4472.5  383.21  4486.5  381.31  4490.4  380.99
  4522.2  379.23  4636.1  368.81    4758   360.9  4793.3  361.44  4799.7  359.95
  4814.1  359.68  4863.8  357.44  4976.1  357.22  4986.1  347.83  4995.9  345.63
  4999.1  346.13  5003.7  354.36  5026.2  357.65  5146.2  357.36  5176.2  360.17
  5196.3  365.56    5214  367.01  5282.9  375.01  5346.4  379.59  5366.4  383.09
  5416.4  386.88  5450.6  391.67  5486.5  396.57  5506.5  397.76  5607.7  400.39
#Mann= 8 ,-1 , 0
  4326.8     .12       0  4486.5     .16       0  4490.4     .08       0
  4814.1     .05       0  4976.1     .03       0  5026.2     .07       0
    5214     .08       0  5450.6     .12       0
Bank Sta=4976.1,5026.2
XS Rating Curve= 0 ,0
Exp/Cntr=0.3,0.1

Type RM Length L Ch R = 1 ,292     ,0,0,0
BEGIN DESCRIPTION:
UNT160 IN CCTC 1.0
END DESCRIPTION:
XS GIS Cut Line= 4
       3556247.4     10627062.92      3556330.74     10627578.57
      3556591.15     10627667.11      3557626.11     10627396.67
#Sta/Elev= 30
  4404.6  389.69  4432.2   386.4  4453.7  382.22  4523.4     374    4726  360.64
  4736.1  358.53  4756.4  358.92  4796.9  355.75  4877.9  354.16    4968  352.58
  4975.9  352.46  4981.2  351.62  4989.1  347.04  4996.7   339.6  4999.4   339.1
  5002.7   339.6  5012.6  350.29  5020.8  352.97  5212.8  351.65  5376.1   353.3
  5551.8  351.92  5572.5  353.59  5583.4  352.98  5675.8  356.44  5717.2  356.51
  5728.2  358.48  5763.5  359.63  5975.6  377.68  6076.8  382.17  6271.7  394.75
#Mann= 5 ,-1 , 0
  4404.6     .08       0  4877.9     .07       0  4975.9     .05       0
  5020.8     .05       0  5583.4      .1       0
Bank Sta=4968,5020.8
XS Rating Curve= 0 ,0
Exp/Cntr=0.3,0.1

Chan Stop Cuts=-1
Use User Specified Reach Order=0
Composite Channel Slope=5