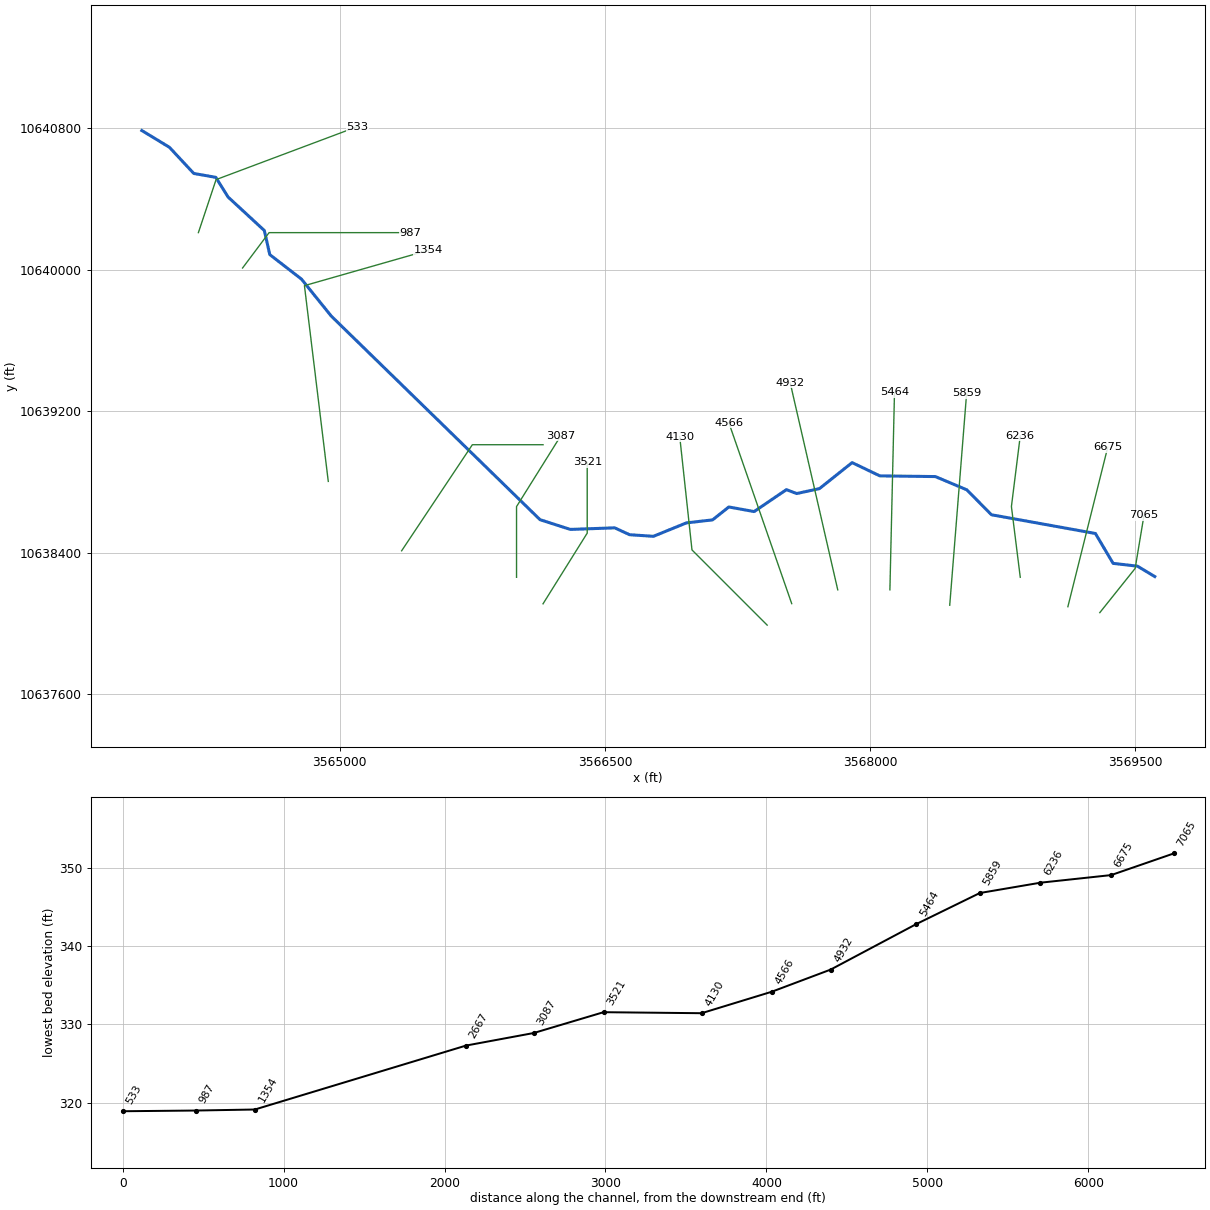
--- UNT161 IN CCTC.prj (project) ---

Proj Title=UNT161 IN CCTC Base Level Engineering
Current Plan=p01
Default Exp/Contr=0.3,0.1
English Units
Geom File=g01
Flow File=f01
Plan File=p01
Y Axis Title=Elevation
X Axis Title(PF)=Main Channel Distance
X Axis Title(XS)=Station
BEGIN DESCRIPTION:
UNT161 IN CCTC
END DESCRIPTION:
DSS Export Rating Curves= 0
DSS Export Rating Curve Sorted= 0
DSS Export Volume Flow Curves= 0
DXF OffsetX= 0
DXF OffsetY= 0
DXF ScaleX= 1
DXF ScaleY= 10

--- UNT161 IN CCTC.p01 (plan) ---

Plan Title=Multiple Run
Program Version=4.10
Short Identifier=Multiple
Geom File=g01
Flow File=f01
Subcritical Flow
K Sum by GR= 0
Std Step Tol= 0.01
Critical Tol= 0.01
Num of Std Step Trials= 20
Max Error Tol= 0.3
Flow Tol Ratio= 0.001
Split Flow NTrial= 30
Split Flow Tol= 0.02
Split Flow Ratio= 0.02
Log Output Level= 0
Friction Slope Method= 1
Unsteady Friction Slope Method= 2
Unsteady Bridges Friction Slope Method= 1
Parabolic Critical Depth
Global Vel Dist= 1 , 1 , 1
Global Log Level= 0
CheckData=True
Encroach Param=-1 ,0,0, 0
BEGIN DESCRIPTION:
Multiple Run
END DESCRIPTION:
Computation Interval=1HOUR
Output Interval=1HOUR
Run HTab= 0
Run UNet= 0
Run PostProcess= 0
Run WQNet= 0
UNET Theta= 1
UNET Theta Warmup= 1
UNET ZTol= 0.02
UNET ZSATol= 0.05
UNET MxIter= 20
UNET MaxInSteps= 0
UNET DtIC= 0
UNET DtMin= 0
UNET MaxCRTS= 20
UNET WFStab= 2
UNET SFStab= 1
UNET WFX= 1
UNET SFX= 1
UNET DSS MLevel= 4
UNET DZMax Abort= 100
UNET Convert EG Bridges= 0
UNET Use Existing IB Tables=-1
UNET Froude Reduction=False
UNET Froude Limit= 1
UNET Froude Power= 10
UNET Time Slicing=0,0, 5
UNET Junction Losses=0
Instantaneous Interval=1HOUR
Write IC File= 0
Write IC File at Sim End=0
Echo Input=False
Echo Parameters=False
Echo Output=False
Write Detailed= 0
WQ AD Non Conservative
WQ ULTIMATE=-1
WQ Max Comp Step=1HOUR
WQ Output Interval=15MIN
WQ Output Selected Increments= 0
WQ Output face flow=0
WQ Output face velocity=0
WQ Output face area=0
WQ Output face dispersion=0
WQ Output cell volume=0
WQ Output cell surface area=0
WQ Output cell continuity=0
WQ Output cumulative cell continuity=0
WQ Output face conc=0
WQ Output face dconc_dx=0
WQ Output face courant=0
WQ Output face peclet=0
WQ Output face adv mass=0
WQ Output face disp mass=0
WQ Output cell mass=0
WQ Output cell source sink temp=0
WQ Output cell source sink nsm=0
WQ Output MaxMinRange=-1
WQ Daily Max Min Mean=-1
WQ Daily Range=0
WQ Daily Time=0
WQ Create Restart=0
WQ Fixed Restart=0
WQ System Summary=0
WQ Use Fixed Temperature=0
Sorting and Armoring Iterations= 10
XS Update Threshold= 0.02
Hydraulics Update Threshold= 0.02
Energy Slope Method= 1
Volume Change Method= 0
XS Weighting Method= 0
Number of US Weighted Cross Sections= 1
Number of DS Weighted Cross Sections= 1
Upstream XS Weight=0.25
Main XS Weight=0.5
Downstream XS Weight=0.25
Number of DS XS's Weighted with US Boundary= 1
Upstream Boundary Weight= 1
Weight of XSs Associated with US Boundary= 0
Number of US XS's Weighted with DS Boundary= 1
Downstream Boundary Weight= 0.5
Weight of XSs Associated with DS Boundary= 0.5
Sediment Output Level= 4
Mass or Volume Output= 0
Output Increment Type= 1
Profile and TS Output Increment= 10
XS Output Flag= 0
XS Output Increment= 10
Disregard all LS=0
Disregard all Conn=0
Disregard all Breaches=0
Disregard all Pumps=0

--- UNT161 IN CCTC.f01 (steady flow) ---

Flow Title=Multiple
Number of Profiles=7
Profile Names=10-year,25-year,50-year,1pct_min,100-year,1pct_plu,500-year
River Rch & RM= UNT161 IN CCTC,Reach-1,7065
    1352    1856    2273    2033    2749    3718    4004
River Rch & RM= UNT161 IN CCTC,Reach-1,6675
    1743    2421    2986    2685    3632    4911    5354
Boundary for River Rch & Prof#=UNT161 IN CCTC,Reach-1,1
Up Type=0
Dn Type=3
Dn Slope=0.005
Boundary for River Rch & Prof#=UNT161 IN CCTC,Reach-1,2
Up Type=0
Dn Type=3
Dn Slope=0.005
Boundary for River Rch & Prof#=UNT161 IN CCTC,Reach-1,3
Up Type=0
Dn Type=3
Dn Slope=0.005
Boundary for River Rch & Prof#=UNT161 IN CCTC,Reach-1,4
Up Type=0
Dn Type=3
Dn Slope=0.005
Boundary for River Rch & Prof#=UNT161 IN CCTC,Reach-1,5
Up Type=0
Dn Type=3
Dn Slope=0.005
Boundary for River Rch & Prof#=UNT161 IN CCTC,Reach-1,6
Up Type=0
Dn Type=3
Dn Slope=0.005
Boundary for River Rch & Prof#=UNT161 IN CCTC,Reach-1,7
Up Type=0
Dn Type=3
Dn Slope=0.005

--- UNT161 IN CCTC.g01 (geometry) ---

Geom Title=Existing Conditions
Program Version=4.10

River Reach=UNT161 IN CCTC  ,Reach-1
Reach XY= 30
      3569610.67     10638264.33        3569513.       10638323.
        3569375.       10638339.      3569274.75       10638508.
       3568686.5       10638614.      3568547.25       10638755.
      3568369.25       10638830.      3568055.25       10638834.
      3567898.25       10638909.      3567713.75       10638762.
       3567584.5       10638734.       3567526.5       10638756.
        3567344.       10638632.      3567200.75       10638658.
      3567108.75       10638585.      3566960.75       10638568.
        3566774.       10638492.       3566639.5       10638501.
        3566555.       10638540.      3566304.25       10638531.
      3566132.75       10638586.       3564950.5       10639739.
        3564783.       10639947.       3564603.5       10640086.
      3564572.75       10640222.      3564367.25       10640412.
      3564298.25       10640523.       3564173.5       10640545.
      3564035.75       10640693.       3563879.5       10640788.

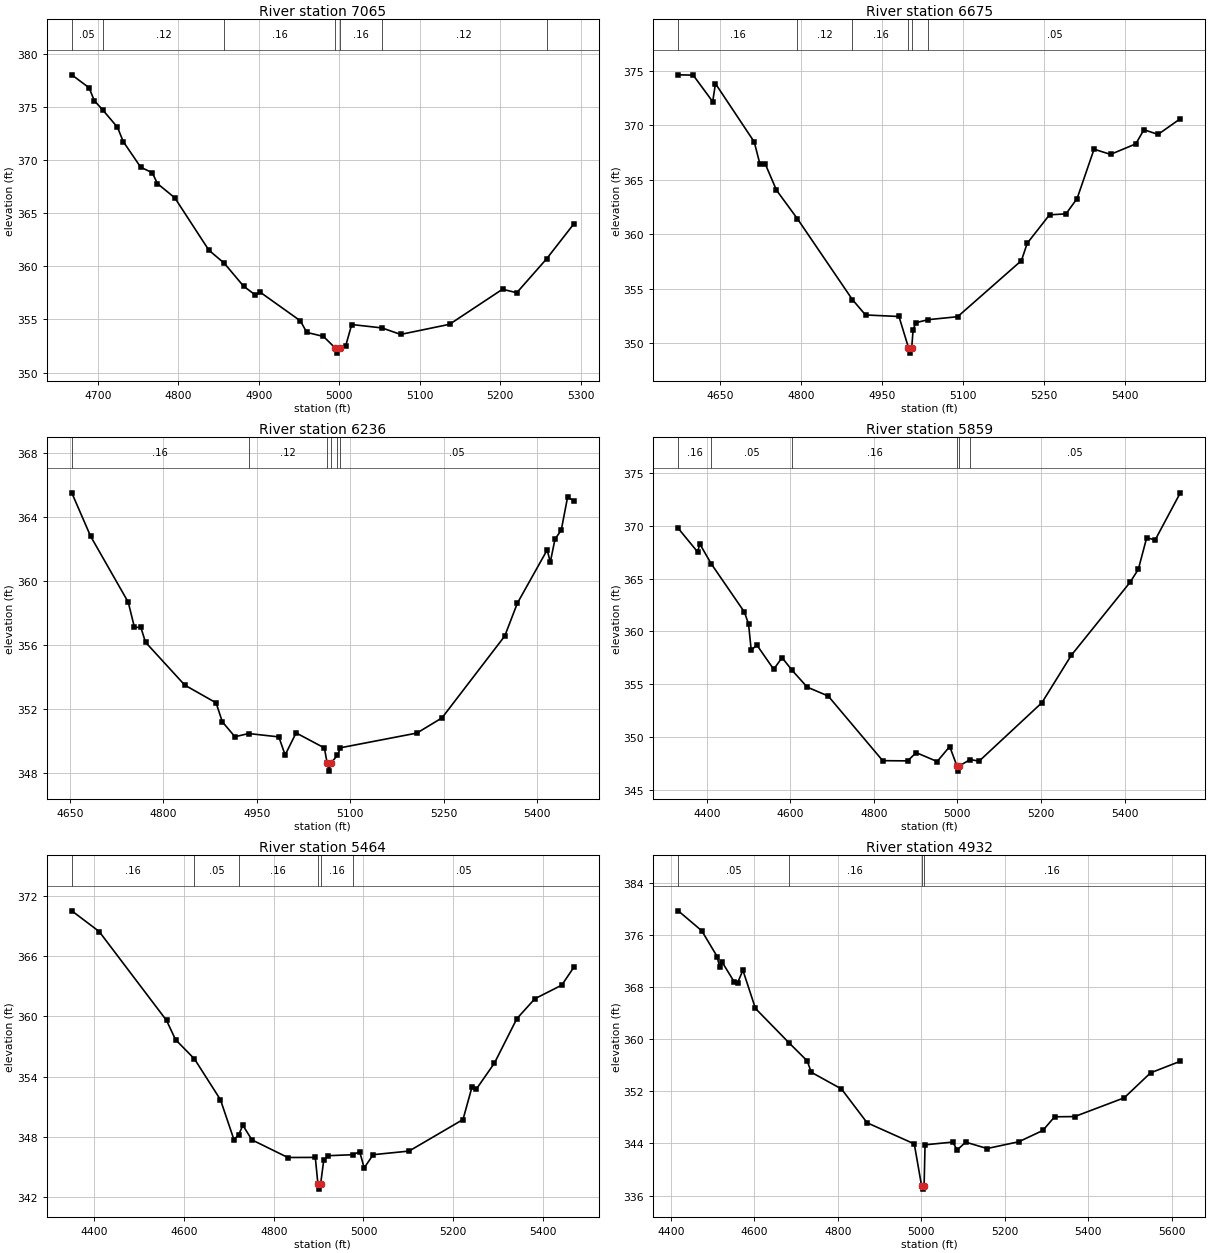
Type RM Length L Ch R = 1 ,7065    ,390,390,390
BEGIN DESCRIPTION:
UNT161 IN CCTC 14.0
END DESCRIPTION:
XS GIS Cut Line= 3
       3569299.6     10638060.17      3569499.61     10638310.19
      3569549.61     10638610.18
#Sta/Elev= 30
  4667.3  378.01  4688.9  376.79  4695.3  375.58  4705.9   374.7  4724.1  373.08
  4731.3  371.73    4753  369.32  4767.4   368.8  4773.8  367.78  4795.4  366.44
  4837.8  361.51  4856.9  360.29    4881  358.12  4895.4  357.31  4901.8  357.55
  4951.5  354.87  4959.5  353.78  4980.3   353.4  4994.6  352.33  4997.4  351.83
  5000.6  352.33  5007.8  352.49  5015.4  354.52  5053.1   354.2  5076.2  353.59
    5137  354.54  5202.9  357.84  5220.6  357.51  5257.6  360.69  5291.6  363.99
#Mann= 7 ,-1 , 0
  4667.3     .05       0  4705.9     .12       0  4856.9     .16       0
  4994.6     .07       0  5000.6     .16       0  5053.1     .12       0
  5257.6     .05       0
Bank Sta=4994.6,5000.6
XS Rating Curve= 0 ,0
Exp/Cntr=0.3,0.1

Type RM Length L Ch R = 1 ,6675    ,439,439,439
BEGIN DESCRIPTION:
UNT161 IN CCTC 13.0
END DESCRIPTION:
XS GIS Cut Line= 2
      3569119.03     10638093.73      3569344.49     10638995.57
#Sta/Elev= 30
  4573.2  374.66  4600.9  374.63    4637  372.19  4642.1  373.85  4713.9  368.49
  4724.6  366.42  4734.5  366.44  4755.1  364.05  4793.7  361.43  4895.7  353.98
    4920  352.57  4981.9  352.43  4999.5  349.56  5002.2  349.06  5005.5  349.56
  5008.1  351.21  5013.2  351.86  5036.3  352.14  5090.5  352.41  5208.6  357.57
  5219.4  359.17  5260.6  361.78  5291.1  361.87  5311.7  363.28  5343.1  367.82
  5373.6  367.34  5420.4  368.31  5435.4  369.61  5461.6  369.18  5502.8  370.62
#Mann= 6 ,-1 , 0
  4573.2     .16       0  4793.7     .12       0  4895.7     .16       0
  4999.5     .07       0  5005.5     .16       0  5036.3     .05       0
Bank Sta=4999.5,5005.5
XS Rating Curve= 0 ,0
Exp/Cntr=0.3,0.1

Type RM Length L Ch R = 1 ,6236    ,377,377,377
BEGIN DESCRIPTION:
UNT161 IN CCTC 12.0
END DESCRIPTION:
XS GIS Cut Line= 3
       3568849.6     10638260.23      3568799.61     10638660.19
      3568849.61     10639060.21
#Sta/Elev= 30
  4653.1  365.49  4683.3  362.78  4743.8  358.65  4753.8  357.07  4763.9  357.09
  4771.5  356.15  4834.5  353.47  4884.8  352.36  4894.9  351.17  4915.1  350.24
  4937.1  350.44  4985.6  350.23  4995.7   349.1  5013.3  350.48  5058.7  349.54
  5063.2  348.59    5066  348.09  5069.2  348.59  5079.7  349.08  5084.5  349.55
  5207.3  350.47  5247.6  351.42  5348.4  356.54  5368.6  358.59  5416.5  361.92
  5421.5  361.15    5429  362.59  5439.1  363.16  5449.2  365.21  5459.3     365
#Mann= 6 ,-1 , 0
  4653.1     .16       0  4937.1     .12       0  5063.2     .07       0
  5069.2     .12       0  5079.7     .16       0  5084.5     .05       0
Bank Sta=5063.2,5069.2
XS Rating Curve= 0 ,0
Exp/Cntr=0.3,0.1

Type RM Length L Ch R = 1 ,5859    ,395,395,395
BEGIN DESCRIPTION:
UNT161 IN CCTC 11.0
END DESCRIPTION:
XS GIS Cut Line= 2
      3568450.63     10638102.43      3568546.11     10639300.33
#Sta/Elev= 30
  4331.8  369.75  4378.3  367.51  4383.3  368.28    4411  366.38  4490.1  361.83
  4500.1   360.7  4506.4  358.24  4520.2  358.69  4560.3  356.41  4580.3  357.51
  4604.4  356.31  4640.5  354.72  4690.7  353.88  4821.1  347.76  4880.8  347.74
  4901.4  348.52  4951.5  347.68  4981.6   349.1  4998.7  347.27  5001.4  346.77
  5004.7  347.27  5030.8  347.87  5051.8  347.71  5202.3  353.25  5272.5  357.73
    5413  364.63    5433  365.87  5453.1  368.87  5473.2  368.64  5533.5  373.11
#Mann= 6 ,-1 , 0
  4331.8     .16       0    4411     .05       0  4604.4     .16       0
  4998.7     .07       0  5004.7     .16       0  5030.8     .05       0
Bank Sta=4998.7,5004.7
XS Rating Curve= 0 ,0
Exp/Cntr=0.3,0.1

Type RM Length L Ch R = 1 ,5464    ,532,532,532
BEGIN DESCRIPTION:
UNT161 IN CCTC 10.0
END DESCRIPTION:
XS GIS Cut Line= 2
      3568112.08     10638189.16      3568138.08     10639307.06
#Sta/Elev= 30
  4350.3  370.52  4411.3  368.46  4561.4   359.6  4581.4  357.69  4623.5  355.77
  4681.4  351.71  4711.4  347.74  4721.7  348.19  4731.4  349.16  4751.4  347.71
  4831.5  345.95  4892.7  345.96  4898.5   343.3  4901.2   342.8  4904.5   343.3
  4911.5  345.69  4921.5  346.13    4977  346.23  4991.5  346.54  5001.5  344.91
  5021.5  346.23  5101.5  346.59  5221.6  349.73  5241.6  352.96  5251.6  352.78
  5291.6  355.35  5341.6  359.78  5381.6  361.76  5441.6  363.12  5468.5   364.9
#Mann= 6 ,-1 , 0
  4350.3     .16       0  4623.5     .05       0  4721.7     .16       0
  4898.5     .03       0  4904.5     .16       0    4977     .05       0
Bank Sta=4898.5,4904.5
XS Rating Curve= 0 ,0
Exp/Cntr=0.3,0.1

Type RM Length L Ch R = 1 ,4932    ,366,366,366
BEGIN DESCRIPTION:
UNT161 IN CCTC 9.0
END DESCRIPTION:
XS GIS Cut Line= 2
      3567816.94     10638189.23      3567547.84     10639361.12
#Sta/Elev= 30
    4418  379.69  4474.3  376.63  4511.3  372.67  4517.1  371.03  4522.3  371.91
  4552.4  368.75    4560  368.62  4572.9  370.57  4602.9  364.71  4683.6  359.42
  4726.8  356.67  4736.6  354.92  4808.9  352.36  4870.3  347.17  4983.3  343.93
  5000.8  337.49  5003.6  336.99  5006.8  337.49  5009.1  343.79  5075.6  344.21
  5085.9  342.99  5106.4   344.2  5157.7  343.22  5233.7  344.26  5291.1  345.99
  5319.4  348.09  5367.4  348.12  5486.1     351  5549.1  354.83  5620.4  356.61
#Mann= 4 ,-1 , 0
    4418     .05       0  4683.6     .16       0  5000.8     .07       0
  5006.8     .16       0
Bank Sta=5000.8,5006.8
XS Rating Curve= 0 ,0
Exp/Cntr=0.3,0.1

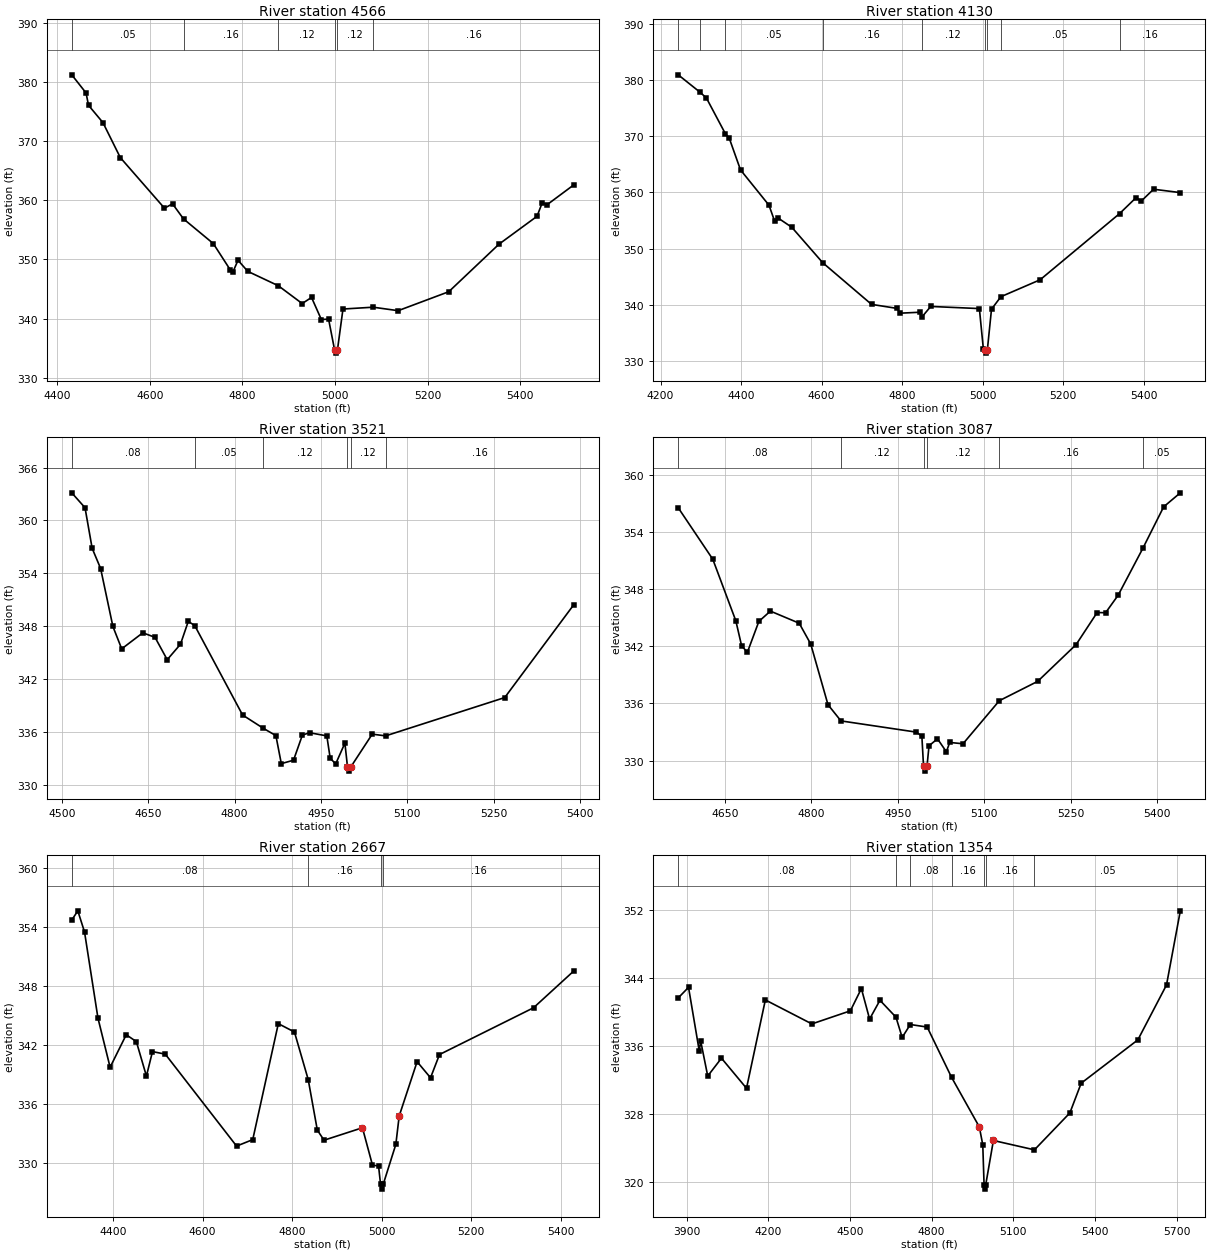
Type RM Length L Ch R = 1 ,4566    ,436,436,436
BEGIN DESCRIPTION:
UNT161 IN CCTC 8.0
END DESCRIPTION:
XS GIS Cut Line= 2
      3567556.53     10638111.07      3567200.66     10639135.31
#Sta/Elev= 30
  4431.6  381.24  4462.4  378.18  4467.8  376.08  4498.9  373.16  4536.5  367.23
  4631.8  358.68  4649.2  359.42  4672.9  356.87  4737.3  352.69  4773.7  348.27
    4780  347.96  4790.6  349.87  4811.8  347.99  4877.7  345.56  4929.2  342.55
  4949.4  343.58  4970.6  339.84  4986.2  339.92  4999.3  334.66  5002.1  334.16
  5005.3  334.66  5017.3  341.62  5082.6  341.93  5136.4  341.34  5245.8  344.55
  5354.2  352.59  5436.4  357.31  5447.6   359.6  5457.5  359.23  5515.9  362.63
#Mann= 6 ,-1 , 0
  4431.6     .05       0  4672.9     .16       0  4877.7     .12       0
  4999.3     .07       0  5005.3     .12       0  5082.6     .16       0
Bank Sta=4999.3,5005.3
XS Rating Curve= 0 ,0
Exp/Cntr=0.3,0.1

Type RM Length L Ch R = 1 ,4130    ,609,609,609
BEGIN DESCRIPTION:
UNT161 IN CCTC 7.0
END DESCRIPTION:
XS GIS Cut Line= 3
      3567417.64     10637989.56      3566992.29      10638414.9
      3566922.96     10639056.24
#Sta/Elev= 30
  4243.9   380.9  4297.1  377.86  4313.7   376.8    4361  370.42  4370.2  369.71
  4398.5     364  4469.2  357.72  4483.4  354.85  4490.4  355.51  4525.8   353.8
  4602.7  347.49  4723.8  340.09  4787.4  339.37  4794.5  338.52  4843.8  338.69
  4848.5  337.81  4870.9  339.72  4991.6  339.34  5001.6  332.07  5005.3  331.92
  5008.1  331.42  5011.3  331.92  5021.7  339.23    5045  341.45  5142.4  344.46
  5339.6  356.22  5380.5  359.05  5393.9  358.48  5424.1  360.56  5490.5  359.96
#Mann= 9 ,-1 , 0
  4243.9     .05       0  4297.1     .16       0    4361     .05       0
  4602.7     .16       0  4848.5     .12       0  5005.3     .07       0
  5011.3     .12       0    5045     .05       0  5339.6     .16       0
Bank Sta=5005.3,5011.3
XS Rating Curve= 0 ,0
Exp/Cntr=0.3,0.1

Type RM Length L Ch R = 1 ,3521    ,434,434,434
BEGIN DESCRIPTION:
UNT161 IN CCTC 6.0
END DESCRIPTION:
XS GIS Cut Line= 3
       3566149.6     10638110.17      3566399.61     10638510.19
      3566399.61     10638910.17
#Sta/Elev= 30
  4517.3  363.14  4540.3  361.45  4552.7  356.84  4567.4  354.55  4588.7  347.97
    4604  345.43  4640.6  347.25  4661.8  346.74    4683   344.2    4706  345.95
  4719.6  348.55  4730.8  348.07  4813.9  337.92  4849.4  336.43  4871.7  335.58
  4881.1   332.4  4902.3  332.79  4917.7  335.64  4930.1  335.91  4960.1  335.55
    4966  333.01  4975.5  332.37  4991.5  334.73    4996  332.05  4998.8  331.55
    5002  332.05    5039  335.75  5062.1  335.55    5269   339.9    5389  350.45
#Mann= 6 ,-1 , 0
  4517.3     .08       0  4730.8     .05       0  4849.4     .12       0
    4996     .07       0    5002     .12       0  5062.1     .16       0
Bank Sta=4996,5002
XS Rating Curve= 0 ,0
Exp/Cntr=0.3,0.1

Type RM Length L Ch R = 1 ,3087    ,420,420,420
BEGIN DESCRIPTION:
UNT161 IN CCTC 5.0
END DESCRIPTION:
XS GIS Cut Line= 3
      3565999.61     10638260.17      3565999.61     10638660.19
       3566249.6     10639060.17
#Sta/Elev= 30
  4568.9  356.52  4628.9  351.12  4668.9  344.66  4678.9  342.05  4688.9  341.35
  4708.9   344.6  4728.9  345.68  4778.9  344.41  4798.9  342.23  4828.9  335.86
  4851.4  334.16  4982.5  332.98  4991.9  332.55  4994.8  329.39  4997.6  328.89
  5000.8  329.39  5004.3  331.55    5019  332.28  5034.4  330.92  5040.3   331.9
  5063.3  331.76  5126.4  336.28    5193  338.31  5259.6  342.16  5296.2  345.53
  5310.9  345.51  5332.7  347.35  5375.4  352.25  5411.7  356.62  5440.6  358.09
#Mann= 6 ,-1 , 0
  4568.9     .08       0  4851.4     .12       0  4994.8     .07       0
  5000.8     .12       0  5126.4     .16       0  5375.4     .05       0
Bank Sta=4994.8,5000.8
XS Rating Curve= 0 ,0
Exp/Cntr=0.3,0.1

Type RM Length L Ch R = 1 ,2667    ,1313,1313,1313
BEGIN DESCRIPTION:
UNT161 IN CCTC 4.0
END DESCRIPTION:
XS GIS Cut Line= 3
      3565349.63     10638410.22      3565749.61     10639010.19
      3566149.64     10639010.19
#Sta/Elev= 30
    4308  354.74  4321.5  355.68  4336.5  353.52  4366.5  344.73  4393.6  339.72
  4429.6  343.04  4452.2  342.34  4474.7  338.82  4488.2  341.32  4516.8  341.06
    4676  331.68  4712.1  332.34  4769.2  344.17  4805.2  343.32    4836  338.46
  4856.3  333.31  4871.3  332.28    4957  333.55  4979.5  329.73    4993  329.66
  4997.5  327.79  5000.3  327.29  5003.5  327.79  5031.6  331.85  5039.1  334.75
  5079.1  340.29  5109.1  338.65  5129.1  341.02  5339.1  345.79  5429.1  349.55
#Mann= 4 ,-1 , 0
    4308     .08       0    4836     .16       0  4997.5     .07       0
  5003.5     .16       0
Bank Sta=4957,5039.1
XS Rating Curve= 0 ,0
Exp/Cntr=0.3,0.1

Type RM Length L Ch R = 1 ,1354    ,367,367,367
BEGIN DESCRIPTION:
UNT161 IN CCTC 3.0
END DESCRIPTION:
XS GIS Cut Line= 3
      3564934.47     10638802.67      3564799.61     10639910.19
       3565499.6     10640110.19
#Sta/Elev= 30
  3869.5  341.61  3907.3  342.85  3946.8  335.35  3951.9  336.55  3977.8  332.42
  4028.2  334.52  4120.2  330.98  4189.4  341.37  4360.2  338.55  4501.7  340.09
    4542  342.71  4572.2  339.12  4610.2  341.33  4669.1  339.34  4691.8  336.96
  4721.7  338.48  4783.7  338.18    4873  332.28  4975.1  326.44  4987.8  324.34
  4992.6  319.62  4995.4  319.12  4998.6  319.62  5026.8  324.84  5177.5  323.74
  5307.6  328.08  5349.2  331.58  5557.2  336.67  5662.5  343.13  5713.2  351.85
#Mann= 7 ,-1 , 0
  3869.5     .08       0  4669.1     .16       0  4721.7     .08       0
    4873     .16       0  4992.6     .07       0  4998.6     .16       0
  5177.5     .05       0
Bank Sta=4975.1,5026.8
XS Rating Curve= 0 ,0
Exp/Cntr=0.3,0.1

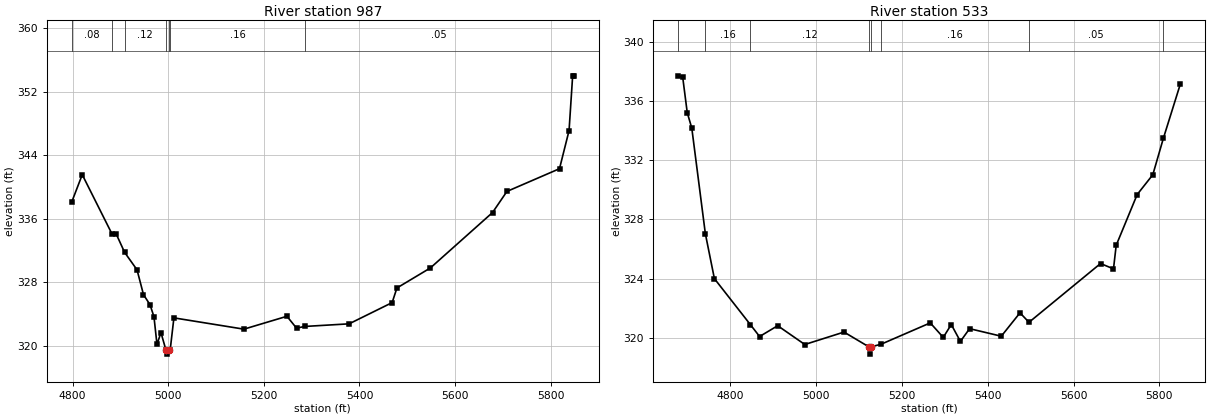
Type RM Length L Ch R = 1 ,987     ,454,454,454
BEGIN DESCRIPTION:
UNT161 IN CCTC 2.0
END DESCRIPTION:
XS GIS Cut Line= 3
      3564449.59     10640010.17      3564599.61     10640210.19
      3565399.58     10640210.19
#Sta/Elev= 30
  4798.3  338.13  4820.2  341.56  4882.7  334.07    4891  334.13  4908.8  331.79
  4934.8  329.59  4948.3  326.47  4961.9  325.21  4970.2  323.69  4976.5  320.21
  4984.8   321.7  4995.3  319.49  4998.1  318.99  5001.3  319.49  5004.1  319.52
  5011.9  323.55  5158.3  322.13  5248.3  323.75  5268.3  322.26  5285.4  322.47
  5378.3   322.8  5468.3  325.47  5478.3  327.31  5548.3  329.83  5678.3   336.8
  5708.3  339.45  5818.3  342.31  5838.3  347.11  5845.8  353.99  5848.3  353.99
#Mann= 7 ,-1 , 0
  4798.3     .08       0  4882.7     .16       0  4908.8     .12       0
  4995.3     .07       0  5001.3     .12       0  5004.1     .16       0
  5285.4     .05       0
Bank Sta=4995.3,5001.3
XS Rating Curve= 0 ,0
Exp/Cntr=0.3,0.1

Type RM Length L Ch R = 1 ,533     ,0,0,0
BEGIN DESCRIPTION:
UNT161 IN CCTC 1.0
END DESCRIPTION:
XS GIS Cut Line= 3
      3564199.62     10640210.23      3564299.61     10640510.19
      3565099.62     10640810.19
#Sta/Elev= 30
  4678.4   337.7  4688.9  337.59  4699.4  335.21    4710  334.17  4741.6  327.04
  4762.7     324  4846.4   320.9  4868.1  320.09  4910.3  320.82  4973.5  319.55
  5064.9  320.39  5122.4   319.4  5125.2   318.9  5128.4   319.4  5150.6  319.56
    5266  321.01  5296.3  320.03    5315   320.9  5336.3  319.76  5357.7  320.62
  5431.6  320.11  5475.2  321.69  5496.2  321.05    5663  325.02  5693.2  324.66
  5699.5  326.25  5748.4  329.68  5784.9  331.02  5809.4  333.47    5849  337.14
#Mann= 8 ,-1 , 0
  4678.4     .08       0  4741.6     .16       0  4846.4     .12       0
  5122.4     .07       0  5128.4     .12       0  5150.6     .16       0
  5496.2     .05       0  5809.4     .16       0
Bank Sta=5122.4,5128.4
XS Rating Curve= 0 ,0
Exp/Cntr=0.3,0.1

Chan Stop Cuts=-1
Use User Specified Reach Order=0
Composite Channel Slope=5