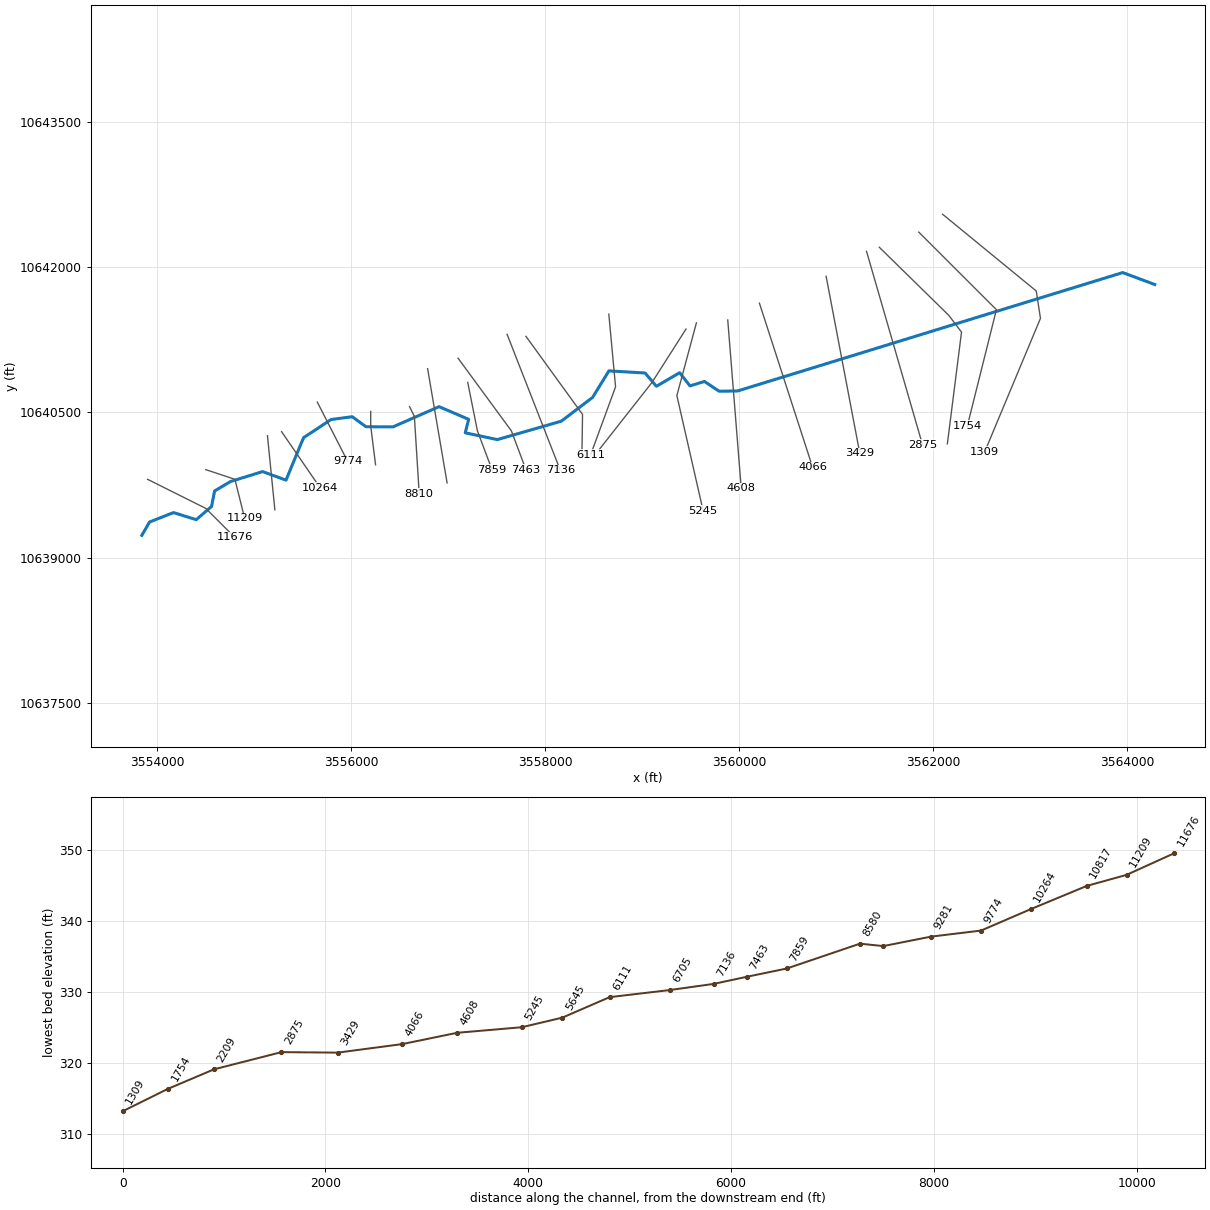
--- UNT162 IN CCTC.prj (project) ---

Proj Title=UNT162 IN CCTC Base Level Engineering
Current Plan=p01
Default Exp/Contr=0.3,0.1
English Units
Geom File=g01
Flow File=f01
Plan File=p01
Y Axis Title=Elevation
X Axis Title(PF)=Main Channel Distance
X Axis Title(XS)=Station
BEGIN DESCRIPTION:
UNT162 IN CCTC
END DESCRIPTION:
DSS Export Rating Curves= 0
DSS Export Rating Curve Sorted= 0
DSS Export Volume Flow Curves= 0
DXF OffsetX= 0
DXF OffsetY= 0
DXF ScaleX= 1
DXF ScaleY= 10

--- UNT162 IN CCTC.p01 (plan) ---

Plan Title=Multiple Run
Short Identifier=Multiple
Geom File=g01
Flow File=f01
Subcritical Flow
K Sum by GR= 0
Std Step Tol= 0.01
Critical Tol= 0.01
Num of Std Step Trials= 20
Max Error Tol= 0.3
Flow Tol Ratio= 0.001
Split Flow NTrial= 30
Split Flow Tol= 0.02
Split Flow Ratio= 0.02
Log Output Level= 0
Friction Slope Method= 1
Unsteady Friction Slope Method= 2
Unsteady Bridges Friction Slope Method= 1
Parabolic Critical Depth
Global Vel Dist=  1 , 1 , 1
Global Log Level= 0
CheckData=True
Encroach Param= -1, 0, 0, 0
BEGIN DESCRIPTION:
Multiple Run
END DESCRIPTION:

--- UNT162 IN CCTC.f01 (steady flow) ---

Flow Title=Multiple
Number of Profiles=7
Profile Names=10-year,25-year,50-year,1pct_min,100-year,1pct_plu,500-year
River Rch & RM= UNT162 IN CCTC,Reach-1,11676
    2152    3032    3777    3428    4636    6270    6967
River Rch & RM= UNT162 IN CCTC,Reach-1,5645
    2558    3619    4519    4108    5556    7514    8376
Boundary for River Rch & Prof#=UNT162 IN CCTC,Reach-1,1
Up Type=0
Dn Type=3
Dn Slope=0.005
Boundary for River Rch & Prof#=UNT162 IN CCTC,Reach-1,2
Up Type=0
Dn Type=3
Dn Slope=0.005
Boundary for River Rch & Prof#=UNT162 IN CCTC,Reach-1,3
Up Type=0
Dn Type=3
Dn Slope=0.005
Boundary for River Rch & Prof#=UNT162 IN CCTC,Reach-1,4
Up Type=0
Dn Type=3
Dn Slope=0.005
Boundary for River Rch & Prof#=UNT162 IN CCTC,Reach-1,5
Up Type=0
Dn Type=3
Dn Slope=0.005
Boundary for River Rch & Prof#=UNT162 IN CCTC,Reach-1,6
Up Type=0
Dn Type=3
Dn Slope=0.005
Boundary for River Rch & Prof#=UNT162 IN CCTC,Reach-1,7
Up Type=0
Dn Type=3
Dn Slope=0.005

--- UNT162 IN CCTC.g01 (geometry) ---

Geom Title=Existing Conditions
Program Version=4.10

River Reach=UNT162 IN CCTC  ,Reach-1
Reach XY= 30
        3553840.       10639232.      3553919.75       10639370.
      3554166.75       10639467.        3554401.       10639394.
        3554559.       10639530.      3554590.25       10639690.
       3554755.5       10639788.        3555085.       10639890.
      3555326.25       10639802.       3555507.5       10640240.
        3555791.       10640427.      3556008.75       10640456.
      3556150.75       10640353.        3556429.       10640351.
      3556904.25       10640560.       3557209.5       10640429.
        3557174.       10640290.      3557505.25       10640220.
      3558164.25       10640410.       3558486.5       10640655.
      3558655.25       10640929.      3559028.25       10640907.
       3559144.5       10640770.       3559384.5       10640910.
      3559490.75       10640774.        3559639.       10640820.
       3559789.5       10640720.      3559979.25       10640721.
       3563951.5       10641943.        3564282.       10641820.

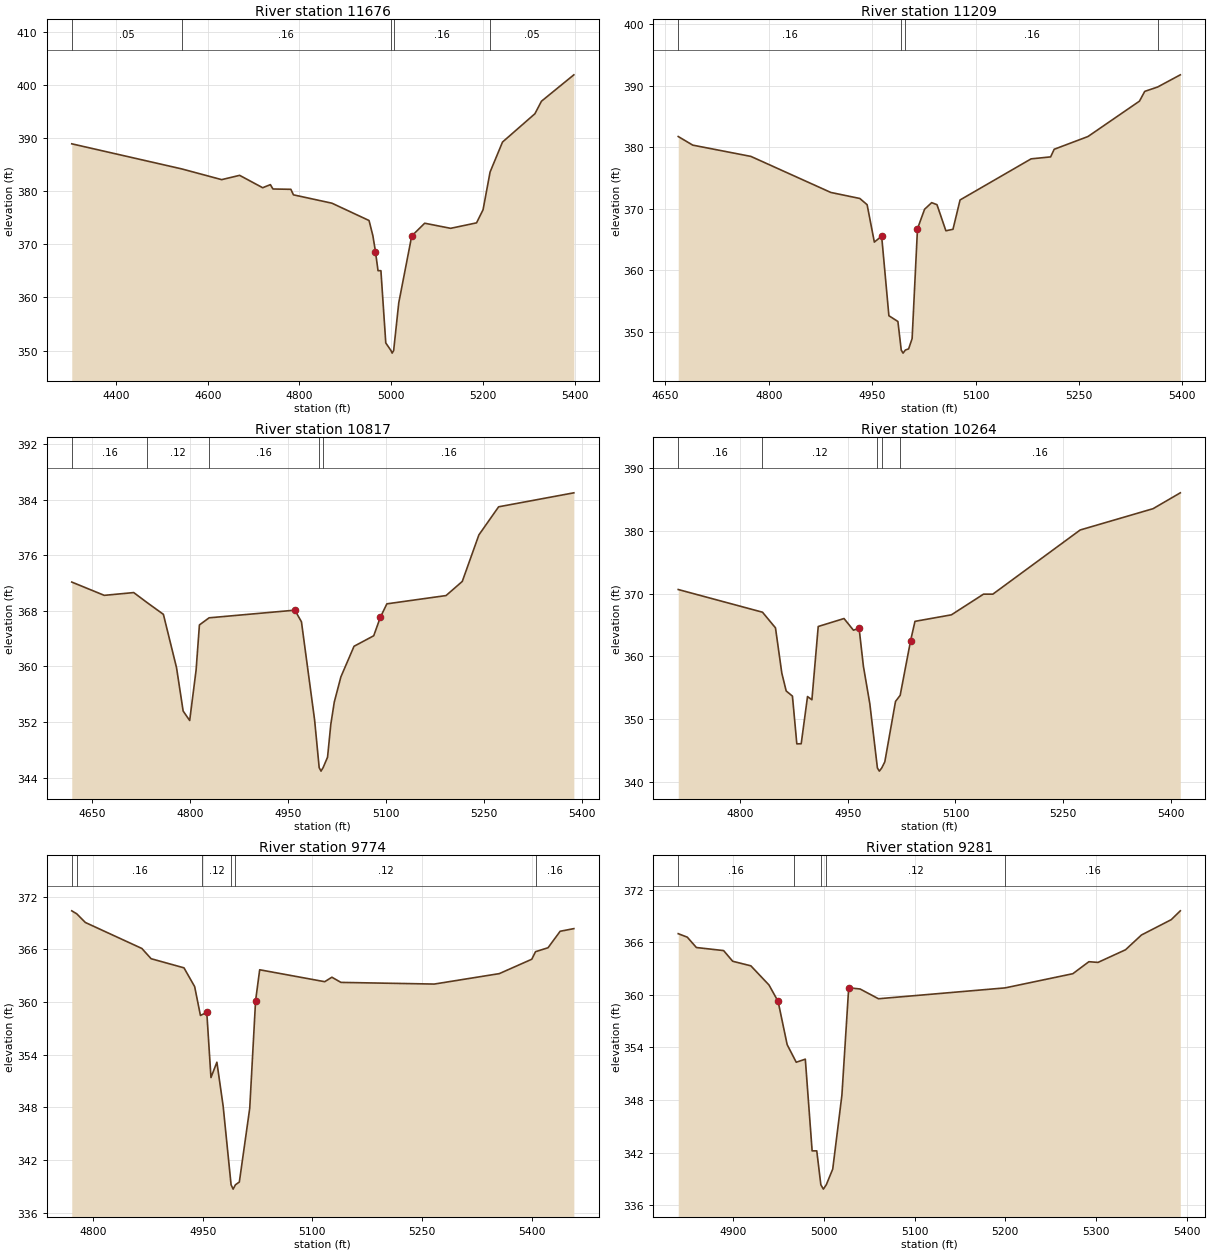
Type RM Length L Ch R = 1 ,11676   ,467,467,467
BEGIN DESCRIPTION:
UNT162 IN CCTC 24.0
END DESCRIPTION:
XS GIS Cut Line= 3
      3553899.63     10639810.18      3554499.61     10639510.19
      3554799.63     10639210.16
#Sta/Elev= 30
  4303.3   388.9  4543.1  384.18  4630.3  382.16  4669.4  382.97  4719.7  380.64
  4736.5  381.22  4742.1   380.4  4781.2  380.34  4786.8   379.3  4870.7  377.73
  4951.7  374.47  4960.1   371.6  4965.7  368.62  4971.3  365.03  4977.6  365.03
  4988.2  351.44  4999.4  350.02  5002.1  349.52  5005.4  350.02  5016.5  358.97
  5044.8  371.56  5073.1  373.96  5129.7     373  5186.2  374.03  5200.4   376.5
  5215.7  383.59  5242.8  389.23  5313.5  394.56  5327.7  396.91  5398.4  401.88
#Mann= 5 ,-1 , 0
  4303.3     .05       0  4543.1     .16       0  4999.4     .07       0
  5005.4     .16       0  5215.7     .05       0
Bank Sta=4965.7,5044.8
XS Rating Curve= 0 ,0
Exp/Cntr=0.3,0.1

Type RM Length L Ch R = 1 ,11209   ,392,392,392
BEGIN DESCRIPTION:
UNT162 IN CCTC 23.0
END DESCRIPTION:
XS GIS Cut Line= 3
      3554499.58      10639910.2      3554799.61     10639810.19
      3554899.62     10639410.15
#Sta/Elev= 30
  4668.5  381.71  4689.6  380.31  4773.9  378.48  4889.9  372.62    4932  371.64
  4942.6  370.63  4953.1  364.55  4963.7  365.51  4974.2  352.58  4987.3  351.64
  4992.1     347  4994.8   346.5  4998.1     347  5002.8  347.19  5007.9  348.86
  5015.7  366.72    5026  369.89  5036.3  370.96    5044  370.63  5056.9  366.39
  5067.2  366.63  5077.5   371.4  5180.6  378.08  5208.9   378.4  5214.1  379.64
  5263.1  381.71  5337.8  387.46  5345.5  389.05  5364.2  389.76  5397.1  391.74
#Mann= 4 ,-1 , 0
  4668.5     .16       0  4992.1     .07       0  4998.1     .16       0
  5364.2     .05       0
Bank Sta=4963.7,5015.7
XS Rating Curve= 0 ,0
Exp/Cntr=0.3,0.1

Type RM Length L Ch R = 1 ,10817   ,553,553,553
BEGIN DESCRIPTION:
UNT162 IN CCTC 22.0
END DESCRIPTION:
XS GIS Cut Line= 2
      3555135.22     10640259.61       3555211.6     10639495.72
#Sta/Elev= 30
  4619.5  372.13  4669.2  370.22  4714.2  370.62  4734.7  369.18  4759.6  367.49
  4779.7  359.82  4789.8  353.59  4799.8  352.23  4809.6  359.47  4814.7  365.97
  4829.5  366.99  4960.6  368.09  4970.7  366.42  4990.8  352.31  4997.8  345.45
  5000.6  344.95  5003.8  345.45  5010.6  346.95  5015.6  351.68  5020.9  354.88
    5031   358.5  5051.1   362.9  5081.2  364.41  5091.3  367.06  5101.3     369
  5191.8  370.19  5216.6  372.22    5242  378.91  5272.2  382.95  5387.2  384.96
#Mann= 5 ,-1 , 0
  4619.5     .16       0  4734.7     .12       0  4829.5     .16       0
  4997.8     .07       0  5003.8     .16       0
Bank Sta=4960.6,5091.3
XS Rating Curve= 0 ,0
Exp/Cntr=0.3,0.1

Type RM Length L Ch R = 1 ,10264   ,490,490,490
BEGIN DESCRIPTION:
UNT162 IN CCTC 21.0
END DESCRIPTION:
XS GIS Cut Line= 2
      3555281.06     10640301.24      3555676.77     10639725.04
#Sta/Elev= 30
    4714  370.66  4831.3  367.04  4849.4  364.54  4858.2  357.32  4864.3  354.47
    4873  353.65  4879.1  346.03  4885.2  346.05    4894  353.58  4900.1  353.07
  4908.9  364.76  4944.8  366.03  4957.9  364.17  4965.8  364.47  4971.8  358.41
  4980.7  352.46  4991.3  342.18    4994  341.68  4997.3  342.18  5001.6  343.16
  5016.5   352.8    5023  353.78  5037.5   362.5  5043.6  365.58  5094.3  366.62
    5139  369.92    5152  369.92  5273.6  380.16  5375.1  383.56    5413  386.09
#Mann= 5 ,-1 , 0
    4714     .16       0  4831.3     .12       0  4991.3     .07       0
  4997.3     .12       0    5023     .16       0
Bank Sta=4965.8,5037.5
XS Rating Curve= 0 ,0
Exp/Cntr=0.3,0.1

Type RM Length L Ch R = 1 ,9774    ,493,493,493
BEGIN DESCRIPTION:
UNT162 IN CCTC 20.0
END DESCRIPTION:
XS GIS Cut Line= 2
      3555649.12     10640606.79      3555961.63     10639995.66
#Sta/Elev= 30
    4771   370.4  4777.8  370.06  4789.6  369.07  4866.8  366.11  4879.5  364.94
  4924.4   363.9    4939  361.76  4946.9  358.47  4949.1  358.56  4955.6  358.81
  4961.3  351.39  4969.4  353.14  4977.9  348.17  4988.8  339.17  4991.6  338.67
  4994.8  339.17  5000.1  339.48  5014.3  347.89  5022.3  360.15  5027.9  363.68
  5116.8  362.32  5126.6  362.83    5139  362.24  5266.6  362.05  5355.5  363.24
  5399.9  364.88    5405  365.74  5422.1  366.19  5438.7  368.07  5457.4  368.37
#Mann= 6 ,-1 , 0
    4771     .05       0  4777.8     .16       0  4949.1     .12       0
  4988.8     .07       0  4994.8     .12       0    5405     .16       0
Bank Sta=4955.6,5022.3
XS Rating Curve= 0 ,0
Exp/Cntr=0.3,0.1

Type RM Length L Ch R = 1 ,9281    ,471,471,471
BEGIN DESCRIPTION:
UNT162 IN CCTC 19.0
END DESCRIPTION:
XS GIS Cut Line= 3
      3556199.61     10640510.22      3556199.61     10640360.19
       3556249.6     10639960.23
#Sta/Elev= 30
  4839.7  366.99  4849.7  366.59  4859.7  365.41  4889.7  365.06  4899.7  363.84
  4919.7  363.32  4939.7  361.13  4949.7  359.26  4959.7  354.32  4967.4  352.77
  4969.7  352.31  4979.7  352.66  4987.2  342.19  4992.3  342.19  4996.8  338.32
  4999.6  337.82  5002.8  338.32  5009.9  340.11    5020  348.55  5027.5  360.82
  5040.1  360.67  5060.3  359.56  5199.8   360.8  5274.4  362.42  5292.1  363.79
  5302.1  363.71  5332.4  365.15    5350  366.84  5382.8  368.59  5392.8   369.6
#Mann= 5 ,-1 , 0
  4839.7     .16       0  4967.4     .12       0  4996.8     .07       0
  5002.8     .12       0  5199.8     .16       0
Bank Sta=4949.7,5027.5
XS Rating Curve= 0 ,0
Exp/Cntr=0.3,0.1

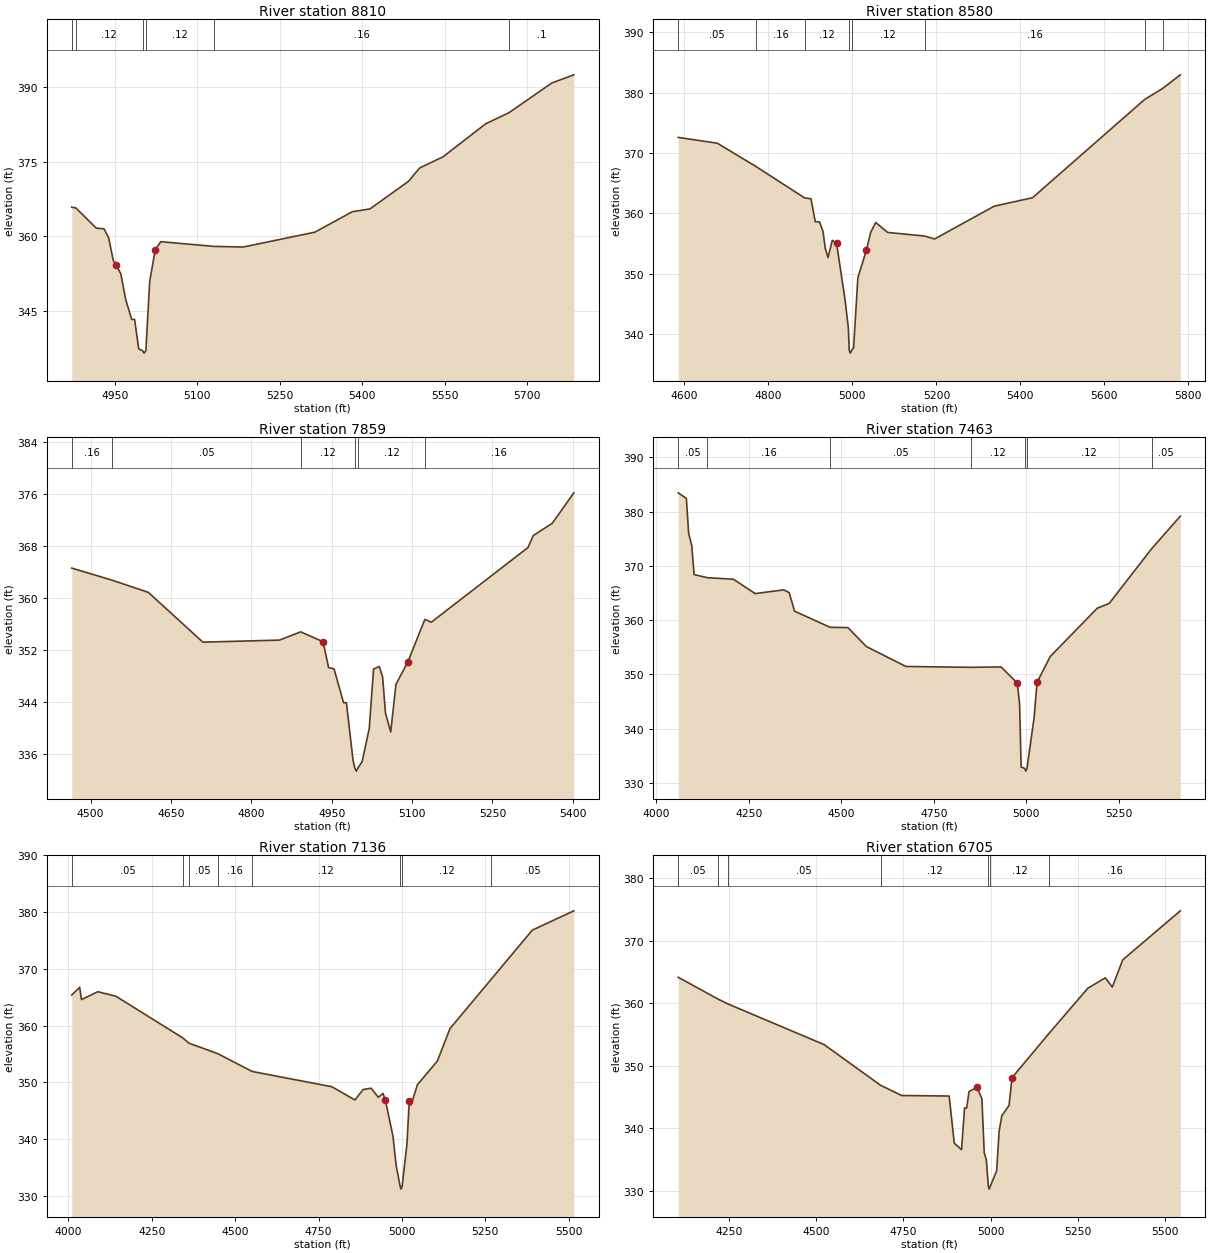
Type RM Length L Ch R = 1 ,8810    ,230,230,230
BEGIN DESCRIPTION:
UNT162 IN CCTC 18.0
END DESCRIPTION:
XS GIS Cut Line= 3
      3556599.62     10640560.18      3556649.61     10640460.19
      3556699.61     10639660.14
#Sta/Elev= 30
  4871.6  365.88    4879  365.72  4916.3  361.66  4930.3  361.52  4938.7  359.72
  4947.1  355.16  4952.6  354.25    4961  352.41  4969.4  347.41  4980.6  343.28
  4985.9  343.28  4993.4  337.34  5000.4  336.99  5003.2  336.49  5006.4  336.99
  5013.4  350.96  5023.5  357.31  5033.5  358.93  5130.7  357.98  5183.8  357.86
    5314  360.85  5381.7  364.95  5414.2  365.54  5484.4   371.1  5504.4  373.77
    5547  376.02  5624.6  382.67  5667.1  384.91  5744.9  390.89    5785  392.53
#Mann= 6 ,-1 , 0
  4871.6     .16       0    4879     .12       0  5000.4     .07       0
  5006.4     .12       0  5130.7     .16       0  5667.1      .1       0
Bank Sta=4952.6,5023.5
XS Rating Curve= 0 ,0
Exp/Cntr=0.3,0.1

Type RM Length L Ch R = 1 ,8580    ,721,721,721
BEGIN DESCRIPTION:
UNT162 IN CCTC 17.0
END DESCRIPTION:
XS GIS Cut Line= 2
      3556786.04     10640951.87       3556987.1      10639773.2
#Sta/Elev= 30
  4585.2  372.58  4678.2  371.62    4771  367.73    4886  362.56  4901.4   362.4
  4911.5  358.61  4921.7  358.58  4930.1  356.97  4935.2  354.24    4942  352.67
  4952.1  355.53  4962.2  355.05  4982.5  345.67  4990.3  341.04  4992.4  337.33
  4995.1  336.83  4998.4  337.33  5002.8  337.69    5013  349.33  5033.3  353.89
  5043.4  356.83  5055.5  358.48    5084  356.83  5172.7  356.23  5195.6  355.74
  5337.6  361.18  5428.9  362.58    5696  378.87  5738.9   380.7  5780.9  382.95
#Mann= 8 ,-1 , 0
  4585.2     .05       0    4771     .16       0    4886     .12       0
  4992.4     .07       0  4998.4     .12       0  5172.7     .16       0
    5696      .1       0  5738.9     .16       0
Bank Sta=4962.2,5033.3
XS Rating Curve= 0 ,0
Exp/Cntr=0.3,0.1

Type RM Length L Ch R = 1 ,7859    ,396,396,396
BEGIN DESCRIPTION:
UNT162 IN CCTC 16.0
END DESCRIPTION:
XS GIS Cut Line= 3
      3557199.61     10640810.17      3557299.61     10640310.19
      3557449.61     10639910.17
#Sta/Elev= 30
  4464.8  364.62  4539.7  362.77  4607.6  360.89  4709.5  353.21  4852.3  353.53
  4892.2   354.8  4933.9  353.27  4944.1   349.3  4954.3   349.1  4972.1  343.88
  4977.4  343.88  4989.8  334.99    4993  333.84  4995.8  333.34    4999  333.84
  5006.7  334.79  5020.1  339.96  5028.1  349.07  5038.8  349.46    5045  347.84
  5050.3  342.29  5060.1  339.38  5069.9  346.71  5092.2  350.19  5123.8  356.72
  5135.8  356.28  5316.4   367.8  5326.2  369.64  5361.8  371.54  5401.9  376.22
#Mann= 6 ,-1 , 0
  4464.8     .16       0  4539.7     .05       0  4892.2     .12       0
    4993     .07       0    4999     .12       0  5123.8     .16       0
Bank Sta=4933.9,5092.2
XS Rating Curve= 0 ,0
Exp/Cntr=0.3,0.1

Type RM Length L Ch R = 1 ,7463    ,327,327,327
BEGIN DESCRIPTION:
UNT162 IN CCTC 15.0
END DESCRIPTION:
XS GIS Cut Line= 3
      3557099.61     10641060.19      3557649.61     10640310.19
      3557799.62     10639910.15
#Sta/Elev= 30
    4059  383.46    4081  382.43  4087.2  375.99  4095.6  373.71  4101.8   368.4
  4137.7  367.82  4208.4  367.53    4267  364.89  4344.2  365.58  4358.9  365.07
  4373.5  361.65  4469.4  358.68  4517.8  358.62  4567.4  355.14  4674.5  351.46
  4849.4   351.3  4931.6  351.38  4975.5  348.41  4981.7  344.65    4986  332.93
  4995.8  332.67  4998.6  332.17  5001.8  332.67  5021.1  342.06  5029.1  348.54
  5064.7   353.3    5192  362.21    5224  363.07  5338.9  373.17  5416.3  379.16
#Mann= 7 ,-1 , 0
    4059     .05       0  4137.7     .16       0  4469.4     .05       0
  4849.4     .12       0  4995.8     .07       0  5001.8     .12       0
  5338.9     .05       0
Bank Sta=4975.5,5029.1
XS Rating Curve= 0 ,0
Exp/Cntr=0.3,0.1

Type RM Length L Ch R = 1 ,7136    ,431,431,431
BEGIN DESCRIPTION:
UNT162 IN CCTC 14.0
END DESCRIPTION:
XS GIS Cut Line= 2
      3557605.48     10641306.02      3558153.71     10639904.21
#Sta/Elev= 30
  4010.2  365.38  4033.9  366.73  4039.3  364.57  4088.2  365.96  4142.5  365.16
  4343.8  357.79  4360.7  356.91  4447.5  355.05  4551.2   351.9  4789.6  349.22
  4859.1  346.88  4883.6  348.72  4907.7  348.96  4929.2  347.35  4943.3  348.03
  4950.6  346.81  4973.1  340.51  4982.8  335.32  4994.6  331.67  4997.3  331.17
  5000.6  331.67  5015.1  339.13    5022  346.71  5027.4  345.97  5046.5  349.59
  5106.2  353.73  5143.9  359.45    5267   368.1  5390.9  376.81  5515.4  380.21
#Mann= 8 ,-1 , 0
  4010.2     .05       0  4343.8     .16       0  4360.7     .05       0
  4447.5     .16       0  4551.2     .12       0  4994.6     .07       0
  5000.6     .12       0    5267     .05       0
Bank Sta=4950.6,5022
XS Rating Curve= 0 ,0
Exp/Cntr=0.3,0.1

Type RM Length L Ch R = 1 ,6705    ,594,594,594
BEGIN DESCRIPTION:
UNT162 IN CCTC 13.0
END DESCRIPTION:
XS GIS Cut Line= 3
      3557799.96     10641285.12      3558383.27      10640479.6
      3558376.32     10640035.19
#Sta/Elev= 30
  4104.9  364.17  4219.8  360.66  4246.9  359.92  4523.3   353.4  4684.8  346.91
  4745.3  345.27  4881.4  345.19  4896.1  337.65  4916.9  336.62  4925.5  343.29
  4931.6  343.27  4938.2  345.89    4961  346.59  4975.2   344.8  4981.9  336.16
  4988.1  334.95  4993.6  330.81  4996.3  330.31  4999.6  330.81  5017.5  333.26
  5024.6  339.56  5032.2  342.02    5053  343.69  5061.6  348.12  5166.5  355.13
  5278.9  362.42  5328.9  364.08  5348.9  362.61  5378.9  366.96  5543.9  374.79
#Mann= 7 ,-1 , 0
  4104.9     .05       0  4219.8     .16       0  4246.9     .05       0
  4684.8     .12       0  4993.6     .07       0  4999.6     .12       0
  5166.5     .16       0
Bank Sta=4961,5061.6
XS Rating Curve= 0 ,0
Exp/Cntr=0.3,0.1

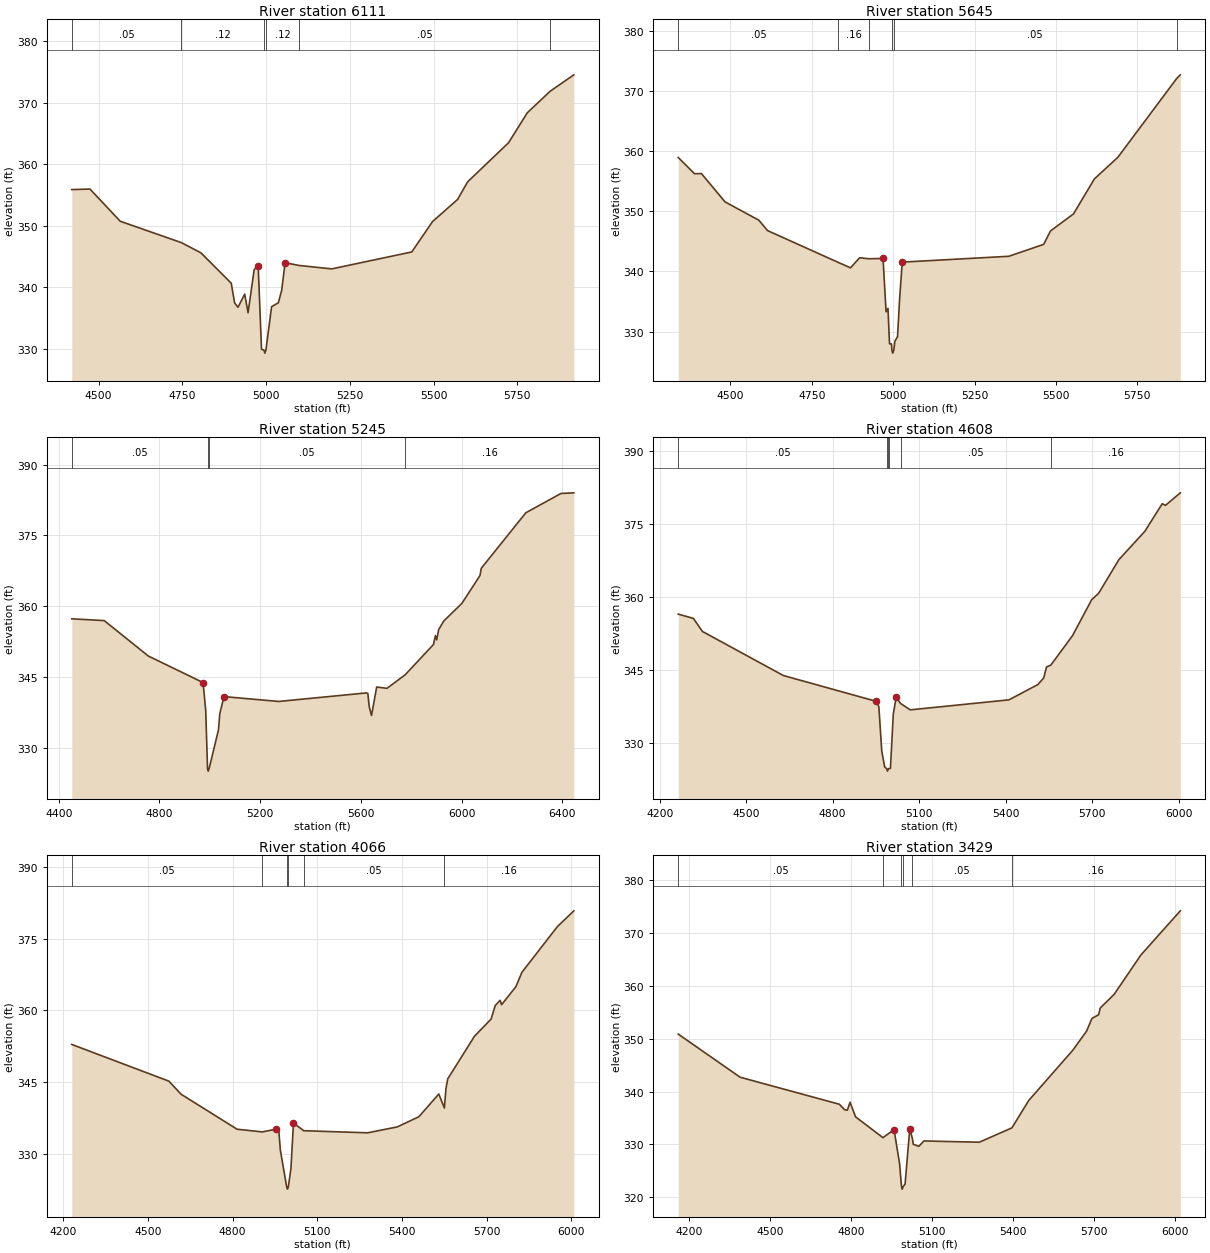
Type RM Length L Ch R = 1 ,6111    ,466,466,466
BEGIN DESCRIPTION:
UNT162 IN CCTC 12.0
END DESCRIPTION:
XS GIS Cut Line= 3
       3558654.1     10641514.29      3558723.54     10640764.33
      3558467.03      10640064.1
#Sta/Elev= 30
  4419.8  355.88  4474.1  355.97  4564.5  350.74  4746.8  347.27  4805.5   345.6
  4895.9  340.67    4906  337.47    4916  336.76  4936.1   338.9  4946.1  335.87
  4964.4  342.89  4976.3   343.5  4986.3  329.93  4993.4  329.81  4996.1  329.31
  4999.4  329.81  5016.4  336.86  5036.5  337.49  5046.6  339.55  5056.6     344
  5098.8  343.55  5196.1     343  5434.9  345.75  5496.9  350.69  5571.4  354.27
    5602  357.16    5724  363.51  5779.7  368.36  5847.9  371.86  5918.7  374.53
#Mann= 6 ,-1 , 0
  4419.8     .05       0  4746.8     .12       0  4993.4     .07       0
  4999.4     .12       0  5098.8     .05       0  5847.9     .16       0
Bank Sta=4976.3,5056.6
XS Rating Curve= 0 ,0
Exp/Cntr=0.3,0.1

Type RM Length L Ch R = 1 ,5645    ,400,400,400
BEGIN DESCRIPTION:
UNT162 IN CCTC 11.0
END DESCRIPTION:
XS GIS Cut Line= 3
      3559449.63     10641360.23      3559099.61     10640810.19
       3558549.6     10640110.18
#Sta/Elev= 30
  4339.7  358.94  4389.7  356.24  4410.9  356.26  4483.7  351.55    4587  348.53
  4614.1  346.79  4831.7  341.49  4868.9   340.6  4896.8  342.27    4925  342.11
  4968.8  342.16  4978.1   333.3    4984  333.86  4988.7  327.97  4994.8  327.97
  4995.9  326.93  4998.6  326.43  5001.9  326.93  5005.2  328.42  5013.3  329.16
  5019.7  335.46  5027.8  341.55    5355  342.52  5462.2   344.5  5483.3  346.74
  5553.8  349.56    5618  355.38  5690.3  358.98  5870.9  372.07  5881.9  372.67
#Mann= 6 ,-1 , 0
  4339.7     .05       0  4831.7     .16       0    4925     .05       0
  4995.9     .03       0  5001.9     .05       0  5870.9     .16       0
Bank Sta=4968.8,5027.8
XS Rating Curve= 0 ,0
Exp/Cntr=0.3,0.1

Type RM Length L Ch R = 1 ,5245    ,637,637,637
BEGIN DESCRIPTION:
UNT162 IN CCTC 10.0
END DESCRIPTION:
XS GIS Cut Line= 3
      3559556.88     10641424.04      3559355.49     10640674.05
      3559626.33      10639486.5
#Sta/Elev= 30
  4451.6  357.35  4580.5  356.97  4755.9  349.46  4973.3  343.84  4983.7  338.01
    4991  325.58  4993.8  325.08    4997  325.58  5034.5  333.84  5039.7  337.24
  5056.1  340.87  5273.7  339.84  5621.9  341.65    5628  341.52  5633.1  338.78
  5642.4  336.87  5662.9   342.9  5703.9  342.62  5776.1  345.49  5888.6  351.91
  5896.2  353.78  5901.4  352.89  5909.1  355.06  5929.6  356.89  6001.4  360.62
  6073.2   366.5  6078.5  368.06  6255.6  379.82  6394.9   383.9  6446.2  384.04
#Mann= 4 ,-1 , 0
  4451.6     .05       0    4991     .03       0    4997     .05       0
  5776.1     .16       0
Bank Sta=4973.3,5056.1
XS Rating Curve= 0 ,0
Exp/Cntr=0.3,0.1

Type RM Length L Ch R = 1 ,4608    ,542,542,542
BEGIN DESCRIPTION:
UNT162 IN CCTC 9.0
END DESCRIPTION:
XS GIS Cut Line= 2
      3559880.14     10641453.94      3560019.03     10639717.79
#Sta/Elev= 30
  4264.5  356.56    4317  355.69  4348.5     353  4629.4  343.94  4951.5  338.64
  4960.5  337.53  4970.5  328.44  4980.5  325.18  4987.6   324.8  4990.3   324.3
  4993.6   324.8  4994.3  324.81  5000.6  324.86  5010.6  336.08  5020.7   339.5
  5035.6  338.21  5069.4  336.89  5411.9  338.95  5512.2  342.09  5532.3  343.45
  5542.3  345.71  5557.2   346.1  5632.6  352.17  5698.9  359.54  5722.9  360.84
  5793.1  367.75  5883.4   373.6  5943.6  379.26  5954.7  378.91  6006.2  381.49
#Mann= 6 ,-1 , 0
  4264.5     .05       0  4987.6     .07       0  4993.6     .05       0
  4994.3     .16       0  5035.6     .05       0  5557.2     .16       0
Bank Sta=4951.5,5020.7
XS Rating Curve= 0 ,0
Exp/Cntr=0.3,0.1

Type RM Length L Ch R = 1 ,4066    ,637,637,637
BEGIN DESCRIPTION:
UNT162 IN CCTC 7.0
END DESCRIPTION:
XS GIS Cut Line= 2
      3560206.52     10641627.55      3560754.53     10639934.95
#Sta/Elev= 30
  4229.8   352.9  4573.9  345.24  4617.2  342.51  4815.6  335.21  4904.9  334.65
  4952.3   335.2  4962.8  335.28  4969.2  330.73  4991.3  323.21  4994.1  322.71
  4997.3  323.21  5006.4     327  5015.4  336.51  5051.8   334.9  5278.1  334.46
  5383.2  335.69  5459.7  337.81  5530.4  342.56  5550.1  339.64  5555.7  343.68
  5561.9   345.7  5656.9  354.62  5715.6  358.18  5730.1  360.99  5747.6  362.11
  5752.9   361.2  5803.7  364.96  5824.7  367.94  5950.8   377.5  6008.9  380.78
#Mann= 6 ,-1 , 0
  4229.8     .05       0  4904.9     .16       0  4991.3     .07       0
  4997.3     .16       0  5051.8     .05       0  5550.1     .16       0
Bank Sta=4952.3,5015.4
XS Rating Curve= 0 ,0
Exp/Cntr=0.3,0.1

Type RM Length L Ch R = 1 ,3429    ,554,554,554
BEGIN DESCRIPTION:
UNT162 IN CCTC 5.0
END DESCRIPTION:
XS GIS Cut Line= 2
      3560894.04     10641905.27      3561241.26     10640078.89
#Sta/Elev= 30
    4159  350.89  4388.1  342.72  4755.3   337.6  4774.9  336.57  4785.1  336.47
  4795.3  337.97  4815.6  335.21  4917.1  331.26  4958.1   332.8  4978.5  326.38
  4985.7  322.01  4988.4  321.51  4991.7  322.01  4998.9  322.43  5016.4  332.99
  5026.3  331.03  5029.4     330  5049.8  329.62  5068.7  330.64  5273.7   330.4
  5394.6  333.12  5456.9  338.31  5619.8  347.82  5670.7  351.42    5691  353.86
  5715.6  354.56  5721.6  355.83    5773  358.42  5872.3  365.89  6018.1  374.25
#Mann= 6 ,-1 , 0
    4159     .05       0  4917.1     .16       0  4985.7     .07       0
  4991.7     .16       0  5026.3     .05       0  5394.6     .16       0
Bank Sta=4958.1,5016.4
XS Rating Curve= 0 ,0
Exp/Cntr=0.3,0.1

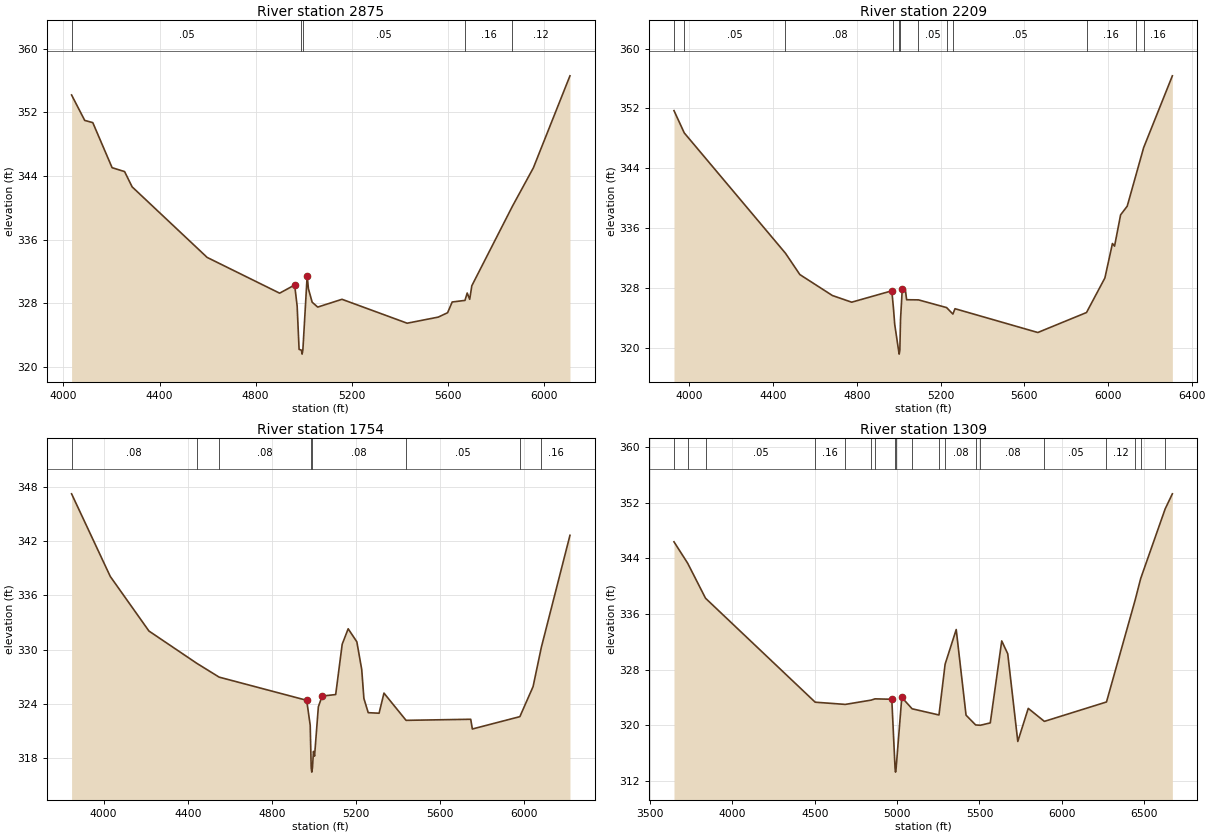
Type RM Length L Ch R = 1 ,2875    ,666,666,666
BEGIN DESCRIPTION:
UNT162 IN CCTC 4.0
END DESCRIPTION:
XS GIS Cut Line= 2
       3561310.7     10642162.24      3561887.08     10640169.21
#Sta/Elev= 30
  4033.8  354.19  4088.5  350.99  4122.1  350.71  4202.5  345.04  4254.5  344.55
  4285.8  342.63  4598.1  333.75  4899.9  329.25  4962.4  330.28  4972.8  327.63
  4980.9  322.18  4990.6  322.08  4993.4  321.58  4996.6  322.08  5014.5  331.43
  5019.7  329.81  5035.3  328.11  5058.5   327.5  5159.4  328.48  5430.8  325.47
  5560.3  326.24  5599.1  326.79  5618.2  328.14  5671.4  328.34  5680.7  329.27
  5691.1  328.48    5700  330.19    5869  340.19  5956.1  345.02  6108.5   356.6
#Mann= 5 ,-1 , 0
  4033.8     .05       0  4990.6     .03       0  4996.6     .05       0
  5671.4     .16       0    5869     .12       0
Bank Sta=4962.4,5014.5
XS Rating Curve= 0 ,0
Exp/Cntr=0.3,0.1

Type RM Length L Ch R = 1 ,2209    ,455,455,455
BEGIN DESCRIPTION:
UNT162 IN CCTC 3.0
END DESCRIPTION:
XS GIS Cut Line= 4
      3561442.61     10642203.94      3562157.92     10641502.52
      3562289.86     10641328.91      3562144.02     10640176.09
#Sta/Elev= 30
  3925.9   351.7  3975.1  348.72  4458.8  332.64  4527.5  329.79  4683.1  326.99
  4775.1   326.1  4966.9  327.62  4974.8  325.31  4980.9  323.12  4999.3  319.66
  5002.1  319.16  5005.3  319.66  5008.6  323.79  5016.9  327.85  5031.1  327.89
  5037.7  326.43  5094.4  326.41  5228.8  325.38  5258.9  324.51  5268.9  325.23
  5664.7  322.05  5897.5  324.72  5985.3  329.34  6021.4  333.94  6031.5  333.59
  6060.4  337.77    6092  338.93  6134.3  343.14  6170.5  346.75  6307.8  356.35
#Mann= 12 ,-1 , 0
  3925.9     .08       0  3975.1     .05       0  4458.8     .08       0
  4974.8     .12       0  4999.3     .07       0  5005.3     .12       0
  5094.4     .05       0  5228.8     .12       0  5258.9     .05       0
  5897.5     .16       0  6134.3     .12       0  6170.5     .16       0
Bank Sta=4966.9,5016.9
XS Rating Curve= 0 ,0
Exp/Cntr=0.3,0.1

Type RM Length L Ch R = 1 ,1754    ,445,445,445
BEGIN DESCRIPTION:
UNT162 IN CCTC 2.0
END DESCRIPTION:
XS GIS Cut Line= 3
      3561849.57     10642360.22      3562649.61     10641560.19
       3562349.6     10640360.14
#Sta/Elev= 30
  3847.7  347.26  4031.6   338.1  4215.4  332.05  4442.9  328.47    4549  326.94
    4965  324.37  4981.7   321.6  4986.4  316.91  4989.2  316.41  4992.4  316.91
  4997.2  318.71  5002.3  318.18  5020.4  323.65  5038.4  324.84  5102.8  325.01
  5133.7  330.59  5162.1   332.3  5203.3  330.86  5226.5  327.79  5236.8  324.58
  5257.4     323    5309  322.94  5332.2  325.17  5437.2  322.15  5744.5  322.27
  5752.2  321.19    5978  322.56  6040.8  325.89  6080.1  330.25  6216.1  342.66
#Mann= 8 ,-1 , 0
  3847.7     .08       0  4442.9     .05       0    4549     .08       0
  4986.4     .07       0  4992.4     .08       0  5437.2     .05       0
    5978     .12       0  6080.1     .16       0
Bank Sta=4965,5038.4
XS Rating Curve= 0 ,0
Exp/Cntr=0.3,0.1

Type RM Length L Ch R = 1 ,1309    ,0,0,0
BEGIN DESCRIPTION:
UNT162 IN CCTC 1.0
END DESCRIPTION:
XS GIS Cut Line= 4
      3562094.59     10642545.02      3563060.26     10641752.95
      3563103.67     10641470.84      3562529.09     10640094.02
#Sta/Elev= 30
  3644.9   346.4  3728.2  343.31  3836.5  338.28  4502.3  323.33  4685.2  323.01
  4842.6  323.63  4865.7  323.81  4967.5  323.75  4987.5  313.77  4990.2  313.27
  4993.5  313.77  5028.2  324.02  5090.9  322.38    5254  321.49  5291.3   328.8
  5358.7  333.78  5418.4  321.46  5476.5  320.06  5504.8  320.01  5565.5  320.35
  5635.1  332.14  5671.6  330.29  5732.6  317.68  5796.1  322.44  5893.9  320.57
  6271.2  323.36  6444.7  337.98    6479  341.13  6627.6  351.14  6671.2   353.3
#Mann= 19 ,-1 , 0
  3644.9     .05       0  3728.2     .08       0  3836.5     .05       0
  4502.3     .16       0  4685.2     .12       0  4842.6     .16       0
  4865.7     .12       0  4987.5     .07       0  4993.5     .12       0
  5090.9     .16       0    5254     .05       0  5291.3     .08       0
  5476.5     .16       0  5504.8     .08       0  5893.9     .05       0
  6271.2     .12       0  6444.7     .16       0    6479     .12       0
  6627.6     .16       0
Bank Sta=4967.5,5028.2
XS Rating Curve= 0 ,0
Exp/Cntr=0.3,0.1

Chan Stop Cuts=-1
Use User Specified Reach Order=0
Composite Channel Slope=5