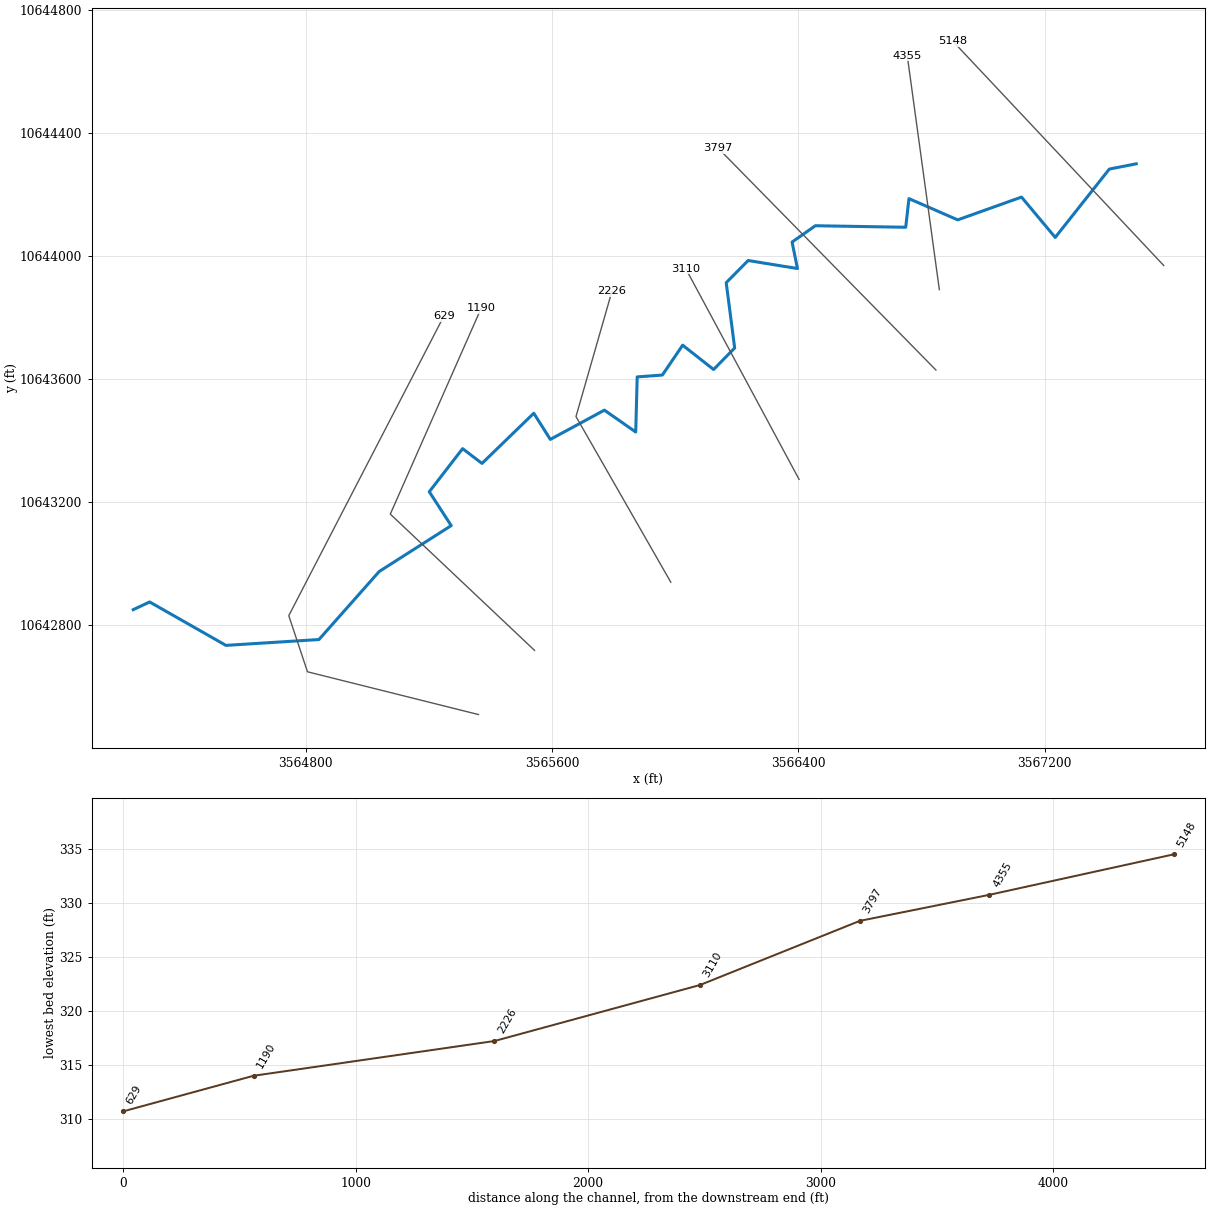
--- UNT163 IN CCTC.prj (project) ---

Proj Title=UNT163 IN CCTC Base Level Engineering
Current Plan=p01
Default Exp/Contr=0.3,0.1
English Units
Geom File=g01
Flow File=f01
Plan File=p01
Y Axis Title=Elevation
X Axis Title(PF)=Main Channel Distance
X Axis Title(XS)=Station
BEGIN DESCRIPTION:
UNT163 IN CCTC
END DESCRIPTION:
DSS Export Rating Curves= 0
DSS Export Rating Curve Sorted= 0
DSS Export Volume Flow Curves= 0
DXF OffsetX= 0
DXF OffsetY= 0
DXF ScaleX= 1
DXF ScaleY= 10

--- UNT163 IN CCTC.p01 (plan) ---

Plan Title=Multiple Run
Short Identifier=Multiple
Geom File=g01
Flow File=f01
Subcritical Flow
K Sum by GR= 0
Std Step Tol= 0.01
Critical Tol= 0.01
Num of Std Step Trials= 20
Max Error Tol= 0.3
Flow Tol Ratio= 0.001
Split Flow NTrial= 30
Split Flow Tol= 0.02
Split Flow Ratio= 0.02
Log Output Level= 0
Friction Slope Method= 1
Unsteady Friction Slope Method= 2
Unsteady Bridges Friction Slope Method= 1
Parabolic Critical Depth
Global Vel Dist=  1 , 1 , 1
Global Log Level= 0
CheckData=True
Encroach Param= -1, 0, 0, 0
BEGIN DESCRIPTION:
Multiple Run
END DESCRIPTION:

--- UNT163 IN CCTC.f01 (steady flow) ---

Flow Title=Multiple
Program Version=4.10
Number of Profiles= 7
Profile Names=10-year,25-year,50-year,1pct_min,100-year,1pct_plu,500-year
River Rch & RM=UNT163 IN CCTC,Reach-1         ,5148
    1379    1897    2325    2081    2814    3806    4107
Boundary for River Rch & Prof#=UNT163 IN CCTC,Reach-1         , 1
Up Type= 0
Dn Type= 3
Dn Slope=0.005
Boundary for River Rch & Prof#=UNT163 IN CCTC,Reach-1         , 2
Up Type= 0
Dn Type= 3
Dn Slope=0.005
Boundary for River Rch & Prof#=UNT163 IN CCTC,Reach-1         , 3
Up Type= 0
Dn Type= 3
Dn Slope=0.005
Boundary for River Rch & Prof#=UNT163 IN CCTC,Reach-1         , 4
Up Type= 0
Dn Type= 3
Dn Slope=0.005
Boundary for River Rch & Prof#=UNT163 IN CCTC,Reach-1         , 5
Up Type= 0
Dn Type= 3
Dn Slope=0.005
Boundary for River Rch & Prof#=UNT163 IN CCTC,Reach-1         , 6
Up Type= 0
Dn Type= 3
Dn Slope=0.005
Boundary for River Rch & Prof#=UNT163 IN CCTC,Reach-1         , 7
Up Type= 0
Dn Type= 3
Dn Slope=0.005
DSS Import GetInterval= 0
DSS Import GetPeak= 0
DSS Import FillOption= 0

--- UNT163 IN CCTC.g01 (geometry) ---

Geom Title=Existing Conditions
Program Version=4.10

River Reach=UNT163 IN CCTC  ,Reach-1
Reach XY= 30
      3567497.92     10644299.04       3567410.5       10644282.
      3567234.75       10644060.      3567125.25       10644191.
        3566918.       10644117.       3566759.5       10644186.
        3566749.       10644093.       3566455.5       10644098.
      3566379.75       10644045.      3566397.25       10643959.
        3566237.       10643985.      3566165.75       10643913.
      3566193.25       10643701.      3566124.75       10643631.
      3566024.25       10643710.      3565958.25       10643613.
       3565876.5       10643607.      3565871.75       10643428.
        3565770.       10643499.      3565594.25       10643404.
       3565540.5       10643489.      3565372.25       10643326.
      3565309.25       10643374.        3565201.       10643234.
      3565272.25       10643124.      3565038.25       10642975.
       3564842.5       10642754.      3564540.25       10642735.
       3564292.5       10642876.        3564239.       10642851.

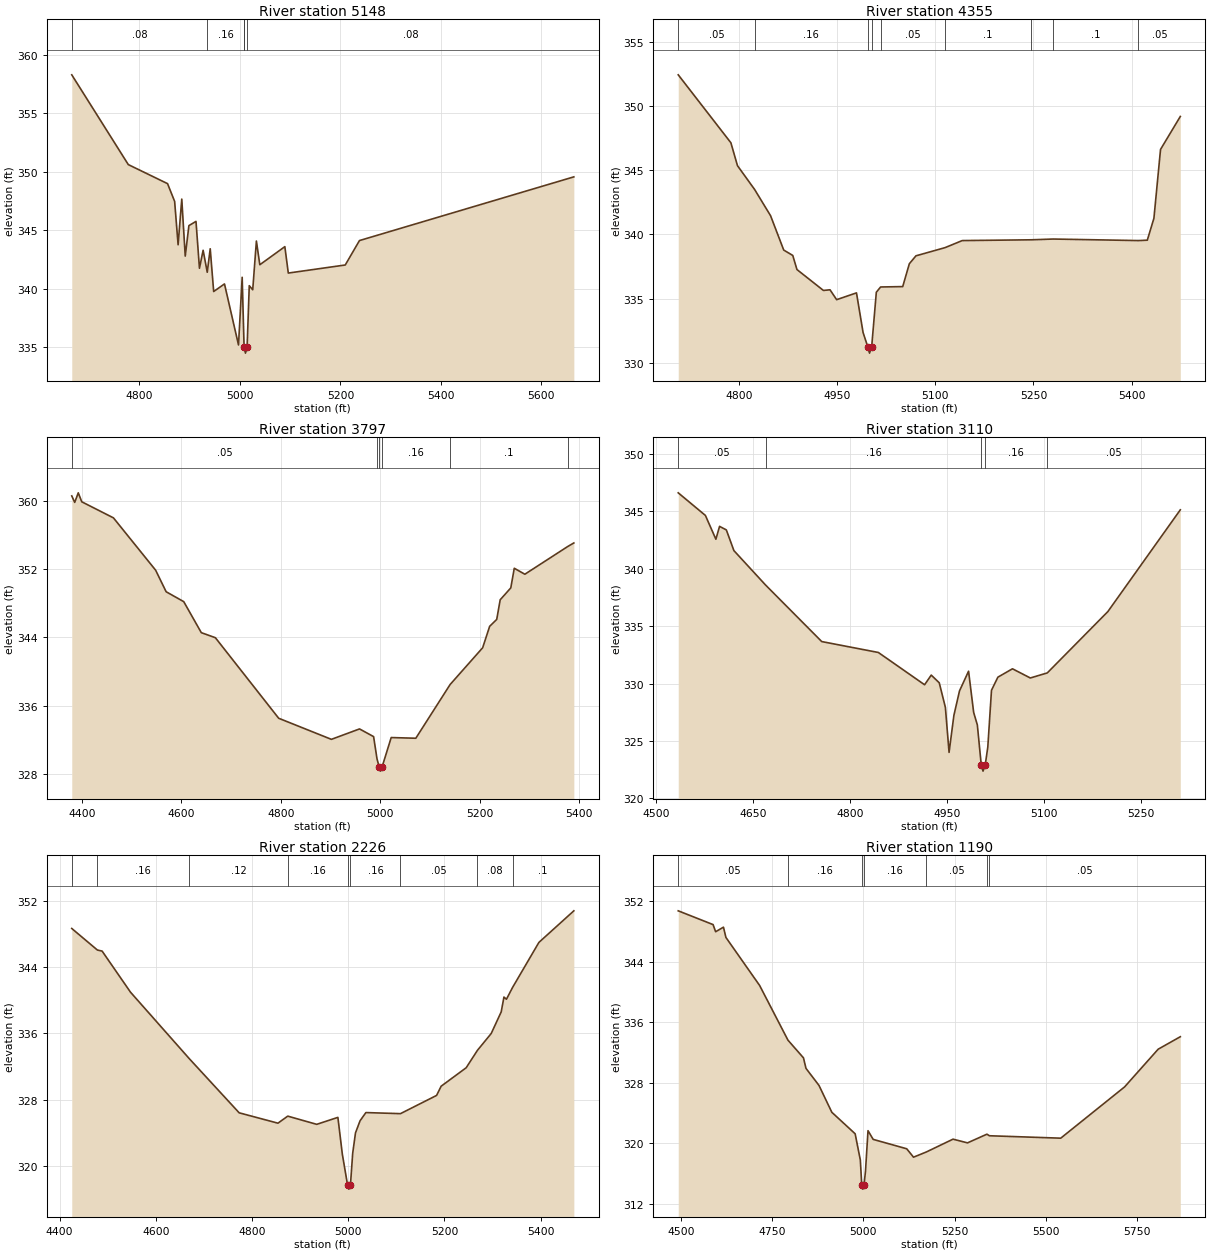
Type RM Length L Ch R = 1 ,5148    ,793,793,793
BEGIN DESCRIPTION:
Mapping XS e7179722
END DESCRIPTION:
XS GIS Cut Line= 2
      3567587.35     10643968.69      3566902.88     10644696.48
#Sta/Elev= 30
  4665.4   358.3  4777.9  350.62    4856  348.99  4870.1  347.47    4877  343.76
  4884.3  347.67  4891.2  342.79  4898.5   345.4  4912.6  345.76  4919.5  341.75
  4926.8  343.29    4935  341.41  4940.9  343.42  4947.8  339.76  4969.3  340.41
  4997.2  335.19  5004.5  340.98  5007.4  336.41  5008.3  334.99  5011.1  334.49
  5014.3  334.99  5018.6  340.26  5025.5  339.91  5032.8  344.08  5039.6  342.05
  5089.4   343.6  5096.3  341.34  5209.6  342.03  5237.9  344.12  5664.5  349.57
#Mann= 5 ,-1 , 0
  4665.4     .08       0    4935     .16       0  5007.4     .08       0
  5008.3     .07       0  5014.3     .08       0
Bank Sta=5008.3,5014.3
XS Rating Curve= 0 ,0
Exp/Cntr=0.3,0.1

Type RM Length L Ch R = 1 ,4355    ,558,558,558
BEGIN DESCRIPTION:
UNT163 IN CCTC 6.0
END DESCRIPTION:
XS GIS Cut Line= 2
      3566858.19     10643890.53      3566754.02     10644650.12
#Sta/Elev= 30
  4707.6  352.45    4788  347.15  4798.1  345.36  4824.2  343.51  4848.6  341.46
  4868.7  338.78  4882.5  338.36  4888.9  337.26  4929.3  335.63  4939.4  335.68
  4949.5  334.91  4979.8  335.44  4989.9  332.34    4997  331.24  4999.7  330.74
    5003  331.24  5010.1  335.49  5016.6   335.9  5050.4  335.93  5060.5  337.71
  5070.6  338.33  5115.1  338.97  5141.3  339.52  5246.6  339.58  5280.2  339.64
  5410.4  339.52  5423.9  339.55    5434  341.26  5444.1  346.63  5474.3   349.2
#Mann= 9 ,-1 , 0
  4707.6     .05       0  4824.2     .16       0    4997     .07       0
    5003     .16       0  5016.6     .05       0  5115.1      .1       0
  5246.6     .15       0  5280.2      .1       0  5410.4     .05       0
Bank Sta=4997,5003
XS Rating Curve= 0 ,0
Exp/Cntr=0.3,0.1

Type RM Length L Ch R = 1 ,3797    ,687,687,687
BEGIN DESCRIPTION:
UNT163 IN CCTC 5.0
END DESCRIPTION:
XS GIS Cut Line= 2
      3566847.14     10643629.27      3566139.71     10644349.72
#Sta/Elev= 30
  4379.7  360.54  4385.6  359.78  4392.8   360.9  4399.8  359.85  4463.5  357.97
  4548.4  351.84  4569.5  349.32  4604.9  348.16  4640.2  344.53  4668.5  343.94
  4795.8  334.51  4901.8  332.04  4958.4  333.26  4986.7  332.36  4993.5  329.78
  4997.8  328.82  5000.6  328.32  5003.8  328.82  5022.1  332.25  5071.6  332.17
  5140.6  338.46    5206  342.76  5220.1  345.27  5234.3  346.08  5241.3  348.38
  5262.6  349.77  5269.6  352.07  5290.9  351.37  5377.5  354.63  5389.4  355.03
#Mann= 6 ,-1 , 0
  4379.7     .05       0  4993.5     .16       0  4997.8     .07       0
  5003.8     .16       0  5140.6      .1       0  5377.5     .05       0
Bank Sta=4997.8,5003.8
XS Rating Curve= 0 ,0
Exp/Cntr=0.3,0.1

Type RM Length L Ch R = 1 ,3110    ,884,884,884
BEGIN DESCRIPTION:
UNT163 IN CCTC 4.0
END DESCRIPTION:
XS GIS Cut Line= 2
      3566402.45     10643274.26       3566034.1     10643958.96
#Sta/Elev= 30
  4533.8  346.61  4575.9  344.64  4592.1  342.57  4597.8  343.69  4608.3  343.38
    4620  341.58  4669.1  338.58    4756  333.66  4843.7  332.71  4915.3   329.9
  4925.6  330.74    4938  330.07  4947.5  327.93  4953.2  324.01  4960.7  327.24
  4969.4  329.37  4983.4  331.08  4991.3  327.49    4997   326.4  5003.1  322.88
  5005.8  322.38  5009.1  322.88  5013.2  324.48  5018.9  329.42  5028.8  330.56
  5051.4  331.29    5079  330.49  5105.3  330.93  5199.1  336.27  5311.3  345.13
#Mann= 5 ,-1 , 0
  4533.8     .05       0  4669.1     .16       0  5003.1     .07       0
  5009.1     .16       0  5105.3     .05       0
Bank Sta=5003.1,5009.1
XS Rating Curve= 0 ,0
Exp/Cntr=0.3,0.1

Type RM Length L Ch R = 1 ,2226    ,1036,1036,1036
BEGIN DESCRIPTION:
UNT163 IN CCTC 3.0
END DESCRIPTION:
XS GIS Cut Line= 3
      3565985.77     10642940.07      3565677.63     10643478.24
      3565794.56     10643885.34
#Sta/Elev= 30
  4425.2  348.65  4478.4  346.05  4488.3  345.92  4547.3  340.96  4669.6  332.93
  4773.2   326.4  4853.8  325.15  4874.2     326  4934.4  325.01  4978.4  325.85
  4987.6  321.43  4998.5  317.69  5001.2  317.19  5004.5  317.69  5009.2  321.53
    5015  323.98  5024.5  325.44  5036.6  326.43  5108.5   326.3  5183.6   328.5
    5193  329.61  5245.1  331.84  5268.6  333.95  5297.1  335.97  5317.9  338.58
  5323.6  340.37  5328.8  340.11  5341.5  341.53  5396.3  346.97  5468.9  350.78
#Mann= 9 ,-1 , 0
  4425.2     .05       0  4478.4     .16       0  4669.6     .12       0
  4874.2     .16       0  4998.5     .07       0  5004.5     .16       0
  5108.5     .05       0  5268.6     .08       0  5341.5      .1       0
Bank Sta=4998.5,5004.5
XS Rating Curve= 0 ,0
Exp/Cntr=0.3,0.1

Type RM Length L Ch R = 1 ,1190    ,561,561,561
BEGIN DESCRIPTION:
UNT163 IN CCTC 2.0
END DESCRIPTION:
XS GIS Cut Line= 3
       3565543.1     10642718.67      3565074.33      10643161.4
      3565369.49     10643829.84
#Sta/Elev= 30
    4493  350.73  4588.5  348.91  4595.4  347.97  4616.9  348.57  4623.7  347.21
    4716  340.87  4793.7  333.64  4836.1  331.31    4843  329.92  4878.6  327.67
  4913.8  324.12  4977.7  321.28  4991.9  317.81  4995.8  314.47  4998.5  313.97
  5001.8  314.47    5006  316.32  5012.9  321.69  5027.1  320.54  5118.9   319.3
  5137.6  318.19  5172.4  318.87  5245.8  320.57  5285.5  320.08  5338.8  321.23
  5345.4  321.02  5540.9   320.7  5715.8  327.47  5807.8  332.45  5868.5   334.1
#Mann= 7 ,-1 , 0
    4493     .05       0  4793.7     .16       0  4995.8     .07       0
  5001.8     .16       0  5172.4     .05       0  5338.8     .16       0
  5345.4     .05       0
Bank Sta=4995.8,5001.8
XS Rating Curve= 0 ,0
Exp/Cntr=0.3,0.1

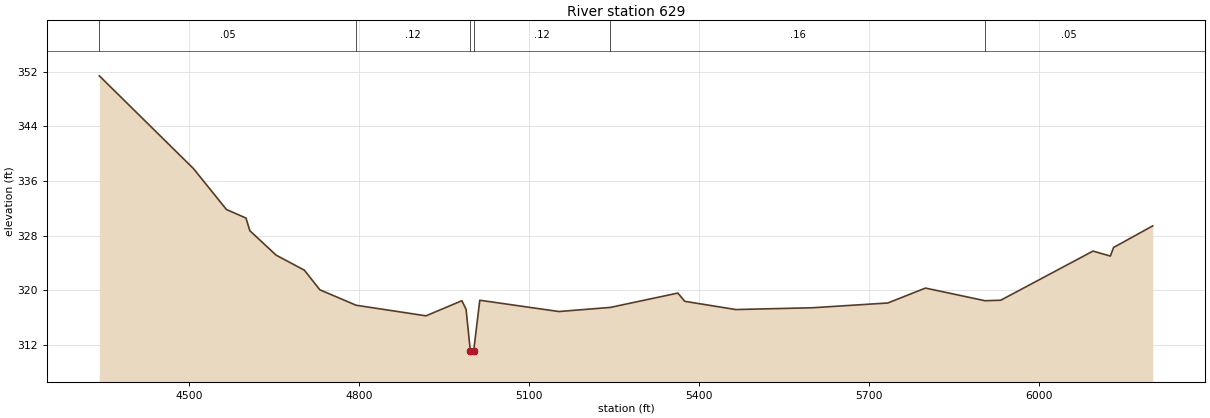
Type RM Length L Ch R = 1 ,629     ,0,0,0
BEGIN DESCRIPTION:
UNT163 IN CCTC 1.0
END DESCRIPTION:
XS GIS Cut Line= 4
      3565360.75     10642510.36      3564805.23     10642649.24
      3564744.47     10642831.53      3565247.94     10643803.74
#Sta/Elev= 30
  4341.4  351.37  4507.5  337.81  4565.8  331.82  4600.3  330.57  4607.1  328.72
  4653.4  325.15  4703.3  322.95  4730.7  320.08  4794.6  317.82  4918.1  316.27
  4981.4  318.48  4988.8  317.22  4996.3  311.17  4999.1  310.67  5002.3  311.17
    5013  318.55  5152.6   316.9  5243.4   317.5  5362.7   319.6  5374.9  318.39
    5465  317.19  5600.1  317.45  5733.4  318.15  5799.8  320.33  5904.9  318.48
  5932.6  318.55  6095.6  325.74  6126.2  325.01  6131.8  326.26    6201  329.43
#Mann= 6 ,-1 , 0
  4341.4     .05       0  4794.6     .12       0  4996.3     .07       0
  5002.3     .12       0  5243.4     .16       0  5904.9     .05       0
Bank Sta=4996.3,5002.3
XS Rating Curve= 0 ,0
Exp/Cntr=0.3,0.1

Chan Stop Cuts=-1
Use User Specified Reach Order=0
Composite Channel Slope=5