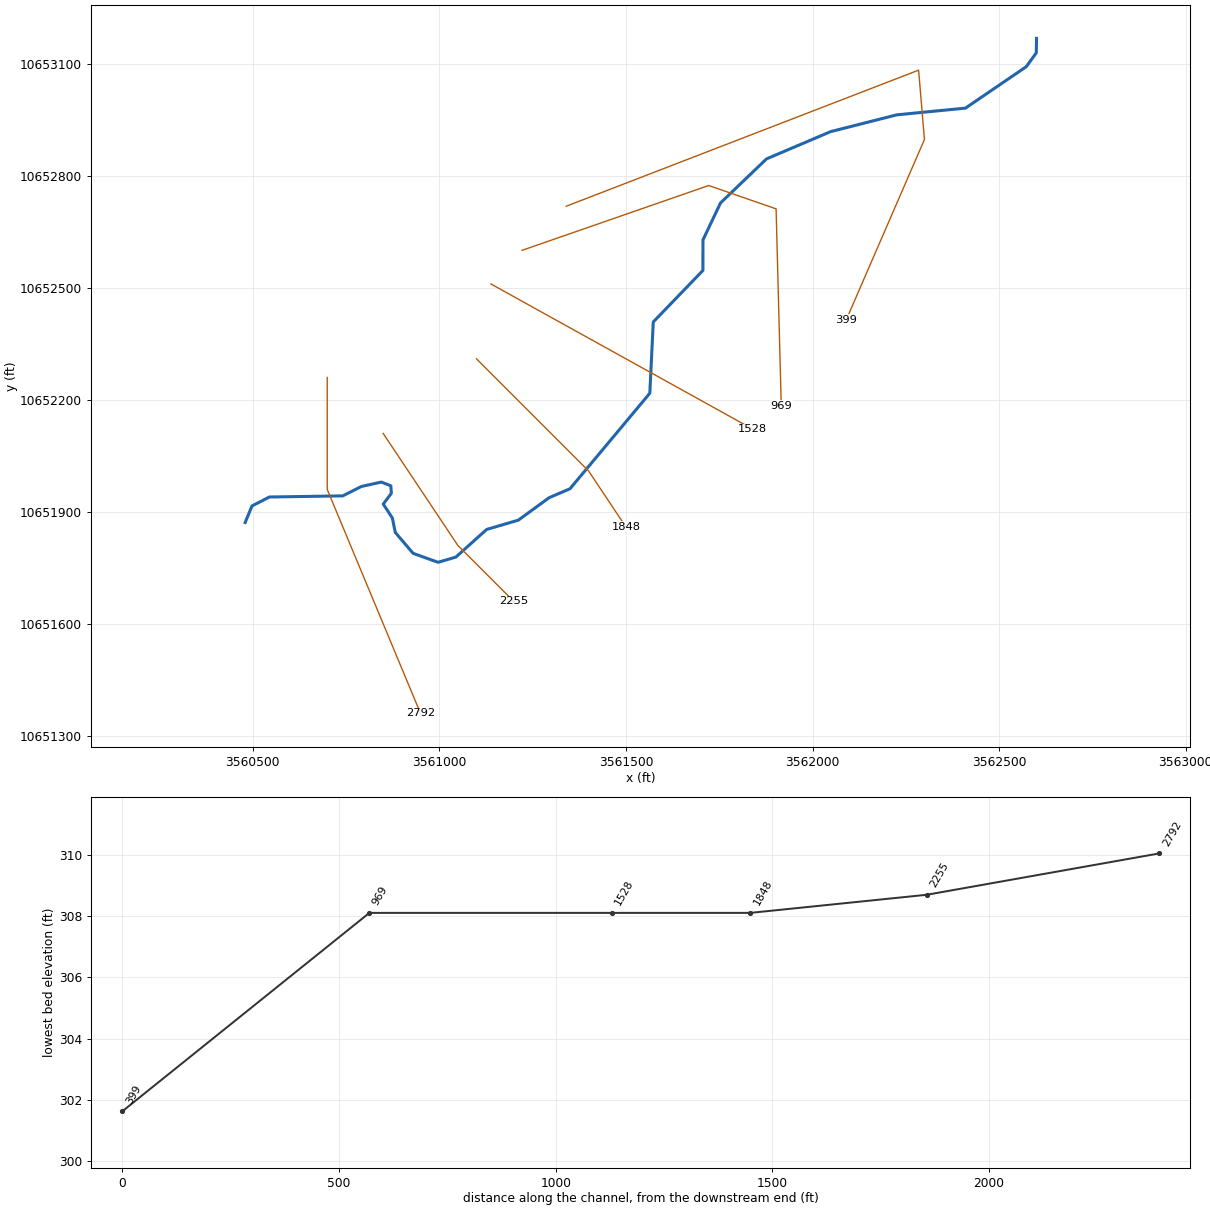
--- UNT165 IN CCTC.prj (project) ---

Proj Title=UNT165 IN CCTC Base Level Engineering
Current Plan=p01
Default Exp/Contr=0.3,0.1
English Units
Geom File=g01
Flow File=f01
Plan File=p01
BEGIN DESCRIPTION:
UNT165 IN CCTC
END DESCRIPTION:

--- UNT165 IN CCTC.p01 (plan) ---

Plan Title=Multiple Run
Short Identifier=Multiple
Geom File=g01
Flow File=f01
Subcritical Flow
K Sum by GR= 0
Std Step Tol= 0.01
Critical Tol= 0.01
Num of Std Step Trials= 20
Max Error Tol= 0.3
Flow Tol Ratio= 0.001
Split Flow NTrial= 30
Split Flow Tol= 0.02
Split Flow Ratio= 0.02
Log Output Level= 0
Friction Slope Method= 1
Unsteady Friction Slope Method= 2
Unsteady Bridges Friction Slope Method= 1
Parabolic Critical Depth
Global Vel Dist=  1 , 1 , 1
Global Log Level= 0
CheckData=True
Encroach Param= -1, 0, 0, 0
BEGIN DESCRIPTION:
Multiple Run
END DESCRIPTION:

--- UNT165 IN CCTC.f01 (steady flow) ---

Flow Title=Multiple
Number of Profiles=7
Profile Names=10-year,25-year,50-year,1pct_min,100-year,1pct_plu,500-year
River Rch & RM= UNT165 IN CCTC,Reach-1,2792
    1030    1388    1676    1478    1999    2703    2832
Boundary for River Rch & Prof#=UNT165 IN CCTC,Reach-1,1
Up Type=0
Dn Type=3
Dn Slope=0.005
Boundary for River Rch & Prof#=UNT165 IN CCTC,Reach-1,2
Up Type=0
Dn Type=3
Dn Slope=0.005
Boundary for River Rch & Prof#=UNT165 IN CCTC,Reach-1,3
Up Type=0
Dn Type=3
Dn Slope=0.005
Boundary for River Rch & Prof#=UNT165 IN CCTC,Reach-1,4
Up Type=0
Dn Type=3
Dn Slope=0.005
Boundary for River Rch & Prof#=UNT165 IN CCTC,Reach-1,5
Up Type=0
Dn Type=3
Dn Slope=0.005
Boundary for River Rch & Prof#=UNT165 IN CCTC,Reach-1,6
Up Type=0
Dn Type=3
Dn Slope=0.005
Boundary for River Rch & Prof#=UNT165 IN CCTC,Reach-1,7
Up Type=0
Dn Type=3
Dn Slope=0.005

--- UNT165 IN CCTC.g01 (geometry) ---

Geom Title=Existing Conditions

River Reach=UNT165 IN CCTC,Reach-1
Reach XY= 30
      3560479.72     10651871.56      3560498.00     10651916.00
      3560544.75     10651940.00      3560741.25     10651943.00
      3560790.75     10651968.00      3560844.50     10651980.00
      3560870.00     10651970.00      3560871.50     10651950.00
      3560849.75     10651921.00      3560874.00     10651884.00
      3560882.00     10651845.00      3560929.75     10651789.00
      3560996.50     10651765.00      3561044.25     10651779.00
      3561126.75     10651853.00      3561211.75     10651878.00
      3561294.00     10651938.00      3561350.00     10651962.00
      3561564.00     10652218.00      3561573.25     10652409.00
      3561706.25     10652547.00      3561706.50     10652629.00
      3561753.50     10652728.00      3561876.75     10652846.00
      3562048.50     10652919.00      3562225.75     10652964.00
      3562409.75     10652982.00      3562572.75     10653093.00
      3562599.50     10653130.00      3562600.25     10653169.00

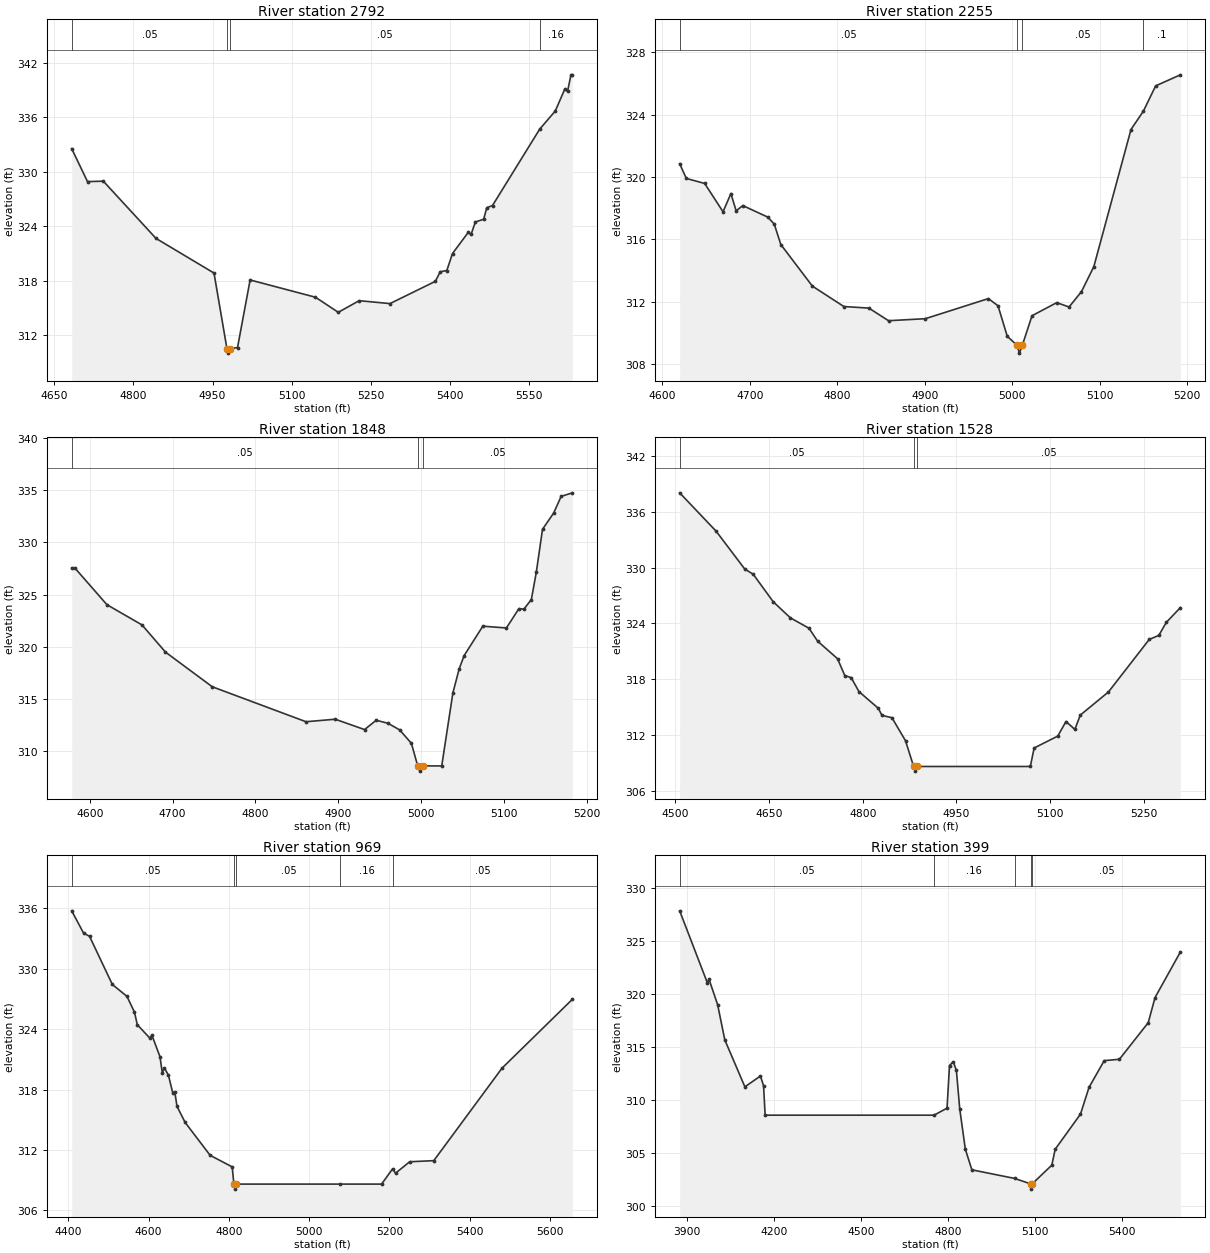
Type RM Length L Ch R = 1,2792,537,537,537
BEGIN DESCRIPTION:
UNT165 IN CCTC 4.0
END DESCRIPTION:
XS GIS Cut Line= 3
      3560699.61     10652260.21      3560699.61     10651960.19
      3560949.60     10651360.20
#Sta/Elev= 30
  4682.8  332.54  4712.8  328.91  4742.8  328.96  4842.8  322.66  4952.8  318.85
  4977.3  310.54  4980.1  310.04  4983.3  310.54  4997.4  310.65  5021.3  318.09
  5145.3  316.19  5188.6  314.53  5228.2  315.81  5286.7  315.49  5372.8  317.94
  5382.0  318.99  5394.5  319.13  5405.3  321.00  5435.1  323.32  5440.5  323.10
  5448.7  324.47  5464.4  324.77  5470.3  326.04  5481.2  326.28  5570.8  334.69
  5600.3  336.68  5618.2  339.07  5623.6  338.85  5630.1  340.66  5632.8  340.66
#Mann=4,-1,0
  4682.8    0.05       0  4977.3   0.035       0  4983.3    0.05       0
  5570.8    0.16       0
Bank Sta=4977.3,4983.3
Exp/Cntr=0.3,0.1

Type RM Length L Ch R = 1,2255,407,407,407
BEGIN DESCRIPTION:
UNT165 IN CCTC 3.0
END DESCRIPTION:
XS GIS Cut Line= 3
      3560849.59     10652110.22      3561049.61     10651810.19
      3561199.59     10651660.21
#Sta/Elev= 30
  4619.8  320.85  4627.4  319.90  4648.4  319.58  4669.4  317.76  4678.4  318.93
  4684.4  317.82  4692.0  318.16  4720.5  317.42  4728.0  316.97  4735.5  315.66
  4771.6  312.99  4807.6  311.68  4836.2  311.58  4858.7  310.77  4900.8  310.90
  4972.9  312.19  4983.9  311.73  4994.5  309.77  5005.7  309.19  5008.4  308.69
  5011.7  309.19  5022.8  311.09  5051.1  311.93  5065.2  311.65  5079.4  312.64
  5093.5  314.24  5136.0  323.04  5150.3  324.23  5164.2  325.84  5192.5  326.55
#Mann=4,-1,0
  4619.8    0.05       0  5005.7   0.035       0  5011.7    0.05       0
  5150.3     0.1       0
Bank Sta=5005.7,5011.7
Exp/Cntr=0.3,0.1

Type RM Length L Ch R = 1,1848,320,320,320
BEGIN DESCRIPTION:
UNT165 IN CCTC 2.0
END DESCRIPTION:
XS GIS Cut Line= 3
      3561099.59     10652310.21      3561399.61     10652010.19
      3561499.63     10651860.16
#Sta/Elev= 30
  4578.1  327.57  4581.7  327.57  4620.6  324.04  4663.0  322.10  4691.3  319.50
  4747.8  316.18  4861.0  312.83  4896.3  313.07  4931.7  312.08  4945.8  312.97
  4960.0  312.68  4974.1  312.05  4988.3  310.76  4995.9  308.60  4998.6  308.10
  5001.9  308.60  5024.9  308.60  5038.4  315.60  5046.0  317.90  5052.0  319.17
  5074.5  321.98  5103.0  321.81  5118.1  323.66  5124.1  323.61  5133.1  324.53
  5139.1  327.14  5146.6  331.26  5160.1  332.82  5169.1  334.41  5182.7  334.75
#Mann=3,-1,0
  4578.1    0.05       0  4995.9   0.035       0  5001.9    0.05       0
Bank Sta=4995.9,5001.9
Exp/Cntr=0.3,0.1

Type RM Length L Ch R = 1,1528,559,559,559
BEGIN DESCRIPTION:
Mapping XS 24d72344
END DESCRIPTION:
XS GIS Cut Line= 2
      3561138.49     10652510.69      3561839.81     10652121.84
#Sta/Elev= 30
  4506.8  338.05  4565.2  333.92  4611.0  329.85  4624.7  329.28  4656.7  326.32
  4684.2  324.59  4713.9  323.48  4727.7  322.09  4759.6  320.20  4771.2  318.39
  4781.5  318.16  4793.9  316.66  4825.0  314.86  4830.7  314.10  4846.7  313.85
  4868.5  311.37  4881.5  308.60  4884.3  308.10  4887.5  308.60  5068.4  308.60
  5074.5  310.59  5112.3  311.87  5125.5  313.44  5139.7  312.59  5148.4  314.13
  5193.5  316.62  5258.8  322.27  5274.2  322.71  5286.2  324.11  5308.7  325.70
#Mann=3,-1,0
  4506.8    0.05       0  4881.5   0.033       0  4887.5    0.05       0
Bank Sta=4881.5,4887.5
Exp/Cntr=0.3,0.1

Type RM Length L Ch R = 1,969,570,570,570
BEGIN DESCRIPTION:
Mapping XS af7c566e
END DESCRIPTION:
XS GIS Cut Line= 4
      3561221.75     10652600.97      3561721.79     10652774.60
      3561902.34     10652712.10      3561916.22     10652184.77
#Sta/Elev= 30
  4408.2  335.76  4437.7  333.55  4452.6  333.23  4509.5  328.44  4545.9  327.26
  4564.7  325.68  4571.7  324.44  4602.9  323.11  4608.2  323.39  4628.2  321.26
  4634.0  319.66  4639.3  320.15  4649.4  319.40  4659.8  317.70  4665.1  317.77
  4670.6  316.33  4690.9  314.73  4753.2  311.46  4808.2  310.31  4812.4  308.60
  4815.2  308.10  4818.4  308.60  5077.7  308.60  5180.5  308.60  5208.0  310.12
  5215.2  309.68  5250.5  310.82  5310.6  310.93  5480.6  320.12  5656.1  326.97
#Mann=5,-1,0
  4408.2    0.05       0  4812.4   0.033       0  4818.4    0.05       0
  5077.7    0.16       0  5208.0    0.05       0
Bank Sta=4812.4,4818.4
Exp/Cntr=0.3,0.1

Type RM Length L Ch R = 1,399,0,0,0
BEGIN DESCRIPTION:
UNT165 IN CCTC 1.0
END DESCRIPTION:
XS GIS Cut Line= 4
      3561339.87     10652719.05      3562284.25     10653083.72
      3562299.87     10652897.95      3562090.20     10652414.30
#Sta/Elev= 30
  3874.2  327.86  3969.8  321.06  3975.1  321.43  4005.1  319.01  4029.7  315.70
  4099.0  311.27  4152.6  312.29  4163.4  311.37  4168.8  308.60  4750.9  308.60
  4795.8  309.26  4804.3  313.28  4817.2  313.64  4828.0  312.82  4839.6  309.18
  4858.8  305.40  4881.4  303.45  5028.5  302.64  5083.5  302.13  5086.3  301.63
  5089.5  302.13  5156.9  303.89  5168.6  305.39  5255.8  308.70  5285.2  311.22
  5337.6  313.74  5390.0  313.87  5489.3  317.32  5512.8  319.69  5600.1  323.98
#Mann=5,-1,0
  3874.2    0.05       0  4750.9    0.16       0  5028.5    0.05       0
  5083.5    0.07       0  5089.5    0.05       0
Bank Sta=5083.5,5089.5
Exp/Cntr=0.3,0.1

Chan Stop Cuts=-1