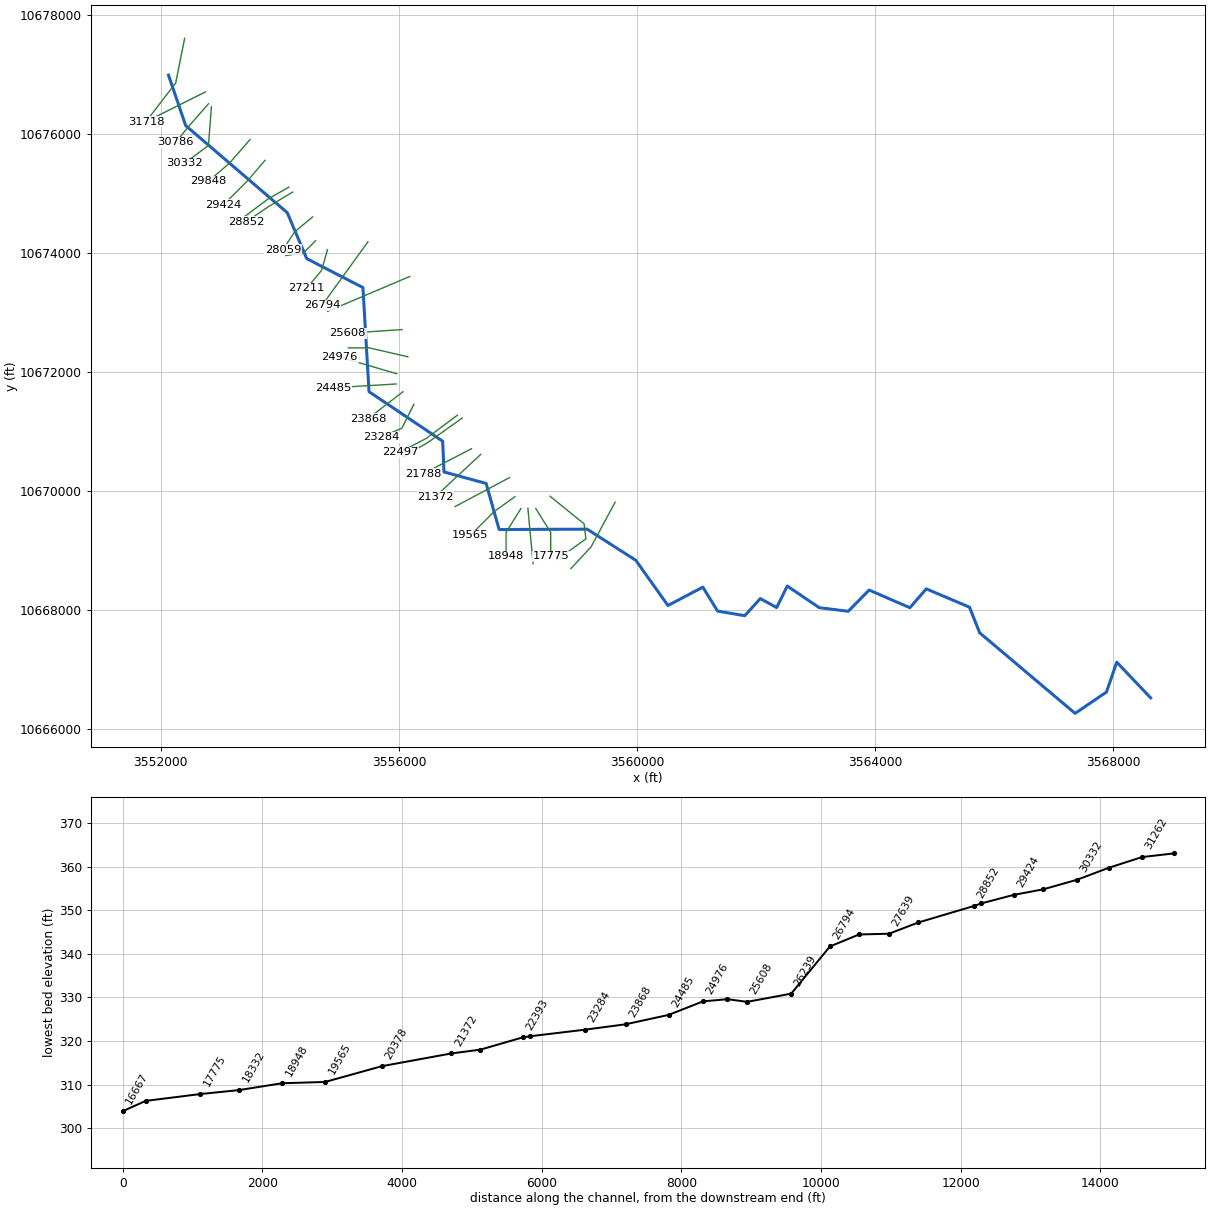
--- UNT166 IN CCTC.prj (project) ---

Proj Title=UNT166 IN CCTC Base Level Engineering
Current Plan=p01
Default Exp/Contr=0.3,0.1
English Units
Geom File=g01
Flow File=f01
Plan File=p01
Y Axis Title=Elevation
X Axis Title(PF)=Main Channel Distance
X Axis Title(XS)=Station
BEGIN DESCRIPTION:
UNT166 IN CCTC
END DESCRIPTION:
DSS Export Rating Curves= 0
DSS Export Rating Curve Sorted= 0
DSS Export Volume Flow Curves= 0
DXF OffsetX= 0
DXF OffsetY= 0
DXF ScaleX= 1
DXF ScaleY= 10

--- UNT166 IN CCTC.p01 (plan) ---

Plan Title=Multiple Run
Short Identifier=Multiple
Geom File=g01
Flow File=f01
Subcritical Flow
K Sum by GR= 0
Std Step Tol= 0.01
Critical Tol= 0.01
Num of Std Step Trials= 20
Max Error Tol= 0.3
Flow Tol Ratio= 0.001
Split Flow NTrial= 30
Split Flow Tol= 0.02
Split Flow Ratio= 0.02
Log Output Level= 0
Friction Slope Method= 1
Unsteady Friction Slope Method= 2
Unsteady Bridges Friction Slope Method= 1
Parabolic Critical Depth
Global Vel Dist=  1 , 1 , 1
Global Log Level= 0
CheckData=True
Encroach Param= -1, 0, 0, 0
BEGIN DESCRIPTION:
Multiple Run
END DESCRIPTION:

--- UNT166 IN CCTC.f01 (steady flow) ---

Flow Title=Multiple
Program Version=4.10
Number of Profiles= 7
Profile Names=10-year,25-year,50-year,1pct_min,100-year,1pct_plu,500-year
River Rch & RM=UNT166 IN CCTC,Reach-1         ,31718
    1935    2699    3337    3004    4063    5495    6011
River Rch & RM=UNT166 IN CCTC,Reach-1         ,24485
    2103    2937    3632    3269    4421    5979    6538
River Rch & RM=UNT166 IN CCTC,Reach-1         ,16667
    3329    4740    5942    5412    7319    9898   11086
River Rch & RM=UNT166 IN CCTC,Reach-1         ,11423
    3486    4971    6236    5685    7688   10397   11661
River Rch & RM=UNT166 IN CCTC,Reach-1         ,7432
    4178    5989    7539    6891    9319   12603   14213
River Rch & RM=UNT166 IN CCTC,Reach-1         ,6218
    4178    5989    7539    6891    9319   12603   14213
Boundary for River Rch & Prof#=UNT166 IN CCTC,Reach-1         , 1
Up Type= 0
Dn Type= 3
Dn Slope=0.005
Boundary for River Rch & Prof#=UNT166 IN CCTC,Reach-1         , 2
Up Type= 0
Dn Type= 3
Dn Slope=0.005
Boundary for River Rch & Prof#=UNT166 IN CCTC,Reach-1         , 3
Up Type= 0
Dn Type= 3
Dn Slope=0.005
Boundary for River Rch & Prof#=UNT166 IN CCTC,Reach-1         , 4
Up Type= 0
Dn Type= 3
Dn Slope=0.005
Boundary for River Rch & Prof#=UNT166 IN CCTC,Reach-1         , 5
Up Type= 0
Dn Type= 3
Dn Slope=0.005
Boundary for River Rch & Prof#=UNT166 IN CCTC,Reach-1         , 6
Up Type= 0
Dn Type= 3
Dn Slope=0.005
Boundary for River Rch & Prof#=UNT166 IN CCTC,Reach-1         , 7
Up Type= 0
Dn Type= 3
Dn Slope=0.005
DSS Import GetInterval= 0
DSS Import GetPeak= 0
DSS Import FillOption= 0

--- UNT166 IN CCTC.g01 (geometry) ---

Geom Title=Existing Conditions

River Reach=UNT166 IN CCTC,Reach-1
Reach XY= 30
      3552128.75     10676991.00      3552417.25     10676144.00
      3554123.75     10674681.00      3554451.25     10673909.00
      3555395.00     10673423.00      3555497.50     10671674.00
      3556734.75     10670842.00      3556756.75     10670325.00
      3557464.50     10670132.00      3557683.75     10669358.00
      3559162.25     10669364.00      3559979.25     10668841.00
      3560519.50     10668081.00      3561105.25     10668390.00
      3561353.25     10667988.00      3561809.50     10667910.00
      3562071.50     10668197.00      3562346.00     10668047.00
      3562524.25     10668408.00      3563061.25     10668045.00
      3563548.25     10667984.00      3563899.50     10668341.00
      3564585.00     10668044.00      3564859.75     10668361.00
      3565585.75     10668053.00      3565756.25     10667623.00
      3567360.00     10666269.00      3567886.75     10666627.00
      3568059.75     10667129.00      3568629.00     10666530.00

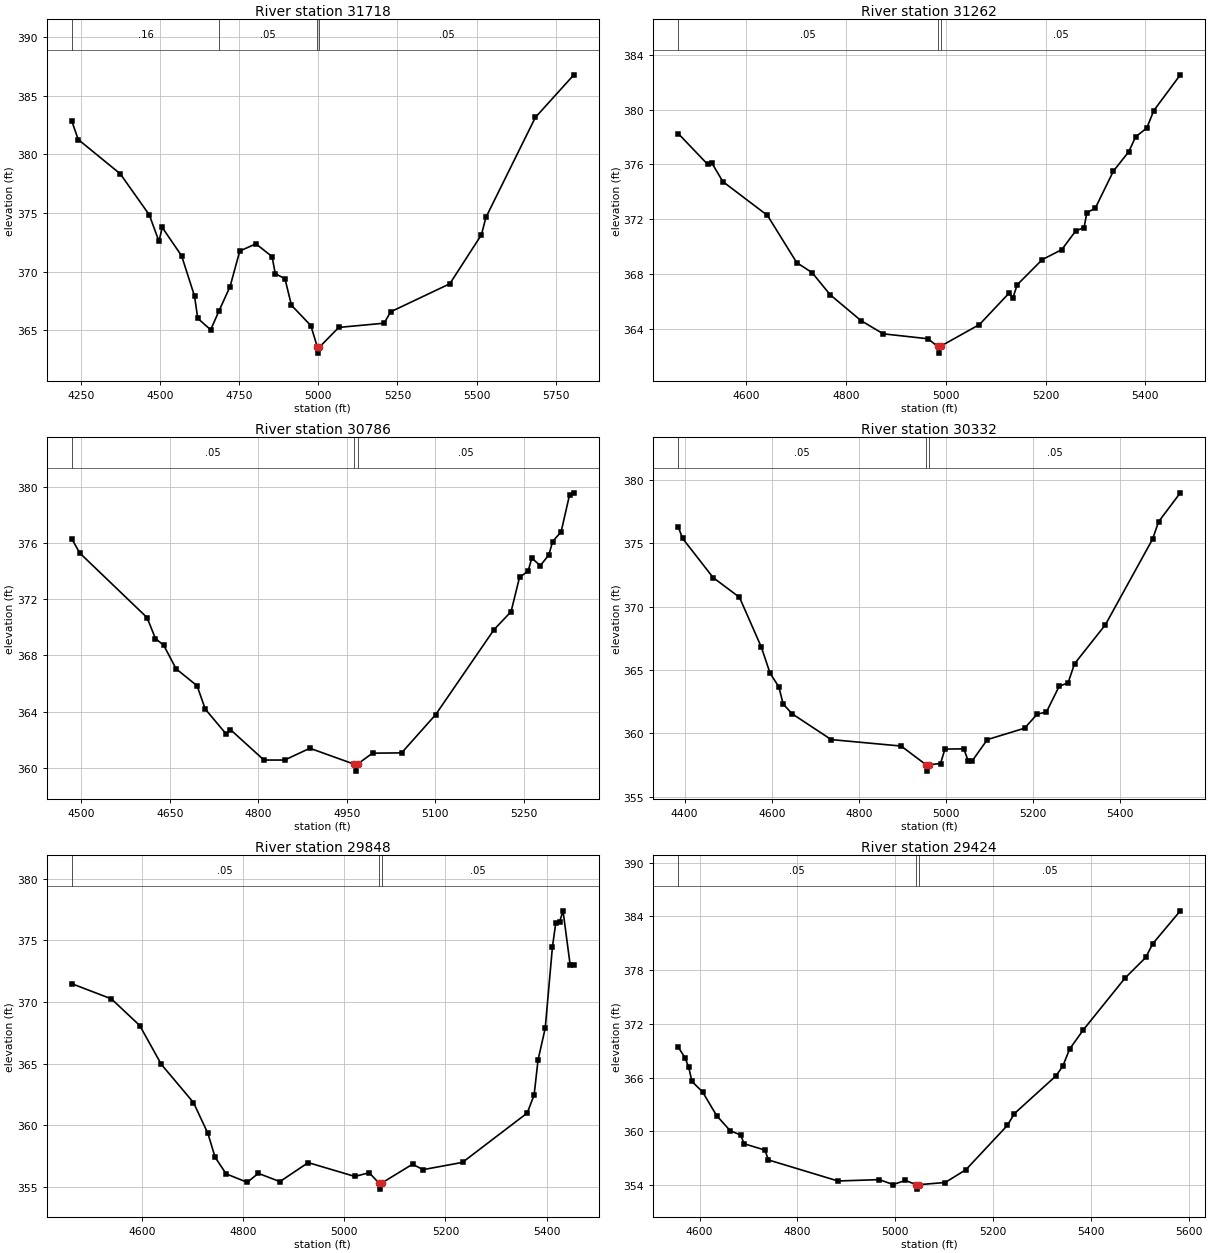
Type RM Length L Ch R = 1,31718,456,456,456
BEGIN DESCRIPTION:
UNT166 IN CCTC 53.0
END DESCRIPTION:
XS GIS Cut Line= 3
      3552399.60     10677610.14      3552249.61     10676860.19
      3551749.59     10676210.16
#Sta/Elev= 30
  4221.9  382.84  4242.2  381.26  4374.8  378.34  4466.6  374.84  4497.2  372.58
  4507.4  373.77  4568.6  371.35  4609.4  367.92  4619.6  366.02  4660.4  365.05
  4687.2  366.69  4721.6  368.73  4752.2  371.76  4803.1  372.37  4854.1  371.29
  4864.3  369.83  4894.9  369.40  4915.3  367.14  4976.5  365.41  4997.3  363.56
  5000.0  363.06  5003.3  363.56  5064.6  365.25  5207.8  365.61  5228.6  366.58
  5415.3  368.97  5515.0  373.14  5529.2  374.62  5685.3  383.14  5806.8  386.77
#Mann=4,-1,0
  4221.9    0.16       0  4687.2    0.05       0  4997.3    0.03       0
  5003.3    0.05       0
Bank Sta=4997.3,5003.3
Exp/Cntr=0.3,0.1

Type RM Length L Ch R = 1,31262,476,476,476
BEGIN DESCRIPTION:
UNT166 IN CCTC 52.0
END DESCRIPTION:
XS GIS Cut Line= 3
      3552749.57     10676710.17      3552249.61     10676460.19
      3551849.60     10676260.18
#Sta/Elev= 30
  4463.7  378.26  4522.4  376.02  4530.7  376.13  4553.1  374.75  4642.5  372.28
  4701.2  368.83  4732.0  368.10  4768.3  366.48  4829.8  364.60  4874.5  363.63
  4964.0  363.27  4983.3  362.72  4986.1  362.22  4989.3  362.72  5067.4  364.31
  5126.1  366.58  5134.5  366.26  5142.9  367.21  5193.2  369.05  5232.3  369.78
  5260.3  371.15  5277.0  371.39  5282.6  372.48  5299.4  372.80  5335.7  375.51
  5366.5  376.93  5380.4  378.02  5402.8  378.67  5416.8  379.94  5469.9  382.55
#Mann=3,-1,0
  4463.7    0.05       0  4983.3    0.03       0  4989.3    0.05       0
Bank Sta=4983.3,4989.3
Exp/Cntr=0.3,0.1

Type RM Length L Ch R = 1,30786,454,454,454
BEGIN DESCRIPTION:
UNT166 IN CCTC 51.0
END DESCRIPTION:
XS GIS Cut Line= 3
      3552799.62     10676510.20      3552449.61     10676110.19
      3552249.59     10675860.17
#Sta/Elev= 30
  4483.6  376.31  4497.4  375.29  4611.3  370.70  4625.5  369.21  4639.7  368.72
  4660.6  367.05  4696.2  365.84  4710.0  364.18  4746.0  362.38  4752.7  362.72
  4809.6  360.55  4844.8  360.55  4887.5  361.39  4962.3  360.26  4965.0  359.76
  4968.3  360.26  4993.8  361.04  5043.1  361.06  5100.8  363.78  5200.0  369.85
  5228.8  371.12  5243.2  373.58  5257.6  374.00  5264.0  374.94  5278.4  374.40
  5292.9  375.17  5299.3  376.12  5313.7  376.81  5328.1  379.46  5335.3  379.59
#Mann=3,-1,0
  4483.6    0.05       0  4962.3    0.03       0  4968.3    0.05       0
Bank Sta=4962.3,4968.3
Exp/Cntr=0.3,0.1

Type RM Length L Ch R = 1,30332,484,484,484
BEGIN DESCRIPTION:
UNT166 IN CCTC 50.0
END DESCRIPTION:
XS GIS Cut Line= 3
      3552849.61     10676460.19      3552799.61     10675810.19
      3552399.63     10675510.20
#Sta/Elev= 30
  4385.5  376.31  4395.5  375.40  4465.7  372.30  4525.9  370.75  4576.1  366.82
  4596.1  364.76  4616.2  363.68  4626.2  362.33  4646.3  361.56  4736.5  359.51
  4897.0  359.00  4954.2  357.52  4956.9  357.02  4960.2  357.52  4987.3  357.62
  4997.3  358.76  5040.5  358.78  5051.0  357.82  5059.3  357.80  5094.7  359.51
  5180.1  360.41  5209.3  361.53  5230.1  361.68  5259.3  363.71  5280.1  364.01
  5294.7  365.50  5365.5  368.58  5473.9  375.35  5487.4  376.71  5537.4  379.00
#Mann=3,-1,0
  4385.5    0.05       0  4954.2    0.03       0  4960.2    0.05       0
Bank Sta=4954.2,4960.2
Exp/Cntr=0.3,0.1

Type RM Length L Ch R = 1,29848,424,424,424
BEGIN DESCRIPTION:
UNT166 IN CCTC 49.0
END DESCRIPTION:
XS GIS Cut Line= 3
      3553499.59     10675910.17      3553149.61     10675510.19
      3552799.58     10675210.16
#Sta/Elev= 30
  4461.3  371.48  4539.6  370.25  4595.6  368.09  4638.3  364.94  4701.9  361.84
  4730.4  359.34  4744.6  357.41  4766.4  356.06  4808.2  355.37  4830.0  356.10
  4872.7  355.43  4928.7  356.97  5020.8  355.85  5049.3  356.15  5068.3  355.32
  5071.0  354.82  5074.3  355.32  5134.9  356.84  5155.8  356.40  5233.7  356.99
  5361.6  360.99  5375.3  362.46  5383.0  365.29  5397.2  367.87  5411.5  374.47
  5418.1  376.41  5425.8  376.52  5432.4  377.39  5446.6  372.97  5453.8  372.97
#Mann=3,-1,0
  4461.3    0.05       0  5068.3    0.03       0  5074.3    0.05       0
Bank Sta=5068.3,5074.3
Exp/Cntr=0.3,0.1

Type RM Length L Ch R = 1,29424,461,461,461
BEGIN DESCRIPTION:
UNT166 IN CCTC 48.0
END DESCRIPTION:
XS GIS Cut Line= 3
      3553749.63     10675560.22      3553449.61     10675210.19
      3553049.61     10674810.19
#Sta/Elev= 30
  4556.2  369.40  4570.0  368.21  4577.6  367.16  4584.2  365.57  4606.2  364.38
  4634.7  361.75  4662.2  360.08  4684.1  359.57  4690.7  358.61  4733.5  357.90
  4740.6  356.80  4882.8  354.45  4967.3  354.60  4995.8  354.05  5020.7  354.52
  5042.5  354.04  5045.2  353.54  5048.5  354.04  5102.1  354.28  5144.5  355.71
  5229.3  360.66  5243.5  361.97  5328.3  366.17  5342.5  367.26  5356.6  369.19
  5384.9  371.35  5469.8  377.11  5512.2  379.41  5526.3  380.93  5582.9  384.62
#Mann=3,-1,0
  4556.2    0.05       0  5042.5    0.03       0  5048.5    0.05       0
Bank Sta=5042.5,5048.5
Exp/Cntr=0.3,0.1

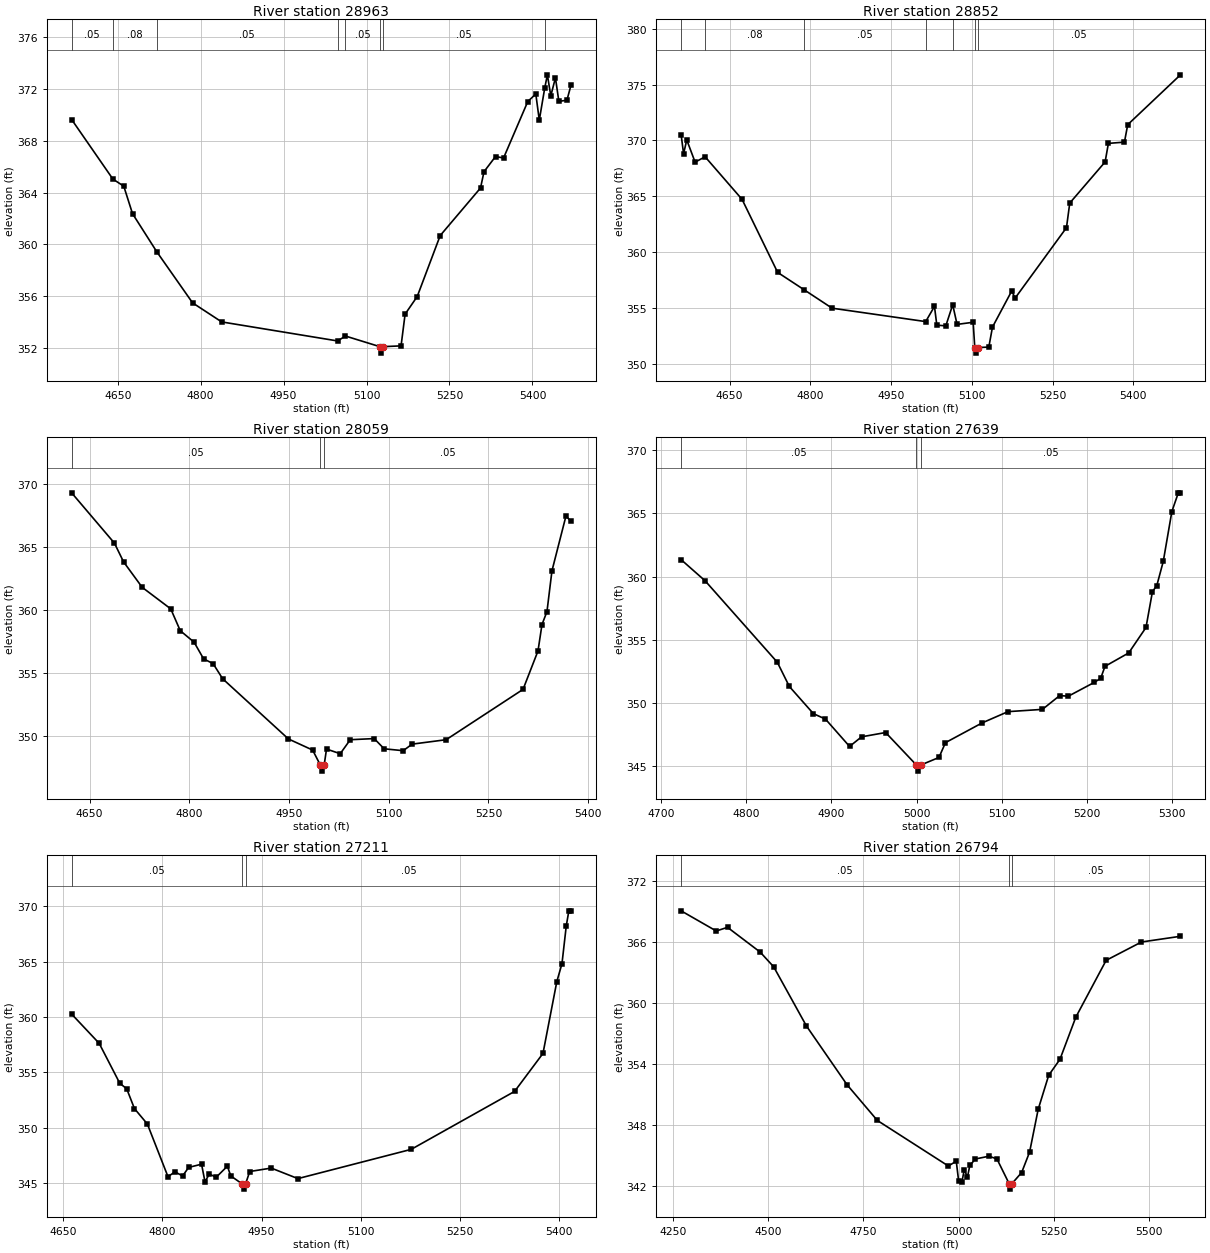
Type RM Length L Ch R = 1,28963,111,111,111
BEGIN DESCRIPTION:
UNT166 IN CCTC 47.0
END DESCRIPTION:
XS GIS Cut Line= 3
      3554149.59     10675110.18      3553799.61     10674910.19
      3553399.60     10674610.18
#Sta/Elev= 30
  4566.6  369.64  4641.2  365.04  4660.9  364.49  4676.7  362.37  4720.7  359.42
  4785.4  355.48  4838.0  354.01  5047.7  352.54  5061.8  352.92  5124.0  352.10
  5126.7  351.60  5130.0  352.10  5162.4  352.16  5169.7  354.61  5191.6  355.97
  5233.2  360.68  5306.1  364.35  5312.4  365.61  5333.2  366.78  5347.8  366.67
  5391.6  371.03  5406.1  371.61  5412.4  369.59  5422.2  372.06  5427.0  373.09
  5433.2  371.47  5441.6  372.86  5447.8  371.04  5462.4  371.13  5469.7  372.29
#Mann=8,-1,0
  4566.6    0.05       0  4641.2    0.08       0  4720.7    0.05       0
  5047.7    0.08       0  5061.8    0.05       0  5124.0    0.03       0
  5130.0    0.05       0  5422.2    0.08       0
Bank Sta=5124,5130
Exp/Cntr=0.3,0.1

Type RM Length L Ch R = 1,28852,793,793,793
BEGIN DESCRIPTION:
UNT166 IN CCTC 46.0
END DESCRIPTION:
XS GIS Cut Line= 3
      3554216.70     10675028.71      3553807.01     10674782.20
      3553435.47     10674528.72
#Sta/Elev= 30
  4559.8  370.53  4564.4  368.81  4570.3  370.05  4585.8  368.06  4604.4  368.54
  4673.1  364.73  4739.2  358.20  4788.6  356.64  4840.3  355.00  5014.3  353.80
  5030.6  355.16  5035.0  353.48  5051.7  353.42  5064.5  355.31  5072.6  353.55
  5102.5  353.74  5105.5  351.48  5108.3  350.98  5111.5  351.48  5131.6  351.52
  5138.4  353.31  5174.3  356.55  5180.3  355.89  5275.9  362.20  5282.0  364.40
  5347.7  368.08  5353.8  369.74  5383.6  369.85  5389.7  371.41  5487.7  375.87
#Mann=7,-1,0
  4559.8    0.05       0  4604.4    0.08       0  4788.6    0.05       0
  5014.3    0.08       0  5064.5    0.05       0  5105.5    0.04       0
  5111.5    0.05       0
Bank Sta=5105.5,5111.5
Exp/Cntr=0.3,0.1

Type RM Length L Ch R = 1,28059,420,420,420
BEGIN DESCRIPTION:
UNT166 IN CCTC 45.0
END DESCRIPTION:
XS GIS Cut Line= 3
      3554549.61     10674610.19      3554249.61     10674360.19
      3554049.59     10674060.17
#Sta/Elev= 30
  4623.0  369.27  4687.4  365.28  4701.1  363.80  4729.1  361.78  4772.1  360.07
  4786.4  358.34  4807.2  357.43  4821.5  356.11  4835.8  355.73  4850.2  354.53
  4949.1  349.76  4985.5  348.88  4996.9  347.71  4999.6  347.21  5002.9  347.71
  5006.4  348.96  5027.0  348.59  5042.1  349.70  5078.1  349.79  5093.1  348.98
  5121.7  348.83  5135.2  349.35  5186.3  349.70  5302.0  353.69  5324.5  356.74
  5330.5  358.83  5338.0  359.86  5345.5  363.09  5366.6  367.44  5374.1  367.00
#Mann=3,-1,0
  4623.0    0.05       0  4996.9   0.035       0  5002.9    0.05       0
Bank Sta=4996.9,5002.9
Exp/Cntr=0.3,0.1

Type RM Length L Ch R = 1,27639,428,428,428
BEGIN DESCRIPTION:
UNT166 IN CCTC 44.0
END DESCRIPTION:
XS GIS Cut Line= 3
      3554599.58     10674210.16      3554399.61     10674010.19
      3554099.65     10673960.20
#Sta/Elev= 30
  4723.3  361.34  4751.5  359.67  4836.4  353.23  4850.5  351.32  4878.8  349.17
  4893.0  348.74  4921.3  346.58  4935.4  347.34  4963.7  347.68  4999.6  345.13
  5002.3  344.63  5005.6  345.13  5026.4  345.71  5034.0  346.88  5077.1  348.44
  5107.5  349.33  5148.0  349.51  5168.3  350.60  5178.4  350.55  5208.9  351.64
  5216.5  351.97  5221.5  352.91  5249.4  353.97  5269.7  355.98  5277.3  358.82
  5282.4  359.29  5290.0  361.20  5300.1  365.14  5307.7  366.62  5310.2  366.62
#Mann=3,-1,0
  4723.3    0.05       0  4999.6   0.035       0  5005.6    0.05       0
Bank Sta=4999.6,5005.6
Exp/Cntr=0.3,0.1

Type RM Length L Ch R = 1,27211,417,417,417
BEGIN DESCRIPTION:
UNT166 IN CCTC 43.0
END DESCRIPTION:
XS GIS Cut Line= 3
      3554799.61     10674060.21      3554699.61     10673710.19
      3554449.63     10673410.22
#Sta/Elev= 30
  4663.1  360.26  4704.7  357.62  4735.9  354.01  4746.3  353.52  4758.0  351.73
  4777.5  350.34  4808.7  345.58  4819.1  346.02  4830.8  345.65  4839.9  346.42
  4859.4  346.71  4864.6  345.12  4871.1  345.82  4881.5  345.53  4898.4  346.53
  4903.6  345.65  4920.1  344.96  4922.9  344.46  4926.1  344.96  4932.2  346.05
  4964.7  346.36  5005.0  345.41  5176.2  348.05  5332.4  353.28  5375.3  356.71
  5396.2  363.19  5404.0  364.81  5410.5  368.23  5414.4  369.58  5417.6  369.58
#Mann=3,-1,0
  4663.1    0.05       0  4920.1   0.035       0  4926.1    0.05       0
Bank Sta=4920.1,4926.1
Exp/Cntr=0.3,0.1

Type RM Length L Ch R = 1,26794,555,555,555
BEGIN DESCRIPTION:
UNT166 IN CCTC 42.0
END DESCRIPTION:
XS GIS Cut Line= 2
      3555478.39     10674190.62      3554710.13     10673127.20
#Sta/Elev= 30
  4270.9  369.04  4363.3  367.06  4392.8  367.42  4478.6  364.99  4514.2  363.54
  4600.1  357.74  4706.8  351.97  4786.5  348.46  4973.0  343.99  4993.8  344.46
  5000.0  342.54  5008.5  342.39  5014.7  343.61  5023.3  342.92  5029.4  344.04
  5044.1  344.68  5079.7  344.95  5100.6  344.69  5133.2  342.22  5135.9  341.72
  5139.2  342.22  5165.6  343.35  5186.5  345.36  5209.0  349.55  5236.7  352.90
  5266.2  354.46  5307.9  358.60  5387.6  364.18  5480.4  365.98  5582.8  366.54
#Mann=3,-1,0
  4270.9    0.05       0  5133.2   0.035       0  5139.2    0.05       0
Bank Sta=5133.2,5139.2
Exp/Cntr=0.3,0.1

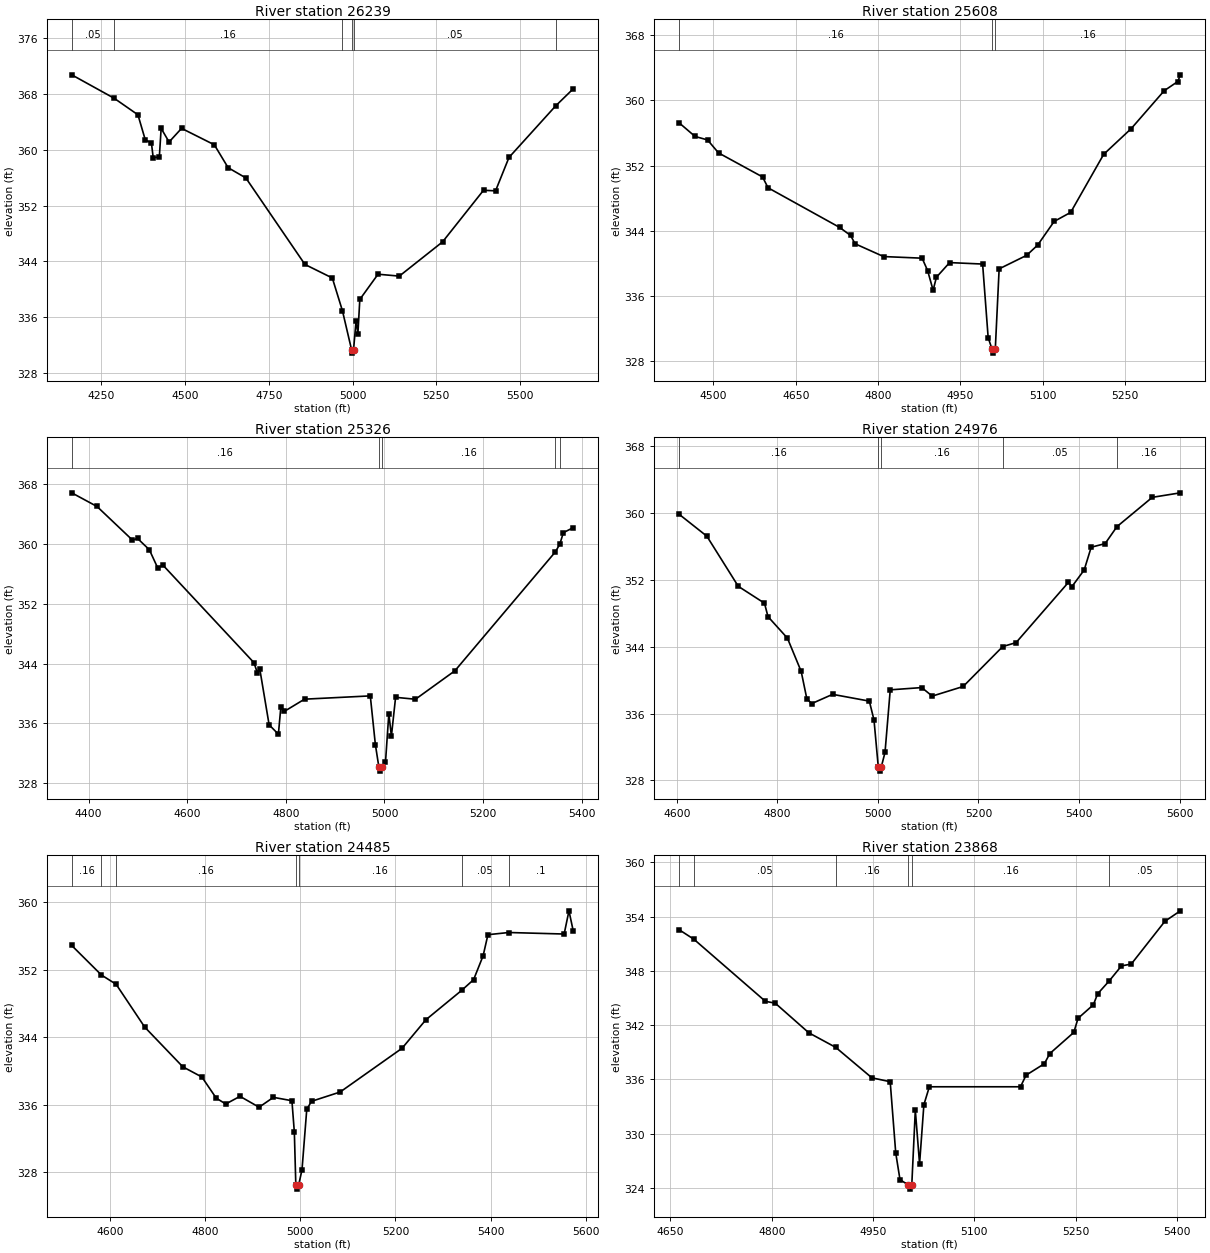
Type RM Length L Ch R = 1,26239,631,631,631
BEGIN DESCRIPTION:
UNT166 IN CCTC 41.0
END DESCRIPTION:
XS GIS Cut Line= 2
      3556181.55     10673609.02      3554802.93     10673023.76
#Sta/Elev= 30
  4161.2  370.70  4288.1  367.34  4358.9  364.98  4380.9  361.38  4399.1  360.97
  4404.5  358.85  4422.8  358.94  4428.2  363.04  4451.9  361.09  4489.2  363.04
  4587.0  360.69  4628.3  357.41  4681.1  355.95  4857.6  343.57  4939.4  341.63
  4969.7  336.93  4996.8  331.38  4999.6  330.88  5002.8  331.38  5010.4  335.54
  5015.8  333.65  5021.5  338.56  5075.9  342.17  5139.5  341.90  5268.7  346.80
  5390.9  354.18  5426.9  354.10  5467.0  358.88  5606.3  366.25  5658.9  368.70
#Mann=6,-1,0
  4161.2    0.05       0  4288.1    0.16       0  4969.7    0.05       0
  4996.8   0.035       0  5002.8    0.05       0  5606.3    0.16       0
Bank Sta=4996.8,5002.8
Exp/Cntr=0.3,0.1

Type RM Length L Ch R = 1,25608,282,282,282
BEGIN DESCRIPTION:
UNT166 IN CCTC 40.0
END DESCRIPTION:
XS GIS Cut Line= 2
      3556051.75     10672717.36      3555140.29     10672654.86
#Sta/Elev= 30
  4436.9  357.29  4466.4  355.59  4489.2  355.16  4509.2  353.57  4589.4  350.62
  4599.4  349.29  4729.7  344.43  4749.8  343.44  4757.9  342.42  4809.9  340.85
  4880.1  340.65  4890.1  339.13  4900.1  336.72  4906.2  338.32  4930.2  340.11
  4990.3  339.93  5000.4  330.90  5007.4  329.50  5010.1  329.00  5013.4  329.50
  5020.4  339.34  5070.5  341.00  5090.6  342.26  5120.6  345.16  5150.7  346.27
  5210.9  353.40  5261.0  356.55  5321.1  361.20  5345.9  362.33  5350.5  363.15
#Mann=3,-1,0
  4436.9    0.16       0  5007.4    0.07       0  5013.4    0.16       0
Bank Sta=5007.4,5013.4
Exp/Cntr=0.3,0.1

Type RM Length L Ch R = 1,25326,350,350,350
BEGIN DESCRIPTION:
UNT166 IN CCTC 39.0
END DESCRIPTION:
XS GIS Cut Line= 3
      3556149.61     10672260.19      3555499.61     10672410.19
      3555149.60     10672410.19
#Sta/Elev= 30
  4365.8  366.86  4417.1  365.03  4489.0  360.53  4499.2  360.76  4523.2  359.24
  4540.3  356.79  4550.5  357.20  4735.3  344.13  4742.1  342.81  4747.2  343.27
  4766.1  335.81  4784.9  334.55  4790.0  338.26  4796.8  337.60  4837.9  339.24
  4971.3  339.68  4981.6  333.16  4988.8  330.11  4991.6  329.61  4994.8  330.11
  5002.1  330.78  5008.9  337.31  5014.1  334.29  5022.6  339.49  5062.9  339.23
  5142.9  343.04  5346.7  358.96  5355.6  359.98  5362.9  361.53  5382.9  362.20
#Mann=5,-1,0
  4365.8    0.16       0  4988.8    0.07       0  4994.8    0.16       0
  5346.7    0.05       0  5355.6    0.16       0
Bank Sta=4988.8,4994.8
Exp/Cntr=0.3,0.1

Type RM Length L Ch R = 1,24976,491,491,491
BEGIN DESCRIPTION:
UNT166 IN CCTC 38.0
END DESCRIPTION:
XS GIS Cut Line= 2
      3555963.04     10671974.75      3555006.10     10672255.59
#Sta/Elev= 30
  4604.1  359.88  4659.8  357.23  4722.3  351.23  4774.4  349.21  4781.4  347.60
  4820.0  345.03  4847.4  341.04  4858.6  337.78  4868.2  337.19  4909.9  338.30
  4982.9  337.49  4992.2  335.23  5000.7  329.61  5003.5  329.11  5006.7  329.61
  5014.1  331.35  5024.5  338.84  5087.1  339.11  5108.0  338.09  5169.5  339.24
  5248.2  344.02  5274.7  344.49  5378.9  351.71  5385.5  351.17  5410.2  353.19
  5424.1  355.91  5451.8  356.34  5475.3  358.37  5545.6  361.88  5601.4  362.42
#Mann=5,-1,0
  4604.1    0.16       0  5000.7    0.07       0  5006.7    0.16       0
  5248.2    0.05       0  5475.3    0.16       0
Bank Sta=5000.7,5006.7
Exp/Cntr=0.3,0.1

Type RM Length L Ch R = 1,24485,617,617,617
BEGIN DESCRIPTION:
UNT166 IN CCTC 37.0
END DESCRIPTION:
XS GIS Cut Line= 2
      3555952.63     10671802.86      3554900.58     10671740.36
#Sta/Elev= 30
  4519.7  354.89  4582.1  351.39  4613.0  350.29  4673.0  345.22  4753.1  340.51
  4793.2  339.30  4823.3  336.80  4843.3  336.10  4873.3  337.01  4913.4  335.72
  4943.5  336.89  4982.4  336.49  4987.5  332.76  4990.6  326.51  4993.3  326.01
  4996.6  326.51  5003.6  328.31  5013.6  335.47  5023.6  336.42  5083.7  337.52
  5213.9  342.71  5264.0  346.09  5339.1  349.57  5364.2  350.84  5384.2  353.67
  5394.3  356.17  5438.0  356.43  5554.5  356.25  5564.6  359.00  5573.6  356.61
#Mann=7,-1,0
  4519.7    0.16       0  4582.1    0.05       0  4613.0    0.16       0
  4990.6    0.07       0  4996.6    0.16       0  5339.1    0.05       0
  5438.0     0.1       0
Bank Sta=4990.6,4996.6
Exp/Cntr=0.3,0.1

Type RM Length L Ch R = 1,23868,584,584,584
BEGIN DESCRIPTION:
UNT166 IN CCTC 36.0
END DESCRIPTION:
XS GIS Cut Line= 2
      3556067.19     10671672.62      3555478.71     10671219.54
#Sta/Elev= 30
  4662.5  352.56  4684.9  351.48  4790.7  344.62  4805.2  344.42  4855.0  341.14
  4894.8  339.53  4948.4  336.16  4975.5  335.73  4983.7  327.86  4990.0  324.90
  5001.5  324.35  5004.3  323.85  5007.5  324.35  5012.7  332.59  5019.0  326.64
  5025.4  333.19  5033.5  335.17  5168.5  335.17  5176.7  336.45  5203.8  337.72
  5212.0  338.85  5247.4  341.18  5253.7  342.74  5276.4  344.24  5282.7  345.45
  5300.0  346.89  5318.0  348.54  5332.5  348.74  5382.3  353.47  5405.2  354.63
#Mann=6,-1,0
  4662.5    0.16       0  4684.9    0.05       0  4894.8    0.16       0
  5001.5    0.07       0  5007.5    0.16       0  5300.0    0.05       0
Bank Sta=5001.5,5007.5
Exp/Cntr=0.3,0.1

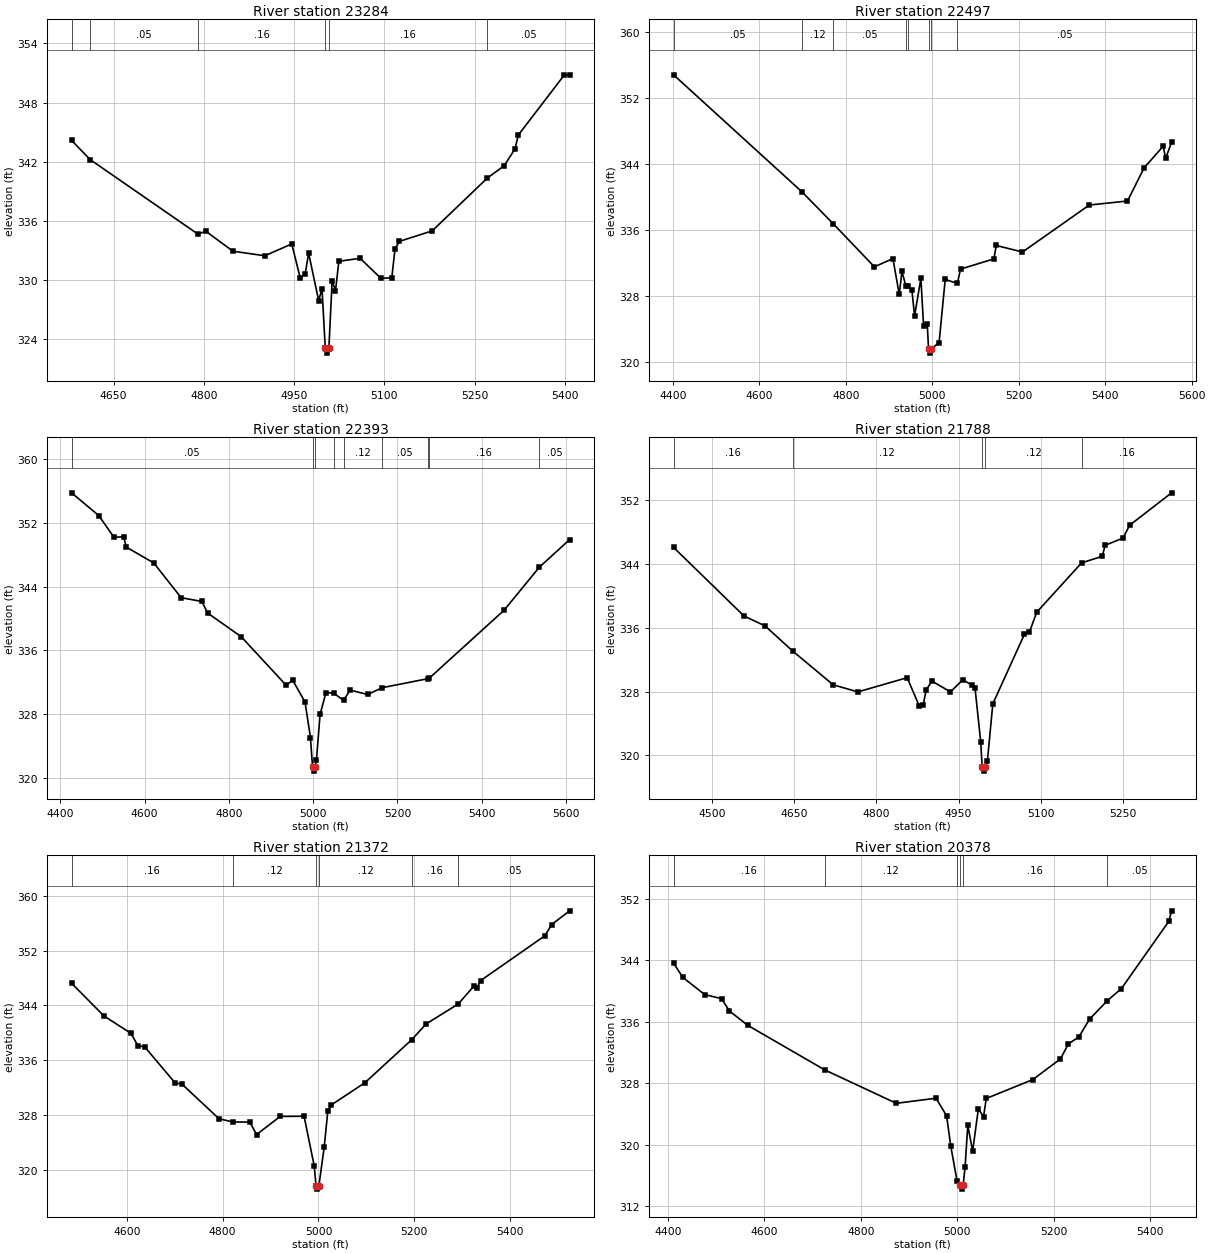
Type RM Length L Ch R = 1,23284,787,787,787
BEGIN DESCRIPTION:
UNT166 IN CCTC 35.0
END DESCRIPTION:
XS GIS Cut Line= 3
      3556249.59     10671460.16      3556049.61     10671060.19
      3555699.58     10670910.17
#Sta/Elev= 30
  4580.0  344.17  4611.1  342.22  4789.7  334.69  4803.6  334.95  4848.3  332.94
  4901.4  332.48  4946.1  333.68  4960.1  330.24  4968.5  330.66  4974.1  332.75
  4990.8  327.94  4996.4  329.13  5001.8  323.11  5004.6  322.61  5007.8  323.11
  5013.2  329.93  5018.8  328.94  5024.4  331.92  5059.8  332.22  5094.3  330.19
  5112.4  330.25  5117.8  333.19  5125.1  333.94  5179.5  335.00  5271.3  340.36
  5299.2  341.60  5317.3  343.32  5322.7  344.71  5398.9  350.78  5408.0  350.82
#Mann=6,-1,0
  4580.0    0.16       0  4611.1    0.05       0  4789.7    0.16       0
  5001.8    0.07       0  5007.8    0.16       0  5271.3    0.05       0
Bank Sta=5001.8,5007.8
Exp/Cntr=0.3,0.1

Type RM Length L Ch R = 1,22497,104,104,104
BEGIN DESCRIPTION:
UNT166 IN CCTC 34.0
END DESCRIPTION:
XS GIS Cut Line= 3
      3556981.63     10671278.22      3556460.83     10670889.36
      3556016.39     10670656.73
#Sta/Elev= 30
  4402.0  354.76  4699.0  340.60  4770.9  336.76  4866.3  331.54  4909.2  332.53
  4923.8  328.21  4930.1  330.98  4938.9  329.27  4943.9  329.16  4953.0  328.73
  4959.3  325.61  4973.9  330.15  4980.1  324.38  4988.5  324.63  4991.7  321.60
  4994.4  321.10  4997.7  321.60  5016.0  322.38  5030.1  330.01  5058.2  329.53
  5065.6  331.26  5142.6  332.50  5148.2  334.12  5208.8  333.33  5363.3  339.01
  5451.6  339.50  5490.1  343.51  5534.2  346.13  5539.8  344.65  5553.6  346.61
#Mann=8,-1,0
  4402.0    0.05       0  4699.0    0.12       0  4770.9    0.05       0
  4938.9    0.12       0  4943.9    0.08       0  4991.7    0.07       0
  4997.7    0.08       0  5058.2    0.05       0
Bank Sta=4991.7,4997.7
Exp/Cntr=0.3,0.1

Type RM Length L Ch R = 1,22393,605,605,605
BEGIN DESCRIPTION:
UNT166 IN CCTC 33.0
END DESCRIPTION:
XS GIS Cut Line= 3
      3557061.51     10671229.63      3556495.56     10670826.86
      3556075.38     10670580.32
#Sta/Elev= 30
  4426.8  355.81  4491.4  352.95  4527.3  350.23  4550.5  350.28  4556.6  348.99
  4621.8  347.00  4686.9  342.63  4736.0  342.16  4749.6  340.71  4829.6  337.72
  4936.5  331.60  4951.3  332.29  4980.8  329.52  4993.7  325.05  4998.7  321.34
  5001.5  320.84  5004.7  321.34  5007.9  322.22  5016.5  327.97  5030.5  330.71
  5048.6  330.65  5072.1  329.73  5087.8  331.02  5129.4  330.47  5164.4  331.33
  5271.8  332.45  5275.9  332.53  5453.0  341.05  5536.6  346.45  5608.6  349.93
#Mann=9,-1,0
  4426.8    0.05       0  4998.7    0.04       0  5004.7    0.05       0
  5048.6    0.08       0  5072.1    0.12       0  5164.4    0.05       0
  5271.8    0.12       0  5275.9    0.16       0  5536.6    0.05       0
Bank Sta=4998.7,5004.7
Exp/Cntr=0.3,0.1

Type RM Length L Ch R = 1,21788,416,416,416
BEGIN DESCRIPTION:
UNT166 IN CCTC 32.0
END DESCRIPTION:
XS GIS Cut Line= 2
      3557218.29     10670714.33      3556410.97     10670297.65
#Sta/Elev= 30
  4430.2  346.07  4558.6  337.48  4597.3  336.22  4647.3  333.09  4721.3  328.85
  4766.3  327.96  4856.3  329.74  4878.8  326.13  4885.3  326.26  4891.0  328.19
  4901.4  329.32  4935.3  327.96  4957.6  329.47  4974.0  328.83  4980.1  328.45
  4990.5  321.70  4993.1  318.53  4995.9  318.03  4999.1  318.53  5002.6  319.24
  5012.6  326.47  5070.2  335.17  5079.1  335.41  5092.7  337.95  5174.5  344.13
  5212.0  344.95  5217.7  346.34  5250.2  347.24  5262.0  348.84  5338.7  352.91
#Mann=5,-1,0
  4430.2    0.16       0  4647.3    0.12       0  4993.1    0.07       0
  4999.1    0.12       0  5174.5    0.16       0
Bank Sta=4993.1,4999.1
Exp/Cntr=0.3,0.1

Type RM Length L Ch R = 1,21372,994,994,994
BEGIN DESCRIPTION:
UNT166 IN CCTC 31.0
END DESCRIPTION:
XS GIS Cut Line= 2
      3557374.50     10670620.55      3556614.39     10669912.50
#Sta/Elev= 30
  4485.0  347.22  4552.4  342.46  4609.0  339.90  4623.2  338.11  4637.4  337.94
  4700.9  332.68  4715.1  332.50  4792.7  327.43  4821.6  326.97  4856.8  326.95
  4870.9  325.13  4920.3  327.78  4970.0  327.80  4991.1  320.56  4994.9  317.66
  4997.7  317.16  5000.9  317.66  5012.1  323.36  5019.4  328.53  5026.3  329.43
  5097.1  332.71  5195.0  339.01  5224.6  341.29  5291.6  344.20  5323.8  346.78
  5330.7  346.49  5338.0  347.60  5472.3  354.16  5486.5  355.80  5523.8  357.80
#Mann=6,-1,0
  4485.0    0.16       0  4821.6    0.12       0  4994.9    0.07       0
  5000.9    0.12       0  5195.0    0.16       0  5291.6    0.05       0
Bank Sta=4994.9,5000.9
Exp/Cntr=0.3,0.1

Type RM Length L Ch R = 1,20378,813,813,813
BEGIN DESCRIPTION:
UNT166 IN CCTC 30.0
END DESCRIPTION:
XS GIS Cut Line= 2
      3557856.68     10670229.65      3556945.62     10669744.67
#Sta/Elev= 30
  4411.9  343.60  4431.2  341.74  4476.6  339.51  4511.4  338.99  4527.7  337.38
  4565.9  335.51  4724.9  329.74  4873.5  325.39  4955.7  326.05  4977.7  323.77
  4986.3  319.86  4999.4  315.29  5006.0  314.74  5008.7  314.24  5012.0  314.74
  5016.0  317.08  5021.6  322.53  5031.7  319.17  5043.6  324.71  5054.2  323.60
  5059.9  326.02  5156.3  328.47  5213.7  331.16  5230.0  333.10  5252.0  334.03
  5273.9  336.32  5310.8  338.73  5339.8  340.28  5438.4  349.05  5444.0  350.40
#Mann=6,-1,0
  4411.9    0.16       0  4724.9    0.12       0  4999.4    0.16       0
  5006.0    0.07       0  5012.0    0.16       0  5310.8    0.05       0
Bank Sta=5006,5012
Exp/Cntr=0.3,0.1

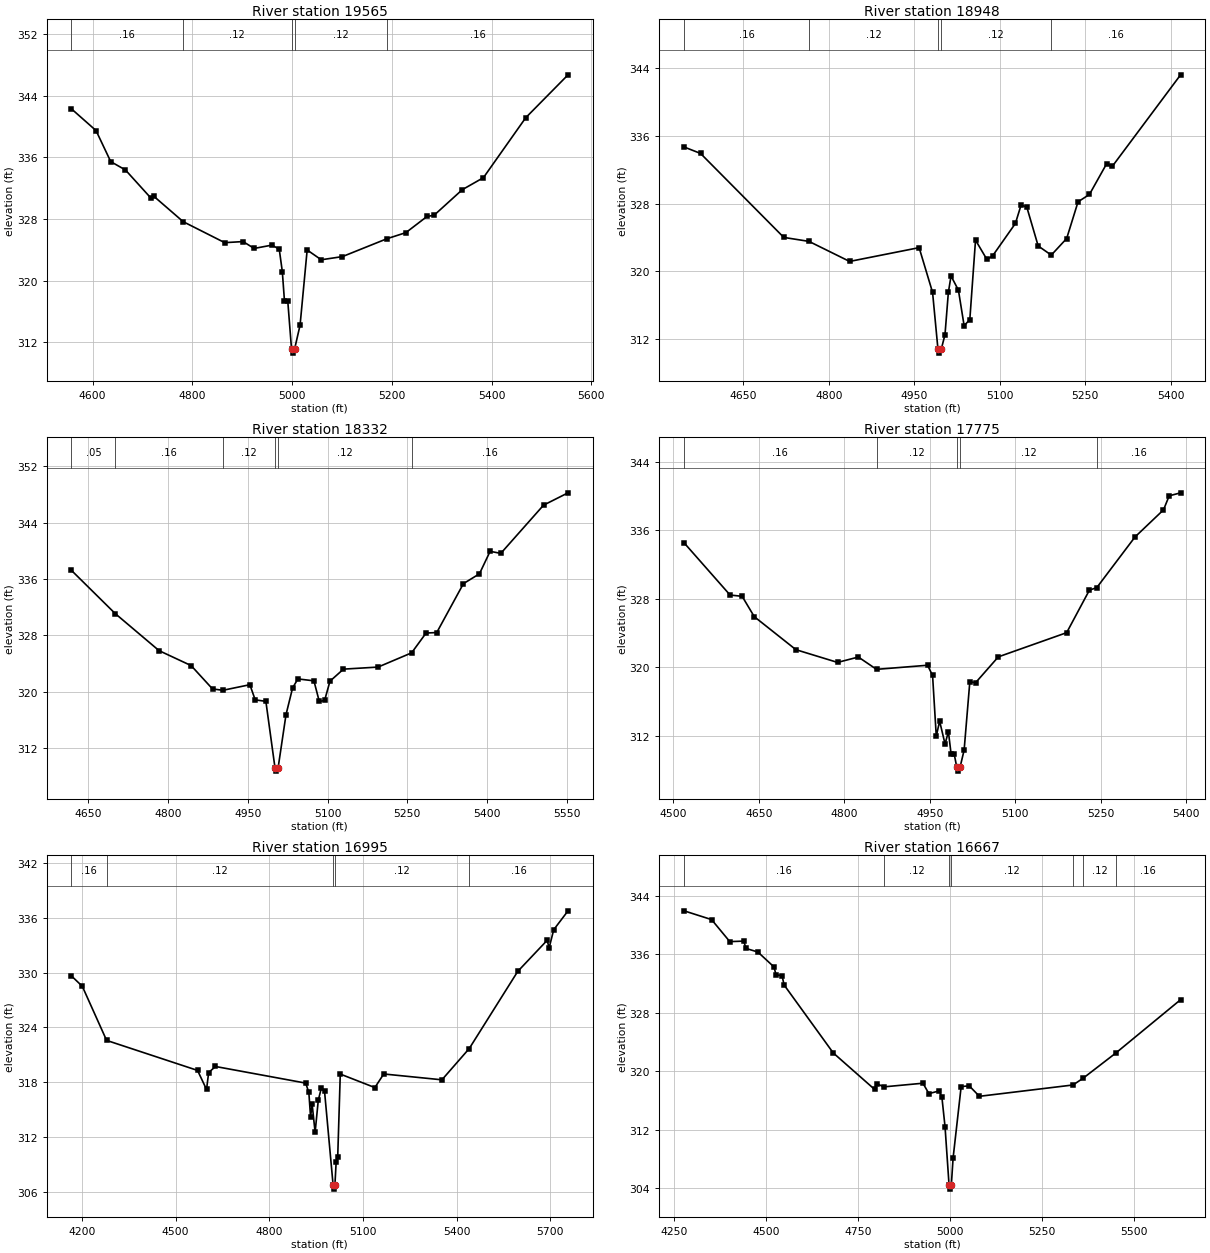
Type RM Length L Ch R = 1,19565,617,617,617
BEGIN DESCRIPTION:
UNT166 IN CCTC 29.0
END DESCRIPTION:
XS GIS Cut Line= 3
      3557949.64     10669910.21      3557599.61     10669660.19
      3557199.64     10669260.22
#Sta/Elev= 30
  4557.6  342.30  4606.8  339.49  4636.3  335.46  4665.8  334.38  4716.2  330.78
  4722.3  330.99  4781.6  327.67  4864.9  324.95  4901.7  325.09  4923.9  324.20
  4959.5  324.63  4974.2  324.11  4980.4  321.20  4984.7  317.39  4991.3  317.39
  4998.9  311.12  5001.6  310.62  5004.9  311.12  5016.0  314.25  5030.2  324.00
  5058.5  322.73  5100.9  323.14  5190.2  325.46  5228.2  326.25  5270.6  328.35
  5284.7  328.50  5341.3  331.82  5383.7  333.38  5468.6  341.16  5553.4  346.72
#Mann=5,-1,0
  4557.6    0.16       0  4781.6    0.12       0  4998.9    0.07       0
  5004.9    0.12       0  5190.2    0.16       0
Bank Sta=4998.9,5004.9
Exp/Cntr=0.3,0.1

Type RM Length L Ch R = 1,18948,616,616,616
BEGIN DESCRIPTION:
UNT166 IN CCTC 28.0
END DESCRIPTION:
XS GIS Cut Line= 3
      3558049.60     10669710.17      3557799.61     10669310.19
      3557799.61     10668910.17
#Sta/Elev= 30
  4545.7  334.69  4574.6  333.93  4720.8  324.00  4765.0  323.53  4836.4  321.16
  4958.4  322.79  4982.0  317.50  4991.4  310.82  4994.1  310.32  4997.4  310.82
  5003.8  312.50  5009.7  317.49  5014.4  319.44  5027.4  317.76  5037.4  313.56
  5047.4  314.29  5057.4  323.68  5077.4  321.39  5087.4  321.82  5127.4  325.65
  5137.4  327.83  5147.4  327.59  5167.4  322.99  5190.4  321.91  5217.4  323.87
  5237.4  328.21  5257.4  329.08  5287.4  332.69  5297.4  332.39  5417.4  343.22
#Mann=5,-1,0
  4545.7    0.16       0  4765.0    0.12       0  4991.4    0.07       0
  4997.4    0.12       0  5190.4    0.16       0
Bank Sta=4991.4,4997.4
Exp/Cntr=0.3,0.1

Type RM Length L Ch R = 1,18332,557,557,557
BEGIN DESCRIPTION:
UNT166 IN CCTC 27.0
END DESCRIPTION:
XS GIS Cut Line= 2
      3558166.19     10669714.28      3558254.52     10668784.26
#Sta/Elev= 30
  4618.1  337.22  4700.2  331.11  4782.9  325.84  4843.2  323.72  4883.4  320.41
  4903.1  320.22  4953.7  321.01  4963.7  318.86  4983.8  318.65  5000.9  309.25
  5003.7  308.75  5006.9  309.25  5021.7  316.77  5034.1  320.56  5044.1  321.83
  5074.2  321.56  5084.3  318.63  5094.3  318.78  5104.4  321.51  5129.8  323.22
  5194.8  323.51  5258.0  325.53  5285.2  328.34  5305.3  328.41  5355.5  335.35
  5385.6  336.74  5405.7  339.93  5425.8  339.64  5506.2  346.48  5552.3  348.23
#Mann=6,-1,0
  4618.1    0.05       0  4700.2    0.16       0  4903.1    0.12       0
  5000.9    0.07       0  5006.9    0.12       0  5258.0    0.16       0
Bank Sta=5000.9,5006.9
Exp/Cntr=0.3,0.1

Type RM Length L Ch R = 1,17775,780,780,780
BEGIN DESCRIPTION:
UNT166 IN CCTC 26.0
END DESCRIPTION:
XS GIS Cut Line= 3
      3558299.59     10669710.21      3558549.61     10669310.19
      3558549.61     10668910.22
#Sta/Elev= 30
  4518.7  334.54  4599.5  328.43  4620.7  328.28  4642.0  325.90  4715.1  322.04
  4788.2  320.55  4824.7  321.18  4856.6  319.74  4946.2  320.22  4955.0  319.03
  4961.5  311.93  4967.4  313.68  4976.9  311.01  4982.8  312.46  4987.5  309.85
  4992.9  309.85  4997.4  308.34  5000.2  307.84  5003.4  308.34  5010.4  310.30
  5020.4  318.30  5030.4  318.17  5070.4  321.20  5190.4  324.03  5230.4  329.01
  5243.2  329.29  5310.4  335.22  5360.4  338.39  5370.4  340.03  5390.4  340.38
#Mann=5,-1,0
  4518.7    0.16       0  4856.6    0.12       0  4997.4    0.07       0
  5003.4    0.12       0  5243.2    0.16       0
Bank Sta=4997.4,5003.4
Exp/Cntr=0.3,0.1

Type RM Length L Ch R = 1,16995,328,328,328
BEGIN DESCRIPTION:
UNT166 IN CCTC 25.0
END DESCRIPTION:
XS GIS Cut Line= 4
      3558538.21     10669917.40      3559111.15     10669452.98
      3559141.53     10669201.24      3558655.43     10668849.68
#Sta/Elev= 30
  4166.3  329.63  4200.9  328.50  4278.8  322.57  4570.2  319.28  4599.0  317.19
  4605.8  319.05  4627.7  319.71  4916.7  317.89  4926.8  316.86  4932.3  314.19
  4937.3  315.59  4946.9  312.49  4957.0  316.01  4967.1  317.38  4977.1  316.99
  5004.4  306.77  5007.1  306.27  5010.4  306.77  5014.3  309.24  5019.3  309.80
  5027.5  318.88  5138.3  317.40  5166.8  318.89  5353.2  318.25  5440.8  321.68
  5596.1  330.13  5690.4  333.54  5696.7  332.71  5711.4  334.70  5757.3  336.77
#Mann=5,-1,0
  4166.3    0.16       0  4278.8    0.12       0  5004.4    0.07       0
  5010.4    0.12       0  5440.8    0.16       0
Bank Sta=5004.4,5010.4
Exp/Cntr=0.3,0.1

Type RM Length L Ch R = 1,16667,486,486,486
BEGIN DESCRIPTION:
UNT166 IN CCTC 24.0
END DESCRIPTION:
XS GIS Cut Line= 3
      3559631.98     10669817.55      3559228.34     10669066.69
      3558889.80     10668702.11
#Sta/Elev= 30
  4276.7  341.95  4351.6  340.75  4401.1  337.74  4439.2  337.81  4444.9  336.81
  4477.4  336.32  4521.2  334.28  4526.9  333.19  4543.1  333.09  4548.8  331.81
  4682.4  322.52  4794.7  317.54  4800.4  318.33  4819.6  317.88  4926.2  318.38
  4942.4  316.96  4970.0  317.32  4977.6  316.55  4986.3  312.43  4997.3  304.40
  5000.1  303.90  5003.3  304.40  5008.2  308.15  5030.1  317.92  5052.0  318.02
  5079.8  316.59  5334.3  318.14  5361.9  319.07  5449.9  322.48  5626.7  329.80
#Mann=7,-1,0
  4276.7    0.16       0  4819.6    0.12       0  4997.3    0.07       0
  5003.3    0.12       0  5334.3    0.16       0  5361.9    0.12       0
  5449.9    0.16       0
Bank Sta=4997.3,5003.3
Exp/Cntr=0.3,0.1