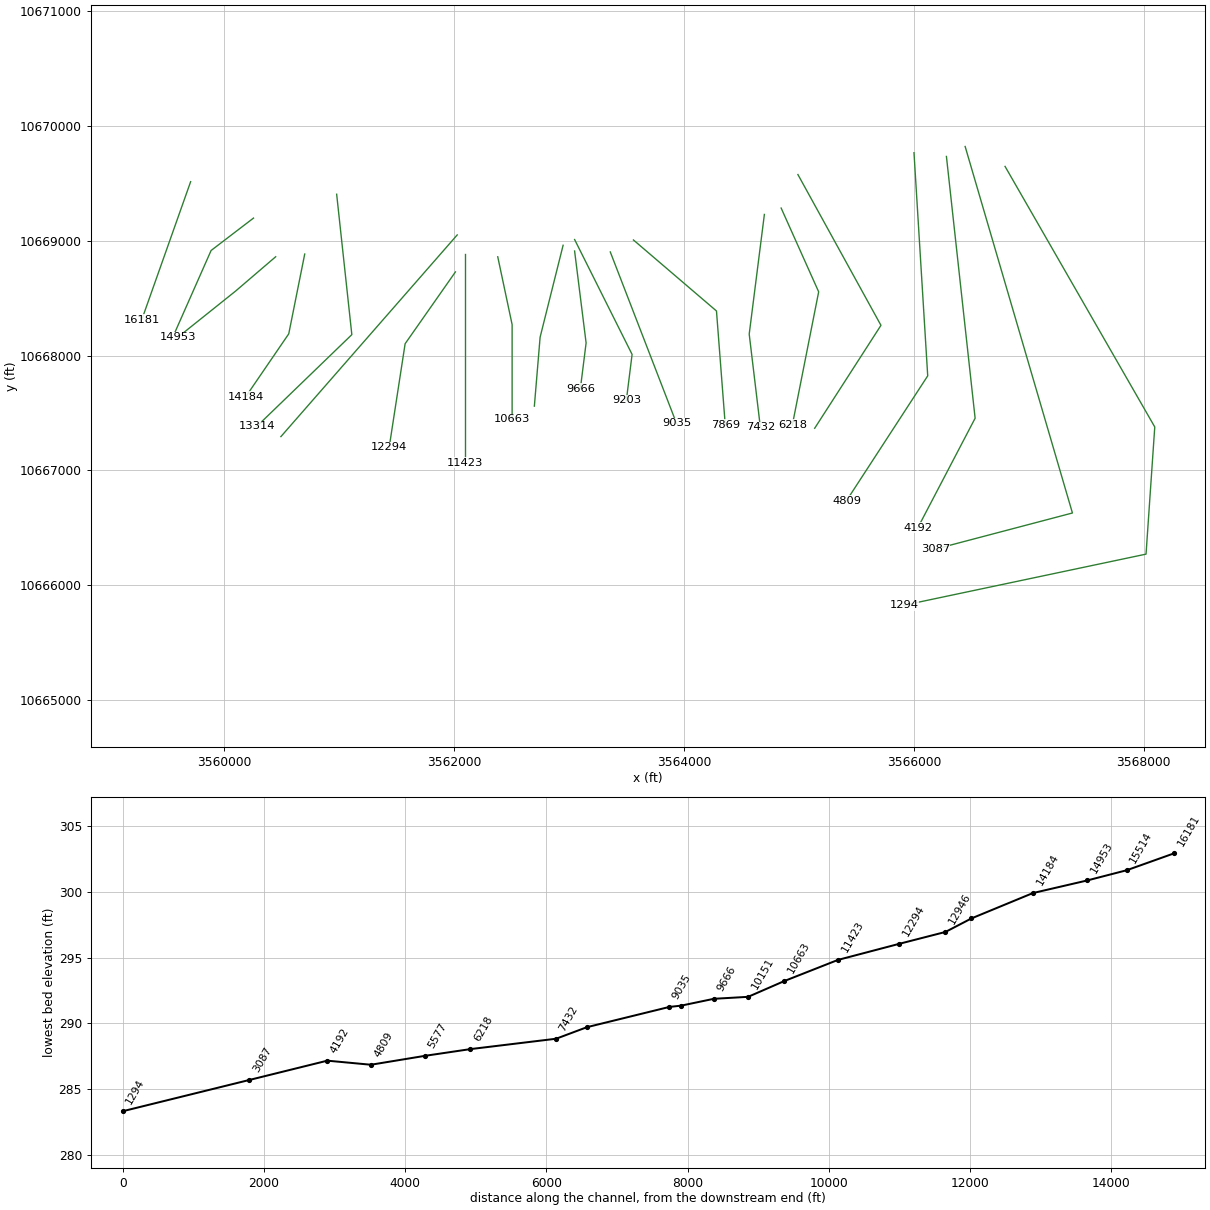
HEC-RAS study UNT166 IN CCTC.prj: UNT166 IN CCTC Base Level Engineering

--- UNT166 IN CCTC.g01 (geometry) --- (continued)

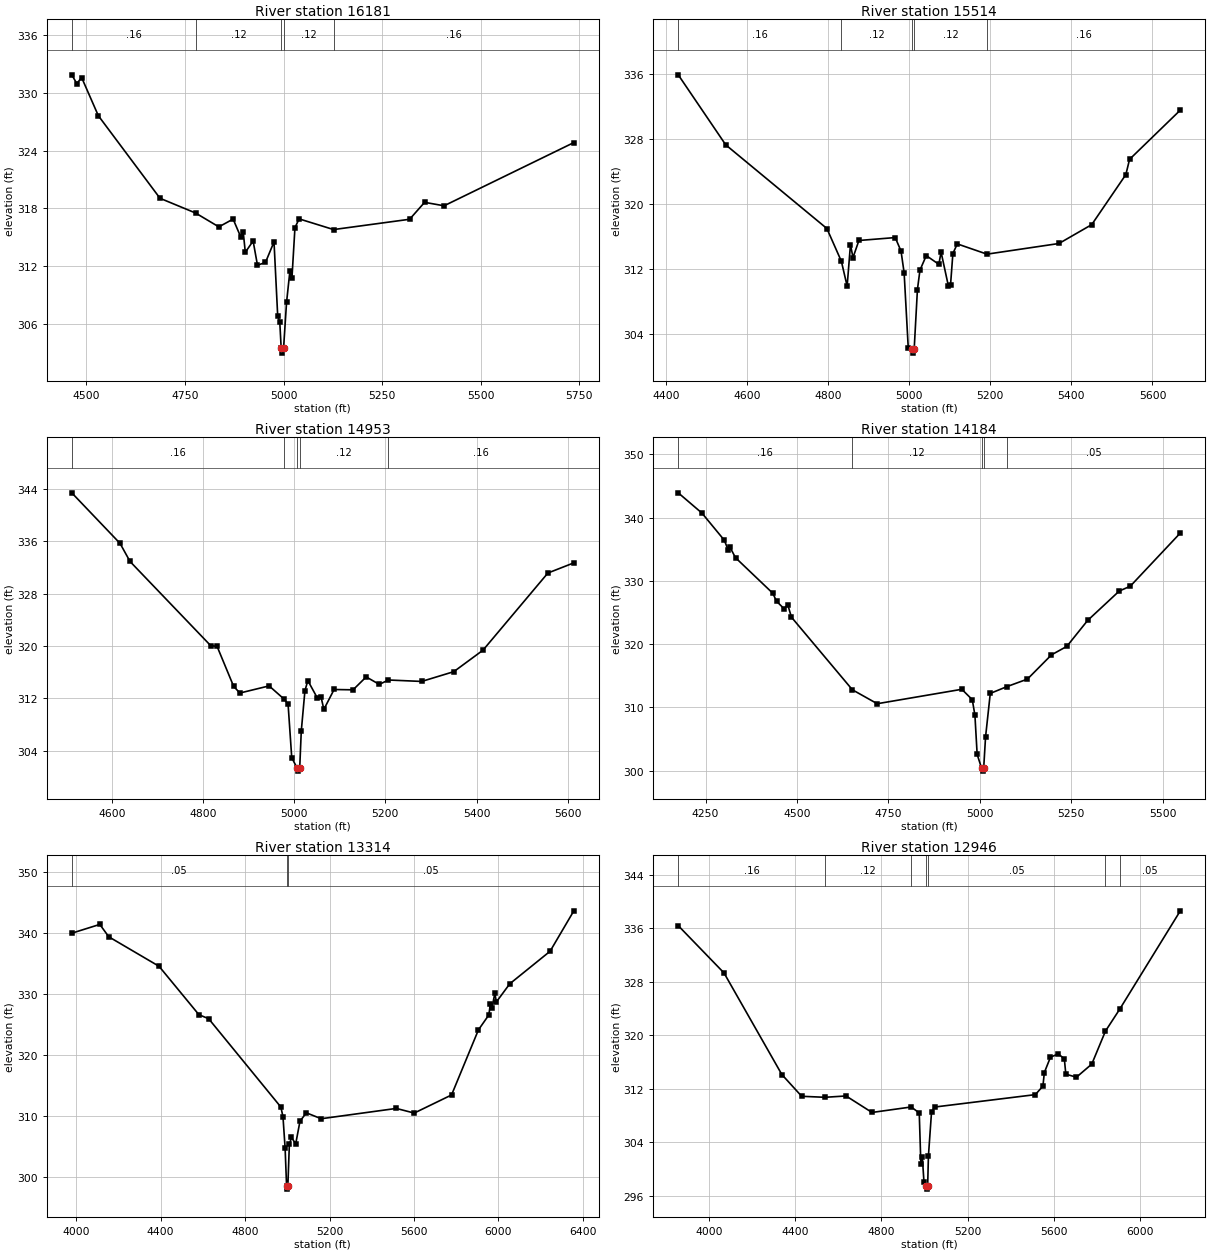
Type RM Length L Ch R = 1,16181,667,667,667
BEGIN DESCRIPTION:
UNT166 IN CCTC 23.0
END DESCRIPTION:
XS GIS Cut Line= 2
      3559710.11     10669513.74      3559285.42     10668313.35
#Sta/Elev= 30
  4463.0  331.87  4475.8  330.96  4488.0  331.59  4530.4  327.62  4686.8  319.04
  4777.0  317.51  4836.0  316.07  4872.2  316.88  4891.1  315.06  4897.8  315.54
  4903.1  313.43  4922.9  314.60  4934.0  312.08  4954.3  312.38  4975.9  314.51
  4985.2  306.86  4990.5  306.19  4994.1  303.45  4996.9  302.95  5000.1  303.45
  5007.7  308.22  5016.1  311.45  5021.4  310.76  5029.0  315.99  5039.6  316.90
  5127.0  315.79  5319.8  316.86  5357.8  318.62  5407.2  318.26  5736.3  324.83
#Mann=5,-1,0
  4463.0    0.16       0  4777.0    0.12       0  4994.1    0.07       0
  5000.1    0.12       0  5127.0    0.16       0
Bank Sta=4994.1,5000.1
Exp/Cntr=0.3,0.1

Type RM Length L Ch R = 1,15514,561,561,561
BEGIN DESCRIPTION:
UNT166 IN CCTC 22.0
END DESCRIPTION:
XS GIS Cut Line= 3
      3560256.95     10669196.87      3559888.06     10668914.78
      3559575.56     10668207.31
#Sta/Elev= 30
  4430.9  335.89  4548.0  327.28  4797.4  316.99  4833.1  312.96  4847.3  309.91
  4855.5  315.00  4861.8  313.42  4876.3  315.52  4965.9  315.88  4980.2  314.21
  4987.8  311.55  4998.0  302.29  5006.6  302.17  5009.4  301.67  5012.6  302.17
  5020.6  309.49  5026.8  311.87  5042.4  313.66  5073.4  312.59  5078.9  314.09
  5096.7  309.98  5102.2  310.04  5108.0  313.92  5118.9  315.10  5192.1  313.84
  5369.5  315.15  5450.3  317.47  5534.4  323.62  5543.6  325.50  5668.7  331.55
#Mann=5,-1,0
  4430.9    0.16       0  4833.1    0.12       0  5006.6    0.07       0
  5012.6    0.12       0  5192.1    0.16       0
Bank Sta=5006.6,5012.6
Exp/Cntr=0.3,0.1

Type RM Length L Ch R = 1,14953,769,769,769
BEGIN DESCRIPTION:
UNT166 IN CCTC 21.0
END DESCRIPTION:
XS GIS Cut Line= 3
      3560449.58     10668860.16      3560099.61     10668560.19
      3559599.57     10668160.16
#Sta/Elev= 30
  4512.2  343.37  4618.1  335.65  4640.0  332.89  4816.7  320.06  4831.0  319.92
  4867.2  313.84  4880.9  312.81  4945.1  313.90  4978.6  311.84  4986.7  311.09
  4994.7  302.95  5006.2  301.39  5008.9  300.89  5012.2  301.39  5015.6  306.98
  5023.6  313.15  5030.0  314.71  5050.8  312.06  5058.8  312.24  5065.2  310.32
  5087.6  313.35  5129.2  313.30  5158.0  315.27  5186.8  314.13  5206.8  314.80
  5279.7  314.58  5350.1  316.07  5414.2  319.35  5556.6  331.13  5613.5  332.68
#Mann=5,-1,0
  4512.2    0.16       0  4978.6    0.12       0  5006.2    0.07       0
  5012.2    0.12       0  5206.8    0.16       0
Bank Sta=5006.2,5012.2
Exp/Cntr=0.3,0.1

Type RM Length L Ch R = 1,14184,870,870,870
BEGIN DESCRIPTION:
UNT166 IN CCTC 20.0
END DESCRIPTION:
XS GIS Cut Line= 3
      3560702.31     10668883.74      3560563.41     10668189.26
      3560188.39     10667640.61
#Sta/Elev= 30
  4175.3  343.90  4240.1  340.70  4301.3  336.41  4311.5  334.92  4316.6  335.32
  4331.9  333.65  4433.9  328.03  4444.1  326.77  4464.4  325.60  4474.7  326.22
  4484.9  324.25  4651.5  312.78  4719.4  310.58  4950.7  312.86  4979.3  311.22
  4986.5  308.76  4992.6  302.58  5004.5  300.43  5007.3  299.93  5010.5  300.43
  5015.6  305.34  5028.5  312.21  5074.8  313.30  5130.1  314.47  5195.8  318.30
  5237.8  319.64  5294.6  323.73  5381.3  328.39  5411.2  329.14  5548.1  337.55
#Mann=5,-1,0
  4175.3    0.16       0  4651.5    0.12       0  5004.5    0.07       0
  5010.5    0.12       0  5074.8    0.05       0
Bank Sta=5004.5,5010.5
Exp/Cntr=0.3,0.1

Type RM Length L Ch R = 1,13314,368,368,368
BEGIN DESCRIPTION:
UNT166 IN CCTC 19.0
END DESCRIPTION:
XS GIS Cut Line= 3
      3560980.08     10669404.51      3561112.02     10668182.32
      3560286.43     10667384.48
#Sta/Elev= 30
  3979.6  339.99  4112.3  341.43  4154.9  339.40  4392.9  334.56  4581.6  326.62
  4627.7  325.96  4969.6  311.47  4979.7  309.89  4989.8  304.73  4996.8  298.50
  4999.6  298.00  5002.8  298.50  5009.9  305.33  5019.9  306.48  5040.0  305.43
  5060.2  309.14  5090.3  310.52  5160.7  309.55  5516.3  311.24  5601.2  310.48
  5777.9  313.45  5905.2  324.13  5954.6  326.58  5961.8  328.43  5968.8  327.65
  5982.9  330.12  5990.1  328.71  6053.7  331.69  6244.6  337.03  6357.0  343.66
#Mann=3,-1,0
  3979.6    0.05       0  4996.8    0.03       0  5002.8    0.05       0
Bank Sta=4996.8,5002.8
Exp/Cntr=0.3,0.1

Type RM Length L Ch R = 1,12946,652,652,652
BEGIN DESCRIPTION:
UNT166 IN CCTC 18.0
END DESCRIPTION:
XS GIS Cut Line= 2
      3562028.66     10669050.34      3560495.03     10667294.65
#Sta/Elev= 30
  3856.8  336.42  4069.3  329.34  4337.9  314.13  4430.0  310.87  4538.2  310.72
  4636.0  310.92  4756.5  308.45  4938.5  309.27  4975.8  308.38  4983.4  300.70
  4990.0  301.83  4997.6  298.11  5008.9  297.47  5011.6  296.97  5014.9  297.47
  5018.5  301.95  5032.8  308.48  5047.0  309.26  5515.0  311.12  5550.1  312.40
  5556.7  314.43  5585.2  316.73  5621.3  317.21  5649.5  316.49  5656.4  314.18
  5705.8  313.73  5776.9  315.69  5840.6  320.64  5906.2  323.89  6188.0  338.64
#Mann=7,-1,0
  3856.8    0.16       0  4538.2    0.12       0  4938.5    0.05       0
  5008.9    0.03       0  5014.9    0.05       0  5840.6    0.16       0
  5906.2    0.05       0
Bank Sta=5008.9,5014.9
Exp/Cntr=0.3,0.1

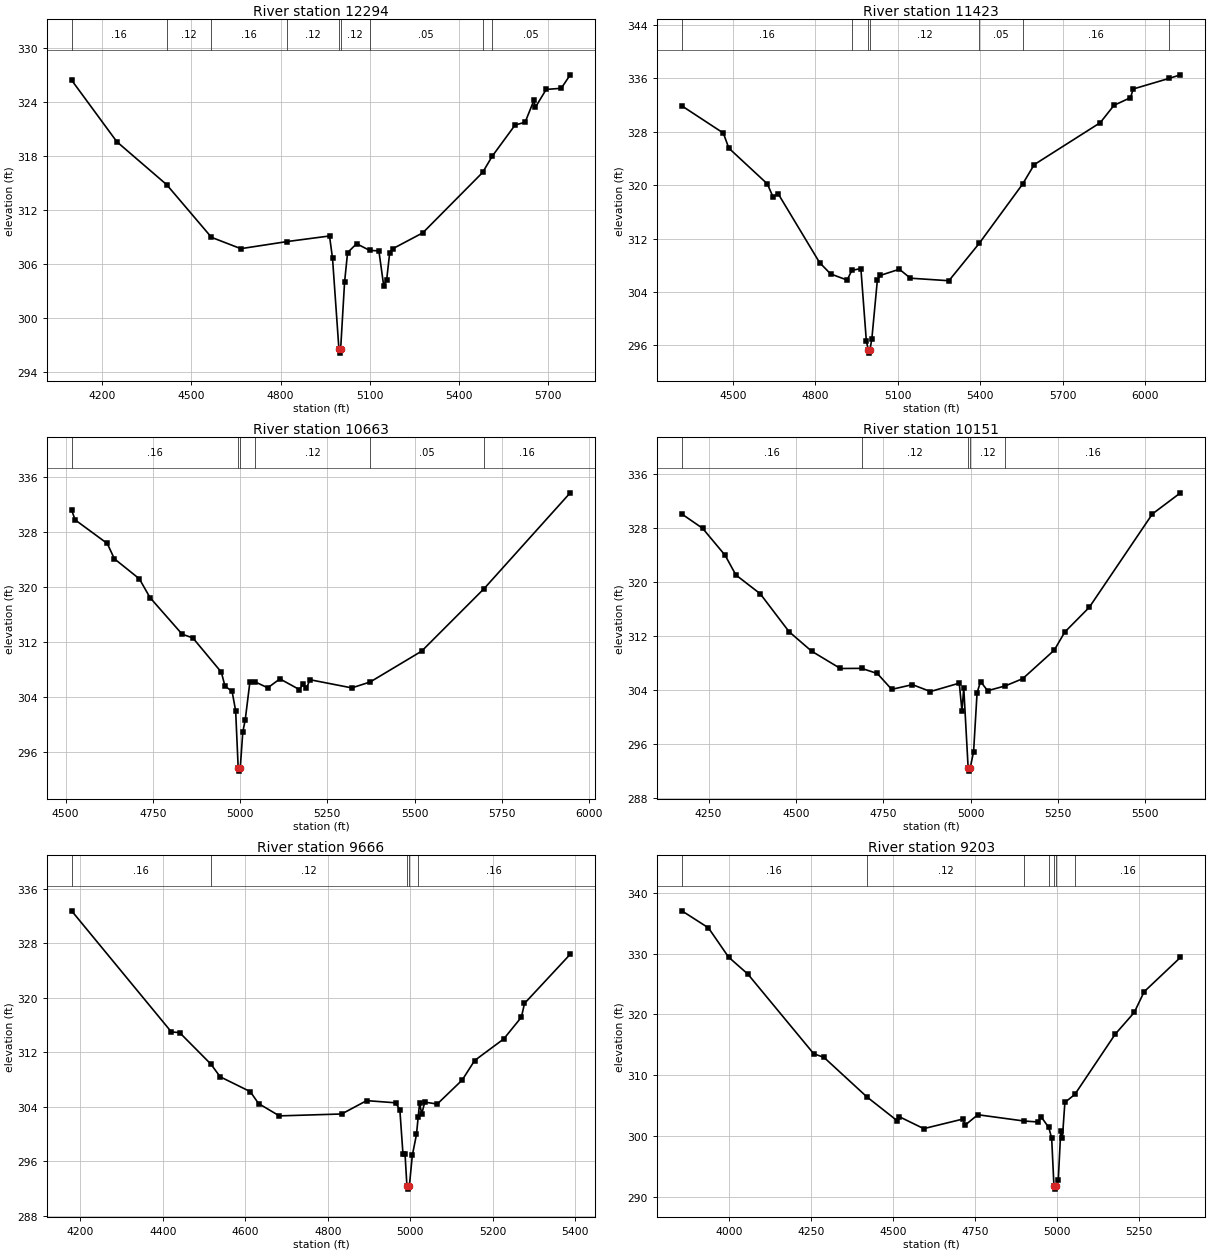
Type RM Length L Ch R = 1,12294,871,871,871
BEGIN DESCRIPTION:
UNT166 IN CCTC 17.0
END DESCRIPTION:
XS GIS Cut Line= 3
      3562013.06     10668728.15      3561575.56     10668103.15
      3561436.67     10667200.38
#Sta/Elev= 30
  4097.5  326.41  4249.7  319.56  4417.2  314.79  4567.7  308.94  4666.4  307.68
  4822.3  308.47  4964.6  309.09  4974.7  306.61  4996.1  296.57  4998.8  296.07
  5002.1  296.57  5015.2  303.96  5025.3  307.24  5055.6  308.23  5099.3  307.49
  5130.6  307.43  5146.7  303.57  5156.8  304.24  5166.9  307.23  5177.0  307.67
  5278.2  309.44  5479.3  316.15  5511.3  317.94  5588.4  321.42  5622.2  321.73
  5651.7  324.16  5656.7  323.39  5693.0  325.38  5743.6  325.50  5773.8  327.00
#Mann=9,-1,0
  4097.5    0.16       0  4417.2    0.12       0  4567.7    0.16       0
  4822.3    0.12       0  4996.1    0.07       0  5002.1    0.12       0
  5099.3    0.05       0  5479.3    0.16       0  5511.3    0.05       0
Bank Sta=4996.1,5002.1
Exp/Cntr=0.3,0.1

Type RM Length L Ch R = 1,11423,760,760,760
BEGIN DESCRIPTION:
UNT166 IN CCTC 16.0
END DESCRIPTION:
XS GIS Cut Line= 2
      3562096.39     10668880.91      3562096.39     10667068.41
#Sta/Elev= 30
  4314.7  331.86  4465.4  327.79  4485.4  325.53  4625.4  320.18  4645.4  318.29
  4665.4  318.66  4815.4  308.39  4855.4  306.70  4915.4  305.78  4932.5  307.22
  4965.4  307.51  4985.4  296.60  4992.4  295.34  4995.2  294.84  4998.4  295.34
  5005.4  297.03  5025.4  305.81  5035.4  306.47  5105.4  307.40  5145.4  306.06
  5285.4  305.68  5395.5  311.27  5553.0  320.13  5595.4  323.06  5835.4  329.34
  5885.4  331.94  5945.4  333.09  5955.4  334.39  6086.0  335.98  6127.2  336.51
#Mann=7,-1,0
  4314.7    0.16       0  4932.5    0.12       0  4992.4    0.07       0
  4998.4    0.12       0  5395.5    0.05       0  5553.0    0.16       0
  6086.0    0.05       0
Bank Sta=4992.4,4998.4
Exp/Cntr=0.3,0.1

Type RM Length L Ch R = 1,10663,512,512,512
BEGIN DESCRIPTION:
UNT166 IN CCTC 15.0
END DESCRIPTION:
XS GIS Cut Line= 3
      3562381.11     10668860.12      3562506.12     10668269.82
      3562506.12     10667444.31
#Sta/Elev= 30
  4517.3  331.22  4527.5  329.78  4619.5  326.35  4639.9  324.12  4711.4  321.21
  4742.1  318.47  4834.1  313.15  4864.8  312.61  4946.5  307.62  4956.8  305.59
  4977.2  304.84  4987.4  302.01  4994.7  293.73  4997.4  293.23  5000.7  293.73
  5007.9  298.93  5014.9  300.70  5028.3  306.22  5044.3  306.19  5079.4  305.35
  5114.3  306.65  5170.3  305.09  5180.3  305.89  5190.3  305.27  5200.3  306.53
  5320.3  305.34  5372.9  306.20  5520.3  310.68  5699.2  319.77  5946.2  333.72
#Mann=6,-1,0
  4517.3    0.16       0  4994.7    0.07       0  5000.7    0.16       0
  5044.3    0.12       0  5372.9    0.05       0  5699.2    0.16       0
Bank Sta=4994.7,5000.7
Exp/Cntr=0.3,0.1

Type RM Length L Ch R = 1,10151,485,485,485
BEGIN DESCRIPTION:
UNT166 IN CCTC 13.0
END DESCRIPTION:
XS GIS Cut Line= 3
      3562949.61     10668960.20      3562749.61     10668160.19
      3562699.61     10667560.20
#Sta/Elev= 30
  4173.6  330.08  4232.9  327.97  4297.3  323.98  4328.2  321.06  4397.8  318.28
  4480.3  312.67  4544.7  309.79  4627.2  307.22  4687.8  307.24  4732.8  306.48
  4774.0  304.13  4833.3  304.83  4884.8  303.81  4967.3  305.05  4975.0  300.99
  4980.2  304.32  4992.7  292.53  4995.4  292.03  4998.7  292.53  5008.3  294.91
  5018.3  303.64  5028.3  305.29  5048.4  303.93  5098.7  304.64  5148.8  305.71
  5239.1  309.93  5269.2  312.61  5339.4  316.28  5520.0  330.10  5600.3  333.22
#Mann=5,-1,0
  4173.6    0.16       0  4687.8    0.12       0  4992.7    0.07       0
  4998.7    0.12       0  5098.7    0.16       0
Bank Sta=4992.7,4998.7
Exp/Cntr=0.3,0.1

Type RM Length L Ch R = 1,9666,463,463,463
BEGIN DESCRIPTION:
UNT166 IN CCTC 12.0
END DESCRIPTION:
XS GIS Cut Line= 3
      3563049.60     10668910.23      3563149.61     10668110.19
      3563099.61     10667710.17
#Sta/Elev= 30
  4178.7  332.73  4420.6  314.96  4440.8  314.85  4516.7  310.22  4539.0  308.37
  4612.1  306.19  4632.2  304.44  4682.6  302.63  4833.8  302.91  4894.3  304.87
  4964.8  304.55  4974.9  303.51  4982.5  296.98  4987.5  296.98  4992.0  292.38
  4994.8  291.88  4998.0  292.38  5005.1  296.82  5015.2  299.91  5019.4  302.49
  5022.8  304.58  5027.8  302.91  5035.4  304.65  5065.6  304.37  5126.1  307.89
  5156.3  310.76  5226.8  313.92  5269.7  317.12  5277.2  319.14  5388.1  326.35
#Mann=5,-1,0
  4178.7    0.16       0  4516.7    0.12       0  4992.0    0.07       0
  4998.0    0.12       0  5019.4    0.16       0
Bank Sta=4992,4998
Exp/Cntr=0.3,0.1

Type RM Length L Ch R = 1,9203,168,168,168
BEGIN DESCRIPTION:
UNT166 IN CCTC 11.0
END DESCRIPTION:
XS GIS Cut Line= 3
      3563049.63     10669010.15      3563549.61     10668010.19
      3563499.61     10667610.19
#Sta/Elev= 30
  3855.1  337.00  3936.1  334.21  3997.6  329.41  4056.3  326.63  4257.5  313.55
  4288.3  312.98  4419.5  306.49  4511.9  302.58  4517.5  303.26  4593.0  301.28
  4713.1  302.86  4718.7  301.83  4757.9  303.56  4899.0  302.53  4942.3  302.37
  4950.7  303.25  4974.4  301.47  4983.2  299.73  4990.2  291.86  4993.0  291.36
  4996.2  291.86  5003.3  292.79  5010.9  300.85  5015.9  299.69  5023.5  305.58
  5053.9  306.89  5177.2  316.78  5235.1  320.33  5265.3  323.73  5376.2  329.37
#Mann=7,-1,0
  3855.1    0.16       0  4419.5    0.12       0  4899.0    0.16       0
  4974.4    0.12       0  4990.2    0.07       0  4996.2    0.12       0
  5053.9    0.16       0
Bank Sta=4990.2,4996.2
Exp/Cntr=0.3,0.1

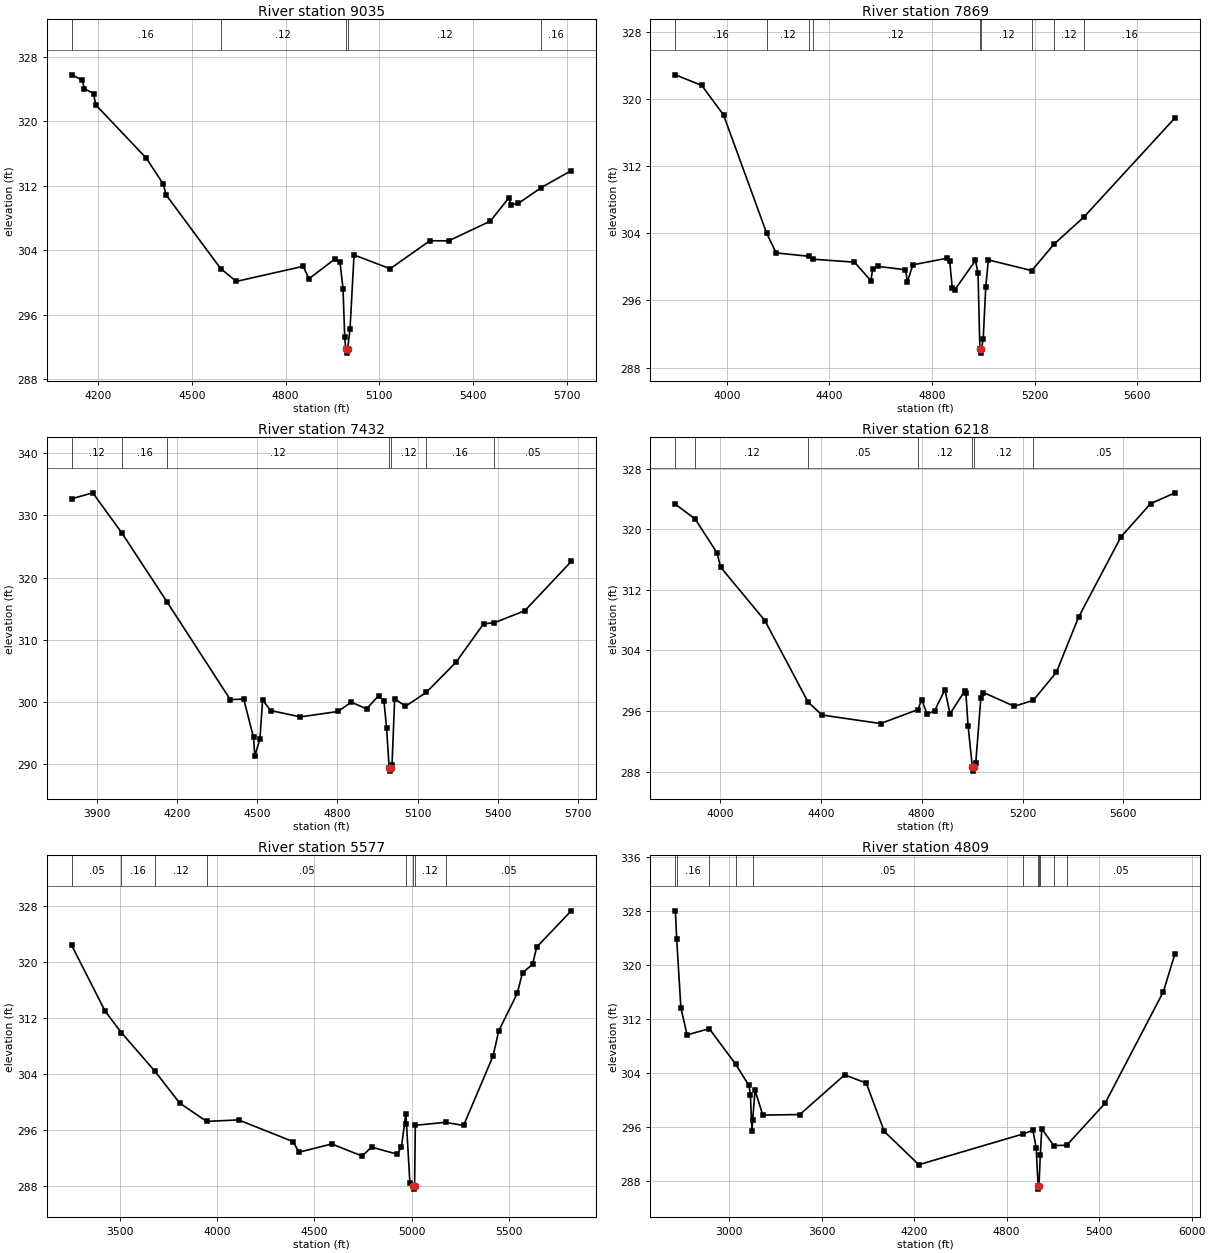
Type RM Length L Ch R = 1,9035,1166,1166,1166
BEGIN DESCRIPTION:
UNT166 IN CCTC 10.0
END DESCRIPTION:
XS GIS Cut Line= 2
      3563359.91     10668902.15      3563936.32     10667409.05
#Sta/Elev= 30
  4114.6  325.76  4148.9  325.10  4154.8  324.06  4184.8  323.44  4191.7  322.04
  4353.8  315.43  4408.4  312.20  4416.8  310.90  4592.0  301.74  4642.0  300.15
  4856.3  302.02  4874.9  300.49  4959.4  302.96  4974.2  302.54  4984.0  299.26
  4989.4  293.20  4992.7  291.76  4995.4  291.26  4998.7  291.76  5006.4  294.24
  5019.3  303.43  5135.0  301.72  5262.2  305.19  5322.1  305.18  5455.9  307.62
  5515.8  310.54  5521.1  309.65  5545.7  309.82  5619.0  311.78  5715.1  313.88
#Mann=5,-1,0
  4114.6    0.16       0  4592.0    0.12       0  4992.7    0.07       0
  4998.7    0.12       0  5619.0    0.16       0
Bank Sta=4992.7,4998.7
Exp/Cntr=0.3,0.1

Type RM Length L Ch R = 1,7869,437,437,437
BEGIN DESCRIPTION:
UNT166 IN CCTC 9.0
END DESCRIPTION:
XS GIS Cut Line= 3
      3563561.29     10669006.31      3564283.54     10668388.23
      3564359.92     10667395.18
#Sta/Elev= 30
  3799.7  322.91  3902.6  321.64  3987.2  318.13  4155.7  304.00  4192.4  301.67
  4319.8  301.27  4335.3  300.92  4497.6  300.57  4561.3  298.36  4568.9  299.79
  4589.8  300.06  4696.3  299.66  4704.0  298.25  4724.8  300.25  4858.7  301.04
  4868.7  300.65  4878.7  297.44  4888.8  297.29  4969.0  300.77  4979.0  299.23
  4986.1  290.22  4988.8  289.72  4992.1  290.22  4999.1  291.43  5009.1  297.60
  5019.1  300.84  5188.4  299.56  5274.6  302.70  5392.1  305.97  5746.3  317.77
#Mann=9,-1,0
  3799.7    0.16       0  4155.7    0.12       0  4319.8    0.16       0
  4335.3    0.12       0  4986.1    0.07       0  4992.1    0.12       0
  5188.4    0.16       0  5274.6    0.12       0  5392.1    0.16       0
Bank Sta=4986.1,4992.1
Exp/Cntr=0.3,0.1

Type RM Length L Ch R = 1,7432,1214,1214,1214
BEGIN DESCRIPTION:
UNT166 IN CCTC 8.0
END DESCRIPTION:
XS GIS Cut Line= 3
      3564700.20     10669228.49      3564568.26     10668186.85
      3564665.42     10667374.81
#Sta/Elev= 30
  3806.3  332.68  3885.2  333.64  3993.5  327.21  4163.7  316.03  4399.3  300.36
  4449.7  300.43  4486.2  294.27  4491.2  291.27  4510.2  294.01  4520.3  300.28
  4550.5  298.59  4661.4  297.57  4801.6  298.44  4852.1  299.95  4909.0  298.85
  4953.6  300.97  4973.8  300.13  4983.8  295.76  4993.4  289.34  4996.2  288.84
  4999.4  289.34  5004.0  289.78  5014.0  300.50  5054.3  299.28  5131.7  301.50
  5243.5  306.38  5346.4  312.56  5385.8  312.71  5500.7  314.67  5674.1  322.59
#Mann=7,-1,0
  3806.3    0.12       0  3993.5    0.16       0  4163.7    0.12       0
  4993.4    0.07       0  4999.4    0.12       0  5131.7    0.16       0
  5385.8    0.05       0
Bank Sta=4993.4,4999.4
Exp/Cntr=0.3,0.1

Type RM Length L Ch R = 1,6218,641,641,641
BEGIN DESCRIPTION:
UNT166 IN CCTC 7.0
END DESCRIPTION:
XS GIS Cut Line= 3
      3564846.04     10669284.07      3565172.42     10668554.90
      3564943.26     10667395.21
#Sta/Elev= 30
  3823.4  323.32  3901.7  321.38  3988.9  316.87  4002.9  315.00  4178.2  307.95
  4349.4  297.18  4405.1  295.46  4637.3  294.34  4785.0  296.18  4800.4  297.50
  4821.6  295.56  4851.3  296.03  4892.1  298.81  4912.5  295.64  4970.3  298.62
  4975.4  298.34  4983.9  294.07  5001.2  288.55  5004.0  288.05  5007.2  288.55
  5014.4  289.10  5034.8  297.78  5045.0  298.44  5167.3  296.62  5242.7  297.41
  5334.4  301.13  5422.2  308.40  5590.7  319.03  5707.6  323.40  5804.4  324.83
#Mann=7,-1,0
  3823.4    0.16       0  3901.7    0.12       0  4349.4    0.05       0
  4785.0    0.12       0  5001.2    0.07       0  5007.2    0.12       0
  5242.7    0.05       0
Bank Sta=5001.2,5007.2
Exp/Cntr=0.3,0.1

Type RM Length L Ch R = 1,5577,768,768,768
BEGIN DESCRIPTION:
UNT166 IN CCTC 5.0
END DESCRIPTION:
XS GIS Cut Line= 3
      3564991.86     10669575.74      3565714.09     10668263.23
      3565137.72     10667367.43
#Sta/Elev= 30
  3254.4  322.35  3426.1  312.95  3509.6  309.88  3680.5  304.41  3808.6  299.83
  3946.6  297.21  4110.8  297.42  4390.7  294.32  4420.5  292.81  4589.0  293.99
  4744.6  292.26  4793.1  293.54  4923.2  292.54  4946.4  293.50  4968.8  298.26
  4972.3  296.90  4989.9  288.43  5008.0  288.04  5010.8  287.54  5014.0  288.04
  5017.7  296.66  5172.9  297.07  5265.3  296.63  5416.5  306.53  5445.8  310.14
  5540.6  315.48  5567.7  318.43  5619.2  319.62  5640.3  322.09  5817.7  327.27
#Mann=8,-1,0
  3254.4    0.05       0  3509.6    0.16       0  3680.5    0.12       0
  3946.6    0.05       0  4972.3    0.12       0  5008.0    0.07       0
  5014.0    0.12       0  5172.9    0.05       0
Bank Sta=5008,5014
Exp/Cntr=0.3,0.1

Type RM Length L Ch R = 1,4809,617,617,617
BEGIN DESCRIPTION:
UNT166 IN CCTC 4.0
END DESCRIPTION:
XS GIS Cut Line= 3
      3566001.42     10669765.81      3566120.78     10667823.56
      3565415.46     10666738.46
#Sta/Elev= 30
  2651.7  327.98  2660.3  323.76  2687.4  313.65  2727.5  309.65  2871.5  310.57
  3043.9  305.28  3128.2  302.18  3138.2  300.83  3148.3  295.50  3153.0  297.08
  3168.3  301.48  3218.4  297.80  3458.8  297.88  3749.4  303.74  3889.7  302.53
  4006.4  295.39  4230.3  290.47  4908.6  295.02  4970.7  295.56  4991.8  292.94
  5003.9  287.36  5006.6  286.86  5009.9  287.36  5018.4  291.95  5028.0  295.77
  5105.5  293.30  5189.6  293.34  5438.6  299.55  5816.1  316.01  5891.8  321.64
#Mann=11,-1,0
  2651.7    0.05       0  2660.3    0.16       0  2871.5    0.12       0
  3043.9    0.16       0  3153.0    0.05       0  4908.6    0.12       0
  5003.9    0.07       0  5009.9    0.12       0  5018.4    0.05       0
  5105.5    0.16       0  5189.6    0.05       0
Bank Sta=5003.9,5009.9
Exp/Cntr=0.3,0.1

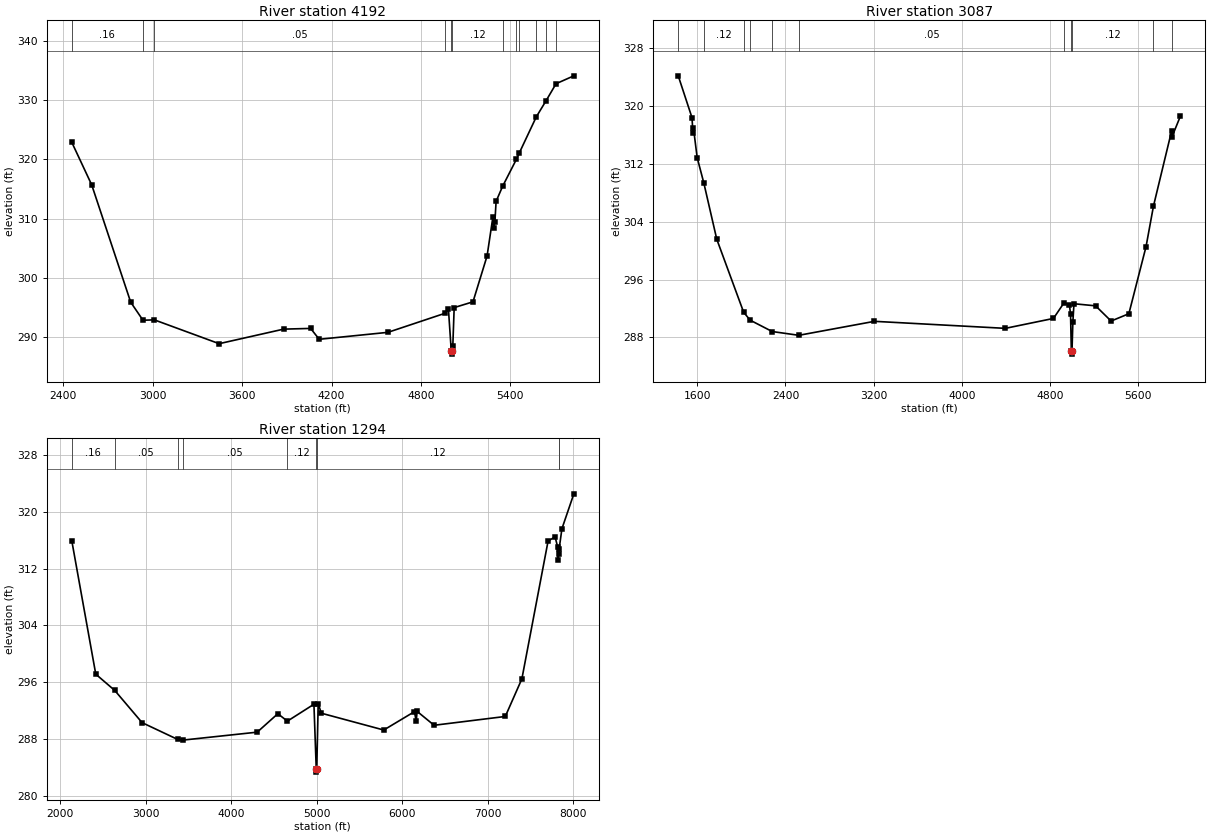
Type RM Length L Ch R = 1,4192,1105,1105,1105
BEGIN DESCRIPTION:
UNT166 IN CCTC 3.0
END DESCRIPTION:
XS GIS Cut Line= 3
      3566283.54     10669733.24      3566533.10     10667454.64
      3566034.28     10666500.38
#Sta/Elev= 30
  2456.7  322.86  2590.5  315.68  2852.1  295.92  2934.5  292.88  3010.9  292.94
  3445.6  288.93  3878.2  291.38  4059.3  291.50  4117.2  289.67  4578.2  290.84
  4958.8  294.03  4984.2  294.74  5003.3  287.67  5006.0  287.17  5009.3  287.67
  5013.5  288.53  5022.7  295.01  5148.9  295.98  5243.5  303.71  5282.0  310.19
  5287.6  308.49  5295.6  309.36  5304.1  312.91  5348.1  315.46  5439.9  319.97
  5461.0  321.13  5574.0  327.15  5638.5  329.82  5706.3  332.72  5825.7  334.05
#Mann=12,-1,0
  2456.7    0.16       0  2934.5    0.12       0  3010.9    0.05       0
  4958.8    0.12       0  5003.3    0.07       0  5009.3    0.12       0
  5348.1    0.05       0  5439.9    0.16       0  5461.0    0.05       0
  5574.0    0.16       0  5638.5    0.05       0  5706.3    0.12       0
Bank Sta=5003.3,5009.3
Exp/Cntr=0.3,0.1

Type RM Length L Ch R = 1,3087,1793,1793,1793
BEGIN DESCRIPTION:
UNT166 IN CCTC 2.0
END DESCRIPTION:
XS GIS Cut Line= 3
      3566446.30     10669820.09      3567379.46     10666629.99
      3566185.92     10666315.33
#Sta/Elev= 30
  1426.3  324.14  1551.2  318.36  1559.6  316.31  1564.8  316.89  1598.2  312.84
  1658.6  309.34  1775.9  301.58  2020.0  291.49  2079.1  290.39  2279.5  288.82
  2521.3  288.30  3207.9  290.23  4395.6  289.26  4832.7  290.63  4927.0  292.75
  4977.4  292.55  4987.8  291.22  4995.1  286.20  4997.9  285.70  5001.1  286.20
  5009.0  290.13  5018.8  292.66  5215.3  292.37  5356.1  290.27  5517.3  291.28
  5673.3  300.55  5740.7  306.15  5904.8  316.49  5909.2  315.73  5984.4  318.54
#Mann=11,-1,0
  1426.3    0.16       0  1658.6    0.12       0  2020.0    0.16       0
  2079.1    0.05       0  2279.5     0.1       0  2521.3    0.05       0
  4927.0    0.12       0  4995.1    0.07       0  5001.1    0.12       0
  5740.7    0.16       0  5909.2    0.12       0
Bank Sta=4995.1,5001.1
Exp/Cntr=0.3,0.1

Type RM Length L Ch R = 1,1294,0,0,0
BEGIN DESCRIPTION:
UNT166 IN CCTC 1.0
END DESCRIPTION:
XS GIS Cut Line= 4
      3566793.52     10669646.48      3568095.60     10667378.69
      3568019.65     10666271.92      3565914.64     10665827.04
#Sta/Elev= 30
  2133.6  315.92  2414.4  297.12  2637.1  294.82  2956.5  290.29  3373.9  287.92
  3433.4  287.83  4303.9  288.95  4545.4  291.55  4656.8  290.50  4967.6  292.88
  4994.7  283.82  4997.5  283.32  5000.7  283.82  5017.7  292.96  5054.0  291.62
  5785.0  289.25  6144.2  291.84  6164.7  290.46  6174.9  291.88  6374.2  289.92
  7207.2  291.16  7401.4  296.46  7708.0  315.87  7789.8  316.46  7820.2  315.03
  7825.3  313.19  7833.6  313.98  7836.8  314.70  7869.9  317.60  8009.5  322.52
#Mann=9,-1,0
  2133.6    0.16       0  2637.1    0.05       0  3373.9    0.16       0
  3433.4    0.05       0  4656.8    0.12       0  4994.7    0.07       0
  5000.7    0.12       0  7833.6    0.16       0  7836.8    0.12       0
Bank Sta=4994.7,5000.7
Exp/Cntr=0.3,0.1

Chan Stop Cuts=-1