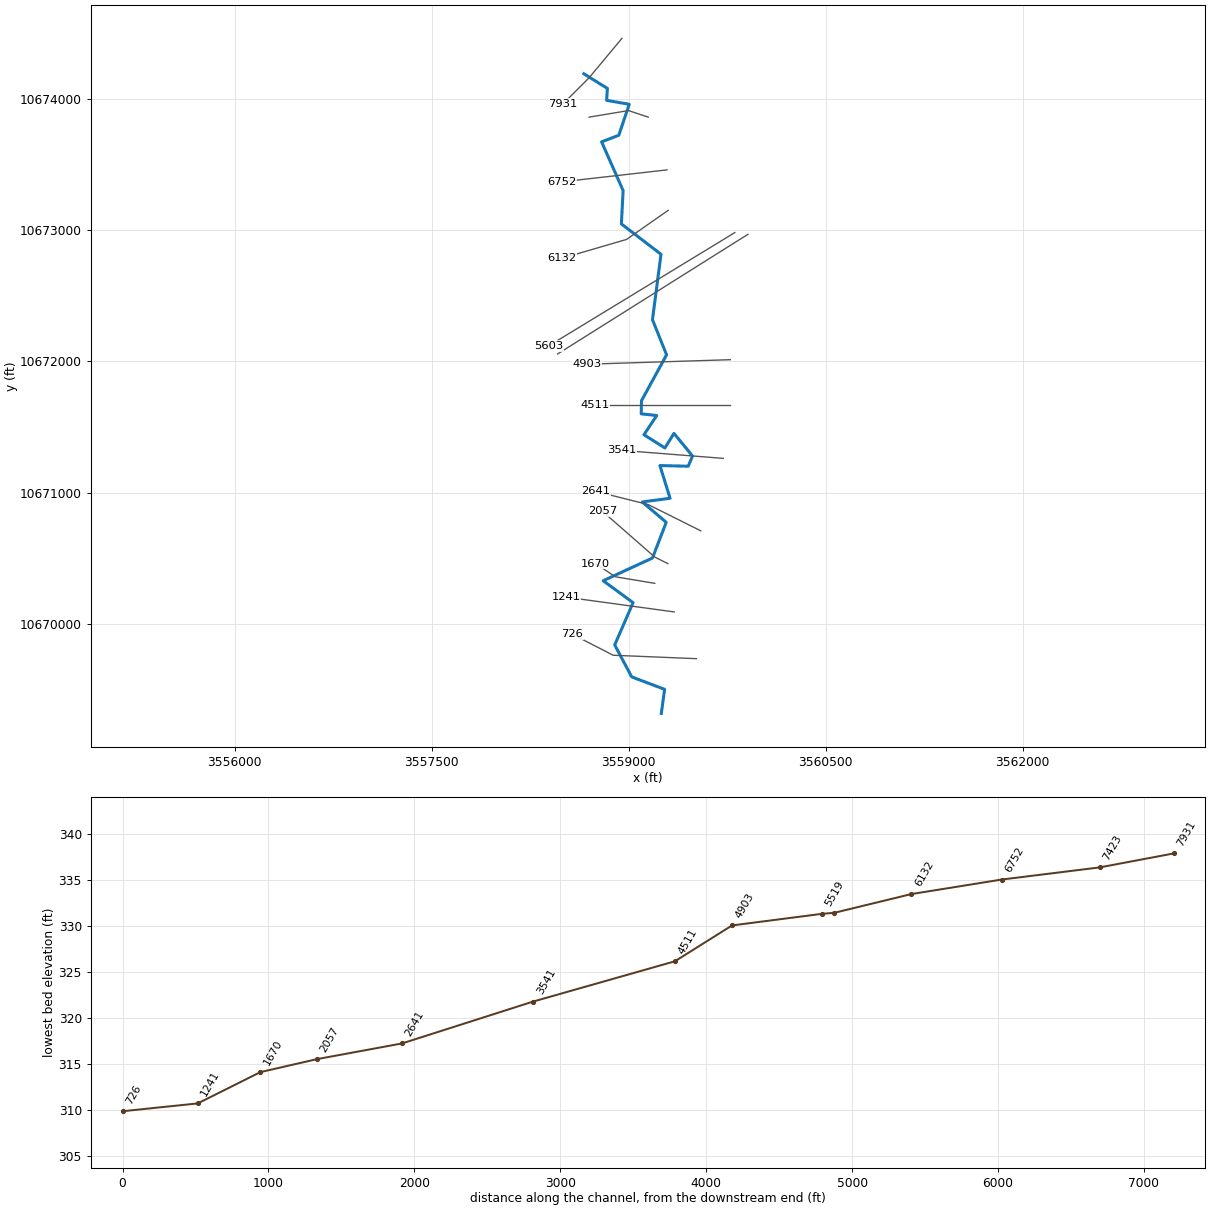
--- UNT167 IN CCTC.prj (project) ---

Proj Title=UNT167 IN CCTC Base Level Engineering
Current Plan=p01
Default Exp/Contr=0.3,0.1
English Units
Geom File=g01
Flow File=f01
Plan File=p01
BEGIN DESCRIPTION:
UNT167 IN CCTC
END DESCRIPTION:

--- UNT167 IN CCTC.p01 (plan) ---

Plan Title=Multiple Run
Short Identifier=Multiple
Geom File=g01
Flow File=f01
Subcritical Flow
K Sum by GR= 0
Std Step Tol= 0.01
Critical Tol= 0.01
Num of Std Step Trials= 20
Max Error Tol= 0.3
Flow Tol Ratio= 0.001
Split Flow NTrial= 30
Split Flow Tol= 0.02
Split Flow Ratio= 0.02
Log Output Level= 0
Friction Slope Method= 1
Unsteady Friction Slope Method= 2
Unsteady Bridges Friction Slope Method= 1
Parabolic Critical Depth
Global Vel Dist=  1 , 1 , 1
Global Log Level= 0
CheckData=True
Encroach Param= -1, 0, 0, 0
BEGIN DESCRIPTION:
Multiple Run
END DESCRIPTION:

--- UNT167 IN CCTC.f01 (steady flow) ---

Flow Title=Multiple
Number of Profiles=7
Profile Names=10-year,25-year,50-year,1pct_min,100-year,1pct_plu,500-year
River Rch & RM= UNT167 IN CCTC,Reach-1,7931
    1498    2061    2525    2255    3050    4124    4437
Boundary for River Rch & Prof#=UNT167 IN CCTC,Reach-1,1
Up Type=0
Dn Type=3
Dn Slope=0.005
Boundary for River Rch & Prof#=UNT167 IN CCTC,Reach-1,2
Up Type=0
Dn Type=3
Dn Slope=0.005
Boundary for River Rch & Prof#=UNT167 IN CCTC,Reach-1,3
Up Type=0
Dn Type=3
Dn Slope=0.005
Boundary for River Rch & Prof#=UNT167 IN CCTC,Reach-1,4
Up Type=0
Dn Type=3
Dn Slope=0.005
Boundary for River Rch & Prof#=UNT167 IN CCTC,Reach-1,5
Up Type=0
Dn Type=3
Dn Slope=0.005
Boundary for River Rch & Prof#=UNT167 IN CCTC,Reach-1,6
Up Type=0
Dn Type=3
Dn Slope=0.005
Boundary for River Rch & Prof#=UNT167 IN CCTC,Reach-1,7
Up Type=0
Dn Type=3
Dn Slope=0.005

--- UNT167 IN CCTC.g01 (geometry) ---

Geom Title=Existing Conditions

River Reach=UNT167 IN CCTC,Reach-1
Reach XY= 30
      3558659.50     10674190.00      3558838.75     10674079.00
      3558833.25     10673988.00      3559005.25     10673958.00
      3558925.50     10673722.00      3558794.75     10673672.00
      3558958.50     10673301.00      3558945.25     10673047.00
      3559247.00     10672816.00      3559182.00     10672318.00
      3559289.50     10672050.00      3559098.50     10671701.00
      3559096.25     10671601.00      3559214.50     10671588.00
      3559117.00     10671442.00      3559276.50     10671341.00
      3559345.75     10671452.00      3559486.75     10671280.00
      3559454.50     10671202.00      3559238.75     10671207.00
      3559316.00     10670958.00      3559104.25     10670930.00
      3559286.75     10670775.00      3559182.00     10670503.00
      3558806.75     10670330.00      3559034.50     10670163.00
      3558894.50     10669841.00      3559023.75     10669598.00
      3559274.25     10669503.00      3559249.50     10669320.00

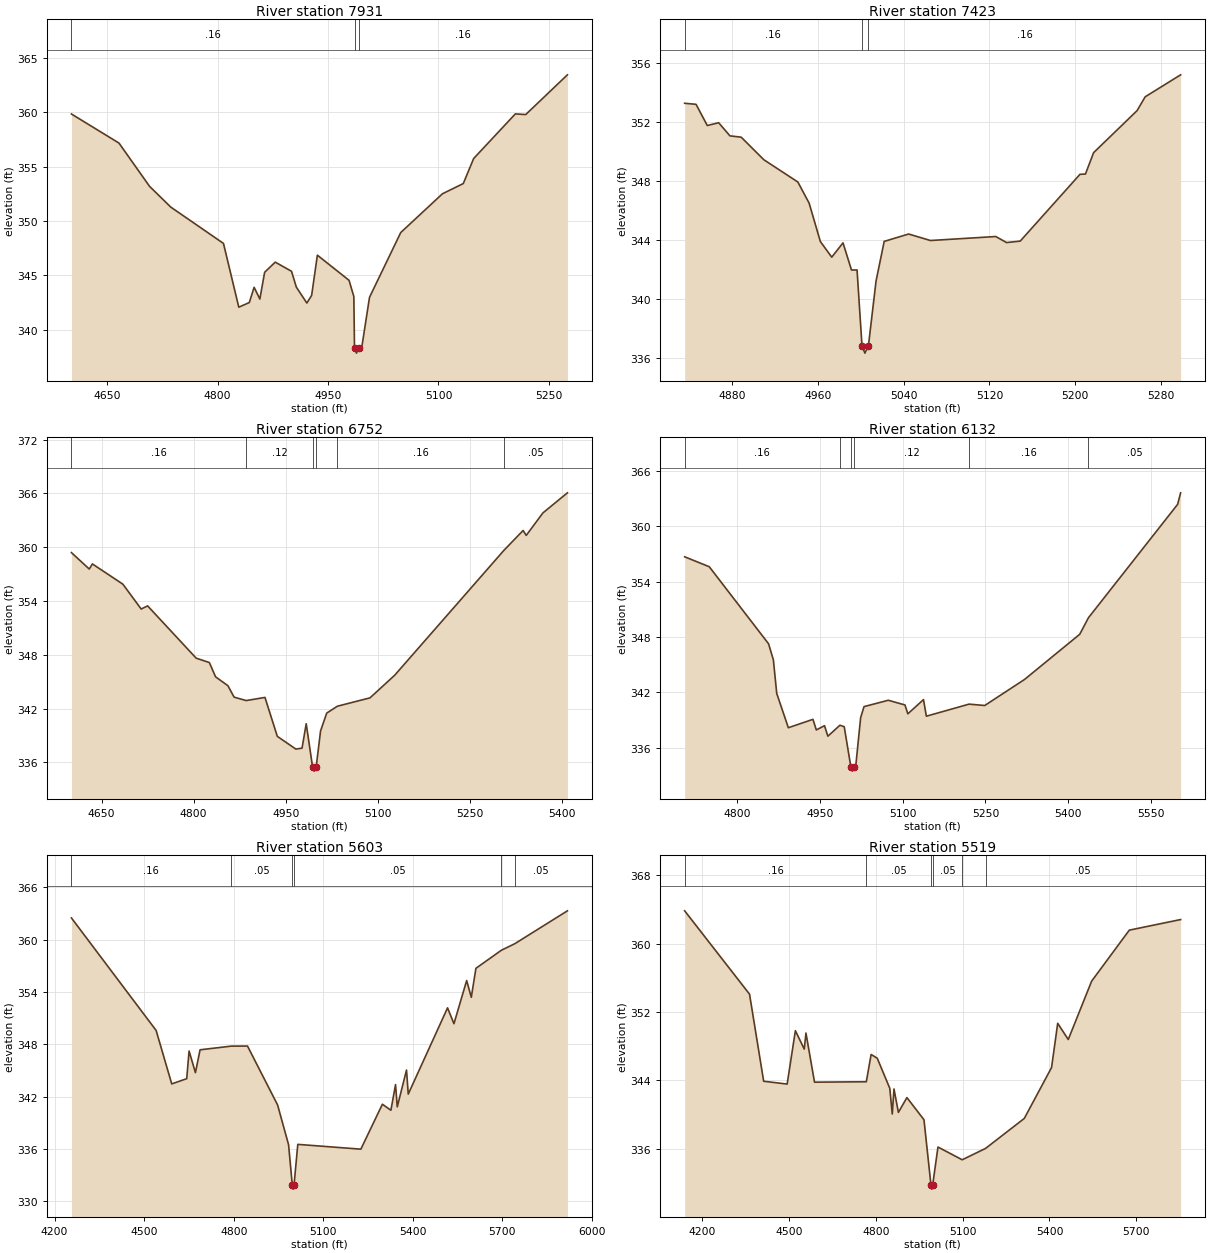
Type RM Length L Ch R = 1,7931,508,508,508
BEGIN DESCRIPTION:
UNT167 IN CCTC 14.0
END DESCRIPTION:
XS GIS Cut Line= 3
      3558949.63     10674460.22      3558699.61     10674160.19
      3558499.60     10673960.18
#Sta/Elev= 30
  4601.7  359.83  4666.2  357.16  4707.8  353.18  4736.5  351.28  4808.1  347.94
  4828.9  342.08  4843.2  342.51  4849.7  343.91  4857.5  342.83  4864.0  345.29
  4878.4  346.22  4900.5  345.38  4907.0  343.93  4921.3  342.46  4927.8  343.16
  4935.6  346.86  4978.6  344.55  4985.1  343.06  4986.0  338.36  4988.7  337.86
  4992.0  338.36  4995.8  338.36  5006.4  342.99  5048.8  348.94  5105.4  352.50
  5133.7  353.44  5147.8  355.74  5204.4  359.84  5218.5  359.78  5275.1  363.43
#Mann=3,-1,0
  4601.7    0.16       0  4986.0    0.07       0  4992.0    0.16       0
Bank Sta=4986,4992
Exp/Cntr=0.3,0.1

Type RM Length L Ch R = 1,7423,671,671,671
BEGIN DESCRIPTION:
UNT167 IN CCTC 13.0
END DESCRIPTION:
XS GIS Cut Line= 3
      3559149.65     10673860.17      3558999.61     10673910.19
      3558699.60     10673860.19
#Sta/Elev= 30
  4835.9  353.29  4846.5  353.22  4857.0  351.78  4867.6  351.97  4878.1  351.08
  4888.6  350.99  4909.7  349.46  4941.4  347.95  4951.9  346.52  4962.4  343.91
  4973.0  342.85  4983.5  343.82  4991.4  341.98  4996.6  341.98  5001.2  336.84
  5003.9  336.34  5007.2  336.84  5014.3  341.23  5021.9  343.92  5044.7  344.42
  5065.0  343.98  5125.9  344.25  5136.0  343.84  5148.7  343.94  5204.4  348.47
  5209.5  348.49  5217.1  349.94  5257.6  352.79  5265.2  353.73  5298.2  355.22
#Mann=3,-1,0
  4835.9    0.16       0  5001.2    0.07       0  5007.2    0.16       0
Bank Sta=5001.2,5007.2
Exp/Cntr=0.3,0.1

Type RM Length L Ch R = 1,6752,620,620,620
BEGIN DESCRIPTION:
UNT167 IN CCTC 12.0
END DESCRIPTION:
XS GIS Cut Line= 2
      3559292.89     10673458.53      3558489.94     10673367.38
#Sta/Elev= 30
  4601.0  359.39  4630.0  357.56  4635.1  358.13  4684.8  355.87  4714.6  353.10
  4725.1  353.45  4804.2  347.62  4825.7  347.13  4835.8  345.54  4855.9  344.55
  4866.0  343.27  4885.8  342.89  4916.3  343.24  4936.4  338.90  4966.6  337.48
  4976.7  337.58  4983.5  340.31  4993.8  335.52  4996.6  335.02  4999.8  335.52
  5006.9  339.51  5016.9  341.49  5034.3  342.26  5087.4  343.19  5127.6  345.71
  5305.7  359.65  5336.9  361.86  5342.0  361.31  5369.2  363.82  5409.1  366.06
#Mann=6,-1,0
  4601.0    0.16       0  4885.8    0.12       0  4993.8    0.07       0
  4999.8    0.12       0  5034.3    0.16       0  5305.7    0.05       0
Bank Sta=4993.8,4999.8
Exp/Cntr=0.3,0.1

Type RM Length L Ch R = 1,6132,529,529,529
BEGIN DESCRIPTION:
UNT167 IN CCTC 11.0
END DESCRIPTION:
XS GIS Cut Line= 3
      3559301.58     10673150.36      3558984.77     10672929.02
      3558494.42     10672785.82
#Sta/Elev= 30
  4705.8  356.70  4750.3  355.62  4857.6  347.26  4866.3  345.52  4872.4  341.87
  4893.4  338.15  4937.9  339.06  4944.0  337.91  4958.8  338.37  4964.9  337.23
  4986.7  338.42  4994.5  338.26  5006.4  333.94  5009.1  333.44  5012.4  333.94
  5015.5  334.09  5024.2  339.24  5030.3  340.44  5074.2  341.13  5104.4  340.62
  5109.6  339.66  5137.9  341.20  5143.1  339.40  5220.4  340.71  5248.7  340.56
  5320.8  343.39  5420.6  348.29  5436.3  350.08  5597.7  362.39  5603.1  363.64
#Mann=6,-1,0
  4705.8    0.16       0  4986.7    0.12       0  5006.4    0.07       0
  5012.4    0.12       0  5220.4    0.16       0  5436.3    0.05       0
Bank Sta=5006.4,5012.4
Exp/Cntr=0.3,0.1

Type RM Length L Ch R = 1,5603,84,84,84
BEGIN DESCRIPTION:
UNT167 IN CCTC 10.0
END DESCRIPTION:
XS GIS Cut Line= 2
      3559809.42     10672981.10      3558390.17     10672117.40
#Sta/Elev= 30
  4256.5  362.48  4540.1  349.59  4592.4  343.46  4642.6  344.06  4650.5  347.23
  4671.8  344.75  4687.3  347.37  4791.6  347.79  4846.2  347.80  4947.0  341.05
  4983.8  336.49  4996.2  331.90  4999.0  331.40  5002.2  331.90  5014.7  336.53
  5225.9  335.98  5298.1  341.13  5326.6  340.44  5342.1  343.38  5347.9  340.83
  5378.9  345.05  5384.7  342.29  5516.4  352.18  5537.8  350.36  5580.4  355.31
  5595.9  353.39  5611.4  356.71  5696.6  358.78  5741.6  359.53  5917.9  363.30
#Mann=6,-1,0
  4256.5    0.16       0  4791.6    0.05       0  4996.2    0.04       0
  5002.2    0.05       0  5696.6    0.16       0  5741.6    0.05       0
Bank Sta=4996.2,5002.2
Exp/Cntr=0.3,0.1

Type RM Length L Ch R = 1,5519,616,616,616
BEGIN DESCRIPTION:
UNT167 IN CCTC 9.0
END DESCRIPTION:
XS GIS Cut Line= 2
      3559909.25     10672968.08      3558459.58     10672056.62
#Sta/Elev= 30
  4140.4  363.82  4364.4  354.08  4413.2  343.90  4494.3  343.57  4522.7  349.81
  4553.3  347.66  4559.2  349.53  4588.8  343.79  4767.6  343.84  4784.2  347.03
  4805.4  346.59  4848.7  343.07  4857.2  340.07  4863.1  343.00  4878.4  340.26
  4907.8  341.99  4966.7  339.40  4990.8  331.79  4993.6  331.29  4996.8  331.79
  5015.0  336.21  5098.7  334.72  5179.4  336.05  5313.0  339.55  5407.2  345.50
  5428.4  350.67  5464.9  348.78  5545.6  355.60  5675.6  361.56  5852.8  362.80
#Mann=6,-1,0
  4140.4    0.16       0  4767.6    0.05       0  4990.8    0.04       0
  4996.8    0.05       0  5098.7    0.12       0  5179.4    0.05       0
Bank Sta=4990.8,4996.8
Exp/Cntr=0.3,0.1

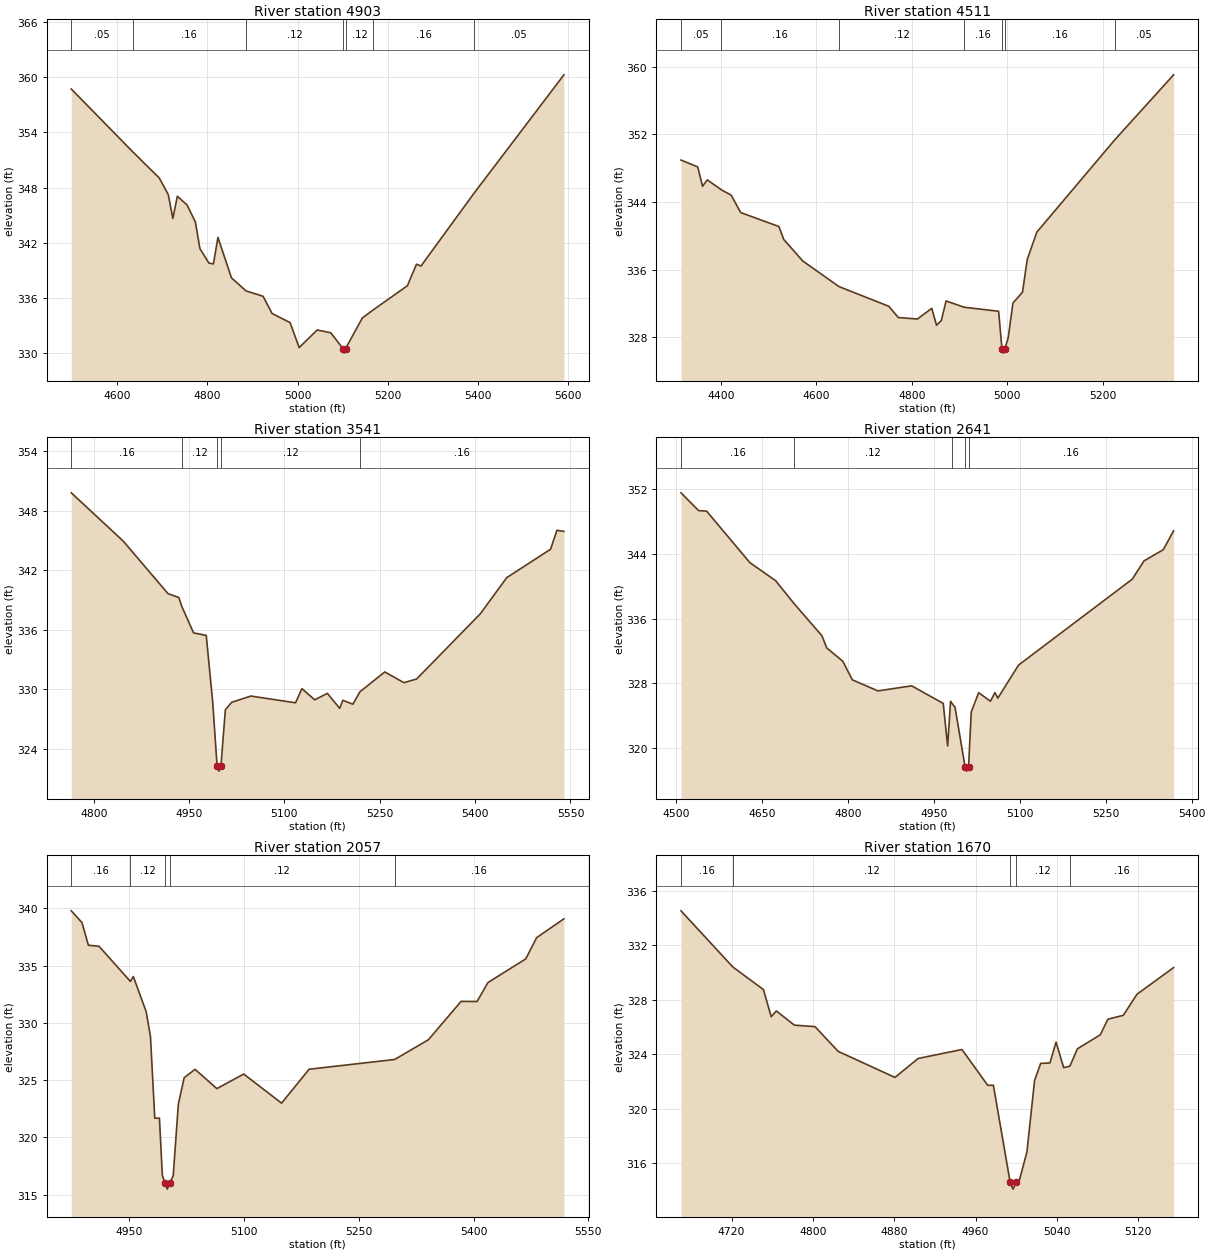
Type RM Length L Ch R = 1,4903,392,392,392
BEGIN DESCRIPTION:
UNT167 IN CCTC 8.0
END DESCRIPTION:
XS GIS Cut Line= 2
      3559774.68     10672013.22      3558682.73     10671978.56
#Sta/Elev= 30
  4498.0  358.69  4634.2  351.88  4693.2  349.03  4713.2  347.22  4723.2  344.65
  4733.2  347.05  4754.7  346.11  4773.2  344.26  4783.2  341.38  4803.2  339.80
  4813.2  339.71  4823.2  342.59  4853.2  338.20  4885.5  336.78  4923.3  336.20
  4943.3  334.33  4983.3  333.34  5003.3  330.63  5043.3  332.54  5073.4  332.24
  5100.4  330.53  5103.1  330.03  5106.4  330.53  5143.4  333.84  5167.8  334.73
  5243.4  337.34  5263.5  339.68  5273.5  339.48  5391.0  347.37  5590.5  360.23
#Mann=7,-1,0
  4498.0    0.05       0  4634.2    0.16       0  4885.5    0.12       0
  5100.4    0.07       0  5106.4    0.12       0  5167.8    0.16       0
  5391.0    0.05       0
Bank Sta=5100.4,5106.4
Exp/Cntr=0.3,0.1

Type RM Length L Ch R = 1,4511,970,970,970
BEGIN DESCRIPTION:
UNT167 IN CCTC 7.0
END DESCRIPTION:
XS GIS Cut Line= 2
      3559774.68     10671666.00      3558743.18     10671666.00
#Sta/Elev= 30
  4316.7  348.96  4351.8  348.15  4361.8  345.86  4371.8  346.62  4401.4  345.44
  4421.8  344.81  4441.8  342.75  4521.8  341.10  4531.8  339.58  4571.8  337.02
  4647.5  334.00  4751.8  331.67  4771.8  330.34  4811.8  330.16  4841.8  331.43
  4851.8  329.43  4861.8  329.98  4871.8  332.30  4909.5  331.56  4981.8  331.08
  4988.8  326.63  4991.5  326.13  4994.8  326.63  5001.8  327.93  5011.8  332.05
  5031.8  333.34  5041.8  337.22  5061.8  340.44  5225.3  351.37  5348.2  359.04
#Mann=7,-1,0
  4316.7    0.05       0  4401.4    0.16       0  4647.5    0.12       0
  4909.5    0.16       0  4988.8    0.07       0  4994.8    0.16       0
  5225.3    0.05       0
Bank Sta=4988.8,4994.8
Exp/Cntr=0.3,0.1

Type RM Length L Ch R = 1,3541,900,900,900
BEGIN DESCRIPTION:
UNT167 IN CCTC 6.0
END DESCRIPTION:
XS GIS Cut Line= 2
      3559721.28     10671261.76      3558948.67     10671322.52
#Sta/Elev= 30
  4764.7  349.82  4846.6  344.94  4916.8  339.66  4933.9  339.26  4938.7  338.35
  4957.0  335.70  4977.0  335.44  4987.1  328.78  4994.1  322.26  4996.8  321.76
  5000.1  322.26  5007.1  327.96  5017.1  328.70  5047.2  329.33  5117.5  328.65
  5127.5  330.08  5147.6  328.95  5167.6  329.60  5186.9  328.09  5191.9  328.90
  5207.7  328.51  5218.8  329.76  5257.9  331.76  5288.0  330.68  5308.0  331.05
  5408.4  337.64  5449.8  341.27  5518.7  344.13  5528.7  346.04  5539.7  345.93
#Mann=5,-1,0
  4764.7    0.16       0  4938.7    0.12       0  4994.1    0.07       0
  5000.1    0.12       0  5218.8    0.16       0
Bank Sta=4994.1,5000.1
Exp/Cntr=0.3,0.1

Type RM Length L Ch R = 1,2641,584,584,584
BEGIN DESCRIPTION:
UNT167 IN CCTC 5.0
END DESCRIPTION:
XS GIS Cut Line= 3
      3559549.65     10670710.17      3559149.61     10670910.19
      3558749.58     10671010.20
#Sta/Elev= 30
  4508.9  351.48  4539.7  349.29  4553.7  349.22  4629.1  342.88  4673.9  340.67
  4705.7  337.88  4754.9  333.87  4763.3  332.37  4791.2  330.74  4808.0  328.44
  4852.7  327.08  4911.4  327.71  4966.5  325.54  4974.2  320.30  4979.3  325.79
  4981.4  325.59  4987.1  325.06  5004.7  317.70  5007.4  317.20  5010.7  317.70
  5015.4  324.48  5028.3  326.86  5048.9  325.81  5056.7  326.87  5061.8  326.19
  5097.9  330.26  5296.3  340.84  5316.9  343.10  5350.4  344.47  5368.5  346.80
#Mann=5,-1,0
  4508.9    0.16       0  4705.7    0.12       0  4981.4    0.16       0
  5004.7    0.07       0  5010.7    0.16       0
Bank Sta=5004.7,5010.7
Exp/Cntr=0.3,0.1

Type RM Length L Ch R = 1,2057,387,387,387
BEGIN DESCRIPTION:
UNT167 IN CCTC 4.0
END DESCRIPTION:
XS GIS Cut Line= 3
      3559299.59     10670460.20      3559199.61     10670510.19
      3558799.60     10670860.20
#Sta/Elev= 30
  4874.7  339.77  4888.7  338.74  4897.0  336.77  4911.0  336.67  4951.9  333.61
  4955.7  334.04  4972.5  330.97  4978.1  328.79  4983.7  321.68  4989.8  321.68
  4993.6  316.69  4997.2  315.99  5000.0  315.49  5003.2  315.99  5007.8  316.67
  5014.5  322.90  5022.1  325.21  5036.3  325.94  5064.8  324.26  5099.9  325.53
  5149.3  322.99  5185.3  325.95  5297.0  326.80  5341.0  328.52  5383.7  331.87
  5404.6  331.86  5418.8  333.51  5468.2  335.58  5482.4  337.43  5518.0  339.07
#Mann=5,-1,0
  4874.7    0.16       0  4951.9    0.12       0  4997.2    0.07       0
  5003.2    0.12       0  5297.0    0.16       0
Bank Sta=4997.2,5003.2
Exp/Cntr=0.3,0.1

Type RM Length L Ch R = 1,1670,429,429,429
BEGIN DESCRIPTION:
UNT167 IN CCTC 3.0
END DESCRIPTION:
XS GIS Cut Line= 3
      3559199.64     10670310.18      3558899.61     10670360.19
      3558749.65     10670460.16
#Sta/Elev= 30
  4670.3  334.53  4721.2  330.41  4751.4  328.74  4759.0  326.75  4764.1  327.17
  4781.8  326.13  4802.1  326.02  4824.9  324.20  4880.7  322.29  4903.5  323.68
  4946.6  324.34  4971.9  321.71  4977.5  321.71  4994.0  314.58  4996.8  314.08
  5000.0  314.58  5003.0  314.72  5010.5  316.82  5018.0  322.07  5024.0  323.32
  5033.1  323.35  5039.1  324.88  5046.6  323.01  5052.7  323.11  5060.1  324.39
  5082.6  325.42  5090.1  326.57  5105.2  326.85  5118.7  328.40  5154.7  330.36
#Mann=5,-1,0
  4670.3    0.16       0  4721.2    0.12       0  4994.0    0.07       0
  5000.0    0.12       0  5052.7    0.16       0
Bank Sta=4994,5000
Exp/Cntr=0.3,0.1

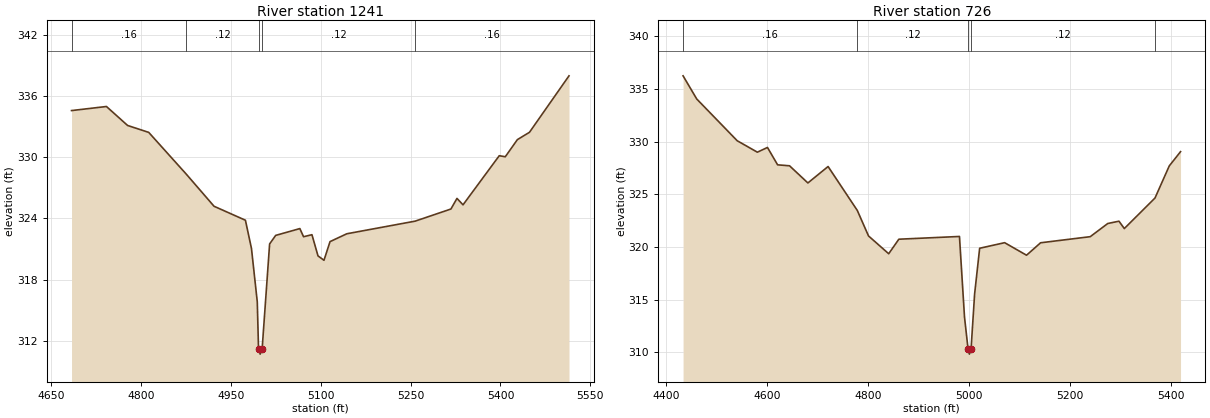
Type RM Length L Ch R = 1,1241,515,515,515
BEGIN DESCRIPTION:
UNT167 IN CCTC 2.0
END DESCRIPTION:
XS GIS Cut Line= 2
      3559347.36     10670092.49      3558524.23     10670205.13
#Sta/Elev= 30
  4683.7  334.58  4742.0  334.98  4777.3  333.12  4812.6  332.44  4875.5  328.33
  4921.7  325.19  4974.1  323.82  4984.2  321.05  4993.9  315.81  4996.0  311.18
  4998.7  310.68  5002.0  311.18  5014.5  321.49  5024.6  322.33  5065.0  323.00
  5071.2  322.20  5085.2  322.40  5095.3  320.32  5105.3  319.89  5115.4  321.72
  5143.4  322.49  5257.6  323.73  5317.3  324.92  5327.4  325.96  5337.5  325.33
  5398.0  330.15  5408.1  330.05  5428.3  331.73  5448.5  332.45  5514.5  337.99
#Mann=5,-1,0
  4683.7    0.16       0  4875.5    0.12       0  4996.0    0.07       0
  5002.0    0.12       0  5257.6    0.16       0
Bank Sta=4996,5002
Exp/Cntr=0.3,0.1

Type RM Length L Ch R = 1,726,0,0,0
BEGIN DESCRIPTION:
UNT167 IN CCTC 1.0
END DESCRIPTION:
XS GIS Cut Line= 3
      3559516.71     10669736.58      3558883.00     10669762.63
      3558570.50     10669923.22
#Sta/Elev= 30
  4433.2  336.25  4460.3  334.05  4540.4  330.09  4580.4  329.00  4600.4  329.45
  4620.5  327.80  4644.1  327.71  4680.5  326.08  4720.5  327.64  4778.4  323.47
  4800.6  321.05  4840.6  319.36  4860.7  320.74  4980.8  321.00  4990.8  313.34
  4997.8  310.33  5000.5  309.83  5003.8  310.33  5010.8  315.53  5020.8  319.88
  5070.3  320.41  5113.7  319.22  5141.5  320.40  5239.9  320.98  5274.6  322.23
  5296.8  322.45  5307.4  321.75  5368.2  324.65  5396.5  327.70  5418.8  329.05
#Mann=5,-1,0
  4433.2    0.16       0  4778.4    0.12       0  4997.8    0.07       0
  5003.8    0.12       0  5368.2    0.16       0
Bank Sta=4997.8,5003.8
Exp/Cntr=0.3,0.1

Chan Stop Cuts=-1