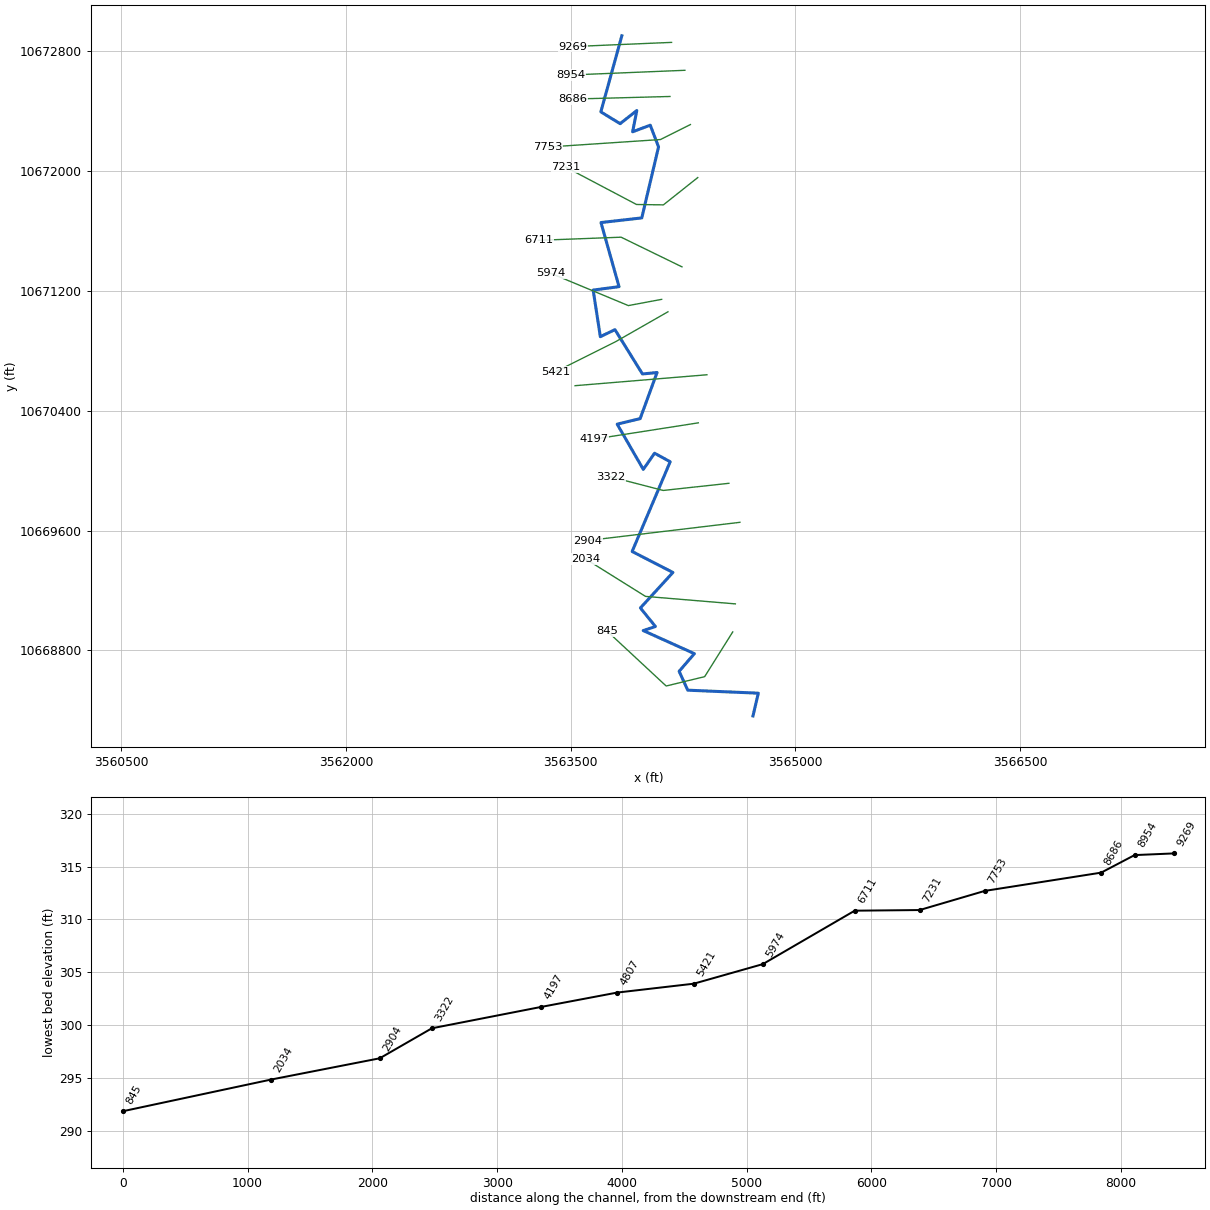
--- UNT169 IN CCTC.prj (project) ---

Proj Title=UNT169 IN CCTC Base Level Engineering
Current Plan=p01
Default Exp/Contr=0.3,0.1
English Units
Geom File=g01
Flow File=f01
Plan File=p01
BEGIN DESCRIPTION:
UNT169 IN CCTC
END DESCRIPTION:

--- UNT169 IN CCTC.p01 (plan) ---

Plan Title=Multiple Run
Short Identifier=Multiple
Geom File=g01
Flow File=f01
Subcritical Flow
K Sum by GR= 0
Std Step Tol= 0.01
Critical Tol= 0.01
Num of Std Step Trials= 20
Max Error Tol= 0.3
Flow Tol Ratio= 0.001
Split Flow NTrial= 30
Split Flow Tol= 0.02
Split Flow Ratio= 0.02
Log Output Level= 0
Friction Slope Method= 1
Unsteady Friction Slope Method= 2
Unsteady Bridges Friction Slope Method= 1
Parabolic Critical Depth
Global Vel Dist=  1 , 1 , 1
Global Log Level= 0
CheckData=True
Encroach Param= -1, 0, 0, 0
BEGIN DESCRIPTION:
Multiple Run
END DESCRIPTION:

--- UNT169 IN CCTC.f01 (steady flow) ---

Flow Title=Multiple
Number of Profiles=7
Profile Names=10-year,25-year,50-year,1pct_min,100-year,1pct_plu,500-year
River Rch & RM= UNT169 IN CCTC,Reach-1,9269
    1460    2005    2454    2190    2962    4005    4300
Boundary for River Rch & Prof#=UNT169 IN CCTC,Reach-1,1
Up Type=0
Dn Type=3
Dn Slope=0.005
Boundary for River Rch & Prof#=UNT169 IN CCTC,Reach-1,2
Up Type=0
Dn Type=3
Dn Slope=0.005
Boundary for River Rch & Prof#=UNT169 IN CCTC,Reach-1,3
Up Type=0
Dn Type=3
Dn Slope=0.005
Boundary for River Rch & Prof#=UNT169 IN CCTC,Reach-1,4
Up Type=0
Dn Type=3
Dn Slope=0.005
Boundary for River Rch & Prof#=UNT169 IN CCTC,Reach-1,5
Up Type=0
Dn Type=3
Dn Slope=0.005
Boundary for River Rch & Prof#=UNT169 IN CCTC,Reach-1,6
Up Type=0
Dn Type=3
Dn Slope=0.005
Boundary for River Rch & Prof#=UNT169 IN CCTC,Reach-1,7
Up Type=0
Dn Type=3
Dn Slope=0.005

--- UNT169 IN CCTC.g01 (geometry) ---

Geom Title=Existing Conditions

River Reach=UNT169 IN CCTC,Reach-1
Reach XY= 30
      3563841.75     10672903.00      3563701.50     10672395.00
      3563830.25     10672316.00      3563941.75     10672404.00
      3563913.75     10672262.00      3564031.50     10672306.00
      3564086.75     10672161.00      3563975.00     10671687.00
      3563702.50     10671656.00      3563823.00     10671228.00
      3563650.25     10671205.00      3563698.25     10670894.00
      3563795.75     10670941.00      3563979.50     10670645.00
      3564077.00     10670655.00      3563964.00     10670347.00
      3563810.75     10670310.00      3563985.00     10670008.00
      3564060.25     10670116.00      3564164.50     10670059.00
      3563910.50     10669460.00      3564182.75     10669320.00
      3563965.75     10669083.00      3564066.00     10668959.00
      3563984.50     10668932.00      3564326.00     10668778.00
      3564224.25     10668660.00      3564281.75     10668534.00
      3564752.75     10668514.00      3564717.25     10668362.00

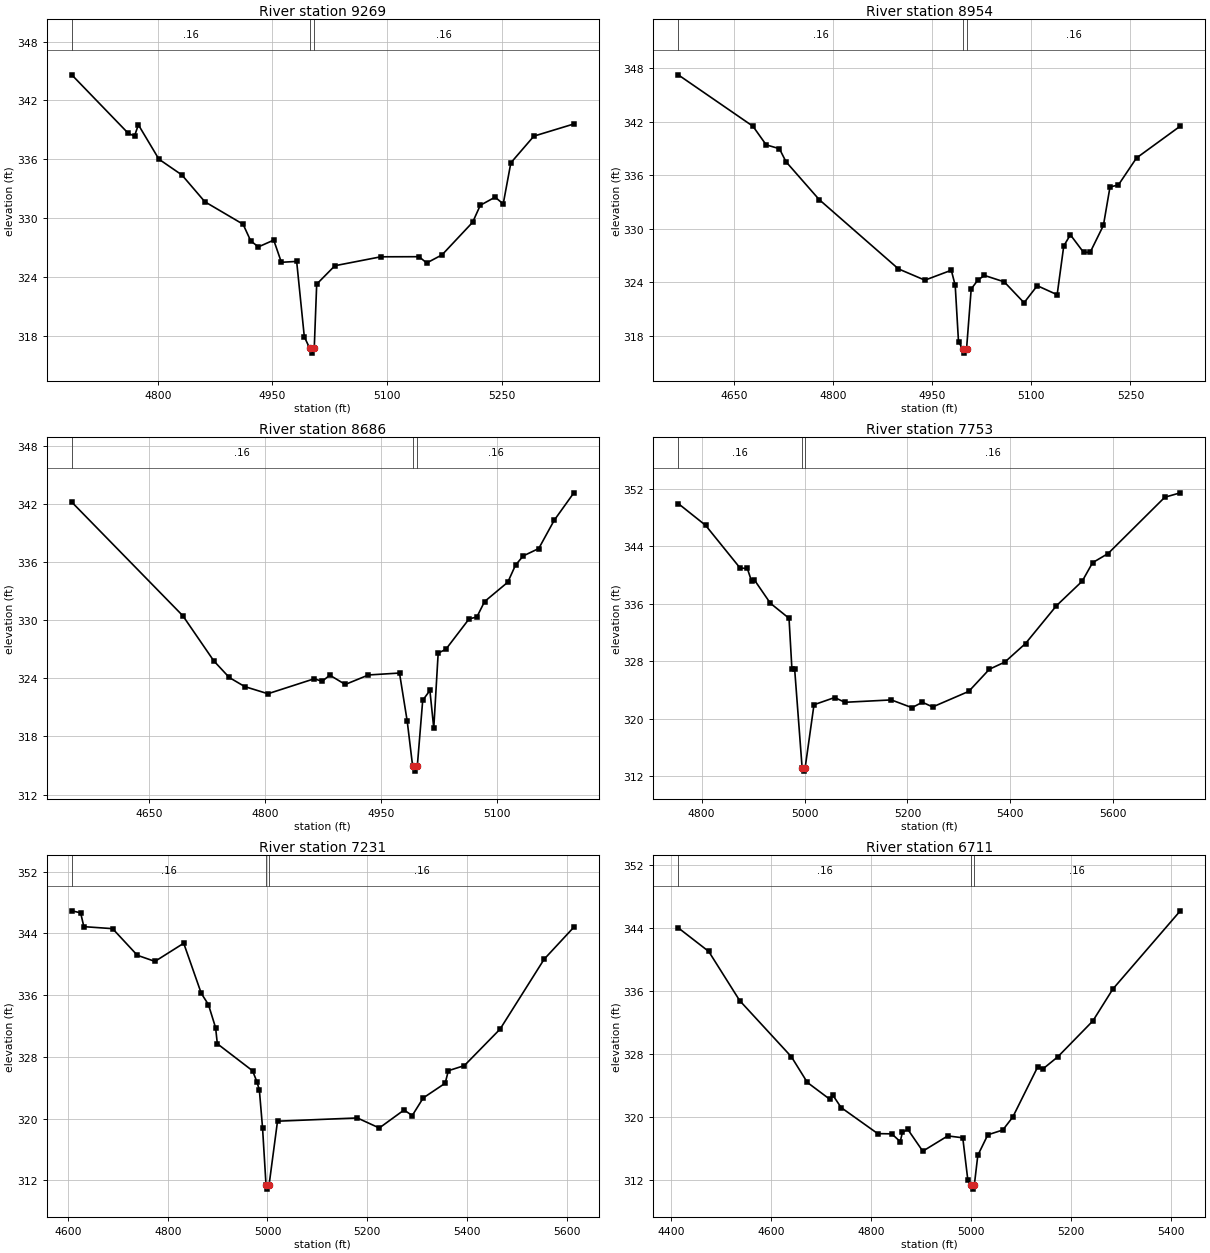
Type RM Length L Ch R = 1,9269,315,315,315
BEGIN DESCRIPTION:
UNT169 IN CCTC 14.0
END DESCRIPTION:
XS GIS Cut Line= 2
      3564173.53     10672858.79      3563517.32     10672831.01
#Sta/Elev= 30
  4687.6  344.61  4761.6  338.64  4769.7  338.37  4774.7  339.52  4801.6  336.01
  4831.7  334.40  4861.7  331.67  4911.7  329.38  4921.7  327.68  4931.7  327.07
  4951.8  327.76  4961.8  325.50  4981.8  325.59  4991.8  317.91  4998.8  316.74
  5001.6  316.24  5004.8  316.74  5008.0  323.27  5031.8  325.15  5091.9  326.06
  5141.9  326.07  5151.9  325.43  5172.0  326.26  5212.0  329.58  5222.0  331.31
  5241.4  332.14  5252.0  331.45  5262.0  335.64  5292.1  338.36  5344.4  339.60
#Mann=3,-1,0
  4687.6    0.16       0  4998.8    0.07       0  5004.8    0.16       0
Bank Sta=4998.8,5004.8
Exp/Cntr=0.3,0.1

Type RM Length L Ch R = 1,8954,268,268,268
BEGIN DESCRIPTION:
UNT169 IN CCTC 13.0
END DESCRIPTION:
XS GIS Cut Line= 2
      3564262.60     10672672.44      3563503.34     10672641.24
#Sta/Elev= 30
  4565.5  347.24  4678.6  341.48  4698.6  339.40  4718.6  338.97  4728.6  337.51
  4778.7  333.28  4898.8  325.51  4938.8  324.25  4978.8  325.36  4984.7  323.66
  4989.7  317.34  4995.9  316.58  4998.6  316.08  5001.9  316.58  5008.9  323.26
  5018.9  324.25  5028.9  324.78  5058.9  324.06  5088.9  321.72  5108.9  323.63
  5139.0  322.62  5149.0  328.08  5159.0  329.33  5179.0  327.36  5189.0  327.37
  5209.0  330.38  5219.0  334.69  5231.6  334.90  5259.1  337.93  5325.4  341.50
#Mann=3,-1,0
  4565.5    0.16       0  4995.9    0.07       0  5001.9    0.16       0
Bank Sta=4995.9,5001.9
Exp/Cntr=0.3,0.1

Type RM Length L Ch R = 1,8686,933,933,933
BEGIN DESCRIPTION:
UNT169 IN CCTC 12.0
END DESCRIPTION:
XS GIS Cut Line= 2
      3564163.12     10672497.68      3563514.25     10672480.33
#Sta/Elev= 30
  4549.9  342.23  4693.5  330.48  4733.5  325.82  4753.5  324.10  4773.5  323.16
  4803.5  322.42  4863.5  323.97  4873.5  323.70  4883.5  324.34  4903.5  323.38
  4933.5  324.36  4973.6  324.56  4983.6  319.57  4990.6  314.92  4993.3  314.42
  4996.6  314.92  5003.6  321.74  5012.9  322.76  5017.9  318.86  5023.6  326.62
  5033.6  327.02  5063.6  330.16  5073.6  330.35  5083.6  331.95  5113.6  333.95
  5123.6  335.72  5133.6  336.67  5153.6  337.43  5173.6  340.35  5199.0  343.19
#Mann=3,-1,0
  4549.9    0.16       0  4990.6    0.07       0  4996.6    0.16       0
Bank Sta=4990.6,4996.6
Exp/Cntr=0.3,0.1

Type RM Length L Ch R = 1,7753,522,522,522
BEGIN DESCRIPTION:
UNT169 IN CCTC 11.0
END DESCRIPTION:
XS GIS Cut Line= 3
      3564299.60     10672310.19      3564099.61     10672210.19
      3563349.58     10672160.19
#Sta/Elev= 30
  4754.7  349.93  4807.8  346.90  4874.9  340.95  4888.9  340.90  4897.2  339.11
  4902.8  339.28  4933.6  336.06  4969.9  333.96  4975.5  326.94  4980.8  326.94
  4995.3  313.19  4998.1  312.69  5001.3  313.19  5018.4  321.93  5058.5  322.93
  5078.5  322.27  5168.7  322.60  5208.8  321.52  5228.9  322.28  5248.9  321.62
  5319.1  323.79  5359.1  326.87  5389.2  327.87  5429.3  330.45  5489.4  335.71
  5539.5  339.13  5559.6  341.70  5589.7  342.97  5699.9  350.81  5730.0  351.42
#Mann=3,-1,0
  4754.7    0.16       0  4995.3    0.07       0  5001.3    0.16       0
Bank Sta=4995.3,5001.3
Exp/Cntr=0.3,0.1

Type RM Length L Ch R = 1,7231,520,520,520
BEGIN DESCRIPTION:
UNT169 IN CCTC 10.0
END DESCRIPTION:
XS GIS Cut Line= 4
      3564348.52     10671956.30      3564119.34     10671774.00
      3563939.66     10671776.60      3563467.02     10672025.91
#Sta/Elev= 30
  4607.5  346.93  4625.3  346.67  4631.7  344.88  4689.4  344.62  4739.0  341.17
  4774.3  340.38  4832.0  342.73  4867.2  336.24  4881.6  334.78  4896.0  331.77
  4899.4  329.71  4970.1  326.21  4978.7  324.80  4983.7  323.73  4990.1  318.81
  4997.1  311.38  4999.8  310.88  5003.1  311.38  5020.1  319.68  5180.2  320.10
  5224.2  318.80  5273.9  321.13  5290.3  320.41  5312.3  322.69  5356.4  324.60
  5362.7  326.22  5394.8  326.88  5466.5  331.61  5554.9  340.67  5614.4  344.81
#Mann=3,-1,0
  4607.5    0.16       0  4997.1    0.07       0  5003.1    0.16       0
Bank Sta=4997.1,5003.1
Exp/Cntr=0.3,0.1

Type RM Length L Ch R = 1,6711,737,737,737
BEGIN DESCRIPTION:
UNT169 IN CCTC 9.0
END DESCRIPTION:
XS GIS Cut Line= 3
      3564243.12     10671360.29      3563836.88     10671558.20
      3563284.76     10671537.37
#Sta/Elev= 30
  4414.9  344.01  4475.9  341.01  4537.9  334.76  4641.3  327.63  4673.2  324.37
  4718.2  322.23  4723.8  322.79  4740.8  321.18  4814.0  317.87  4842.1  317.84
  4859.0  316.85  4863.3  318.02  4874.1  318.41  4904.1  315.64  4954.1  317.58
  4984.1  317.34  4994.2  312.00  5001.2  311.32  5003.9  310.82  5007.2  311.32
  5014.2  315.11  5034.2  317.72  5064.2  318.33  5084.2  319.98  5134.2  326.37
  5144.3  326.08  5174.3  327.63  5244.3  332.18  5284.4  336.24  5419.3  346.17
#Mann=3,-1,0
  4414.9    0.16       0  5001.2    0.07       0  5007.2    0.16       0
Bank Sta=5001.2,5007.2
Exp/Cntr=0.3,0.1

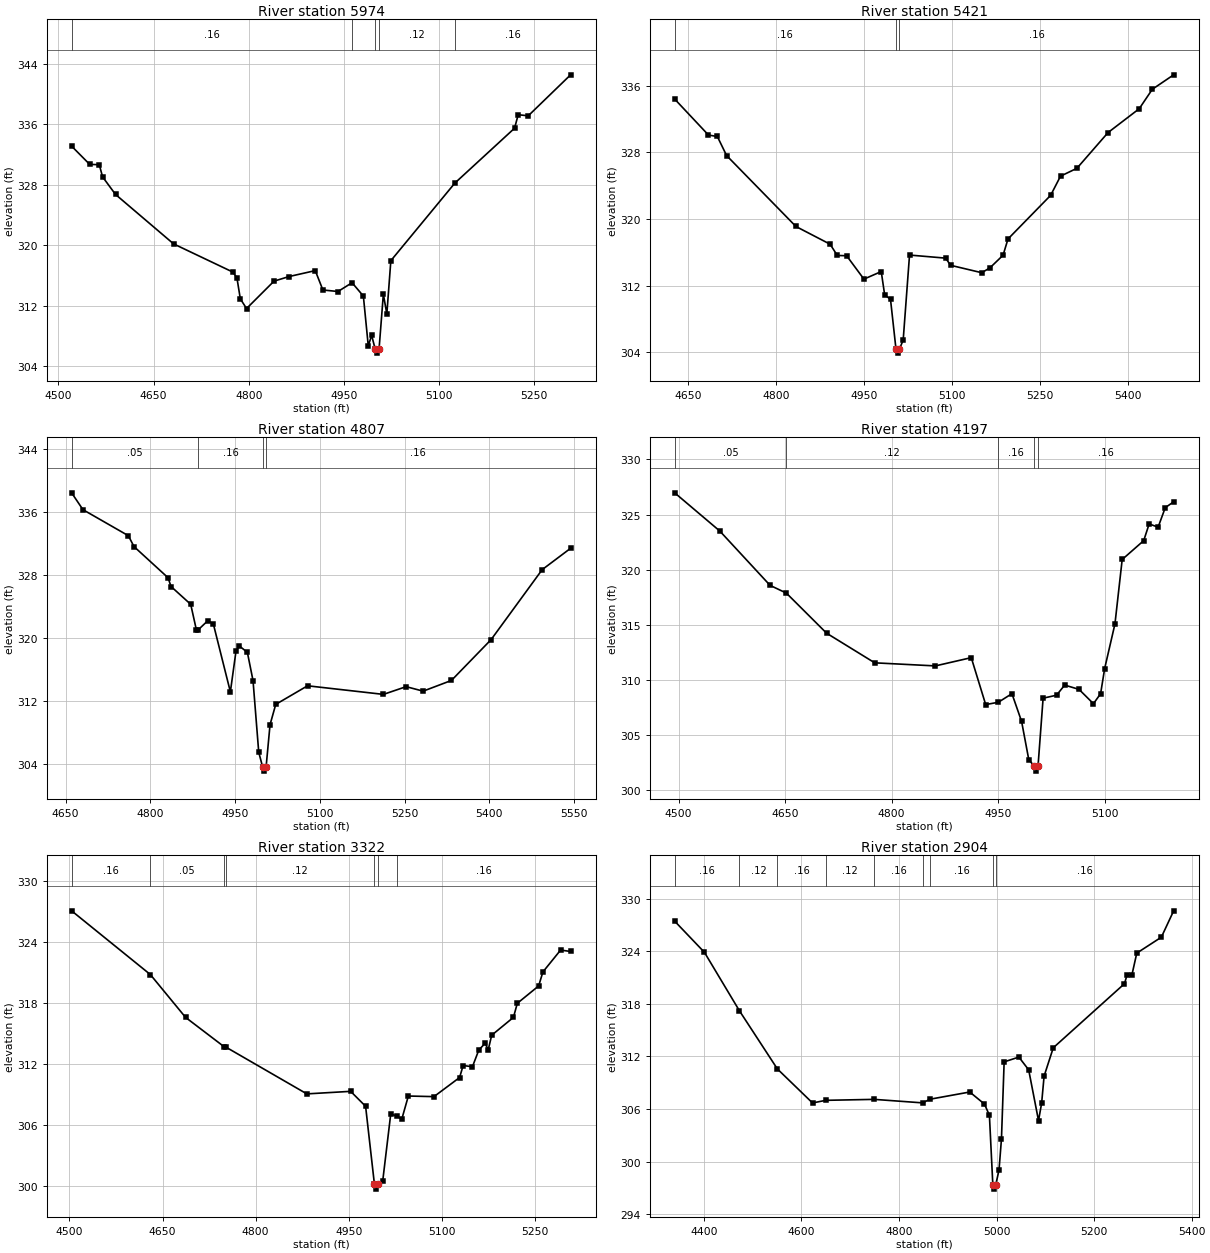
Type RM Length L Ch R = 1,5974,553,553,553
BEGIN DESCRIPTION:
UNT169 IN CCTC 8.0
END DESCRIPTION:
XS GIS Cut Line= 3
      3564107.59     10671143.22      3563885.39     10671101.56
      3563368.06     10671316.82
#Sta/Elev= 30
  4520.9  333.10  4549.4  330.69  4564.5  330.65  4569.7  329.04  4590.1  326.72
  4681.6  320.19  4774.9  316.47  4781.4  315.72  4786.8  312.93  4796.6  311.65
  4839.9  315.27  4863.8  315.88  4904.9  316.66  4916.9  314.10  4940.7  313.90
  4962.9  315.06  4980.7  313.30  4988.4  306.74  4993.8  308.10  4999.4  306.26
  5002.1  305.76  5005.4  306.26  5012.2  313.54  5017.7  310.93  5024.0  317.97
  5124.9  328.22  5219.0  335.47  5224.7  337.25  5240.6  337.11  5307.3  342.52
#Mann=5,-1,0
  4520.9    0.16       0  4962.9    0.12       0  4999.4    0.07       0
  5005.4    0.12       0  5124.9    0.16       0
Bank Sta=4999.4,5005.4
Exp/Cntr=0.3,0.1

Type RM Length L Ch R = 1,5421,614,614,614
BEGIN DESCRIPTION:
UNT169 IN CCTC 7.0
END DESCRIPTION:
XS GIS Cut Line= 3
      3564149.60     10671060.19      3563799.61     10670860.19
      3563399.63     10670660.20
#Sta/Elev= 30
  4627.2  334.40  4684.8  330.08  4699.9  329.91  4715.7  327.62  4833.8  319.11
  4892.1  316.98  4904.3  315.63  4920.2  315.60  4949.7  312.79  4979.2  313.70
  4985.0  310.92  4995.0  310.36  5004.3  304.41  5007.0  303.91  5010.3  304.41
  5016.6  305.48  5027.4  315.68  5089.0  315.31  5097.4  314.45  5150.5  313.56
  5164.5  314.15  5186.8  315.66  5195.2  317.61  5267.9  322.85  5284.7  325.15
  5312.6  326.09  5365.7  330.38  5418.8  333.24  5441.2  335.58  5477.5  337.31
#Mann=3,-1,0
  4627.2    0.16       0  5004.3    0.07       0  5010.3    0.16       0
Bank Sta=5004.3,5010.3
Exp/Cntr=0.3,0.1

Type RM Length L Ch R = 1,4807,610,610,610
BEGIN DESCRIPTION:
UNT169 IN CCTC 6.0
END DESCRIPTION:
XS GIS Cut Line= 2
      3564409.66     10670639.75      3563529.47     10670566.84
#Sta/Elev= 30
  4660.5  338.39  4680.6  336.25  4760.9  332.95  4770.9  331.57  4831.1  327.62
  4836.5  326.50  4871.3  324.24  4881.3  321.01  4884.5  321.00  4901.4  322.15
  4911.4  321.74  4941.5  313.13  4951.5  318.32  4957.3  318.96  4971.6  318.14
  4981.6  314.56  4991.7  305.47  4998.7  303.57  5001.5  303.07  5004.7  303.57
  5011.7  308.96  5021.8  311.54  5078.1  313.90  5212.4  312.81  5252.6  313.79
  5282.7  313.22  5332.8  314.58  5403.1  319.77  5493.4  328.64  5543.7  331.35
#Mann=4,-1,0
  4660.5    0.05       0  4884.5    0.16       0  4998.7    0.07       0
  5004.7    0.16       0
Bank Sta=4998.7,5004.7
Exp/Cntr=0.3,0.1

Type RM Length L Ch R = 1,4197,875,875,875
BEGIN DESCRIPTION:
UNT169 IN CCTC 5.0
END DESCRIPTION:
XS GIS Cut Line= 2
      3564352.41     10670318.79      3563657.94     10670210.28
#Sta/Elev= 30
  4494.4  326.97  4558.0  323.50  4628.8  318.57  4651.7  317.87  4708.4  314.23
  4776.2  311.54  4861.6  311.26  4912.2  312.01  4932.5  307.75  4950.3  307.96
  4969.5  308.74  4983.1  306.22  4993.2  302.76  5000.3  302.21  5003.1  301.71
  5006.3  302.21  5013.4  308.33  5032.3  308.60  5043.8  309.52  5064.0  309.13
  5084.3  307.83  5094.4  308.74  5100.1  311.02  5114.6  315.07  5124.8  320.92
  5155.1  322.63  5162.8  324.15  5175.4  323.85  5185.5  325.63  5197.3  326.15
#Mann=5,-1,0
  4494.4    0.05       0  4651.7    0.12       0  4950.3    0.16       0
  5000.3    0.07       0  5006.3    0.16       0
Bank Sta=5000.3,5006.3
Exp/Cntr=0.3,0.1

Type RM Length L Ch R = 1,3322,418,418,418
BEGIN DESCRIPTION:
UNT169 IN CCTC 4.0
END DESCRIPTION:
XS GIS Cut Line= 3
      3564556.44     10669915.15      3564118.03     10669867.40
      3563766.46     10669958.55
#Sta/Elev= 30
  4503.5  327.07  4630.4  320.80  4687.1  316.59  4749.5  313.69  4752.5  313.65
  4882.6  309.06  4953.2  309.31  4977.3  307.84  4991.5  300.19  4994.3  299.69
  4997.5  300.19  5004.9  300.49  5017.9  307.12  5027.3  306.85  5035.8  306.61
  5046.2  308.85  5087.5  308.79  5128.8  310.67  5134.5  311.85  5149.5  311.73
  5159.8  313.38  5169.9  314.03  5175.0  313.41  5180.5  314.83  5215.6  316.59
  5221.8  317.97  5256.2  319.68  5263.1  321.06  5291.6  323.21  5307.7  323.07
#Mann=7,-1,0
  4503.5    0.16       0  4630.4    0.05       0  4749.5    0.16       0
  4752.5    0.12       0  4991.5    0.07       0  4997.5    0.12       0
  5027.3    0.16       0
Bank Sta=4991.5,4997.5
Exp/Cntr=0.3,0.1

Type RM Length L Ch R = 1,2904,870,870,870
BEGIN DESCRIPTION:
UNT169 IN CCTC 3.0
END DESCRIPTION:
XS GIS Cut Line= 2
      3564630.21     10669654.73      3563614.55     10669533.20
#Sta/Elev= 30
  4340.2  327.45  4401.2  323.89  4472.9  317.22  4550.8  310.57  4622.8  306.69
  4650.0  306.99  4749.2  307.10  4848.4  306.70  4863.9  307.12  4945.1  307.94
  4975.3  306.56  4985.4  305.28  4992.4  297.35  4995.2  296.85  4998.4  297.35
  5005.1  299.03  5010.1  302.58  5015.6  311.38  5045.8  311.93  5065.9  310.47
  5086.1  304.67  5092.5  306.69  5097.5  309.75  5116.3  312.99  5262.3  320.31
  5267.4  321.28  5277.4  321.28  5287.5  323.80  5337.9  325.62  5363.1  328.63
#Mann=9,-1,0
  4340.2    0.16       0  4472.9    0.12       0  4550.8    0.16       0
  4650.0    0.12       0  4749.2    0.16       0  4848.4    0.12       0
  4863.9    0.16       0  4992.4    0.07       0  4998.4    0.16       0
Bank Sta=4992.4,4998.4
Exp/Cntr=0.3,0.1

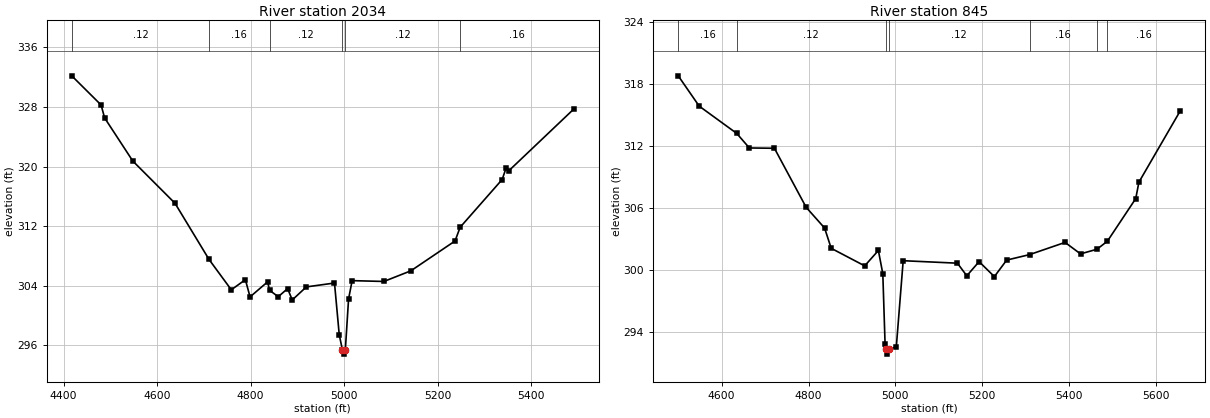
Type RM Length L Ch R = 1,2034,1189,1189,1189
BEGIN DESCRIPTION:
UNT169 IN CCTC 2.0
END DESCRIPTION:
XS GIS Cut Line= 3
      3564599.61     10669110.19      3563999.61     10669160.19
      3563599.59     10669410.20
#Sta/Elev= 30
  4417.4  332.18  4480.1  328.27  4487.6  326.54  4547.9  320.75  4638.2  315.08
  4711.0  307.54  4758.6  303.47  4788.7  304.83  4798.7  302.52  4836.3  304.54
  4840.4  303.41  4858.9  302.54  4879.0  303.63  4889.0  302.11  4919.1  303.86
  4979.3  304.38  4989.4  297.47  4996.4  295.34  4999.2  294.84  5002.4  295.34
  5009.4  302.24  5017.0  304.70  5084.9  304.59  5142.7  306.02  5237.1  310.02
  5248.0  311.86  5337.9  318.27  5346.7  319.88  5352.6  319.47  5491.2  327.73
#Mann=6,-1,0
  4417.4    0.12       0  4711.0    0.16       0  4840.4    0.12       0
  4996.4    0.07       0  5002.4    0.12       0  5248.0    0.16       0
Bank Sta=4996.4,5002.4
Exp/Cntr=0.3,0.1

Type RM Length L Ch R = 1,845,0,0,0
BEGIN DESCRIPTION:
UNT169 IN CCTC 1.0
END DESCRIPTION:
XS GIS Cut Line= 4
      3564582.17     10668922.99      3564394.65     10668624.35
      3564137.70     10668561.85      3563743.25     10668928.62
#Sta/Elev= 30
  4500.1  318.77  4548.3  315.84  4634.7  313.20  4663.8  311.79  4721.5  311.76
  4794.5  306.05  4837.0  304.04  4852.2  302.08  4929.3  300.38  4960.8  301.87
  4971.0  299.62  4976.2  292.83  4978.4  292.34  4981.2  291.84  4984.4  292.34
  5002.0  292.51  5017.9  300.88  5142.7  300.64  5164.3  299.42  5192.6  300.79
  5227.8  299.34  5256.1  300.94  5308.9  301.47  5390.5  302.65  5426.1  301.54
  5464.0  301.99  5488.0  302.77  5553.2  306.89  5560.5  308.48  5655.8  315.39
#Mann=7,-1,0
  4500.1    0.16       0  4634.7    0.12       0  4978.4    0.07       0
  4984.4    0.12       0  5308.9    0.16       0  5464.0    0.12       0
  5488.0    0.16       0
Bank Sta=4978.4,4984.4
Exp/Cntr=0.3,0.1

Chan Stop Cuts=-1