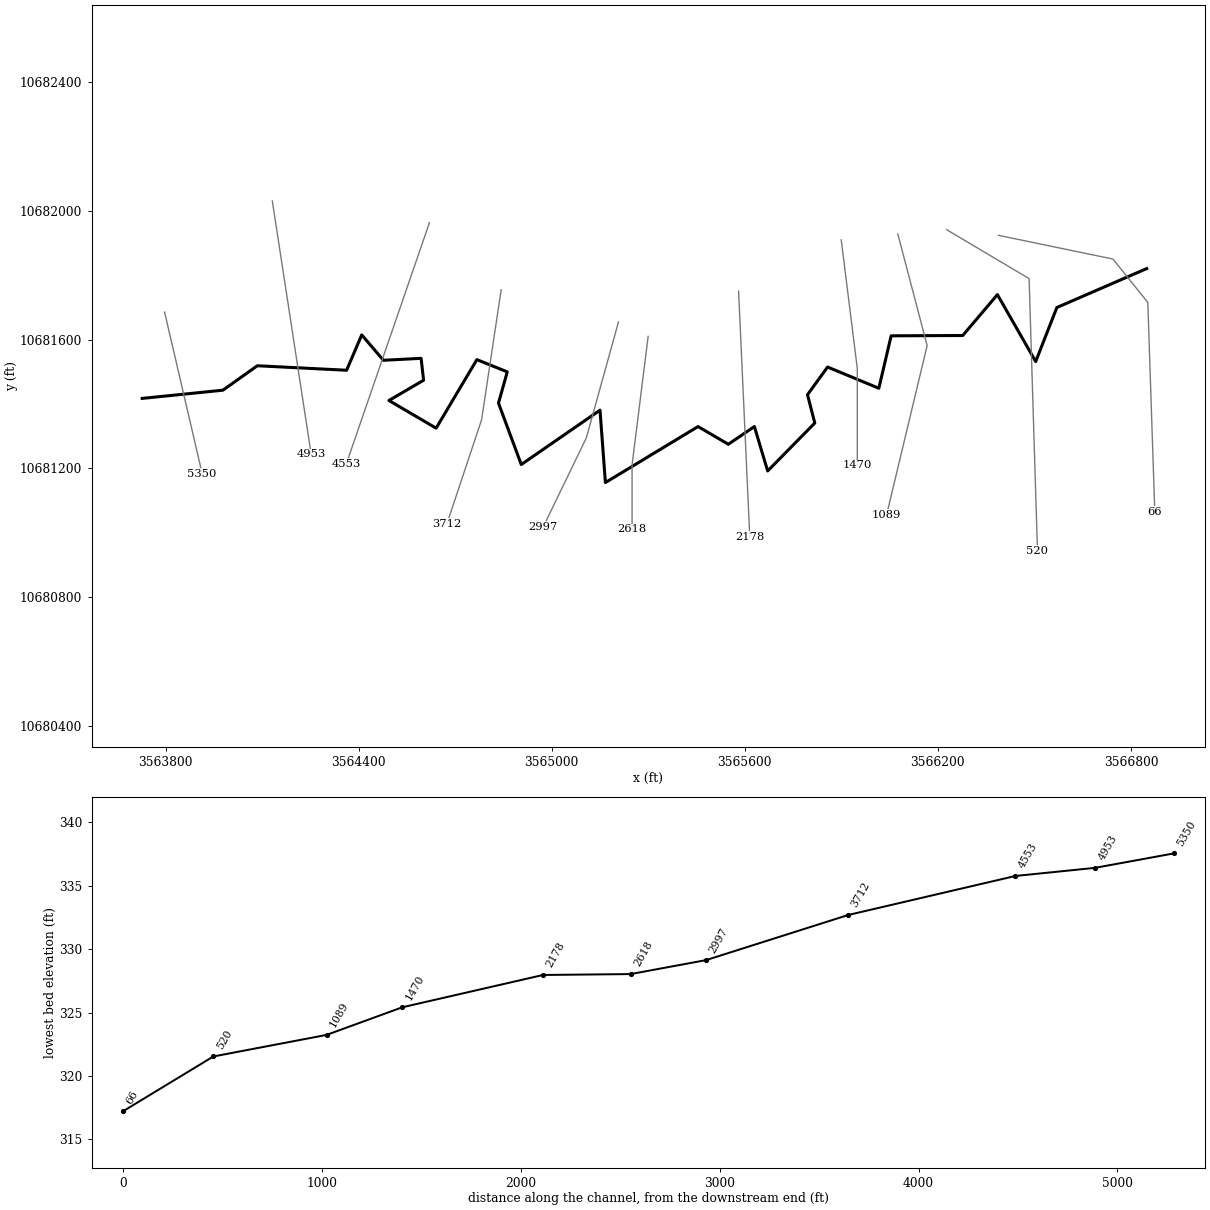
--- UNT171 IN CCTC.prj (project) ---

Proj Title=UNT171 IN CCTC Base Level Engineering
Current Plan=p01
Default Exp/Contr=0.3,0.1
English Units
Geom File=g01
Flow File=f01
Plan File=p01
BEGIN DESCRIPTION:
UNT171 IN CCTC
END DESCRIPTION:

--- UNT171 IN CCTC.p01 (plan) ---

Plan Title=Multiple Run
Short Identifier=Multiple
Geom File=g01
Flow File=f01
Subcritical Flow
K Sum by GR= 0
Std Step Tol= 0.01
Critical Tol= 0.01
Num of Std Step Trials= 20
Max Error Tol= 0.3
Flow Tol Ratio= 0.001
Split Flow NTrial= 30
Split Flow Tol= 0.02
Split Flow Ratio= 0.02
Log Output Level= 0
Friction Slope Method= 1
Unsteady Friction Slope Method= 2
Unsteady Bridges Friction Slope Method= 1
Parabolic Critical Depth
Global Vel Dist=  1 , 1 , 1
Global Log Level= 0
CheckData=True
Encroach Param= -1, 0, 0, 0
BEGIN DESCRIPTION:
Multiple Run
END DESCRIPTION:

--- UNT171 IN CCTC.f01 (steady flow) ---

Flow Title=Multiple
Number of Profiles=7
Profile Names=10-year,25-year,50-year,1pct_min,100-year,1pct_plu,500-year
River Rch & RM= UNT171 IN CCTC,Reach-1,5350
    1197    1630    1984    1762    2383    3223    3427
River Rch & RM= UNT171 IN CCTC,Reach-1,4953
    1568    2170    2669    2394    3238    4379    4751
Boundary for River Rch & Prof#=UNT171 IN CCTC,Reach-1,1
Up Type=0
Dn Type=3
Dn Slope=0.005
Boundary for River Rch & Prof#=UNT171 IN CCTC,Reach-1,2
Up Type=0
Dn Type=3
Dn Slope=0.005
Boundary for River Rch & Prof#=UNT171 IN CCTC,Reach-1,3
Up Type=0
Dn Type=3
Dn Slope=0.005
Boundary for River Rch & Prof#=UNT171 IN CCTC,Reach-1,4
Up Type=0
Dn Type=3
Dn Slope=0.005
Boundary for River Rch & Prof#=UNT171 IN CCTC,Reach-1,5
Up Type=0
Dn Type=3
Dn Slope=0.005
Boundary for River Rch & Prof#=UNT171 IN CCTC,Reach-1,6
Up Type=0
Dn Type=3
Dn Slope=0.005
Boundary for River Rch & Prof#=UNT171 IN CCTC,Reach-1,7
Up Type=0
Dn Type=3
Dn Slope=0.005

--- UNT171 IN CCTC.g01 (geometry) ---

Geom Title=Existing Conditions

River Reach=UNT171 IN CCTC,Reach-1
Reach XY= 30
      3563727.17     10681417.51      3563978.00     10681443.00
      3564085.00     10681519.00      3564362.50     10681505.00
      3564409.50     10681615.00      3564476.75     10681536.00
      3564594.00     10681542.00      3564601.75     10681474.00
      3564494.00     10681411.00      3564640.75     10681325.00
      3564767.25     10681538.00      3564861.75     10681500.00
      3564834.50     10681403.00      3564905.25     10681212.00
      3565150.00     10681381.00      3565166.75     10681156.00
      3565454.75     10681330.00      3565548.75     10681275.00
      3565629.75     10681330.00      3565671.00     10681192.00
      3565817.50     10681341.00      3565794.75     10681429.00
      3565857.25     10681515.00      3566016.50     10681449.00
      3566054.75     10681612.00      3566277.25     10681613.00
      3566385.00     10681740.00      3566504.00     10681532.00
      3566569.75     10681700.00      3566849.00     10681821.00

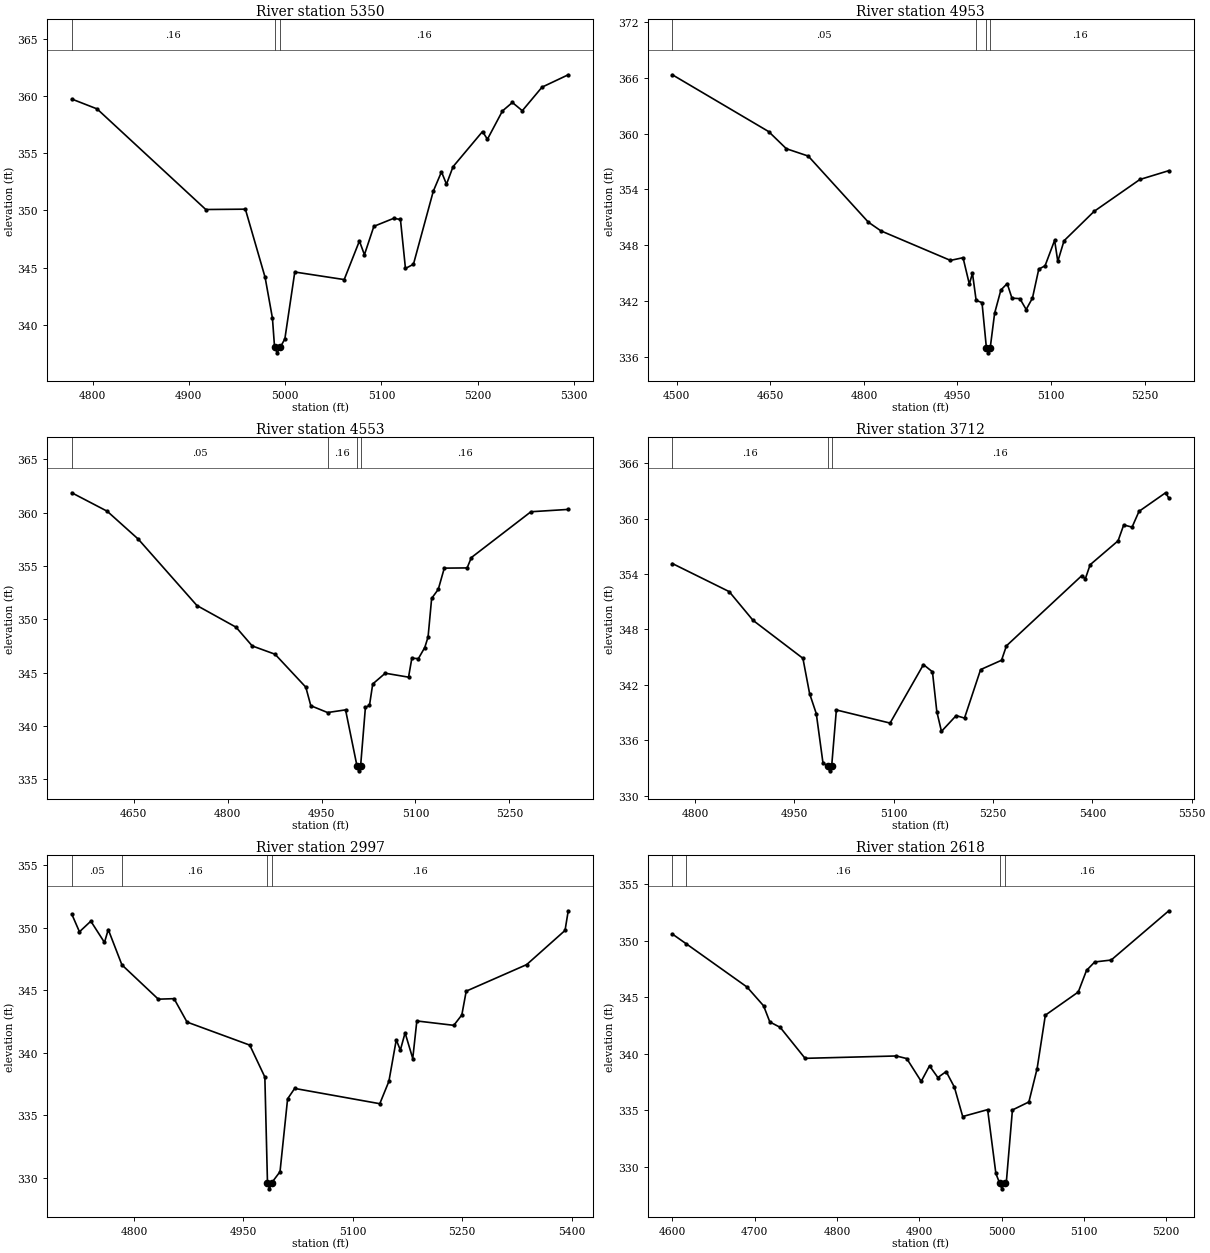
Type RM Length L Ch R = 1,5350,397,397,397
BEGIN DESCRIPTION:
UNT171 IN CCTC 8.0
END DESCRIPTION:
XS GIS Cut Line= 2
      3563796.82     10681685.67      3563913.66     10681183.69
#Sta/Elev= 30
  4778.5  359.73  4804.7  358.87  4917.6  350.08  4958.7  350.11  4979.2  344.15
  4986.8  340.59  4989.0  338.06  4991.7  337.56  4995.0  338.06  4999.7  338.78
  5010.0  344.62  5061.3  343.96  5077.1  347.33  5082.3  346.13  5092.1  348.61
  5112.7  349.31  5119.7  349.21  5124.9  344.93  5133.2  345.30  5153.8  351.68
  5162.3  353.37  5167.5  352.29  5174.3  353.82  5204.9  356.89  5210.0  356.22
  5225.6  358.69  5235.9  359.43  5246.2  358.71  5266.7  360.77  5293.9  361.85
#Mann=3,-1,0
  4778.5    0.16       0  4989.0    0.07       0  4995.0    0.16       0
Bank Sta=4989,4995
Exp/Cntr=0.3,0.1

Type RM Length L Ch R = 1,4953,400,400,400
BEGIN DESCRIPTION:
Mapping XS f8eb6627
END DESCRIPTION:
XS GIS Cut Line= 2
      3564131.63     10682030.80      3564252.37     10681244.11
#Sta/Elev= 30
  4492.9  366.32  4647.3  360.21  4675.6  358.37  4710.7  357.58  4807.1  350.47
  4827.4  349.53  4938.7  346.36  4958.9  346.65  4969.0  343.81  4974.0  344.98
  4979.9  342.06  4989.3  341.82  4996.4  336.92  4999.1  336.42  5002.4  336.92
  5009.5  340.67  5019.6  343.18  5029.7  343.87  5037.3  342.30  5050.0  342.25
  5060.1  341.08  5070.2  342.31  5080.3  345.42  5090.4  345.78  5105.7  348.52
  5110.8  346.25  5120.8  348.47  5169.0  351.63  5242.4  355.06  5288.8  356.01
#Mann=4,-1,0
  4492.9    0.05       0  4979.9    0.16       0  4996.4    0.07       0
  5002.4    0.16       0
Bank Sta=4996.4,5002.4
Exp/Cntr=0.3,0.1

Type RM Length L Ch R = 1,4553,841,841,841
BEGIN DESCRIPTION:
UNT171 IN CCTC 7.0
END DESCRIPTION:
XS GIS Cut Line= 2
      3564619.92     10681963.60      3564361.51     10681213.88
#Sta/Elev= 30
  4551.0  361.87  4607.5  360.14  4657.2  357.52  4750.9  351.29  4813.3  349.26
  4839.2  347.50  4875.7  346.72  4924.8  343.63  4932.8  341.89  4959.6  341.25
  4988.3  341.50  5006.4  336.28  5009.2  335.78  5012.4  336.28  5020.0  341.73
  5026.5  341.92  5031.7  343.93  5051.7  344.94  5088.9  344.57  5094.2  346.35
  5104.6  346.31  5114.8  347.35  5120.1  348.34  5125.8  351.96  5136.4  352.81
  5146.0  354.80  5182.5  354.82  5189.2  355.79  5284.4  360.09  5344.0  360.31
#Mann=4,-1,0
  4551.0    0.05       0  4959.6    0.16       0  5006.4    0.07       0
  5012.4    0.16       0
Bank Sta=5006.4,5012.4
Exp/Cntr=0.3,0.1

Type RM Length L Ch R = 1,3712,715,715,715
BEGIN DESCRIPTION:
UNT171 IN CCTC 6.0
END DESCRIPTION:
XS GIS Cut Line= 3
      3564842.82     10681755.06      3564782.06     10681351.46
      3564674.09     10681027.53
#Sta/Elev= 30
  4765.9  355.14  4851.7  352.10  4887.7  348.99  4963.0  344.88  4973.1  341.06
  4983.2  338.89  4993.3  333.55  5000.4  333.20  5003.2  332.70  5006.4  333.20
  5013.5  339.29  5094.6  337.87  5145.0  344.20  5158.6  343.42  5165.2  339.11
  5172.2  336.97  5194.4  338.68  5207.0  338.41  5231.3  343.66  5262.9  344.67
  5270.3  346.23  5384.1  353.83  5389.4  353.48  5396.7  355.01  5438.9  357.60
  5447.4  359.32  5460.0  359.08  5470.5  360.79  5510.6  362.80  5515.5  362.23
#Mann=3,-1,0
  4765.9    0.16       0  5000.4    0.07       0  5006.4    0.16       0
Bank Sta=5000.4,5006.4
Exp/Cntr=0.3,0.1

Type RM Length L Ch R = 1,2997,379,379,379
BEGIN DESCRIPTION:
Mapping XS c4eb22b2
END DESCRIPTION:
XS GIS Cut Line= 3
      3565207.42     10681655.30      3565107.58     10681295.03
      3564973.82     10681018.87
#Sta/Elev= 30
  4714.7  351.08  4725.2  349.67  4740.8  350.52  4759.5  348.82  4764.7  349.85
  4783.4  347.03  4833.3  344.29  4854.9  344.33  4872.7  342.46  4958.7  340.62
  4979.4  338.07  4983.0  329.64  4985.7  329.14  4989.0  329.64  5000.2  330.51
  5010.6  336.33  5020.3  337.16  5137.0  335.94  5149.5  337.73  5159.6  341.04
  5165.2  340.22  5171.7  341.60  5182.2  339.55  5187.8  342.55  5238.5  342.20
  5249.5  343.03  5255.5  344.93  5338.4  347.05  5391.0  349.78  5395.4  351.35
#Mann=4,-1,0
  4714.7    0.05       0  4783.4    0.16       0  4983.0    0.07       0
  4989.0    0.16       0
Bank Sta=4983,4989
Exp/Cntr=0.3,0.1

Type RM Length L Ch R = 1,2618,440,440,440
BEGIN DESCRIPTION:
UNT171 IN CCTC 5.0
END DESCRIPTION:
XS GIS Cut Line= 3
      3565299.61     10681610.18      3565249.61     10681210.19
      3565249.61     10681010.19
#Sta/Elev= 30
  4600.0  350.59  4617.0  349.72  4690.7  345.90  4710.8  344.24  4718.4  342.81
  4731.0  342.33  4761.2  339.59  4872.1  339.80  4884.7  339.57  4902.3  337.55
  4912.4  338.93  4922.5  337.89  4932.6  338.42  4942.6  337.04  4952.7  334.44
  4983.0  335.05  4993.0  329.40  4997.6  328.54  5000.3  328.04  5003.6  328.54
  5005.6  328.54  5013.1  335.02  5033.1  335.73  5043.1  338.68  5053.1  343.41
  5093.1  345.46  5103.1  347.37  5113.1  348.12  5133.1  348.29  5203.1  352.65
#Mann=4,-1,0
  4600.0    0.05       0  4617.0    0.16       0  4997.6    0.07       0
  5003.6    0.16       0
Bank Sta=4997.6,5003.6
Exp/Cntr=0.3,0.1

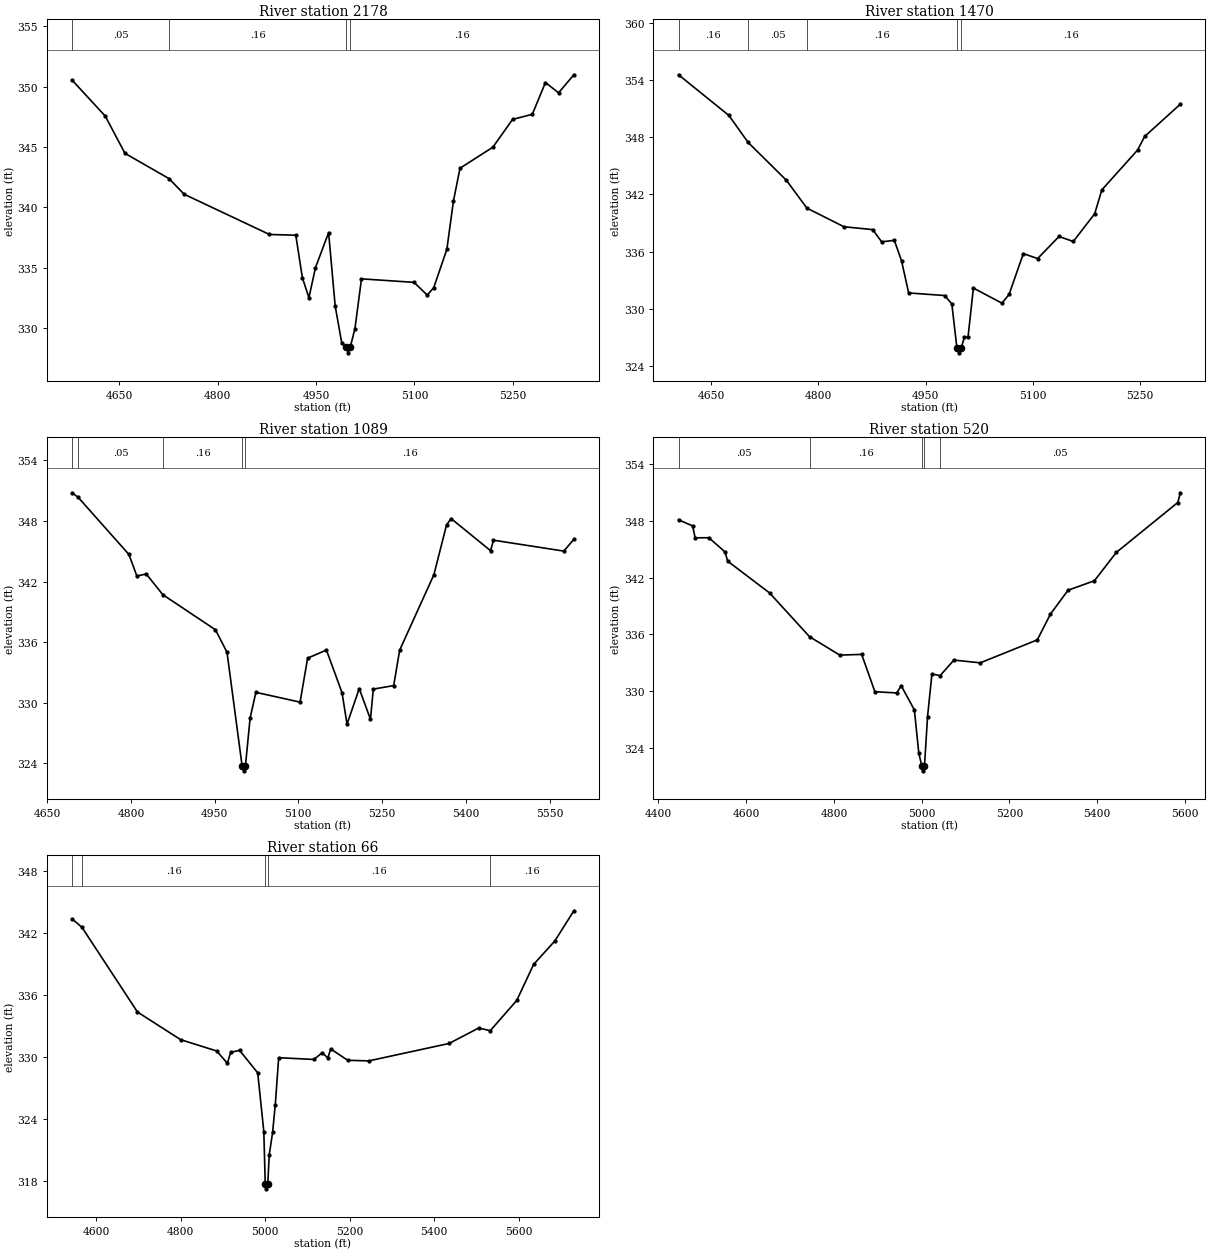
Type RM Length L Ch R = 1,2178,708,708,708
BEGIN DESCRIPTION:
UNT171 IN CCTC 4.0
END DESCRIPTION:
XS GIS Cut Line= 2
      3565580.68     10681750.72      3565615.39     10680986.91
#Sta/Elev= 30
  4578.3  350.53  4628.9  347.55  4658.9  344.47  4726.1  342.38  4749.0  341.09
  4879.1  337.76  4919.2  337.70  4929.2  334.19  4939.2  332.53  4949.2  335.02
  4969.2  337.91  4979.2  331.85  4989.3  328.76  4996.3  328.47  4999.0  327.97
  5002.3  328.47  5009.3  329.96  5019.3  334.09  5099.4  333.80  5119.4  332.75
  5129.4  333.36  5149.4  336.54  5159.4  340.52  5169.4  343.24  5219.5  344.98
  5249.5  347.28  5279.6  347.70  5299.6  350.33  5319.6  349.48  5342.9  350.97
#Mann=4,-1,0
  4578.3    0.05       0  4726.1    0.16       0  4996.3    0.07       0
  5002.3    0.16       0
Bank Sta=4996.3,5002.3
Exp/Cntr=0.3,0.1

Type RM Length L Ch R = 1,1470,381,381,381
BEGIN DESCRIPTION:
UNT171 IN CCTC 3.0
END DESCRIPTION:
XS GIS Cut Line= 3
      3565899.60     10681910.23      3565949.61     10681510.19
      3565949.61     10681210.14
#Sta/Elev= 30
  4603.9  354.53  4674.5  350.27  4701.3  347.46  4755.1  343.48  4783.8  340.57
  4835.7  338.62  4876.0  338.32  4888.6  337.04  4906.3  337.20  4916.4  335.06
  4926.4  331.69  4976.8  331.42  4986.9  330.54  4994.0  325.92  4996.7  325.42
  5000.0  325.92  5004.5  327.07  5009.6  327.07  5017.1  332.20  5057.1  330.62
  5067.1  331.53  5087.1  335.81  5107.1  335.29  5137.1  337.60  5157.1  337.08
  5187.1  339.98  5197.1  342.48  5247.1  346.64  5257.1  348.07  5307.1  351.45
#Mann=5,-1,0
  4603.9    0.16       0  4701.3    0.05       0  4783.8    0.16       0
  4994.0    0.07       0  5000.0    0.16       0
Bank Sta=4994,5000
Exp/Cntr=0.3,0.1

Type RM Length L Ch R = 1,1089,569,569,569
BEGIN DESCRIPTION:
Mapping XS aab84a90
END DESCRIPTION:
XS GIS Cut Line= 3
      3566075.47     10681928.69      3566166.61     10681581.49
      3566040.75     10681056.33
#Sta/Elev= 30
  4694.6  350.80  4705.5  350.35  4796.4  344.69  4810.7  342.55  4827.5  342.75
  4857.2  340.70  4951.5  337.22  4972.2  334.99  4999.2  323.74  5001.9  323.24
  5005.2  323.74  5013.6  328.48  5023.9  331.02  5103.1  330.05  5116.6  334.41
  5150.3  335.21  5178.3  330.98  5187.2  327.87  5209.1  331.39  5229.2  328.35
  5234.3  331.34  5270.8  331.69  5281.5  335.20  5342.8  342.67  5365.5  347.61
  5373.7  348.24  5444.4  345.06  5449.6  346.10  5575.6  345.02  5593.6  346.19
#Mann=5,-1,0
  4694.6    0.16       0  4705.5    0.05       0  4857.2    0.16       0
  4999.2    0.07       0  5005.2    0.16       0
Bank Sta=4999.2,5005.2
Exp/Cntr=0.3,0.1

Type RM Length L Ch R = 1,520,454,454,454
BEGIN DESCRIPTION:
UNT171 IN CCTC 2.0
END DESCRIPTION:
XS GIS Cut Line= 3
      3566227.38     10681941.73      3566483.45     10681789.82
      3566509.47     10680944.37
#Sta/Elev= 30
  4445.8  348.13  4477.8  347.48  4483.7  346.22  4514.9  346.23  4551.9  344.72
  4557.7  343.75  4653.3  340.38  4744.3  335.75  4813.2  333.80  4863.2  333.87
  4893.3  329.92  4943.3  329.79  4953.3  330.55  4983.3  327.99  4993.3  323.44
  5000.3  322.04  5003.1  321.54  5006.3  322.04  5013.3  327.28  5023.3  331.80
  5041.9  331.62  5073.3  333.27  5133.4  332.98  5263.4  335.41  5293.4  338.14
  5333.5  340.67  5393.5  341.67  5443.5  344.67  5583.6  349.96  5589.4  350.99
#Mann=5,-1,0
  4445.8    0.05       0  4744.3    0.16       0  5000.3    0.07       0
  5006.3    0.16       0  5041.9    0.05       0
Bank Sta=5000.3,5006.3
Exp/Cntr=0.3,0.1

Type RM Length L Ch R = 1,66,0,0,0
BEGIN DESCRIPTION:
UNT171 IN CCTC 1.0
END DESCRIPTION:
XS GIS Cut Line= 4
      3566388.01     10681924.36      3566743.87     10681850.59
      3566852.38     10681716.04      3566874.07     10681065.07
#Sta/Elev= 30
  4542.8  343.41  4566.3  342.58  4697.6  334.37  4799.7  331.69  4885.1  330.59
  4910.3  329.40  4918.2  330.45  4939.1  330.66  4982.2  328.47  4996.6  322.78
  5000.0  317.72  5002.8  317.22  5006.0  317.72  5009.5  320.53  5017.4  322.69
  5023.8  325.40  5031.8  329.94  5114.9  329.77  5135.0  330.42  5148.0  329.91
  5155.0  330.79  5195.0  329.69  5245.0  329.63  5435.1  331.32  5505.2  332.82
  5532.5  332.56  5595.2  335.49  5635.2  338.99  5685.3  341.26  5730.4  344.19
#Mann=5,-1,0
  4542.8    0.05       0  4566.3    0.16       0  5000.0    0.07       0
  5006.0    0.16       0  5532.5    0.16       0
Bank Sta=5000,5006
Exp/Cntr=0.3,0.1

Chan Stop Cuts=-1