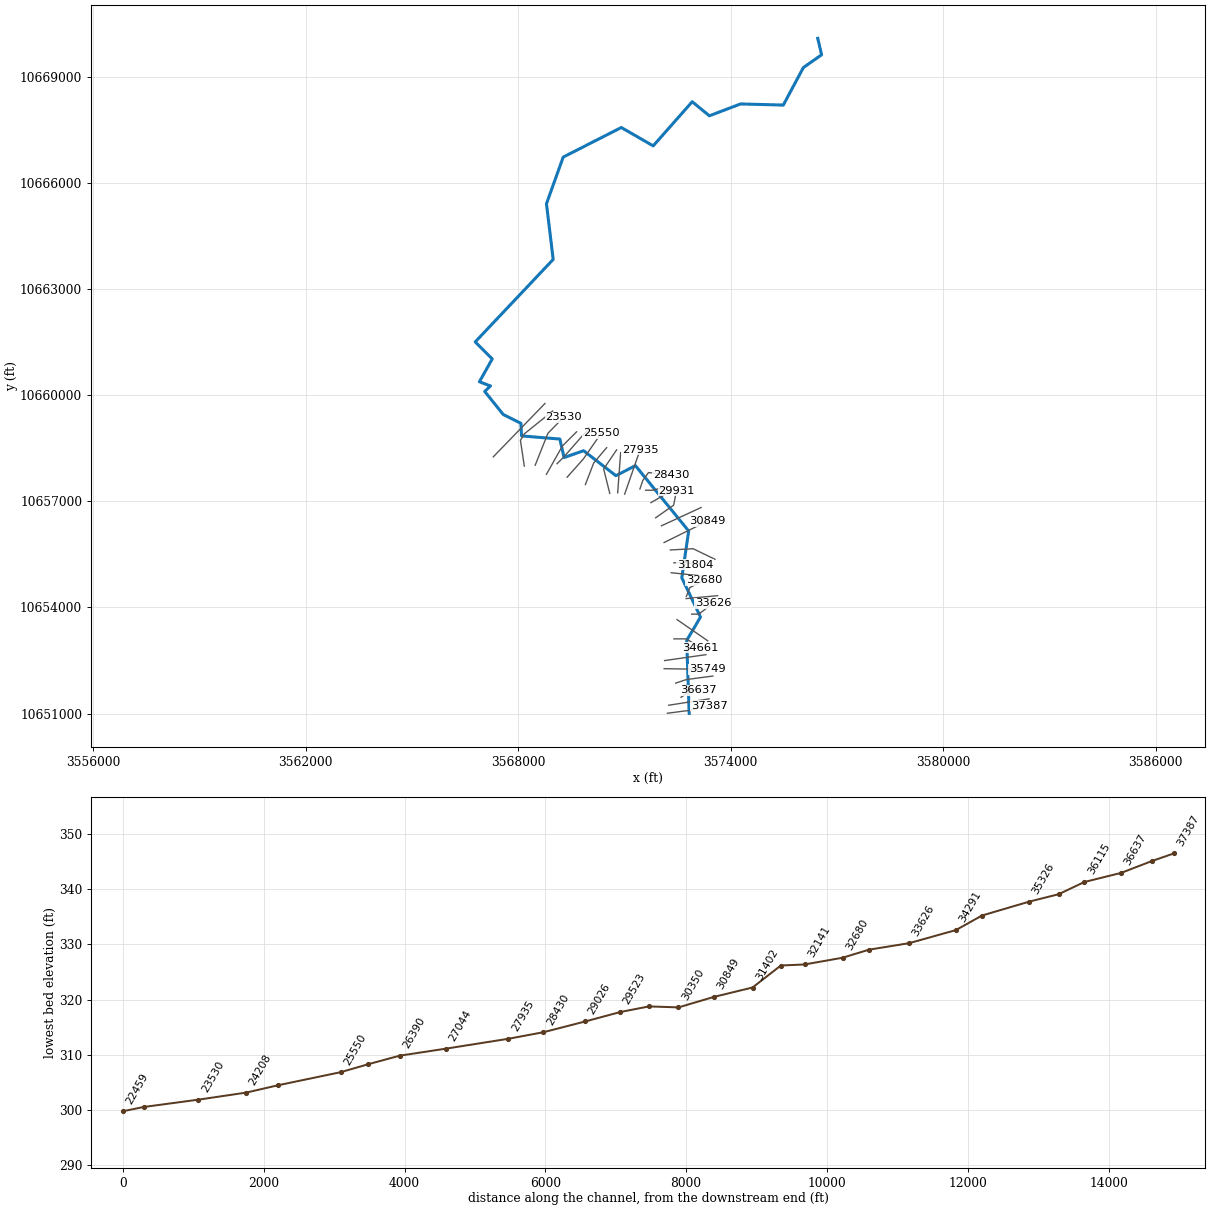
--- UNT175 IN CCTC.prj (project) ---

Proj Title=UNT175 IN CCTC Base Level Engineering
Current Plan=p01
Default Exp/Contr=0.3,0.1
English Units
Geom File=g01
Flow File=f01
Plan File=p01
Y Axis Title=Elevation
X Axis Title(PF)=Main Channel Distance
X Axis Title(XS)=Station
BEGIN DESCRIPTION:
UNT175 IN CCTC
END DESCRIPTION:
DSS Export Rating Curves= 0
DSS Export Rating Curve Sorted= 0
DSS Export Volume Flow Curves= 0
DXF OffsetX= 0
DXF OffsetY= 0
DXF ScaleX= 1
DXF ScaleY= 10

--- UNT175 IN CCTC.p01 (plan) ---

Plan Title=Multiple Run
Short Identifier=Multiple
Geom File=g01
Flow File=f01
Subcritical Flow
K Sum by GR= 0
Std Step Tol= 0.01
Critical Tol= 0.01
Num of Std Step Trials= 20
Max Error Tol= 0.3
Flow Tol Ratio= 0.001
Split Flow NTrial= 30
Split Flow Tol= 0.02
Split Flow Ratio= 0.02
Log Output Level= 0
Friction Slope Method= 1
Unsteady Friction Slope Method= 2
Unsteady Bridges Friction Slope Method= 1
Parabolic Critical Depth
Global Vel Dist=  1 , 1 , 1
Global Log Level= 0
CheckData=True
Encroach Param= -1, 0, 0, 0
BEGIN DESCRIPTION:
Multiple Run
END DESCRIPTION:

--- UNT175 IN CCTC.f01 (steady flow) ---

Flow Title=Multiple
Program Version=4.10
Number of Profiles= 7
Profile Names=10-year,25-year,50-year,1pct_min,100-year,1pct_plu,500-year
River Rch & RM=UNT175 IN CCTC,Reach-1         ,37387
    1565    2163    2660    2386    3227    4365    4734
River Rch & RM=UNT175 IN CCTC,Reach-1         ,33626
    2399    3396    4242    3861    5221    7061    7887
River Rch & RM=UNT175 IN CCTC,Reach-1         ,30849
    2642    3735    4660    4231    5722    7738    8606
River Rch & RM=UNT175 IN CCTC,Reach-1         ,21449
    3155    4493    5633    5136    6945    9393   10535
Boundary for River Rch & Prof#=UNT175 IN CCTC,Reach-1         , 1
Up Type= 0
Dn Type= 3
Dn Slope=0.00213
Boundary for River Rch & Prof#=UNT175 IN CCTC,Reach-1         , 2
Up Type= 0
Dn Type= 3
Dn Slope=0.00213
Boundary for River Rch & Prof#=UNT175 IN CCTC,Reach-1         , 3
Up Type= 0
Dn Type= 3
Dn Slope=0.00213
Boundary for River Rch & Prof#=UNT175 IN CCTC,Reach-1         , 4
Up Type= 0
Dn Type= 3
Dn Slope=0.00213
Boundary for River Rch & Prof#=UNT175 IN CCTC,Reach-1         , 5
Up Type= 0
Dn Type= 3
Dn Slope=0.00213
Boundary for River Rch & Prof#=UNT175 IN CCTC,Reach-1         , 6
Up Type= 0
Dn Type= 3
Dn Slope=0.00213
Boundary for River Rch & Prof#=UNT175 IN CCTC,Reach-1         , 7
Up Type= 0
Dn Type= 3
Dn Slope=0.00213
DSS Import GetInterval= 0
DSS Import GetPeak= 0
DSS Import FillOption= 0

--- UNT175 IN CCTC.g01 (geometry) ---

Geom Title=Existing Conditions
Program Version=4.10

River Reach=UNT175 IN CCTC  ,Reach-1
Reach XY= 30
      3572830.25       10651005.        3572760.       10653065.
      3573149.75       10653727.        3572622.       10654836.
        3572816.       10656158.      3571312.25       10658005.
        3570761.       10657722.        3569848.       10658427.
      3569296.75       10658234.      3569177.75       10658757.
       3568096.5       10658845.        3568079.       10659201.
      3567580.25       10659451.       3567055.5       10660102.
      3567220.75       10660257.       3566906.5       10660375.
       3567269.5       10661021.       3566788.5       10661501.
        3568990.       10663833.        3568800.       10665405.
        3569273.       10666724.        3570914.       10667560.
        3571814.       10667041.      3572915.75       10668289.
        3573400.       10667891.       3574280.5       10668226.
      3575488.25       10668194.       3576053.5       10669254.
       3576569.5       10669615.       3576459.5       10670080.

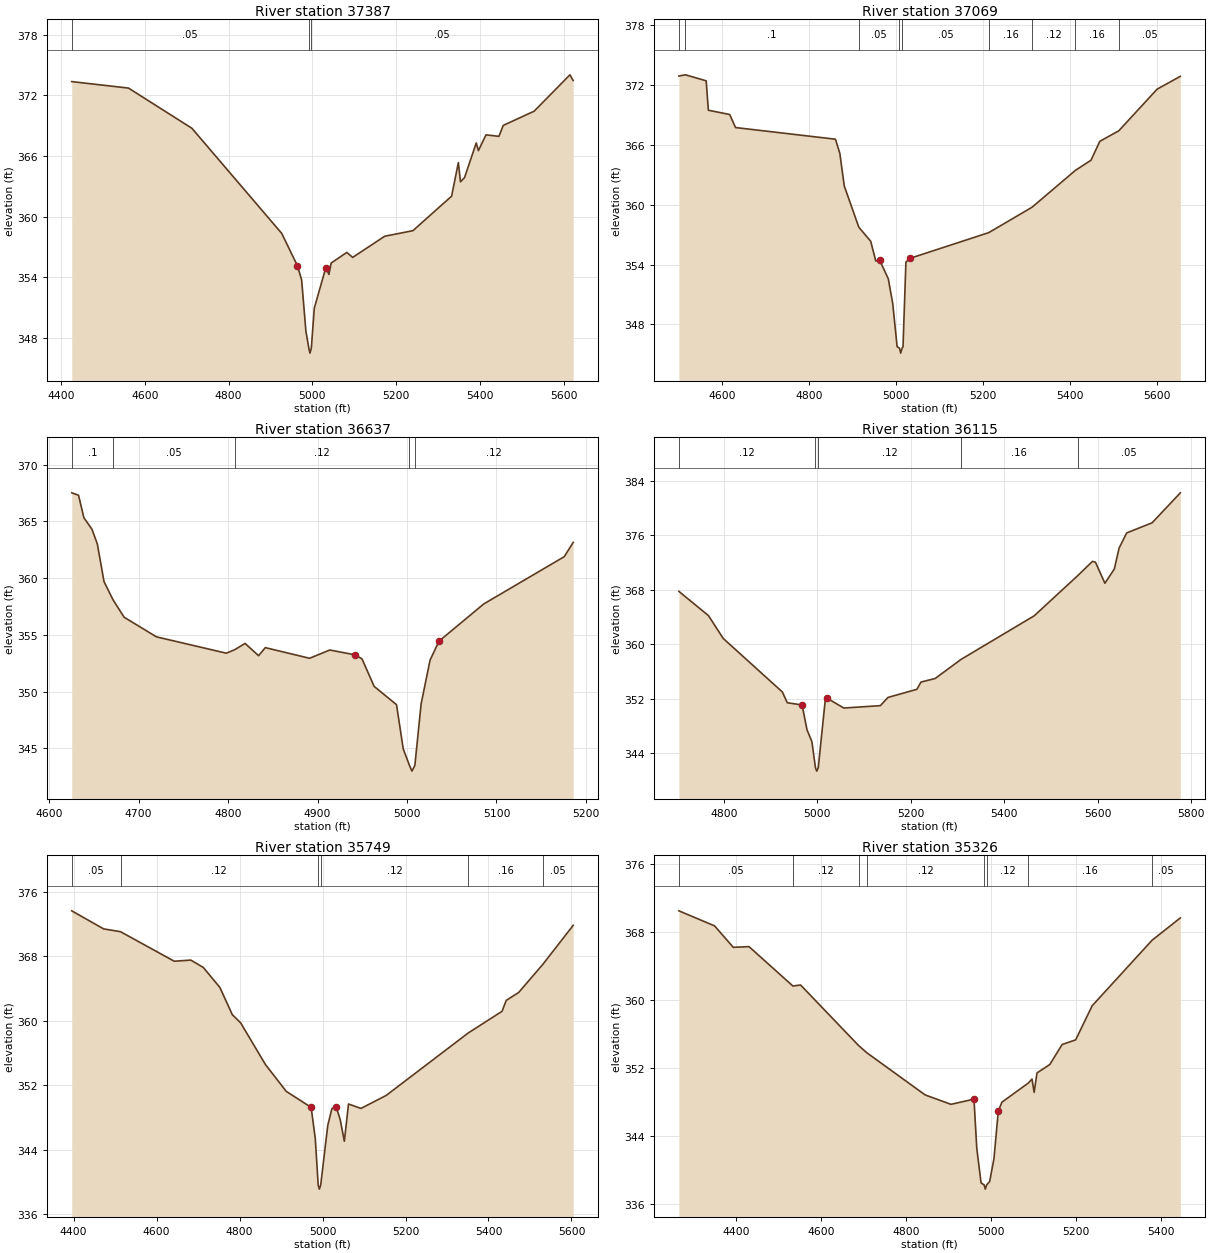
Type RM Length L Ch R = 1 ,37387   ,318,318,318
BEGIN DESCRIPTION:
Mapping XS 2b1b8a6b
END DESCRIPTION:
XS GIS Cut Line= 4
      3572215.28     10651008.59      3572710.04     10651073.69
      3572819.41     10651084.11      3573392.33     10651216.92
#Sta/Elev= 30
  4425.6  373.35  4561.1  372.71  4712.4  368.74  4926.9  358.35  4964.4  355.15
  4974.4  353.75  4984.5  348.72  4991.5  347.02  4994.3  346.52  4997.5  347.02
  5004.6  350.96  5032.1  354.97  5039.5   354.3    5045  355.43  5082.2  356.47
  5096.3  355.98  5172.7  358.07    5240  358.62  5332.4  362.03  5348.5  365.35
  5353.6  363.45  5363.2  363.86  5391.2  367.29  5396.3  366.53  5414.5  368.09
  5445.3  367.94  5455.6  369.02  5529.5  370.43  5614.8  374.02  5622.6  373.46
#Mann= 3 ,-1 , 0
  4425.6     .05       0  4991.5     .03       0  4997.5     .05       0
Bank Sta=4964.4,5032.1
XS Rating Curve= 0 ,0
Exp/Cntr=0.3,0.1

Type RM Length L Ch R = 1 ,37069   ,432,432,432
BEGIN DESCRIPTION:
Mapping XS 7cba5831
END DESCRIPTION:
XS GIS Cut Line= 2
      3572254.35     10651235.16      3573392.35     10651414.84
#Sta/Elev= 30
  4501.6  372.91  4516.7  373.03  4564.3  372.43  4569.3  369.48  4618.3  369.05
  4631.8  367.74  4861.3  366.57  4871.4  365.15  4881.5  361.89  4914.9  357.75
  4942.3  356.33    4954  354.35  4962.5  354.47  4982.7  352.57  4992.9  350.09
    5003  345.76  5008.4  345.61  5011.2  345.11  5014.4  345.61  5016.5  345.73
  5023.2  354.25  5033.4  354.63  5213.6   357.2  5313.1  359.75  5412.7  363.45
  5448.4  364.46  5468.7  366.36  5512.2  367.41  5600.3  371.59  5653.7  372.88
#Mann= 9 ,-1 , 0
  4501.6     .05       0  4516.7      .1       0  4914.9     .05       0
  5008.4     .03       0  5014.4     .05       0  5213.6     .16       0
  5313.1     .12       0  5412.7     .16       0  5512.2     .05       0
Bank Sta=4962.5,5033.4
XS Rating Curve= 0 ,0
Exp/Cntr=0.3,0.1

Type RM Length L Ch R = 1 ,36637   ,522,522,522
BEGIN DESCRIPTION:
UNT175 IN CCTC 38.0
END DESCRIPTION:
XS GIS Cut Line= 3
      3572599.58     10651460.17      3572899.61     10651660.19
      3573099.62     10651660.19
#Sta/Elev= 30
  4625.2  367.52  4632.8  367.31  4638.8  365.32  4647.8  364.31  4653.8  363.02
  4661.3  359.69  4671.4  358.08  4683.8  356.55  4719.9  354.82    4798  353.38
  4807.5  353.69    4819  354.24  4834.1  353.16  4841.6  353.87  4891.1  352.93
  4913.7  353.66  4942.2  353.23  4949.7  352.88  4963.3  350.45  4988.3  348.84
  4995.8  344.94  5002.8  343.48  5005.5  342.98  5008.8  343.48  5015.8  348.91
  5025.8  352.77  5035.8  354.44  5085.8  357.72  5175.8  361.89  5185.8  363.15
#Mann= 5 ,-1 , 0
  4625.2      .1       0  4671.4     .05       0  4807.5     .12       0
  5002.8     .07       0  5008.8     .12       0
Bank Sta=4942.2,5035.8
XS Rating Curve= 0 ,0
Exp/Cntr=0.3,0.1

Type RM Length L Ch R = 1 ,36115   ,366,366,366
BEGIN DESCRIPTION:
UNT175 IN CCTC 37.0
END DESCRIPTION:
XS GIS Cut Line= 3
      3572449.57     10651860.18      3572749.61     10651960.19
       3573499.6     10652060.19
#Sta/Elev= 30
  4703.7  367.74    4767  364.18  4798.6  360.82  4925.1  352.96  4935.6  351.38
  4967.3  351.05  4977.8  347.41  4988.3  345.66  4995.9  341.83  4998.6  341.33
  5001.9  341.83  5017.3  352.08    5020  352.08  5056.5   350.6  5134.7  350.95
  5151.1  352.16  5212.9  353.35  5221.7  354.42    5252  354.94  5307.5  357.75
  5463.9  364.15  5556.7  370.03  5588.7  372.15    5595  372.03  5615.2  368.93
  5635.4  371.04  5645.5  374.09  5661.8  376.33  5716.1  377.81  5776.6  382.22
#Mann= 5 ,-1 , 0
  4703.7     .12       0  4995.9     .07       0  5001.9     .12       0
  5307.5     .16       0  5556.7     .05       0
Bank Sta=4967.3,5020
XS Rating Curve= 0 ,0
Exp/Cntr=0.3,0.1

Type RM Length L Ch R = 1 ,35749   ,423,423,423
BEGIN DESCRIPTION:
UNT175 IN CCTC 36.0
END DESCRIPTION:
XS GIS Cut Line= 2
      3572122.68     10652268.18        3573331.     10652247.34
#Sta/Elev= 30
  4395.6  373.63  4472.5  371.39  4513.2  371.04  4642.6  367.38  4682.6  367.52
  4712.6  366.61  4752.6  364.13  4782.6  360.75  4802.6  359.74  4862.6  354.55
  4912.6  351.24  4972.6  349.25  4982.6  345.37  4989.6  339.61  4992.4  339.11
  4995.6  339.61  5012.6     347  5022.6   349.1  5032.6  349.35  5042.6  347.74
  5052.6  345.05  5062.6  349.67  5092.6  349.12  5153.4  350.73  5351.2  358.48
  5432.7  361.17  5442.7  362.52  5472.7   363.5  5531.1     367  5604.1  371.83
#Mann= 6 ,-1 , 0
  4395.6     .05       0  4513.2     .12       0  4989.6     .07       0
  4995.6     .12       0  5351.2     .16       0  5531.1     .05       0
Bank Sta=4972.6,5032.6
XS Rating Curve= 0 ,0
Exp/Cntr=0.3,0.1

Type RM Length L Ch R = 1 ,35326   ,665,665,665
BEGIN DESCRIPTION:
UNT175 IN CCTC 35.0
END DESCRIPTION:
XS GIS Cut Line= 2
      3572136.51     10652497.34      3573303.17     10652664.01
#Sta/Elev= 30
    4266  370.47  4349.9   368.7  4393.8  366.18  4430.8  366.26  4533.9  361.63
    4552  361.75  4688.2  354.64  4707.5  353.79  4844.9  348.82  4905.5  347.72
  4959.5  348.33  4966.1  342.55  4976.2  338.48  4983.3  338.25  4986.1  337.75
  4989.3  338.25  4996.4  338.65  5006.5  341.34  5016.6  346.91  5025.1  347.97
  5086.9  350.21  5095.9  350.69  5100.9  349.12  5107.6  351.41  5137.9  352.41
  5166.6  354.75  5198.5   355.3  5237.3  359.31    5378  367.01  5444.5  369.64
#Mann= 8 ,-1 , 0
    4266     .05       0  4533.9     .12       0  4688.2     .08       0
  4707.5     .12       0  4983.3     .07       0  4989.3     .12       0
  5086.9     .16       0    5378     .05       0
Bank Sta=4959.5,5016.6
XS Rating Curve= 0 ,0
Exp/Cntr=0.3,0.1

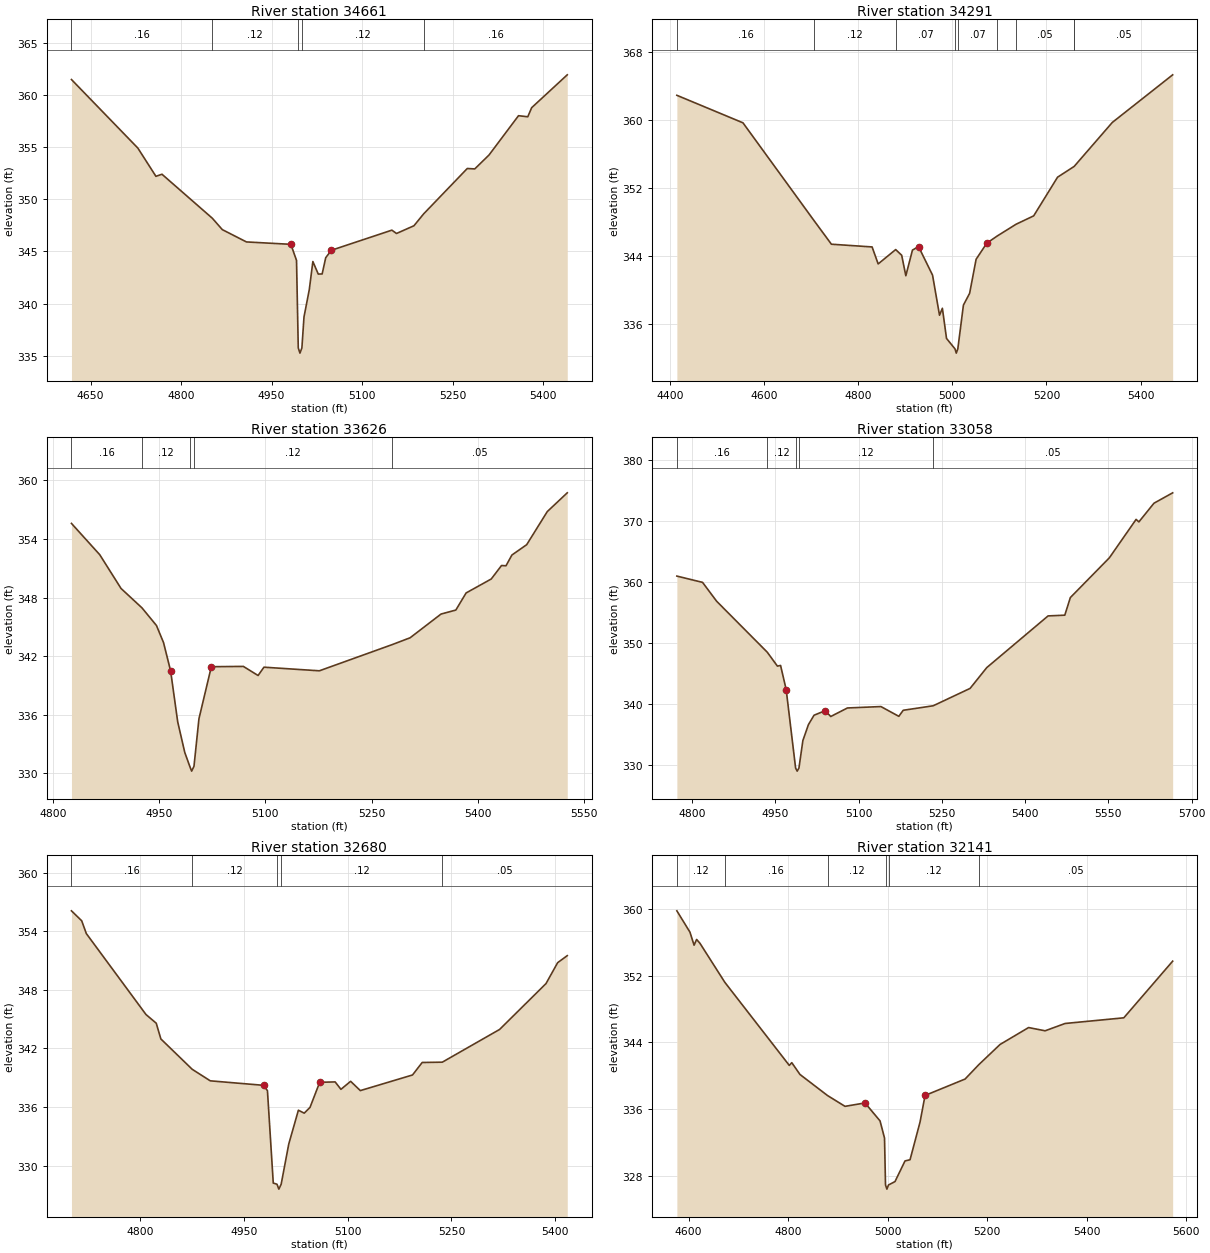
Type RM Length L Ch R = 1 ,34661   ,370,370,370
BEGIN DESCRIPTION:
UNT175 IN CCTC 34.0
END DESCRIPTION:
XS GIS Cut Line= 3
       3572399.6     10653110.19      3572749.61     10653110.19
       3573149.6     10652860.19
#Sta/Elev= 30
  4618.3  361.48  4728.3  354.91  4758.3   352.2  4768.3   352.4  4851.8  348.18
  4868.3  347.09  4908.3  345.91  4981.9  345.68  4991.3  344.14  4994.2  335.75
    4997  335.25  5000.2  335.75  5003.7  338.72  5012.5  341.35  5018.4  344.03
  5027.3  342.83  5033.8  342.84  5039.7   344.4  5049.1  345.11  5149.3  347.04
    5157  346.72  5185.9  347.46    5202   348.6  5274.3  352.95  5286.7  352.91
  5310.3  354.24  5359.2  358.01  5374.6  357.91    5381  358.78    5440  361.93
#Mann= 5 ,-1 , 0
  4618.3     .16       0  4851.8     .12       0  4994.2     .07       0
  5000.2     .12       0    5202     .16       0
Bank Sta=4981.9,5049.1
XS Rating Curve= 0 ,0
Exp/Cntr=0.3,0.1

Type RM Length L Ch R = 1 ,34291   ,665,665,665
BEGIN DESCRIPTION:
UNT175 IN CCTC 33.0
END DESCRIPTION:
XS GIS Cut Line= 2
       3572487.4      10653653.9      3573354.84     10653055.37
#Sta/Elev= 30
  4414.4  362.96  4554.9  359.72  4706.1   348.2  4742.9  345.43  4829.4  345.11
  4842.3  343.11  4879.5   344.8  4892.3  344.13  4901.1  341.72  4915.2  344.74
  4928.1  345.15  4957.9  341.79  4972.7  337.07  4978.8  337.89  4987.6  334.34
  5005.6  333.11  5008.3  332.61  5011.6  333.11  5023.5  338.26  5036.7  339.65
  5050.5  343.66  5073.2  345.55  5095.7  346.41  5135.4  347.78  5172.9  348.77
  5223.6  353.32    5259  354.59  5259.1   354.6  5339.9  359.76  5468.3  365.37
#Mann= 9 ,-1 , 0
  4414.4     .16       0  4706.1     .12       0  4879.5     .07       0
  5005.6     .07       0  5011.6     .07       0  5095.7     .12       0
  5135.4     .05       0    5259     .16       0  5259.1     .05       0
Bank Sta=4928.1,5073.2
XS Rating Curve= 0 ,0
Exp/Cntr=0.3,0.1

Type RM Length L Ch R = 1 ,33626   ,568,568,568
BEGIN DESCRIPTION:
UNT175 IN CCTC 32.0
END DESCRIPTION:
XS GIS Cut Line= 3
      3572899.65     10653810.19      3573099.61     10653810.19
      3573499.64     10654110.21
#Sta/Elev= 30
  4826.2  355.59  4866.2  352.38  4896.2  348.93  4925.8  346.94  4946.2  345.14
  4956.2  343.39  4966.2  340.49  4976.2  335.28  4986.2  332.14  4993.2  330.73
  4995.9  330.23  4999.2  330.73  5006.2  335.59  5023.7  340.92  5068.9  340.95
  5089.7  340.02    5098  340.87  5176.2   340.5  5278.6  343.17  5304.3  343.88
    5348  346.31  5368.9  346.72  5383.4  348.47  5418.9   349.9  5433.4  351.28
  5439.7  351.25    5448  352.35  5468.9  353.41    5498   356.8  5526.2  358.72
#Mann= 5 ,-1 , 0
  4826.2     .16       0  4925.8     .12       0  4993.2     .07       0
  4999.2     .12       0  5278.6     .05       0
Bank Sta=4966.2,5023.7
XS Rating Curve= 0 ,0
Exp/Cntr=0.3,0.1

Type RM Length L Ch R = 1 ,33058   ,378,378,378
BEGIN DESCRIPTION:
UNT175 IN CCTC 31.0
END DESCRIPTION:
XS GIS Cut Line= 2
       3572743.5     10654248.54      3573633.18       10654331.
#Sta/Elev= 30
  4772.3  360.99  4818.6  359.96    4844  356.87  4935.2  348.53  4953.5  346.25
  4959.2  346.36  4969.3  342.41  4986.3  329.56  4989.1  329.06  4992.3  329.56
  4999.4  334.07  5009.4  336.67  5019.5  338.21  5039.6  338.96  5049.6     338
  5079.7   339.4    5140  339.63  5172.3  338.03  5180.2  339.02  5234.3  339.76
  5300.7   342.6  5330.8  346.01  5441.3  354.47  5471.4  354.59  5481.4  357.47
  5551.7  363.98  5599.9  370.27  5604.9  369.86  5632.1  372.92  5665.8  374.62
#Mann= 5 ,-1 , 0
  4772.3     .16       0  4935.2     .12       0  4986.3     .07       0
  4992.3     .12       0  5234.3     .05       0
Bank Sta=4969.3,5039.6
XS Rating Curve= 0 ,0
Exp/Cntr=0.3,0.1

Type RM Length L Ch R = 1 ,32680   ,539,539,539
BEGIN DESCRIPTION:
UNT175 IN CCTC 30.0
END DESCRIPTION:
XS GIS Cut Line= 3
      3572749.62     10654310.21      3572849.61     10654560.19
      3573249.56     10654760.17
#Sta/Elev= 30
  4700.9  356.09  4715.7  355.07  4722.4  353.76  4808.6  345.47  4823.4  344.58
  4830.1  342.97  4875.4  339.86  4901.5  338.68  4978.5  338.22  4984.1  337.67
  4992.5  328.21  4997.9  328.09  5000.6  327.59  5003.9  328.09  5014.9  332.21
  5028.8  335.67  5037.2  335.37  5045.6  335.96  5059.6  338.53  5081.9  338.57
  5090.3  337.81  5104.3  338.63  5118.3  337.68  5193.7  339.28  5207.7  340.56
  5236.7  340.59  5319.5  343.94  5386.6  348.64  5403.4  350.78  5417.3   351.5
#Mann= 5 ,-1 , 0
  4700.9     .16       0  4875.4     .12       0  4997.9     .07       0
  5003.9     .12       0  5236.7     .05       0
Bank Sta=4978.5,5059.6
XS Rating Curve= 0 ,0
Exp/Cntr=0.3,0.1

Type RM Length L Ch R = 1 ,32141   ,337,337,337
BEGIN DESCRIPTION:
UNT175 IN CCTC 29.0
END DESCRIPTION:
XS GIS Cut Line= 2
      3572323.46     10654979.15      3573314.63     10654875.18
#Sta/Elev= 30
  4576.5  359.82  4602.8  357.26  4611.1  355.69  4616.2  356.38  4622.9  355.92
  4672.9  351.23  4802.5  341.24  4807.5  341.57    4824  340.15  4879.3  337.62
  4914.5  336.32  4954.7  336.73  4984.9  334.57  4993.9  332.51  4995.9  326.87
  4998.7  326.37  5001.9  326.87    5015  327.28  5035.1  329.76  5045.2   329.9
  5065.3  334.43  5075.4  337.63  5155.8   339.6  5183.6  341.34  5226.2  343.76
  5283.5  345.79  5316.7   345.4  5356.9  346.28  5474.9  346.96  5573.1  353.77
#Mann= 6 ,-1 , 0
  4576.5     .12       0  4672.9     .16       0  4879.3     .12       0
  4995.9     .07       0  5001.9     .12       0  5183.6     .05       0
Bank Sta=4954.7,5075.4
XS Rating Curve= 0 ,0
Exp/Cntr=0.3,0.1

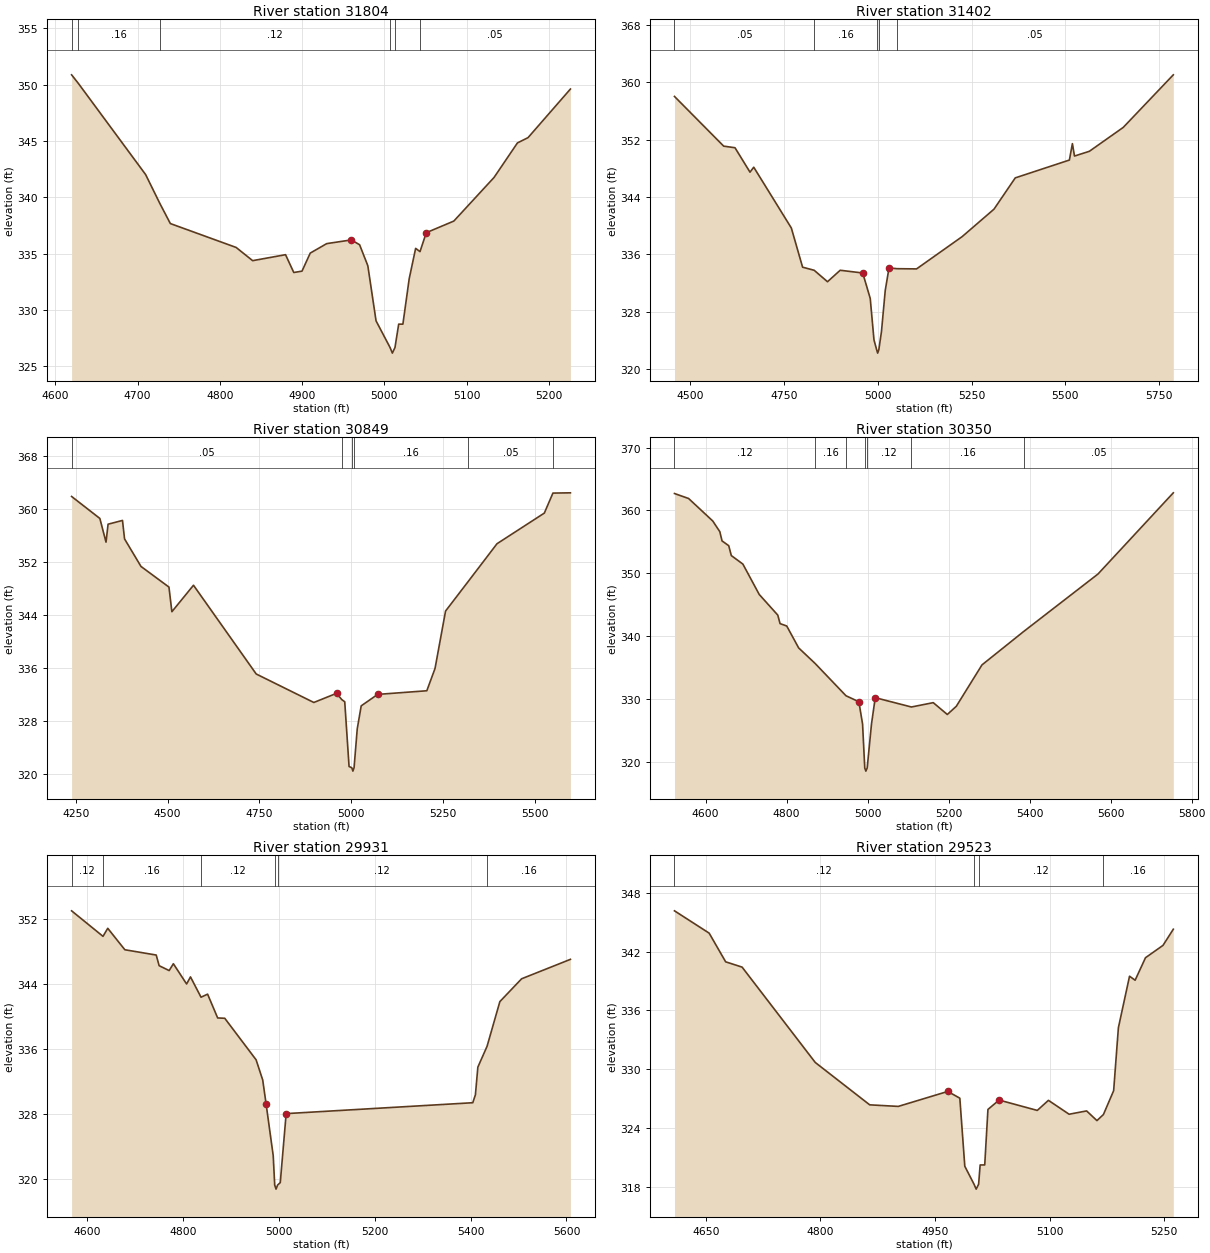
Type RM Length L Ch R = 1 ,31804   ,402,402,402
BEGIN DESCRIPTION:
UNT175 IN CCTC 28.0
END DESCRIPTION:
XS GIS Cut Line= 3
      3572399.57     10655260.19      3572799.61     10655260.19
      3572999.61     10655210.19
#Sta/Elev= 30
  4619.9  350.86  4628.2  350.09  4709.9  342.01  4727.1  339.46  4739.9  337.67
  4819.9  335.55  4839.9  334.38  4879.9  334.91  4889.9  333.33  4899.9  333.45
  4909.9  335.05  4929.9  335.89  4959.9  336.22  4969.9  335.79  4979.9  333.93
  4989.9  329.04  5006.9  326.68  5009.7  326.18  5012.9  326.68  5017.4  328.75
  5022.5  328.75  5030.2  332.79    5038  335.47  5043.3  335.18  5050.9  336.86
  5084.4  337.89  5133.3  341.76  5161.7  344.82  5174.6  345.29  5226.1   349.6
#Mann= 6 ,-1 , 0
  4619.9     .08       0  4628.2     .16       0  4727.1     .12       0
  5006.9     .07       0  5012.9     .12       0  5043.3     .05       0
Bank Sta=4959.9,5050.9
XS Rating Curve= 0 ,0
Exp/Cntr=0.3,0.1

Type RM Length L Ch R = 1 ,31402   ,553,553,553
BEGIN DESCRIPTION:
UNT175 IN CCTC 27.0
END DESCRIPTION:
XS GIS Cut Line= 3
      3572298.59      10655623.1      3572940.94     10655657.82
      3573558.99     10655359.21
#Sta/Elev= 30
  4458.2  358.03  4589.4  351.09  4619.5  350.87  4659.5  347.46  4669.5  348.15
  4769.7  339.66  4799.7  334.19  4830.5  333.76  4866.1  332.16  4899.9  333.76
    4960  333.38    4980  329.83    4990  324.04    4997  322.69  4999.8  322.19
    5003  322.69    5010  325.22    5020  330.94  5030.1   334.1  5051.1  333.98
  5103.5  333.95  5225.1  338.46  5309.9  342.29  5366.6  346.66  5510.9  349.15
  5518.9  351.44  5524.5  349.71  5564.1  350.37  5654.5  353.71  5787.9  361.05
#Mann= 5 ,-1 , 0
  4458.2     .05       0  4830.5     .16       0    4997     .07       0
    5003     .16       0  5051.1     .05       0
Bank Sta=4960,5030.1
XS Rating Curve= 0 ,0
Exp/Cntr=0.3,0.1

Type RM Length L Ch R = 1 ,30849   ,499,499,499
BEGIN DESCRIPTION:
UNT175 IN CCTC 26.0
END DESCRIPTION:
XS GIS Cut Line= 2
      3572121.83     10655832.94       3573340.4     10656435.71
#Sta/Elev= 30
  4238.4  361.96  4315.4  358.64  4332.2  355.06  4337.8  357.77  4377.1  358.34
  4382.7  355.55  4427.5  351.39  4503.7  348.27  4511.7  344.55  4570.6  348.55
  4741.6  335.14  4898.6  330.84  4960.4  332.22  4974.7  331.28  4982.8  330.95
  4994.6  321.17  5002.2  320.97    5005  320.47  5008.2  320.97  5016.9  326.86
  5027.7  330.33  5072.5  332.06  5206.5  332.61  5228.9  335.98  5257.6  344.65
  5319.9  349.16  5397.8  354.82  5526.8  359.45  5550.2  362.47  5597.9  362.51
#Mann= 6 ,-1 , 0
  4238.4     .05       0  4974.7     .16       0  5002.2     .07       0
  5008.2     .16       0  5319.9     .05       0  5550.2      .1       0
Bank Sta=4960.4,5072.5
XS Rating Curve= 0 ,0
Exp/Cntr=0.3,0.1

Type RM Length L Ch R = 1 ,30350   ,419,419,419
BEGIN DESCRIPTION:
UNT175 IN CCTC 25.0
END DESCRIPTION:
XS GIS Cut Line= 2
      3572048.03     10656306.02      3573166.22     10656821.77
#Sta/Elev= 30
  4523.3  362.69  4558.1   361.9  4617.7  358.33  4635.2  356.63  4640.7  355.16
  4657.2   354.4  4663.6  352.83  4692.1  351.48  4732.5  346.65  4778.3  343.37
  4783.9  342.02  4800.4  341.64  4829.8  338.16  4870.6  335.68  4946.6  330.56
  4978.5   329.6  4987.6  326.07    4993  319.08  4995.7  318.58    4999  319.08
  5009.6  326.05  5018.9  330.25  5108.2  328.77  5162.1  329.46  5196.8  327.58
    5219  328.88  5282.4  335.46    5385  340.75  5568.8   349.9  5754.7   362.8
#Mann= 7 ,-1 , 0
  4523.3     .12       0  4870.6     .16       0  4946.6     .12       0
    4993     .07       0    4999     .12       0  5108.2     .16       0
    5385     .05       0
Bank Sta=4978.5,5018.9
XS Rating Curve= 0 ,0
Exp/Cntr=0.3,0.1

Type RM Length L Ch R = 1 ,29931   ,408,408,408
BEGIN DESCRIPTION:
UNT175 IN CCTC 24.0
END DESCRIPTION:
XS GIS Cut Line= 3
      3571883.13     10656531.73      3572390.91     10656887.61
      3572473.38     10657299.97
#Sta/Elev= 30
  4567.6     353  4633.1  349.86    4643  350.85  4678.7  348.21  4744.1  347.56
  4750.2  346.25  4771.1  345.65  4779.9  346.49  4807.5     344  4815.6  344.87
  4837.6  342.37  4851.3  342.75  4872.3  339.82  4887.1  339.78  4952.5  334.67
  4966.3  332.18  4973.4  329.22  4988.2  322.87  4991.3  319.26  4994.1  318.76
  4997.3  319.26  5002.9  319.56  5015.2  328.05  5404.5  329.39    5410  330.37
  5415.1  333.77  5434.3  336.33    5461  341.83  5506.4  344.64  5608.2  347.03
#Mann= 6 ,-1 , 0
  4567.6     .12       0  4633.1     .16       0  4837.6     .12       0
  4991.3     .07       0  4997.3     .12       0  5434.3     .16       0
Bank Sta=4973.4,5015.2
XS Rating Curve= 0 ,0
Exp/Cntr=0.3,0.1

Type RM Length L Ch R = 1 ,29523   ,497,497,497
BEGIN DESCRIPTION:
UNT175 IN CCTC 23.0
END DESCRIPTION:
XS GIS Cut Line= 3
       3571749.6     10656960.18      3572099.61     10657160.19
      3572299.59     10657310.18
#Sta/Elev= 30
  4608.9  346.17  4654.3  343.89  4675.9  340.96  4697.4  340.42  4793.2  330.68
  4864.5  326.35  4901.9  326.19  4966.7  327.72  4982.5  327.03    4989  320.08
  5001.1  318.24  5003.9  317.74  5007.1  318.24  5009.1  320.21  5015.1  320.21
  5019.3  325.88  5033.9  326.84  5083.9  325.78  5098.5  326.81  5125.6  325.39
  5148.5  325.73    5162  324.74  5170.5  325.36  5183.9   327.8  5190.1  334.23
  5204.7  339.49    5212  339.08  5225.6  341.38  5248.5  342.64    5262  344.29
#Mann= 4 ,-1 , 0
  4608.9     .12       0  5001.1     .07       0  5007.1     .12       0
  5170.5     .16       0
Bank Sta=4966.7,5033.9
XS Rating Curve= 0 ,0
Exp/Cntr=0.3,0.1

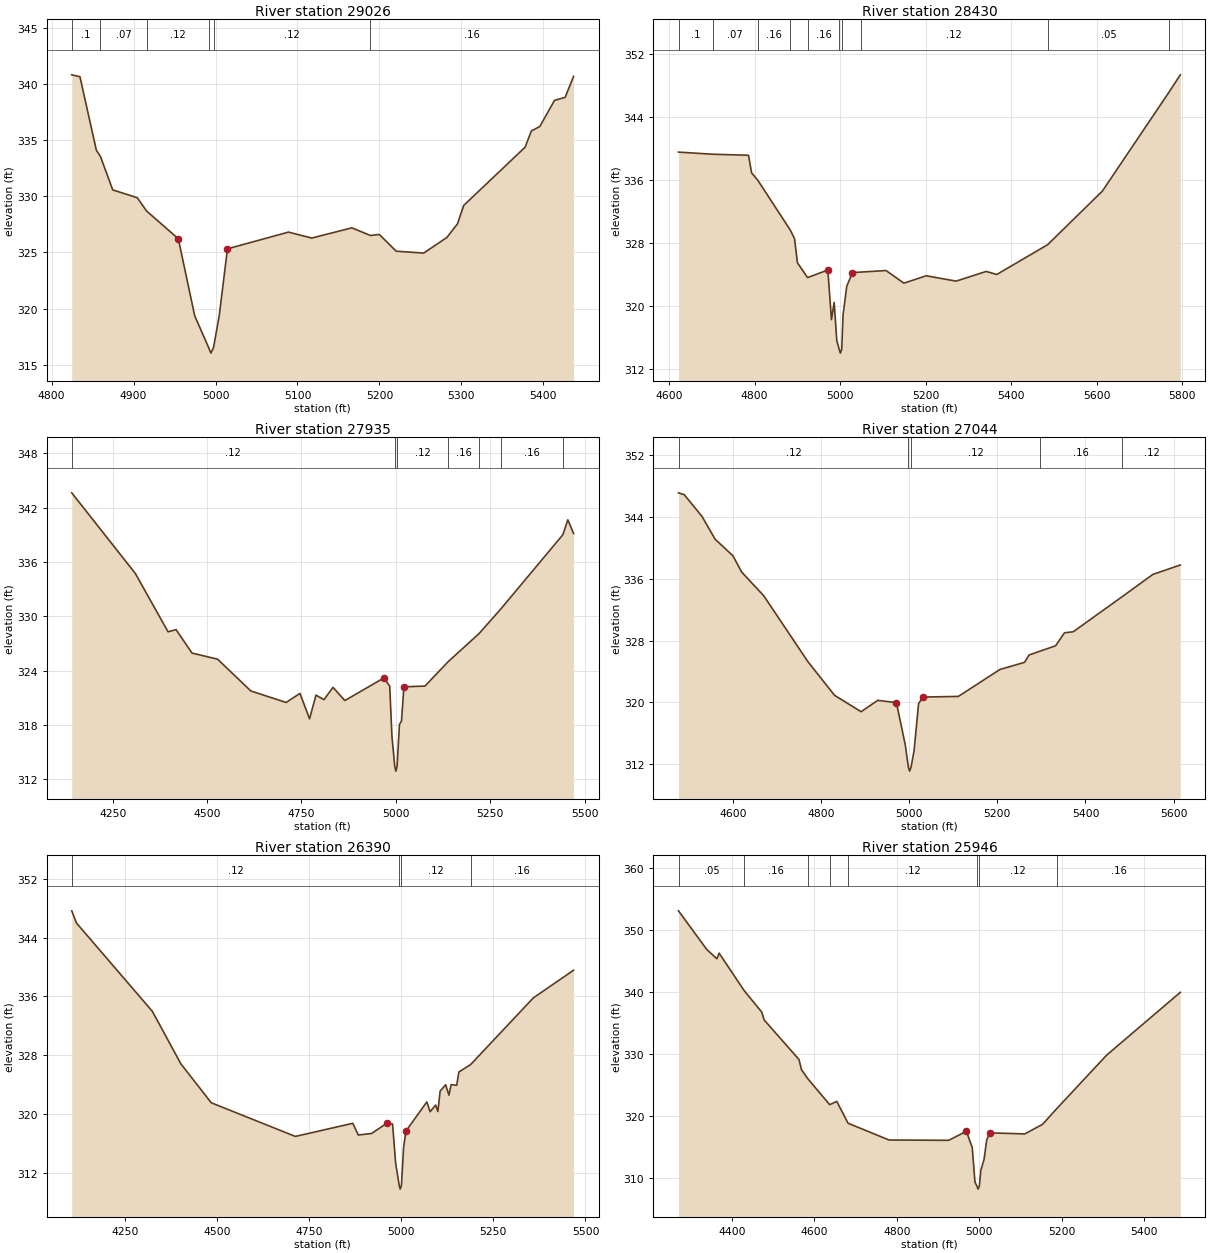
Type RM Length L Ch R = 1 ,29026   ,596,596,596
BEGIN DESCRIPTION:
UNT175 IN CCTC 22.0
END DESCRIPTION:
XS GIS Cut Line= 3
      3571599.59     10657310.19      3571799.61     10657310.19
      3572199.58     10657410.18
#Sta/Elev= 30
  4824.6  340.82  4834.6  340.65  4854.6  334.11  4859.6  333.55  4874.6  330.57
  4904.6  329.87  4915.9  328.69  4954.6  326.22  4974.6  319.36  4991.6  316.53
  4994.4  316.03  4997.6  316.53  5004.6   319.4  5014.6  325.32    5089  326.81
  5117.4  326.28  5166.4  327.19    5189  326.51  5199.9   326.6  5220.5  325.11
    5254  324.94  5282.3  326.33  5295.2  327.54  5302.9  329.19  5377.7  334.37
  5385.4  335.82  5395.7  336.22  5413.7  338.55  5426.6  338.81  5436.9  340.68
#Mann= 6 ,-1 , 0
  4824.6      .1       0  4859.6     .07       0  4915.9     .12       0
  4991.6     .07       0  4997.6     .12       0    5189     .16       0
Bank Sta=4954.6,5014.6
XS Rating Curve= 0 ,0
Exp/Cntr=0.3,0.1

Type RM Length L Ch R = 1 ,28430   ,495,495,495
BEGIN DESCRIPTION:
UNT175 IN CCTC 21.0
END DESCRIPTION:
XS GIS Cut Line= 4
      3571438.54     10657345.28      3571521.86     10657588.29
      3571681.58     10657810.51      3572320.47     10657734.13
#Sta/Elev= 30
  4621.9  339.56  4702.1  339.29  4785.7  339.16  4792.9  336.93  4807.2  336.01
  4883.4  329.68  4893.4  328.58  4900.1  325.53  4923.9  323.65  4971.3  324.61
  4979.7  318.32  4986.1   320.5  4992.2  315.67  4997.8  314.57  5000.5  314.07
  5003.8  314.57  5006.9  318.93  5015.5  322.55  5028.9  324.28    5049  324.35
  5107.6  324.54  5149.2  322.94  5201.6  323.88  5271.3   323.2  5341.8  324.43
  5366.4  324.04  5485.5  327.82  5613.6  334.62  5769.4  347.16  5795.9  349.36
#Mann= 10 ,-1 , 0
  4621.9      .1       0  4702.1     .07       0  4807.2     .16       0
  4883.4     .12       0  4923.9     .16       0  4997.8     .07       0
  5003.8     .16       0    5049     .12       0  5485.5     .05       0
  5769.4     .16       0
Bank Sta=4971.3,5028.9
XS Rating Curve= 0 ,0
Exp/Cntr=0.3,0.1

Type RM Length L Ch R = 1 ,27935   ,891,891,891
BEGIN DESCRIPTION:
UNT175 IN CCTC 20.0
END DESCRIPTION:
XS GIS Cut Line= 2
      3571007.96     10657199.36      3571444.83      10658454.5
#Sta/Elev= 30
  4141.6  343.65  4310.3  334.72  4396.6  328.29  4417.8  328.53  4460.1  325.94
  4527.9  325.26  4615.9  321.75  4709.2  320.48    4746  321.48  4771.4  318.67
  4788.4  321.29  4809.5  320.79  4833.6  322.15  4864.7  320.69  4968.4  323.19
  4983.7  322.28  4989.6  316.71  4997.1  313.39  4999.9  312.89  5003.1  313.39
  5009.5  318.05  5014.8  318.42  5021.3  322.21    5077  322.29  5138.3  324.98
  5220.7  328.11  5279.5  330.89  5442.4  339.03  5455.4  340.67  5470.6  339.16
#Mann= 7 ,-1 , 0
  4141.6     .12       0  4997.1     .07       0  5003.1     .12       0
  5138.3     .16       0  5220.7     .12       0  5279.5     .16       0
  5442.4     .05       0
Bank Sta=4968.4,5021.3
XS Rating Curve= 0 ,0
Exp/Cntr=0.3,0.1

Type RM Length L Ch R = 1 ,27044   ,654,654,654
BEGIN DESCRIPTION:
UNT175 IN CCTC 19.0
END DESCRIPTION:
XS GIS Cut Line= 2
      3570811.32     10657237.18      3570894.63     10658372.33
#Sta/Elev= 30
  4476.9  347.15  4489.9  346.91    4530  344.11  4560.1  341.13  4600.2     339
  4620.3  336.88  4670.4   333.8  4770.7  325.25  4830.9  320.91    4891  318.79
  4928.9  320.26  4971.2  319.96  4991.3  314.48  4998.3  311.59  5001.1  311.09
  5004.3  311.59  5011.3  313.77  5021.4  319.83  5031.4  320.69  5111.6  320.77
  5205.9  324.26    5262  325.19    5272  326.14  5297.2  326.64  5332.2  327.33
  5352.3  329.01  5372.3  329.15  5483.8  333.72  5552.8  336.58  5615.1   337.8
#Mann= 5 ,-1 , 0
  4476.9     .12       0  4998.3     .07       0  5004.3     .12       0
  5297.2     .16       0  5483.8     .12       0
Bank Sta=4971.2,5031.4
XS Rating Curve= 0 ,0
Exp/Cntr=0.3,0.1

Type RM Length L Ch R = 1 ,26390   ,444,444,444
BEGIN DESCRIPTION:
UNT175 IN CCTC 18.0
END DESCRIPTION:
XS GIS Cut Line= 3
      3570587.35     10657221.57      3570415.49     10657909.04
      3570780.09     10658450.74
#Sta/Elev= 30
  4106.2  347.63  4118.9  345.98    4325  333.97  4402.3  326.84  4484.8  321.55
  4712.9  316.98  4868.7  318.76  4883.7  317.17  4919.7  317.38  4961.7  318.79
  4976.7  318.66    4985  313.37  4994.7  310.32  4997.4  309.82  5000.7  310.32
  5006.6  315.46  5012.7  317.69  5069.7  321.67  5078.6  320.34  5093.5  321.24
  5099.6  320.36  5105.7  323.13  5120.6     324  5129.6  322.59  5135.6  324.01
  5150.6  323.93  5156.6  325.73  5188.4  326.74  5358.6   335.8  5467.8  339.56
#Mann= 4 ,-1 , 0
  4106.2     .12       0  4994.7     .07       0  5000.7     .12       0
  5188.4     .16       0
Bank Sta=4961.7,5012.7
XS Rating Curve= 0 ,0
Exp/Cntr=0.3,0.1

Type RM Length L Ch R = 1 ,25946   ,396,396,396
BEGIN DESCRIPTION:
UNT175 IN CCTC 17.0
END DESCRIPTION:
XS GIS Cut Line= 3
      3569899.84     10657471.49      3570134.24     10658080.91
      3570498.79     10658513.17
#Sta/Elev= 30
    4270  353.09  4338.6  346.87  4363.3  345.37  4368.6  346.28  4429.5  340.24
  4472.2  336.78  4477.9  335.53  4562.5  329.15  4568.6  327.51  4583.9  326.06
  4637.1  321.88  4654.3   322.4  4681.7  318.89  4781.1  316.19    4926  316.14
  4968.9  317.59  4983.2  314.98  4989.8   309.4  4994.5  308.78  4997.3  308.28
  5000.5  308.78    5004  311.31  5011.8  313.04  5018.3   316.2  5026.1  317.34
  5110.7  317.17  5153.6   318.7  5188.8  321.27  5309.6  329.86  5488.4  339.97
#Mann= 8 ,-1 , 0
    4270     .05       0  4429.5     .16       0  4583.9     .12       0
  4637.1     .16       0  4681.7     .12       0  4994.5     .07       0
  5000.5     .12       0  5188.8     .16       0
Bank Sta=4968.9,5026.1
XS Rating Curve= 0 ,0
Exp/Cntr=0.3,0.1

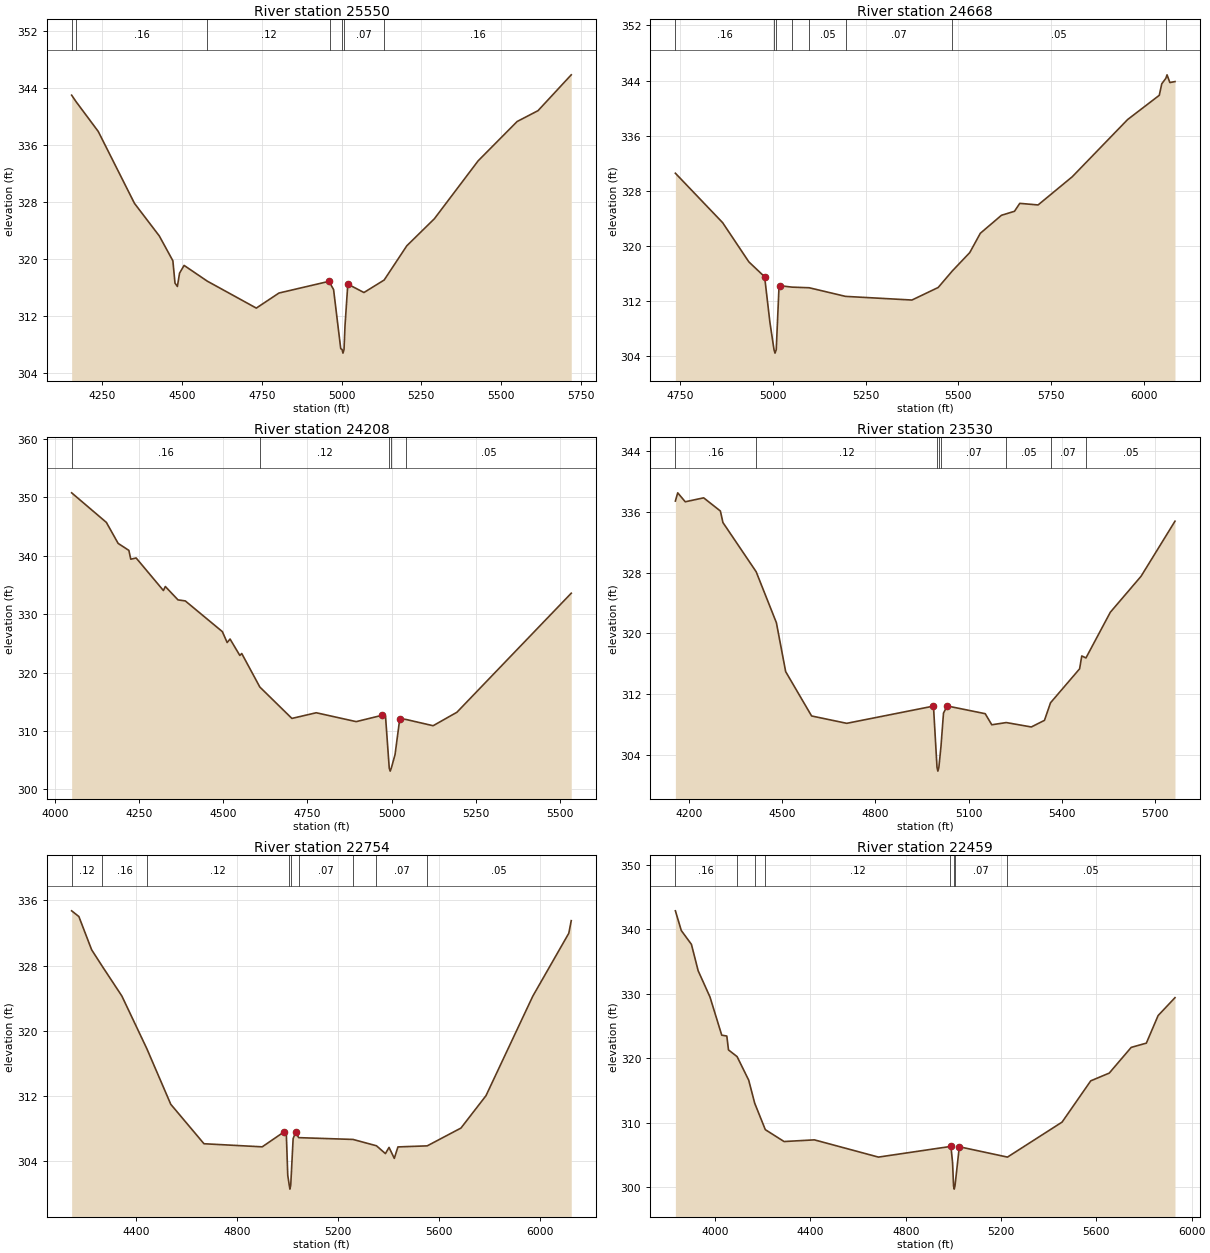
Type RM Length L Ch R = 1 ,25550   ,882,882,882
BEGIN DESCRIPTION:
UNT175 IN CCTC 16.0
END DESCRIPTION:
XS GIS Cut Line= 3
      3569382.95     10657678.55       3569841.3     10658192.46
      3570341.29     10658914.66
#Sta/Elev= 30
  4153.4  342.96  4167.6  342.03  4236.8  337.88  4350.5   327.8  4428.3  323.24
  4470.9  319.76  4477.6  316.63  4485.1  316.16  4491.8  318.02  4506.1  319.11
    4579   316.9  4732.6  313.13  4803.7  315.24  4960.9  316.88    4964   316.6
    4975  315.72  4997.4  307.45  5001.7  307.32  5004.4  306.82  5007.7  307.32
  5010.8  310.64  5019.6  316.49  5070.2  315.31  5133.6  317.06  5204.7  321.86
  5291.2  325.65  5428.4  333.76  5550.7  339.27  5616.2  340.79  5720.4  345.81
#Mann= 7 ,-1 , 0
  4153.4     .05       0  4167.6     .16       0    4579     .12       0
    4964     .07       0  5001.7     .07       0  5007.7     .07       0
  5133.6     .16       0
Bank Sta=4960.9,5019.6
XS Rating Curve= 0 ,0
Exp/Cntr=0.3,0.1

Type RM Length L Ch R = 1 ,24668   ,460,460,460
BEGIN DESCRIPTION:
UNT175 IN CCTC 15.0
END DESCRIPTION:
XS GIS Cut Line= 3
      3569099.61     10658060.19      3569299.61     10658260.19
      3569999.64     10659060.22
#Sta/Elev= 30
  4737.7  330.56    4865  323.39  4935.7   317.7  4978.1  315.54  4992.3  308.96
  5003.4  304.97  5006.1  304.47  5009.4  304.97    5017  314.24  5020.5  314.24
  5052.2  314.04  5098.2  313.95    5196   312.7    5375  312.17  5445.7  313.99
  5483.6  316.38  5530.7  319.05  5559.2  321.85  5616.1  324.46  5651.2  325.04
  5665.5  326.19  5714.8  325.96  5806.9  330.05  5955.9  338.34  6041.3  341.86
    6048  343.53  6058.8  344.31  6062.2  344.83  6069.8  343.71  6083.6  343.85
#Mann= 8 ,-1 , 0
  4737.7     .16       0  5003.4     .07       0  5009.4     .16       0
  5052.2     .07       0  5098.2     .05       0    5196     .07       0
  5483.6     .05       0  6058.8     .16       0
Bank Sta=4978.1,5020.5
XS Rating Curve= 0 ,0
Exp/Cntr=0.3,0.1

Type RM Length L Ch R = 1 ,24208   ,678,678,678
BEGIN DESCRIPTION:
UNT175 IN CCTC 14.0
END DESCRIPTION:
XS GIS Cut Line= 3
      3568799.62      10657760.2      3569249.61     10658560.19
      3569649.57     10658960.15
#Sta/Elev= 30
  4049.7   350.8  4152.9  345.73  4187.7  342.14  4219.6  340.94  4225.3  339.43
  4241.2  339.64  4322.2  334.06  4327.9  334.75  4365.5  332.46  4387.2  332.28
  4497.2  327.02  4511.5  325.15  4520.1  325.75  4549.1  322.94  4554.8  323.27
  4608.5  317.53  4703.7  312.15    4776  313.12  4894.6   311.6  4971.1  312.68
  4981.7  312.52  4992.8  303.62  4995.6  303.12  4998.8  303.62    5010  305.95
  5024.1  312.12  5042.7  311.97  5123.1   310.9  5193.8  313.21  5533.2   333.6
#Mann= 5 ,-1 , 0
  4049.7     .16       0  4608.5     .12       0  4992.8     .07       0
  4998.8     .12       0  5042.7     .05       0
Bank Sta=4971.1,5024.1
XS Rating Curve= 0 ,0
Exp/Cntr=0.3,0.1

Type RM Length L Ch R = 1 ,23530   ,776,776,776
BEGIN DESCRIPTION:
UNT175 IN CCTC 12.0
END DESCRIPTION:
XS GIS Cut Line= 3
      3568481.89     10658017.98      3568841.27     10658919.02
      3569288.12     10659376.27
#Sta/Elev= 30
  4155.7  337.44  4163.2  338.52  4187.5  337.34  4246.8  337.86  4300.7  336.12
  4308.8  334.61  4415.9  328.12  4481.1   321.4    4511  314.95  4594.5  309.11
  4707.7  308.14  4987.1  310.41  4998.5  302.34  5001.3  301.84  5004.5  302.34
  5011.3  305.11  5019.4  309.49  5031.2  310.43  5153.8  309.41  5174.9  307.95
  5221.7  308.24  5302.2  307.66  5344.6  308.53  5364.2  310.85  5457.8  315.32
  5464.8  317.02  5478.3  316.76  5556.8  322.78  5655.8  327.52  5765.1  334.78
#Mann= 8 ,-1 , 0
  4155.7     .16       0  4415.9     .12       0  4998.5     .07       0
  5004.5     .12       0  5011.3     .07       0  5221.7     .05       0
  5364.2     .07       0  5478.3     .05       0
Bank Sta=4987.1,5031.2
XS Rating Curve= 0 ,0
Exp/Cntr=0.3,0.1

Type RM Length L Ch R = 1 ,22754   ,295,295,295
BEGIN DESCRIPTION:
UNT175 IN CCTC 11.0
END DESCRIPTION:
XS GIS Cut Line= 4
      3568174.61      10657991.9      3568065.23      10658721.1
       3568174.6     10658903.39      3568975.65      10659548.4
#Sta/Elev= 30
  4145.9  334.73  4174.5  334.03  4225.1  329.94  4267.4   327.9  4344.7  324.26
  4443.8  317.77  4538.5  310.94    4670  306.09  4900.6  305.71  4987.1  307.55
  4995.8  307.49  5001.7  302.21  5007.5  301.01  5010.2  300.51  5013.5  301.01
    5023  306.72  5032.8   307.5  5044.9  306.84  5260.2  306.62    5353  305.84
  5388.4  304.88  5402.8  305.64  5423.6  304.29    5438   305.7    5554  305.83
  5687.6  308.02  5786.7     312  5972.3  324.25  6114.6  331.97  6124.3  333.52
#Mann= 9 ,-1 , 0
  4145.9     .12       0  4267.4     .16       0  4443.8     .12       0
  5007.5     .07       0  5013.5     .12       0  5044.9     .07       0
  5260.2     .05       0    5353     .07       0    5554     .05       0
Bank Sta=4987.1,5032.8
XS Rating Curve= 0 ,0
Exp/Cntr=0.3,0.1

Type RM Length L Ch R = 1 ,22459   ,1010,1010,1010
BEGIN DESCRIPTION:
UNT175 IN CCTC 10.0
END DESCRIPTION:
XS GIS Cut Line= 2
      3567299.66     10658254.98      3568757.95     10659761.89
#Sta/Elev= 30
  3833.1  342.84  3857.9  339.79  3900.4  337.65  3928.7  333.56  3978.3   329.5
  4027.7  323.58    4049  323.45    4056   321.3  4092.2  320.26  4140.9  316.61
    4166  313.05  4210.6  308.95  4289.3  307.11  4416.6  307.37  4685.4   304.7
  4986.3  306.34  4989.5  306.43  4996.5  303.87  5000.7  300.24  5003.4  299.74
  5006.7  300.24  5024.8   306.3    5227   304.7  5456.2  310.12  5576.5  316.51
  5654.2  317.71  5746.3  321.69  5809.9  322.35  5859.3  326.62  5930.1  329.39
#Mann= 8 ,-1 , 0
  3833.1     .16       0  4092.2     .05       0    4166     .16       0
  4210.6     .12       0  4986.3     .07       0  5000.7     .07       0
  5006.7     .07       0    5227     .05       0
Bank Sta=4989.5,5024.8
XS Rating Curve= 0 ,0
Exp/Cntr=0.3,0.1