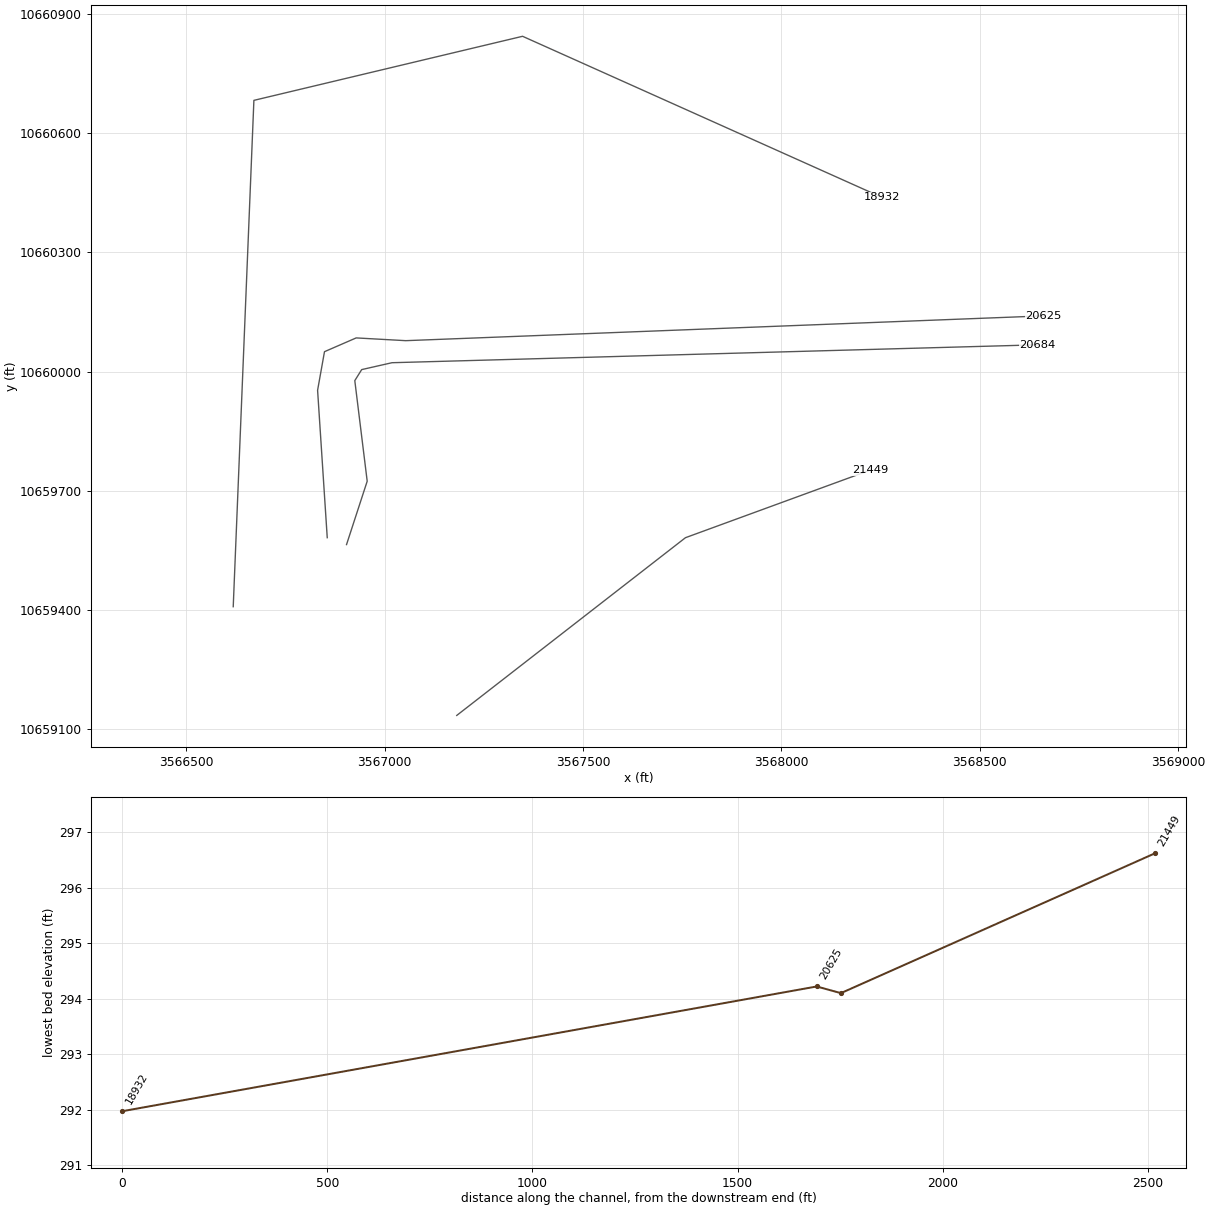
HEC-RAS study UNT175 IN CCTC.prj: UNT175 IN CCTC Base Level Engineering

--- UNT175 IN CCTC.g01 (geometry) --- (continued)

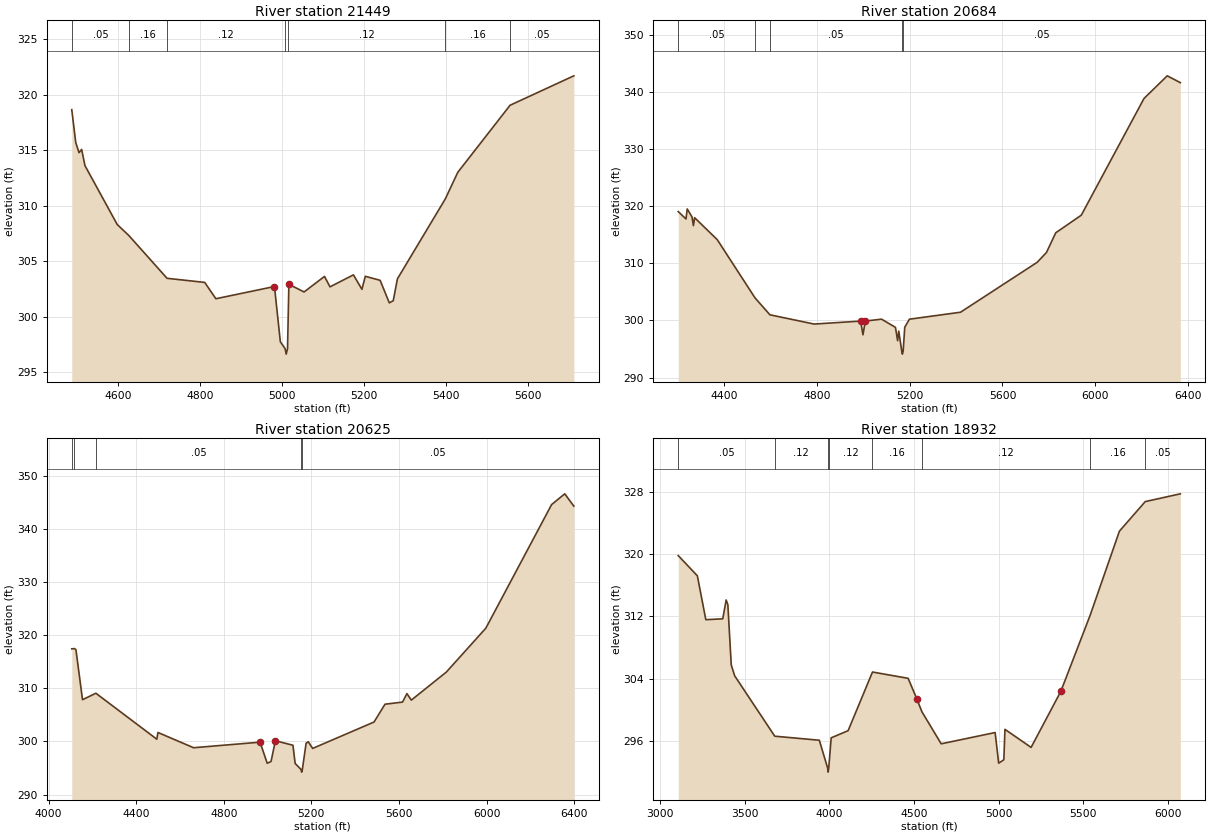
Type RM Length L Ch R = 1 ,21449   ,765,765,765
BEGIN DESCRIPTION:
UNT175 IN CCTC 9.0
END DESCRIPTION:
XS GIS Cut Line= 3
      3567181.92      10659133.3       3567758.3      10659581.2
      3568223.62     10659751.36
#Sta/Elev= 30
  4487.5  318.64  4497.2  315.68  4505.2  314.77  4511.6  315.06  4519.7   313.6
  4598.4   308.3  4626.9   307.3  4720.1  303.45    4812  303.08  4839.2  301.61
  4982.2  302.71  4996.6  297.73  5008.1  297.12  5010.9  296.62  5014.1  297.12
  5017.4  302.91  5054.5  302.22  5104.3  303.62  5117.8  302.68  5174.9  303.76
  5195.7  302.46  5203.9  303.63  5240.1  303.27  5262.5  301.24  5272.1  301.43
  5282.3   303.4    5399  310.59  5429.7     313  5557.3  319.04  5712.9  321.69
#Mann= 7 ,-1 , 0
  4487.5     .05       0  4626.9     .16       0  4720.1     .12       0
  5008.1     .07       0  5014.1     .12       0    5399     .16       0
  5557.3     .05       0
Bank Sta=4982.2,5017.4
XS Rating Curve= 0 ,0
Exp/Cntr=0.3,0.1

Type RM Length L Ch R = 1 ,20684   ,59,59,59
BEGIN DESCRIPTION:
UNT175 IN CCTC 8.0
END DESCRIPTION:
XS GIS Cut Line= 6
      3566904.13     10659563.84      3566956.21     10659723.56
      3566924.96     10659977.04      3566942.32     10660004.81
      3567018.71     10660022.17      3568645.86     10660067.28
#Sta/Elev= 30
  4203.6  319.04    4237  317.75  4242.3   319.5  4262.9  318.11  4268.9  316.58
  4274.2  317.97  4371.6  314.13  4534.3  303.94  4598.5  300.98    4789  299.36
  4989.2  299.88  4999.2  297.49  5009.2  299.88  5079.2  300.22  5139.2  298.78
  5148.4  296.45  5153.4  298.12  5166.2   294.6    5169   294.1  5172.2   294.6
  5179.2   298.8  5199.2  300.21  5419.3  301.43  5749.4  310.16  5789.4  311.88
  5829.5  315.33  5939.5  318.41  6209.6  338.83  6309.6  342.79  6365.9   341.6
#Mann= 5 ,-1 , 0
  4203.6     .05       0  4534.3     .12       0  4598.5     .05       0
  5166.2     .04       0  5172.2     .05       0
Bank Sta=4989.2,5009.2
XS Rating Curve= 0 ,0
Exp/Cntr=0.3,0.1

Type RM Length L Ch R = 1 ,20625   ,1693,1693,1693
BEGIN DESCRIPTION:
UNT175 IN CCTC 7.0
END DESCRIPTION:
XS GIS Cut Line= 6
      3566855.52      10659581.2      3566831.21     10659952.73
      3566848.57     10660049.95      3566928.43     10660084.67
      3567053.43     10660077.73      3568661.05     10660140.23
#Sta/Elev= 30
  4106.1  317.47  4118.2  317.52  4125.1  317.33  4155.2  307.88  4216.2   309.1
  4494.4  300.43  4499.5   301.7  4662.2  298.82  4965.8  299.87  4998.4   295.9
  5015.8  296.22  5035.8  300.14  5115.9  299.29  5125.9  295.86  5152.9  294.72
  5155.6  294.22  5158.9  294.72  5175.9  299.67  5185.9  299.95  5205.9  298.69
  5486.1  303.67  5536.2  307.03  5616.2  307.43  5636.3  309.03  5656.3   307.8
  5816.4   313.1  5996.5  321.37  6296.8  344.68  6356.8  346.71  6398.3  344.39
#Mann= 5 ,-1 , 0
  4106.1     .05       0  4118.2     .08       0  4216.2     .05       0
  5152.9     .04       0  5158.9     .05       0
Bank Sta=4965.8,5035.8
XS Rating Curve= 0 ,0
Exp/Cntr=0.3,0.1

Type RM Length L Ch R = 1 ,18932   ,0,0,0
BEGIN DESCRIPTION:
UNT175 IN CCTC 6.0
END DESCRIPTION:
XS GIS Cut Line= 4
      3566618.59     10659407.28      3566670.67     10660683.34
      3567347.75      10660844.8      3568253.97     10660438.57
#Sta/Elev= 30
  3107.5  319.81  3220.5  317.21  3270.5  311.57  3370.6  311.68  3390.6   314.1
  3400.7   313.5  3420.7  305.76  3440.7  304.36  3677.8  296.59  3941.1  296.07
  3990.5  292.47  3993.2  291.97  3996.5  292.47  4011.2  296.38  4111.2   297.3
  4255.2  304.84  4465.8  304.03    4517  301.39  4547.5  299.72  4661.1  295.61
  4979.8  297.06  5000.8  293.12  5031.2  293.56  5037.8  297.47  5192.3  295.15
  5367.6  302.34  5540.5   312.1  5714.1  322.95  5866.6  326.75  6073.8  327.75
#Mann= 8 ,-1 , 0
  3107.5     .05       0  3677.8     .12       0  3990.5     .07       0
  3996.5     .12       0  4255.2     .16       0  4547.5     .12       0
  5540.5     .16       0  5866.6     .05       0
#XS Ineff= 2 , 0
         4157.58  298.81
Permanent Ineff=
       F       F
Bank Sta=4517,5367.6
XS Rating Curve= 0 ,0
Exp/Cntr=0.3,0.1

Chan Stop Cuts=-1
Use User Specified Reach Order=0
Composite Channel Slope=5