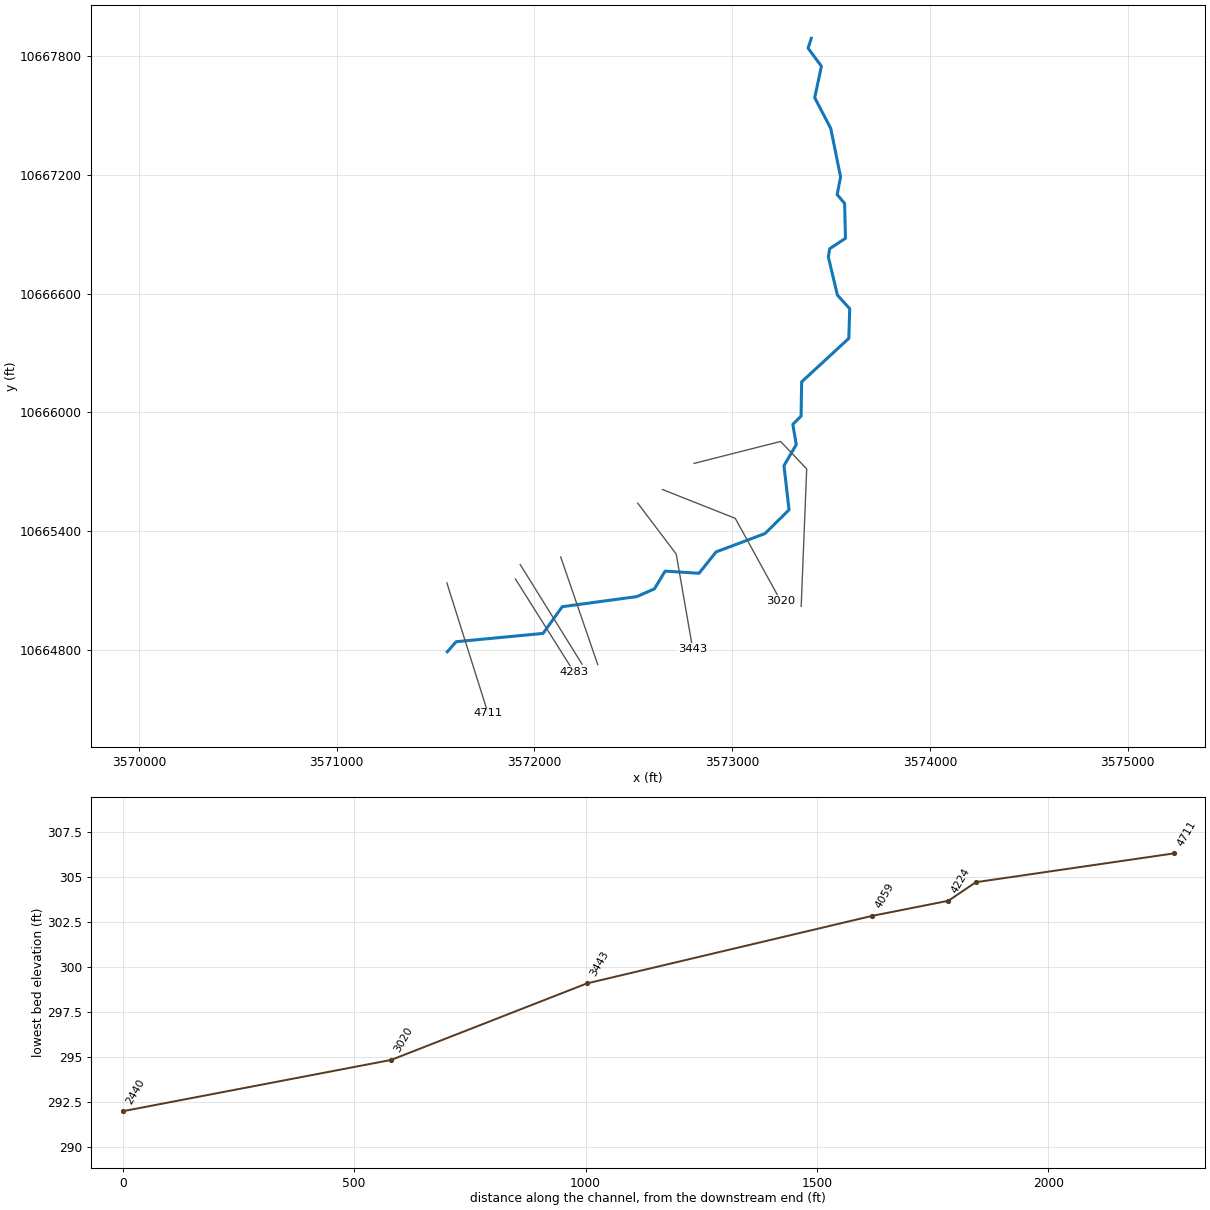
--- UNT177 IN CCTC.prj (project) ---

Proj Title=UNT177 IN CCTC Base Level Engineering
Current Plan=p01
Default Exp/Contr=0.3,0.1
English Units
Geom File=g01
Flow File=f01
Plan File=p01
BEGIN DESCRIPTION:
UNT177 IN CCTC
END DESCRIPTION:

--- UNT177 IN CCTC.p01 (plan) ---

Plan Title=Multiple Run
Short Identifier=Multiple
Geom File=g01
Flow File=f01
Subcritical Flow
K Sum by GR= 0
Std Step Tol= 0.01
Critical Tol= 0.01
Num of Std Step Trials= 20
Max Error Tol= 0.3
Flow Tol Ratio= 0.001
Split Flow NTrial= 30
Split Flow Tol= 0.02
Split Flow Ratio= 0.02
Log Output Level= 0
Friction Slope Method= 1
Unsteady Friction Slope Method= 2
Unsteady Bridges Friction Slope Method= 1
Parabolic Critical Depth
Global Vel Dist=  1 , 1 , 1
Global Log Level= 0
CheckData=True
Encroach Param= -1, 0, 0, 0
BEGIN DESCRIPTION:
Multiple Run
END DESCRIPTION:

--- UNT177 IN CCTC.f01 (steady flow) ---

Flow Title=Multiple
Number of Profiles=7
Profile Names=10-year,25-year,50-year,1pct_min,100-year,1pct_plu,500-year
River Rch & RM= UNT177 IN CCTC,Reach-1,4711
     994    1339    1618    1428    1932    2613    2742
Boundary for River Rch & Prof#=UNT177 IN CCTC,Reach-1,1
Up Type=0
Dn Type=3
Dn Slope=0.005
Boundary for River Rch & Prof#=UNT177 IN CCTC,Reach-1,2
Up Type=0
Dn Type=3
Dn Slope=0.005
Boundary for River Rch & Prof#=UNT177 IN CCTC,Reach-1,3
Up Type=0
Dn Type=3
Dn Slope=0.005
Boundary for River Rch & Prof#=UNT177 IN CCTC,Reach-1,4
Up Type=0
Dn Type=3
Dn Slope=0.005
Boundary for River Rch & Prof#=UNT177 IN CCTC,Reach-1,5
Up Type=0
Dn Type=3
Dn Slope=0.005
Boundary for River Rch & Prof#=UNT177 IN CCTC,Reach-1,6
Up Type=0
Dn Type=3
Dn Slope=0.005
Boundary for River Rch & Prof#=UNT177 IN CCTC,Reach-1,7
Up Type=0
Dn Type=3
Dn Slope=0.005

--- UNT177 IN CCTC.g01 (geometry) ---

Geom Title=Existing Conditions

River Reach=UNT177 IN CCTC,Reach-1
Reach XY= 30
      3571559.71     10664789.22      3571604.50     10664840.00
      3572043.75     10664882.00      3572140.75     10665017.00
      3572517.25     10665068.00      3572606.75     10665107.00
      3572661.00     10665197.00      3572832.50     10665186.00
      3572918.75     10665294.00      3573166.25     10665387.00
      3573287.75     10665507.00      3573262.00     10665730.00
      3573324.25     10665837.00      3573306.75     10665939.00
      3573348.50     10665981.00      3573351.50     10666154.00
      3573590.00     10666374.00      3573594.50     10666524.00
      3573532.50     10666592.00      3573486.50     10666785.00
      3573493.00     10666827.00      3573573.00     10666880.00
      3573568.75     10667056.00      3573531.00     10667101.00
      3573548.25     10667190.00      3573498.75     10667435.00
      3573417.50     10667591.00      3573451.50     10667750.00
      3573384.00     10667841.00      3573400.00     10667891.00

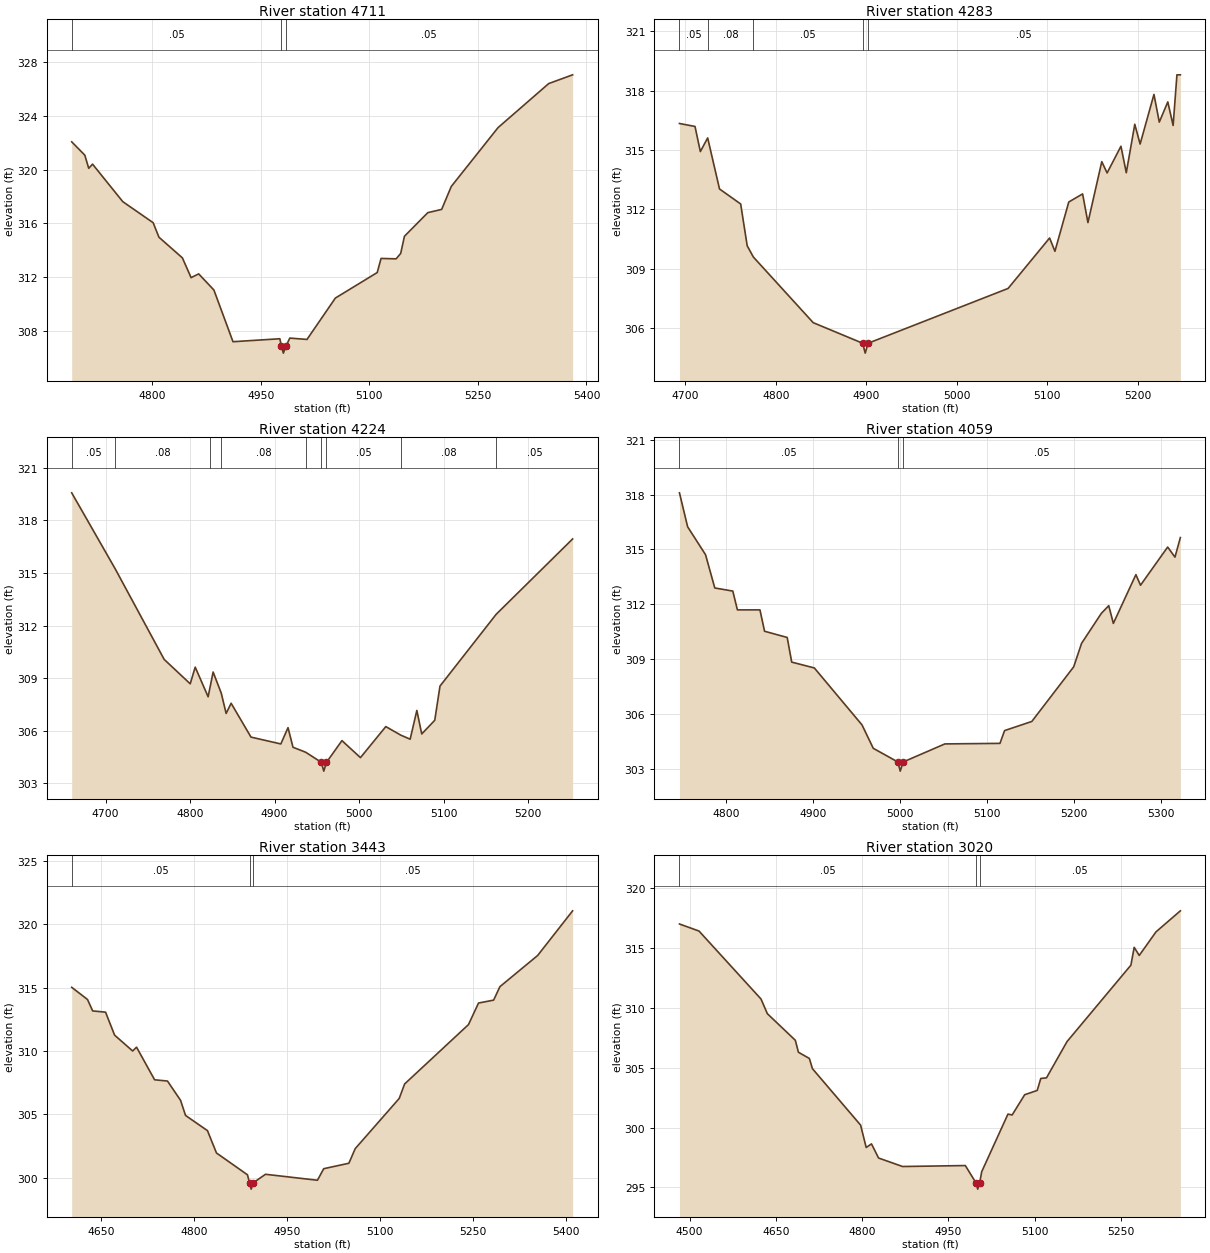
Type RM Length L Ch R = 1,4711,428,428,428
BEGIN DESCRIPTION:
UNT177 IN CCTC 4.0
END DESCRIPTION:
XS GIS Cut Line= 2
      3571557.47     10665137.46      3571765.82     10664477.67
#Sta/Elev= 30
  4689.0  322.06  4707.1  321.07  4712.5  320.09  4717.8  320.40  4759.5  317.61
  4801.5  316.04  4809.5  314.96  4841.9  313.42  4853.9  311.95  4864.4  312.23
  4885.4  311.03  4911.8  307.18  4976.5  307.40  4978.7  306.83  4981.4  306.33
  4984.7  306.83  4990.3  307.45  5014.0  307.35  5053.2  310.43  5111.0  312.33
  5116.3  313.38  5137.1  313.35  5143.4  313.75  5148.6  315.03  5180.9  316.79
  5200.0  317.03  5213.3  318.74  5277.9  323.12  5347.9  326.40  5380.9  327.05
#Mann=3,-1,0
  4689.0    0.05       0  4978.7    0.03       0  4984.7    0.05       0
Bank Sta=4978.7,4984.7
Exp/Cntr=0.3,0.1

Type RM Length L Ch R = 1,4283,59,59,59
BEGIN DESCRIPTION:
TEHUACANA CREEK 70.0
END DESCRIPTION:
XS GIS Cut Line= 2
      3571903.97     10665157.45      3572199.10     10664688.72
#Sta/Elev= 30
  4693.4  316.34  4710.6  316.19  4716.5  314.92  4724.6  315.61  4737.7  313.03
  4761.1  312.27  4768.3  310.16  4775.1  309.59  4841.3  306.27  4896.0  305.23
  4898.8  304.73  4902.0  305.23  5056.8  308.00  5102.7  310.55  5108.6  309.88
  5123.9  312.37  5139.2  312.78  5145.1  311.33  5160.4  314.41  5166.3  313.84
  5181.6  315.19  5187.5  313.85  5196.9  316.30  5202.8  315.30  5218.1  317.81
  5224.0  316.41  5233.4  317.43  5239.3  316.24  5243.5  318.80  5247.3  318.80
#Mann=5,-1,0
  4693.4    0.05       0  4724.6    0.08       0  4775.1    0.05       0
  4896.0    0.04       0  4902.0    0.05       0
Bank Sta=4896,4902
Exp/Cntr=0.3,0.1

Type RM Length L Ch R = 1,4224,165,165,165
BEGIN DESCRIPTION:
Mapping XS e377da3a
END DESCRIPTION:
XS GIS Cut Line= 2
      3571928.27     10665230.38      3572240.78     10664726.89
#Sta/Elev= 30
  4660.0  319.57  4711.4  315.24  4769.4  310.07  4800.2  308.68  4806.1  309.63
  4821.4  307.94  4824.1  308.59  4827.3  309.35  4836.9  308.15  4842.7  306.99
  4848.6  307.57  4872.1  305.64  4907.4  305.25  4915.9  306.18  4921.8  305.06
  4936.7  304.78  4955.4  304.20  4958.2  303.70  4961.4  304.20  4979.7  305.44
  5001.6  304.47  5031.6  306.24  5049.4  305.75  5060.4  305.52  5068.3  307.16
  5074.1  305.82  5089.5  306.60  5095.7  308.55  5162.1  312.64  5252.6  316.94
#Mann=9,-1,0
  4660.0    0.05       0  4711.4    0.08       0  4824.1    0.05       0
  4836.9    0.08       0  4936.7    0.05       0  4955.4    0.04       0
  4961.4    0.05       0  5049.4    0.08       0  5162.1    0.05       0
Bank Sta=4955.4,4961.4
Exp/Cntr=0.3,0.1

Type RM Length L Ch R = 1,4059,616,616,616
BEGIN DESCRIPTION:
UNT177 IN CCTC 3.0
END DESCRIPTION:
XS GIS Cut Line= 2
      3572133.12     10665268.60      3572320.33     10664724.30
#Sta/Elev= 30
  4746.8  318.10  4756.2  316.24  4776.8  314.71  4787.4  312.89  4808.1  312.72
  4813.4  311.69  4839.3  311.69  4844.6  310.52  4870.6  310.18  4875.8  308.83
  4901.8  308.51  4956.6  305.39  4969.5  304.11  4997.8  303.36  5000.5  302.86
  5003.8  303.36  5051.8  304.35  5115.1  304.38  5120.4  305.08  5151.7  305.58
  5199.8  308.57  5208.9  309.86  5231.6  311.50  5240.1  311.92  5245.4  310.95
  5271.3  313.62  5276.6  313.04  5307.8  315.13  5316.2  314.58  5322.4  315.65
#Mann=3,-1,0
  4746.8    0.05       0  4997.8    0.03       0  5003.8    0.05       0
Bank Sta=4997.8,5003.8
Exp/Cntr=0.3,0.1

Type RM Length L Ch R = 1,3443,423,423,423
BEGIN DESCRIPTION:
UNT177 IN CCTC 2.0
END DESCRIPTION:
XS GIS Cut Line= 3
      3572522.75     10665540.20      3572717.20     10665283.24
      3572800.44     10664804.66
#Sta/Elev= 30
  4602.6  315.02  4628.1  314.06  4636.4  313.16  4657.2  313.06  4671.8  311.25
  4700.9  310.00  4707.2  310.30  4736.3  307.73  4757.1  307.63  4778.2  306.11
  4786.2  304.92  4821.6  303.72  4836.1  301.96  4886.1  300.24  4889.4  299.61
  4892.1  299.11  4895.4  299.61  4915.2  300.28  4999.0  299.81  5009.1  300.72
  5049.7  301.15  5059.9  302.30  5130.9  306.26  5139.6  307.40  5242.6  312.08
  5258.8  313.78  5283.2  314.01  5293.3  315.07  5354.2  317.53  5410.6  321.05
#Mann=3,-1,0
  4602.6    0.05       0  4889.4    0.03       0  4895.4    0.05       0
Bank Sta=4889.4,4895.4
Exp/Cntr=0.3,0.1

Type RM Length L Ch R = 1,3020,580,580,580
BEGIN DESCRIPTION:
Mapping XS 2b6b3e80
END DESCRIPTION:
XS GIS Cut Line= 3
      3572647.76     10665609.63      3573015.81     10665463.80
      3573244.78     10665047.51
#Sta/Elev= 30
  4482.4  317.02  4516.4  316.43  4624.2  310.75  4635.3  309.52  4683.9  307.30
  4689.3  306.30  4708.3  305.78  4713.6  304.93  4797.4  300.21  4807.1  298.34
  4816.3  298.64  4828.6  297.46  4870.4  296.75  4979.5  296.83  4998.3  295.36
  5001.0  294.86  5004.3  295.36  5008.0  296.32  5053.6  301.13  5060.9  301.06
  5082.7  302.75  5104.5  303.11  5110.7  304.11  5120.6  304.16  5156.3  307.19
  5267.4  313.58  5273.1  315.07  5281.9  314.39  5311.0  316.36  5353.4  318.12
#Mann=3,-1,0
  4482.4    0.05       0  4998.3    0.03       0  5004.3    0.05       0
Bank Sta=4998.3,5004.3
Exp/Cntr=0.3,0.1

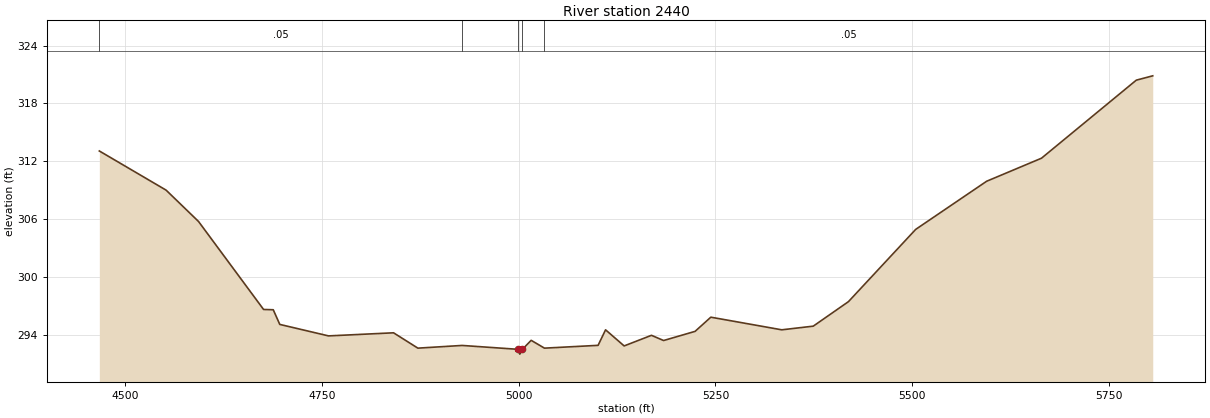
Type RM Length L Ch R = 1,2440,0,0,0
BEGIN DESCRIPTION:
UNT177 IN CCTC 1.0
END DESCRIPTION:
XS GIS Cut Line= 4
      3572807.44     10665741.57      3573244.98     10665852.69
      3573376.93     10665713.80      3573349.15     10665019.35
#Sta/Elev= 30
  4467.5  313.07  4552.3  309.01  4593.5  305.76  4676.1  296.64  4688.4  296.61
  4696.7  295.09  4758.6  293.90  4841.2  294.22  4872.1  292.63  4928.3  292.91
  4998.9  292.51  5001.6  292.01  5004.9  292.51  5016.0  293.44  5032.9  292.63
  5101.0  292.92  5110.5  294.53  5134.1  292.86  5168.8  293.96  5184.2  293.42
  5224.2  294.37  5244.2  295.84  5334.3  294.53  5374.3  294.91  5419.0  297.45
  5504.4  304.94  5594.5  309.93  5664.2  312.32  5784.6  320.41  5805.5  320.86
#Mann=5,-1,0
  4467.5    0.05       0  4928.3    0.16       0  4998.9    0.07       0
  5004.9    0.16       0  5032.9    0.05       0
Bank Sta=4998.9,5004.9
Exp/Cntr=0.3,0.1

Chan Stop Cuts=-1