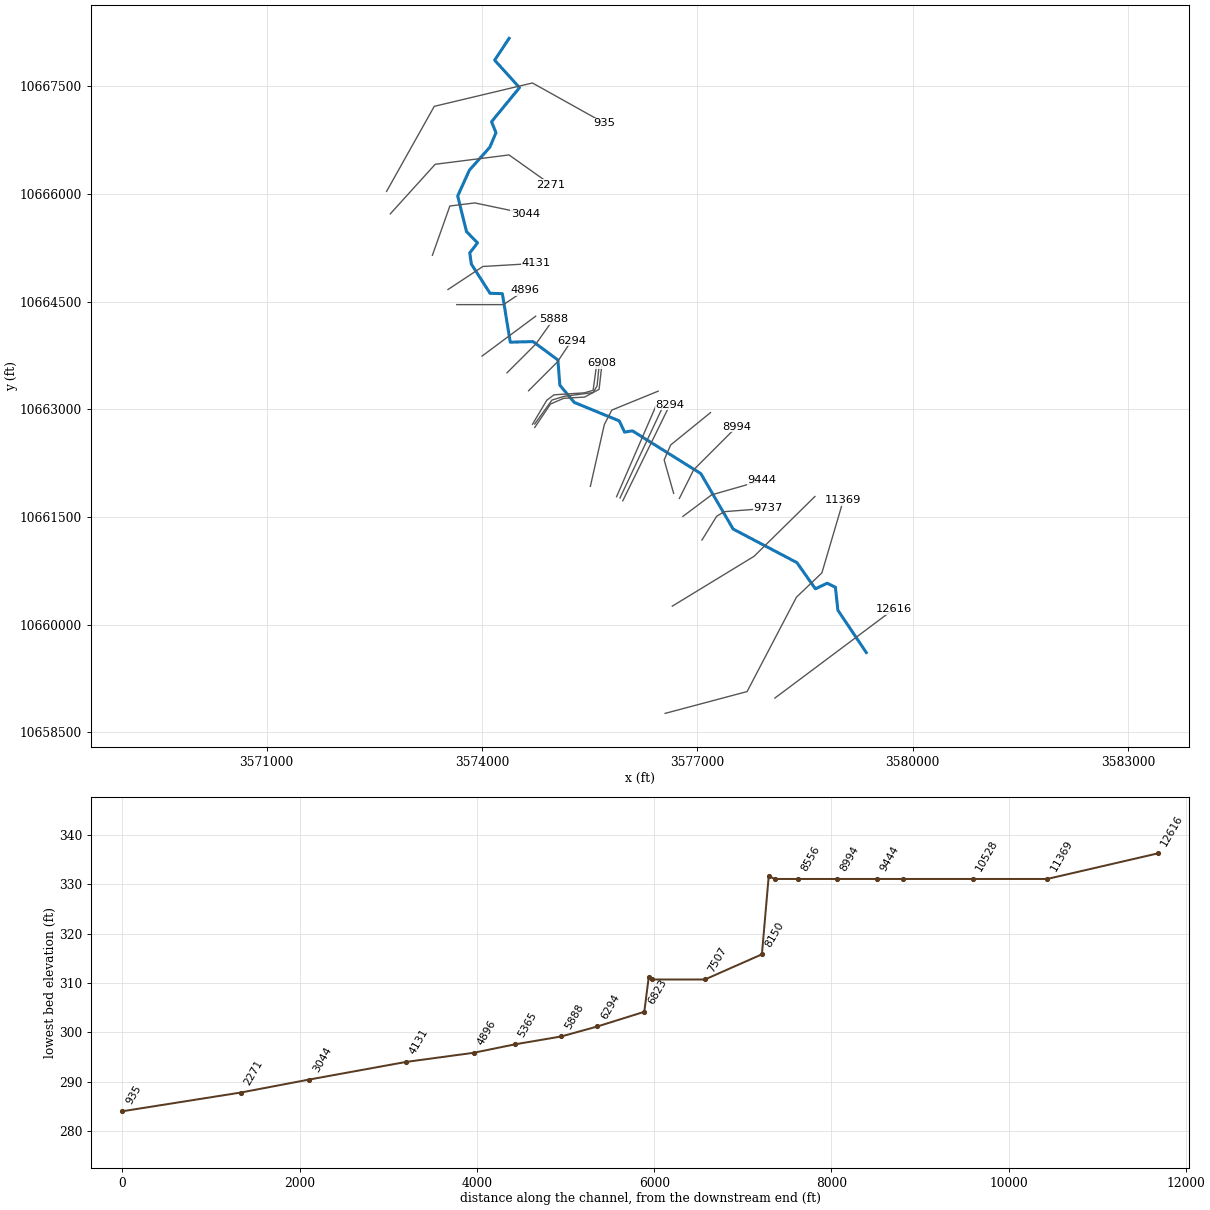
--- UNT178 IN CCTC.prj (project) ---

Proj Title=UNT178 IN CCTC Base Level Engineering
Current Plan=p01
Default Exp/Contr=0.3,0.1
English Units
Geom File=g01
Flow File=f01
Plan File=p01
Y Axis Title=Elevation
X Axis Title(PF)=Main Channel Distance
X Axis Title(XS)=Station
BEGIN DESCRIPTION:
UNT178 IN CCTC
END DESCRIPTION:
DSS Export Rating Curves= 0
DSS Export Rating Curve Sorted= 0
DSS Export Volume Flow Curves= 0
DXF OffsetX= 0
DXF OffsetY= 0
DXF ScaleX= 1
DXF ScaleY= 10

--- UNT178 IN CCTC.p01 (plan) ---

Plan Title=Multiple Run
Short Identifier=Multiple
Geom File=g01
Flow File=f01
Subcritical Flow
K Sum by GR= 0
Std Step Tol= 0.01
Critical Tol= 0.01
Num of Std Step Trials= 20
Max Error Tol= 0.3
Flow Tol Ratio= 0.001
Split Flow NTrial= 30
Split Flow Tol= 0.02
Split Flow Ratio= 0.02
Log Output Level= 0
Friction Slope Method= 1
Unsteady Friction Slope Method= 2
Unsteady Bridges Friction Slope Method= 1
Parabolic Critical Depth
Global Vel Dist=  1 , 1 , 1
Global Log Level= 0
CheckData=True
Encroach Param= -1, 0, 0, 0
BEGIN DESCRIPTION:
Multiple Run
END DESCRIPTION:

--- UNT178 IN CCTC.f01 (steady flow) ---

Flow Title=Multiple
Program Version=4.10
Number of Profiles= 7
Profile Names=10-year,25-year,50-year,1pct_min,100-year,1pct_plu,500-year
River Rch & RM=UNT178 IN CCTC,Reach-1         ,12616
    2555    3628    4541    4139    5598    7570    8484
River Rch & RM=UNT178 IN CCTC,Reach-1         ,9737
    2555    3628    4541    4139    5598    7570    8484
Boundary for River Rch & Prof#=UNT178 IN CCTC,Reach-1         , 1
Up Type= 0
Dn Type= 3
Dn Slope=0.005
Boundary for River Rch & Prof#=UNT178 IN CCTC,Reach-1         , 2
Up Type= 0
Dn Type= 3
Dn Slope=0.005
Boundary for River Rch & Prof#=UNT178 IN CCTC,Reach-1         , 3
Up Type= 0
Dn Type= 3
Dn Slope=0.005
Boundary for River Rch & Prof#=UNT178 IN CCTC,Reach-1         , 4
Up Type= 0
Dn Type= 3
Dn Slope=0.005
Boundary for River Rch & Prof#=UNT178 IN CCTC,Reach-1         , 5
Up Type= 0
Dn Type= 3
Dn Slope=0.005
Boundary for River Rch & Prof#=UNT178 IN CCTC,Reach-1         , 6
Up Type= 0
Dn Type= 3
Dn Slope=0.005
Boundary for River Rch & Prof#=UNT178 IN CCTC,Reach-1         , 7
Up Type= 0
Dn Type= 3
Dn Slope=0.005
DSS Import GetInterval= 0
DSS Import GetPeak= 0
DSS Import FillOption= 0

--- UNT178 IN CCTC.g01 (geometry) ---

Geom Title=Existing Conditions
Program Version=4.10

River Reach=UNT178 IN CCTC  ,Reach-1
Reach XY= 30
      3579352.54     10659613.39      3578957.49     10660202.02
      3578922.33     10660523.63      3578807.75     10660578.32
      3578643.68     10660501.06      3578386.74     10660865.65
        3577498.      10661333.9       3577048.5       10662106.
      3576095.25       10662702.        3575986.       10662684.
        3575913.       10662840.       3575285.5       10663098.
        3575085.       10663338.        3575058.       10663689.
      3574711.75       10663945.      3574394.75       10663937.
      3574284.25       10664613.        3574113.       10664618.
        3573852.       10665026.       3573830.5       10665180.
        3573939.       10665321.        3573785.       10665477.
       3573662.5       10665974.      3573825.25       10666333.
      3574109.75       10666653.      3574195.75       10666855.
      3574133.75       10667008.      3574523.25       10667483.
      3574177.25       10667866.       3574378.5       10668170.

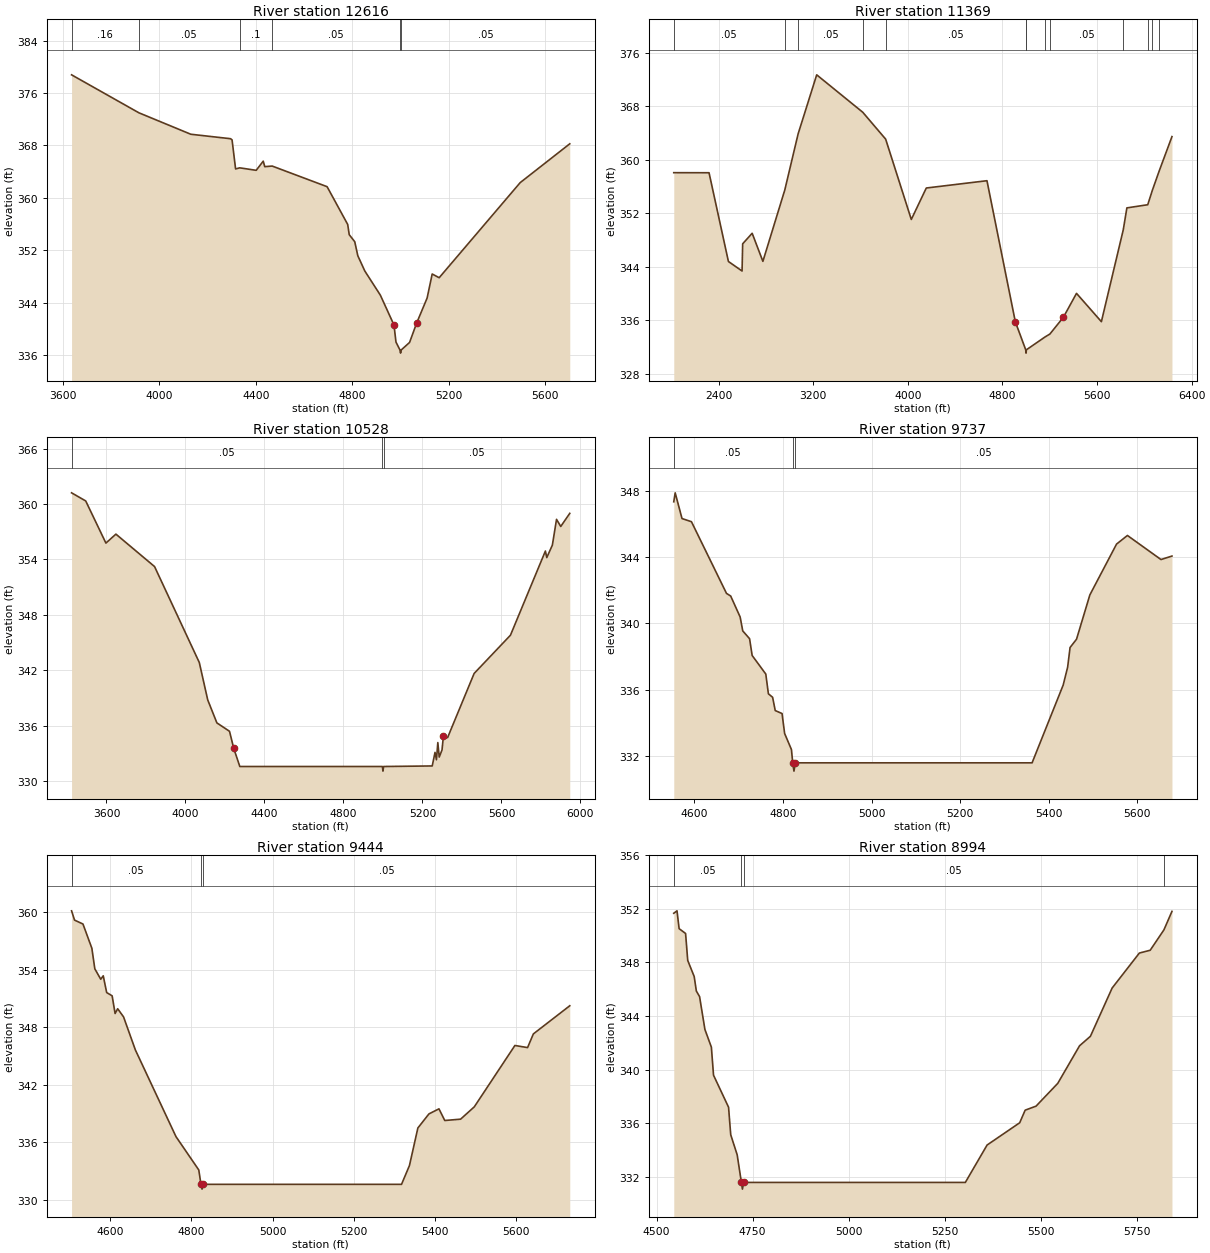
Type RM Length L Ch R = 1 ,12616   ,1247,1247,1247
BEGIN DESCRIPTION:
Mapping XS b173d2b6
END DESCRIPTION:
XS GIS Cut Line= 2
      3578079.61      10658978.5      3579733.09     10660215.36
#Sta/Elev= 30
  3636.2  378.79  3915.1  372.99  4130.5  369.71  4295.1  369.03  4301.4  368.85
    4316  364.41    4333  364.58  4401.4   364.2  4430.6   365.6  4436.9  364.76
  4467.8  364.85  4695.3   361.7  4780.7  355.93    4787  354.37  4809.9  353.29
  4822.6  351.15  4851.6  348.82  4916.2  345.12  4972.5  340.56  4980.8  337.96
    4997  336.77  4999.8  336.27    5003  336.77  5037.1   337.9  5066.3  340.85
  5109.8  344.68  5130.9  348.36  5159.8  347.79  5495.6  362.32  5701.1  368.25
#Mann= 6 ,-1 , 0
  3636.2     .16       0  3915.1     .05       0    4333      .1       0
  4467.8     .05       0    4997     .03       0    5003     .05       0
Bank Sta=4972.5,5066.3
XS Rating Curve= 0 ,0
Exp/Cntr=0.3,0.1

Type RM Length L Ch R = 1 ,11369   ,841,841,841
BEGIN DESCRIPTION:
Mapping XS 1a9b807b
END DESCRIPTION:
XS GIS Cut Line= 5
      3576551.44     10658765.42      3577692.92     10659069.24
      3578380.42     10660384.34      3578734.59     10660722.88
      3579033.59     10661736.89
#Sta/Elev= 30
  2021.3  358.05  2319.5  358.04  2483.4  344.78  2598.7  343.36  2603.8  347.42
  2684.1     349  2774.8   344.8  2960.1  355.47  3072.6  363.84  3229.8  372.67
  3619.1  367.08  3812.9  363.06  4029.7  351.06  4156.5  355.76  4669.4  356.85
  4909.2  335.78    4997  331.59  4999.8  331.09    5003  331.59  5161.7  333.52
  5201.3  333.94  5316.1  336.46  5426.5  340.02  5636.9  335.79  5821.8  349.51
  5852.4  352.79  6028.7  353.26  6068.1  355.43  6124.7  358.26  6233.6  363.44
#Mann= 13 ,-1 , 0
  2021.3     .05       0  2960.1     .16       0  3072.6     .05       0
  3619.1      .1       0  3812.9     .05       0    4997    .035       0
    5003     .05       0  5161.7      .1       0  5201.3     .05       0
  5821.8     .08       0  6028.7     .05       0  6068.1     .08       0
  6124.7     .05       0
Bank Sta=4909.2,5316.1
XS Rating Curve= 0 ,0
Exp/Cntr=0.3,0.1

Type RM Length L Ch R = 1 ,10528   ,791,791,791
BEGIN DESCRIPTION:
Mapping XS 95c83dec
END DESCRIPTION:
XS GIS Cut Line= 3
      3576651.22     10660259.32      3577790.14     10660953.79
      3578637.35      10661787.1
#Sta/Elev= 30
  3423.4  361.21    3495  360.33  3597.2  355.77  3647.9  356.74  3843.5  353.23
    4070  342.85  4112.7   338.8  4159.1  336.31    4223   335.4  4244.3  333.57
  4275.2  331.59    4997  331.59  4999.8  331.09    5003  331.59  5249.4  331.65
  5263.5  333.12  5270.7  332.32  5277.7  334.18  5284.8  332.61  5298.9  333.38
    5306  334.87  5327.2  334.72  5461.5  341.66  5645.4   345.8  5822.3  354.91
  5829.3   354.2  5857.6  355.55  5878.7  358.34    5900  357.57  5945.7  358.99
#Mann= 3 ,-1 , 0
  3423.4     .05       0    4997    .033       0    5003     .05       0
Bank Sta=4244.3,5306
XS Rating Curve= 0 ,0
Exp/Cntr=0.3,0.1

Type RM Length L Ch R = 1 ,9737    ,293,293,293
BEGIN DESCRIPTION:
UNT178 IN CCTC 16.0
END DESCRIPTION:
XS GIS Cut Line= 4
      3577064.24     10661180.32      3577268.25      10661510.2
      3577372.41      10661575.3      3577984.35     10661623.04
#Sta/Elev= 30
  4553.7  347.32  4556.9  347.86  4572.3  346.31  4593.6  346.12  4672.7   341.8
  4682.2  341.64  4703.5  340.38  4709.4  339.54  4724.8  339.07  4730.6  338.06
  4761.4  336.94  4767.3  335.75  4776.8  335.54  4782.7  334.74  4798.1  334.56
  4803.9  333.36  4819.3  332.39  4822.2  331.59    4825  331.09  4828.2  331.59
  5362.5  331.59  5432.7  336.28  5442.7  337.35  5448.2  338.54  5462.8  339.04
  5492.9  341.71  5553.1  344.77  5577.7  345.29  5653.4  343.84  5678.2  344.05
#Mann= 3 ,-1 , 0
  4553.7     .05       0  4822.2    .033       0  4828.2     .05       0
Bank Sta=4822.2,4828.2
XS Rating Curve= 0 ,0
Exp/Cntr=0.3,0.1

Type RM Length L Ch R = 1 ,9444    ,450,450,450
BEGIN DESCRIPTION:
UNT178 IN CCTC 15.0
END DESCRIPTION:
XS GIS Cut Line= 3
       3576799.6     10661510.18      3577199.61     10661810.19
      3577899.59     10662010.18
#Sta/Elev= 30
  4504.5  360.17  4511.8   359.2  4532.6  358.79  4554.5  356.26  4561.8  354.11
  4576.4  353.02  4582.6  353.38    4591  351.63  4604.5  351.29  4611.8  349.44
  4618.1  349.94  4632.6  349.09  4661.8  345.63  4761.8  336.58  4818.1  333.09
  4823.4  331.59  4826.1  331.09  4829.4  331.59  5317.8  331.59  5337.3  333.55
  5358.1  337.48  5385.4  338.95  5410.1  339.48  5424.4  338.26  5463.4   338.4
  5497.2  339.69  5597.3   346.1  5628.5  345.88  5642.8  347.31  5732.5  350.25
#Mann= 3 ,-1 , 0
  4504.5     .05       0  4823.4    .033       0  4829.4     .05       0
Bank Sta=4823.4,4829.4
XS Rating Curve= 0 ,0
Exp/Cntr=0.3,0.1

Type RM Length L Ch R = 1 ,8994    ,438,438,438
BEGIN DESCRIPTION:
UNT178 IN CCTC 14.0
END DESCRIPTION:
XS GIS Cut Line= 3
      3576749.62     10661760.22      3576949.61     10662160.19
       3577549.6     10662760.18
#Sta/Elev= 30
  4544.8  351.67  4553.2  351.85  4558.7  350.52  4575.5  350.16  4581.1  348.15
  4597.9  346.95  4603.5  345.87  4611.9  345.45  4625.8     343  4642.6  341.68
  4648.2  339.59  4687.3   337.2  4692.9  335.15  4709.7  333.65  4720.7  331.59
  4723.4  331.09  4726.7  331.59  5303.1  331.59  5359.7  334.38  5444.5  336.04
  5458.7  336.98    5487  337.28  5543.5  338.98  5600.1  341.78  5628.4  342.49
  5684.9  346.09  5755.7   348.7  5783.9  348.91  5819.6  350.43  5840.5  351.81
#Mann= 4 ,-1 , 0
  4544.8     .05       0  4720.7    .033       0  4726.7     .05       0
  5819.6      .1       0
Bank Sta=4720.7,4726.7
XS Rating Curve= 0 ,0
Exp/Cntr=0.3,0.1

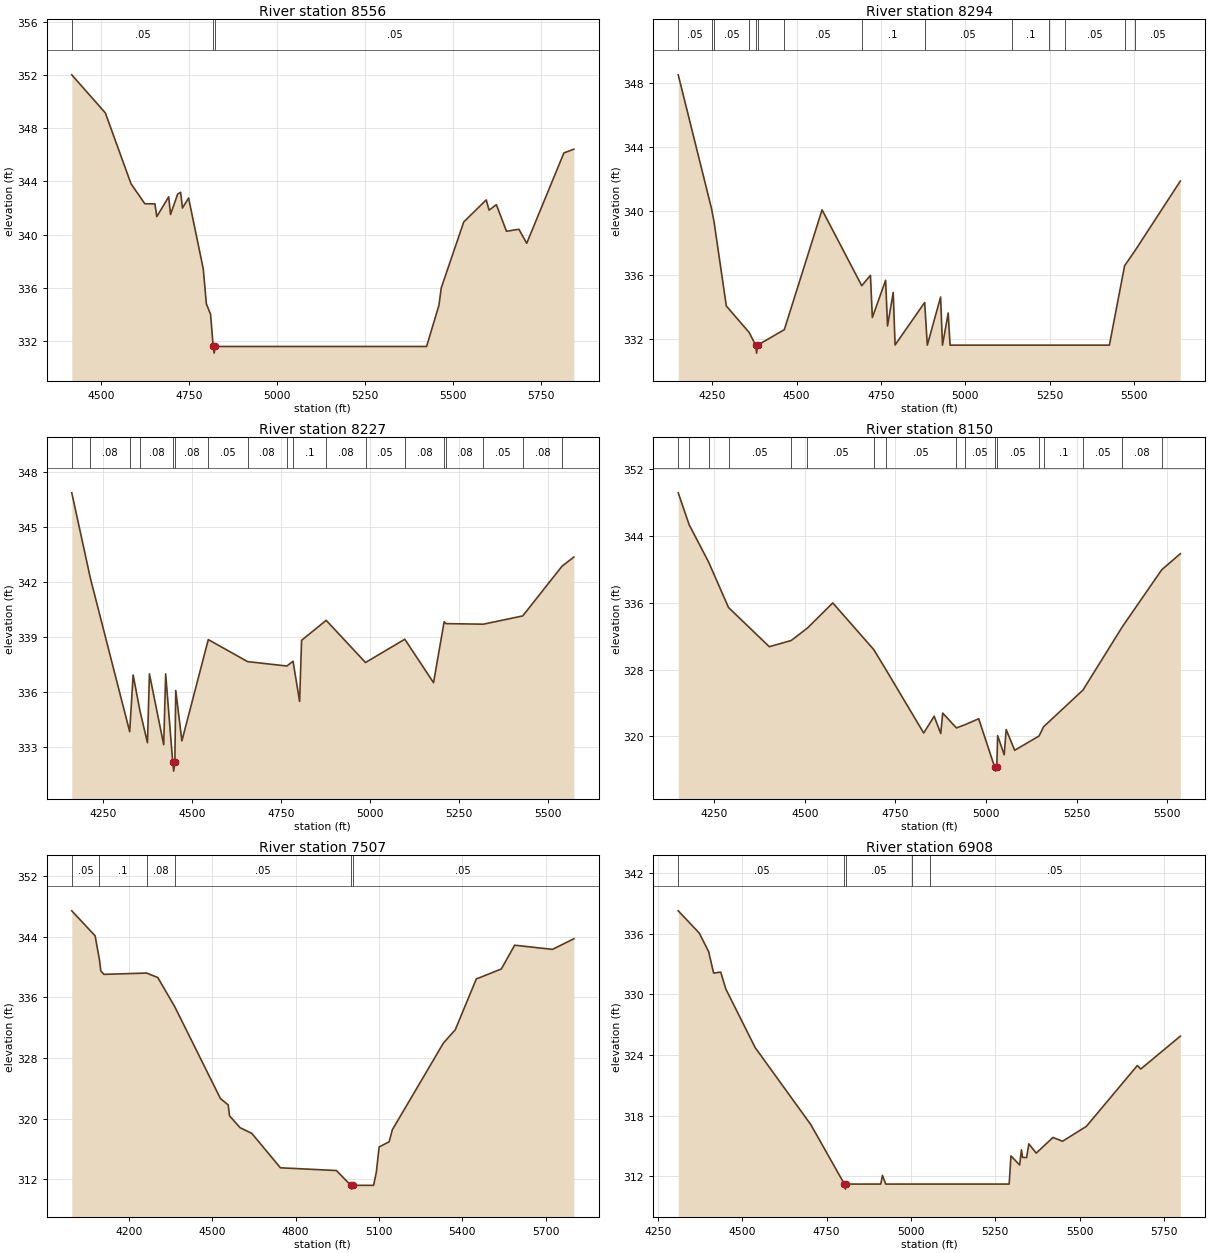
Type RM Length L Ch R = 1 ,8556    ,262,262,262
BEGIN DESCRIPTION:
UNT178 IN CCTC 13.0
END DESCRIPTION:
XS GIS Cut Line= 4
       3576669.9     10661830.97      3576537.95     10662296.27
      3576628.23      10662504.6      3577183.31      10662955.6
#Sta/Elev= 30
  4417.4  352.01  4512.7  349.15  4585.7  343.82  4624.9  342.32  4653.6  342.31
  4658.8  341.35  4692.7  342.84  4697.9  341.51    4718  343.04  4726.6  343.18
  4731.8     342  4749.2  342.75  4790.8  337.43  4799.7  334.79  4811.6  334.01
    4819  331.59  4821.7  331.09    4825  331.59  5425.1  331.59  5460.2  334.69
  5466.7  335.99  5530.6  340.95  5594.5  342.61  5602.5  341.84  5623.3  342.25
    5652  340.25  5687.2   340.4  5709.5  339.35  5815.1  346.14  5843.3  346.42
#Mann= 3 ,-1 , 0
  4417.4     .05       0    4819    .033       0    4825     .05       0
Bank Sta=4819,4825
XS Rating Curve= 0 ,0
Exp/Cntr=0.3,0.1

Type RM Length L Ch R = 1 ,8294    ,67,67,67
BEGIN DESCRIPTION:
UNT178 IN CCTC 12.0
END DESCRIPTION:
XS GIS Cut Line= 2
      3575961.82     10661727.22       3576617.2     10663064.01
#Sta/Elev= 30
  4148.8  348.51  4247.6  340.13  4255.3  339.27  4291.4  334.04  4358.9  332.39
  4378.4  331.59  4381.1  331.09  4384.4  331.59  4463.4  332.56  4575.3  340.06
    4693  335.31  4718.8  335.96  4724.4  333.32  4763.8  335.65  4769.4  332.79
  4786.3  334.89  4791.8   331.6  4879.5  334.26  4887.4  331.59  4926.8   334.6
  4932.4  331.59  4949.3   333.6  4954.9  331.59  5138.3  331.59  5249.7  331.59
  5295.7  331.59  5427.3  331.59  5472.4  336.56  5503.8  337.52  5637.6  341.86
#Mann= 14 ,-1 , 0
  4148.8     .05       0  4247.6     .08       0  4255.3     .05       0
  4358.9     .08       0  4378.4    .033       0  4384.4     .08       0
  4463.4     .05       0    4693      .1       0  4879.5     .05       0
  5138.3      .1       0  5249.7     .08       0  5295.7     .05       0
  5472.4     .08       0  5503.8     .05       0
Bank Sta=4378.4,4384.4
XS Rating Curve= 0 ,0
Exp/Cntr=0.3,0.1

Type RM Length L Ch R = 1 ,8227    ,77,77,77
BEGIN DESCRIPTION:
Mapping XS 71d04f2a
END DESCRIPTION:
XS GIS Cut Line= 2
      3575922.75     10661766.25       3576521.7     10663042.28
#Sta/Elev= 30
  4163.2  346.85  4215.4   342.2  4325.8  333.83  4335.5  336.92  4354.7  334.96
  4375.7  333.23  4381.2  336.98  4421.3  333.12  4426.8  336.98  4446.6  332.18
  4449.4  331.68  4452.6  332.18  4455.1  336.08  4472.4  333.33  4546.5  338.85
  4656.8  337.65  4767.2  337.41  4784.4  337.67  4802.9  335.48  4808.4  338.81
  4877.5   339.9  4987.9   337.6  5098.2  338.87  5178.9   336.5  5208.6  339.82
  5214.1  339.72  5318.9  339.69  5429.3  340.14  5539.6  342.85  5572.8  343.35
#Mann= 18 ,-1 , 0
  4163.2     .05       0  4215.4     .08       0  4325.8     .05       0
  4354.7     .08       0  4446.6     .04       0  4452.6     .08       0
  4546.5     .05       0  4656.8     .08       0  4767.2     .05       0
  4784.4      .1       0  4877.5     .08       0  4987.9     .05       0
  5098.2     .08       0  5208.6      .1       0  5214.1     .08       0
  5318.9     .05       0  5429.3     .08       0  5539.6     .05       0
Bank Sta=4446.6,4452.6
XS Rating Curve= 0 ,0
Exp/Cntr=0.3,0.1

Type RM Length L Ch R = 1 ,8150    ,643,643,643
BEGIN DESCRIPTION:
Mapping XS e83084de
END DESCRIPTION:
XS GIS Cut Line= 2
      3575875.03     10661783.67       3576426.2     10663055.25
#Sta/Elev= 30
  4150.3  349.19  4180.4  345.37  4233.9  340.91  4289.1  335.44  4401.7  330.74
    4462  331.48  4506.5  332.96  4576.9  335.99  4690.1  330.39    4724  327.96
  4827.9  320.39  4856.8   322.4  4874.9  320.33  4880.3  322.78  4918.2     321
  4941.4  321.38  4979.7   322.1  5023.6  316.32  5026.3  315.82  5029.6  316.32
    5032  320.08  5050.1  317.78  5055.5  320.81    5079  318.32  5146.3  320.03
  5158.8  321.14  5267.5  325.54  5376.3  333.14    5485  339.97  5536.2  341.89
#Mann= 17 ,-1 , 0
  4150.3     .08       0  4180.4     .05       0  4233.9     .08       0
  4289.1     .05       0    4462     .08       0  4506.5     .05       0
  4690.1     .08       0    4724     .05       0  4918.2     .08       0
  4941.4     .05       0  5023.6     .04       0  5029.6     .05       0
  5146.3     .08       0  5158.8      .1       0  5267.5     .05       0
  5376.3     .08       0    5485     .05       0
Bank Sta=5023.6,5029.6
XS Rating Curve= 0 ,0
Exp/Cntr=0.3,0.1

Type RM Length L Ch R = 1 ,7507    ,599,599,599
BEGIN DESCRIPTION:
UNT178 IN CCTC 11.0
END DESCRIPTION:
XS GIS Cut Line= 4
      3575510.17     10661928.19      3575704.62     10662789.32
      3575808.78     10662990.71       3576454.6     10663254.59
#Sta/Elev= 30
  3994.2  347.39  4078.3   344.1    4094  340.91  4098.8  339.47  4109.7  339.02
  4263.6  339.19  4303.8   338.6    4365  334.75  4529.3  322.66  4557.1  321.82
  4562.2  320.37  4600.3  318.81  4642.1  318.07  4745.3  313.53  4946.7  313.17
  4998.8  311.22  5001.6  310.72  5004.8  311.22  5080.6  311.22  5090.5  312.97
  5100.6  316.28  5136.8  316.96  5147.9  318.53    5332  329.97  5374.6  331.72
  5450.3  338.41  5540.4  339.73  5588.4  342.86  5724.7  342.31  5801.4  343.71
#Mann= 6 ,-1 , 0
  3994.2     .05       0    4094      .1       0  4263.6     .08       0
    4365     .05       0  4998.8     .03       0  5004.8     .05       0
Bank Sta=4998.8,5004.8
XS Rating Curve= 0 ,0
Exp/Cntr=0.3,0.1

Type RM Length L Ch R = 1 ,6908    ,35,35,35
BEGIN DESCRIPTION:
UNT178 IN CCTC 10.0
END DESCRIPTION:
XS GIS Cut Line= 6
      3574735.84     10662748.63      3574954.59     10663075.01
      3575138.62     10663154.88      3575430.28     10663172.24
      3575631.67     10663279.88      3575673.19      10663646.6
#Sta/Elev= 30
  4310.7  338.25  4372.8  336.06  4400.6  334.23  4415.6  332.09  4436.6  332.19
  4451.6  330.52  4538.6  324.72  4703.6  317.09  4802.9  311.22  4805.7  310.72
  4808.9  311.22  4910.6  311.22  4915.6  312.08  4925.3  311.22  5002.1  311.22
  5056.1  311.22  5290.9  311.22  5296.2  314.01  5321.9  313.11  5327.2  314.61
  5330.5  313.86  5342.6  313.84  5349.1   315.2  5371.1  314.28  5420.5  315.83
  5449.2  315.46  5519.6  316.93  5670.6  322.95  5680.6   322.6  5797.8  325.85
#Mann= 5 ,-1 , 0
  4310.7     .05       0  4802.9     .03       0  4808.9     .05       0
  5002.1     .07       0  5056.1     .05       0
Bank Sta=4802.9,4808.9
XS Rating Curve= 0 ,0
Exp/Cntr=0.3,0.1

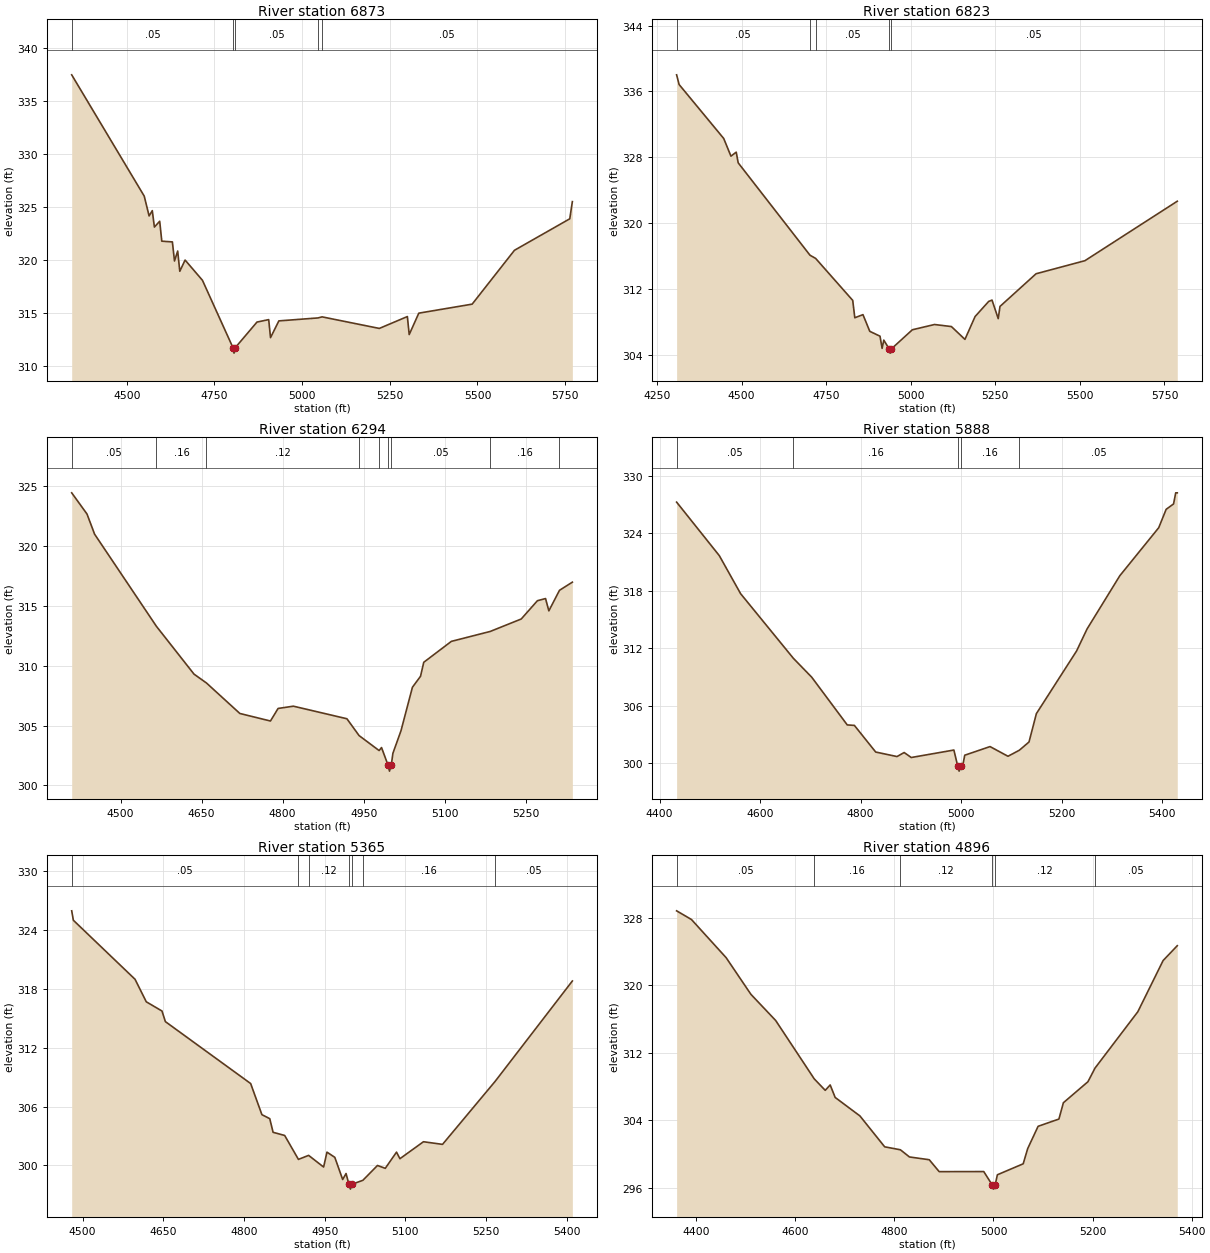
Type RM Length L Ch R = 1 ,6873    ,50,50,50
BEGIN DESCRIPTION:
Mapping XS b4272b27
END DESCRIPTION:
XS GIS Cut Line= 6
      3574735.83     10662797.23      3574975.42     10663130.57
      3575145.56     10663182.65      3575548.34     10663234.74
      3575603.89     10663328.49      3575635.14     10663644.46
#Sta/Elev= 30
    4343  337.43  4549.8  325.99  4563.7  324.12  4572.8  324.62  4578.8  323.07
  4593.9  323.62  4599.9  321.74  4630.1  321.67  4636.1  319.87  4645.2  320.81
  4651.2   318.9  4666.3  319.96  4715.8  318.05    4803  311.68  4805.8  311.18
    4809  311.68  4871.3  314.11  4904.7  314.34  4909.9  312.64  4933.7  314.22
  5045.2   314.5  5056.9   314.6  5220.1  313.51  5300.1  314.63  5305.3  312.93
  5332.7  314.95  5484.8   315.8  5605.4  320.88  5763.1  323.85  5770.5  325.47
#Mann= 5 ,-1 , 0
    4343     .05       0    4803     .03       0    4809     .05       0
  5045.2     .07       0  5056.9     .05       0
Bank Sta=4803,4809
XS Rating Curve= 0 ,0
Exp/Cntr=0.3,0.1

Type RM Length L Ch R = 1 ,6823    ,529,529,529
BEGIN DESCRIPTION:
UNT178 IN CCTC 9.0
END DESCRIPTION:
XS GIS Cut Line= 6
       3574704.6     10662793.78      3574902.51      10663127.1
       3575003.2     10663203.49      3575426.81     10663231.26
      3575548.34     10663265.99       3575603.9     10663672.26
#Sta/Elev= 30
  4308.2  338.01  4315.6  336.83  4447.4  330.27  4468.8  328.12  4484.4  328.61
  4490.2  327.31  4702.3  316.08    4719  315.69  4828.7  310.58  4834.8  308.47
  4858.9  308.85  4879.1  306.82  4909.3  306.23  4915.5  304.75  4920.5  305.75
  4936.5  304.67  4939.3  304.17  4942.5  304.67  5004.9  307.01  5070.3  307.65
  5120.3   307.4  5160.3  305.84  5190.3  308.62  5230.3  310.45  5240.3  310.62
  5258.7  308.36  5263.9  309.85  5370.5  313.82  5514.9  315.41  5787.8  322.64
#Mann= 5 ,-1 , 0
  4308.2     .05       0  4702.3     .16       0    4719     .05       0
  4936.5     .03       0  4942.5     .05       0
Bank Sta=4936.5,4942.5
XS Rating Curve= 0 ,0
Exp/Cntr=0.3,0.1

Type RM Length L Ch R = 1 ,6294    ,406,406,406
BEGIN DESCRIPTION:
UNT178 IN CCTC 8.0
END DESCRIPTION:
XS GIS Cut Line= 3
      3574649.62      10663260.2      3575049.61     10663660.19
       3575249.6     10663960.17
#Sta/Elev= 30
  4409.7  324.47    4438   322.7  4452.1  321.01  4566.4  313.31    4636  309.31
    4659  308.57  4720.8  306.02  4777.4  305.39  4791.5  306.44  4819.8  306.63
  4918.8  305.58  4941.4  304.17  4978.4  302.92  4982.9  303.17  4994.9   301.7
  4997.6   301.2  5000.9   301.7  5003.9  302.69  5018.9  304.58    5040  308.21
    5055  309.13    5061   310.3  5112.1  312.05    5184  312.88  5241.3  313.92
  5271.3  315.45  5286.3  315.63  5292.4   314.6  5312.1  316.32  5335.9     317
#Mann= 9 ,-1 , 0
  4409.7     .05       0  4566.4     .16       0    4659     .12       0
  4941.4     .16       0  4978.4     .05       0  4994.9     .03       0
  5000.9     .05       0    5184     .16       0  5312.1     .05       0
Bank Sta=4994.9,5000.9
XS Rating Curve= 0 ,0
Exp/Cntr=0.3,0.1

Type RM Length L Ch R = 1 ,5888    ,523,523,523
BEGIN DESCRIPTION:
UNT178 IN CCTC 7.0
END DESCRIPTION:
XS GIS Cut Line= 3
      3574349.61     10663510.19      3574749.61     10663910.19
      3574999.61     10664260.18
#Sta/Elev= 30
  4433.9  327.24  4518.8  321.66  4561.2  317.69  4666.1  310.95  4702.6  308.98
  4773.3     304  4787.5  303.95  4829.9  301.17  4872.3   300.7  4886.5  301.12
  4900.6   300.6  4985.4  301.38  4993.1  299.68  4995.8  299.18  4999.1  299.68
  5002.7  299.68    5007  300.84  5057.3  301.74    5093  300.73  5115.6  301.36
  5134.8  302.22  5149.5  305.18  5229.4  311.71  5250.3  314.01  5315.4  319.56
  5392.8  324.57  5407.6  326.49  5422.3  327.05  5426.6  328.21  5429.7  328.21
#Mann= 5 ,-1 , 0
  4433.9     .05       0  4666.1     .16       0  4993.1     .07       0
  4999.1     .16       0  5115.6     .05       0
Bank Sta=4993.1,4999.1
XS Rating Curve= 0 ,0
Exp/Cntr=0.3,0.1

Type RM Length L Ch R = 1 ,5365    ,469,469,469
BEGIN DESCRIPTION:
UNT178 IN CCTC 6.0
END DESCRIPTION:
XS GIS Cut Line= 2
      3574002.05     10663743.43      3574748.53     10664298.94
#Sta/Elev= 30
  4479.9  325.94    4483  324.98  4597.7  318.96  4618.5  316.67  4647.7  315.73
    4654  314.65  4812.5  308.34  4833.4  305.17    4848  304.76  4854.2  303.37
  4875.7  303.05  4901.3  300.61  4920.2  301.02  4948.1  299.83  4954.3  301.35
  4968.9  300.82  4983.5  298.56  4989.8  299.17  4995.1  298.08  4997.9  297.58
  5001.1  298.08  5021.1  298.48  5048.2  299.99  5062.7   299.7  5083.6  301.35
  5089.9  300.68  5133.7  302.41  5169.1  302.14    5267  308.57  5410.4  318.79
#Mann= 7 ,-1 , 0
  4479.9     .05       0  4901.3     .16       0  4920.2     .12       0
  4995.1     .07       0  5001.1     .12       0  5021.1     .16       0
    5267     .05       0
Bank Sta=4995.1,5001.1
XS Rating Curve= 0 ,0
Exp/Cntr=0.3,0.1

Type RM Length L Ch R = 1 ,4896    ,765,765,765
BEGIN DESCRIPTION:
UNT178 IN CCTC 5.0
END DESCRIPTION:
XS GIS Cut Line= 3
      3573649.58     10664460.19      3574299.61     10664460.19
      3574599.62      10664660.2
#Sta/Elev= 30
  4360.4  328.82  4390.4  327.79  4460.4  323.27  4510.4  318.93  4560.4  315.83
  4638.2  308.92  4660.4  307.56  4670.4   308.2  4680.4  306.72  4730.4  304.53
  4780.4  300.87  4812.1  300.52  4830.4  299.67  4870.4  299.34  4890.4  297.93
  4980.4  297.94  4997.4  296.36  5000.2  295.86  5003.4  296.36  5007.9  297.56
    5060  298.86    5069  300.65  5090.1   303.3  5132.1  304.16  5141.1  306.09
  5190.7  308.58  5204.9  310.19  5291.4  316.87  5342.4  322.93    5371  324.69
#Mann= 6 ,-1 , 0
  4360.4     .05       0  4638.2     .16       0  4812.1     .12       0
  4997.4     .07       0  5003.4     .12       0  5204.9     .05       0
Bank Sta=4997.4,5003.4
XS Rating Curve= 0 ,0
Exp/Cntr=0.3,0.1

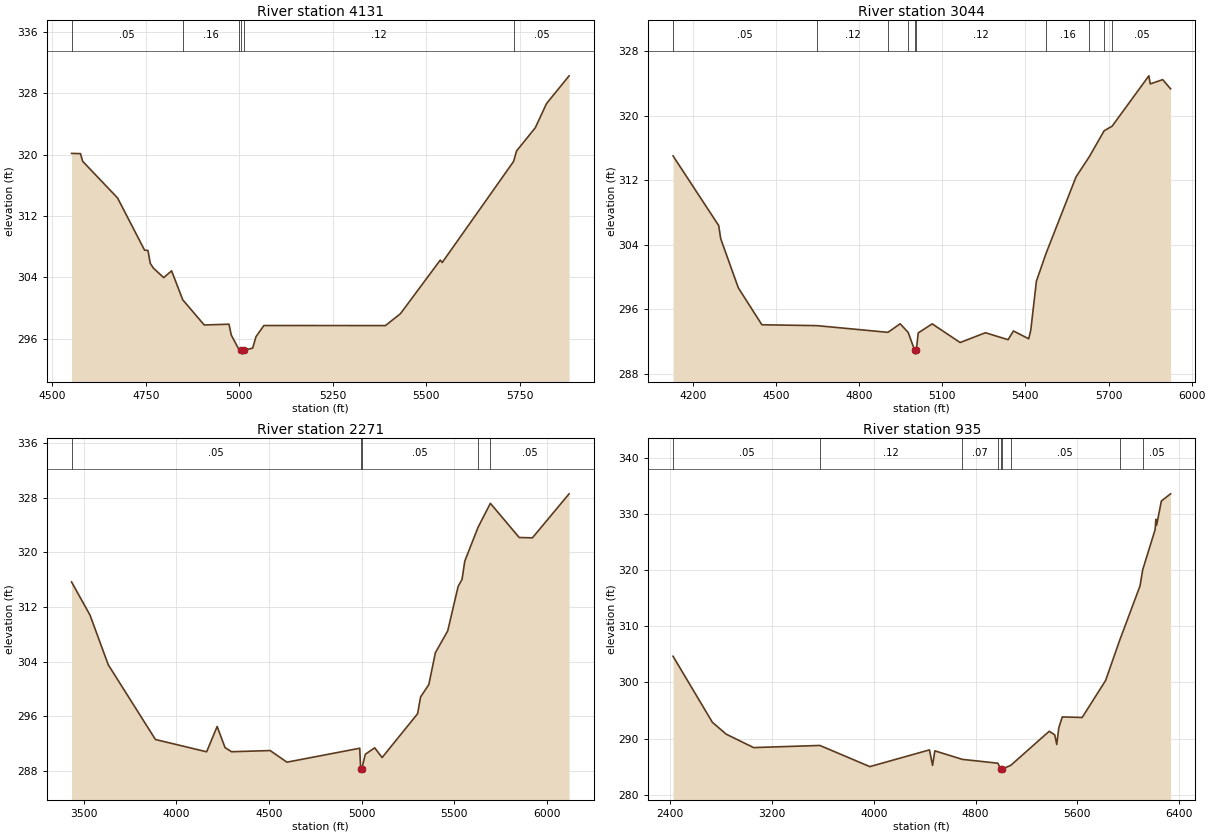
Type RM Length L Ch R = 1 ,4131    ,1087,1087,1087
BEGIN DESCRIPTION:
UNT178 IN CCTC 4.0
END DESCRIPTION:
XS GIS Cut Line= 3
      3573527.19     10664670.48      3574013.33     10664991.68
       3574759.9     10665035.09
#Sta/Elev= 30
  4551.1  320.16  4574.9  320.13  4580.9  319.13  4674.2  314.35  4746.4  307.55
  4755.5  307.51  4761.5  305.85  4769.7  305.22  4797.6  303.97  4818.6  304.86
  4848.5  301.08  4905.9   297.8  4972.2   297.9  4978.2  296.49  4999.3  294.55
  5005.3   294.5  5008.1     294  5011.3   294.5  5035.4  294.78  5044.4  296.28
  5065.5  297.73  5390.5  297.72  5430.6  299.27  5537.2  306.26  5542.3  305.94
  5733.3  319.12  5741.1  320.48  5791.2   323.5  5821.2  326.65  5881.6  330.27
#Mann= 6 ,-1 , 0
  4551.1     .05       0  4848.5     .16       0  4999.3     .12       0
  5005.3     .07       0  5011.3     .12       0  5733.3     .05       0
Bank Sta=5005.3,5011.3
XS Rating Curve= 0 ,0
Exp/Cntr=0.3,0.1

Type RM Length L Ch R = 1 ,3044    ,773,773,773
BEGIN DESCRIPTION:
UNT178 IN CCTC 3.0
END DESCRIPTION:
XS GIS Cut Line= 4
       3573310.2     10665147.92      3573553.26      10665833.7
      3573900.48      10665877.1      3574603.56     10665729.54
#Sta/Elev= 30
    4128  315.02  4292.9  306.38  4300.2  304.74  4363.8  298.66  4448.7  294.09
  4648.2  293.98  4903.7  293.15  4947.9  294.21  4976.7  293.14  5000.1  290.95
  5002.8  290.45  5006.1  290.95  5013.1  293.08  5063.5   294.2  5164.3  291.89
  5255.7   293.1  5337.4  292.24  5356.8  293.32  5411.8  292.35  5419.2   293.4
  5439.6  299.49  5474.5  302.94  5582.7  312.42  5630.8  314.93  5684.1  318.13
  5712.9   318.7  5845.5  324.94  5850.6  323.94  5895.4  324.47  5923.9  323.33
#Mann= 10 ,-1 , 0
    4128     .05       0  4648.2     .12       0  4903.7     .16       0
  4976.7     .12       0  5000.1     .07       0  5006.1     .12       0
  5474.5     .16       0  5630.8     .05       0  5684.1     .16       0
  5712.9     .05       0
Bank Sta=5000.1,5006.1
XS Rating Curve= 0 ,0
Exp/Cntr=0.3,0.1

Type RM Length L Ch R = 1 ,2271    ,1336,1336,1336
BEGIN DESCRIPTION:
UNT178 IN CCTC 2.0
END DESCRIPTION:
XS GIS Cut Line= 4
      3572724.25     10665725.17      3573349.26     10666415.29
      3574377.91      10666545.5      3574963.84     10666128.84
#Sta/Elev= 30
  3434.1  315.68  3533.7  310.83  3632.4  303.54  3887.2  292.59  4163.6  290.79
  4220.4   294.5    4263  291.41  4298.1   290.8  4506.6  290.97  4597.4  289.27
  4990.5  291.31  4995.4  288.31  4998.2  287.81  5001.4  288.31  5020.7  290.43
  5071.1  291.37  5111.4  289.95  5302.9  296.37    5319  298.83  5363.4  300.63
  5399.1  305.32  5465.5   308.5    5522  315.04  5542.9  316.05  5557.7  318.73
  5629.6   323.7    5696   327.2  5851.6  322.19  5922.9  322.14    6121  328.59
#Mann= 5 ,-1 , 0
  3434.1     .05       0  4995.4     .03       0  5001.4     .05       0
  5629.6     .16       0    5696     .05       0
Bank Sta=4995.4,5001.4
XS Rating Curve= 0 ,0
Exp/Cntr=0.3,0.1

Type RM Length L Ch R = 1 ,935     ,0,0,0
BEGIN DESCRIPTION:
UNT178 IN CCTC 1.0
END DESCRIPTION:
XS GIS Cut Line= 4
      3572672.17     10666037.67      3573336.24     10667222.58
      3574703.43     10667548.11      3575705.28     10666988.63
#Sta/Elev= 30
  2422.3  304.65  2731.5   292.9    2840  290.78  3055.7  288.39  3576.6  288.77
  3969.4     285  4438.1  287.98  4462.5  285.22  4480.3  287.81  4697.1  286.29
    4976  285.61  4998.5  284.52  5001.2  284.02  5004.5  284.52  5076.8  285.22
  5379.3  291.29  5422.8  290.67  5438.7  288.95  5454.7   291.9  5482.2  293.85
  5638.6  293.75  5822.6  300.33  5934.2  307.54  6093.3  317.17  6114.7  320.08
  6212.1   327.2  6217.8  329.04  6223.9     328  6261.3   332.3  6333.5  333.57
#Mann= 9 ,-1 , 0
  2422.3     .05       0  3576.6     .12       0  4697.1     .07       0
    4976     .12       0  4998.5     .07       0  5004.5     .12       0
  5076.8     .05       0  5934.2     .16       0  6114.7     .05       0
Bank Sta=4998.5,5004.5
XS Rating Curve= 0 ,0
Exp/Cntr=0.3,0.1

Chan Stop Cuts=-1
Use User Specified Reach Order=0
Composite Channel Slope=5