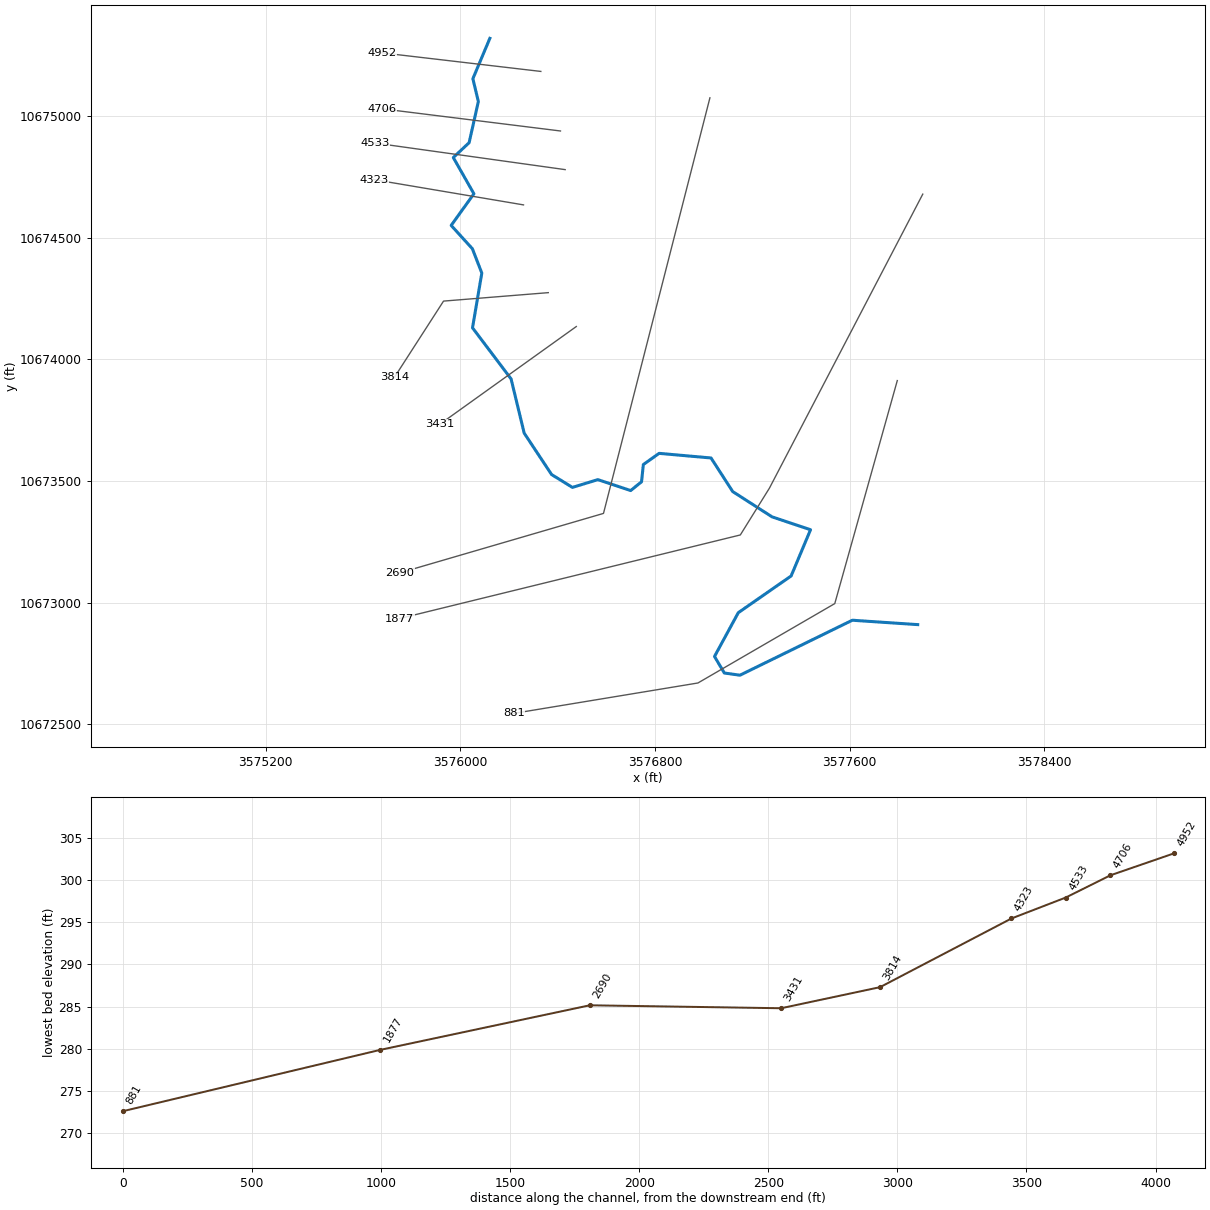
--- UNT179 IN CCTC.prj (project) ---

Proj Title=UNT179 IN CCTC Base Level Engineering
Current Plan=p01
Default Exp/Contr=0.3,0.1
English Units
Geom File=g01
Flow File=f01
Plan File=p01
BEGIN DESCRIPTION:
UNT179 IN CCTC
END DESCRIPTION:

--- UNT179 IN CCTC.p01 (plan) ---

Plan Title=Multiple Run
Short Identifier=Multiple
Geom File=g01
Flow File=f01
Subcritical Flow
K Sum by GR= 0
Std Step Tol= 0.01
Critical Tol= 0.01
Num of Std Step Trials= 20
Max Error Tol= 0.3
Flow Tol Ratio= 0.001
Split Flow NTrial= 30
Split Flow Tol= 0.02
Split Flow Ratio= 0.02
Log Output Level= 0
Friction Slope Method= 1
Unsteady Friction Slope Method= 2
Unsteady Bridges Friction Slope Method= 1
Parabolic Critical Depth
Global Vel Dist=  1 , 1 , 1
Global Log Level= 0
CheckData=True
Encroach Param= -1, 0, 0, 0
BEGIN DESCRIPTION:
Multiple Run
END DESCRIPTION:

--- UNT179 IN CCTC.f01 (steady flow) ---

Flow Title=Multiple
Number of Profiles=7
Profile Names=10-year,25-year,50-year,1pct_min,100-year,1pct_plu,500-year
River Rch & RM= UNT179 IN CCTC,Reach-1,4952
    1052    1428    1735    1540    2083    2817    2992
Boundary for River Rch & Prof#=UNT179 IN CCTC,Reach-1,1
Up Type=0
Dn Type=3
Dn Slope=0.005
Boundary for River Rch & Prof#=UNT179 IN CCTC,Reach-1,2
Up Type=0
Dn Type=3
Dn Slope=0.005
Boundary for River Rch & Prof#=UNT179 IN CCTC,Reach-1,3
Up Type=0
Dn Type=3
Dn Slope=0.005
Boundary for River Rch & Prof#=UNT179 IN CCTC,Reach-1,4
Up Type=0
Dn Type=3
Dn Slope=0.005
Boundary for River Rch & Prof#=UNT179 IN CCTC,Reach-1,5
Up Type=0
Dn Type=3
Dn Slope=0.005
Boundary for River Rch & Prof#=UNT179 IN CCTC,Reach-1,6
Up Type=0
Dn Type=3
Dn Slope=0.005
Boundary for River Rch & Prof#=UNT179 IN CCTC,Reach-1,7
Up Type=0
Dn Type=3
Dn Slope=0.005

--- UNT179 IN CCTC.g01 (geometry) ---

Geom Title=Existing Conditions

River Reach=UNT179 IN CCTC,Reach-1
Reach XY= 30
      3576120.75     10675320.00      3576051.00     10675154.00
      3576073.50     10675060.00      3576035.50     10674891.00
      3575970.50     10674830.00      3576055.25     10674681.00
      3575961.75     10674551.00      3576049.00     10674455.00
      3576087.75     10674355.00      3576049.50     10674130.00
      3576208.00     10673920.00      3576262.00     10673697.00
      3576374.50     10673527.00      3576460.25     10673474.00
      3576564.50     10673506.00      3576699.50     10673461.00
      3576744.25     10673497.00      3576751.75     10673568.00
      3576816.50     10673614.00      3577030.00     10673595.00
      3577119.00     10673457.00      3577280.75     10673353.00
      3577439.00     10673300.00      3577359.25     10673110.00
      3577142.00     10672959.00      3577044.25     10672779.00
      3577084.75     10672711.00      3577148.75     10672702.00
      3577610.75     10672928.00      3577879.50     10672910.00

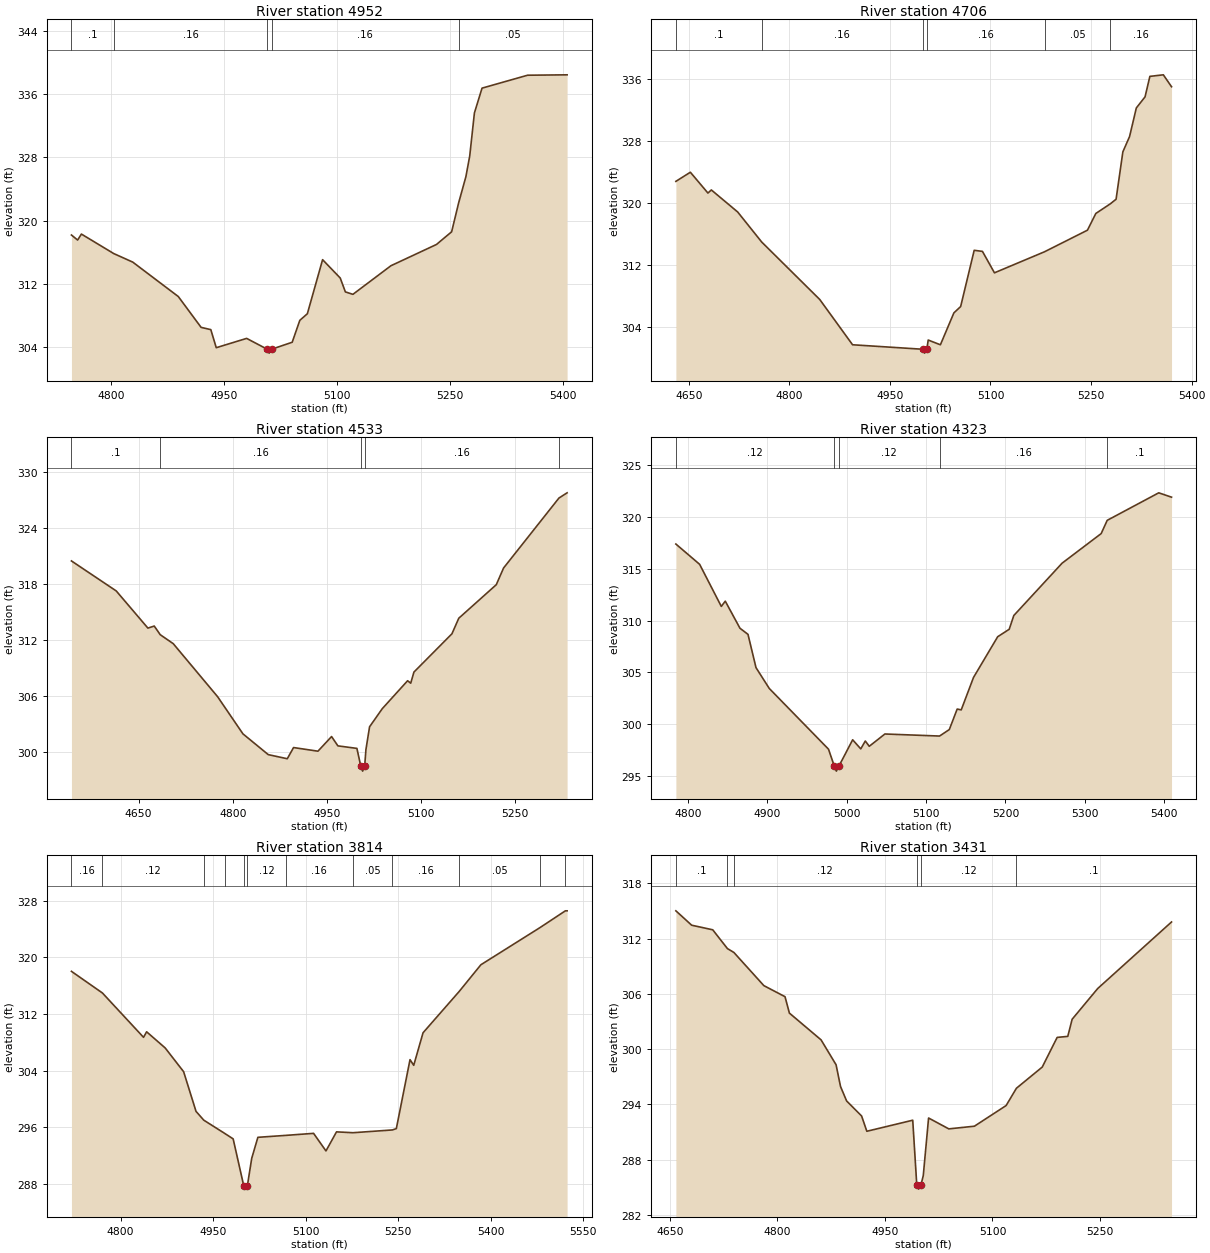
Type RM Length L Ch R = 1,4952,246,246,246
BEGIN DESCRIPTION:
UNT179 IN CCTC 7.0
END DESCRIPTION:
XS GIS Cut Line= 2
      3576330.33     10675183.96      3575677.58     10675260.34
#Sta/Elev= 30
  4747.8  318.16  4756.0  317.52  4761.0  318.28  4803.8  315.81  4829.1  314.72
  4889.5  310.35  4919.7  306.44  4932.6  306.15  4939.8  303.86  4980.1  305.04
  5007.3  303.67  5010.0  303.17  5013.3  303.67  5040.5  304.55  5050.6  307.33
  5060.6  308.17  5080.8  315.03  5104.2  312.70  5111.0  310.94  5121.0  310.63
  5171.4  314.26  5231.8  316.96  5251.9  318.57  5261.3  322.28  5270.8  325.56
  5275.9  328.20  5282.1  333.65  5292.2  336.80  5352.6  338.44  5405.0  338.49
#Mann=5,-1,0
  4747.8     0.1       0  4803.8    0.16       0  5007.3    0.07       0
  5013.3    0.16       0  5261.3    0.05       0
Bank Sta=5007.3,5013.3
Exp/Cntr=0.3,0.1

Type RM Length L Ch R = 1,4706,173,173,173
BEGIN DESCRIPTION:
Mapping XS d86325b6
END DESCRIPTION:
XS GIS Cut Line= 2
      3576411.08     10674939.16      3575677.52     10675030.32
#Sta/Elev= 30
  4630.8  322.77  4652.4  323.95  4678.6  321.26  4683.7  321.66  4723.0  318.81
  4758.9  314.92  4845.4  307.50  4894.3  301.65  4999.1  301.07  5001.8  300.57
  5005.1  301.07  5007.1  302.26  5025.3  301.65  5045.4  305.77  5055.5  306.59
  5075.7  313.86  5088.0  313.72  5105.9  310.95  5180.6  313.67  5244.6  316.46
  5257.1  318.62  5278.6  319.86  5287.3  320.46  5297.4  326.58  5307.4  328.56
  5317.5  332.26  5330.5  333.69  5337.7  336.34  5357.8  336.54  5370.0  335.00
#Mann=6,-1,0
  4630.8     0.1       0  4758.9    0.16       0  4999.1    0.07       0
  5005.1    0.16       0  5180.6    0.05       0  5278.6    0.16       0
Bank Sta=4999.1,5005.1
Exp/Cntr=0.3,0.1

Type RM Length L Ch R = 1,4533,210,210,210
BEGIN DESCRIPTION:
Mapping XS 4b558a4a
END DESCRIPTION:
XS GIS Cut Line= 2
      3576430.35     10674780.31      3575647.76     10674889.69
#Sta/Elev= 30
  4542.9  320.49  4614.3  317.27  4664.8  313.28  4674.9  313.50  4684.5  312.57
  4705.2  311.61  4775.9  305.92  4816.3  301.93  4856.7  299.70  4887.0  299.26
  4897.0  300.46  4935.9  300.07  4957.6  301.64  4967.7  300.64  4998.0  300.37
  5004.3  298.43  5007.1  297.93  5010.3  298.43  5012.4  300.25  5018.2  302.69
  5038.4  304.63  5078.8  307.63  5083.8  307.37  5088.9  308.56  5149.5  312.67
  5160.4  314.34  5220.2  317.94  5231.8  319.73  5320.1  327.24  5333.1  327.80
#Mann=5,-1,0
  4542.9     0.1       0  4684.5    0.16       0  5004.3    0.07       0
  5010.3    0.16       0  5320.1     0.1       0
Bank Sta=5004.3,5010.3
Exp/Cntr=0.3,0.1

Type RM Length L Ch R = 1,4323,509,509,509
BEGIN DESCRIPTION:
UNT179 IN CCTC 6.0
END DESCRIPTION:
XS GIS Cut Line= 2
      3576259.13     10674635.35      3575643.76     10674739.36
#Sta/Elev= 30
  4785.0  317.40  4814.9  315.44  4842.2  311.37  4847.2  311.88  4865.7  309.26
  4875.8  308.67  4885.9  305.45  4902.6  303.44  4977.2  297.57  4984.4  295.95
  4987.1  295.45  4990.4  295.95  5007.6  298.48  5017.8  297.60  5023.5  298.36
  5028.5  297.85  5048.2  299.04  5117.0  298.84  5129.3  299.47  5139.2  301.45
  5144.3  301.37  5159.8  304.51  5190.2  308.44  5204.7  309.16  5210.5  310.49
  5271.3  315.55  5320.5  318.41  5328.1  319.69  5393.0  322.35  5409.1  321.93
#Mann=5,-1,0
  4785.0    0.12       0  4984.4    0.07       0  4990.4    0.12       0
  5117.0    0.16       0  5328.1     0.1       0
Bank Sta=4984.4,4990.4
Exp/Cntr=0.3,0.1

Type RM Length L Ch R = 1,3814,383,383,383
BEGIN DESCRIPTION:
UNT179 IN CCTC 5.0
END DESCRIPTION:
XS GIS Cut Line= 3
      3576360.97     10674274.60      3575930.42     10674239.88
      3575729.04     10673927.39
#Sta/Elev= 30
  4720.3  318.03  4770.5  314.98  4837.2  308.72  4842.2  309.50  4872.2  307.23
  4902.2  303.87  4922.3  298.27  4934.9  297.03  4968.5  295.18  4982.5  294.39
  4999.6  287.80  5002.3  287.30  5005.6  287.80  5012.6  291.64  5022.6  294.61
  5067.4  294.88  5112.9  295.17  5133.0  292.69  5150.1  295.38  5176.9  295.26
  5240.7  295.65  5247.1  295.84  5269.3  305.57  5275.3  304.77  5290.4  309.36
  5349.0  315.19  5384.2  318.96  5480.0  324.20  5521.2  326.57  5524.0  326.57
#Mann=12,-1,0
  4720.3    0.16       0  4770.5    0.12       0  4934.9    0.07       0
  4968.5    0.12       0  4999.6    0.07       0  5005.6    0.12       0
  5067.4    0.16       0  5176.9    0.05       0  5240.7    0.16       0
  5349.0    0.05       0  5480.0     0.1       0  5521.2    0.05       0
Bank Sta=4999.6,5005.6
Exp/Cntr=0.3,0.1

Type RM Length L Ch R = 1,3431,741,741,741
BEGIN DESCRIPTION:
UNT179 IN CCTC 4.0
END DESCRIPTION:
XS GIS Cut Line= 2
      3576476.14     10674135.33      3575914.16     10673732.92
#Sta/Elev= 30
  4658.5  315.01  4680.5  313.45  4709.9  312.95  4730.4  310.91  4739.4  310.49
  4781.2  306.89  4810.7  305.69  4816.8  303.91  4861.0  301.00  4881.9  298.30
  4888.1  295.94  4896.6  294.37  4917.5  292.74  4924.8  291.08  4988.8  292.28
  4994.4  285.30  4997.1  284.80  5000.4  285.30  5003.5  286.27  5010.9  292.52
  5039.1  291.34  5074.8  291.63  5119.0  293.87  5133.4  295.75  5169.4  298.05
  5190.2  301.27  5205.0  301.38  5211.1  303.24  5246.8  306.58  5349.7  313.80
#Mann=6,-1,0
  4658.5     0.1       0  4730.4    0.16       0  4739.4    0.12       0
  4994.4    0.07       0  5000.4    0.12       0  5133.4     0.1       0
Bank Sta=4994.4,5000.4
Exp/Cntr=0.3,0.1

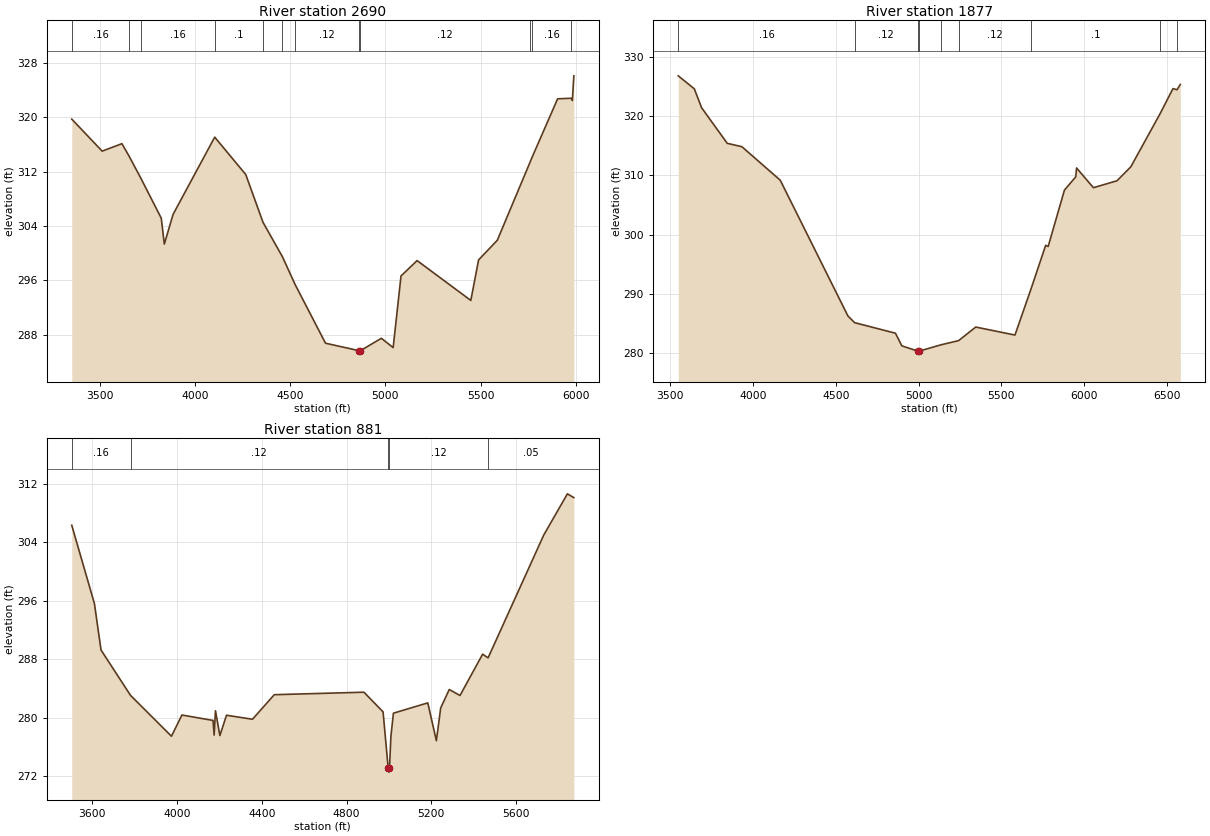
Type RM Length L Ch R = 1,2690,813,813,813
BEGIN DESCRIPTION:
UNT179 IN CCTC 3.0
END DESCRIPTION:
XS GIS Cut Line= 3
      3577025.39     10675075.45      3576587.89     10673367.12
      3575749.36     10673122.33
#Sta/Elev= 30
  3353.1  319.72  3512.8  315.01  3616.6  316.11  3653.6  314.30  3716.7  310.99
  3823.1  305.15  3839.2  301.34  3885.2  305.71  4103.9  317.07  4266.9  311.57
  4357.4  304.55  4459.6  299.47  4526.0  295.40  4685.7  286.76  4862.7  285.65
  4865.4  285.15  4868.7  285.65  4979.2  287.48  5041.1  286.11  5082.4  296.65
  5166.9  298.91  5449.0  293.05  5489.8  299.01  5588.1  301.90  5758.6  313.28
  5772.9  314.24  5904.9  322.71  5976.8  322.79  5982.3  322.46  5990.1  326.09
#Mann=12,-1,0
  3353.1    0.16       0  3653.6     0.1       0  3716.7    0.16       0
  4103.9     0.1       0  4357.4    0.12       0  4459.6    0.16       0
  4526.0    0.12       0  4862.7    0.07       0  4868.7    0.12       0
  5758.6     0.1       0  5772.9    0.16       0  5976.8    0.05       0
Bank Sta=4862.7,4868.7
Exp/Cntr=0.3,0.1

Type RM Length L Ch R = 1,1877,996,996,996
BEGIN DESCRIPTION:
UNT179 IN CCTC 2.0
END DESCRIPTION:
XS GIS Cut Line= 4
      3577900.37     10674679.58      3577270.18     10673471.29
      3577150.39     10673278.58      3575750.08     10672935.01
#Sta/Elev= 30
  3548.8  326.82  3645.9  324.63  3690.0  321.43  3844.7  315.43  3933.0  314.86
  4164.8  309.20  4573.2  286.30  4613.9  285.16  4860.4  283.38  4898.9  281.25
  4996.5  280.35  4999.3  279.85  5002.5  280.35  5136.6  281.43  5241.8  282.13
  5345.2  284.42  5582.0  283.07  5679.4  290.89  5767.4  298.21  5782.5  298.02
  5880.6  307.53  5948.8  309.77  5953.9  311.27  6055.7  307.94  6198.3  309.11
  6281.4  311.46  6459.4  320.49  6536.0  324.66  6560.3  324.47  6580.3  325.36
#Mann=9,-1,0
  3548.8    0.16       0  4613.9    0.12       0  4996.5    0.07       0
  5002.5    0.12       0  5136.6    0.07       0  5241.8    0.12       0
  5679.4     0.1       0  6459.4    0.05       0  6560.3    0.16       0
Bank Sta=4996.5,5002.5
Exp/Cntr=0.3,0.1

Type RM Length L Ch R = 1,881,0,0,0
BEGIN DESCRIPTION:
UNT179 IN CCTC 1.0
END DESCRIPTION:
XS GIS Cut Line= 4
      3577795.62     10673913.16      3577538.66     10672996.46
      3576976.16     10672670.07      3576219.58     10672545.13
#Sta/Elev= 30
  3503.6  306.34  3610.5  295.63  3641.7  289.28  3780.8  283.08  3974.0  277.49
  4023.4  280.39  4170.2  279.65  4175.4  277.65  4181.7  280.97  4202.5  277.58
  4233.7  280.36  4356.3  279.81  4459.2  283.17  4882.3  283.51  4972.6  280.82
  4996.9  273.08  4999.7  272.58  5002.9  273.08  5009.5  277.46  5021.4  280.64
  5183.6  282.05  5224.1  276.88  5244.4  281.35  5284.9  283.88  5335.6  283.06
  5442.4  288.71  5468.2  288.21  5730.9  305.01  5842.4  310.64  5872.8  310.12
#Mann=5,-1,0
  3503.6    0.16       0  3780.8    0.12       0  4996.9    0.07       0
  5002.9    0.12       0  5468.2    0.05       0
Bank Sta=4996.9,5002.9
Exp/Cntr=0.3,0.1

Chan Stop Cuts=-1