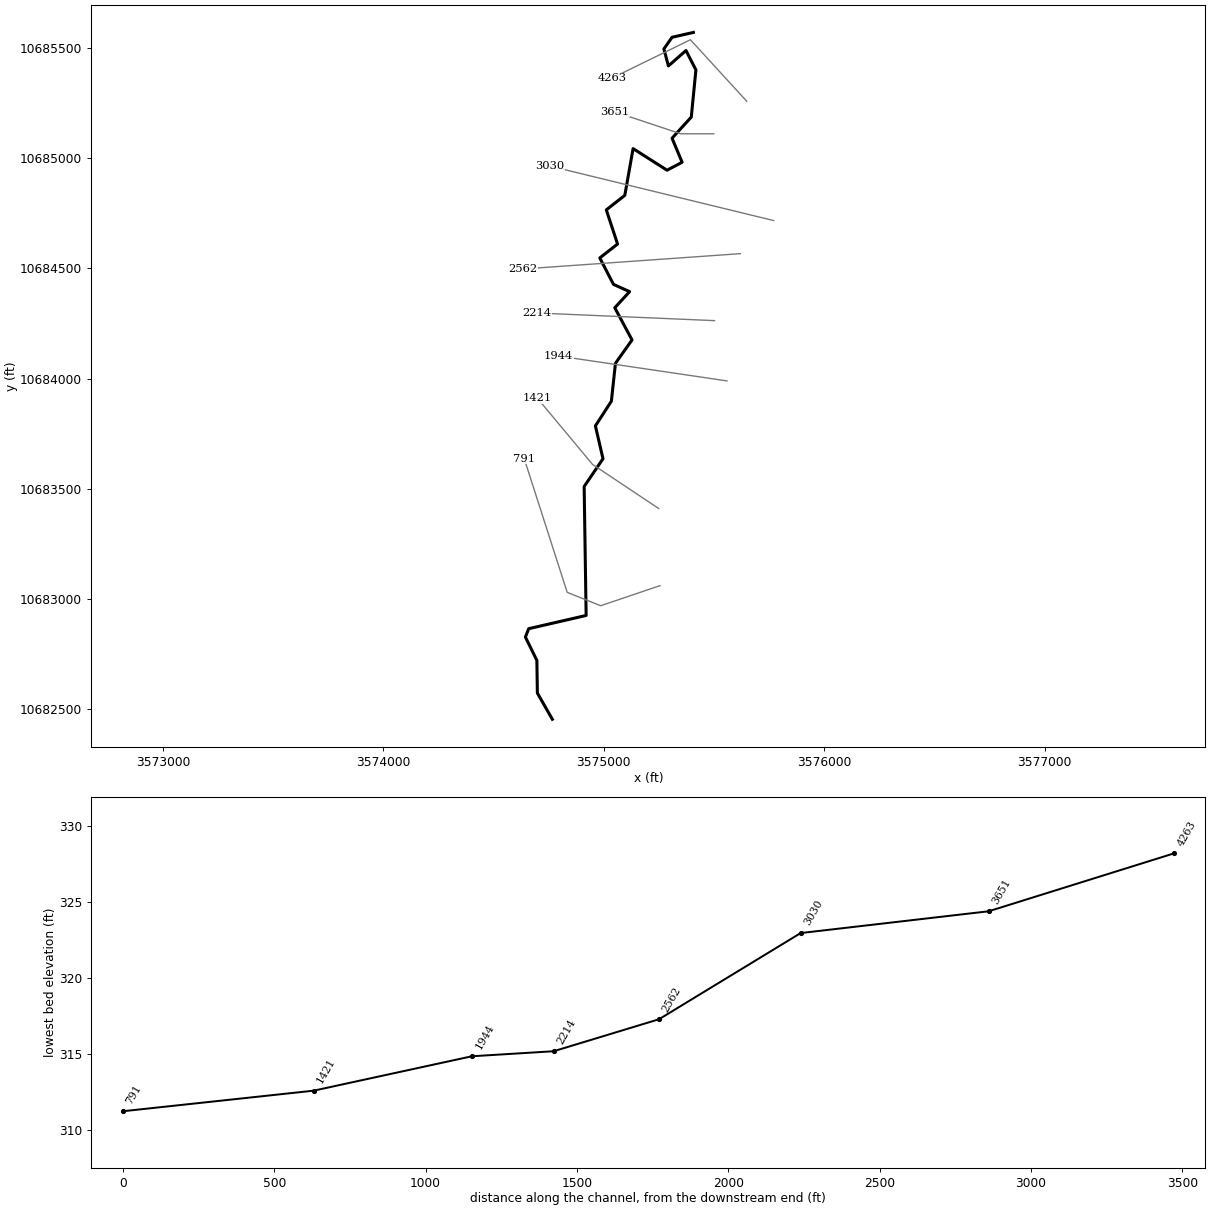
--- UNT181 IN CCTC.prj (project) ---

Proj Title=UNT181 IN CCTC Base Level Engineering
Current Plan=p01
Default Exp/Contr=0.3,0.1
English Units
Geom File=g01
Flow File=f01
Plan File=p01
Y Axis Title=Elevation
X Axis Title(PF)=Main Channel Distance
X Axis Title(XS)=Station
BEGIN DESCRIPTION:
UNT181 IN CCTC
END DESCRIPTION:
DSS Export Rating Curves= 0
DSS Export Rating Curve Sorted= 0
DSS Export Volume Flow Curves= 0
DXF OffsetX= 0
DXF OffsetY= 0
DXF ScaleX= 1
DXF ScaleY= 10

--- UNT181 IN CCTC.p01 (plan) ---

Plan Title=Multiple Run
Short Identifier=Multiple
Geom File=g01
Flow File=f01
Subcritical Flow
K Sum by GR= 0
Std Step Tol= 0.01
Critical Tol= 0.01
Num of Std Step Trials= 20
Max Error Tol= 0.3
Flow Tol Ratio= 0.001
Split Flow NTrial= 30
Split Flow Tol= 0.02
Split Flow Ratio= 0.02
Log Output Level= 0
Friction Slope Method= 1
Unsteady Friction Slope Method= 2
Unsteady Bridges Friction Slope Method= 1
Parabolic Critical Depth
Global Vel Dist=  1 , 1 , 1
Global Log Level= 0
CheckData=True
Encroach Param= -1, 0, 0, 0
BEGIN DESCRIPTION:
Multiple Run
END DESCRIPTION:

--- UNT181 IN CCTC.f01 (steady flow) ---

Flow Title=Multiple
Number of Profiles=7
Profile Names=10-year,25-year,50-year,1pct_min,100-year,1pct_plu,500-year
River Rch & RM= UNT181 IN CCTC,Reach-1,4263
     887    1184    1422    1247    1687    2281    2366
Boundary for River Rch & Prof#=UNT181 IN CCTC,Reach-1,1
Up Type=0
Dn Type=3
Dn Slope=0.005
Boundary for River Rch & Prof#=UNT181 IN CCTC,Reach-1,2
Up Type=0
Dn Type=3
Dn Slope=0.005
Boundary for River Rch & Prof#=UNT181 IN CCTC,Reach-1,3
Up Type=0
Dn Type=3
Dn Slope=0.005
Boundary for River Rch & Prof#=UNT181 IN CCTC,Reach-1,4
Up Type=0
Dn Type=3
Dn Slope=0.005
Boundary for River Rch & Prof#=UNT181 IN CCTC,Reach-1,5
Up Type=0
Dn Type=3
Dn Slope=0.005
Boundary for River Rch & Prof#=UNT181 IN CCTC,Reach-1,6
Up Type=0
Dn Type=3
Dn Slope=0.005
Boundary for River Rch & Prof#=UNT181 IN CCTC,Reach-1,7
Up Type=0
Dn Type=3
Dn Slope=0.005

--- UNT181 IN CCTC.g01 (geometry) ---

Geom Title=Existing Conditions
Program Version=4.10

River Reach=UNT181 IN CCTC  ,Reach-1
Reach XY= 30
      3575407.02       10685570.      3575310.25       10685548.
      3575273.25       10685495.      3575293.75       10685418.
       3575373.5       10685488.       3575418.5       10685400.
       3575397.5       10685186.      3575310.25       10685090.
        3575356.       10684981.       3575287.5       10684945.
       3575133.5       10685043.        3575096.       10684831.
        3575012.       10684765.        3575063.       10684610.
       3574982.5       10684547.       3575044.5       10684427.
      3575117.75       10684394.       3575050.5       10684321.
      3575128.75       10684175.       3575053.5       10684069.
        3575035.       10683897.       3574962.5       10683785.
        3574997.       10683636.       3574911.5       10683510.
       3574920.5       10682925.        3574660.       10682865.
        3574645.       10682827.        3574697.       10682721.
      3574699.25       10682573.      3574767.25       10682454.

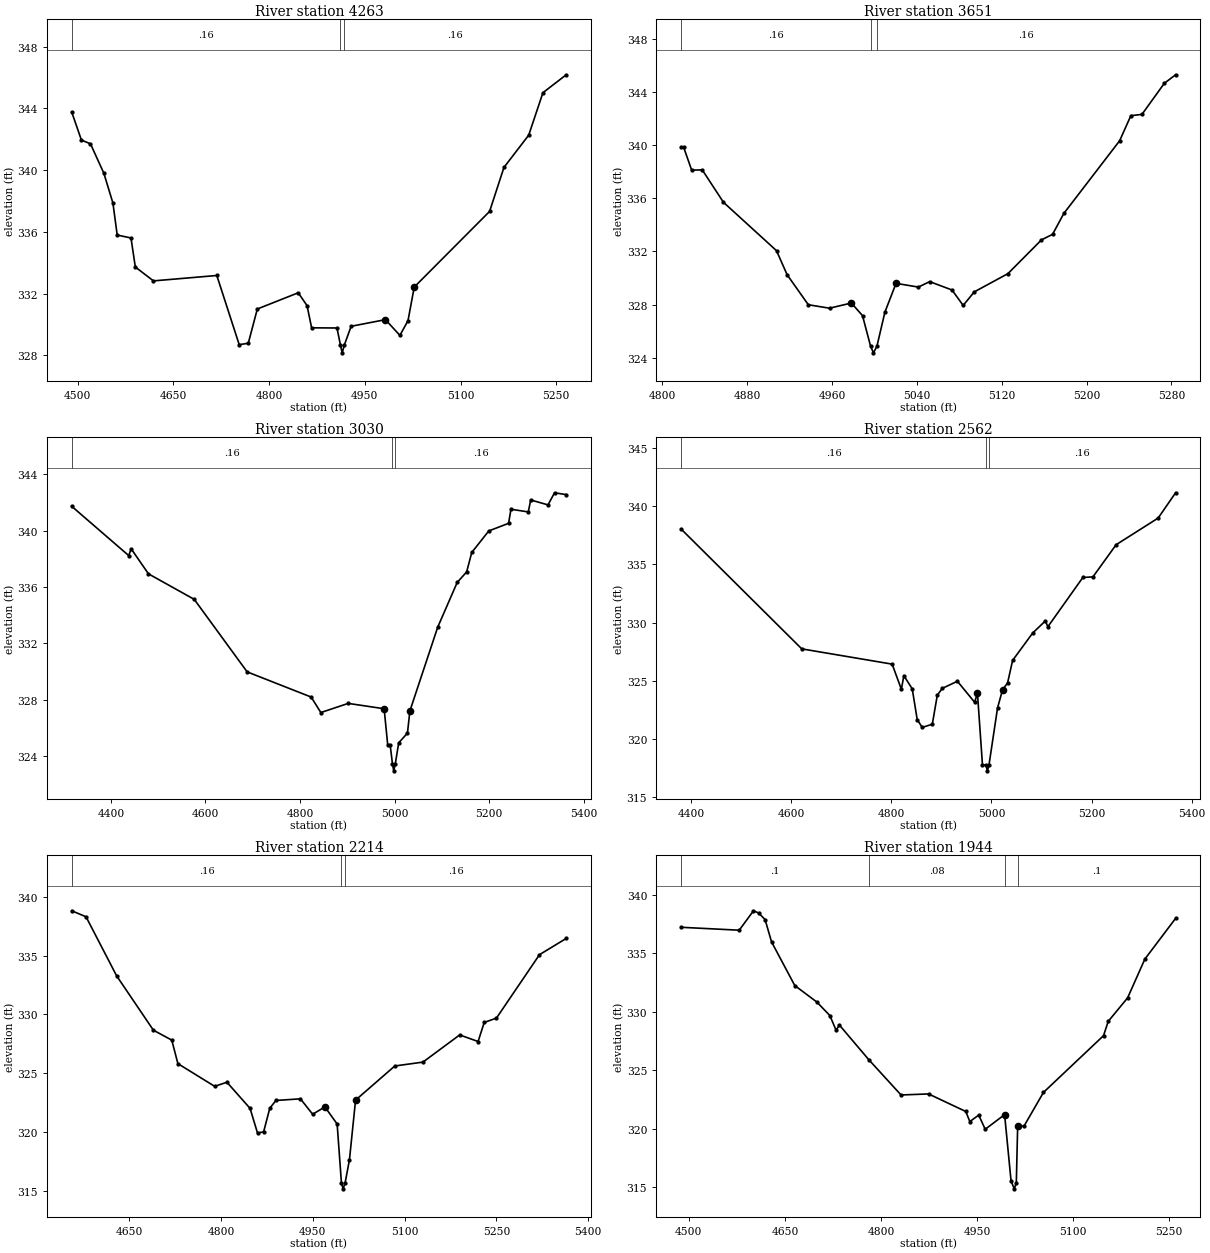
Type RM Length L Ch R = 1 ,4263    ,612,612,612
BEGIN DESCRIPTION:
UNT181 IN CCTC 7.0
END DESCRIPTION:
XS GIS Cut Line= 3
      3575648.79     10685258.21      3575393.59     10685536.85
      3575036.82     10685362.37
#Sta/Elev= 30
  4490.7  343.77  4505.9  341.95  4520.1  341.71  4541.1   339.8  4555.3  337.87
    4562   335.8  4583.6  335.61  4590.4  333.73  4618.8  332.83  4718.1  333.18
  4753.2   328.7  4767.4  328.79  4781.6  331.01  4845.7  332.06  4859.5  331.23
  4866.7  329.79  4906.4  329.78  4911.9  328.67  4914.6  328.17  4917.9  328.67
  4928.6  329.89  4982.4  330.32    5005   329.3  5017.7  330.25  5027.5  332.43
  5145.6  337.33  5168.1  340.18  5206.9  342.27  5229.2  345.02  5265.7  346.18
#Mann= 3 ,-1 , 0
  4490.7     .16       0  4911.9     .07       0  4917.9     .16       0
Bank Sta=4982.4,5027.5
XS Rating Curve= 0 ,0
Exp/Cntr=0.3,0.1

Type RM Length L Ch R = 1 ,3651    ,621,621,621
BEGIN DESCRIPTION:
UNT181 IN CCTC 6.0
END DESCRIPTION:
XS GIS Cut Line= 3
      3575499.65     10685110.19      3575349.61     10685110.19
      3575049.58      10685210.2
#Sta/Elev= 30
  4817.6  339.83  4820.1  339.83  4827.6  338.12  4837.6  338.14  4857.6   335.7
  4907.6  332.06  4917.6  330.25  4937.6  327.99  4957.6  327.73  4978.2  328.12
  4988.7  327.17  4996.3  324.87    4999  324.37  5002.3  324.87  5009.8  327.43
  5020.3   329.6  5041.4  329.32    5052  329.73  5073.1   329.1  5083.6  327.94
  5094.1  328.96  5125.8  330.33  5157.4  332.87  5167.9  333.29  5178.5  334.86
  5231.2  340.34  5241.7  342.22  5252.2  342.32  5273.3  344.66  5283.9   345.3
#Mann= 3 ,-1 , 0
  4817.6     .16       0  4996.3     .07       0  5002.3     .16       0
Bank Sta=4978.2,5020.3
XS Rating Curve= 0 ,0
Exp/Cntr=0.3,0.1

Type RM Length L Ch R = 1 ,3030    ,468,468,468
BEGIN DESCRIPTION:
Mapping XS ac87602d
END DESCRIPTION:
XS GIS Cut Line= 2
      3575771.21     10684716.53      3574755.61     10684963.92
#Sta/Elev= 30
  4317.3  341.73  4437.8  338.23    4443  338.71  4479.6  336.93  4576.3  335.12
  4688.1  329.97  4823.5  328.18  4843.9  327.08  4901.8  327.73  4977.7  327.35
  4985.2   324.8  4990.4  324.78  4995.3  323.44    4998  322.94  5001.3  323.44
  5008.5  324.93    5027  325.62  5032.1  327.19  5090.9  333.14  5132.1  336.32
  5152.1  337.07  5162.9  338.45  5198.9  339.98  5240.7  340.52  5245.8  341.52
  5282.4  341.33  5287.5  342.18  5324.1  341.83  5337.9  342.69  5362.6  342.56
#Mann= 3 ,-1 , 0
  4317.3     .16       0  4995.3     .07       0  5001.3     .16       0
Bank Sta=4977.7,5032.1
XS Rating Curve= 0 ,0
Exp/Cntr=0.3,0.1

Type RM Length L Ch R = 1 ,2562    ,348,348,348
BEGIN DESCRIPTION:
UNT181 IN CCTC 5.0
END DESCRIPTION:
XS GIS Cut Line= 2
      3575620.14     10684566.36      3574634.88     10684496.92
#Sta/Elev= 30
  4380.1  338.04  4621.2  327.75  4801.7  326.44  4820.1  324.28  4825.1  325.45
  4841.8  324.32  4851.8  321.67  4861.8  321.01  4881.9  321.28  4891.9  323.78
  4901.9  324.36    4932  324.97  4966.4  323.17  4972.1  323.93  4982.1  317.79
  4989.1  317.78  4991.9  317.28  4995.1  317.78  5012.2  322.68  5022.2  324.24
  5032.2  324.82  5042.3  326.76  5082.4  329.11  5107.7  330.15  5112.7  329.65
  5182.6  333.88  5202.7  333.93    5249  336.69    5333  338.98  5367.8  341.15
#Mann= 3 ,-1 , 0
  4380.1     .16       0  4989.1     .07       0  4995.1     .16       0
Bank Sta=4972.1,5022.2
XS Rating Curve= 0 ,0
Exp/Cntr=0.3,0.1

Type RM Length L Ch R = 1 ,2214    ,270,270,270
BEGIN DESCRIPTION:
UNT181 IN CCTC 4.0
END DESCRIPTION:
XS GIS Cut Line= 2
      3575502.95     10684262.55      3574695.69     10684297.27
#Sta/Elev= 30
  4556.2  338.81  4579.6   338.3  4629.6  333.28  4689.7  328.66  4719.7  327.82
  4729.7  325.82  4789.8  323.89  4809.8  324.24  4847.6  322.02  4859.8  319.92
  4869.8  320.03  4879.8  322.02  4889.8  322.69  4929.9  322.83  4949.9  321.52
  4969.9  322.14  4989.9  320.69  4996.9  315.68  4999.7  315.18  5002.9  315.68
    5010  317.65    5020  322.72  5084.1  325.62  5130.1  325.95  5190.1  328.26
  5220.2   327.7  5230.2  329.32  5250.2  329.69  5320.5  335.08  5364.2  336.46
#Mann= 3 ,-1 , 0
  4556.2     .16       0  4996.9     .07       0  5002.9     .16       0
Bank Sta=4969.9,5020
XS Rating Curve= 0 ,0
Exp/Cntr=0.3,0.1

Type RM Length L Ch R = 1 ,1944    ,523,523,523
BEGIN DESCRIPTION:
UNT181 IN CCTC 3.0
END DESCRIPTION:
XS GIS Cut Line= 2
      3575559.41      10683989.1       3574795.5     10684101.95
#Sta/Elev= 30
  4487.8   337.2  4578.6  336.95  4600.9  338.61  4608.9  338.42    4619  337.86
  4629.1  335.95  4665.4  332.22  4699.9  330.81  4720.1  329.66  4729.9   328.4
    4735  328.85  4780.7   325.9  4831.3  322.87  4874.2  322.96  4932.4  321.46
  4938.7   320.6  4952.6  321.15  4962.7  319.94    4993  321.19  5003.1  315.52
  5008.1  314.85  5011.3  315.35  5013.4  320.21  5023.4  320.22  5053.7  323.09
  5147.5  327.94  5154.8  329.16  5185.1  331.17    5212  334.48    5260  337.96
#Mann= 4 ,-1 , 0
  4487.8      .1       0  4780.7     .08       0    4993     .05       0
  5013.4      .1       0
Bank Sta=4993,5013.4
XS Rating Curve= 0 ,0
Exp/Cntr=0.3,0.1

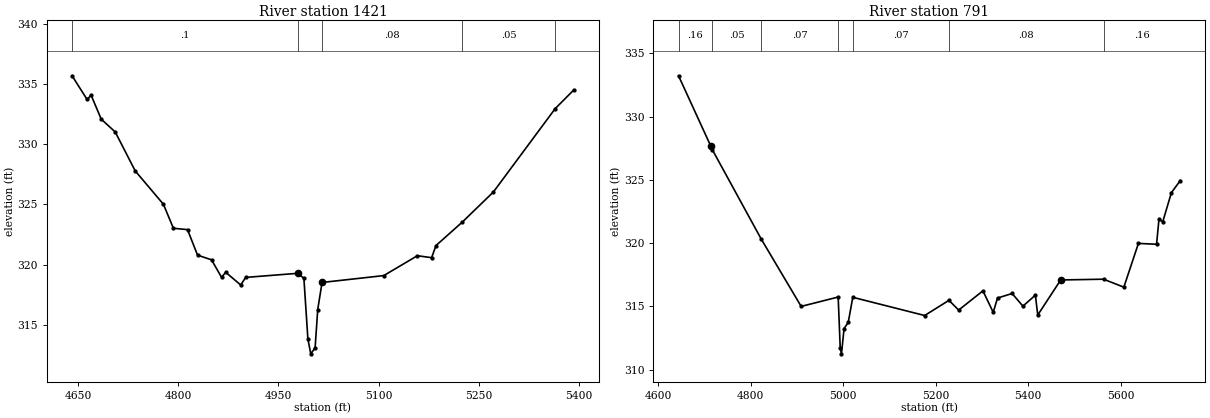
Type RM Length L Ch R = 1 ,1421    ,630,630,630
BEGIN DESCRIPTION:
UNT181 IN CCTC 2.0
END DESCRIPTION:
XS GIS Cut Line= 3
      3575249.61     10683410.19      3574949.61     10683610.19
      3574699.59     10683910.21
#Sta/Elev= 30
  4641.2  335.69  4663.7  333.72  4669.7  334.08  4684.8  332.09  4705.8  331.02
  4735.8  327.78  4777.9  325.02  4792.9  323.02    4814  322.91    4829  320.79
    4850   320.4    4865  318.94  4871.1  319.37  4893.6  318.31  4901.1  318.94
  4979.2  319.28  4988.2  318.86  4994.2  313.82  4998.5  312.59    5005  313.09
  5008.9  316.27  5015.4  318.52  5107.8  319.09    5158  320.74  5179.4  320.58
    5186  321.59  5225.6  323.55  5271.9  326.04  5364.2  332.95  5392.3  334.52
#Mann= 5 ,-1 , 0
  4641.2      .1       0  4979.2     .05       0  5015.4     .08       0
  5225.6     .05       0  5364.2     .16       0
Bank Sta=4979.2,5015.4
XS Rating Curve= 0 ,0
Exp/Cntr=0.3,0.1

Type RM Length L Ch R = 1 ,791     ,0,0,0
BEGIN DESCRIPTION:
UNT181 IN CCTC 1.0
END DESCRIPTION:
XS GIS Cut Line= 4
      3575255.57     10683060.29      3574986.47     10682969.14
      3574834.56     10683029.91      3574639.61     10683636.41
#Sta/Elev= 30
  4644.2  333.22  4713.8  327.67  4717.2  327.38  4822.7  320.33  4909.3  314.99
 4989.32  315.73  4993.7  311.74  4996.4  311.24  5002.1  313.24  5011.1  313.73
  5020.9  315.71  5176.3  314.27  5228.8  315.47  5249.8   314.7  5302.3  316.22
  5324.5  314.52  5333.8  315.65  5365.3  316.01  5388.7  315.01  5415.6  315.88
  5420.8  314.31  5470.4  317.08    5563  317.14  5606.9  316.51  5638.4  319.97
  5677.6   319.9  5682.8  321.87    5691  321.68  5709.7  323.98    5729  324.94
#Mann= 7 ,-1 , 0
  4644.2     .16       0  4717.2     .05       0  4822.7     .07       0
 4989.32     .05       0  5020.9     .07       0  5228.8     .08       0
    5563     .16       0
Bank Sta=4713.8,5470.4
XS Rating Curve= 0 ,0
Exp/Cntr=0.3,0.1

Chan Stop Cuts=-1
Use User Specified Reach Order=0
Composite Channel Slope=5