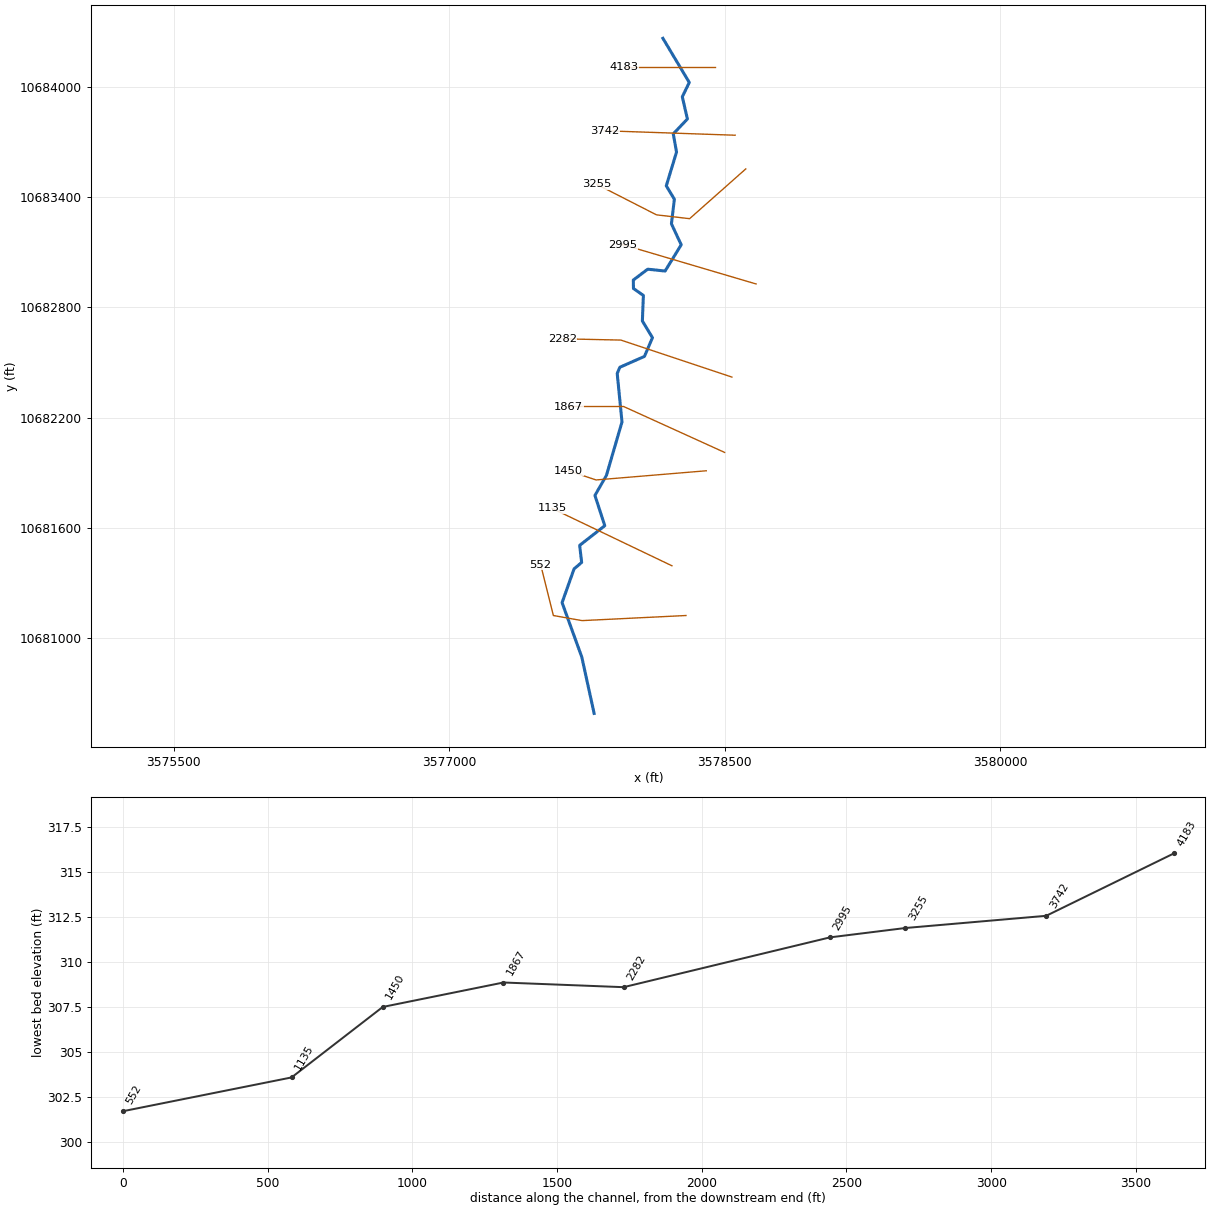
--- UNT182 IN CCTC.prj (project) ---

Proj Title=UNT182 IN CCTC Base Level Engineering
Current Plan=p01
Default Exp/Contr=0.3,0.1
English Units
Geom File=g01
Flow File=f01
Plan File=p01
Y Axis Title=Elevation
X Axis Title(PF)=Main Channel Distance
X Axis Title(XS)=Station
BEGIN DESCRIPTION:
UNT182 IN CCTC
END DESCRIPTION:
DSS Export Rating Curves= 0
DSS Export Rating Curve Sorted= 0
DSS Export Volume Flow Curves= 0
DXF OffsetX= 0
DXF OffsetY= 0
DXF ScaleX= 1
DXF ScaleY= 10

--- UNT182 IN CCTC.p01 (plan) ---

Plan Title=Multiple Run
Short Identifier=Multiple
Geom File=g01
Flow File=f01
Subcritical Flow
K Sum by GR= 0
Std Step Tol= 0.01
Critical Tol= 0.01
Num of Std Step Trials= 20
Max Error Tol= 0.3
Flow Tol Ratio= 0.001
Split Flow NTrial= 30
Split Flow Tol= 0.02
Split Flow Ratio= 0.02
Log Output Level= 0
Friction Slope Method= 1
Unsteady Friction Slope Method= 2
Unsteady Bridges Friction Slope Method= 1
Parabolic Critical Depth
Global Vel Dist=  1 , 1 , 1
Global Log Level= 0
CheckData=True
Encroach Param= -1, 0, 0, 0
BEGIN DESCRIPTION:
Multiple Run
END DESCRIPTION:

--- UNT182 IN CCTC.f01 (steady flow) ---

Flow Title=Multiple
Number of Profiles=7
Profile Names=10-year,25-year,50-year,1pct_min,100-year,1pct_plu,500-year
River Rch & RM= UNT182 IN CCTC,Reach-1,4183
    1096    1487    1805    1601    2165    2928    3102
Boundary for River Rch & Prof#=UNT182 IN CCTC,Reach-1,1
Up Type=0
Dn Type=3
Dn Slope=0.005
Boundary for River Rch & Prof#=UNT182 IN CCTC,Reach-1,2
Up Type=0
Dn Type=3
Dn Slope=0.005
Boundary for River Rch & Prof#=UNT182 IN CCTC,Reach-1,3
Up Type=0
Dn Type=3
Dn Slope=0.005
Boundary for River Rch & Prof#=UNT182 IN CCTC,Reach-1,4
Up Type=0
Dn Type=3
Dn Slope=0.005
Boundary for River Rch & Prof#=UNT182 IN CCTC,Reach-1,5
Up Type=0
Dn Type=3
Dn Slope=0.005
Boundary for River Rch & Prof#=UNT182 IN CCTC,Reach-1,6
Up Type=0
Dn Type=3
Dn Slope=0.005
Boundary for River Rch & Prof#=UNT182 IN CCTC,Reach-1,7
Up Type=0
Dn Type=3
Dn Slope=0.005

--- UNT182 IN CCTC.g01 (geometry) ---

Geom Title=Existing Conditions
Program Version=4.10

River Reach=UNT182 IN CCTC  ,Reach-1
Reach XY= 30
      3578163.61     10684265.29      3578307.25       10684025.
      3578269.25       10683947.        3578297.       10683826.
        3578220.       10683745.      3578237.75       10683646.
        3578182.       10683462.        3578226.       10683389.
        3578210.       10683255.      3578263.25       10683141.
       3578175.5       10682998.      3578080.75       10683008.
       3578002.5       10682949.      3578003.25       10682903.
      3578057.25       10682865.      3578051.75       10682726.
      3578106.75       10682635.        3578063.       10682533.
        3577929.       10682474.      3577914.75       10682440.
      3577940.75       10682176.        3577856.       10681885.
       3577793.5       10681776.        3577847.       10681611.
      3577710.25       10681504.        3577721.       10681411.
      3577679.75       10681376.       3577614.5       10681192.
      3577721.75       10680896.        3577789.       10680589.

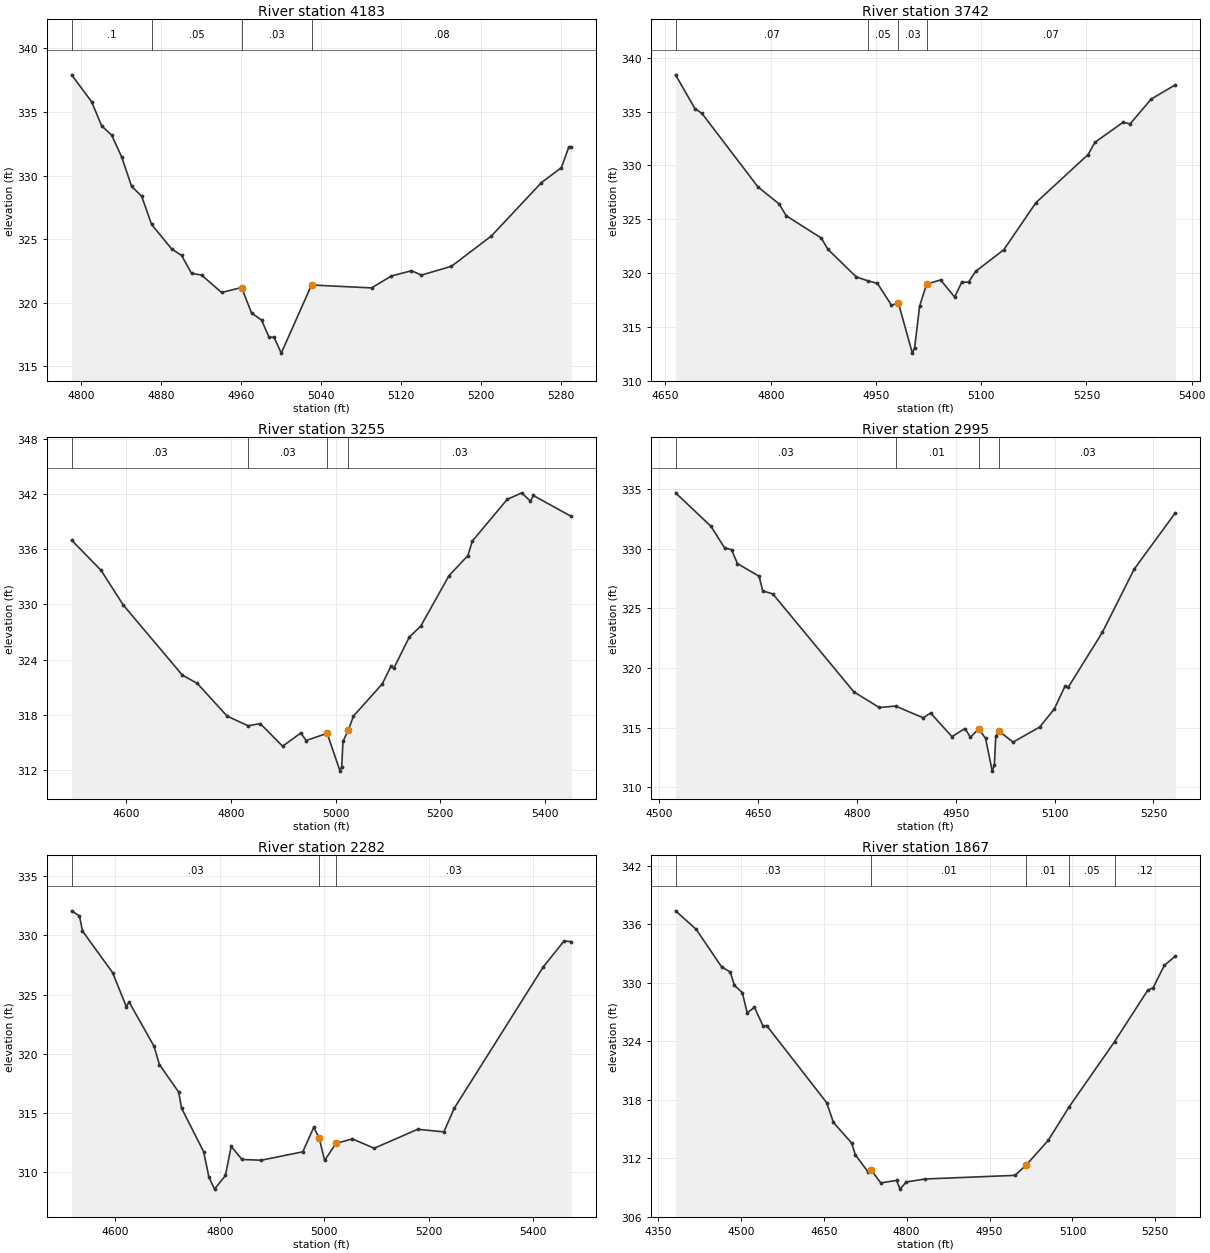
Type RM Length L Ch R = 1 ,4183    ,441,441,441
BEGIN DESCRIPTION:
UNT182 IN CCTC 8.0
END DESCRIPTION:
XS GIS Cut Line= 3
      3578449.57     10684110.19      3578249.61     10684110.19
      3577949.57     10684110.19
#Sta/Elev= 30
  4790.9  337.92  4810.9   335.8  4820.9  333.91  4830.9  333.18  4840.9  331.47
  4850.9  329.14  4860.9  328.38  4870.9  326.15  4890.9  324.23  4900.9  323.71
  4910.9   322.3  4920.9  322.17  4940.9   320.8  4960.9  321.19  4970.9  319.19
  4980.9  318.63  4988.4  317.28  4993.4  317.28  5000.6  316.03  5030.9  321.39
  5090.9  321.16  5110.9   322.1  5130.9  322.51  5140.9  322.17  5170.9  322.86
  5210.9  325.25  5260.9  329.44  5280.9  330.62  5288.4  332.26  5290.9  332.26
#Mann= 4 ,-1 , 0
  4790.9      .1       0  4870.9     .05       0  4960.9     .03       0
  5030.9     .08       0
Bank Sta=4960.9,5030.9
XS Rating Curve= 0 ,0
Exp/Cntr=0.3,0.1

Type RM Length L Ch R = 1 ,3742    ,487,487,487
BEGIN DESCRIPTION:
UNT182 IN CCTC 7.0
END DESCRIPTION:
XS GIS Cut Line= 2
      3578557.17     10683737.63      3577845.29     10683761.94
#Sta/Elev= 30
  4664.4  338.41    4692  335.27    4702  334.83    4782  327.99    4812  326.42
  4822.1  325.32  4872.1  323.25  4881.5  322.21  4922.1  319.63    4938  319.29
  4952.1  319.04  4972.1  317.02  4982.1   317.2  5001.9  312.56  5005.2  313.06
  5012.2  316.91  5022.2  318.97  5042.2  319.36  5062.2  317.77  5072.2  319.13
  5082.2  319.17  5092.2  320.16  5132.2  322.16  5178.1  326.54  5252.3     331
  5262.3  332.15  5302.3     334  5312.3  333.86  5342.4  336.16  5376.7  337.48
#Mann= 4 ,-1 , 0
  4664.4     .07       0    4938     .05       0  4982.1     .03       0
  5022.2     .07       0
Bank Sta=4982.1,5022.2
XS Rating Curve= 0 ,0
Exp/Cntr=0.3,0.1

Type RM Length L Ch R = 1 ,3255    ,260,260,260
BEGIN DESCRIPTION:
UNT182 IN CCTC 6.0
END DESCRIPTION:
XS GIS Cut Line= 4
      3578614.71     10683554.03      3578309.15      10683283.2
       3578128.6     10683304.03      3577803.41     10683470.08
#Sta/Elev= 30
  4495.6  336.99  4551.7  333.72  4594.3  329.94  4707.2  322.32  4735.7  321.42
  4792.6  317.87  4832.8  316.81  4856.1  317.05  4898.8  314.59  4933.7  316.03
  4943.7  315.21    4984  315.99  5008.6  311.88  5011.8  312.38  5014.2  315.11
  5024.3  316.33  5034.3  317.87  5089.2  321.36  5105.8  323.27  5111.4  323.07
  5140.7  326.43  5163.1  327.67  5216.9  333.14    5253  335.32  5261.4  336.89
    5328  341.42  5355.9  342.14  5372.5  341.23  5378.1  341.85  5450.8  339.57
#Mann= 4 ,-1 , 0
  4495.6     .03       0  4832.8     .03       0    4984     .01       0
  5024.3     .03       0
Bank Sta=4984,5024.3
XS Rating Curve= 0 ,0
Exp/Cntr=0.3,0.1

Type RM Length L Ch R = 1 ,2995    ,713,713,713
BEGIN DESCRIPTION:
UNT182 IN CCTC 5.0
END DESCRIPTION:
XS GIS Cut Line= 2
      3578671.14     10682927.52       3577943.3      10683142.4
#Sta/Elev= 30
  4524.4  334.67  4578.1  331.87    4599  330.05  4609.4  329.91  4618.4  328.74
  4651.1  327.69  4656.9  326.45    4672  326.21  4795.3  317.99  4833.8  316.69
  4858.4  316.81  4900.4  315.83  4911.8  316.22  4944.1  314.25  4963.9  314.93
  4972.2   314.2  4984.8   314.9  4995.2   314.1  5005.3  311.36  5008.5  311.86
  5010.7   314.3  5016.1  314.69  5036.9  313.79  5077.3  315.05  5099.5  316.56
  5115.8  318.48    5121  318.41  5172.5  322.98  5220.9  328.28  5283.3  332.99
#Mann= 4 ,-1 , 0
  4524.4     .03       0  4858.4     .01       0  4984.8     .01       0
  5016.1     .03       0
Bank Sta=4984.8,5016.1
XS Rating Curve= 0 ,0
Exp/Cntr=0.3,0.1

Type RM Length L Ch R = 1 ,2282    ,415,415,415
BEGIN DESCRIPTION:
UNT182 IN CCTC 4.0
END DESCRIPTION:
XS GIS Cut Line= 3
      3578539.22     10682420.56      3577935.02     10682621.96
      3577615.58     10682628.91
#Sta/Elev= 30
  4516.3  332.07  4531.3  331.63    4537  330.37  4594.6  326.86  4620.9  323.99
  4626.2  324.38    4674  320.64  4684.2   319.1  4721.1  316.78  4726.7  315.41
  4768.9  311.75    4779   309.6  4789.7  308.59  4810.6  309.74  4821.6   312.2
  4842.3  311.09  4879.2  311.03  4958.6  311.74  4979.7  313.81  4990.2  312.87
  5000.4  311.01  5021.9  312.44  5053.5  312.83  5095.3  312.04  5178.6  313.64
  5228.6  313.42  5248.6  315.42  5418.7  327.33  5458.7  329.53  5472.7  329.47
#Mann= 3 , 0 , 0
  4516.3     .03       0  4990.2     .01       0  5021.9     .03       0
Bank Sta=4990.2,5021.9
XS Rating Curve= 0 ,0
Exp/Cntr=0.3,0.1

Type RM Length L Ch R = 1 ,1867    ,417,417,417
BEGIN DESCRIPTION:
UNT182 IN CCTC 3.0
END DESCRIPTION:
XS GIS Cut Line= 3
      3578499.62     10682010.19      3577949.61     10682260.19
      3577649.57     10682260.19
#Sta/Elev= 30
  4381.9  337.38  4419.3  335.48  4465.4  331.62  4480.8  331.11  4488.5  329.73
  4502.7     329  4511.5  326.91  4524.7   327.5  4540.1  325.58  4546.7  325.62
  4655.4  317.71  4667.5  315.69  4700.5  313.58  4707.1  312.38  4730.1  310.61
  4735.6  310.82  4753.2  309.49  4781.7  309.74  4788.1  308.85  4799.3  309.58
  4833.4  309.89  4996.1  310.26  5016.1  311.31  5056.1  313.84  5094.2   317.3
  5176.2  323.97  5236.1  329.23  5246.1  329.51  5266.1  331.78  5286.1  332.73
#Mann= 5 ,-1 , 0
  4381.9     .03       0  4735.6     .01       0  5016.1     .01       0
  5094.2     .05       0  5176.2     .12       0
Bank Sta=4735.6,5016.1
XS Rating Curve= 0 ,0
Exp/Cntr=0.3,0.1

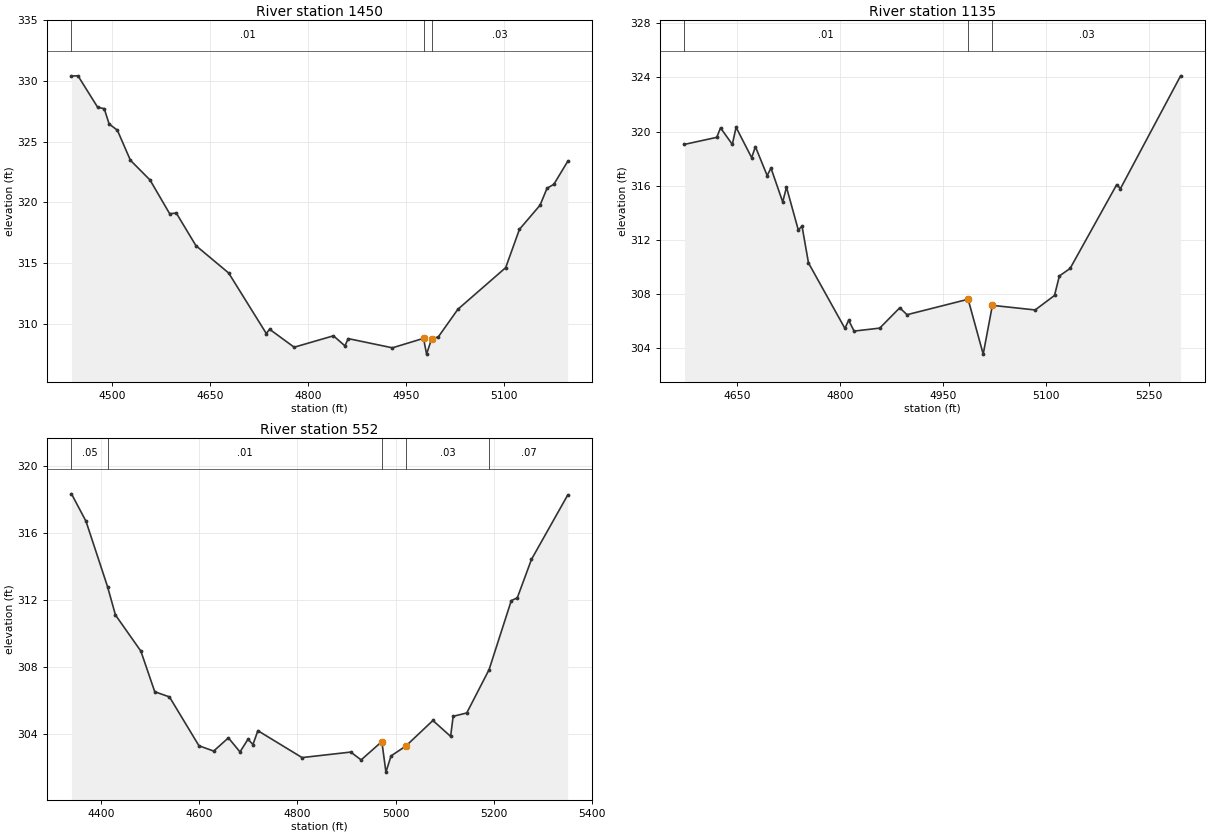
Type RM Length L Ch R = 1 ,1450    ,315,315,315
BEGIN DESCRIPTION:
UNT182 IN CCTC 2.0
END DESCRIPTION:
XS GIS Cut Line= 3
      3578399.62     10681910.19      3577799.61     10681860.19
      3577649.61     10681910.19
#Sta/Elev= 30
  4437.8  330.42  4447.8  330.43  4477.9  327.84    4488  327.72  4495.5  326.46
  4508.1  325.95  4528.1  323.47  4558.2  321.84  4588.3  319.06  4598.4  319.12
  4628.5  316.43  4678.6  314.18  4736.3  309.19  4741.4  309.54    4779  308.06
  4839.2     309  4856.8  308.17  4861.8  308.77  4929.5  308.01  4977.2  308.79
  4981.9  307.49  4989.7  308.77  4999.7   308.9  5029.9  311.19  5103.1  314.62
  5124.2  317.78  5155.8  319.77  5166.4  321.16  5176.9  321.49    5198  323.37
#Mann= 3 , 0 , 0
  4437.8     .01       0  4977.2     .01       0  4989.7     .03       0
Bank Sta=4977.2,4989.7
XS Rating Curve= 0 ,0
Exp/Cntr=0.3,0.1

Type RM Length L Ch R = 1 ,1135    ,583,583,583
BEGIN DESCRIPTION:
Mapping XS bfbf12aa
END DESCRIPTION:
XS GIS Cut Line= 2
      3578212.79      10681392.8      3577560.13     10681705.25
#Sta/Elev= 30
  4573.2  319.05  4620.3  319.57  4625.8  320.27    4643  319.05  4648.5  320.31
  4671.2  318.07  4676.7  318.88  4693.8  316.75  4699.4   317.3  4716.5   314.8
    4722  315.89  4739.2  312.74  4744.7  313.01  4754.1   310.3  4807.2  305.47
  4812.7  306.07  4820.6  305.27    4858  305.49  4887.2  306.99  4897.8  306.48
  4986.9  307.62  5008.9  303.57  5022.3  307.17  5084.7  306.83  5112.9   307.9
    5120  309.34  5135.6  309.89  5203.6  316.08  5209.1  315.79  5296.8  324.11
#Mann= 3 , 0 , 0
  4573.2     .01       0  4986.9     .01       0  5022.3     .03       0
Bank Sta=4986.9,5022.3
XS Rating Curve= 0 ,0
Exp/Cntr=0.3,0.1

Type RM Length L Ch R = 1 ,552     ,0,0,0
BEGIN DESCRIPTION:
UNT182 IN CCTC 1.0
END DESCRIPTION:
XS GIS Cut Line= 4
      3578289.21     10681121.97      3577723.21     10681094.19
      3577566.96     10681121.96      3577497.52     10681399.74
#Sta/Elev= 30
  4339.2  318.34  4368.8   316.7  4412.7  312.79  4428.9  311.09  4480.7  308.93
    4509   306.5    4539  306.19  4599.1  303.27  4629.1  302.95  4659.2  303.74
  4682.8   302.9  4699.2  303.66  4709.2  303.34  4719.3  304.17  4809.4  302.56
  4908.7  302.89  4929.8  302.42  4972.1  303.52  4980.4  301.69  4990.8  302.66
    5021  303.25  5076.2  304.78  5112.3  303.83  5117.5  305.03  5145.2  305.23
  5190.7  307.82    5236  311.95  5248.3  312.12  5277.2  314.42  5350.9  318.26
#Mann= 5 ,-1 , 0
  4339.2     .05       0  4412.7     .01       0  4972.1     .01       0
    5021     .03       0  5190.7     .07       0
Bank Sta=4972.1,5021
XS Rating Curve= 0 ,0
Exp/Cntr=0.3,0.1

Chan Stop Cuts=-1
Use User Specified Reach Order=0
Composite Channel Slope=5