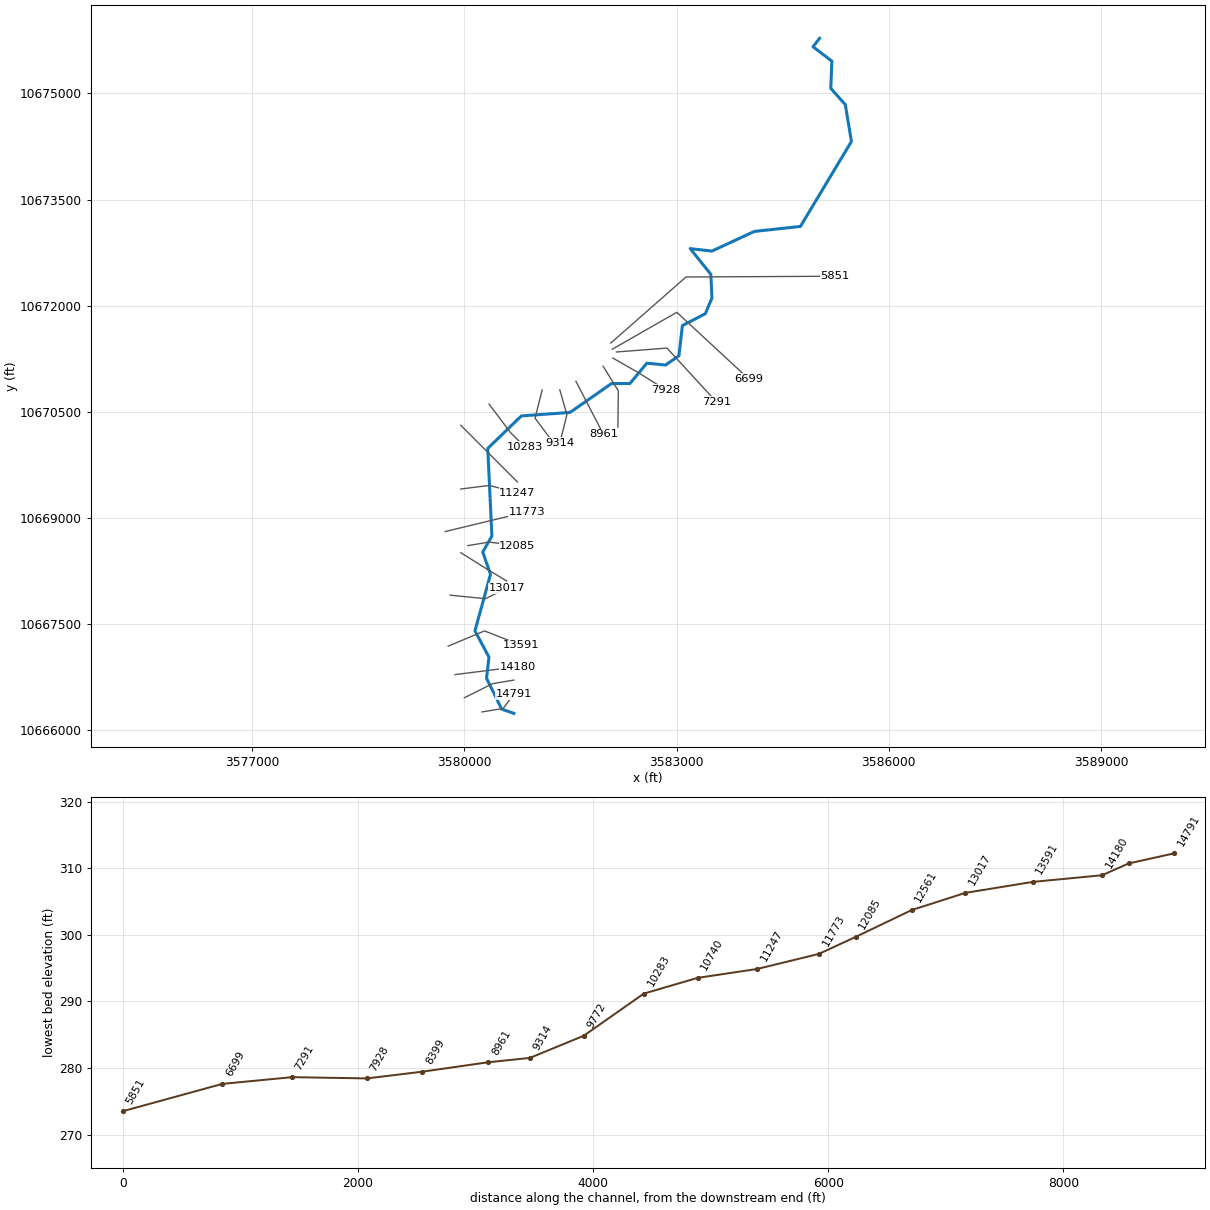
--- UNT183 IN CCTC.prj (project) ---

Proj Title=UNT183 IN CCTC Base Level Engineering
Current Plan=p01
Default Exp/Contr=0.3,0.1
English Units
Geom File=g01
Flow File=f01
Plan File=p01
BEGIN DESCRIPTION:
UNT183 IN CCTC
END DESCRIPTION:

--- UNT183 IN CCTC.p01 (plan) ---

Plan Title=Multiple Run
Short Identifier=Multiple
Geom File=g01
Flow File=f01
Subcritical Flow
K Sum by GR= 0
Std Step Tol= 0.01
Critical Tol= 0.01
Num of Std Step Trials= 20
Max Error Tol= 0.3
Flow Tol Ratio= 0.001
Split Flow NTrial= 30
Split Flow Tol= 0.02
Split Flow Ratio= 0.02
Log Output Level= 0
Friction Slope Method= 1
Unsteady Friction Slope Method= 2
Unsteady Bridges Friction Slope Method= 1
Parabolic Critical Depth
Global Vel Dist=  1 , 1 , 1
Global Log Level= 0
CheckData=True
Encroach Param= -1, 0, 0, 0
BEGIN DESCRIPTION:
Multiple Run
END DESCRIPTION:

--- UNT183 IN CCTC.f01 (steady flow) ---

Flow Title=Multiple
Number of Profiles=7
Profile Names=10-year,25-year,50-year,1pct_min,100-year,1pct_plu,500-year
River Rch & RM= UNT183 IN CCTC,Reach-1,14791
    1392    1920    2359    2115    2860    3868    4191
River Rch & RM= UNT183 IN CCTC,Reach-1,14406
    2035    2854    3543    3204    4333    5860    6463
Boundary for River Rch & Prof#=UNT183 IN CCTC,Reach-1,1
Up Type=0
Dn Type=3
Dn Slope=0.005
Boundary for River Rch & Prof#=UNT183 IN CCTC,Reach-1,2
Up Type=0
Dn Type=3
Dn Slope=0.005
Boundary for River Rch & Prof#=UNT183 IN CCTC,Reach-1,3
Up Type=0
Dn Type=3
Dn Slope=0.005
Boundary for River Rch & Prof#=UNT183 IN CCTC,Reach-1,4
Up Type=0
Dn Type=3
Dn Slope=0.005
Boundary for River Rch & Prof#=UNT183 IN CCTC,Reach-1,5
Up Type=0
Dn Type=3
Dn Slope=0.005
Boundary for River Rch & Prof#=UNT183 IN CCTC,Reach-1,6
Up Type=0
Dn Type=3
Dn Slope=0.005
Boundary for River Rch & Prof#=UNT183 IN CCTC,Reach-1,7
Up Type=0
Dn Type=3
Dn Slope=0.005

--- UNT183 IN CCTC.g01 (geometry) ---

Geom Title=Existing Conditions

River Reach=UNT183 IN CCTC,Reach-1
Reach XY= 30
      3580699.50     10666240.00      3580527.75     10666300.00
      3580313.75     10666737.00      3580348.25     10667035.00
      3580149.75     10667405.00      3580369.50     10668204.00
      3580260.00     10668520.00      3580389.50     10668745.00
      3580331.00     10669984.00      3580806.25     10670443.00
      3581494.00     10670492.00      3582079.50     10670900.00
      3582340.25     10670901.00      3582580.50     10671188.00
      3582843.50     10671162.00      3583033.25     10671293.00
      3583082.00     10671719.00      3583406.25     10671887.00
      3583499.25     10672109.00      3583484.25     10672443.00
      3583192.00     10672807.00      3583499.25     10672772.00
      3584100.00     10673050.00      3584750.25     10673120.00
      3585471.25     10674321.00      3585384.50     10674842.00
      3585179.50     10675071.00      3585194.75     10675456.00
      3584928.50     10675659.00      3585020.75     10675778.00

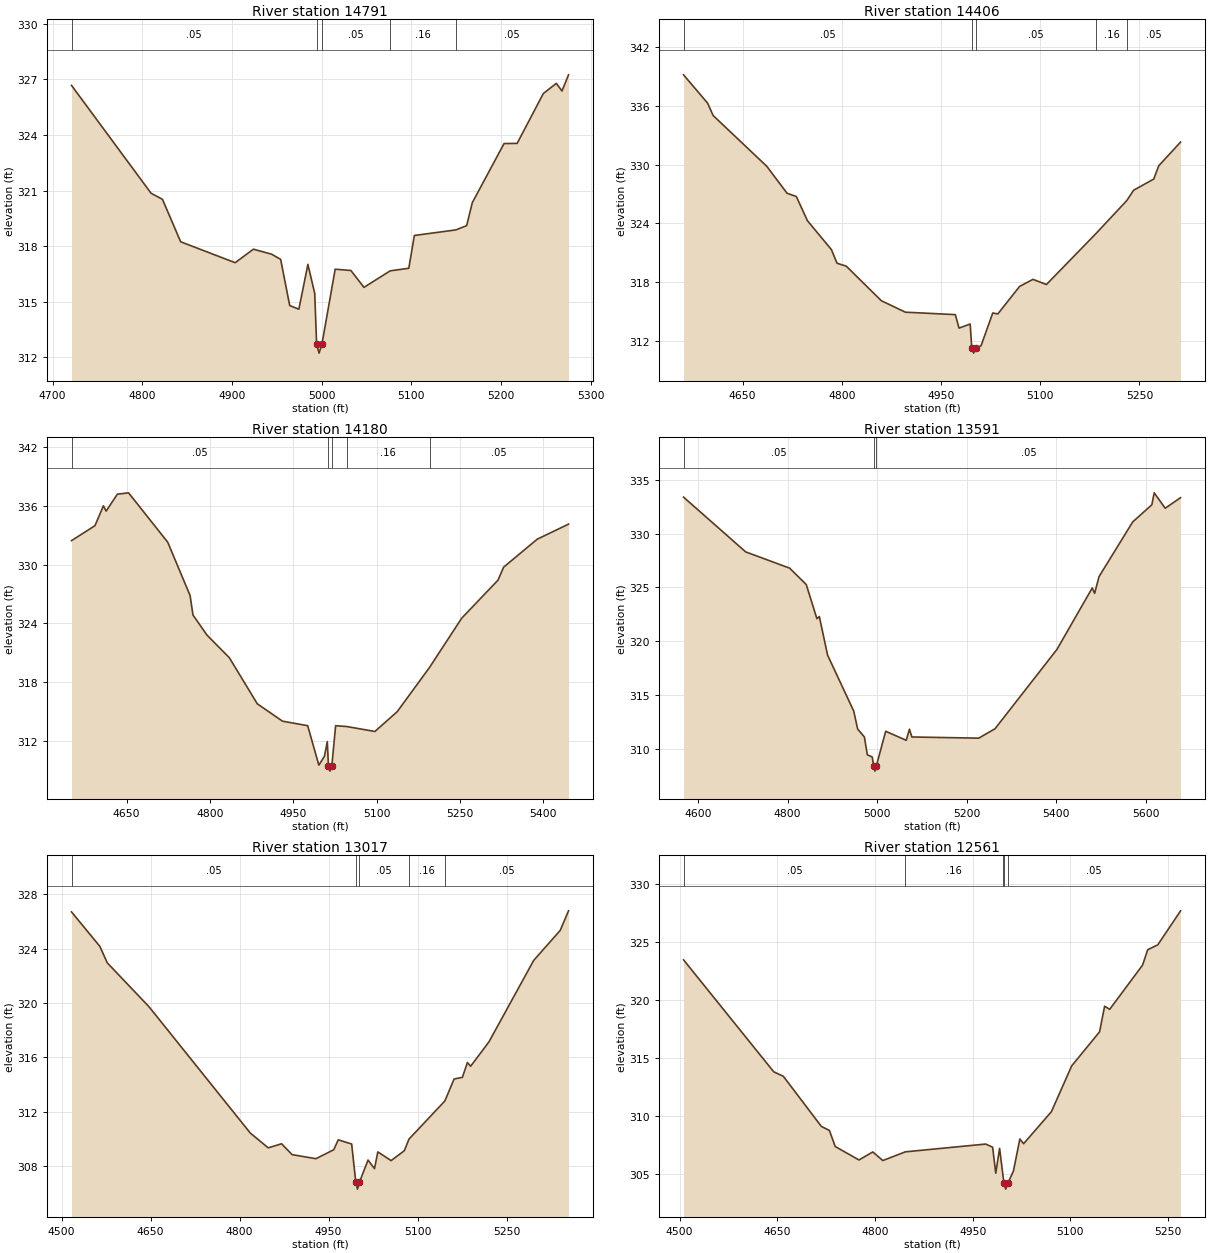
Type RM Length L Ch R = 1,14791,385,385,385
BEGIN DESCRIPTION:
UNT183 IN CCTC 19.0
END DESCRIPTION:
XS GIS Cut Line= 3
      3580249.57     10666260.18      3580549.61     10666310.19
      3580699.62     10666510.21
#Sta/Elev= 30
  4721.0  326.68  4809.7  320.86  4822.4  320.53  4842.7  318.24  4903.5  317.11
  4923.8  317.84  4944.1  317.57  4954.2  317.29  4964.3  314.80  4974.5  314.60
  4984.6  317.02  4992.2  315.45  4994.3  312.73  4997.0  312.23  5000.3  312.73
  5015.0  316.76  5032.5  316.69  5047.1  315.78  5076.3  316.67  5097.1  316.81
  5103.3  318.58  5149.5  318.88  5161.6  319.11  5167.9  320.35  5203.3  323.54
  5217.9  323.55  5247.1  326.24  5261.6  326.79  5267.9  326.38  5275.2  327.25
#Mann=5,-1,0
  4721.0    0.05       0  4994.3    0.03       0  5000.3    0.05       0
  5076.3    0.16       0  5149.5    0.05       0
Bank Sta=4994.3,5000.3
Exp/Cntr=0.3,0.1

Type RM Length L Ch R = 1,14406,226,226,226
BEGIN DESCRIPTION:
UNT183 IN CCTC 18.0
END DESCRIPTION:
XS GIS Cut Line= 3
      3579999.59     10666460.18      3580399.61     10666660.19
      3580699.64     10666710.19
#Sta/Elev= 30
  4560.7  339.20  4597.1  336.30  4605.4  335.04  4686.5  329.84  4717.2  327.08
  4731.2  326.75  4748.0  324.27  4784.3  321.31  4792.7  319.92  4806.7  319.62
  4859.8  316.08  4896.1  314.91  4971.6  314.66  4977.2  313.28  4994.0  313.70
  4996.5  311.22  4999.3  310.72  5002.5  311.22  5010.5  311.48  5028.2  314.83
  5035.8  314.73  5068.8  317.55  5089.0  318.27  5109.3  317.74  5184.4  322.97
  5230.8  326.33  5241.1  327.39  5271.5  328.53  5279.1  329.89  5312.1  332.32
#Mann=5,-1,0
  4560.7    0.05       0  4996.5    0.03       0  5002.5    0.05       0
  5184.4    0.16       0  5230.8    0.05       0
Bank Sta=4996.5,5002.5
Exp/Cntr=0.3,0.1

Type RM Length L Ch R = 1,14180,589,589,589
BEGIN DESCRIPTION:
UNT183 IN CCTC 17.0
END DESCRIPTION:
XS GIS Cut Line= 2
      3579867.73     10666788.06      3580755.62     10666899.04
#Sta/Elev= 30
  4550.9  332.44  4593.1  333.96  4608.3  335.98  4613.3  335.45  4633.4  337.17
  4653.6  337.31  4724.1  332.28  4764.4  326.84  4769.6  324.86  4794.7  322.82
  4835.0  320.51  4885.4  315.81  4930.8  314.04  4976.1  313.58  4996.2  309.56
  5006.3  310.47  5011.4  311.96  5013.5  309.45  5016.2  308.95  5019.5  309.45
  5026.4  313.58  5047.0  313.49  5097.1  312.99  5137.3  315.01  5195.5  319.52
  5253.3  324.53  5318.7  328.41  5328.8  329.73  5389.2  332.58  5445.7  334.12
#Mann=5,-1,0
  4550.9    0.05       0  5013.5    0.03       0  5019.5    0.05       0
  5047.0    0.16       0  5195.5    0.05       0
Bank Sta=5013.5,5019.5
Exp/Cntr=0.3,0.1

Type RM Length L Ch R = 1,13591,574,574,574
BEGIN DESCRIPTION:
UNT183 IN CCTC 16.0
END DESCRIPTION:
XS GIS Cut Line= 3
      3579771.31     10667189.73      3580285.24     10667405.02
      3580799.09     10667203.65
#Sta/Elev= 30
  4567.9  333.38  4706.5  328.30  4804.6  326.79  4841.7  325.27  4865.5  322.10
  4870.9  322.30  4889.3  318.72  4947.7  313.52  4956.4  311.86  4971.4  311.12
  4978.1  309.46  4988.9  309.27  4992.2  308.45  4995.0  307.95  4998.2  308.45
  5019.0  311.65  5064.8  310.81  5072.0  311.84  5077.4  311.12  5226.5  311.01
  5262.9  311.88  5401.2  319.25  5479.9  324.95  5485.3  324.45  5495.0  326.00
  5570.2  331.08  5612.9  332.67  5618.2  333.78  5642.7  332.35  5677.0  333.33
#Mann=3,-1,0
  4567.9    0.05       0  4992.2    0.03       0  4998.2    0.05       0
Bank Sta=4992.2,4998.2
Exp/Cntr=0.3,0.1

Type RM Length L Ch R = 1,13017,456,456,456
BEGIN DESCRIPTION:
UNT183 IN CCTC 15.0
END DESCRIPTION:
XS GIS Cut Line= 3
      3579799.66     10667910.18      3580299.61     10667860.19
      3580599.65     10668010.21
#Sta/Elev= 30
  4516.6  326.71  4564.3  324.18  4576.9  322.96  4647.2  319.73  4818.0  310.43
  4848.2  309.34  4870.8  309.64  4888.4  308.84  4928.6  308.54  4958.7  309.20
  4966.3  309.93  4988.9  309.62  4995.9  306.80  4998.7  306.30  5001.9  306.80
  5016.5  308.44  5027.4  307.81  5033.0  309.04  5055.4  308.40  5077.7  309.13
  5085.5  309.98  5146.0  312.79  5161.6  314.41  5175.6  314.53  5184.0  315.62
  5189.5  315.35  5220.3  317.14  5295.8  323.14  5340.5  325.35  5354.5  326.79
#Mann=5,-1,0
  4516.6    0.05       0  4995.9    0.03       0  5001.9    0.05       0
  5085.5    0.16       0  5146.0    0.05       0
Bank Sta=4995.9,5001.9
Exp/Cntr=0.3,0.1

Type RM Length L Ch R = 1,12561,476,476,476
BEGIN DESCRIPTION:
UNT183 IN CCTC 14.0
END DESCRIPTION:
XS GIS Cut Line= 3
      3579949.65     10668510.16      3580349.61     10668260.19
      3580599.61     10668110.19
#Sta/Elev= 30
  4506.0  323.46  4644.5  313.82  4659.3  313.43  4717.6  309.12  4730.0  308.77
  4738.9  307.39  4775.4  306.23  4796.6  306.92  4812.0  306.18  4846.6  306.93
  4970.0  307.60  4980.6  307.33  4985.4  305.09  4991.3  307.23  4996.3  304.98
  4998.0  304.22  5000.7  303.72  5004.0  304.22  5012.6  305.29  5022.4  308.03
  5028.2  307.63  5070.9  310.39  5102.0  314.33  5144.8  317.26  5152.6  319.47
  5160.4  319.20  5210.9  323.01  5218.7  324.33  5234.2  324.75  5269.2  327.68
#Mann=5,-1,0
  4506.0    0.05       0  4846.6    0.16       0  4996.3    0.05       0
  4998.0    0.03       0  5004.0    0.05       0
Bank Sta=4998,5004
Exp/Cntr=0.3,0.1

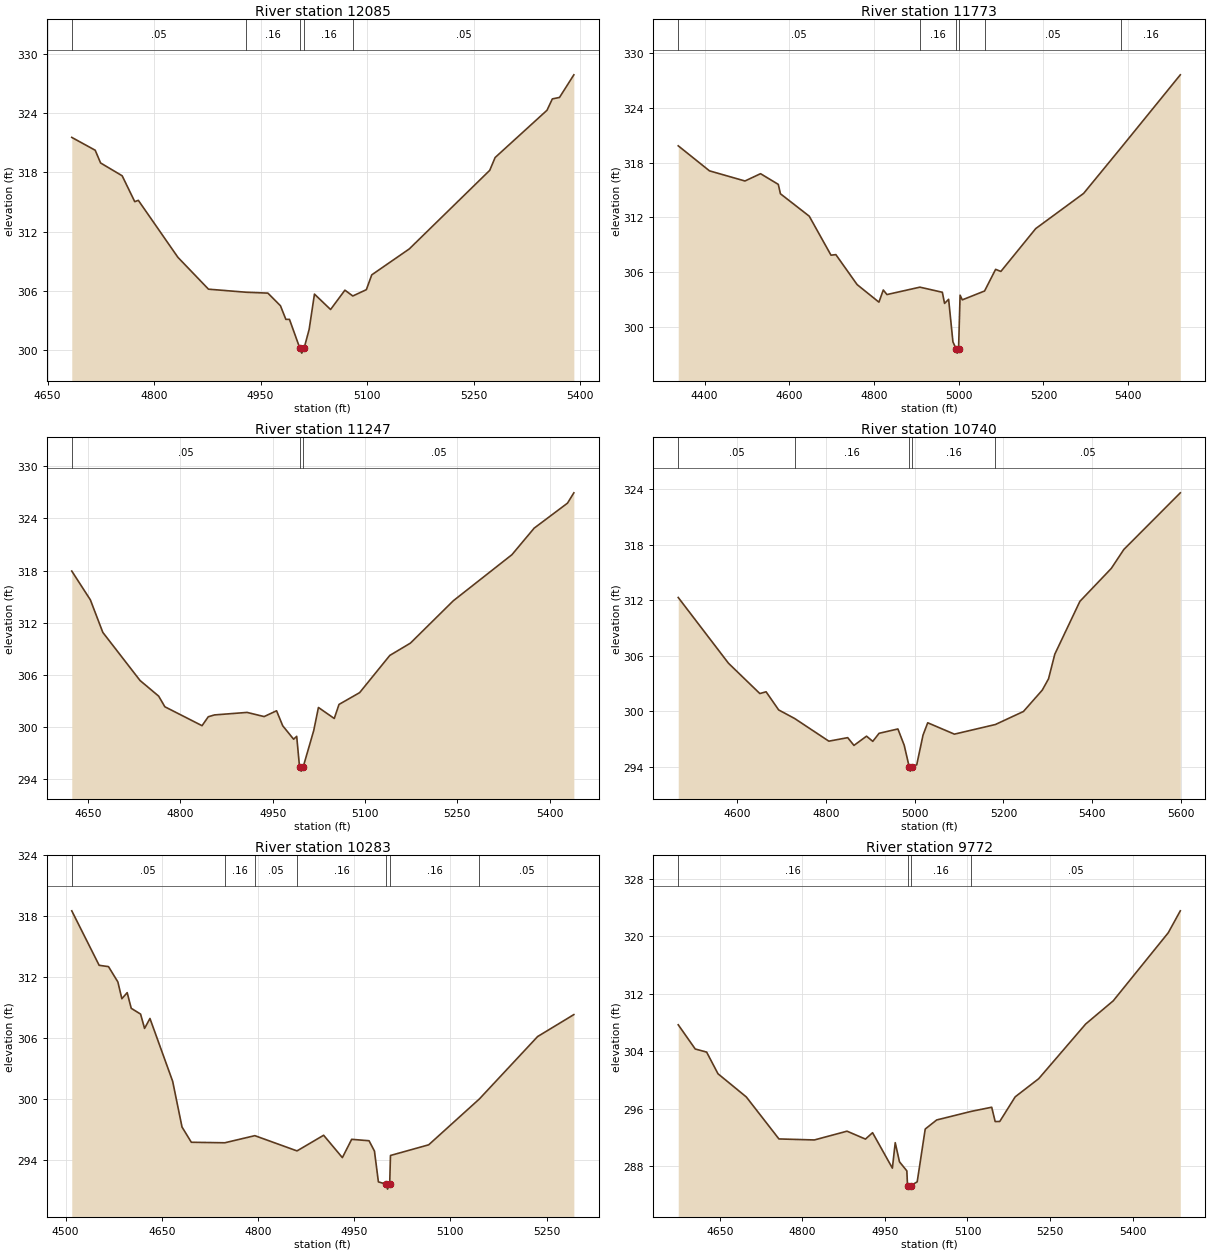
Type RM Length L Ch R = 1,12085,312,312,312
BEGIN DESCRIPTION:
UNT183 IN CCTC 13.0
END DESCRIPTION:
XS GIS Cut Line= 3
      3580049.60     10668610.19      3580349.61     10668660.19
      3580749.65     10668610.18
#Sta/Elev= 30
  4684.0  321.55  4717.0  320.25  4724.6  318.96  4755.0  317.66  4772.7  315.04
  4777.8  315.17  4833.5  309.40  4876.6  306.17  4929.5  305.86  4960.3  305.77
  4978.0  304.49  4985.6  303.11  4990.7  303.11  5005.3  300.19  5008.0  299.69
  5011.3  300.19  5018.4  302.09  5025.9  305.67  5048.6  304.11  5068.8  306.07
  5079.9  305.48  5099.0  306.12  5106.6  307.62  5159.5  310.25  5272.8  318.21
  5280.4  319.51  5353.5  324.30  5361.0  325.45  5371.1  325.60  5391.3  327.89
#Mann=5,-1,0
  4684.0    0.05       0  4929.5    0.16       0  5005.3    0.07       0
  5011.3    0.16       0  5079.9    0.05       0
Bank Sta=5005.3,5011.3
Exp/Cntr=0.3,0.1

Type RM Length L Ch R = 1,11773,526,526,526
BEGIN DESCRIPTION:
UNT183 IN CCTC 12.0
END DESCRIPTION:
XS GIS Cut Line= 2
      3579728.82     10668808.89      3580881.63     10669086.67
#Sta/Elev= 30
  4337.6  319.83  4411.4  317.09  4495.2  315.98  4532.0  316.78  4573.9  315.61
  4579.0  314.58  4647.0  312.13  4698.4  307.86  4709.9  307.92  4760.1  304.64
  4811.6  302.72  4821.9  304.05  4830.5  303.55  4908.4  304.36  4961.4  303.80
  4966.6  302.58  4976.2  303.03  4986.4  298.37  4993.7  297.64  4996.5  297.14
  4999.7  297.64  5003.3  303.48  5008.5  302.97  5061.1  303.94  5087.2  306.31
  5099.6  306.08  5181.9  310.77  5295.0  314.62  5383.7  319.63  5523.4  327.60
#Mann=6,-1,0
  4337.6    0.05       0  4908.4    0.16       0  4993.7    0.07       0
  4999.7    0.16       0  5061.1    0.05       0  5383.7    0.16       0
Bank Sta=4993.7,4999.7
Exp/Cntr=0.3,0.1

Type RM Length L Ch R = 1,11247,507,507,507
BEGIN DESCRIPTION:
UNT183 IN CCTC 11.0
END DESCRIPTION:
XS GIS Cut Line= 3
      3579949.61     10669410.19      3580349.61     10669460.19
      3580749.59     10669360.19
#Sta/Elev= 30
  4623.8  317.94  4654.0  314.62  4674.2  310.87  4734.7  305.32  4764.9  303.52
  4775.0  302.29  4835.4  300.11  4845.5  301.14  4855.6  301.35  4908.5  301.64
  4936.2  301.16  4956.4  301.83  4966.4  300.10  4984.1  298.55  4989.1  298.88
  4993.7  295.37  4996.4  294.87  4999.7  295.37  5016.8  299.56  5024.4  302.21
  5050.1  300.94  5057.8  302.56  5091.3  303.92  5140.3  308.21  5173.8  309.63
  5243.4  314.51  5338.7  319.83  5374.8  322.89  5428.9  325.77  5439.2  326.96
#Mann=3,-1,0
  4623.8    0.05       0  4993.7    0.03       0  4999.7    0.05       0
Bank Sta=4993.7,4999.7
Exp/Cntr=0.3,0.1

Type RM Length L Ch R = 1,10740,457,457,457
BEGIN DESCRIPTION:
UNT183 IN CCTC 10.0
END DESCRIPTION:
XS GIS Cut Line= 3
      3579949.58     10670310.22      3580349.61     10669910.19
      3580749.60     10669510.20
#Sta/Elev= 30
  4467.1  312.31  4580.3  305.20  4651.0  301.92  4665.1  302.11  4693.4  300.15
  4729.5  299.22  4806.5  296.77  4849.0  297.15  4863.1  296.31  4891.4  297.31
  4905.5  296.75  4919.7  297.62  4962.1  298.09  4976.3  296.33  4987.4  294.03
  4990.1  293.53  4993.4  294.03  5004.5  294.21  5018.7  297.42  5029.3  298.76
  5089.4  297.53  5181.7  298.57  5245.0  299.98  5287.4  302.29  5301.5  303.51
  5315.7  306.18  5372.2  311.89  5442.9  315.45  5471.2  317.50  5598.5  323.63
#Mann=5,-1,0
  4467.1    0.05       0  4729.5    0.16       0  4987.4    0.07       0
  4993.4    0.16       0  5181.7    0.05       0
Bank Sta=4987.4,4993.4
Exp/Cntr=0.3,0.1

Type RM Length L Ch R = 1,10283,511,511,511
BEGIN DESCRIPTION:
UNT183 IN CCTC 9.0
END DESCRIPTION:
XS GIS Cut Line= 3
      3580349.62     10670610.17      3580649.61     10670210.19
      3580849.60     10670010.20
#Sta/Elev= 30
  4509.7  318.55  4552.4  313.19  4567.0  313.06  4581.6  311.55  4587.8  309.90
  4596.1  310.50  4602.4  308.96  4617.0  308.39  4623.2  306.98  4631.6  307.96
  4667.0  301.78  4681.6  297.28  4696.1  295.78  4748.3  295.73  4795.1  296.43
  4860.9  294.93  4902.4  296.47  4931.6  294.27  4946.1  296.07  4973.2  295.93
  4981.6  294.92  4987.8  291.88  4999.4  291.67  5002.1  291.17  5005.4  291.67
  5006.6  294.48  5066.2  295.53  5145.2  300.04  5236.0  306.18  5292.5  308.34
#Mann=7,-1,0
  4509.7    0.05       0  4748.3    0.16       0  4795.1    0.05       0
  4860.9    0.16       0  4999.4    0.07       0  5005.4    0.16       0
  5145.2    0.05       0
Bank Sta=4999.4,5005.4
Exp/Cntr=0.3,0.1

Type RM Length L Ch R = 1,9772,458,458,458
BEGIN DESCRIPTION:
UNT183 IN CCTC 8.0
END DESCRIPTION:
XS GIS Cut Line= 3
      3581099.61     10670810.20      3580999.61     10670410.19
      3581299.60     10670010.21
#Sta/Elev= 30
  4574.5  307.70  4605.4  304.33  4626.1  303.90  4646.7  300.89  4698.2  297.66
  4757.5  291.82  4821.9  291.68  4881.2  292.90  4914.7  291.80  4927.6  292.69
  4963.6  287.76  4968.8  291.30  4976.5  288.64  4989.9  287.38  4991.1  285.34
  4993.9  284.84  4997.1  285.34  5008.7  285.85  5023.3  293.20  5044.1  294.46
  5107.2  295.66  5144.1  296.23  5150.4  294.24  5158.7  294.25  5186.8  297.68
  5229.5  300.20  5314.9  307.81  5364.9  311.03  5464.9  320.50  5486.8  323.55
#Mann=4,-1,0
  4574.5    0.16       0  4991.1    0.07       0  4997.1    0.16       0
  5107.2    0.05       0
Bank Sta=4991.1,4997.1
Exp/Cntr=0.3,0.1

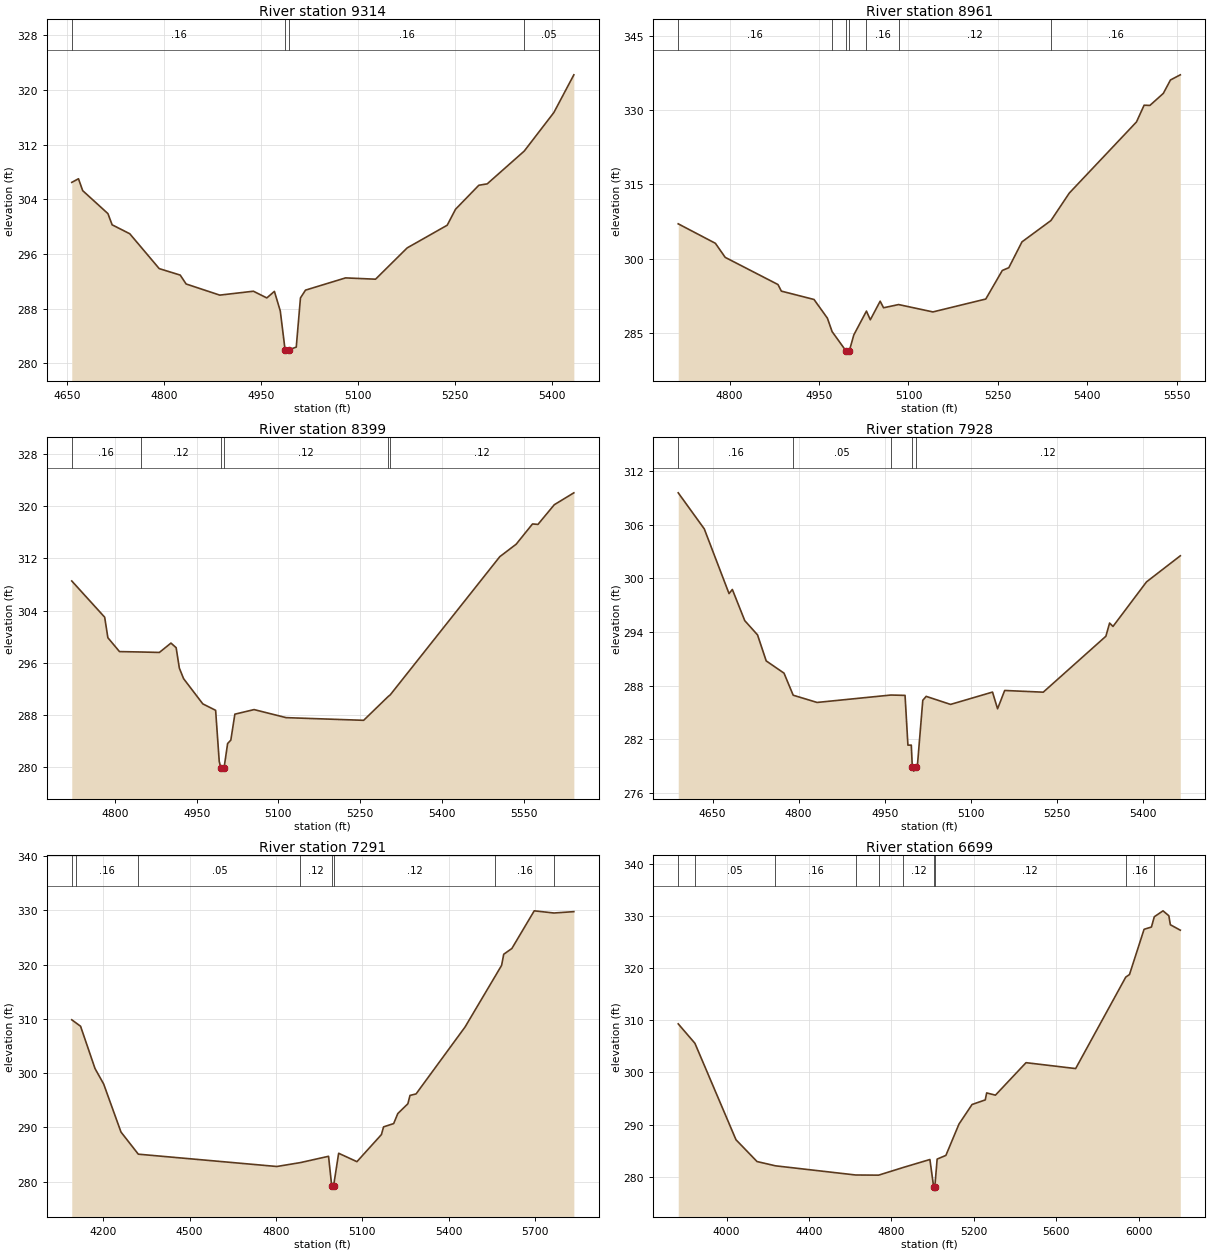
Type RM Length L Ch R = 1,9314,353,353,353
BEGIN DESCRIPTION:
UNT183 IN CCTC 7.0
END DESCRIPTION:
XS GIS Cut Line= 3
      3581349.60     10670810.21      3581449.61     10670460.19
      3581349.62     10670060.22
#Sta/Elev= 30
  4657.3  306.50  4667.7  307.03  4674.2  305.29  4713.2  301.93  4719.7  300.29
  4747.0  298.98  4792.5  293.88  4825.0  292.93  4834.1  291.63  4886.1  290.00
  4938.1  290.57  4958.9  289.59  4970.6  290.55  4979.7  287.68  4987.1  282.01
  4989.9  281.51  4993.1  282.01  5004.4  282.39  5010.9  289.59  5018.7  290.73
  5080.6  292.52  5127.0  292.33  5175.9  296.91  5237.8  300.23  5250.7  302.57
  5286.7  306.08  5299.6  306.28  5356.9  311.08  5402.7  316.72  5433.6  322.24
#Mann=4,-1,0
  4657.3    0.16       0  4987.1    0.07       0  4993.1    0.16       0
  5356.9    0.05       0
Bank Sta=4987.1,4993.1
Exp/Cntr=0.3,0.1

Type RM Length L Ch R = 1,8961,562,562,562
BEGIN DESCRIPTION:
UNT183 IN CCTC 6.0
END DESCRIPTION:
XS GIS Cut Line= 2
      3581576.92     10670932.33      3581964.46     10670184.93
#Sta/Elev= 30
  4713.9  307.03  4776.2  303.09  4792.7  300.24  4881.2  294.74  4886.8  293.41
  4941.6  291.72  4964.0  287.94  4971.9  285.22  4994.9  281.36  4997.7  280.86
  5000.9  281.36  5008.3  284.54  5029.5  289.37  5036.0  287.61  5052.5  291.37
  5058.2  290.04  5083.4  290.69  5141.0  289.20  5229.6  291.81  5257.3  297.59
  5268.2  298.15  5290.3  303.38  5338.9  307.70  5369.6  313.25  5482.3  327.65
  5495.1  331.04  5504.8  331.00  5527.3  333.43  5539.3  336.15  5555.8  337.19
#Mann=7,-1,0
  4713.9    0.16       0  4971.9    0.12       0  4994.9    0.07       0
  5000.9    0.12       0  5029.5    0.16       0  5083.4    0.12       0
  5338.9    0.16       0
Bank Sta=4994.9,5000.9
Exp/Cntr=0.3,0.1

Type RM Length L Ch R = 1,8399,471,471,471
BEGIN DESCRIPTION:
UNT183 IN CCTC 5.0
END DESCRIPTION:
XS GIS Cut Line= 3
      3581961.58     10671144.65      3582176.87     10670797.41
      3582169.93     10670284.32
#Sta/Elev= 30
  4720.7  308.52  4781.1  302.98  4787.0  299.84  4808.3  297.72  4847.2  297.66
  4881.5  297.59  4902.8  299.02  4912.3  298.32  4918.2  295.19  4926.0  293.58
  4961.3  289.72  4984.8  288.74  4991.4  280.94  4994.3  279.94  4997.0  279.44
  5000.3  279.94  5006.8  283.66  5012.7  284.18  5020.1  288.15  5055.4  288.85
  5114.2  287.62  5256.5  287.21  5301.8  290.87  5305.2  291.09  5506.5  312.24
  5536.5  314.14  5566.5  317.24  5576.5  317.17  5606.5  320.18  5642.4  322.00
#Mann=6,-1,0
  4720.7    0.16       0  4847.2    0.12       0  4994.3    0.07       0
  5000.3    0.12       0  5301.8    0.16       0  5305.2    0.12       0
Bank Sta=4994.3,5000.3
Exp/Cntr=0.3,0.1

Type RM Length L Ch R = 1,7928,637,637,637
BEGIN DESCRIPTION:
UNT183 IN CCTC 4.0
END DESCRIPTION:
XS GIS Cut Line= 3
      3582099.60     10671260.19      3582449.61     10671060.19
      3582849.59     10670810.20
#Sta/Elev= 30
  4590.3  309.59  4635.7  305.55  4678.8  298.31  4684.6  298.77  4706.2  295.28
  4728.5  293.68  4743.6  290.77  4774.6  289.40  4790.6  286.93  4832.2  286.12
  4961.0  286.95  4985.5  286.91  4990.5  281.34  4996.4  281.34  4998.1  278.93
  5000.8  278.43  5004.1  278.93  5007.0  279.03  5016.4  286.36  5022.3  286.80
  5064.8  285.90  5137.9  287.28  5146.7  285.41  5159.1  287.46  5226.3  287.27
  5335.4  293.53  5341.9  295.01  5347.8  294.63  5406.2  299.62  5465.1  302.54
#Mann=5,-1,0
  4590.3    0.16       0  4790.6    0.05       0  4961.0    0.12       0
  4998.1    0.07       0  5004.1    0.12       0
Bank Sta=4998.1,5004.1
Exp/Cntr=0.3,0.1

Type RM Length L Ch R = 1,7291,592,592,592
BEGIN DESCRIPTION:
UNT183 IN CCTC 2.0
END DESCRIPTION:
XS GIS Cut Line= 3
      3582149.13     10671346.03      3582864.37     10671401.58
      3583558.59     10670644.88
#Sta/Elev= 30
  4090.7  309.82  4106.7  309.20  4121.3  308.63  4171.4  300.85  4201.5  297.99
  4261.7  289.14  4321.9  285.06  4803.2  282.79  4885.2  283.51  4982.8  284.67
  4994.0  279.12  4996.7  278.62  5000.0  279.12  5017.9  285.23  5081.4  283.68
  5166.5  288.67  5173.9  290.09  5209.1  290.70  5223.3  292.54  5258.4  294.35
  5265.8  295.89  5286.8  296.16  5457.0  308.49  5562.3  317.90  5584.0  319.85
  5591.4  321.90  5619.7  322.96  5697.4  329.90  5765.8  329.50  5835.0  329.75
#Mann=8,-1,0
  4090.7    0.05       0  4106.7    0.16       0  4321.9    0.05       0
  4885.2    0.12       0  4994.0    0.07       0  5000.0    0.12       0
  5562.3    0.16       0  5765.8    0.12       0
Bank Sta=4994,5000
Exp/Cntr=0.3,0.1

Type RM Length L Ch R = 1,6699,848,848,848
BEGIN DESCRIPTION:
Mapping XS 3c80d7d0
END DESCRIPTION:
XS GIS Cut Line= 3
      3582091.69     10671385.78      3583003.20     10671906.64
      3584021.77     10670963.92
#Sta/Elev= 30
  3765.2  309.30  3846.2  305.58  4045.6  287.08  4147.8  282.90  4237.3  282.08
  4626.5  280.32  4738.0  280.29  4858.2  281.77  4987.1  283.29  5005.1  278.11
  5007.9  277.61  5011.1  278.11  5022.3  283.37  5064.8  284.08  5128.3  290.09
  5191.8  293.84  5255.9  294.72  5262.7  296.06  5305.2  295.63  5453.8  301.86
  5694.7  300.73  5938.1  318.27  5956.1  318.76  6027.0  327.44  6062.7  327.87
  6076.6  329.84  6118.9  330.98  6147.2  330.04  6154.6  328.31  6202.9  327.27
#Mann=10,-1,0
  3765.2    0.16       0  3846.2    0.05       0  4237.3    0.16       0
  4626.5     0.1       0  4738.0    0.16       0  4858.2    0.12       0
  5005.1    0.07       0  5011.1    0.12       0  5938.1    0.16       0
  6076.6    0.05       0
Bank Sta=5005.1,5011.1
Exp/Cntr=0.3,0.1

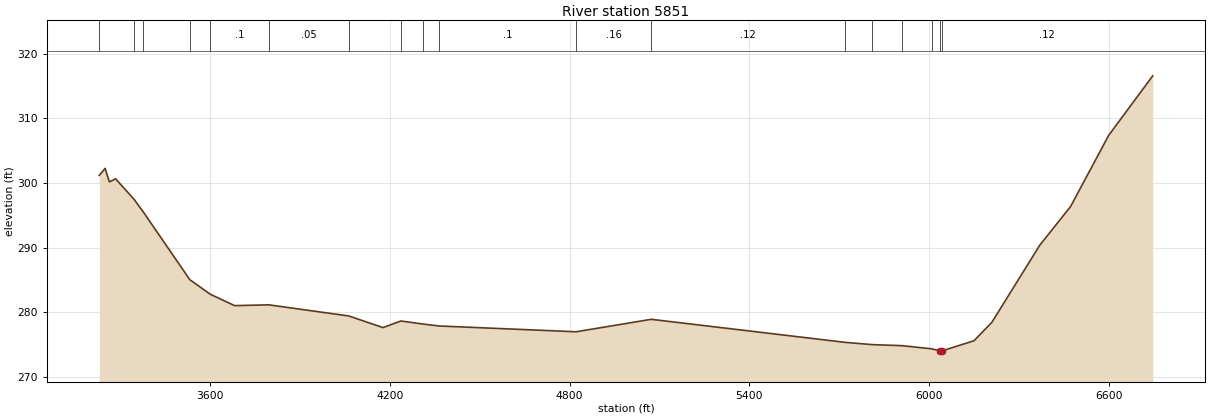
Type RM Length L Ch R = 1,5851,0,0,0
BEGIN DESCRIPTION:
UNT183 IN CCTC 1.0
END DESCRIPTION:
XS GIS Cut Line= 3
      3582070.01     10671472.59      3583133.40     10672405.77
      3585236.48     10672416.62
#Sta/Elev= 30
  3229.8  301.18  3249.1  302.26  3263.3  300.17  3284.2  300.64  3345.8  297.47
  3376.5  295.52  3532.1  285.02  3600.3  282.77  3681.6  281.01  3796.0  281.13
  4062.8  279.41  4177.1  277.61  4236.7  278.63  4310.2  278.16  4363.9  277.86
  4822.1  276.96  5072.8  278.89  5721.0  275.32  5811.5  274.97  5910.4  274.81
  6009.4  274.32  6037.8  274.00  6040.6  273.50  6043.8  274.00  6150.8  275.57
  6210.8  278.45  6370.8  290.39  6473.3  296.35  6600.8  307.39  6747.7  316.59
#Mann=18,-1,0
  3229.8    0.16       0  3345.8    0.05       0  3376.5    0.16       0
  3532.1    0.05       0  3600.3     0.1       0  3796.0    0.05       0
  4062.8    0.16       0  4236.7    0.12       0  4310.2    0.16       0
  4363.9     0.1       0  4822.1    0.16       0  5072.8    0.12       0
  5721.0     0.1       0  5811.5    0.05       0  5910.4    0.16       0
  6009.4    0.12       0  6037.8    0.07       0  6043.8    0.12       0
Bank Sta=6037.8,6043.8
Exp/Cntr=0.3,0.1

Chan Stop Cuts=-1