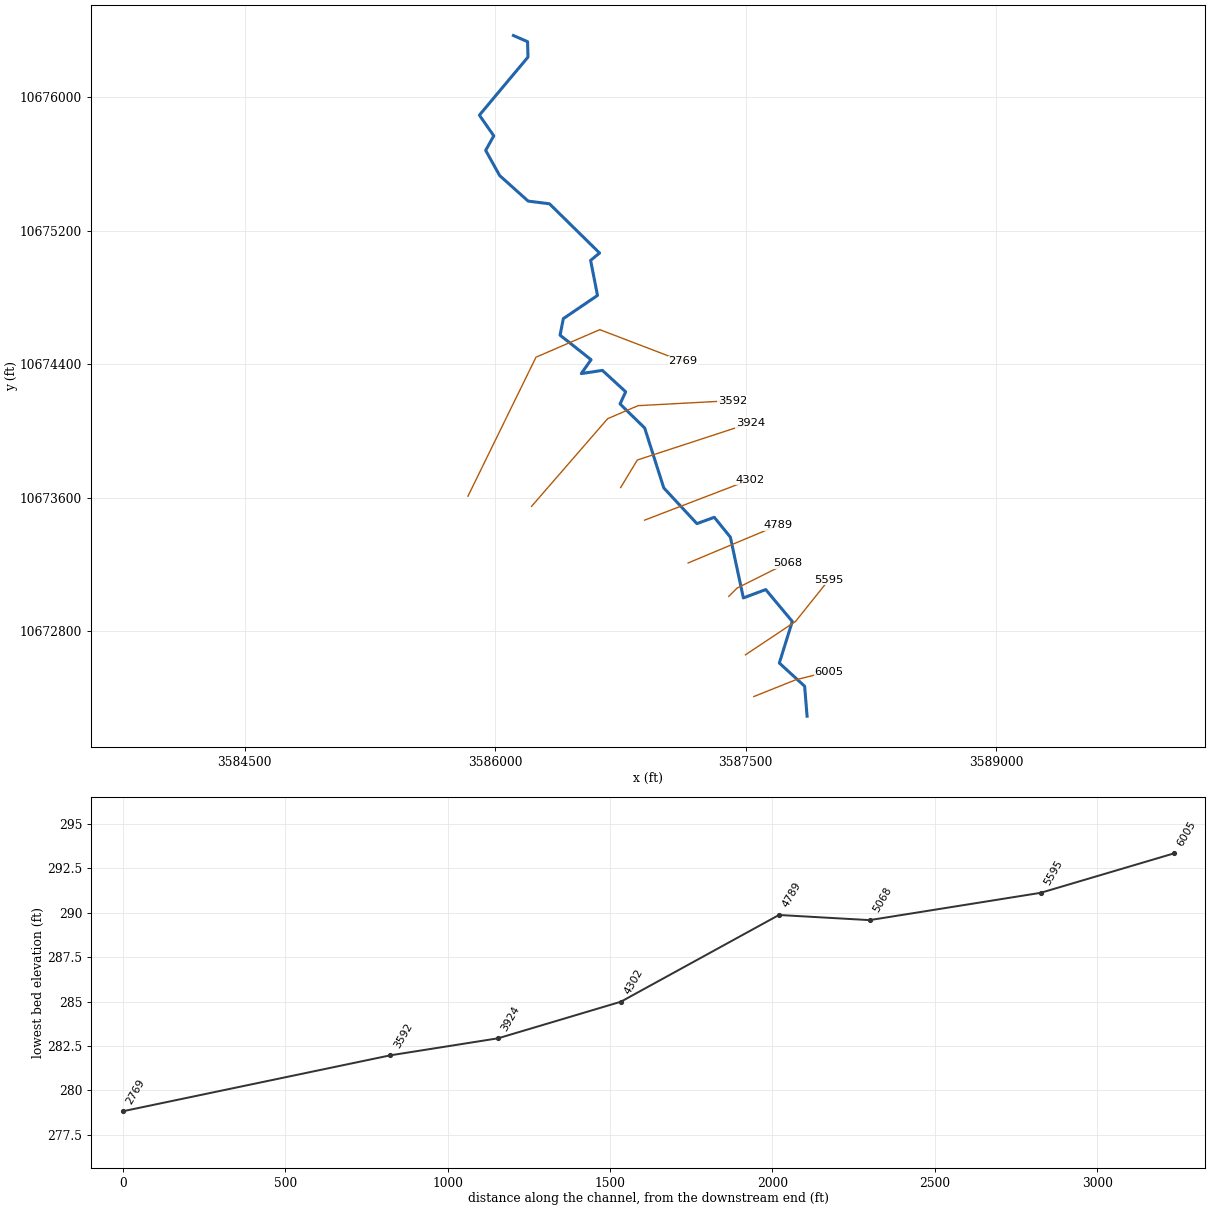
--- UNT185 IN CCTC.prj (project) ---

Proj Title=UNT185 IN CCTC Base Level Engineering
Current Plan=p01
Default Exp/Contr=0.3,0.1
English Units
Geom File=g01
Flow File=f01
Plan File=p01
Y Axis Title=Elevation
X Axis Title(PF)=Main Channel Distance
X Axis Title(XS)=Station
BEGIN DESCRIPTION:
UNT185 IN CCTC
END DESCRIPTION:
DSS Export Rating Curves= 0
DSS Export Rating Curve Sorted= 0
DSS Export Volume Flow Curves= 0
DXF OffsetX= 0
DXF OffsetY= 0
DXF ScaleX= 1
DXF ScaleY= 10

--- UNT185 IN CCTC.p01 (plan) ---

Plan Title=Multiple Run
Short Identifier=Multiple
Geom File=g01
Flow File=f01
Subcritical Flow
K Sum by GR= 0
Std Step Tol= 0.01
Critical Tol= 0.01
Num of Std Step Trials= 20
Max Error Tol= 0.3
Flow Tol Ratio= 0.001
Split Flow NTrial= 30
Split Flow Tol= 0.02
Split Flow Ratio= 0.02
Log Output Level= 0
Friction Slope Method= 1
Unsteady Friction Slope Method= 2
Unsteady Bridges Friction Slope Method= 1
Parabolic Critical Depth
Global Vel Dist=  1 , 1 , 1
Global Log Level= 0
CheckData=True
Encroach Param= -1, 0, 0, 0
BEGIN DESCRIPTION:
Multiple Run
END DESCRIPTION:

--- UNT185 IN CCTC.f01 (steady flow) ---

Flow Title=Multiple
Program Version=4.10
Number of Profiles= 7
Profile Names=10-year,25-year,50-year,1pct_min,100-year,1pct_plu,500-year
River Rch & RM=UNT185 IN CCTC,Reach-1         ,6005
    1180    1605    1952    1733    2343    3169    3365
Boundary for River Rch & Prof#=UNT185 IN CCTC,Reach-1         , 1
Up Type= 0
Dn Type= 3
Dn Slope=0.0057
Boundary for River Rch & Prof#=UNT185 IN CCTC,Reach-1         , 2
Up Type= 0
Dn Type= 3
Dn Slope=0.0057
Boundary for River Rch & Prof#=UNT185 IN CCTC,Reach-1         , 3
Up Type= 0
Dn Type= 3
Dn Slope=0.0057
Boundary for River Rch & Prof#=UNT185 IN CCTC,Reach-1         , 4
Up Type= 0
Dn Type= 3
Dn Slope=0.0057
Boundary for River Rch & Prof#=UNT185 IN CCTC,Reach-1         , 5
Up Type= 0
Dn Type= 3
Dn Slope=0.0057
Boundary for River Rch & Prof#=UNT185 IN CCTC,Reach-1         , 6
Up Type= 0
Dn Type= 3
Dn Slope=0.0057
Boundary for River Rch & Prof#=UNT185 IN CCTC,Reach-1         , 7
Up Type= 0
Dn Type= 3
Dn Slope=0.0057
DSS Import GetInterval= 0
DSS Import GetPeak= 0
DSS Import FillOption= 0

--- UNT185 IN CCTC.g01 (geometry) ---

Geom Title=Existing Conditions
Program Version=4.10

River Reach=UNT185 IN CCTC  ,Reach-1
Reach XY= 30
      3587868.75     10672292.51        3587854.       10672472.
       3587702.5       10672611.        3587780.       10672860.
        3587621.       10673051.        3587487.       10673001.
      3587409.25       10673365.      3587312.75       10673484.
      3587208.75       10673446.      3587010.25       10673660.
      3586895.75       10674019.       3586748.5       10674163.
        3586782.       10674236.       3586642.5       10674364.
        3586516.       10674345.      3586574.75       10674428.
        3586389.       10674575.       3586408.5       10674674.
      3586613.25       10674813.        3586572.       10675023.
      3586625.75       10675067.       3586325.5       10675362.
        3586198.       10675378.      3586027.25       10675531.
      3585943.25       10675682.        3585992.       10675769.
      3585905.75       10675893.        3586197.       10676241.
      3586194.25       10676333.       3586109.5       10676370.

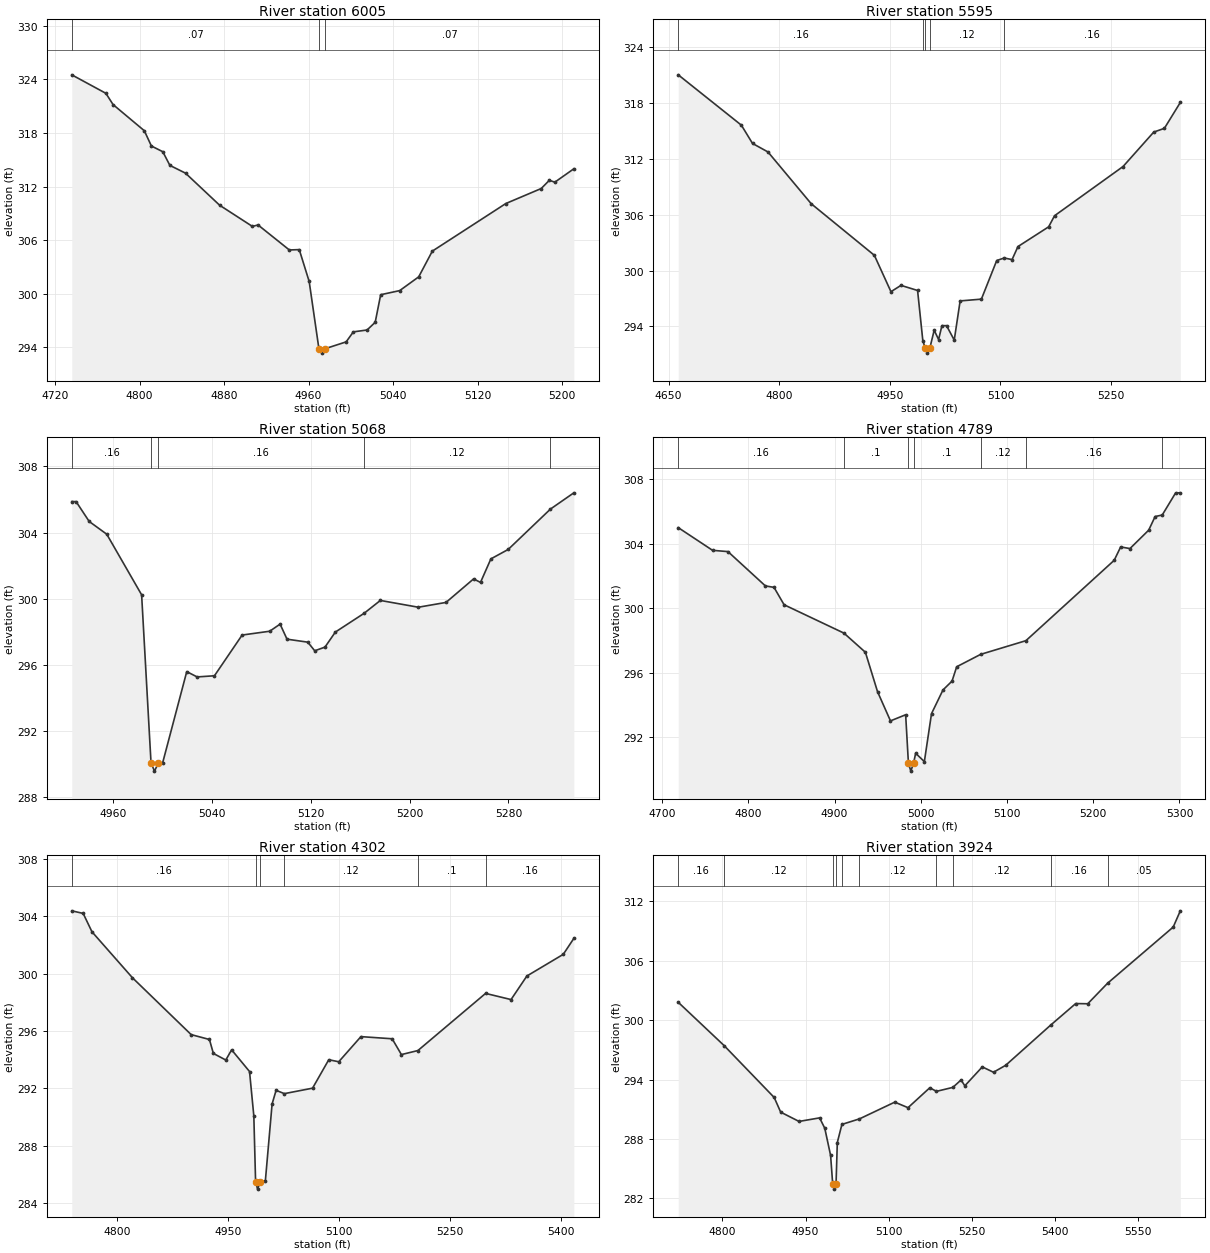
Type RM Length L Ch R = 1 ,6005    ,410,410,410
BEGIN DESCRIPTION:
UNT185 IN CCTC 8.0
END DESCRIPTION:
XS GIS Cut Line= 3
       3587549.6     10672410.18      3587799.61     10672510.19
      3587999.58     10672560.18
#Sta/Elev= 30
  4735.8  324.51  4768.1  322.44  4774.9  321.18  4804.5  318.25  4811.2  316.54
    4822   315.9  4828.7  314.37  4843.5   313.5  4875.8  309.91  4906.8  307.54
  4912.2   307.7  4941.8   304.9  4951.2  304.94  4960.6  301.37  4969.8  293.85
  4972.5  293.35  4975.8  293.85  4995.6  294.61  5002.4  295.73  5015.4  295.94
  5023.1   296.8  5028.3  299.89  5046.3  300.35  5064.3  301.89  5077.2  304.77
  5146.8   310.1  5180.3  311.78    5188   312.7  5193.2  312.49  5211.2  313.99
#Mann= 3 ,-1 , 0
  4735.8     .07       0  4969.8     .07       0  4975.8     .07       0
Bank Sta=4969.8,4975.8
XS Rating Curve= 0 ,0
Exp/Cntr=0.3,0.1

Type RM Length L Ch R = 1 ,5595    ,527,527,527
BEGIN DESCRIPTION:
UNT185 IN CCTC 7.0
END DESCRIPTION:
XS GIS Cut Line= 3
      3587499.61     10672660.19      3587799.61     10672860.19
       3587999.6     10673110.18
#Sta/Elev= 30
  4663.1  321.03  4748.7  315.62  4763.8  313.66  4784.8  312.74  4843.4  307.18
    4929  301.64  4951.5  297.73  4965.1  298.41  4987.6  297.86  4994.7  292.48
  4998.1  291.63  5000.9  291.13  5004.1  291.63  5010.1  293.59  5016.1  292.59
  5020.6  294.08  5026.9  294.08  5037.3  292.53  5045.3  296.74  5074.1  296.93
  5094.9  301.08    5105  301.35  5115.7  301.18  5123.7  302.58  5165.3   304.7
  5173.3  305.89  5266.2  311.18  5307.8  314.88  5322.2  315.28  5343.8  318.06
#Mann= 5 ,-1 , 0
  4663.1     .16       0  4994.7     .12       0  4998.1     .07       0
  5004.1     .12       0    5105     .16       0
Bank Sta=4998.1,5004.1
XS Rating Curve= 0 ,0
Exp/Cntr=0.3,0.1

Type RM Length L Ch R = 1 ,5068    ,279,279,279
BEGIN DESCRIPTION:
UNT185 IN CCTC 6.0
END DESCRIPTION:
XS GIS Cut Line= 3
      3587399.63     10673010.21      3587449.61     10673060.19
      3587749.61     10673210.19
#Sta/Elev= 30
  4926.8  305.87  4930.3  305.87  4940.9  304.67  4955.1   303.9  4983.3  300.24
  4990.9  290.09  4993.7  289.59  4996.9  290.09  5000.3  290.09  5019.8   295.6
  5028.2  295.28  5042.2  295.35  5064.6  297.81  5086.9  298.04  5095.3  298.47
  5100.9  297.56  5117.7  297.38  5123.3  296.86  5131.6  297.08    5140  297.99
  5163.2  299.12  5176.4   299.9  5207.1  299.49  5229.5  299.78  5251.8   301.2
  5257.4  300.99  5265.8  302.41  5279.8  302.98    5314  305.42  5332.9   306.4
#Mann= 5 ,-1 , 0
  4926.8     .16       0  4990.9     .07       0  4996.9     .16       0
  5163.2     .12       0    5314     .16       0
Bank Sta=4990.9,4996.9
XS Rating Curve= 0 ,0
Exp/Cntr=0.3,0.1

Type RM Length L Ch R = 1 ,4789    ,487,487,487
BEGIN DESCRIPTION:
UNT185 IN CCTC 5.0
END DESCRIPTION:
XS GIS Cut Line= 2
      3587156.36     10673210.44      3587693.45     10673435.67
#Sta/Elev= 30
  4718.6     305  4758.4  303.59  4776.3  303.51  4819.7  301.38  4829.7  301.29
  4841.4  300.21  4910.8  298.45  4935.7  297.26  4949.8  294.81  4964.8     293
  4982.4  293.38  4985.6  290.38  4988.4  289.88  4991.6  290.38    4994  290.99
  5004.1  290.47  5012.4  293.45  5025.7  294.92  5036.2  295.47  5041.6  296.36
  5069.4  297.13  5121.9  297.98  5224.3  302.97  5231.8   303.8  5242.6   303.7
  5264.3  304.84  5271.8  305.69    5280  305.78  5295.6  307.16    5301  307.16
#Mann= 7 ,-1 , 0
  4718.6     .16       0  4910.8      .1       0  4985.6     .07       0
  4991.6      .1       0  5069.4     .12       0  5121.9     .16       0
    5280     .05       0
Bank Sta=4985.6,4991.6
XS Rating Curve= 0 ,0
Exp/Cntr=0.3,0.1

Type RM Length L Ch R = 1 ,4302    ,378,378,378
BEGIN DESCRIPTION:
UNT185 IN CCTC 4.0
END DESCRIPTION:
XS GIS Cut Line= 2
      3586895.22     10673466.88       3587528.9     10673709.94
#Sta/Elev= 30
  4738.5  304.37  4753.9  304.19  4765.8  302.91  4820.5  299.71  4899.9  295.75
  4924.6  295.41  4929.9  294.44  4946.7  293.98  4954.6  294.69  4978.8  293.18
  4984.6  290.09    4987  285.49  4989.7  284.99    4993  285.49  5000.2  285.57
  5009.3  290.92  5014.7  291.87  5025.9  291.64    5064  292.02  5085.9     294
  5099.4  293.86  5129.4  295.61  5171.6  295.46  5184.1  294.36  5206.4  294.64
  5297.9  298.62  5332.3  298.19  5353.7  299.83  5402.9  301.34  5417.2  302.45
#Mann= 6 ,-1 , 0
  4738.5     .16       0    4987     .07       0    4993     .16       0
  5025.9     .12       0  5206.4      .1       0  5297.9     .16       0
Bank Sta=4987,4993
XS Rating Curve= 0 ,0
Exp/Cntr=0.3,0.1

Type RM Length L Ch R = 1 ,3924    ,332,332,332
BEGIN DESCRIPTION:
UNT185 IN CCTC 3.0
END DESCRIPTION:
XS GIS Cut Line= 3
      3586751.96     10673662.16       3586851.8     10673827.11
      3587528.92     10674048.48
#Sta/Elev= 30
  4720.5  301.81  4803.1  297.44  4893.5  292.19  4905.2  290.71  4938.3  289.77
  4975.4  290.13  4984.7  289.08  4995.2  286.34    4999  283.43  5001.8  282.93
    5005  283.43  5007.3  287.64  5015.6  289.47  5047.3  290.03  5110.9  291.72
  5134.8  291.16    5174  293.17  5186.1  292.81  5215.6  293.21  5230.4  293.96
  5237.2  293.37  5268.7  295.28  5288.9  294.74  5310.8  295.44  5391.7  299.49
  5437.1  301.68  5458.8  301.66  5494.5  303.73  5612.9  309.41  5625.7  311.05
#Mann= 10 ,-1 , 0
  4720.5     .16       0  4803.1     .12       0    4999     .07       0
    5005     .12       0  5015.6     .16       0  5047.3     .12       0
  5186.1     .08       0  5215.6     .12       0  5391.7     .16       0
  5494.5     .05       0
Bank Sta=4999,5005
XS Rating Curve= 0 ,0
Exp/Cntr=0.3,0.1

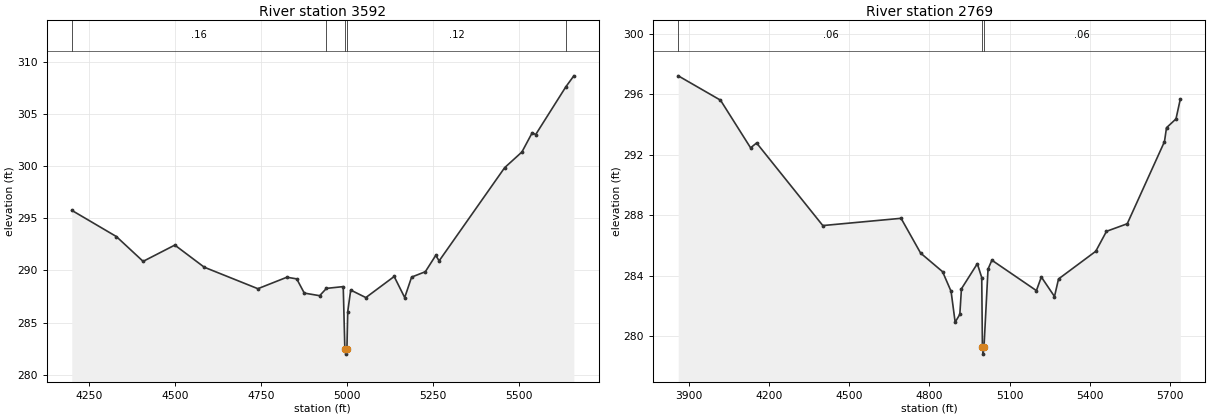
Type RM Length L Ch R = 1 ,3592    ,823,823,823
BEGIN DESCRIPTION:
UNT185 IN CCTC 2.0
END DESCRIPTION:
XS GIS Cut Line= 4
      3586218.11     10673549.33      3586673.84     10674074.51
      3586856.14     10674152.64      3587420.34     10674183.02
#Sta/Elev= 30
  4199.5  295.75    4329  293.24  4406.8  290.86  4498.9  292.42  4584.4   290.3
  4740.2  288.24  4824.6  289.34  4853.1  289.18    4875  287.82  4919.7  287.57
  4939.4  288.27  4988.2  288.44  4992.9  282.47  4995.6  281.97  4998.9  282.47
  5001.3  286.05  5009.9  288.11  5053.9  287.39  5136.2  289.41  5166.8  287.39
  5186.8  289.35  5226.8  289.87  5256.9  291.43  5266.9  290.91  5457.2  299.84
  5507.3  301.34  5537.3  303.19  5547.3  303.01  5635.2   307.6  5658.2  308.64
#Mann= 5 ,-1 , 0
  4199.5     .16       0  4939.4     .12       0  4992.9     .07       0
  4998.9     .12       0  5635.2     .05       0
Bank Sta=4992.9,4998.9
XS Rating Curve= 0 ,0
Exp/Cntr=0.3,0.1

Type RM Length L Ch R = 1 ,2769    ,0,0,0
BEGIN DESCRIPTION:
UNT185 IN CCTC 1.0
END DESCRIPTION:
XS GIS Cut Line= 4
       3585836.9     10673609.75      3586244.88     10674443.07
      3586626.82       10674608.      3587124.88     10674417.53
#Sta/Elev= 30
  3860.8  297.22  4018.8  295.61  4131.3  292.46  4153.8  292.78  4401.3  287.32
  4693.9   287.8    4767   285.5  4849.1  284.27  4880.9  282.97  4896.1  280.93
  4913.6  281.45  4919.6  283.14    4979   284.8  4995.5  283.88    4998  279.32
  5000.7  278.82    5004  279.32    5019  284.44  5033.4  285.03  5199.9  283.02
  5218.3  283.92  5267.5  282.63  5282.6  283.79  5421.8  285.62  5461.9  286.94
  5539.5  287.44  5678.7  292.87  5686.3  293.79  5721.7  294.37  5737.9  295.68
#Mann= 3 ,-1 , 0
  3860.8     .06       0    4998     .05       0    5004     .06       0
Bank Sta=4998,5004
XS Rating Curve= 0 ,0
Exp/Cntr=0.3,0.1

Chan Stop Cuts=-1
Use User Specified Reach Order=0
Composite Channel Slope=5