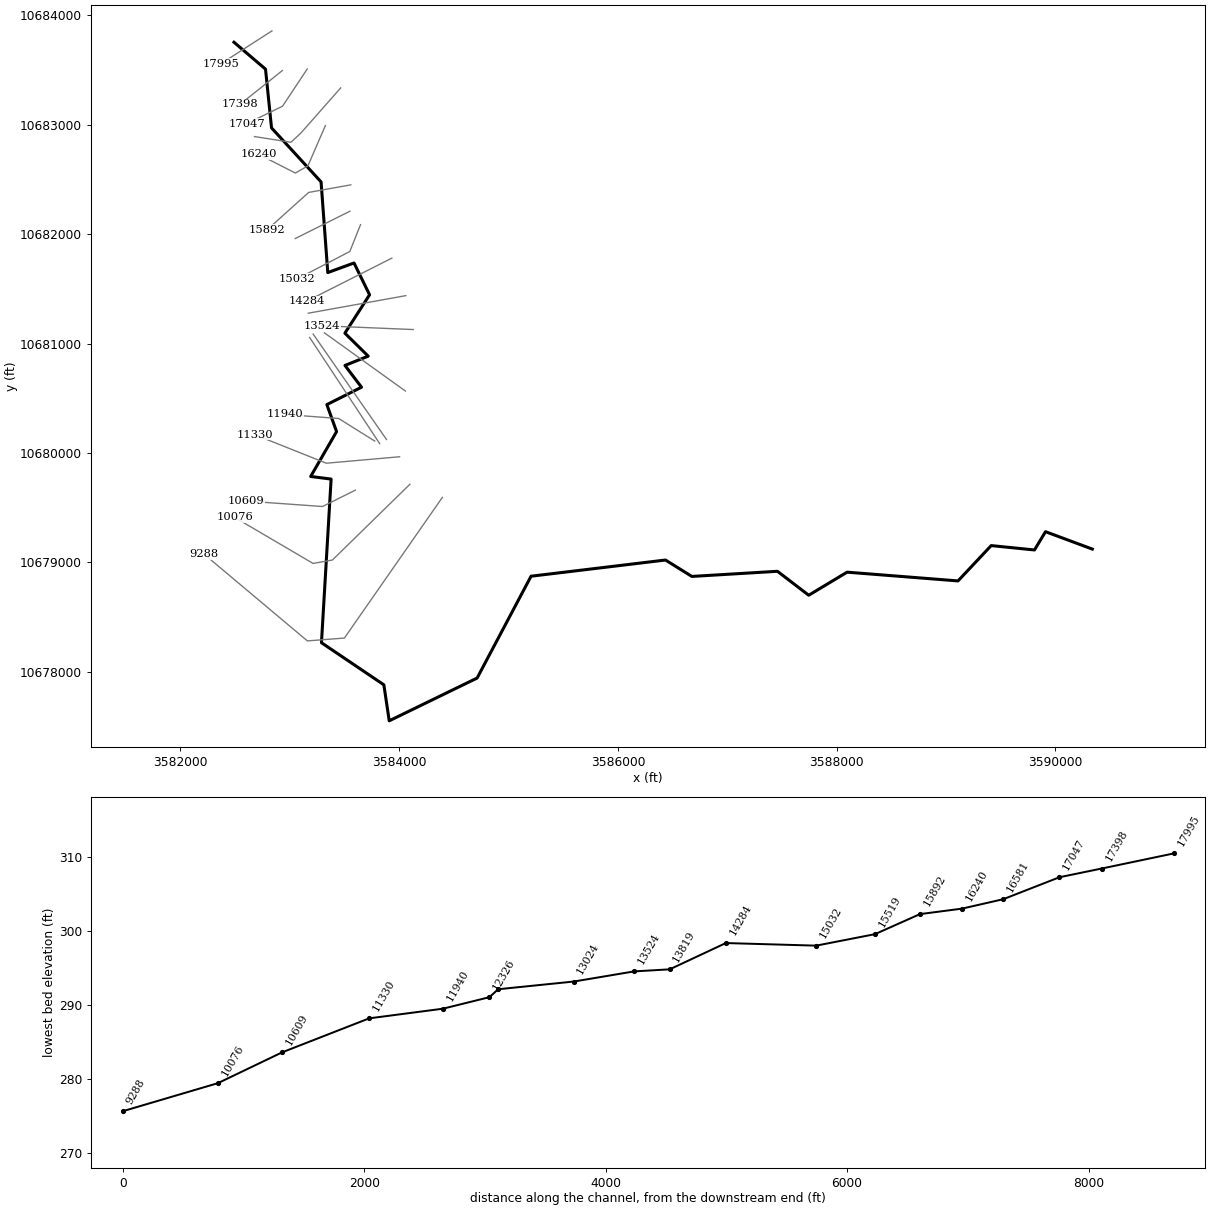
--- UNT186 IN CCTC.prj (project) ---

Proj Title=UNT186 IN CCTC Base Level Engineering
Current Plan=p01
Default Exp/Contr=0.3,0.1
English Units
Geom File=g01
Flow File=f01
Plan File=p01
BEGIN DESCRIPTION:
UNT186 IN CCTC
END DESCRIPTION:

--- UNT186 IN CCTC.p01 (plan) ---

Plan Title=Multiple Run
Short Identifier=Multiple
Geom File=g01
Flow File=f01
Subcritical Flow
K Sum by GR= 0
Std Step Tol= 0.01
Critical Tol= 0.01
Num of Std Step Trials= 20
Max Error Tol= 0.3
Flow Tol Ratio= 0.001
Split Flow NTrial= 30
Split Flow Tol= 0.02
Split Flow Ratio= 0.02
Log Output Level= 0
Friction Slope Method= 1
Unsteady Friction Slope Method= 2
Unsteady Bridges Friction Slope Method= 1
Parabolic Critical Depth
Global Vel Dist=  1 , 1 , 1
Global Log Level= 0
CheckData=True
Encroach Param= -1, 0, 0, 0
BEGIN DESCRIPTION:
Multiple Run
END DESCRIPTION:

--- UNT186 IN CCTC.f01 (steady flow) ---

Flow Title=Multiple
Number of Profiles=7
Profile Names=10-year,25-year,50-year,1pct_min,100-year,1pct_plu,500-year
River Rch & RM= UNT186 IN CCTC,Reach-1,17995
    1240    1695    2068    1842    2492    3369    3603
River Rch & RM= UNT186 IN CCTC,Reach-1,11940
    1629    2252    2768    2480    3354    4535    4908
Boundary for River Rch & Prof#=UNT186 IN CCTC,Reach-1,1
Up Type=0
Dn Type=3
Dn Slope=0.005
Boundary for River Rch & Prof#=UNT186 IN CCTC,Reach-1,2
Up Type=0
Dn Type=3
Dn Slope=0.005
Boundary for River Rch & Prof#=UNT186 IN CCTC,Reach-1,3
Up Type=0
Dn Type=3
Dn Slope=0.005
Boundary for River Rch & Prof#=UNT186 IN CCTC,Reach-1,4
Up Type=0
Dn Type=3
Dn Slope=0.005
Boundary for River Rch & Prof#=UNT186 IN CCTC,Reach-1,5
Up Type=0
Dn Type=3
Dn Slope=0.005
Boundary for River Rch & Prof#=UNT186 IN CCTC,Reach-1,6
Up Type=0
Dn Type=3
Dn Slope=0.005
Boundary for River Rch & Prof#=UNT186 IN CCTC,Reach-1,7
Up Type=0
Dn Type=3
Dn Slope=0.005

--- UNT186 IN CCTC.g01 (geometry) ---

Geom Title=Existing Conditions

River Reach=UNT186 IN CCTC,Reach-1
Reach XY= 30
      3582489.75     10683755.00      3582778.00     10683509.00
      3582833.00     10682972.00      3583286.00     10682478.00
      3583347.25     10681649.00      3583587.25     10681737.00
      3583729.25     10681446.00      3583503.75     10681095.00
      3583717.00     10680885.00      3583504.50     10680800.00
      3583655.75     10680601.00      3583338.75     10680442.00
      3583427.75     10680195.00      3583191.00     10679785.00
      3583377.75     10679761.00      3583289.50     10678265.00
      3583860.00     10677880.00      3583909.00     10677551.00
      3584712.75     10677942.00      3585205.75     10678873.00
      3586435.00     10679021.00      3586676.00     10678871.00
      3587458.50     10678918.00      3587744.50     10678699.00
      3588095.00     10678910.00      3589109.25     10678830.00
      3589412.75     10679153.00      3589808.50     10679113.00
      3589909.25     10679280.00      3590337.25     10679121.00

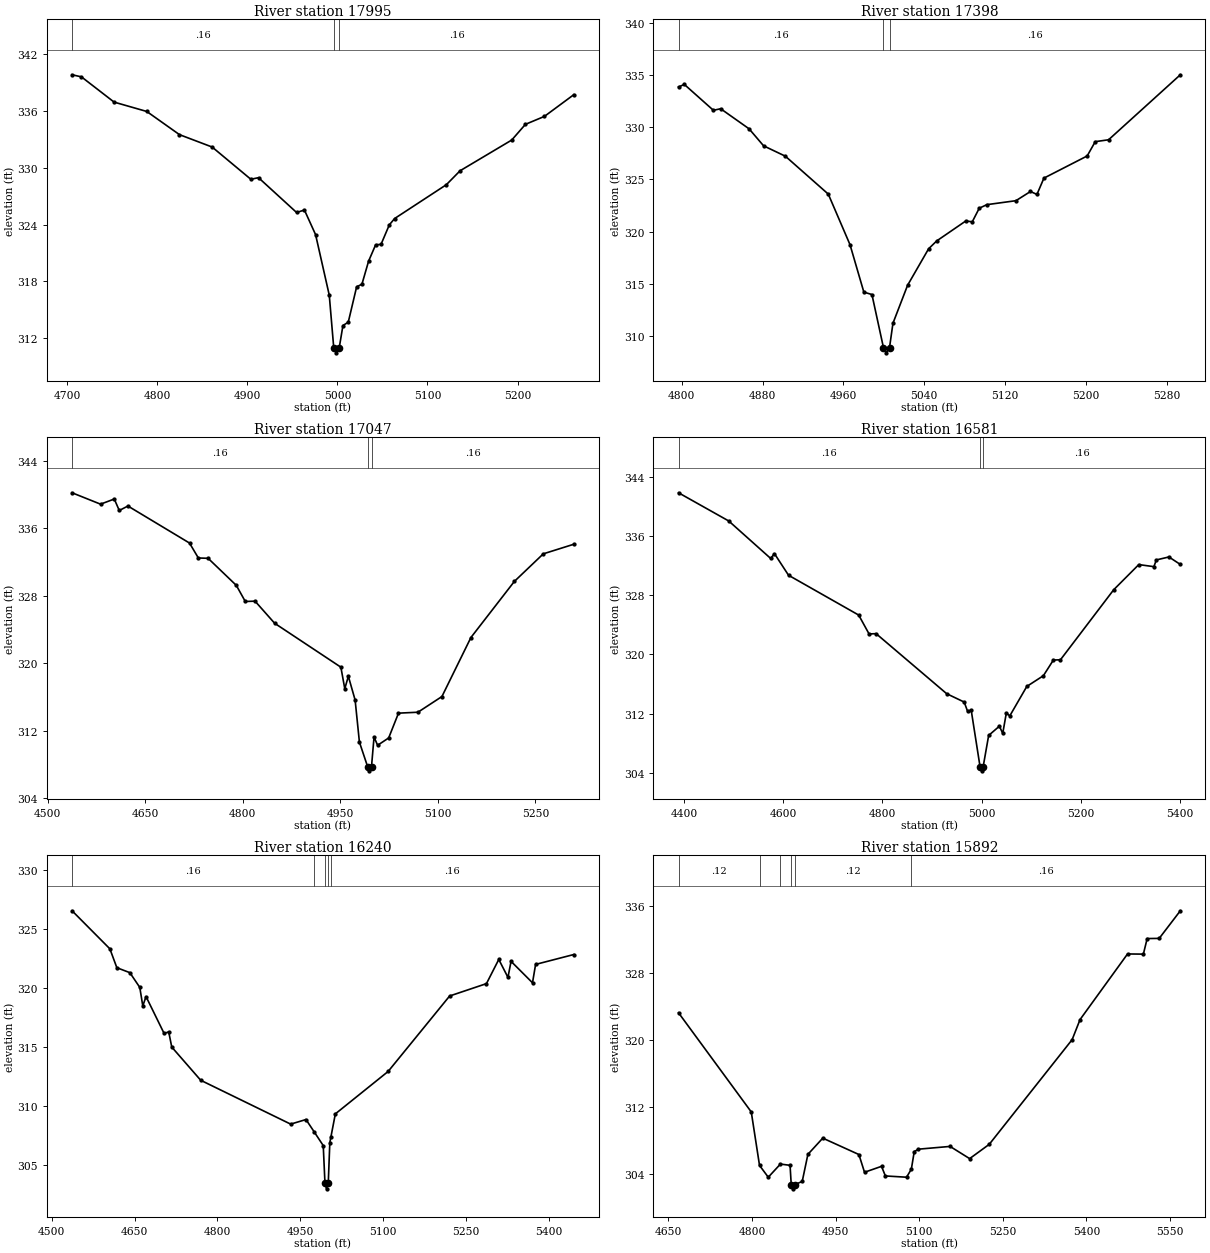
Type RM Length L Ch R = 1,17995,597,597,597
BEGIN DESCRIPTION:
UNT186 IN CCTC 19.0
END DESCRIPTION:
XS GIS Cut Line= 2
      3582836.63     10683858.67      3582367.90     10683557.03
#Sta/Elev= 30
  4705.2  339.85  4715.6  339.63  4751.9  336.96  4788.2  335.97  4824.5  333.52
  4860.8  332.21  4903.8  328.80  4912.3  328.97  4954.6  325.29  4963.3  325.55
  4975.7  322.95  4990.9  316.55  4995.9  310.95  4998.7  310.45  5001.9  310.95
  5006.1  313.34  5012.0  313.69  5021.3  317.43  5027.2  317.71  5034.6  320.15
  5042.4  321.87  5048.4  321.92  5057.6  323.98  5063.5  324.65  5121.0  328.23
  5136.2  329.70  5193.6  332.95  5208.8  334.61  5229.9  335.45  5262.6  337.75
#Mann=3,-1,0
  4705.2    0.16       0  4995.9    0.07       0  5001.9    0.16       0
Bank Sta=4995.9,5001.9
Exp/Cntr=0.3,0.1

Type RM Length L Ch R = 1,17398,351,351,351
BEGIN DESCRIPTION:
Mapping XS f01c4a3b
END DESCRIPTION:
XS GIS Cut Line= 2
      3582932.16     10683496.28      3582544.17     10683186.32
#Sta/Elev= 30
  4796.8  333.85  4802.5  334.10  4831.3  331.62  4838.5  331.77  4866.6  329.85
  4881.0  328.22  4902.5  327.23  4945.0  323.60  4966.5  318.76  4980.2  314.22
  4988.2  313.99  4999.6  308.91  5002.4  308.41  5005.6  308.91  5009.0  311.24
  5023.5  314.88  5044.3  318.37  5052.3  319.12  5081.1  321.03  5087.5  320.95
  5094.4  322.25  5101.9  322.59  5130.7  322.97  5145.1  323.85  5151.5  323.57
  5158.4  325.13  5201.2  327.25  5209.2  328.62  5222.4  328.80  5293.4  335.02
#Mann=3,-1,0
  4796.8    0.16       0  4999.6    0.07       0  5005.6    0.16       0
Bank Sta=4999.6,5005.6
Exp/Cntr=0.3,0.1

Type RM Length L Ch R = 1,17047,466,466,466
BEGIN DESCRIPTION:
UNT186 IN CCTC 18.0
END DESCRIPTION:
XS GIS Cut Line= 3
      3583159.50     10683510.67      3582933.83     10683170.42
      3582607.40     10683010.68
#Sta/Elev= 30
  4537.4  340.20  4581.2  338.85  4602.3  339.46  4610.0  338.10  4623.3  338.63
  4718.0  334.24  4731.6  332.47  4746.6  332.43  4790.0  329.22  4803.8  327.31
  4818.8  327.35  4848.9  324.73  4950.8  319.52  4956.8  316.97  4962.3  318.44
  4972.7  315.63  4979.3  310.64  4991.9  307.73  4994.7  307.23  4997.9  307.73
  5001.8  311.24  5007.3  310.26  5024.3  311.13  5039.4  314.07  5069.3  314.18
  5106.2  316.04  5150.8  323.04  5217.6  329.69  5262.1  332.96  5309.1  334.10
#Mann=3,-1,0
  4537.4    0.16       0  4991.9    0.07       0  4997.9    0.16       0
Bank Sta=4991.9,4997.9
Exp/Cntr=0.3,0.1

Type RM Length L Ch R = 1,16581,341,341,341
BEGIN DESCRIPTION:
UNT186 IN CCTC 17.0
END DESCRIPTION:
XS GIS Cut Line= 4
      3583465.10     10683337.11      3583100.49     10682923.89
      3583010.22     10682840.56      3582676.90     10682892.63
#Sta/Elev= 30
  4389.2  341.82  4490.4  338.01  4574.9  332.95  4582.5  333.60  4610.9  330.68
  4752.3  325.30  4773.2  322.75  4787.4  322.79  4929.6  314.68  4964.9  313.55
  4971.7  312.31  4979.1  312.43  4997.0  304.76  4999.8  304.26  5003.0  304.76
  5014.2  309.04  5035.8  310.29  5042.6  309.32  5049.9  312.10  5056.7  311.67
  5091.1  315.66  5124.5  317.11  5144.7  319.23  5158.9  319.26  5266.2  328.72
  5316.8  332.12  5347.2  331.84  5352.2  332.75  5377.5  333.15  5400.5  332.14
#Mann=3,-1,0
  4389.2    0.16       0  4997.0    0.07       0  5003.0    0.16       0
Bank Sta=4997,5003
Exp/Cntr=0.3,0.1

Type RM Length L Ch R = 1,16240,348,348,348
BEGIN DESCRIPTION:
Mapping XS 7d09d3ba
END DESCRIPTION:
XS GIS Cut Line= 4
      3583325.35     10682992.94      3583165.64     10682624.91
      3583051.06     10682558.94      3582717.77     10682729.06
#Sta/Elev= 30
  4537.0  326.58  4605.4  323.35  4618.0  321.75  4641.5  321.33  4659.5  320.08
  4664.9  318.51  4670.8  319.30  4703.5  316.17  4711.8  316.31  4717.3  315.02
  4769.7  312.20  4932.4  308.48  4960.1  308.87  4975.4  307.79  4991.3  306.66
  4994.4  303.49  4997.2  302.99  5000.4  303.49  5003.2  306.91  5005.0  307.35
  5013.2  309.35  5108.7  312.95  5219.9  319.35  5286.5  320.40  5308.8  322.45
  5325.4  320.93  5331.0  322.29  5369.8  320.47  5375.4  322.03  5444.6  322.87
#Mann=5,-1,0
  4537.0    0.16       0  4975.4    0.12       0  4994.4    0.07       0
  5000.4    0.12       0  5005.0    0.16       0
Bank Sta=4994.4,5000.4
Exp/Cntr=0.3,0.1

Type RM Length L Ch R = 1,15892,373,373,373
BEGIN DESCRIPTION:
UNT186 IN CCTC 16.0
END DESCRIPTION:
XS GIS Cut Line= 3
      3583558.04     10682451.31      3583172.59     10682381.86
      3582794.34     10682041.78
#Sta/Elev= 30
  4668.3  323.29  4798.8  311.44  4813.6  305.05  4829.3  303.64  4851.1  305.21
  4868.4  305.06  4870.5  302.75  4873.2  302.25  4876.5  302.75  4890.2  303.13
  4900.4  306.37  4927.1  308.31  4991.9  306.35  5002.0  304.23  5032.5  304.94
  5039.4  303.79  5077.4  303.64  5086.0  304.60  5091.2  306.70  5098.7  306.99
  5155.5  307.32  5190.6  305.86  5225.8  307.57  5374.5  320.08  5388.7  322.48
  5473.9  330.32  5502.3  330.30  5509.1  332.16  5530.7  332.18  5568.6  335.48
#Mann=6,-1,0
  4668.3    0.12       0  4813.6    0.16       0  4851.1    0.12       0
  4870.5    0.07       0  4876.5    0.12       0  5086.0    0.16       0
Bank Sta=4870.5,4876.5
Exp/Cntr=0.3,0.1

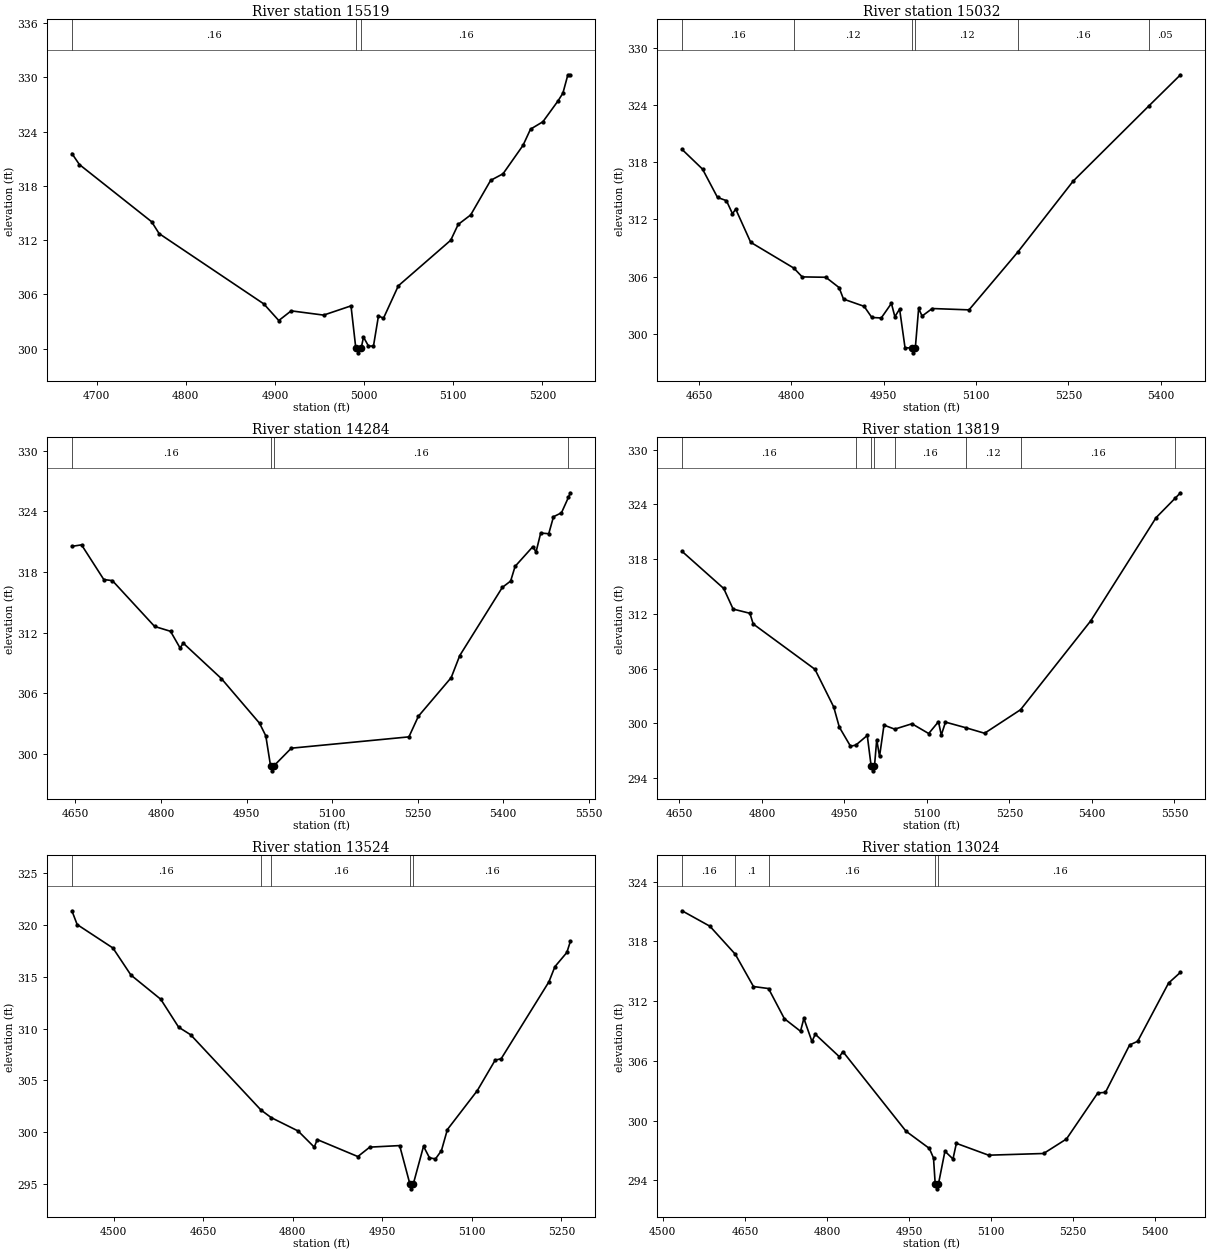
Type RM Length L Ch R = 1,15519,487,487,487
BEGIN DESCRIPTION:
UNT186 IN CCTC 15.0
END DESCRIPTION:
XS GIS Cut Line= 3
      3583549.59     10682210.18      3583249.61     10682060.19
      3583049.60     10681960.19
#Sta/Elev= 30
  4672.3  321.57  4680.7  320.35  4761.7  314.03  4770.1  312.72  4887.5  304.95
  4904.3  303.11  4918.2  304.18  4954.6  303.71  4985.3  304.73  4990.7  300.04
  4993.5  299.54  4996.7  300.04  4999.3  301.28  5004.9  300.29  5010.5  300.29
  5016.1  303.63  5021.7  303.36  5038.4  306.95  5097.1  311.98  5105.5  313.73
  5119.5  314.78  5141.9  318.60  5155.8  319.33  5178.2  322.47  5186.6  324.26
  5200.5  325.08  5217.3  327.36  5222.9  328.23  5228.5  330.27  5231.3  330.27
#Mann=3,-1,0
  4672.3    0.16       0  4990.7    0.07       0  4996.7    0.16       0
Bank Sta=4990.7,4996.7
Exp/Cntr=0.3,0.1

Type RM Length L Ch R = 1,15032,748,748,748
BEGIN DESCRIPTION:
Mapping XS 2512d7a9
END DESCRIPTION:
XS GIS Cut Line= 3
      3583646.54     10682087.13      3583548.89     10681841.93
      3583064.97     10681590.20
#Sta/Elev= 30
  4622.5  319.34  4655.8  317.27  4680.1  314.30  4694.6  313.96  4704.4  312.59
  4709.7  313.07  4734.0  309.59  4804.1  306.88  4817.6  305.96  4856.0  305.92
  4877.5  304.84  4884.7  303.63  4918.2  302.87  4930.7  301.70  4946.0  301.65
  4962.5  303.18  4968.1  301.78  4975.8  302.58  4984.6  298.53  4995.3  298.49
  4998.1  297.99  5001.3  298.49  5006.7  302.65  5012.3  301.85  5028.8  302.64
  5088.5  302.50  5167.4  308.54  5257.6  316.01  5380.2  323.88  5431.9  327.17
#Mann=6,-1,0
  4622.5    0.16       0  4804.1    0.12       0  4995.3    0.07       0
  5001.3    0.12       0  5167.4    0.16       0  5380.2    0.05       0
Bank Sta=4995.3,5001.3
Exp/Cntr=0.3,0.1

Type RM Length L Ch R = 1,14284,465,465,465
BEGIN DESCRIPTION:
Mapping XS 2b84e3e5
END DESCRIPTION:
XS GIS Cut Line= 2
      3583932.98     10681781.15      3583153.17     10681386.91
#Sta/Elev= 30
  4643.8  320.54  4660.7  320.69  4699.7  317.26  4714.8  317.15  4788.8  312.62
  4816.7  312.14  4833.4  310.49  4839.0  310.97  4905.9  307.46  4972.7  303.05
  4983.7  301.80  4992.0  298.84  4994.8  298.34  4998.0  298.84  5028.4  300.58
  5234.6  301.70  5251.2  303.74  5308.7  307.56  5323.7  309.74  5398.3  316.48
  5412.9  317.11  5420.7  318.56  5451.8  320.51  5457.4  319.98  5465.6  321.86
  5479.7  321.79  5488.0  323.47  5502.0  323.86  5514.3  325.40  5517.6  325.84
#Mann=4,-1,0
  4643.8    0.16       0  4992.0    0.07       0  4998.0    0.16       0
  5514.3    0.05       0
Bank Sta=4992,4998
Exp/Cntr=0.3,0.1

Type RM Length L Ch R = 1,13819,295,295,295
BEGIN DESCRIPTION:
UNT186 IN CCTC 14.0
END DESCRIPTION:
XS GIS Cut Line= 2
      3584061.04     10681438.28      3583169.08     10681277.68
#Sta/Elev= 30
  4654.6  318.85  4730.4  314.78  4747.5  312.52  4778.0  312.06  4784.0  310.89
  4896.3  305.92  4930.4  301.79  4940.6  299.58  4960.9  297.49  4970.6  297.61
  4991.4  298.67  4998.5  295.29  5001.3  294.79  5004.5  295.29  5008.6  298.21
  5013.7  296.37  5021.8  299.80  5041.3  299.36  5072.6  299.95  5103.1  298.88
  5120.9  300.18  5126.0  298.71  5133.6  300.13  5170.3  299.52  5204.7  298.91
  5270.1  301.49  5397.8  311.24  5516.6  322.55  5551.3  324.68  5560.9  325.27
#Mann=8,-1,0
  4654.6    0.16       0  4970.6    0.12       0  4998.5    0.07       0
  5004.5    0.12       0  5041.3    0.16       0  5170.3    0.12       0
  5270.1    0.16       0  5551.3    0.05       0
Bank Sta=4998.5,5004.5
Exp/Cntr=0.3,0.1

Type RM Length L Ch R = 1,13524,500,500,500
BEGIN DESCRIPTION:
UNT186 IN CCTC 13.0
END DESCRIPTION:
XS GIS Cut Line= 2
      3584128.39     10681128.24      3583293.71     10681162.93
#Sta/Elev= 30
  4429.7  321.38  4438.5  320.05  4498.5  317.78  4528.6  315.17  4578.6  312.83
  4608.6  310.13  4628.7  309.40  4746.5  302.13  4763.8  301.39  4808.8  300.10
  4835.9  298.54  4840.9  299.27  4908.9  297.63  4928.9  298.54  4979.0  298.69
  4996.0  295.01  4998.7  294.51  5002.0  295.01  5019.0  298.62  5029.0  297.51
  5039.0  297.40  5049.0  298.20  5059.0  300.24  5109.1  304.00  5139.1  306.95
  5149.1  307.08  5229.2  314.52  5239.2  315.98  5259.2  317.35  5265.1  318.42
#Mann=5,-1,0
  4429.7    0.16       0  4746.5    0.12       0  4763.8    0.16       0
  4996.0    0.07       0  5002.0    0.16       0
Bank Sta=4996,5002
Exp/Cntr=0.3,0.1

Type RM Length L Ch R = 1,13024,626,626,626
BEGIN DESCRIPTION:
UNT186 IN CCTC 12.0
END DESCRIPTION:
XS GIS Cut Line= 2
      3584056.80     10680566.15      3583316.80     10681097.83
#Sta/Elev= 30
  4535.1  321.07  4586.0  319.52  4632.4  316.71  4665.7  313.46  4693.2  313.26
  4722.2  310.23  4751.7  308.97  4757.8  310.26  4772.6  307.94  4778.7  308.67
  4822.9  306.40  4829.1  306.93  4944.5  298.93  4987.2  297.20  4994.8  296.24
  4997.9  293.64  5000.7  293.14  5003.9  293.64  5015.7  296.92  5030.4  296.14
  5036.6  297.71  5095.5  296.52  5196.1  296.69  5237.9  298.15  5295.1  302.77
  5309.1  302.83  5353.3  307.59  5368.0  307.96  5424.5  313.81  5446.3  314.89
#Mann=5,-1,0
  4535.1    0.16       0  4632.4     0.1       0  4693.2    0.16       0
  4997.9    0.07       0  5003.9    0.16       0
Bank Sta=4997.9,5003.9
Exp/Cntr=0.3,0.1

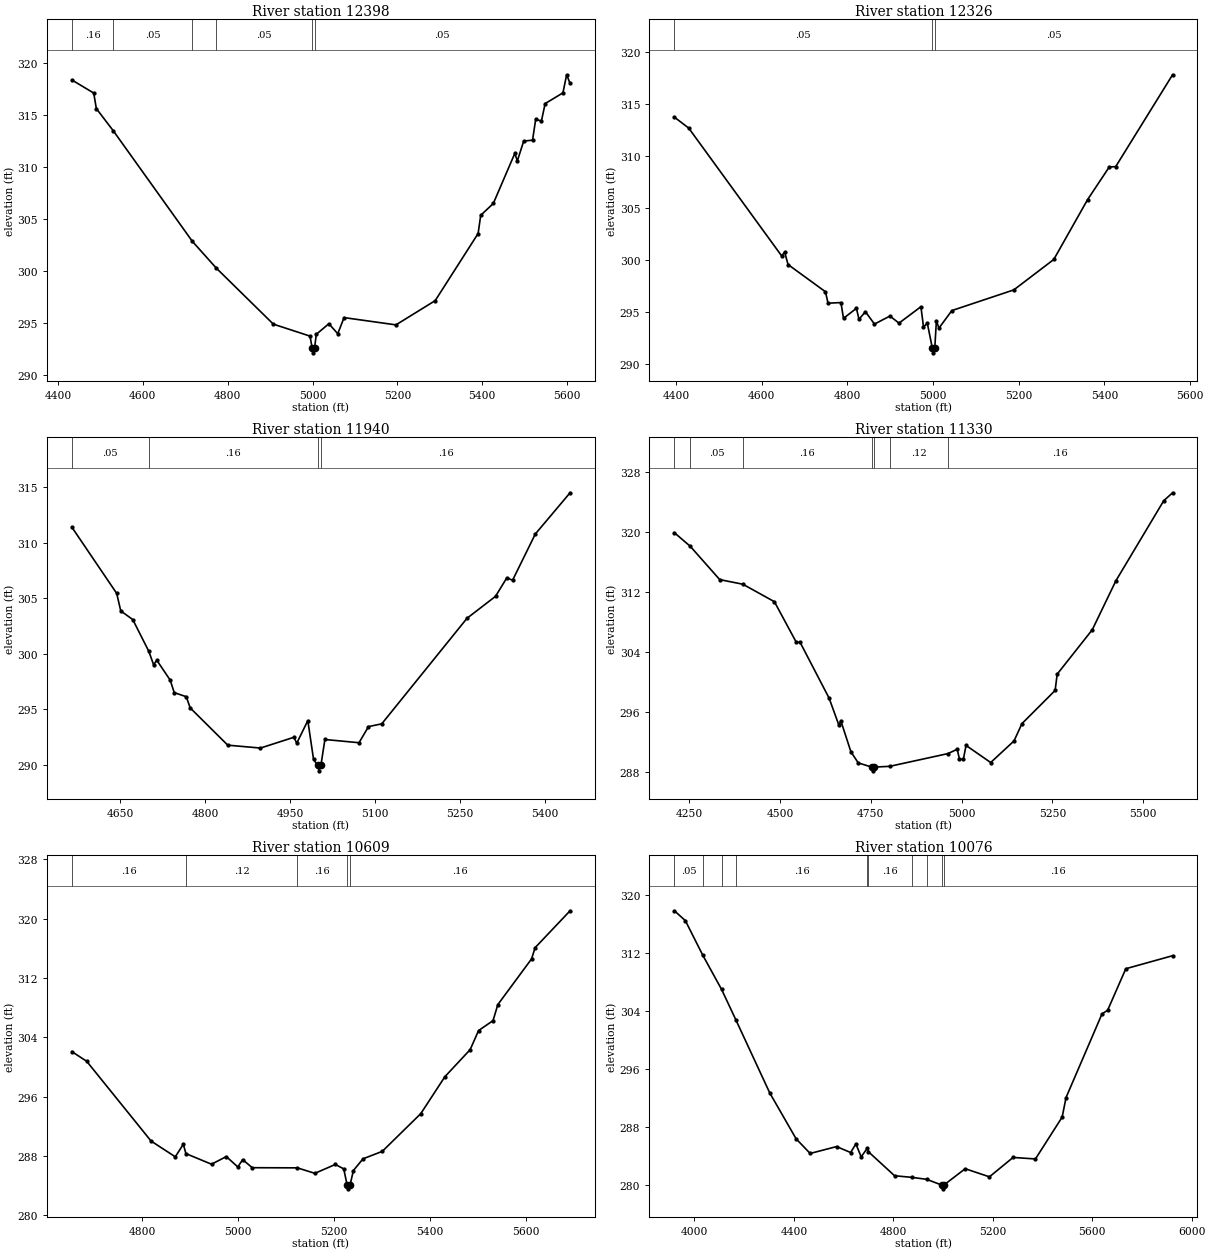
Type RM Length L Ch R = 1,12398,72,72,72
BEGIN DESCRIPTION:
UNT186 IN CCTC 11.0
END DESCRIPTION:
XS GIS Cut Line= 2
      3583884.16     10680123.12      3583213.42     10681086.76
#Sta/Elev= 30
  4432.9  318.35  4484.4  317.09  4490.5  315.60  4530.5  313.46  4716.9  302.82
  4773.5  300.24  4907.7  294.86  4994.1  293.71  4999.0  292.60  5001.7  292.10
  5005.0  292.60  5008.9  293.88  5038.5  294.90  5059.5  293.94  5074.4  295.49
  5196.6  294.79  5289.1  297.12  5390.3  303.58  5396.4  305.33  5426.1  306.47
  5476.7  311.28  5482.8  310.57  5497.7  312.47  5518.6  312.56  5525.9  314.55
  5539.5  314.41  5548.3  316.08  5590.2  317.11  5598.9  318.85  5607.0  318.02
#Mann=6,-1,0
  4432.9    0.16       0  4530.5    0.05       0  4716.9    0.16       0
  4773.5    0.05       0  4999.0    0.04       0  5005.0    0.05       0
Bank Sta=4999,5005
Exp/Cntr=0.3,0.1

Type RM Length L Ch R = 1,12326,386,386,386
BEGIN DESCRIPTION:
UNT186 IN CCTC 10.0
END DESCRIPTION:
XS GIS Cut Line= 2
      3583821.66     10680085.28      3583181.53     10681055.90
#Sta/Elev= 30
  4396.3  313.72  4429.7  312.67  4646.5  300.37  4653.7  300.72  4661.6  299.53
  4748.9  296.91  4754.9  295.81  4785.0  295.87  4791.0  294.35  4821.2  295.32
  4827.1  294.26  4842.2  294.99  4863.3  293.80  4899.4  294.57  4920.5  293.89
  4971.7  295.47  4977.7  293.53  4986.7  293.87  4998.1  291.53  5000.9  291.03
  5004.1  291.53  5007.8  294.11  5013.8  293.41  5043.9  295.10  5188.5  297.09
  5281.8  300.02  5360.5  305.77  5411.2  308.92  5426.3  308.96  5559.0  317.80
#Mann=3,-1,0
  4396.3    0.05       0  4998.1    0.04       0  5004.1    0.05       0
Bank Sta=4998.1,5004.1
Exp/Cntr=0.3,0.1

Type RM Length L Ch R = 1,11940,610,610,610
BEGIN DESCRIPTION:
UNT186 IN CCTC 9.0
END DESCRIPTION:
XS GIS Cut Line= 3
      3583776.56     10680108.82      3583446.74     10680314.96
      3582958.47     10680351.85
#Sta/Elev= 30
  4565.2  311.39  4644.2  305.44  4651.4  303.86  4672.6  303.08  4700.9  300.22
  4709.2  299.03  4715.1  299.41  4738.5  297.64  4745.7  296.51  4766.9  296.14
  4773.9  295.13  4840.1  291.78  4897.8  291.52  4956.7  292.49  4961.8  291.96
  4981.3  293.99  4991.4  290.50  4998.4  289.97  5001.2  289.47  5004.4  289.97
  5011.4  292.29  5071.6  292.00  5088.3  293.45  5111.7  293.70  5262.1  303.20
  5312.3  305.17  5332.3  306.84  5342.4  306.62  5382.5  310.78  5443.8  314.49
#Mann=4,-1,0
  4565.2    0.05       0  4700.9    0.16       0  4998.4    0.07       0
  5004.4    0.16       0
Bank Sta=4998.4,5004.4
Exp/Cntr=0.3,0.1

Type RM Length L Ch R = 1,11330,721,721,721
BEGIN DESCRIPTION:
UNT186 IN CCTC 8.0
END DESCRIPTION:
XS GIS Cut Line= 3
      3584003.93     10679965.14      3583333.81     10679906.11
      3582684.48     10680165.15
#Sta/Elev= 30
  4209.2  319.96  4252.8  318.15  4334.0  313.70  4397.8  313.08  4484.6  310.75
  4544.8  305.34  4555.2  305.34  4635.2  297.88  4662.4  294.24  4667.4  294.87
  4695.4  290.70  4715.5  289.23  4752.6  288.67  4755.4  288.17  4758.6  288.67
  4802.0  288.77  4962.4  290.47  4988.0  291.05  4994.1  289.75  5004.9  289.70
  5012.3  291.56  5080.2  289.28  5144.4  292.16  5166.4  294.48  5257.6  298.90
  5263.3  301.08  5360.0  307.01  5424.8  313.53  5556.7  324.23  5581.0  325.29
#Mann=7,-1,0
  4209.2    0.16       0  4252.8    0.05       0  4397.8    0.16       0
  4752.6    0.07       0  4758.6    0.16       0  4802.0    0.12       0
  4962.4    0.16       0
Bank Sta=4752.6,4758.6
Exp/Cntr=0.3,0.1

Type RM Length L Ch R = 1,10609,533,533,533
BEGIN DESCRIPTION:
UNT186 IN CCTC 7.0
END DESCRIPTION:
XS GIS Cut Line= 3
      3583599.64     10679660.20      3583299.61     10679510.19
      3582599.64     10679560.19
#Sta/Elev= 30
  4654.2  302.08  4685.0  300.78  4819.1  290.02  4869.5  287.90  4886.2  289.59
  4891.6  288.33  4944.9  286.90  4975.7  287.93  4999.7  286.53  5009.7  287.52
  5029.7  286.43  5123.5  286.41  5160.1  285.67  5202.7  286.87  5220.2  286.27
  5227.3  284.08  5230.0  283.58  5233.3  284.08  5240.3  286.05  5260.3  287.63
  5300.4  288.63  5380.6  293.72  5430.8  298.70  5483.4  302.35  5500.9  304.92
  5531.0  306.26  5541.0  308.42  5611.2  314.58  5618.7  316.10  5691.4  321.07
#Mann=5,-1,0
  4654.2    0.16       0  4891.6    0.12       0  5123.5    0.16       0
  5227.3    0.07       0  5233.3    0.16       0
Bank Sta=5227.3,5233.3
Exp/Cntr=0.3,0.1

Type RM Length L Ch R = 1,10076,788,788,788
BEGIN DESCRIPTION:
UNT186 IN CCTC 6.0
END DESCRIPTION:
XS GIS Cut Line= 4
      3584098.27     10679713.87      3583389.91     10679021.14
      3583212.83     10678989.89      3582494.36     10679411.60
#Sta/Elev= 30
  3919.5  317.84  3963.6  316.48  4033.7  311.70  4109.2  306.98  4167.0  302.75
  4303.0  292.67  4409.0  286.33  4465.6  284.30  4571.8  285.25  4628.4  284.43
  4649.5  285.62  4670.8  283.83  4695.9  285.05  4700.1  284.53  4805.1  281.22
  4873.4  281.00  4933.7  280.73  4996.5  279.91  4999.2  279.41  5002.5  279.91
  5089.2  282.19  5186.6  281.07  5281.8  283.75  5371.7  283.54  5479.1  289.32
  5494.8  292.03  5639.3  303.58  5662.0  304.09  5735.1  309.83  5923.2  311.63
#Mann=10,-1,0
  3919.5    0.05       0  4033.7    0.16       0  4109.2    0.05       0
  4167.0    0.16       0  4695.9    0.12       0  4700.1    0.16       0
  4873.4    0.12       0  4933.7    0.16       0  4996.5    0.07       0
  5002.5    0.16       0
Bank Sta=4996.5,5002.5
Exp/Cntr=0.3,0.1

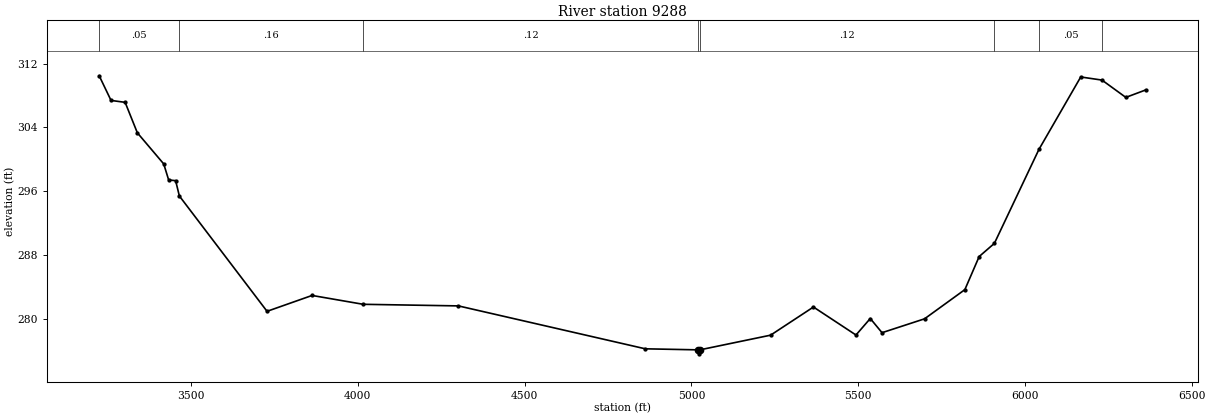
Type RM Length L Ch R = 1,9288,0,0,0
BEGIN DESCRIPTION:
UNT186 IN CCTC 5.0
END DESCRIPTION:
XS GIS Cut Line= 4
      3584395.11     10679594.04      3583499.29     10678307.59
      3583160.75     10678281.55      3582218.03     10679073.22
#Sta/Elev= 30
  3224.4  310.48  3259.9  307.39  3302.2  307.15  3338.8  303.33  3417.9  299.43
  3432.7  297.42  3453.6  297.33  3464.8  295.41  3727.7  280.95  3862.7  282.94
  4016.0  281.83  4301.4  281.63  4861.9  276.25  5019.4  276.12  5022.1  275.62
  5025.4  276.12  5237.5  277.96  5366.0  281.49  5493.5  277.98  5536.4  280.05
  5571.6  278.27  5699.1  280.01  5820.0  283.67  5862.9  287.82  5908.5  289.47
  6042.1  301.25  6167.4  310.33  6231.1  309.94  6302.6  307.77  6362.6  308.71
#Mann=8,-1,0
  3224.4    0.05       0  3464.8    0.16       0  4016.0    0.12       0
  5019.4    0.07       0  5025.4    0.12       0  5908.5    0.16       0
  6042.1    0.05       0  6231.1    0.16       0
Bank Sta=5019.4,5025.4
Exp/Cntr=0.3,0.1

Chan Stop Cuts=-1