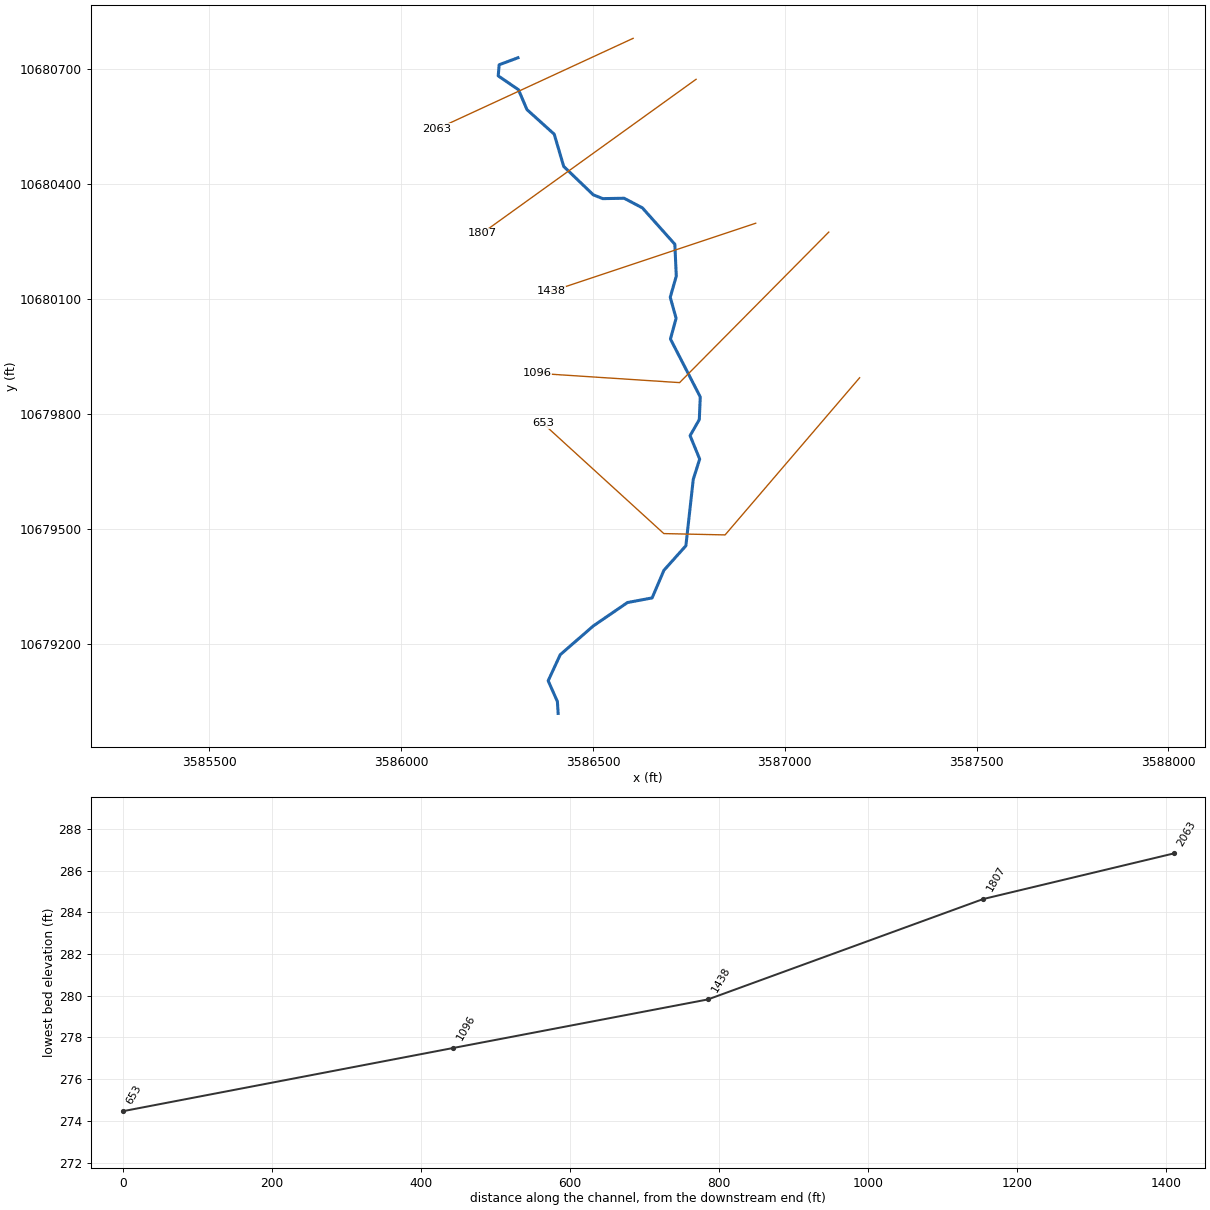
--- UNT189 IN CCTC.prj (project) ---

Proj Title=UNT189 IN CCTC Base Level Engineering
Current Plan=p01
Default Exp/Contr=0.3,0.1
English Units
Geom File=g01
Flow File=f01
Plan File=p01
BEGIN DESCRIPTION:
UNT189 IN CCTC
END DESCRIPTION:

--- UNT189 IN CCTC.p01 (plan) ---

Plan Title=Multiple Run
Short Identifier=Multiple
Geom File=g01
Flow File=f01
Subcritical Flow
K Sum by GR= 0
Std Step Tol= 0.01
Critical Tol= 0.01
Num of Std Step Trials= 20
Max Error Tol= 0.3
Flow Tol Ratio= 0.001
Split Flow NTrial= 30
Split Flow Tol= 0.02
Split Flow Ratio= 0.02
Log Output Level= 0
Friction Slope Method= 1
Unsteady Friction Slope Method= 2
Unsteady Bridges Friction Slope Method= 1
Parabolic Critical Depth
Global Vel Dist=  1 , 1 , 1
Global Log Level= 0
CheckData=True
Encroach Param= -1, 0, 0, 0
BEGIN DESCRIPTION:
Multiple Run
END DESCRIPTION:

--- UNT189 IN CCTC.f01 (steady flow) ---

Flow Title=Multiple
Number of Profiles=7
Profile Names=10-year,25-year,50-year,1pct_min,100-year,1pct_plu,500-year
River Rch & RM= UNT189 IN CCTC,Reach-1,2063
     520     675     797     690     933    1261    1269
Boundary for River Rch & Prof#=UNT189 IN CCTC,Reach-1,1
Up Type=0
Dn Type=3
Dn Slope=0.005
Boundary for River Rch & Prof#=UNT189 IN CCTC,Reach-1,2
Up Type=0
Dn Type=3
Dn Slope=0.005
Boundary for River Rch & Prof#=UNT189 IN CCTC,Reach-1,3
Up Type=0
Dn Type=3
Dn Slope=0.005
Boundary for River Rch & Prof#=UNT189 IN CCTC,Reach-1,4
Up Type=0
Dn Type=3
Dn Slope=0.005
Boundary for River Rch & Prof#=UNT189 IN CCTC,Reach-1,5
Up Type=0
Dn Type=3
Dn Slope=0.005
Boundary for River Rch & Prof#=UNT189 IN CCTC,Reach-1,6
Up Type=0
Dn Type=3
Dn Slope=0.005
Boundary for River Rch & Prof#=UNT189 IN CCTC,Reach-1,7
Up Type=0
Dn Type=3
Dn Slope=0.005

--- UNT189 IN CCTC.g01 (geometry) ---

Geom Title=Existing Conditions

River Reach=UNT189 IN CCTC,Reach-1
Reach XY= 30
      3586304.26     10680729.26      3586255.25     10680711.00
      3586252.75     10680682.00      3586305.50     10680646.00
      3586327.75     10680594.00      3586398.75     10680530.00
      3586423.50     10680446.00      3586500.50     10680372.00
      3586525.25     10680362.00      3586581.00     10680363.00
      3586628.50     10680338.00      3586713.25     10680243.00
      3586717.00     10680160.00      3586701.25     10680105.00
      3586716.50     10680050.00      3586701.75     10679996.00
      3586779.50     10679845.00      3586777.00     10679786.00
      3586753.00     10679744.00      3586778.00     10679683.00
      3586761.25     10679630.00      3586742.00     10679457.00
      3586684.75     10679393.00      3586654.00     10679321.00
      3586589.75     10679309.00      3586500.75     10679248.00
      3586414.50     10679173.00      3586383.00     10679105.00
      3586407.00     10679051.00      3586409.00     10679020.00

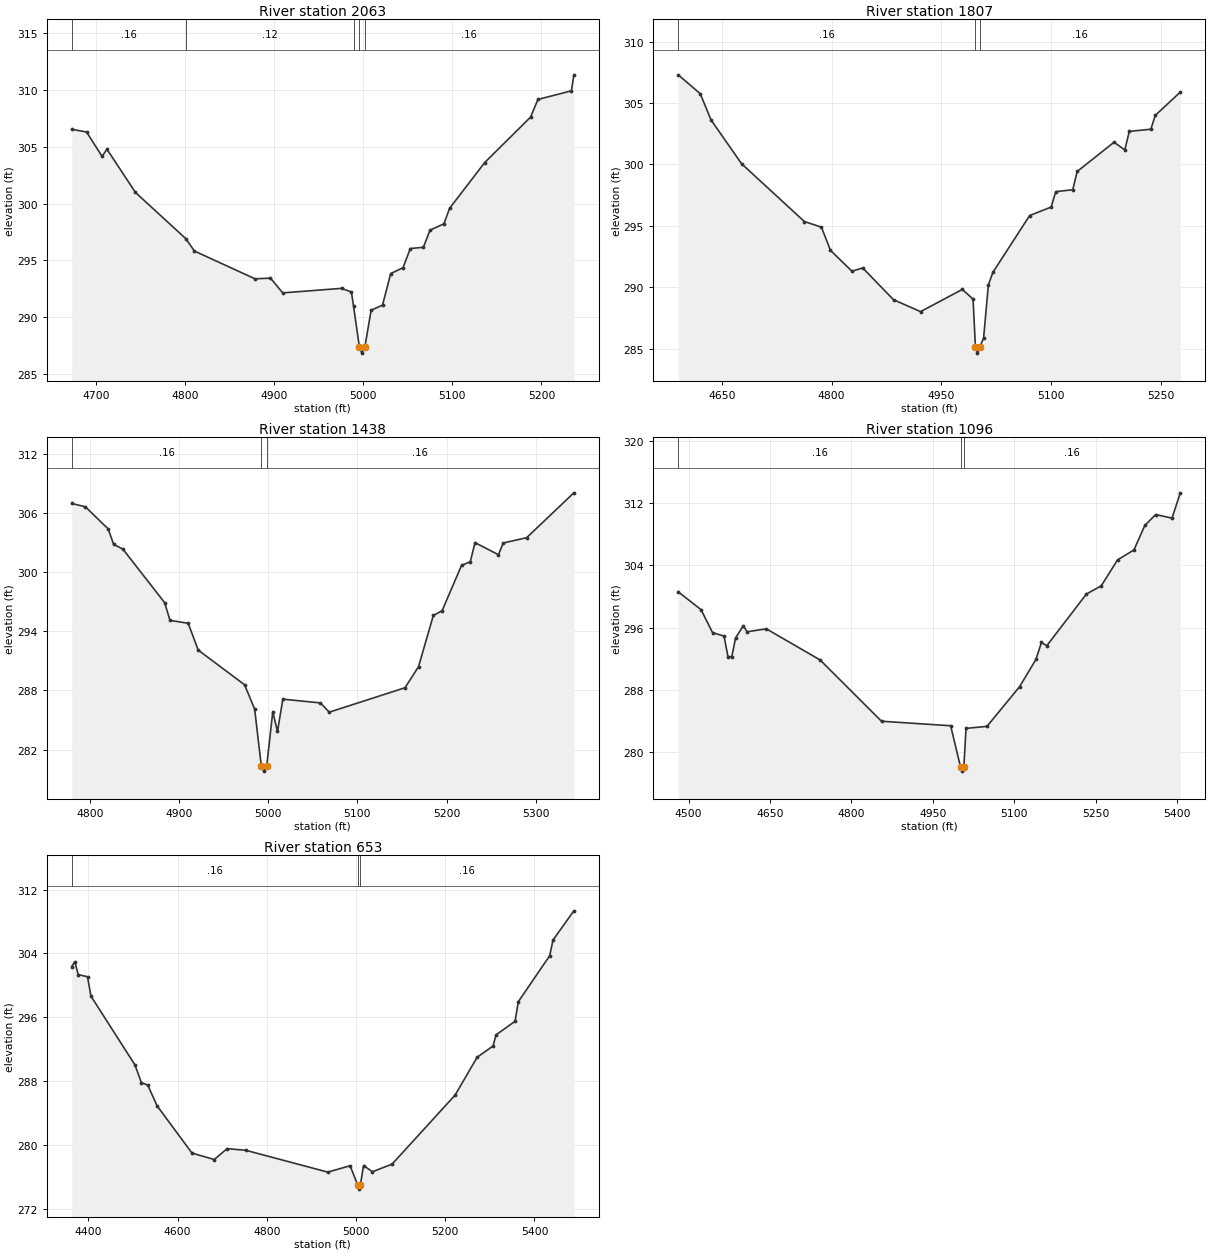
Type RM Length L Ch R = 1,2063,256,256,256
BEGIN DESCRIPTION:
UNT189 IN CCTC 3.0
END DESCRIPTION:
XS GIS Cut Line= 2
      3586604.52     10680779.90      3586093.05     10680543.64
#Sta/Elev= 30
  4672.9  306.55  4689.5  306.31  4706.9  304.16  4712.4  304.79  4744.4  300.98
  4801.0  296.90  4810.5  295.82  4878.5  293.37  4895.9  293.43  4909.6  292.13
  4975.8  292.53  4986.7  292.20  4989.1  290.96  4995.7  287.32  4998.4  286.82
  5001.7  287.32  5008.8  290.60  5021.6  291.05  5030.8  293.83  5044.6  294.35
  5052.8  296.04  5067.5  296.15  5074.9  297.66  5090.5  298.22  5096.9  299.59
  5136.3  303.62  5187.7  307.62  5196.0  309.18  5233.6  309.94  5236.3  311.35
#Mann=5,-1,0
  4672.9    0.16       0  4801.0    0.12       0  4989.1    0.16       0
  4995.7    0.07       0  5001.7    0.16       0
Bank Sta=4995.7,5001.7
Exp/Cntr=0.3,0.1

Type RM Length L Ch R = 1,1807,369,369,369
BEGIN DESCRIPTION:
Mapping XS e6c37efa
END DESCRIPTION:
XS GIS Cut Line= 2
      3586768.57     10680673.13      3586211.27     10680272.09
#Sta/Elev= 30
  4590.4  307.30  4620.5  305.76  4635.2  303.63  4677.0  300.06  4762.9  295.35
  4786.2  294.89  4798.6  293.00  4828.0  291.30  4842.7  291.57  4884.8  288.98
  4921.8  288.01  4978.9  289.82  4993.6  289.03  4996.8  285.13  4999.6  284.63
  5002.8  285.13  5008.0  285.86  5014.5  290.19  5020.7  291.21  5071.0  295.84
  5100.4  296.53  5106.6  297.78  5129.9  297.94  5136.0  299.43  5186.4  301.81
  5201.1  301.18  5207.2  302.69  5236.7  302.87  5242.8  304.00  5277.0  305.89
#Mann=3,-1,0
  4590.4    0.16       0  4996.8    0.07       0  5002.8    0.16       0
Bank Sta=4996.8,5002.8
Exp/Cntr=0.3,0.1

Type RM Length L Ch R = 1,1438,342,342,342
BEGIN DESCRIPTION:
UNT189 IN CCTC 2.0
END DESCRIPTION:
XS GIS Cut Line= 2
      3586924.08     10680297.88      3586390.17     10680119.91
#Sta/Elev= 30
  4779.8  306.97  4795.1  306.63  4820.7  304.38  4826.7  302.83  4837.2  302.33
  4883.9  296.91  4889.9  295.11  4910.3  294.82  4921.5  292.10  4973.5  288.58
  4984.8  286.11  4992.3  280.32  4995.1  279.82  4998.3  280.32  5005.1  285.84
  5010.4  283.84  5016.4  287.12  5058.6  286.74  5068.4  285.80  5153.4  288.28
  5168.5  290.42  5185.1  295.61  5194.9  296.09  5216.7  300.69  5226.5  301.06
  5231.8  303.00  5258.1  301.77  5263.4  302.96  5289.7  303.50  5342.6  308.05
#Mann=3,-1,0
  4779.8    0.16       0  4992.3    0.07       0  4998.3    0.16       0
Bank Sta=4992.3,4998.3
Exp/Cntr=0.3,0.1

Type RM Length L Ch R = 1,1096,443,443,443
BEGIN DESCRIPTION:
Mapping XS dce98b90
END DESCRIPTION:
XS GIS Cut Line= 3
      3587114.50     10680274.71      3586725.58     10679882.32
      3586354.35     10679906.61
#Sta/Elev= 30
  4481.1  300.60  4523.1  298.30  4544.3  295.35  4565.5  294.89  4572.6  292.26
  4579.7  292.23  4586.7  294.67  4600.9  296.22  4608.0  295.45  4643.3  295.83
  4742.3  291.82  4855.4  283.92  4982.7  283.34  5001.0  277.99  5003.7  277.49
  5007.0  277.99  5011.0  283.00  5049.6  283.26  5109.7  288.38  5139.8  291.89
  5149.8  294.07  5159.8  293.66  5232.8  300.32  5260.0  301.37  5290.1  304.72
  5320.2  306.00  5340.2  309.15  5360.2  310.56  5390.3  310.10  5405.6  313.36
#Mann=3,-1,0
  4481.1    0.16       0  5001.0    0.07       0  5007.0    0.16       0
Bank Sta=5001,5007
Exp/Cntr=0.3,0.1

Type RM Length L Ch R = 1,653,0,0,0
BEGIN DESCRIPTION:
UNT189 IN CCTC 1.0
END DESCRIPTION:
XS GIS Cut Line= 4
      3587194.97     10679895.03      3586844.25     10679485.27
      3586684.53     10679488.74      3586369.50     10679776.07
#Sta/Elev= 30
  4362.8  302.35  4369.6  302.95  4377.2  301.34  4398.1  301.07  4405.8  298.64
  4504.6  290.01  4518.8  287.80  4533.1  287.50  4554.0  284.90  4632.4  278.97
  4682.4  278.17  4710.9  279.53  4752.7  279.33  4936.8  276.59  4986.8  277.39
  5003.8  274.96  5006.6  274.46  5009.8  274.96  5016.8  277.42  5036.8  276.64
  5080.8  277.59  5222.1  286.24  5271.6  290.99  5307.2  292.39  5313.9  293.79
  5356.5  295.49  5363.9  297.95  5434.2  303.71  5441.6  305.67  5488.3  309.33
#Mann=3,-1,0
  4362.8    0.16       0  5003.8    0.07       0  5009.8    0.16       0
Bank Sta=5003.8,5009.8
Exp/Cntr=0.3,0.1

Chan Stop Cuts=-1