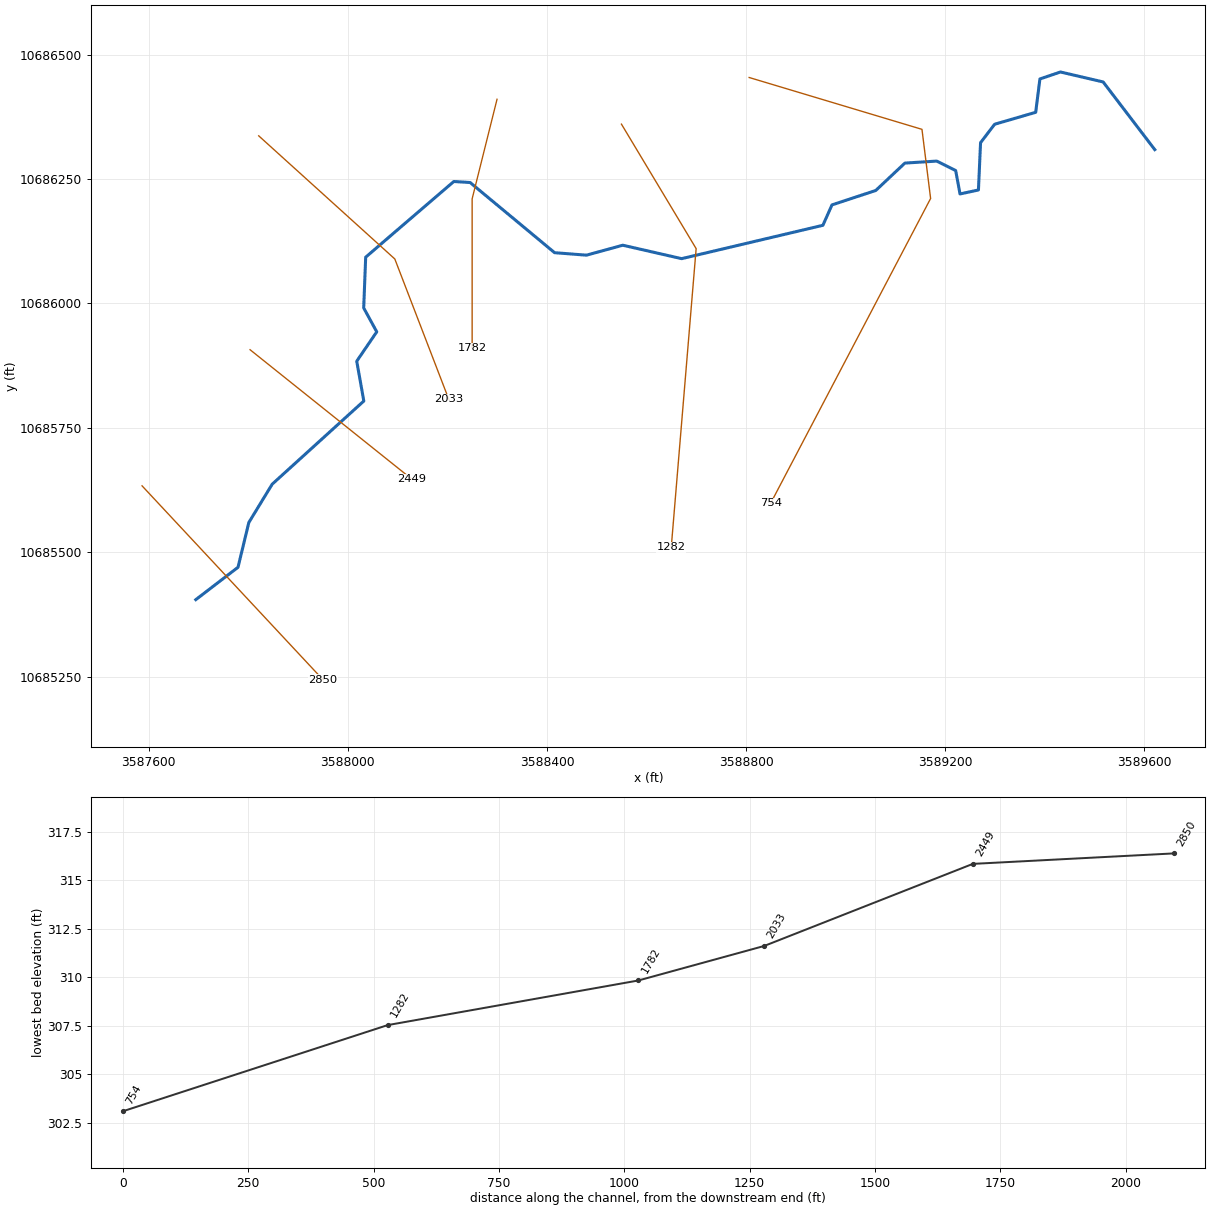
--- UNT196 IN CCTC.prj (project) ---

Proj Title=UNT196 IN CCTC Base Level Engineering
Current Plan=p01
Default Exp/Contr=0.3,0.1
English Units
Geom File=g01
Flow File=f01
Plan File=p01
Y Axis Title=Elevation
X Axis Title(PF)=Main Channel Distance
X Axis Title(XS)=Station
BEGIN DESCRIPTION:
UNT196 IN CCTC
END DESCRIPTION:
DSS Export Rating Curves= 0
DSS Export Rating Curve Sorted= 0
DSS Export Volume Flow Curves= 0
DXF OffsetX= 0
DXF OffsetY= 0
DXF ScaleX= 1
DXF ScaleY= 10

--- UNT196 IN CCTC.p01 (plan) ---

Plan Title=Multiple Run
Short Identifier=Multiple
Geom File=g01
Flow File=f01
Subcritical Flow
K Sum by GR= 0
Std Step Tol= 0.01
Critical Tol= 0.01
Num of Std Step Trials= 20
Max Error Tol= 0.3
Flow Tol Ratio= 0.001
Split Flow NTrial= 30
Split Flow Tol= 0.02
Split Flow Ratio= 0.02
Log Output Level= 0
Friction Slope Method= 1
Unsteady Friction Slope Method= 2
Unsteady Bridges Friction Slope Method= 1
Parabolic Critical Depth
Global Vel Dist=  1 , 1 , 1
Global Log Level= 0
CheckData=True
Encroach Param= -1, 0, 0, 0
BEGIN DESCRIPTION:
Multiple Run
END DESCRIPTION:

--- UNT196 IN CCTC.f01 (steady flow) ---

Flow Title=Multiple
Program Version=4.10
Number of Profiles= 7
Profile Names=10-year,25-year,50-year,1pct_min,100-year,1pct_plu,500-year
River Rch & RM=UNT196 IN CCTC,Reach-1         ,2850
     423     541     631     541     732     990     976
Boundary for River Rch & Prof#=UNT196 IN CCTC,Reach-1         , 1
Up Type= 0
Dn Type= 3
Dn Slope=0.0095
Boundary for River Rch & Prof#=UNT196 IN CCTC,Reach-1         , 2
Up Type= 0
Dn Type= 3
Dn Slope=0.0095
Boundary for River Rch & Prof#=UNT196 IN CCTC,Reach-1         , 3
Up Type= 0
Dn Type= 3
Dn Slope=0.0095
Boundary for River Rch & Prof#=UNT196 IN CCTC,Reach-1         , 4
Up Type= 0
Dn Type= 3
Dn Slope=0.0095
Boundary for River Rch & Prof#=UNT196 IN CCTC,Reach-1         , 5
Up Type= 0
Dn Type= 3
Dn Slope=0.0095
Boundary for River Rch & Prof#=UNT196 IN CCTC,Reach-1         , 6
Up Type= 0
Dn Type= 3
Dn Slope=0.0095
Boundary for River Rch & Prof#=UNT196 IN CCTC,Reach-1         , 7
Up Type= 0
Dn Type= 3
Dn Slope=0.0095
DSS Import GetInterval= 0
DSS Import GetPeak= 0
DSS Import FillOption= 0

--- UNT196 IN CCTC.g01 (geometry) ---

Geom Title=Existing Conditions
Program Version=4.10

River Reach=UNT196 IN CCTC  ,Reach-1
Reach XY= 30
       3587694.5       10685405.      3587779.25       10685470.
        3587801.       10685560.        3587848.       10685637.
        3588032.       10685804.      3588017.75       10685884.
        3588058.       10685943.      3588031.75       10685991.
      3588035.75       10686093.      3588212.75       10686245.
       3588245.5       10686243.      3588415.25       10686102.
      3588479.25       10686097.      3588552.25       10686117.
       3588670.5       10686090.      3588954.25       10686157.
       3588972.5       10686198.       3589060.5       10686227.
        3589119.       10686282.        3589183.       10686286.
        3589221.       10686267.      3589229.75       10686220.
      3589266.75       10686228.        3589271.       10686323.
      3589299.25       10686360.      3589381.75       10686384.
      3589390.25       10686451.       3589431.5       10686465.
      3589517.25       10686445.        3589621.       10686309.

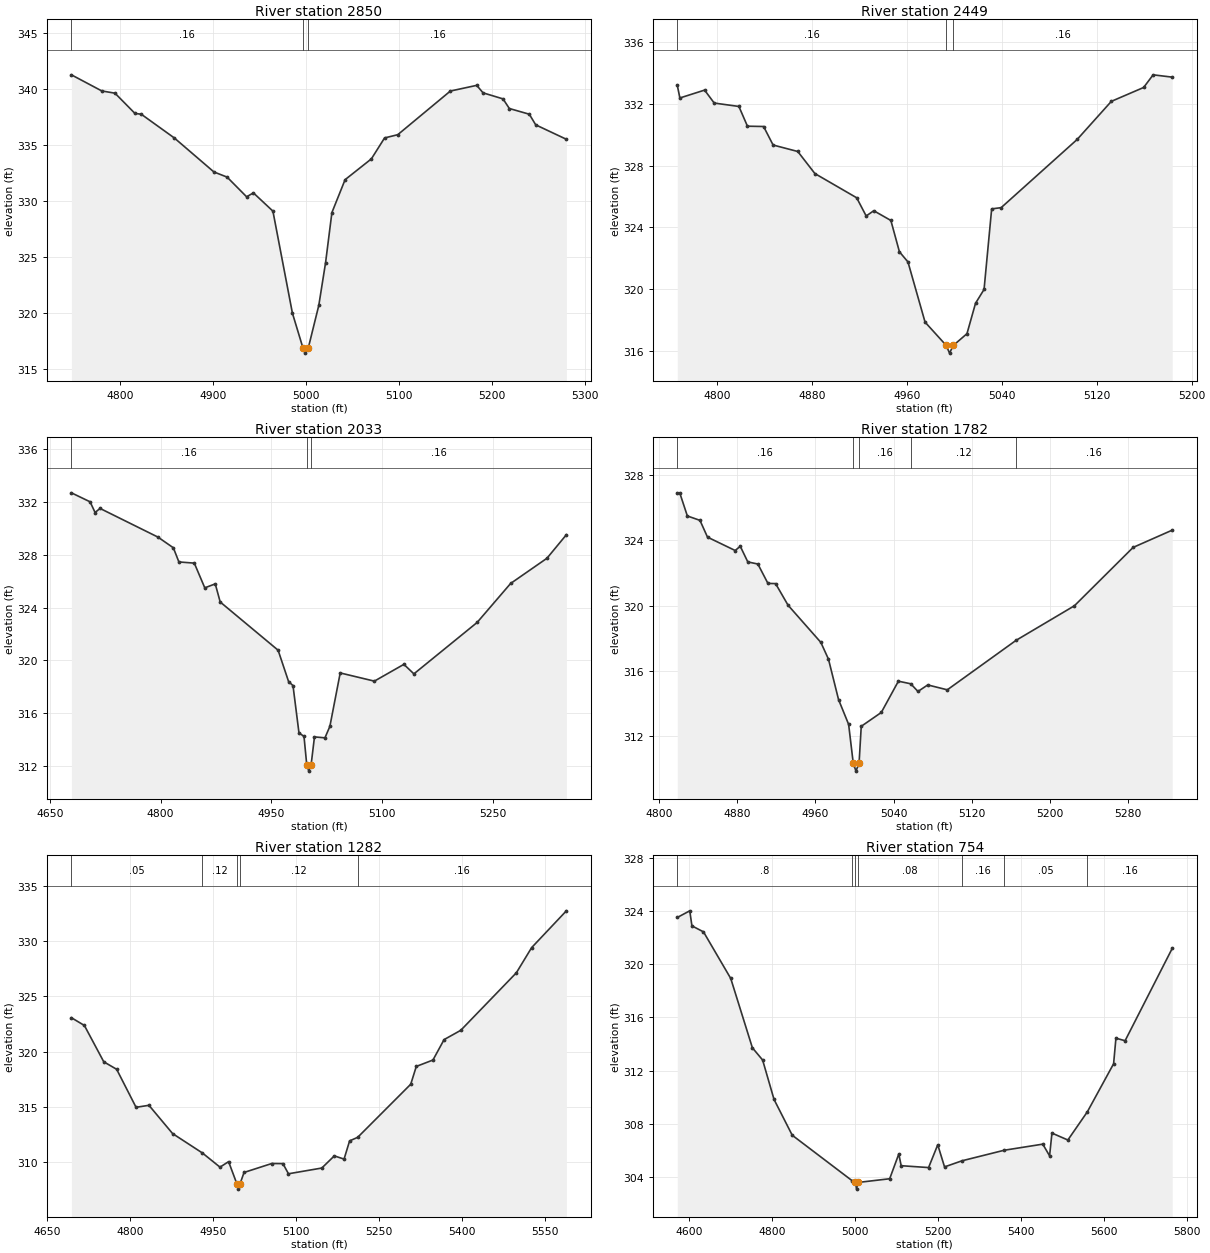
Type RM Length L Ch R = 1 ,2850    ,401,401,401
BEGIN DESCRIPTION:
UNT196 IN CCTC 5.0
END DESCRIPTION:
XS GIS Cut Line= 2
      3587586.48     10685633.62      3587950.01     10685244.11
#Sta/Elev= 30
  4747.6  341.26  4780.3  339.82  4794.5  339.62    4816  337.81  4822.8  337.74
  4858.5  335.61    4901  332.58  4915.2  332.12  4936.2  330.36  4943.5  330.71
  4964.5  329.08  4985.5  319.96  4996.7  316.89  4999.4  316.39  5002.7  316.89
  5013.9  320.66  5021.2  324.48    5028  328.95  5042.2  331.89  5070.5  333.75
  5084.7  335.62  5098.9  335.91  5155.5  339.81  5183.9  340.32  5190.7  339.65
  5212.2  339.11    5219  338.25  5240.5  337.74  5247.4  336.79  5280.4   335.5
#Mann= 3 ,-1 , 0
  4747.6     .16       0  4996.7     .07       0  5002.7     .16       0
Bank Sta=4996.7,5002.7
XS Rating Curve= 0 ,0
Exp/Cntr=0.3,0.1

Type RM Length L Ch R = 1 ,2449    ,416,416,416
BEGIN DESCRIPTION:
UNT196 IN CCTC 4.0
END DESCRIPTION:
XS GIS Cut Line= 2
      3587803.47     10685907.07      3588129.02     10685646.64
#Sta/Elev= 30
  4766.7  333.21  4768.9  332.39  4789.7   332.9  4797.8  332.06  4818.6  331.84
  4825.8  330.56  4839.4  330.54  4847.4  329.34  4868.2  328.92  4882.6  327.49
  4917.8  325.92  4925.8  324.74  4932.2  325.08  4946.6  324.45  4953.8  322.42
    4961  321.76  4975.4  317.86  4993.2  316.35    4996  315.85  4999.2  316.35
  5010.7  317.11  5017.9  319.08  5025.1  319.98  5031.5   325.2  5039.5  325.28
  5103.5   329.7  5132.3  332.17  5159.5  333.07  5167.5  333.89  5183.6  333.74
#Mann= 3 ,-1 , 0
  4766.7     .16       0  4993.2     .07       0  4999.2     .16       0
Bank Sta=4993.2,4999.2
XS Rating Curve= 0 ,0
Exp/Cntr=0.3,0.1

Type RM Length L Ch R = 1 ,2033    ,251,251,251
BEGIN DESCRIPTION:
Mapping XS bb4460c7
END DESCRIPTION:
XS GIS Cut Line= 3
      3587820.84     10686336.76      3588094.27     10686089.37
      3588202.78     10685807.25
#Sta/Elev= 30
    4679  332.68  4704.3     332  4711.1  331.19  4717.8   331.5  4796.3  329.33
  4817.2  328.52  4824.7  327.45  4845.6  327.36  4859.8  325.49    4874  325.79
  4880.7  324.42  4959.2  320.77  4973.4   318.4  4979.4  318.09  4987.5  314.51
  4994.3  314.25    4998  312.12  5000.8  311.62    5004  312.12  5008.5  314.21
  5022.7  314.14  5029.4  315.01  5043.4  319.05  5089.7  318.43  5129.7   319.7
  5143.3  318.98    5229  322.87  5274.4  325.82  5323.7  327.73    5350  329.51
#Mann= 3 ,-1 , 0
    4679     .16       0    4998     .07       0    5004     .16       0
Bank Sta=4998,5004
XS Rating Curve= 0 ,0
Exp/Cntr=0.3,0.1

Type RM Length L Ch R = 1 ,1782    ,500,500,500
BEGIN DESCRIPTION:
UNT196 IN CCTC 3.0
END DESCRIPTION:
XS GIS Cut Line= 3
       3588299.6     10686410.15      3588249.61     10686210.19
      3588249.61      10685910.2
#Sta/Elev= 30
  4818.8  326.92  4821.3  326.92  4829.1   325.5    4842  325.23  4849.7   324.2
    4878  323.38  4883.2  323.64  4890.9  322.68  4901.2  322.55  4911.5  321.36
  4919.3  321.35  4932.1  320.02  4965.6  317.74  4973.4  316.71  4983.7  314.23
    4994  312.71  4998.7  310.34  5001.5  309.84  5004.7  310.34  5006.9  312.59
  5027.4  313.44  5044.9  315.36  5057.5   315.2  5064.9  314.73  5074.9  315.13
  5094.9  314.83  5165.3  317.87  5224.9  319.99  5284.9  323.57  5324.9  324.63
#Mann= 5 ,-1 , 0
  4818.8     .16       0  4998.7     .07       0  5004.7     .16       0
  5057.5     .12       0  5165.3     .16       0
Bank Sta=4998.7,5004.7
XS Rating Curve= 0 ,0
Exp/Cntr=0.3,0.1

Type RM Length L Ch R = 1 ,1282    ,528,528,528
BEGIN DESCRIPTION:
UNT196 IN CCTC 2.0
END DESCRIPTION:
XS GIS Cut Line= 3
      3588549.59     10686360.23      3588699.61     10686110.19
      3588649.61     10685510.16
#Sta/Elev= 30
  4694.5  323.06  4717.9  322.36  4752.9  319.07  4776.2  318.39  4811.2  314.95
  4834.5  315.13  4877.2  312.57  4931.1  310.81  4962.8  309.53  4978.3  310.03
  4993.1  308.04  4995.9  307.54  4999.1  308.04  5006.2  309.05  5056.3  309.86
  5076.4  309.85  5086.4  308.93  5146.6  309.45  5169.2  310.55  5186.8  310.26
  5196.8  311.91  5211.4  312.23  5307.2  317.04  5317.2  318.65  5347.3  319.23
  5367.4  321.08  5397.5  321.92  5497.9  327.13  5525.5  329.41  5588.2  332.74
#Mann= 5 ,-1 , 0
  4694.5     .05       0  4931.1     .12       0  4993.1     .07       0
  4999.1     .12       0  5211.4     .16       0
Bank Sta=4993.1,4999.1
XS Rating Curve= 0 ,0
Exp/Cntr=0.3,0.1

Type RM Length L Ch R = 1 ,754     ,0,0,0
BEGIN DESCRIPTION:
UNT196 IN CCTC 1.0
END DESCRIPTION:
XS GIS Cut Line= 4
      3588806.12     10686453.94       3589153.3     10686349.78
      3589170.66     10686210.89      3588849.47     10685598.89
#Sta/Elev= 30
  4571.9  323.51    4602  324.01  4607.2  322.88  4635.1  322.43  4700.8  318.93
    4753  313.72  4777.7   312.8  4805.2  309.84  4849.1  307.15  4993.7  303.73
  5001.5   303.6  5004.2   303.1  5007.5   303.6  5084.1  303.88  5106.1  305.74
  5111.8  304.86  5177.9  304.72    5200  306.43  5216.4  304.77  5258.6  305.23
    5360  306.02  5453.3  306.48  5469.7   305.6  5475.4  307.31  5513.8  306.79
  5560.8  308.91  5624.1  312.52  5629.7  314.44  5651.8  314.25  5765.5  321.19
#Mann= 7 ,-1 , 0
  4571.9      .8       0  4993.7     .12       0  5001.5     .07       0
  5007.5     .08       0  5258.6     .16       0    5360     .05       0
  5560.8     .16       0
Bank Sta=5001.5,5007.5
XS Rating Curve= 0 ,0
Exp/Cntr=0.3,0.1

Chan Stop Cuts=-1
Use User Specified Reach Order=0
Composite Channel Slope=5