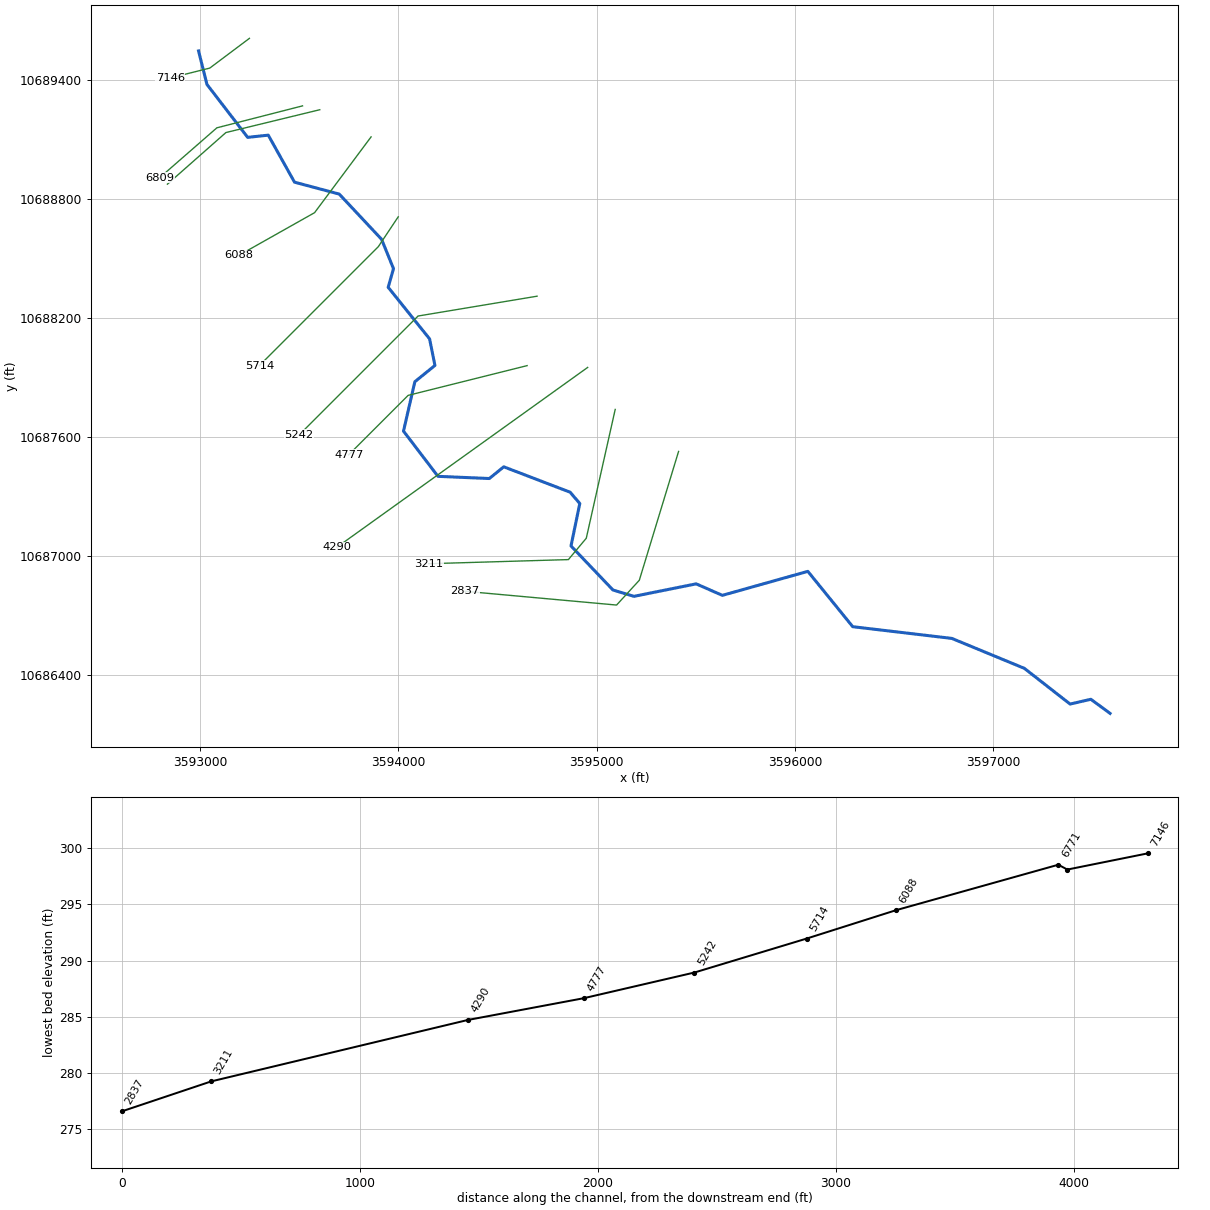
--- UNT198 IN CCTC.prj (project) ---

Proj Title=UNT198 IN CCTC Base Level Engineering
Current Plan=p01
Default Exp/Contr=0.3,0.1
English Units
Geom File=g01
Flow File=f01
Plan File=p01
BEGIN DESCRIPTION:
UNT198 IN CCTC
END DESCRIPTION:

--- UNT198 IN CCTC.p01 (plan) ---

Plan Title=Multiple Run
Short Identifier=Multiple
Geom File=g01
Flow File=f01
Subcritical Flow
K Sum by GR= 0
Std Step Tol= 0.01
Critical Tol= 0.01
Num of Std Step Trials= 20
Max Error Tol= 0.3
Flow Tol Ratio= 0.001
Split Flow NTrial= 30
Split Flow Tol= 0.02
Split Flow Ratio= 0.02
Log Output Level= 0
Friction Slope Method= 1
Unsteady Friction Slope Method= 2
Unsteady Bridges Friction Slope Method= 1
Parabolic Critical Depth
Global Vel Dist=  1 , 1 , 1
Global Log Level= 0
CheckData=True
Encroach Param= -1, 0, 0, 0
BEGIN DESCRIPTION:
Multiple Run
END DESCRIPTION:

--- UNT198 IN CCTC.f01 (steady flow) ---

Flow Title=Multiple
Number of Profiles=7
Profile Names=10-year,25-year,50-year,1pct_min,100-year,1pct_plu,500-year
River Rch & RM= UNT198 IN CCTC,Reach-1,7146
    1335    1840    2258    2024    2737    3701    4006
River Rch & RM= UNT198 IN CCTC,Reach-1,4290
    1656    2305    2847    2565    3469    4692    5136
Boundary for River Rch & Prof#=UNT198 IN CCTC,Reach-1,1
Up Type=0
Dn Type=3
Dn Slope=0.005
Boundary for River Rch & Prof#=UNT198 IN CCTC,Reach-1,2
Up Type=0
Dn Type=3
Dn Slope=0.005
Boundary for River Rch & Prof#=UNT198 IN CCTC,Reach-1,3
Up Type=0
Dn Type=3
Dn Slope=0.005
Boundary for River Rch & Prof#=UNT198 IN CCTC,Reach-1,4
Up Type=0
Dn Type=3
Dn Slope=0.005
Boundary for River Rch & Prof#=UNT198 IN CCTC,Reach-1,5
Up Type=0
Dn Type=3
Dn Slope=0.005
Boundary for River Rch & Prof#=UNT198 IN CCTC,Reach-1,6
Up Type=0
Dn Type=3
Dn Slope=0.005
Boundary for River Rch & Prof#=UNT198 IN CCTC,Reach-1,7
Up Type=0
Dn Type=3
Dn Slope=0.005

--- UNT198 IN CCTC.g01 (geometry) ---

Geom Title=Existing Conditions

River Reach=UNT198 IN CCTC,Reach-1
Reach XY= 30
      3592993.05     10689546.60      3593035.25     10689378.00
      3593240.50     10689111.00      3593344.50     10689122.00
      3593476.75     10688885.00      3593702.25     10688825.00
      3593915.75     10688597.00      3593975.75     10688449.00
      3593949.00     10688355.00      3594157.75     10688095.00
      3594184.75     10687961.00      3594083.50     10687879.00
      3594026.25     10687630.00      3594200.00     10687402.00
      3594459.00     10687391.00      3594531.75     10687450.00
      3594866.25     10687322.00      3594915.00     10687265.00
      3594870.75     10687051.00      3595082.25     10686829.00
      3595188.00     10686797.00      3595501.75     10686860.00
      3595633.75     10686802.00      3596064.75     10686923.00
      3596291.00     10686644.00      3596790.50     10686585.00
      3597156.25     10686434.00      3597386.75     10686254.00
      3597491.50     10686278.00      3597588.50     10686207.00

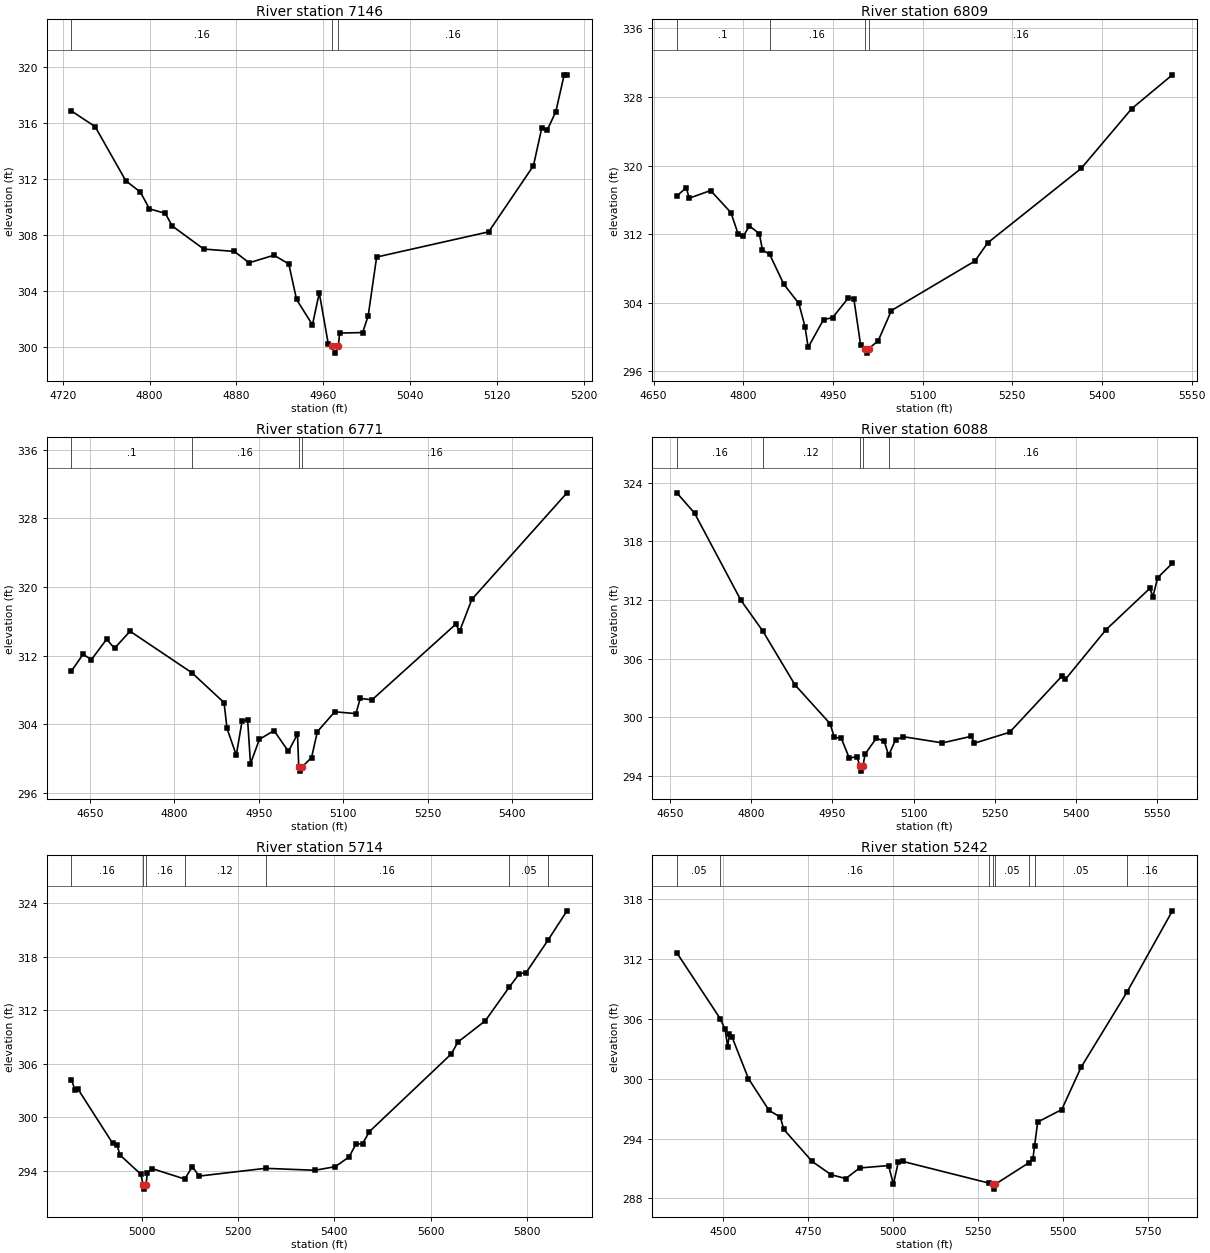
Type RM Length L Ch R = 1,7146,337,337,337
BEGIN DESCRIPTION:
UNT198 IN CCTC 9.0
END DESCRIPTION:
XS GIS Cut Line= 3
      3593249.57     10689610.16      3593049.61     10689460.19
      3592849.62     10689410.19
#Sta/Elev= 30
  4728.1  316.84  4749.9  315.72  4778.1  311.86  4791.6  311.04  4799.9  309.85
  4814.5  309.53  4820.8  308.63  4849.9  306.98  4878.1  306.81  4891.6  306.00
  4914.5  306.54  4928.1  305.92  4935.3  303.38  4949.9  301.57  4956.2  303.85
  4964.5  300.20  4967.8  300.05  4970.5  299.55  4973.8  300.05  4974.9  300.98
  4996.1  301.02  5001.2  302.21  5009.0  306.41  5112.1  308.21  5153.3  312.93
  5161.0  315.63  5166.2  315.51  5173.9  316.79  5181.6  319.42  5184.2  319.42
#Mann=3,-1,0
  4728.1    0.16       0  4967.8    0.07       0  4973.8    0.16       0
Bank Sta=4967.8,4973.8
Exp/Cntr=0.3,0.1

Type RM Length L Ch R = 1,6809,38,38,38
BEGIN DESCRIPTION:
Mapping XS a4bdfd32
END DESCRIPTION:
XS GIS Cut Line= 3
      3593517.25     10689269.73      3593085.38     10689159.05
      3592796.77     10688907.33
#Sta/Elev= 30
  4689.0  316.45  4704.7  317.41  4709.8  316.19  4745.5  317.08  4779.5  314.50
  4791.4  312.04  4800.1  311.74  4810.4  312.95  4827.0  312.04  4832.2  310.14
  4844.2  309.64  4867.8  306.16  4893.0  303.91  4903.4  301.20  4908.6  298.78
  4934.3  302.02  4949.4  302.25  4975.6  304.53  4985.0  304.48  4996.3  299.09
  5003.6  298.61  5006.3  298.11  5009.6  298.61  5025.8  299.56  5047.9  303.08
  5187.6  308.86  5208.8  310.97  5365.2  319.66  5449.6  326.62  5517.8  330.58
#Mann=4,-1,0
  4689.0     0.1       0  4844.2    0.16       0  5003.6    0.07       0
  5009.6    0.16       0
Bank Sta=5003.6,5009.6
Exp/Cntr=0.3,0.1

Type RM Length L Ch R = 1,6771,683,683,683
BEGIN DESCRIPTION:
UNT198 IN CCTC 8.0
END DESCRIPTION:
XS GIS Cut Line= 3
      3593604.08     10689250.21      3593130.96     10689135.18
      3592836.05     10688874.97
#Sta/Elev= 30
  4617.2  310.20  4637.8  312.15  4652.7  311.53  4679.6  313.90  4693.8  312.85
  4721.3  314.84  4830.9  310.01  4888.3  306.52  4893.5  303.52  4910.0  300.40
  4920.3  304.39  4930.1  304.52  4935.2  299.41  4951.1  302.25  4977.0  303.26
  5002.6  300.84  5018.7  302.86  5020.9  299.04  5023.6  298.54  5026.9  299.04
  5043.7  300.12  5054.0  303.14  5084.9  305.45  5122.6  305.24  5130.1  307.02
  5151.0  306.84  5299.9  315.66  5306.6  314.83  5328.4  318.55  5497.4  330.96
#Mann=4,-1,0
  4617.2     0.1       0  4830.9    0.16       0  5020.9    0.07       0
  5026.9    0.16       0
Bank Sta=5020.9,5026.9
Exp/Cntr=0.3,0.1

Type RM Length L Ch R = 1,6088,374,374,374
BEGIN DESCRIPTION:
UNT198 IN CCTC 7.0
END DESCRIPTION:
XS GIS Cut Line= 3
      3593862.76     10689113.23      3593578.01     10688731.25
      3593196.04     10688515.96
#Sta/Elev= 30
  4662.9  322.96  4695.6  320.88  4781.1  311.97  4821.7  308.81  4881.1  303.30
  4945.8  299.34  4953.6  297.95  4966.6  297.83  4981.2  295.82  4995.8  295.96
  5000.5  294.98  5003.2  294.48  5006.5  294.98  5010.4  296.22  5031.3  297.85
  5045.9  297.53  5053.9  296.09  5066.7  297.69  5081.3  298.00  5153.2  297.37
  5206.4  298.04  5212.4  297.34  5277.4  298.46  5374.3  304.23  5380.0  303.86
  5455.2  308.95  5536.1  313.18  5541.8  312.35  5550.7  314.28  5577.8  315.75
#Mann=5,-1,0
  4662.9    0.16       0  4821.7    0.12       0  5000.5    0.07       0
  5006.5    0.12       0  5053.9    0.16       0
Bank Sta=5000.5,5006.5
Exp/Cntr=0.3,0.1

Type RM Length L Ch R = 1,5714,472,472,472
BEGIN DESCRIPTION:
UNT198 IN CCTC 6.0
END DESCRIPTION:
XS GIS Cut Line= 3
      3593999.59     10688710.16      3593899.61     10688560.19
      3593299.59     10687960.17
#Sta/Elev= 30
  4854.1  304.22  4861.6  303.04  4867.6  303.17  4939.7  297.09  4948.7  296.92
  4954.7  295.79  4998.3  293.62  5002.8  292.46  5005.6  291.96  5008.8  292.46
  5011.8  293.75  5020.8  294.27  5089.4  293.09  5105.1  294.48  5119.2  293.42
  5257.0  294.29  5359.6  294.07  5402.0  294.48  5430.3  295.56  5444.5  296.97
  5458.6  297.07  5472.8  298.41  5642.5  307.09  5656.6  308.44  5713.2  310.81
  5762.7  314.56  5783.9  316.09  5798.0  316.21  5843.2  319.82  5882.9  323.13
#Mann=7,-1,0
  4854.1    0.16       0  5002.8    0.07       0  5008.8    0.16       0
  5089.4    0.12       0  5257.0    0.16       0  5762.7    0.05       0
  5843.2    0.16       0
Bank Sta=5002.8,5008.8
Exp/Cntr=0.3,0.1

Type RM Length L Ch R = 1,5242,465,465,465
BEGIN DESCRIPTION:
UNT198 IN CCTC 5.0
END DESCRIPTION:
XS GIS Cut Line= 3
      3594699.62     10688310.19      3594099.61     10688210.19
      3593499.62     10687610.20
#Sta/Elev= 30
  4363.7  312.60  4491.2  306.01  4505.6  304.94  4513.2  303.18  4518.3  304.49
  4525.9  304.17  4574.1  300.01  4634.9  296.81  4667.9  296.15  4678.0  294.92
  4761.6  291.70  4817.4  290.37  4860.5  289.99  4901.0  291.05  4986.1  291.29
  5000.3  289.43  5014.4  291.60  5028.6  291.70  5280.5  289.54  5294.3  289.43
  5297.0  288.93  5300.3  289.43  5398.5  291.57  5410.4  291.97  5415.2  293.22
  5424.5  295.65  5495.2  296.90  5551.8  301.12  5686.4  308.63  5820.5  316.81
#Mann=8,-1,0
  4363.7    0.05       0  4491.2    0.16       0  5280.5    0.05       0
  5294.3    0.07       0  5300.3    0.05       0  5398.5    0.16       0
  5415.2    0.05       0  5686.4    0.16       0
Bank Sta=5294.3,5300.3
Exp/Cntr=0.3,0.1

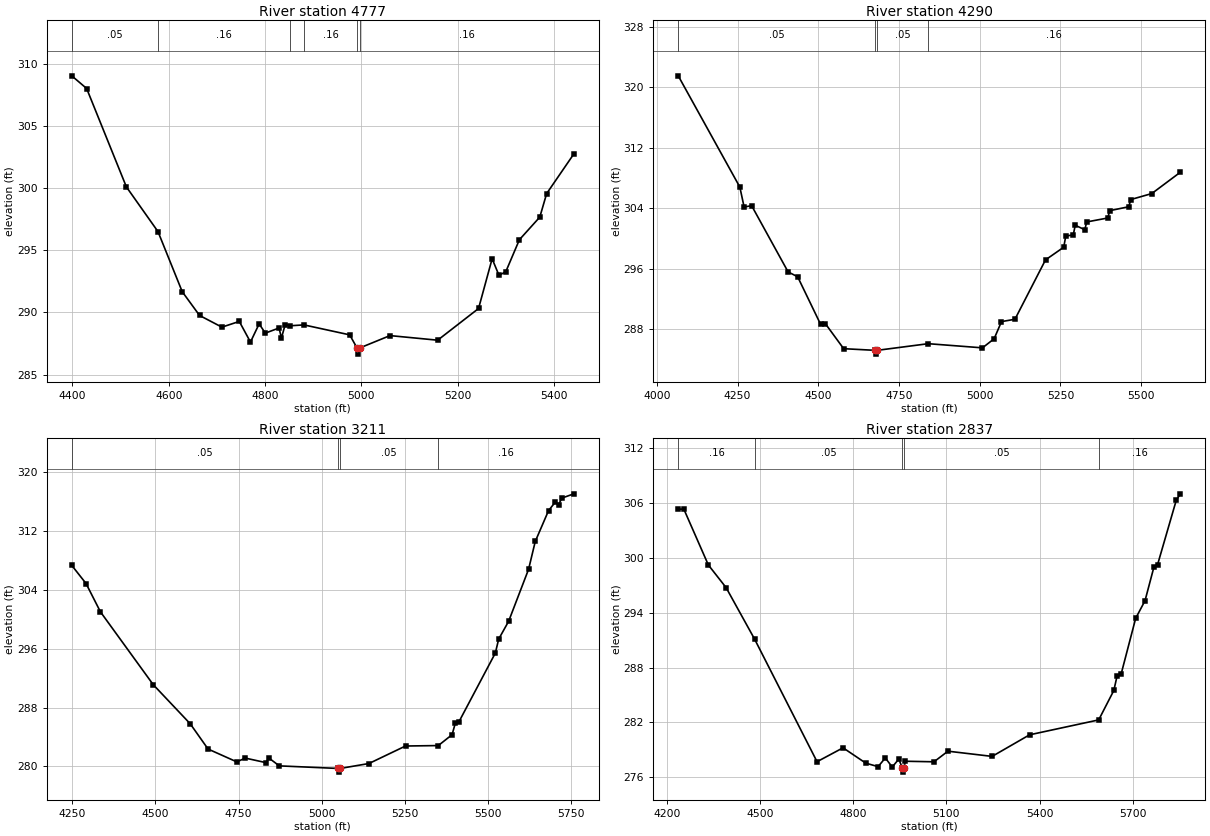
Type RM Length L Ch R = 1,4777,487,487,487
BEGIN DESCRIPTION:
UNT198 IN CCTC 4.0
END DESCRIPTION:
XS GIS Cut Line= 3
      3594649.62     10687960.19      3594049.61     10687810.19
      3593749.64     10687510.22
#Sta/Elev= 30
  4398.5  309.02  4429.4  308.00  4511.9  300.09  4577.6  296.49  4627.9  291.66
  4663.9  289.75  4710.3  288.81  4746.4  289.27  4769.6  287.61  4787.6  289.07
  4800.5  288.33  4828.9  288.74  4834.0  287.94  4841.7  289.02  4851.6  288.92
  4880.7  288.99  4975.7  288.19  4990.8  287.14  4993.5  286.64  4996.8  287.14
  5059.4  288.13  5158.4  287.76  5243.3  290.31  5271.5  294.31  5285.7  292.98
  5299.8  293.26  5328.1  295.84  5370.5  297.66  5384.7  299.55  5441.2  302.74
#Mann=6,-1,0
  4398.5    0.05       0  4577.6    0.16       0  4851.6    0.12       0
  4880.7    0.16       0  4990.8    0.07       0  4996.8    0.16       0
Bank Sta=4990.8,4996.8
Exp/Cntr=0.3,0.1

Type RM Length L Ch R = 1,4290,1079,1079,1079
BEGIN DESCRIPTION:
UNT198 IN CCTC 3.0
END DESCRIPTION:
XS GIS Cut Line= 2
      3594954.66     10687951.04      3593691.03     10687044.97
#Sta/Elev= 30
  4066.2  321.50  4257.0  306.79  4270.2  304.15  4293.5  304.33  4406.5  295.57
  4436.0  294.93  4507.3  288.62  4522.0  288.72  4578.5  285.42  4676.2  285.20
  4678.9  284.70  4682.2  285.20  4840.5  286.08  5008.3  285.53  5044.5  286.73
  5067.3  289.00  5109.0  289.31  5203.6  297.16  5260.1  298.84  5266.3  300.31
  5289.6  300.47  5295.7  301.74  5325.2  301.15  5331.3  302.18  5396.4  302.70
  5402.6  303.67  5461.5  304.19  5467.7  305.14  5532.7  305.93  5621.1  308.75
#Mann=4,-1,0
  4066.2    0.05       0  4676.2    0.07       0  4682.2    0.05       0
  4840.5    0.16       0
Bank Sta=4676.2,4682.2
Exp/Cntr=0.3,0.1

Type RM Length L Ch R = 1,3211,374,374,374
BEGIN DESCRIPTION:
UNT198 IN CCTC 2.0
END DESCRIPTION:
XS GIS Cut Line= 4
      3595093.53     10687739.19      3594947.70     10687089.91
      3594857.42     10686982.27      3594153.57     10686961.47
#Sta/Elev= 30
  4248.2  307.32  4291.1  304.86  4334.4  301.01  4493.2  291.11  4604.5  285.79
  4658.1  282.36  4744.7  280.61  4769.9  281.13  4831.4  280.52  4841.6  281.12
  4872.4  280.07  5049.2  279.72  5052.0  279.22  5055.2  279.72  5142.0  280.39
  5252.0  282.77  5350.6  282.83  5392.1  284.31  5402.1  285.93  5412.1  286.01
  5522.2  295.41  5532.2  297.30  5562.2  299.73  5622.2  306.80  5642.2  310.57
  5682.2  314.77  5702.2  315.91  5712.2  315.57  5722.2  316.47  5758.3  317.05
#Mann=4,-1,0
  4248.2    0.05       0  5049.2    0.03       0  5055.2    0.05       0
  5350.6    0.16       0
Bank Sta=5049.2,5055.2
Exp/Cntr=0.3,0.1

Type RM Length L Ch R = 1,2837,0,0,0
BEGIN DESCRIPTION:
UNT198 IN CCTC 1.0
END DESCRIPTION:
XS GIS Cut Line= 4
      3595412.98     10687527.42      3595215.06     10686878.11
      3595100.48     10686753.11      3594336.61     10686822.55
#Sta/Elev= 30
  4237.2  305.31  4255.2  305.32  4334.1  299.21  4391.1  296.74  4483.1  291.09
  4683.8  277.70  4767.5  279.22  4840.7  277.54  4880.3  277.16  4903.4  278.11
  4925.7  277.12  4946.7  277.98  4957.9  277.06  4960.6  276.56  4963.9  277.06
  4967.7  277.75  5060.1  277.69  5105.0  278.85  5247.1  278.28  5367.6  280.64
  5590.0  282.27  5638.7  285.49  5648.8  287.02  5662.3  287.30  5709.0  293.38
  5739.1  295.31  5767.8  299.00  5779.3  299.23  5839.5  306.28  5852.6  306.99
#Mann=5,-1,0
  4237.2    0.16       0  4483.1    0.05       0  4957.9    0.03       0
  4963.9    0.05       0  5590.0    0.16       0
Bank Sta=4957.9,4963.9
Exp/Cntr=0.3,0.1

Chan Stop Cuts=-1