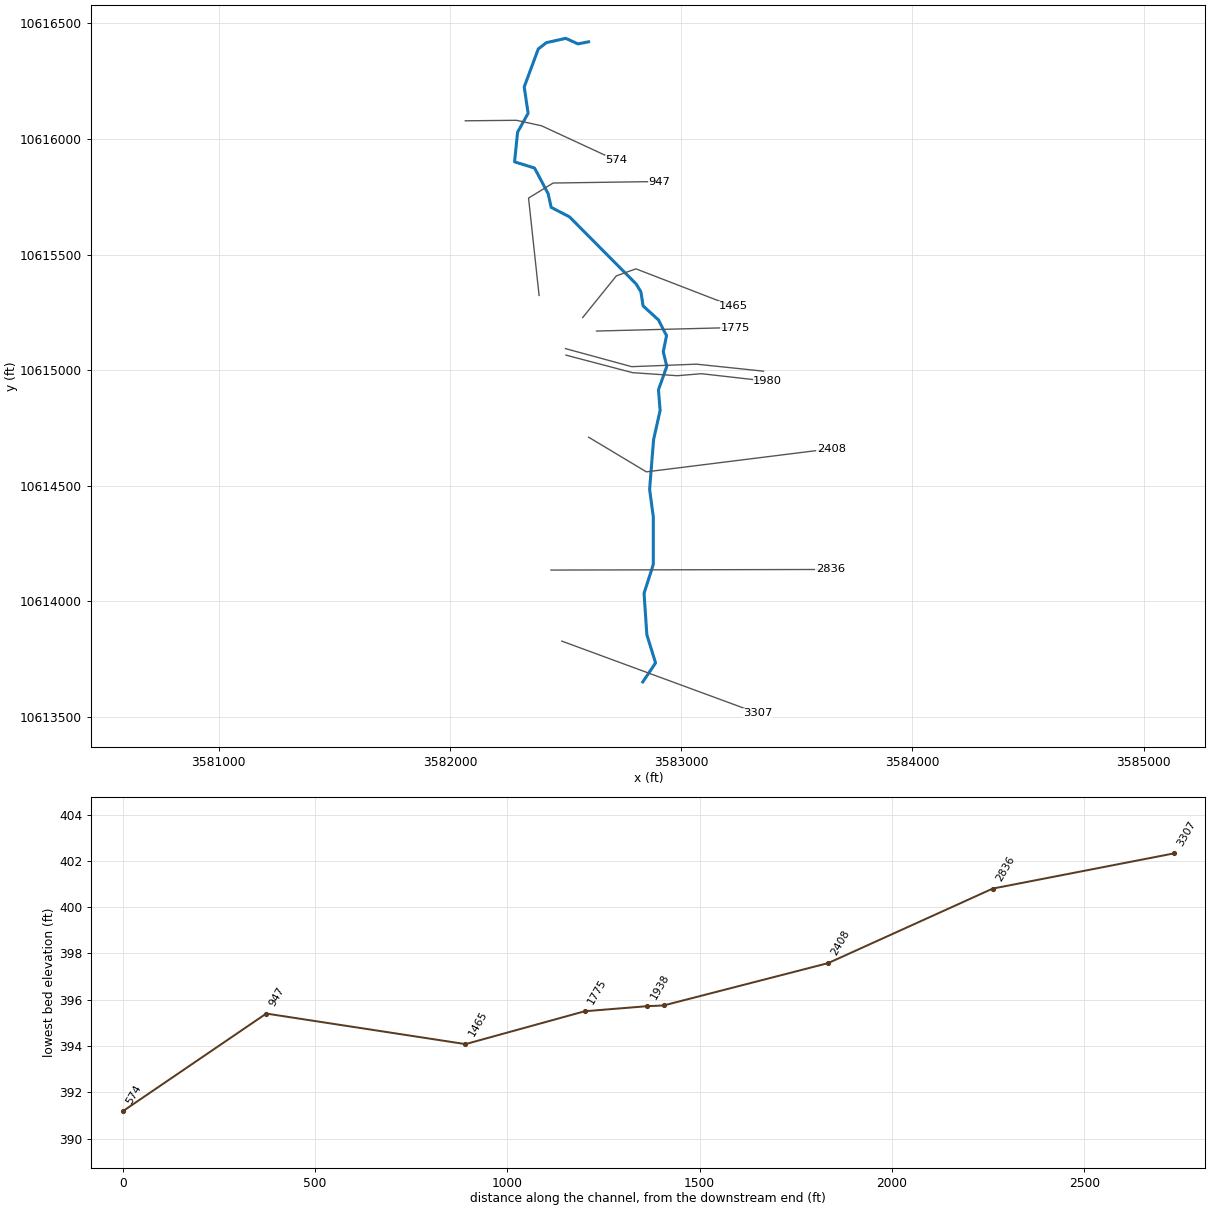
--- UNT203 IN CCTC.prj (project) ---

Proj Title=UNT203 IN CCTC Base Level Engineering
Current Plan=p01
Default Exp/Contr=0.3,0.1
English Units
Geom File=g01
Flow File=f01
Plan File=p01
BEGIN DESCRIPTION:
UNT203 IN CCTC
END DESCRIPTION:

--- UNT203 IN CCTC.p01 (plan) ---

Plan Title=Multiple Run
Short Identifier=Multiple
Geom File=g01
Flow File=f01
Subcritical Flow
K Sum by GR= 0
Std Step Tol= 0.01
Critical Tol= 0.01
Num of Std Step Trials= 20
Max Error Tol= 0.3
Flow Tol Ratio= 0.001
Split Flow NTrial= 30
Split Flow Tol= 0.02
Split Flow Ratio= 0.02
Log Output Level= 0
Friction Slope Method= 1
Unsteady Friction Slope Method= 2
Unsteady Bridges Friction Slope Method= 1
Parabolic Critical Depth
Global Vel Dist=  1 , 1 , 1
Global Log Level= 0
CheckData=True
Encroach Param= -1, 0, 0, 0
BEGIN DESCRIPTION:
Multiple Run
END DESCRIPTION:

--- UNT203 IN CCTC.f01 (steady flow) ---

Flow Title=Multiple
Number of Profiles=7
Profile Names=10-year,25-year,50-year,1pct_min,100-year,1pct_plu,500-year
River Rch & RM= UNT203 IN CCTC,Reach-1,3307
    1644    2277    2804    2519    3407    4608    5012
Boundary for River Rch & Prof#=UNT203 IN CCTC,Reach-1,1
Up Type=0
Dn Type=3
Dn Slope=0.005
Boundary for River Rch & Prof#=UNT203 IN CCTC,Reach-1,2
Up Type=0
Dn Type=3
Dn Slope=0.005
Boundary for River Rch & Prof#=UNT203 IN CCTC,Reach-1,3
Up Type=0
Dn Type=3
Dn Slope=0.005
Boundary for River Rch & Prof#=UNT203 IN CCTC,Reach-1,4
Up Type=0
Dn Type=3
Dn Slope=0.005
Boundary for River Rch & Prof#=UNT203 IN CCTC,Reach-1,5
Up Type=0
Dn Type=3
Dn Slope=0.005
Boundary for River Rch & Prof#=UNT203 IN CCTC,Reach-1,6
Up Type=0
Dn Type=3
Dn Slope=0.005
Boundary for River Rch & Prof#=UNT203 IN CCTC,Reach-1,7
Up Type=0
Dn Type=3
Dn Slope=0.005

--- UNT203 IN CCTC.g01 (geometry) ---

Geom Title=Existing Conditions

River Reach=UNT203 IN CCTC,Reach-1
Reach XY= 30
      3582833.86     10613651.61      3582889.25     10613734.00
      3582851.50     10613856.00      3582839.50     10614035.00
      3582879.50     10614160.00      3582879.50     10614365.00
      3582863.50     10614485.00      3582880.75     10614700.00
      3582909.00     10614826.00      3582901.75     10614915.00
      3582937.75     10615016.00      3582922.50     10615080.00
      3582936.75     10615149.00      3582902.00     10615217.00
      3582835.25     10615278.00      3582825.75     10615339.00
      3582805.00     10615373.00      3582517.00     10615663.00
      3582437.75     10615704.00      3582424.75     10615763.00
      3582366.00     10615874.00      3582279.50     10615901.00
      3582292.50     10616029.00      3582338.00     10616111.00
      3582321.25     10616225.00      3582382.00     10616389.00
      3582416.50     10616416.00      3582500.75     10616435.00
      3582553.50     10616411.00      3582599.50     10616420.00

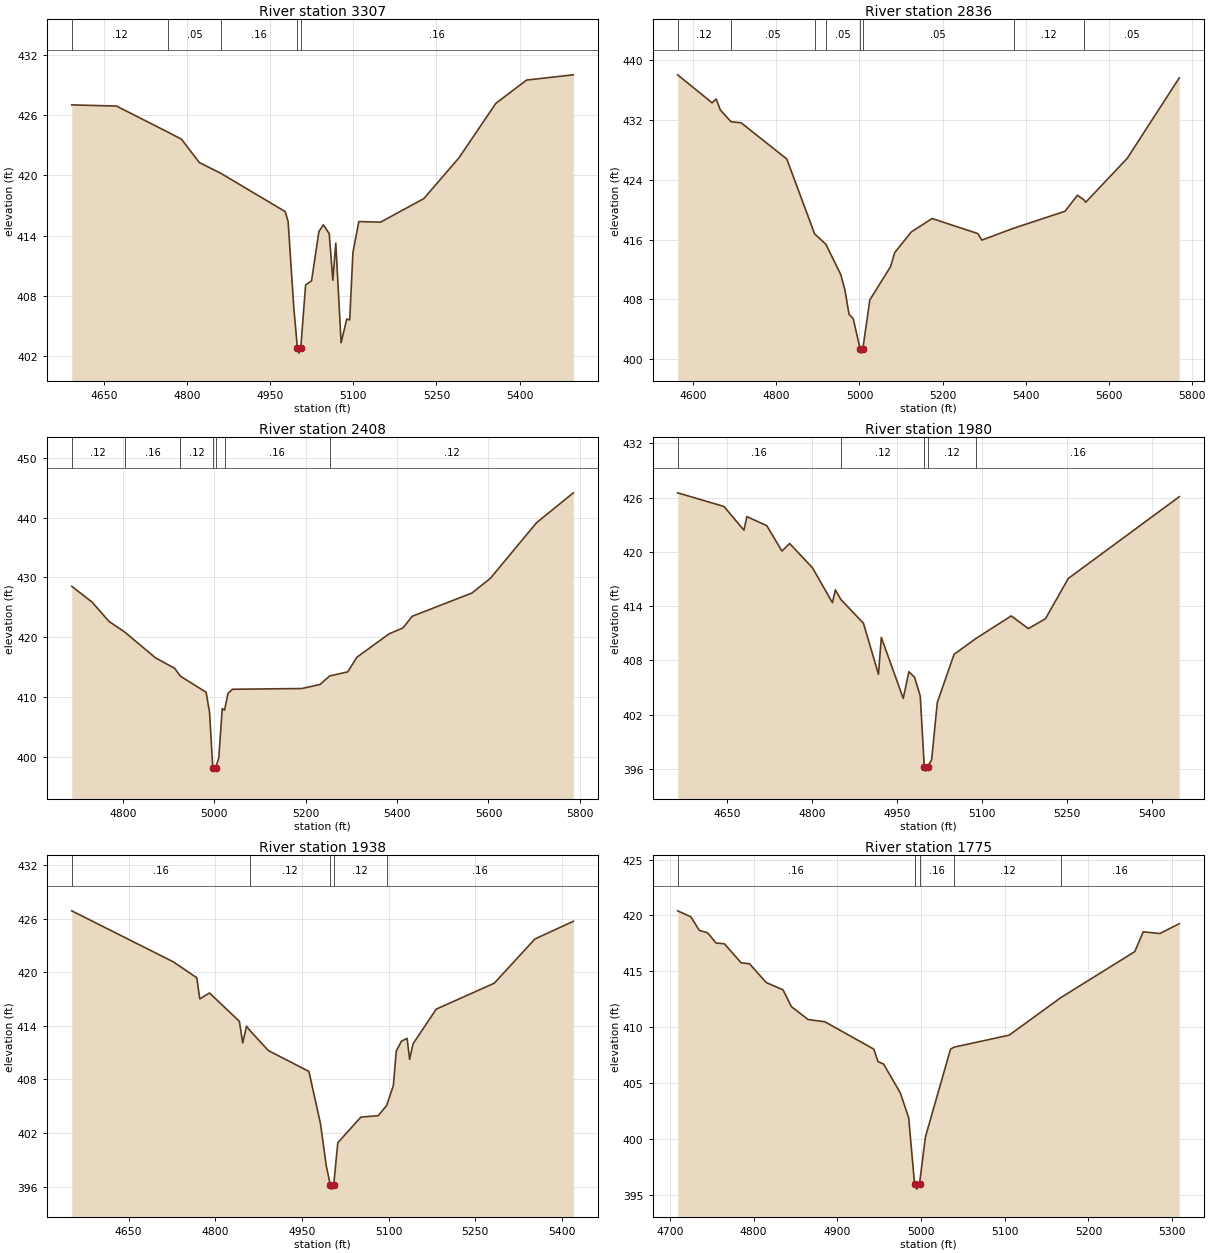
Type RM Length L Ch R = 1,3307,471,471,471
BEGIN DESCRIPTION:
UNT203 IN CCTC 4.0
END DESCRIPTION:
XS GIS Cut Line= 2
      3582483.76     10613828.23      3583332.67     10613515.74
#Sta/Elev= 30
  4592.2  427.02  4673.0  426.90  4765.6  424.31  4790.2  423.60  4822.2  421.29
  4861.4  420.20  4977.0  416.41  4982.4  415.43  4992.7  406.82  4999.2  402.82
  5001.9  402.32  5005.2  402.82  5014.0  409.11  5024.7  409.51  5037.9  414.41
  5046.0  415.09  5056.6  414.20  5063.1  409.57  5068.4  413.27  5078.0  403.35
  5088.2  405.71  5093.5  405.63  5099.3  412.33  5109.9  415.41  5149.1  415.35
  5227.1  417.69  5290.8  421.77  5357.0  427.17  5412.6  429.49  5496.8  430.01
#Mann=5,-1,0
  4592.2    0.12       0  4765.6    0.05       0  4861.4    0.16       0
  4999.2    0.07       0  5005.2    0.16       0
Bank Sta=4999.2,5005.2
Exp/Cntr=0.3,0.1

Type RM Length L Ch R = 1,2836,428,428,428
BEGIN DESCRIPTION:
Mapping XS ad1c02ef
END DESCRIPTION:
XS GIS Cut Line= 2
      3582436.85     10614135.52      3583644.95     10614138.12
#Sta/Elev= 30
  4562.1  438.06  4644.9  434.32  4654.9  434.82  4664.9  433.35  4690.6  431.78
  4714.9  431.64  4824.9  426.79  4891.9  416.77  4919.1  415.37  4954.9  411.32
  4964.9  409.26  4974.9  405.99  4984.9  405.42  5001.9  401.30  5004.6  400.80
  5007.9  401.30  5024.9  407.93  5074.9  412.38  5084.9  414.26  5124.9  417.03
  5174.9  418.82  5284.9  416.81  5294.9  415.94  5371.3  417.52  5494.9  419.79
  5524.9  421.93  5540.2  421.35  5544.9  421.00  5644.9  426.88  5770.2  437.65
#Mann=8,-1,0
  4562.1    0.12       0  4690.6    0.05       0  4891.9    0.08       0
  4919.1    0.05       0  5001.9    0.03       0  5007.9    0.05       0
  5371.3    0.12       0  5540.2    0.05       0
Bank Sta=5001.9,5007.9
Exp/Cntr=0.3,0.1

Type RM Length L Ch R = 1,2408,428,428,428
BEGIN DESCRIPTION:
UNT203 IN CCTC 3.0
END DESCRIPTION:
XS GIS Cut Line= 3
      3582599.59     10614710.20      3582849.61     10614560.19
      3583649.61     10614660.19
#Sta/Elev= 30
  4687.9  428.51  4732.6  425.85  4769.6  422.62  4803.9  420.85  4870.6  416.57
  4913.4  414.77  4925.8  413.46  4982.0  410.78  4989.5  407.43  4996.6  398.08
  4999.4  397.58  5002.6  398.08  5009.7  399.79  5017.3  408.06  5022.3  407.77
  5023.8  408.33  5029.9  410.60  5039.9  411.28  5191.1  411.40  5231.4  412.08
  5252.1  413.50  5291.9  414.19  5312.0  416.64  5382.6  420.56  5412.8  421.54
  5433.0  423.49  5564.0  427.39  5604.3  429.86  5705.1  439.14  5785.7  444.15
#Mann=7,-1,0
  4687.9    0.12       0  4803.9    0.16       0  4925.8    0.12       0
  4996.6    0.07       0  5002.6    0.12       0  5023.8    0.16       0
  5252.1    0.12       0
Bank Sta=4996.6,5002.6
Exp/Cntr=0.3,0.1

Type RM Length L Ch R = 1,1980,42,42,42
BEGIN DESCRIPTION:
Mapping XS e86b24d7
END DESCRIPTION:
XS GIS Cut Line= 5
      3582501.79     10615064.98      3582790.40     10614989.04
      3582983.54     10614976.01      3583087.71     10614984.70
      3583374.13     10614952.15
#Sta/Elev= 30
  4563.2  426.52  4644.9  425.01  4680.1  422.39  4685.2  423.89  4720.4  422.89
  4747.1  420.08  4760.7  420.92  4801.0  418.23  4836.2  414.37  4841.4  415.79
  4850.9  414.74  4890.9  412.10  4917.4  406.46  4922.4  410.54  4961.1  403.79
  4971.1  406.74  4981.1  406.13  4991.1  404.05  4998.2  396.25  5000.9  395.75
  5004.2  396.25  5011.2  397.01  5021.2  403.34  5050.7  408.66  5089.2  410.41
  5151.6  412.91  5181.8  411.51  5212.0  412.60  5252.2  417.05  5448.0  426.09
#Mann=5,-1,0
  4563.2    0.16       0  4850.9    0.12       0  4998.2    0.07       0
  5004.2    0.12       0  5089.2    0.16       0
Bank Sta=4998.2,5004.2
Exp/Cntr=0.3,0.1

Type RM Length L Ch R = 1,1938,163,163,163
BEGIN DESCRIPTION:
UNT203 IN CCTC 2.0
END DESCRIPTION:
XS GIS Cut Line= 4
      3582499.60     10615093.20      3582786.06     10615015.08
      3583066.01     10615025.93      3583355.75     10614995.66
#Sta/Elev= 30
  4551.6  426.86  4727.8  421.14  4768.1  419.37  4773.3  417.00  4790.0  417.67
  4841.8  414.50  4847.6  412.08  4854.2  413.95  4860.2  413.46  4892.1  411.22
  4962.2  408.89  4982.2  403.06  4992.2  398.36  4999.2  396.22  5001.9  395.72
  5005.2  396.22  5012.2  400.91  5052.2  403.78  5082.2  403.94  5096.8  405.08
  5108.4  407.31  5113.4  411.16  5122.3  412.27  5132.2  412.59  5136.6  410.24
  5142.4  411.97  5182.6  415.86  5283.1  418.76  5353.5  423.71  5420.0  425.69
#Mann=5,-1,0
  4551.6    0.16       0  4860.2    0.12       0  4999.2    0.07       0
  5005.2    0.12       0  5096.8    0.16       0
Bank Sta=4999.2,5005.2
Exp/Cntr=0.3,0.1

Type RM Length L Ch R = 1,1775,310,310,310
BEGIN DESCRIPTION:
Mapping XS c82c0d8f
END DESCRIPTION:
XS GIS Cut Line= 2
      3582633.82     10615169.16      3583232.73     10615184.35
#Sta/Elev= 30
  4709.4  420.41  4725.2  419.87  4735.2  418.66  4745.2  418.44  4755.2  417.53
  4765.2  417.46  4785.2  415.76  4795.2  415.67  4815.2  413.99  4835.2  413.34
  4845.2  411.84  4865.2  410.68  4885.2  410.48  4943.7  408.03  4948.7  406.91
  4955.3  406.70  4975.3  404.12  4985.3  401.89  4992.3  396.00  4995.0  395.50
  4998.3  396.00  5005.3  400.17  5035.3  408.03  5039.6  408.21  5105.3  409.28
  5166.8  412.63  5255.4  416.76  5265.4  418.53  5285.4  418.38  5308.5  419.26
#Mann=5,-1,0
  4709.4    0.16       0  4992.3    0.07       0  4998.3    0.16       0
  5039.6    0.12       0  5166.8    0.16       0
Bank Sta=4992.3,4998.3
Exp/Cntr=0.3,0.1

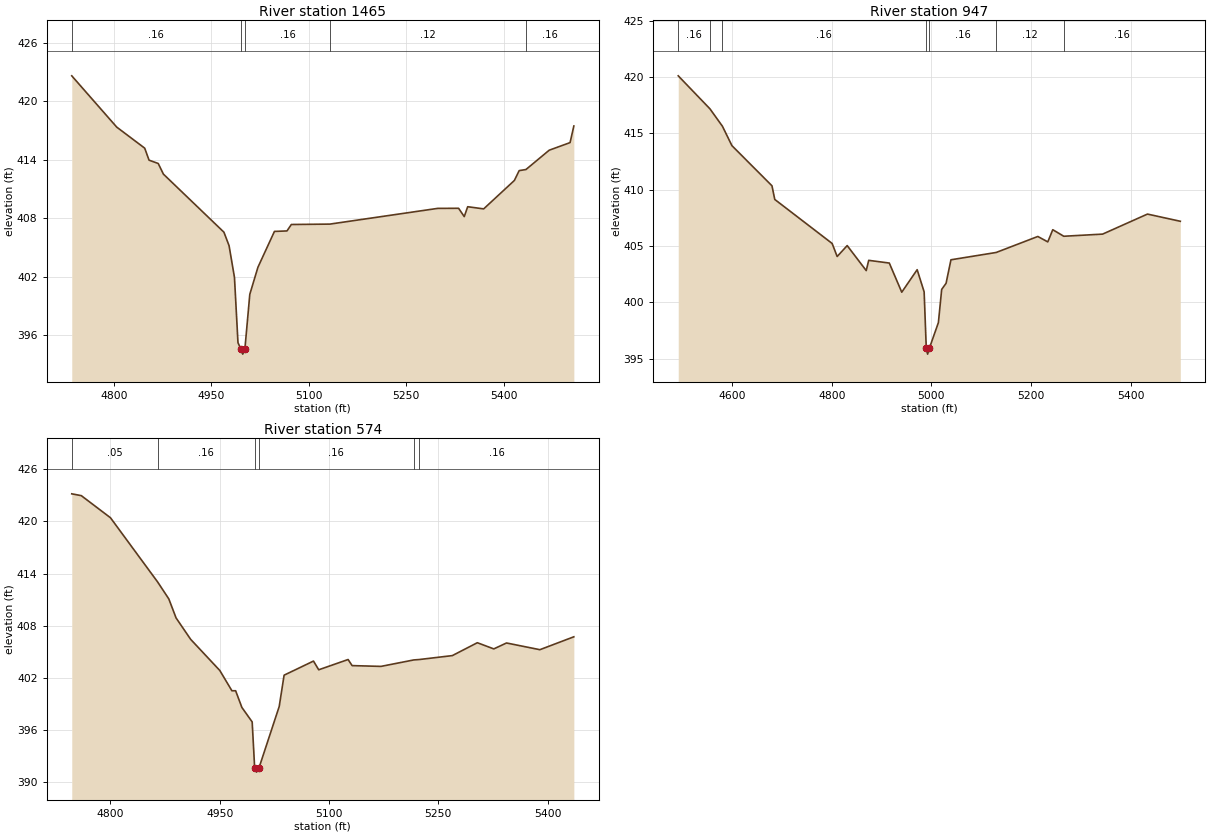
Type RM Length L Ch R = 1,1465,518,518,518
BEGIN DESCRIPTION:
Mapping XS 7dab3974
END DESCRIPTION:
XS GIS Cut Line= 4
      3582574.30     10615227.66      3582719.72     10615407.81
      3582804.36     10615438.19      3583224.98     10615275.58
#Sta/Elev= 30
  4735.3  422.59  4804.4  417.34  4847.5  415.18  4854.2  413.95  4868.3  413.61
  4876.3  412.52  4969.4  406.57  4977.3  405.19  4985.6  401.94  4991.0  395.25
  4995.6  394.58  4998.3  394.08  5001.6  394.58  5009.2  400.21  5021.7  402.98
  5047.1  406.65  5066.4  406.70  5073.1  407.36  5132.4  407.40  5298.2  409.01
  5330.4  409.02  5339.1  408.17  5344.4  409.18  5369.0  408.96  5416.2  411.87
  5423.6  412.88  5434.0  412.99  5469.8  414.97  5501.9  415.75  5507.7  417.45
#Mann=5,-1,0
  4735.3    0.16       0  4995.6    0.07       0  5001.6    0.16       0
  5132.4    0.12       0  5434.0    0.16       0
Bank Sta=4995.6,5001.6
Exp/Cntr=0.3,0.1

Type RM Length L Ch R = 1,947,373,373,373
BEGIN DESCRIPTION:
Mapping XS 78cf4ece
END DESCRIPTION:
XS GIS Cut Line= 4
      3582385.52     10615323.16      3582339.95     10615744.18
      3582446.28     10615809.29      3582905.47     10615815.78
#Sta/Elev= 30
  4492.0  420.12  4555.6  417.19  4580.7  415.64  4599.7  413.92  4680.1  410.35
  4685.7  409.14  4800.8  405.23  4810.9  404.07  4831.0  405.04  4869.2  402.82
  4874.2  403.73  4915.5  403.49  4940.5  400.90  4971.4  402.90  4985.4  400.93
  4989.7  395.90  4992.4  395.40  4995.7  395.90  5014.0  398.20  5020.6  401.15
  5029.4  401.69  5039.2  403.78  5130.0  404.43  5213.5  405.85  5233.5  405.37
  5243.5  406.45  5265.6  405.87  5343.5  406.06  5433.5  407.84  5499.4  407.20
#Mann=7,-1,0
  4492.0    0.16       0  4555.6    0.05       0  4580.7    0.16       0
  4989.7    0.07       0  4995.7    0.16       0  5130.0    0.12       0
  5265.6    0.16       0
Bank Sta=4989.7,4995.7
Exp/Cntr=0.3,0.1

Type RM Length L Ch R = 1,574,0,0,0
BEGIN DESCRIPTION:
UNT203 IN CCTC 1.0
END DESCRIPTION:
XS GIS Cut Line= 4
      3582066.50     10616078.38      3582287.86     10616080.55
      3582396.37     10616056.68      3582719.71     10615906.95
#Sta/Elev= 30
  4747.1  423.16  4760.2  422.95  4800.2  420.41  4865.0  413.02  4880.2  411.09
  4890.2  408.90  4910.2  406.44  4950.2  402.86  4966.8  400.53  4971.9  400.53
  4980.5  398.61  4994.6  396.95  4998.0  391.68  5000.7  391.18  5004.0  391.68
  5031.7  398.72  5038.4  402.32  5078.7  403.94  5085.9  402.94  5126.2  404.12
  5131.7  403.42  5171.3  403.33  5216.2  404.07  5224.0  404.12  5269.2  404.57
  5303.5  406.05  5326.1  405.34  5343.5  406.02  5389.3  405.25  5435.9  406.73
#Mann=6,-1,0
  4747.1    0.05       0  4865.0    0.16       0  4998.0    0.07       0
  5004.0    0.16       0  5216.2    0.12       0  5224.0    0.16       0
Bank Sta=4998,5004
Exp/Cntr=0.3,0.1

Chan Stop Cuts=-1