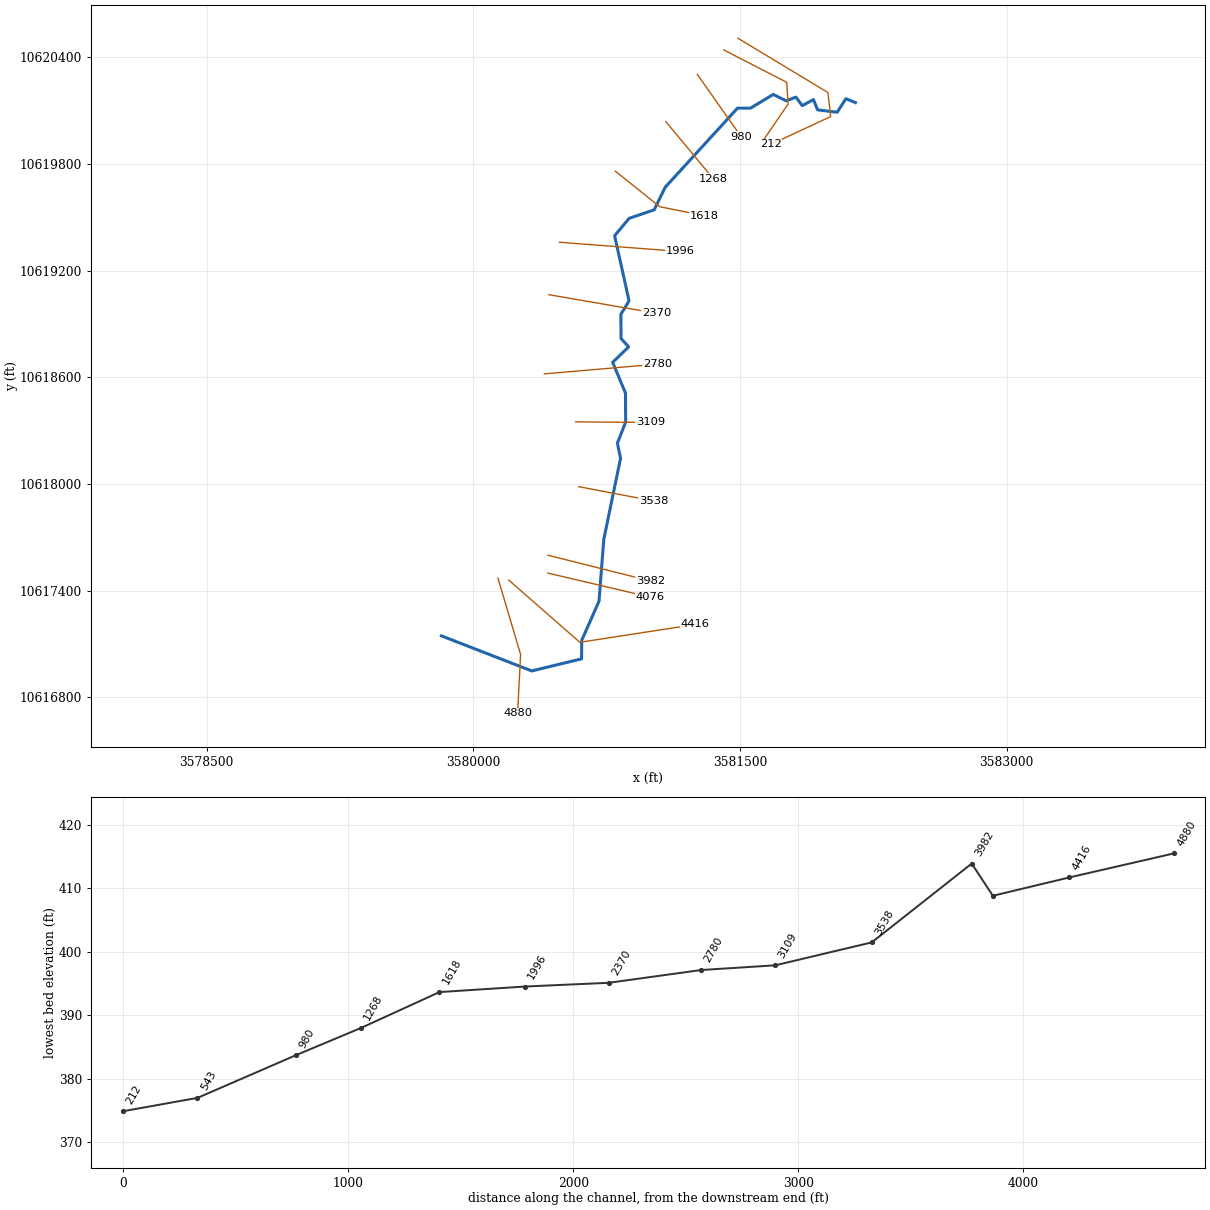
--- UNT204 IN CCTC.prj (project) ---

Proj Title=UNT204 IN CCTC Base Level Engineering
Current Plan=p01
Default Exp/Contr=0.3,0.1
English Units
Geom File=g01
Flow File=f01
Plan File=p01
BEGIN DESCRIPTION:
UNT204 IN CCTC
END DESCRIPTION:

--- UNT204 IN CCTC.p01 (plan) ---

Plan Title=Multiple Run
Short Identifier=Multiple
Geom File=g01
Flow File=f01
Subcritical Flow
K Sum by GR= 0
Std Step Tol= 0.01
Critical Tol= 0.01
Num of Std Step Trials= 20
Max Error Tol= 0.3
Flow Tol Ratio= 0.001
Split Flow NTrial= 30
Split Flow Tol= 0.02
Split Flow Ratio= 0.02
Log Output Level= 0
Friction Slope Method= 1
Unsteady Friction Slope Method= 2
Unsteady Bridges Friction Slope Method= 1
Parabolic Critical Depth
Global Vel Dist=  1 , 1 , 1
Global Log Level= 0
CheckData=True
Encroach Param= -1, 0, 0, 0
BEGIN DESCRIPTION:
Multiple Run
END DESCRIPTION:

--- UNT204 IN CCTC.f01 (steady flow) ---

Flow Title=Multiple
Number of Profiles=7
Profile Names=10-year,25-year,50-year,1pct_min,100-year,1pct_plu,500-year
River Rch & RM= UNT204 IN CCTC,Reach-1,4880
    1218    1637    1974    1737    2349    3176    3311
Boundary for River Rch & Prof#=UNT204 IN CCTC,Reach-1,1
Up Type=0
Dn Type=3
Dn Slope=0.005
Boundary for River Rch & Prof#=UNT204 IN CCTC,Reach-1,2
Up Type=0
Dn Type=3
Dn Slope=0.005
Boundary for River Rch & Prof#=UNT204 IN CCTC,Reach-1,3
Up Type=0
Dn Type=3
Dn Slope=0.005
Boundary for River Rch & Prof#=UNT204 IN CCTC,Reach-1,4
Up Type=0
Dn Type=3
Dn Slope=0.005
Boundary for River Rch & Prof#=UNT204 IN CCTC,Reach-1,5
Up Type=0
Dn Type=3
Dn Slope=0.005
Boundary for River Rch & Prof#=UNT204 IN CCTC,Reach-1,6
Up Type=0
Dn Type=3
Dn Slope=0.005
Boundary for River Rch & Prof#=UNT204 IN CCTC,Reach-1,7
Up Type=0
Dn Type=3
Dn Slope=0.005

--- UNT204 IN CCTC.g01 (geometry) ---

Geom Title=Existing Conditions

River Reach=UNT204 IN CCTC,Reach-1
Reach XY= 30
      3579821.05     10617146.28      3580329.00     10616949.00
      3580609.50     10617017.00      3580610.25     10617121.00
      3580707.50     10617341.00      3580734.50     10617689.00
      3580828.75     10618145.00      3580811.00     10618230.00
      3580857.50     10618349.00      3580856.50     10618512.00
      3580784.50     10618685.00      3580874.25     10618772.00
      3580831.50     10618819.00      3580830.75     10618955.00
      3580876.50     10619031.00      3580795.50     10619397.00
      3580877.00     10619495.00      3581018.00     10619543.00
      3581080.00     10619670.00      3581486.75     10620115.00
      3581560.25     10620115.00      3581687.75     10620192.00
      3581760.75     10620156.00      3581815.25     10620177.00
      3581850.75     10620129.00      3581913.75     10620163.00
      3581937.50     10620105.00      3582047.50     10620092.00
      3582096.25     10620168.00      3582150.00     10620146.00

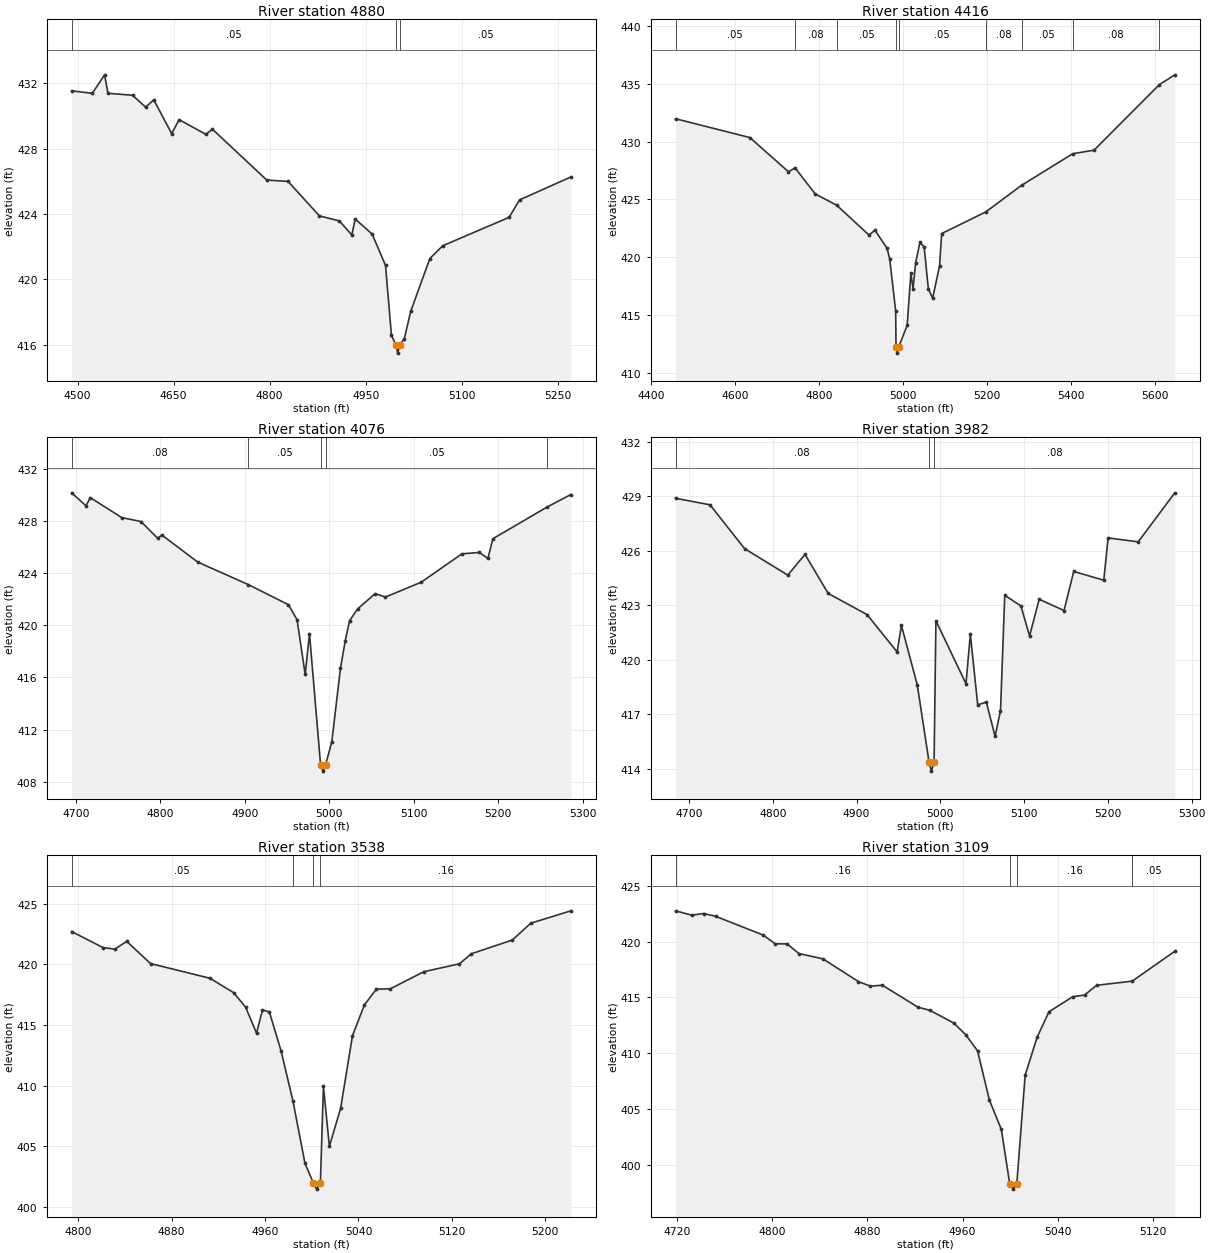
Type RM Length L Ch R = 1,4880,464,464,464
BEGIN DESCRIPTION:
UNT204 IN CCTC 8.0
END DESCRIPTION:
XS GIS Cut Line= 3
      3580138.94     10617471.13      3580266.54     10617041.45
      3580249.61     10616710.21
#Sta/Elev= 30
  4490.7  431.53  4523.0  431.38  4542.2  432.51  4547.4  431.38  4585.8  431.26
  4606.4  430.53  4619.0  430.98  4647.0  428.91  4658.6  429.77  4700.3  428.87
  4710.7  429.18  4795.5  426.07  4828.7  425.99  4877.7  423.88  4908.9  423.57
  4928.4  422.71  4933.6  423.69  4960.2  422.76  4981.0  420.85  4990.3  416.56
  4997.3  415.98  5000.0  415.48  5003.3  415.98  5010.3  416.35  5020.3  418.03
  5050.3  421.27  5070.4  422.05  5174.1  423.79  5190.5  424.86  5270.6  426.26
#Mann=3,-1,0
  4490.7    0.05       0  4997.3    0.04       0  5003.3    0.05       0
Bank Sta=4997.3,5003.3
Exp/Cntr=0.3,0.1

Type RM Length L Ch R = 1,4416,340,340,340
BEGIN DESCRIPTION:
UNT204 IN CCTC 7.0
END DESCRIPTION:
XS GIS Cut Line= 3
      3580199.60     10617460.19      3580599.61     10617110.19
      3581249.65     10617210.19
#Sta/Elev= 30
  4457.4  431.99  4634.4  430.36  4726.5  427.40  4742.1  427.74  4790.1  425.48
  4841.5  424.50  4918.2  421.92  4932.4  422.34  4960.9  420.80  4967.6  419.85
  4981.8  415.34  4982.6  412.20  4985.3  411.70  4988.6  412.20  5009.2  414.11
  5018.0  418.63  5023.1  417.29  5029.4  419.54  5039.5  421.28  5049.6  420.89
  5059.7  417.24  5069.9  416.46  5086.3  419.25  5091.4  422.05  5196.3  423.92
  5281.9  426.23  5403.4  428.96  5454.3  429.27  5610.1  434.95  5646.6  435.79
#Mann=9,-1,0
  4457.4    0.05       0  4742.1    0.08       0  4841.5    0.05       0
  4982.6    0.04       0  4988.6    0.05       0  5196.3    0.08       0
  5281.9    0.05       0  5403.4    0.08       0  5610.1    0.05       0
Bank Sta=4982.6,4988.6
Exp/Cntr=0.3,0.1

Type RM Length L Ch R = 1,4076,94,94,94
BEGIN DESCRIPTION:
Mapping XS 6cbeecd2
END DESCRIPTION:
XS GIS Cut Line= 2
      3580419.66     10617499.45      3580995.28     10617364.21
#Sta/Elev= 30
  4694.9  430.15  4711.9  429.16  4717.0  429.78  4754.3  428.25  4777.0  427.95
  4796.7  426.67  4801.8  426.91  4844.3  424.84  4903.9  423.12  4951.7  421.57
  4961.9  420.42  4971.5  416.22  4976.6  419.34  4989.7  409.31  4992.5  408.81
  4995.7  409.31  5003.0  411.04  5013.3  416.71  5019.0  418.82  5024.1  420.35
  5033.8  421.26  5054.4  422.42  5066.6  422.16  5109.0  423.30  5157.1  425.47
  5177.6  425.58  5187.9  425.12  5193.8  426.63  5258.2  429.07  5286.2  430.02
#Mann=5,-1,0
  4694.9    0.08       0  4903.9    0.05       0  4989.7    0.03       0
  4995.7    0.05       0  5258.2    0.08       0
Bank Sta=4989.7,4995.7
Exp/Cntr=0.3,0.1

Type RM Length L Ch R = 1,3982,444,444,444
BEGIN DESCRIPTION:
UNT204 IN CCTC 6.0
END DESCRIPTION:
XS GIS Cut Line= 2
      3580419.67     10617600.14      3580997.77     10617454.75
#Sta/Elev= 30
  4683.8  428.90  4725.0  428.54  4766.2  426.13  4817.8  424.67  4838.4  425.81
  4866.1  423.66  4912.4  422.50  4948.4  420.44  4953.5  421.91  4972.5  418.61
  4986.5  414.38  4989.3  413.88  4992.5  414.38  4994.7  422.16  5030.6  418.69
  5035.8  421.41  5044.6  417.53  5054.9  417.68  5065.3  415.80  5071.8  417.20
  5076.9  423.56  5096.2  422.97  5106.5  421.32  5118.0  423.34  5147.7  422.72
  5159.2  424.87  5195.1  424.39  5200.3  426.72  5236.2  426.50  5279.9  429.20
#Mann=3,-1,0
  4683.8    0.08       0  4986.5    0.07       0  4992.5    0.08       0
Bank Sta=4986.5,4992.5
Exp/Cntr=0.3,0.1

Type RM Length L Ch R = 1,3538,429,429,429
BEGIN DESCRIPTION:
UNT204 IN CCTC 5.0
END DESCRIPTION:
XS GIS Cut Line= 2
      3580593.22     10617985.57      3581013.40     10617905.70
#Sta/Elev= 30
  4794.3  422.71  4821.2  421.39  4831.3  421.26  4841.5  421.90  4861.9  420.07
  4912.8  418.86  4933.1  417.67  4943.3  416.49  4952.7  414.33  4957.8  416.25
  4963.7  416.08  4973.8  412.84  4983.9  408.73  4994.2  403.59  5001.4  401.97
  5004.1  401.47  5007.4  401.97  5010.0  409.94  5015.1  405.00  5024.7  408.12
  5034.9  414.13  5045.1  416.66  5055.3  417.96  5067.3  417.99  5096.0  419.40
  5126.5  420.05  5136.7  420.88  5171.8  422.01  5187.6  423.40  5222.0  424.42
#Mann=4,-1,0
  4794.3    0.05       0  4983.9    0.16       0  5001.4    0.07       0
  5007.4    0.16       0
Bank Sta=5001.4,5007.4
Exp/Cntr=0.3,0.1

Type RM Length L Ch R = 1,3109,329,329,329
BEGIN DESCRIPTION:
UNT204 IN CCTC 4.0
END DESCRIPTION:
XS GIS Cut Line= 2
      3580575.94     10618350.15      3580995.32     10618346.68
#Sta/Elev= 30
  4718.9  422.75  4732.6  422.36  4742.6  422.51  4752.6  422.26  4792.6  420.58
  4802.6  419.80  4812.6  419.79  4822.6  418.93  4842.6  418.46  4872.6  416.42
  4882.6  416.01  4892.6  416.10  4922.6  414.13  4932.6  413.85  4952.6  412.72
  4962.6  411.68  4972.6  410.23  4982.6  405.81  4992.6  403.20  4999.6  398.36
  5002.3  397.86  5005.6  398.36  5012.6  408.05  5022.6  411.43  5032.6  413.72
  5052.6  415.07  5062.6  415.22  5072.6  416.09  5102.5  416.46  5138.3  419.13
#Mann=4,-1,0
  4718.9    0.16       0  4999.6    0.07       0  5005.6    0.16       0
  5102.5    0.05       0
Bank Sta=4999.6,5005.6
Exp/Cntr=0.3,0.1

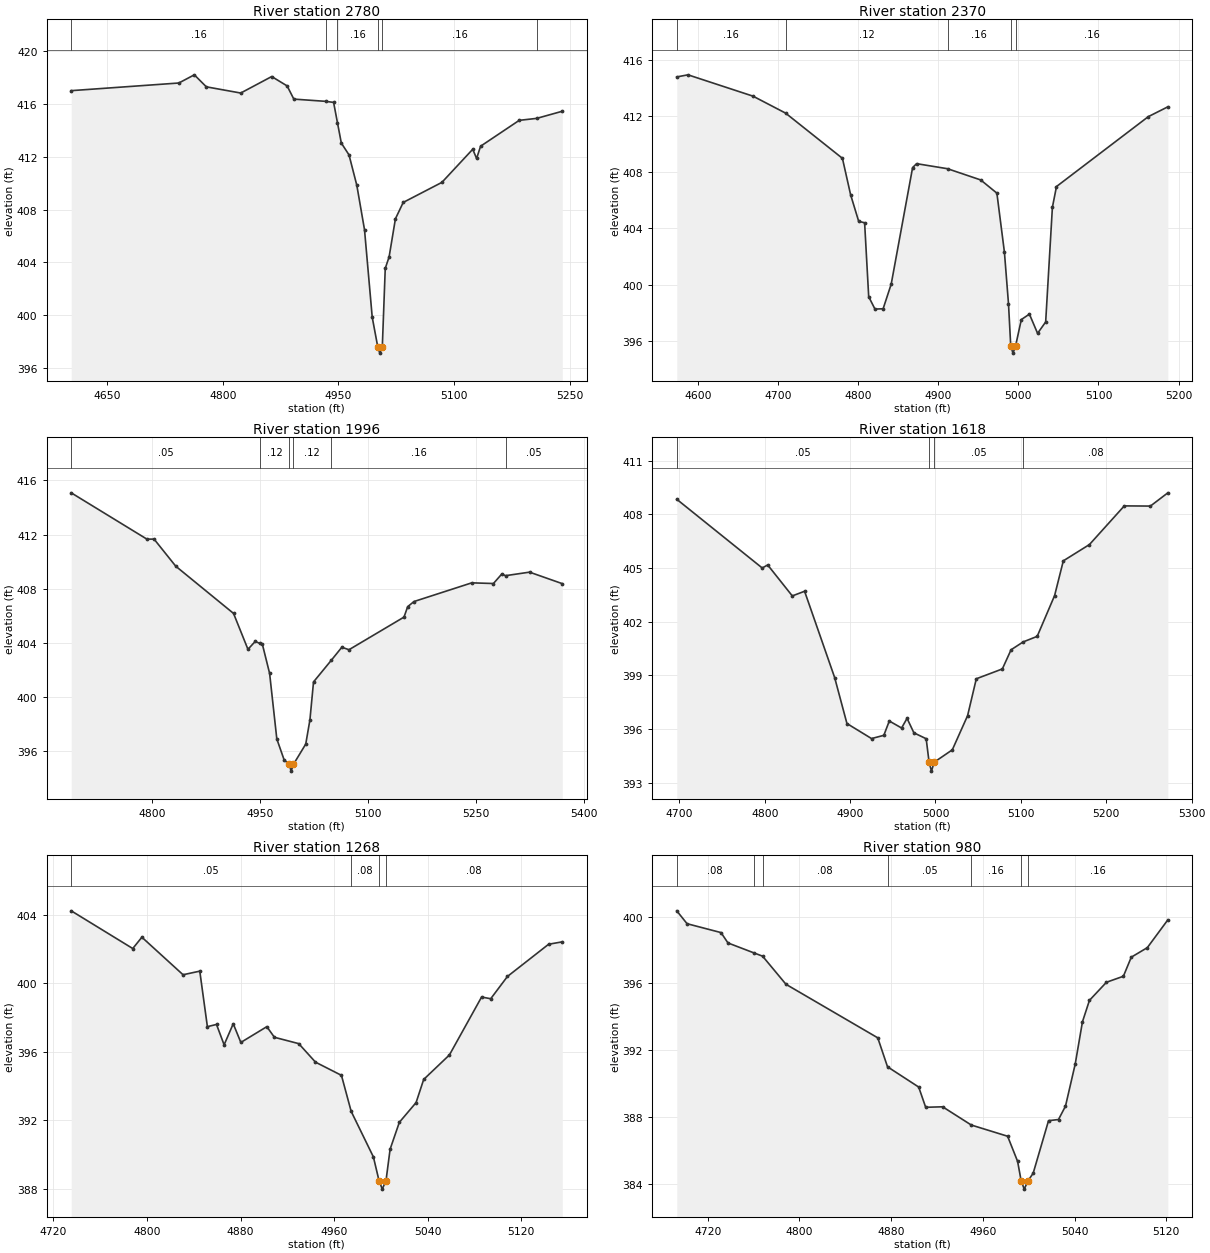
Type RM Length L Ch R = 1,2780,410,410,410
BEGIN DESCRIPTION:
Mapping XS 4664a7de
END DESCRIPTION:
XS GIS Cut Line= 2
      3580400.51     10618620.11      3581035.26     10618674.74
#Sta/Elev= 30
  4603.3  417.01  4742.9  417.59  4763.0  418.21  4778.6  417.30  4823.2  416.83
  4863.4  418.08  4883.4  417.37  4892.1  416.37  4933.5  416.20  4943.7  416.12
  4948.7  414.58  4953.7  413.04  4963.7  412.14  4973.8  409.84  4983.8  406.47
  4993.8  399.84  5000.9  397.62  5003.6  397.12  5006.9  397.62  5010.7  403.54
  5015.7  404.41  5023.9  407.30  5034.0  408.54  5084.2  410.06  5124.2  412.57
  5129.2  411.87  5134.4  412.80  5184.5  414.76  5207.2  414.91  5240.4  415.45
#Mann=6,-1,0
  4603.3    0.16       0  4933.5    0.05       0  4948.7    0.16       0
  5000.9    0.07       0  5006.9    0.16       0  5207.2    0.05       0
Bank Sta=5000.9,5006.9
Exp/Cntr=0.3,0.1

Type RM Length L Ch R = 1,2370,374,374,374
BEGIN DESCRIPTION:
Mapping XS a6f1500a
END DESCRIPTION:
XS GIS Cut Line= 2
      3580425.77     10619065.42      3581029.86     10618961.26
#Sta/Elev= 30
  4573.6  414.79  4587.6  414.94  4668.8  413.42  4709.5  412.21  4780.4  408.99
  4790.6  406.40  4800.7  404.50  4808.1  404.40  4813.2  399.13  4821.0  398.25
  4831.2  398.27  4841.3  400.03  4868.0  408.33  4873.0  408.61  4911.6  408.25
  4953.0  407.45  4973.2  406.51  4982.6  402.31  4987.7  398.63  4990.5  395.61
  4993.3  395.11  4996.5  395.61  5003.7  397.50  5013.8  397.89  5024.0  396.52
  5034.1  397.33  5042.5  405.50  5047.6  406.98  5162.2  411.96  5186.6  412.66
#Mann=5,-1,0
  4573.6    0.16       0  4709.5    0.12       0  4911.6    0.16       0
  4990.5    0.07       0  4996.5    0.16       0
Bank Sta=4990.5,4996.5
Exp/Cntr=0.3,0.1

Type RM Length L Ch R = 1,1996,378,378,378
BEGIN DESCRIPTION:
UNT204 IN CCTC 3.0
END DESCRIPTION:
XS GIS Cut Line= 2
      3580484.80     10619360.56      3581165.01     10619308.50
#Sta/Elev= 30
  4687.3  415.08  4792.4  411.66  4802.4  411.66  4832.5  409.66  4912.8  406.17
  4932.8  403.52  4942.9  404.10  4949.1  403.96  4952.9  403.88  4962.9  401.74
  4972.9  396.90  4983.0  395.36  4990.0  395.02  4992.8  394.52  4996.0  395.02
  5013.1  396.52  5018.9  398.31  5023.9  401.11  5048.6  402.71  5063.2  403.67
  5073.2  403.49  5149.6  405.90  5154.7  406.67  5163.5  407.05  5243.7  408.43
  5273.8  408.38  5285.4  409.08  5290.7  408.96  5324.0  409.22  5369.5  408.37
#Mann=6,-1,0
  4687.3    0.05       0  4949.1    0.12       0  4990.0    0.07       0
  4996.0    0.12       0  5048.6    0.16       0  5290.7    0.05       0
Bank Sta=4990,4996
Exp/Cntr=0.3,0.1

Type RM Length L Ch R = 1,1618,350,350,350
BEGIN DESCRIPTION:
UNT204 IN CCTC 2.0
END DESCRIPTION:
XS GIS Cut Line= 3
      3580799.61     10619760.19      3581049.61     10619560.19
      3581299.60     10619510.19
#Sta/Elev= 30
  4697.0  408.84  4797.1  405.00  4803.5  405.17  4832.3  403.44  4846.7  403.70
  4881.9  398.88  4896.3  396.31  4925.1  395.47  4939.5  395.65  4945.9  396.45
  4960.3  396.06  4966.7  396.60  4974.7  395.79  4989.1  395.46  4992.5  394.15
  4995.3  393.65  4998.5  394.15  5019.7  394.84  5037.6  396.75  5047.8  398.81
  5078.3  399.36  5088.5  400.43  5102.7  400.87  5119.1  401.18  5139.5  403.46
  5149.7  405.40  5180.3  406.31  5221.1  408.47  5251.7  408.46  5272.1  409.20
#Mann=4,-1,0
  4697.0    0.05       0  4992.5    0.04       0  4998.5    0.05       0
  5102.7    0.08       0
Bank Sta=4992.5,4998.5
Exp/Cntr=0.3,0.1

Type RM Length L Ch R = 1,1268,288,288,288
BEGIN DESCRIPTION:
Mapping XS c7b16c4f
END DESCRIPTION:
XS GIS Cut Line= 2
      3581083.70     10620038.88      3581351.94     10619715.95
#Sta/Elev= 30
  4735.2  404.22  4787.8  402.02  4795.6  402.68  4830.8  400.49  4845.1  400.70
  4851.6  397.46  4859.4  397.59  4865.9  396.40  4873.7  397.63  4880.2  396.54
  4902.4  397.46  4908.9  396.84  4929.7  396.47  4944.0  395.39  4966.2  394.62
  4974.5  392.52  4993.5  389.86  4998.3  388.48  5001.1  387.98  5004.3  388.48
  5007.8  390.31  5015.7  391.88  5030.0  393.03  5036.5  394.38  5058.5  395.81
  5086.0  399.19  5093.8  399.09  5108.1  400.39  5143.3  402.27  5155.0  402.41
#Mann=4,-1,0
  4735.2    0.05       0  4974.5    0.08       0  4998.3    0.07       0
  5004.3    0.08       0
Bank Sta=4998.3,5004.3
Exp/Cntr=0.3,0.1

Type RM Length L Ch R = 1,980,437,437,437
BEGIN DESCRIPTION:
Mapping XS fa6ad298
END DESCRIPTION:
XS GIS Cut Line= 2
      3581260.78     10620304.51      3581507.37     10619954.08
#Sta/Elev= 30
  4692.9  400.34  4701.9  399.57  4731.5  399.04  4737.6  398.42  4760.1  397.83
  4767.8  397.63  4788.2  395.95  4868.3  392.75  4876.8  391.02  4904.0  389.81
  4910.1  388.60  4924.9  388.63  4949.9  387.54  4981.6  386.87  4990.3  385.37
  4993.4  384.21  4996.1  383.71  4999.4  384.21  5003.9  384.66  5017.3  387.80
  5026.0  387.87  5032.1  388.67  5040.6  391.19  5046.9  393.71  5053.0  394.99
  5067.8  396.07  5082.6  396.43  5089.5  397.57  5103.5  398.14  5121.4  399.80
#Mann=7,-1,0
  4692.9    0.08       0  4760.1    0.05       0  4767.8    0.08       0
  4876.8    0.05       0  4949.9    0.16       0  4993.4    0.07       0
  4999.4    0.16       0
Bank Sta=4993.4,4999.4
Exp/Cntr=0.3,0.1

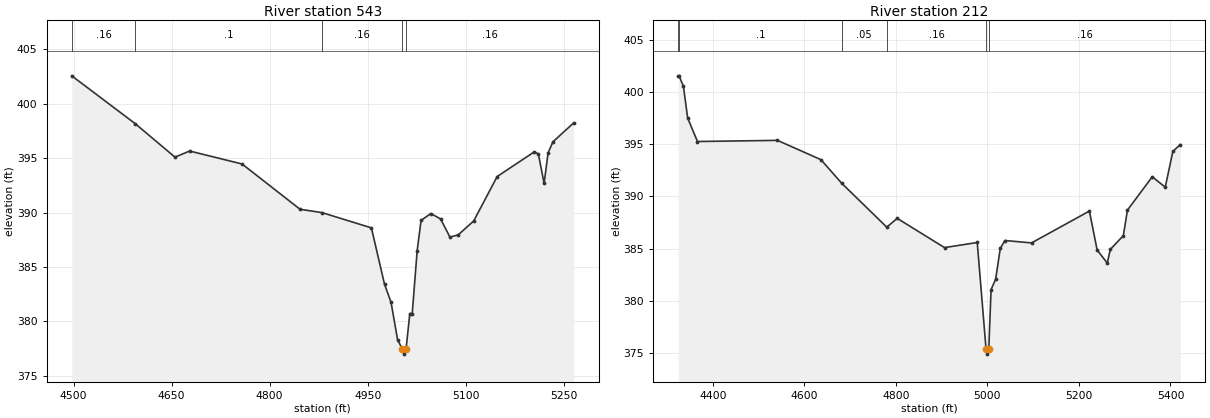
Type RM Length L Ch R = 1,543,331,331,331
BEGIN DESCRIPTION:
Mapping XS 70447c92
END DESCRIPTION:
XS GIS Cut Line= 4
      3581409.19     10620442.53      3581763.40     10620260.22
      3581771.21     10620137.82      3581631.67     10619933.67
#Sta/Elev= 30
  4497.2  402.56  4594.4  398.16  4655.1  395.09  4677.6  395.65  4757.8  394.46
  4846.5  390.30  4880.2  389.99  4955.7  388.59  4975.8  383.41  4985.8  381.75
  4995.8  378.31  5002.8  377.49  5005.6  376.99  5008.8  377.49  5014.5  380.72
  5018.2  380.72  5025.7  386.46  5031.7  389.27  5046.6  389.91  5061.6  389.41
  5075.9  387.74  5088.6  387.95  5112.3  389.23  5148.2  393.31  5205.1  395.58
  5211.2  395.38  5220.0  392.68  5226.1  395.48  5233.4  396.49  5265.5  398.25
#Mann=5,-1,0
  4497.2    0.16       0  4594.4     0.1       0  4880.2    0.16       0
  5002.8    0.07       0  5008.8    0.16       0
Bank Sta=5002.8,5008.8
Exp/Cntr=0.3,0.1

Type RM Length L Ch R = 1,212,0,0,0
BEGIN DESCRIPTION:
UNT204 IN CCTC 1.0
END DESCRIPTION:
XS GIS Cut Line= 4
      3581489.93     10620507.63      3581995.17     10620202.92
      3582010.79     10620067.51      3581674.88     10619911.27
#Sta/Elev= 30
  4324.7  401.54  4326.4  401.54  4336.0  400.54  4345.3  397.50  4366.7  395.25
  4541.4  395.36  4636.5  393.51  4681.4  391.27  4780.2  387.05  4803.1  387.89
  4906.4  385.09  4977.9  385.58  4997.1  375.39  4999.8  374.89  5003.1  375.39
  5008.1  381.07  5018.1  382.06  5028.2  385.01  5038.3  385.77  5096.5  385.54
  5222.9  388.59  5239.8  384.86  5261.9  383.61  5268.7  384.92  5297.1  386.24
  5306.0  388.68  5360.2  391.87  5388.6  390.88  5405.3  394.31  5421.5  394.96
#Mann=6,-1,0
  4324.7    0.16       0  4326.4     0.1       0  4681.4    0.05       0
  4780.2    0.16       0  4997.1    0.07       0  5003.1    0.16       0
Bank Sta=4997.1,5003.1
Exp/Cntr=0.3,0.1

Chan Stop Cuts=-1