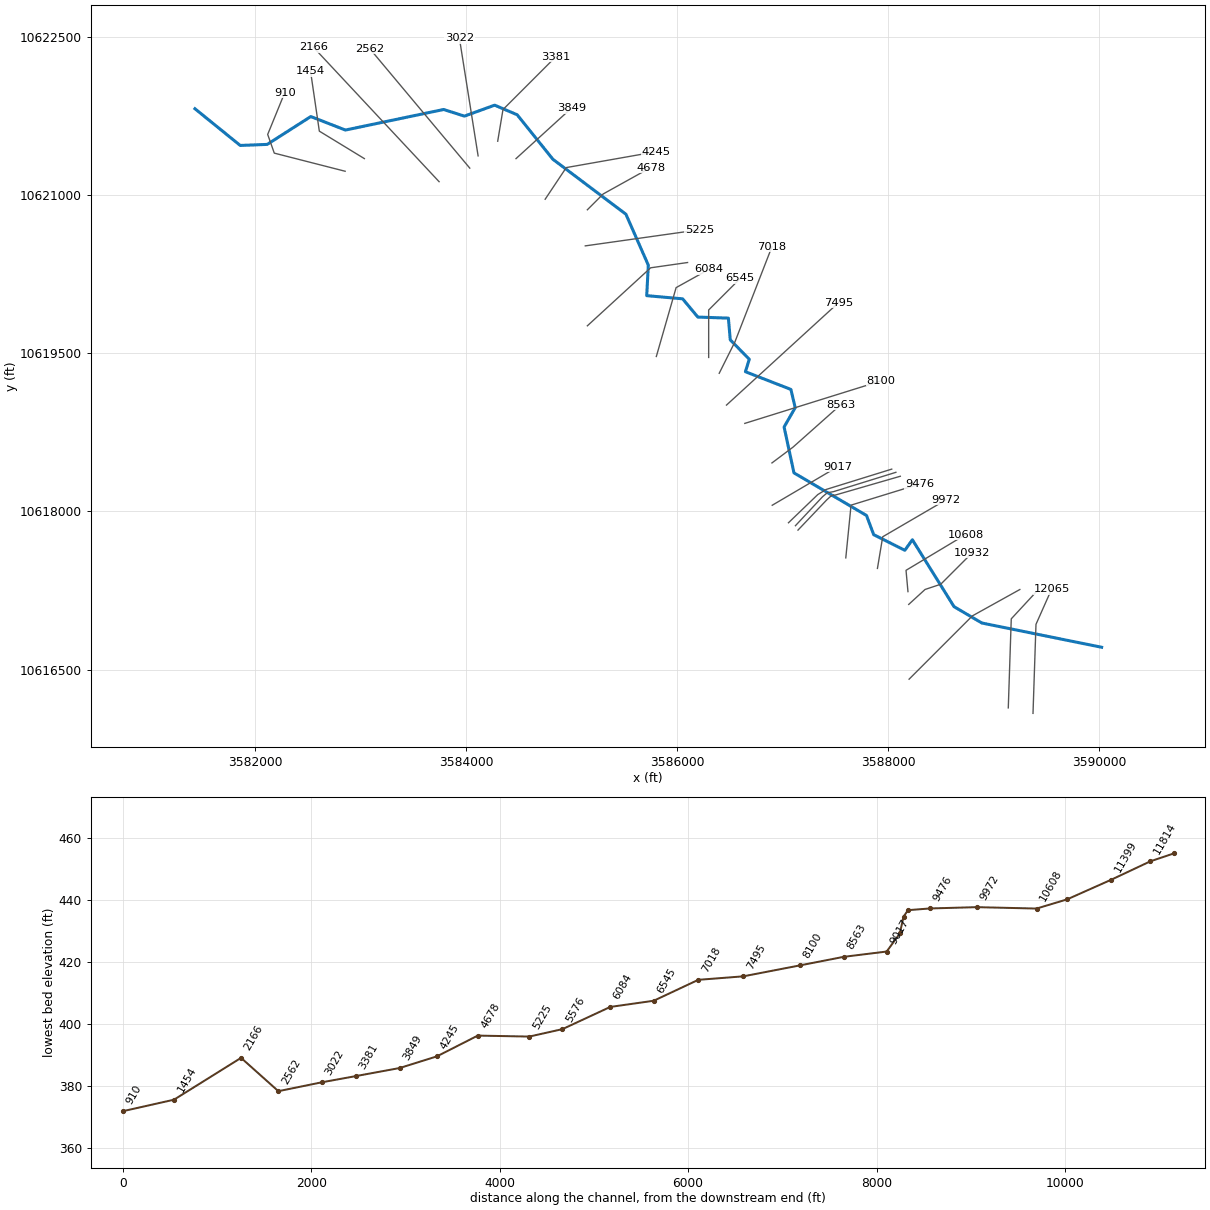
--- UNT205 IN CCTC.prj (project) ---

Proj Title=UNT205 IN CCTC Base Level Engineering
Current Plan=p01
Default Exp/Contr=0.3,0.1
English Units
Geom File=g01
Flow File=f01
Plan File=p01
Y Axis Title=Elevation
X Axis Title(PF)=Main Channel Distance
X Axis Title(XS)=Station
BEGIN DESCRIPTION:
UNT205 IN CCTC
END DESCRIPTION:
DSS Export Rating Curves= 0
DSS Export Rating Curve Sorted= 0
DSS Export Volume Flow Curves= 0
DXF OffsetX= 0
DXF OffsetY= 0
DXF ScaleX= 1
DXF ScaleY= 10

--- UNT205 IN CCTC.p01 (plan) ---

Plan Title=Multiple Run
Short Identifier=Multiple
Geom File=g01
Flow File=f01
Subcritical Flow
K Sum by GR= 0
Std Step Tol= 0.01
Critical Tol= 0.01
Num of Std Step Trials= 20
Max Error Tol= 0.3
Flow Tol Ratio= 0.001
Split Flow NTrial= 30
Split Flow Tol= 0.02
Split Flow Ratio= 0.02
Log Output Level= 0
Friction Slope Method= 1
Unsteady Friction Slope Method= 2
Unsteady Bridges Friction Slope Method= 1
Parabolic Critical Depth
Global Vel Dist=  1 , 1 , 1
Global Log Level= 0
CheckData=True
Encroach Param= -1, 0, 0, 0
BEGIN DESCRIPTION:
Multiple Run
END DESCRIPTION:

--- UNT205 IN CCTC.f01 (steady flow) ---

Flow Title=Multiple
Program Version=4.10
Number of Profiles= 7
Profile Names=10-year,25-year,50-year,1pct_min,100-year,1pct_plu,500-year
River Rch & RM=UNT205 IN CCTC,Reach-1         ,12065
    1371    1870    2279    2027    2741    3707    3950
River Rch & RM=UNT205 IN CCTC,Reach-1         ,11399
    1371    1870    2279    2027    2741    3707    3950
Boundary for River Rch & Prof#=UNT205 IN CCTC,Reach-1         , 1
Up Type= 0
Dn Type= 3
Dn Slope=0.005
Boundary for River Rch & Prof#=UNT205 IN CCTC,Reach-1         , 2
Up Type= 0
Dn Type= 3
Dn Slope=0.005
Boundary for River Rch & Prof#=UNT205 IN CCTC,Reach-1         , 3
Up Type= 0
Dn Type= 3
Dn Slope=0.005
Boundary for River Rch & Prof#=UNT205 IN CCTC,Reach-1         , 4
Up Type= 0
Dn Type= 3
Dn Slope=0.005
Boundary for River Rch & Prof#=UNT205 IN CCTC,Reach-1         , 5
Up Type= 0
Dn Type= 3
Dn Slope=0.005
Boundary for River Rch & Prof#=UNT205 IN CCTC,Reach-1         , 6
Up Type= 0
Dn Type= 3
Dn Slope=0.005
Boundary for River Rch & Prof#=UNT205 IN CCTC,Reach-1         , 7
Up Type= 0
Dn Type= 3
Dn Slope=0.005
DSS Import GetInterval= 0
DSS Import GetPeak= 0
DSS Import FillOption= 0

--- UNT205 IN CCTC.g01 (geometry) ---

Geom Title=Existing Conditions
Program Version=4.10

River Reach=UNT205 IN CCTC  ,Reach-1
Reach XY= 30
      3590024.99     10616712.61      3588889.32     10616942.77
       3588625.5       10617098.      3588230.75       10617732.
       3588159.5       10617632.      3587864.25       10617780.
        3587796.       10617962.      3587108.25       10618366.
      3587014.75       10618801.        3587120.       10618984.
      3587079.25       10619157.      3586647.75       10619325.
      3586684.75       10619443.       3586504.5       10619627.
       3586486.5       10619833.        3586197.       10619843.
        3586053.       10620016.      3585712.25       10620046.
       3585727.5       10620335.      3585515.25       10620818.
        3584823.       10621339.        3584484.       10621761.
       3584270.5       10621852.        3583984.       10621748.
        3583787.       10621811.      3582855.75       10621616.
      3582527.75       10621744.       3582114.5       10621480.
      3581858.75       10621470.       3581429.5       10621818.

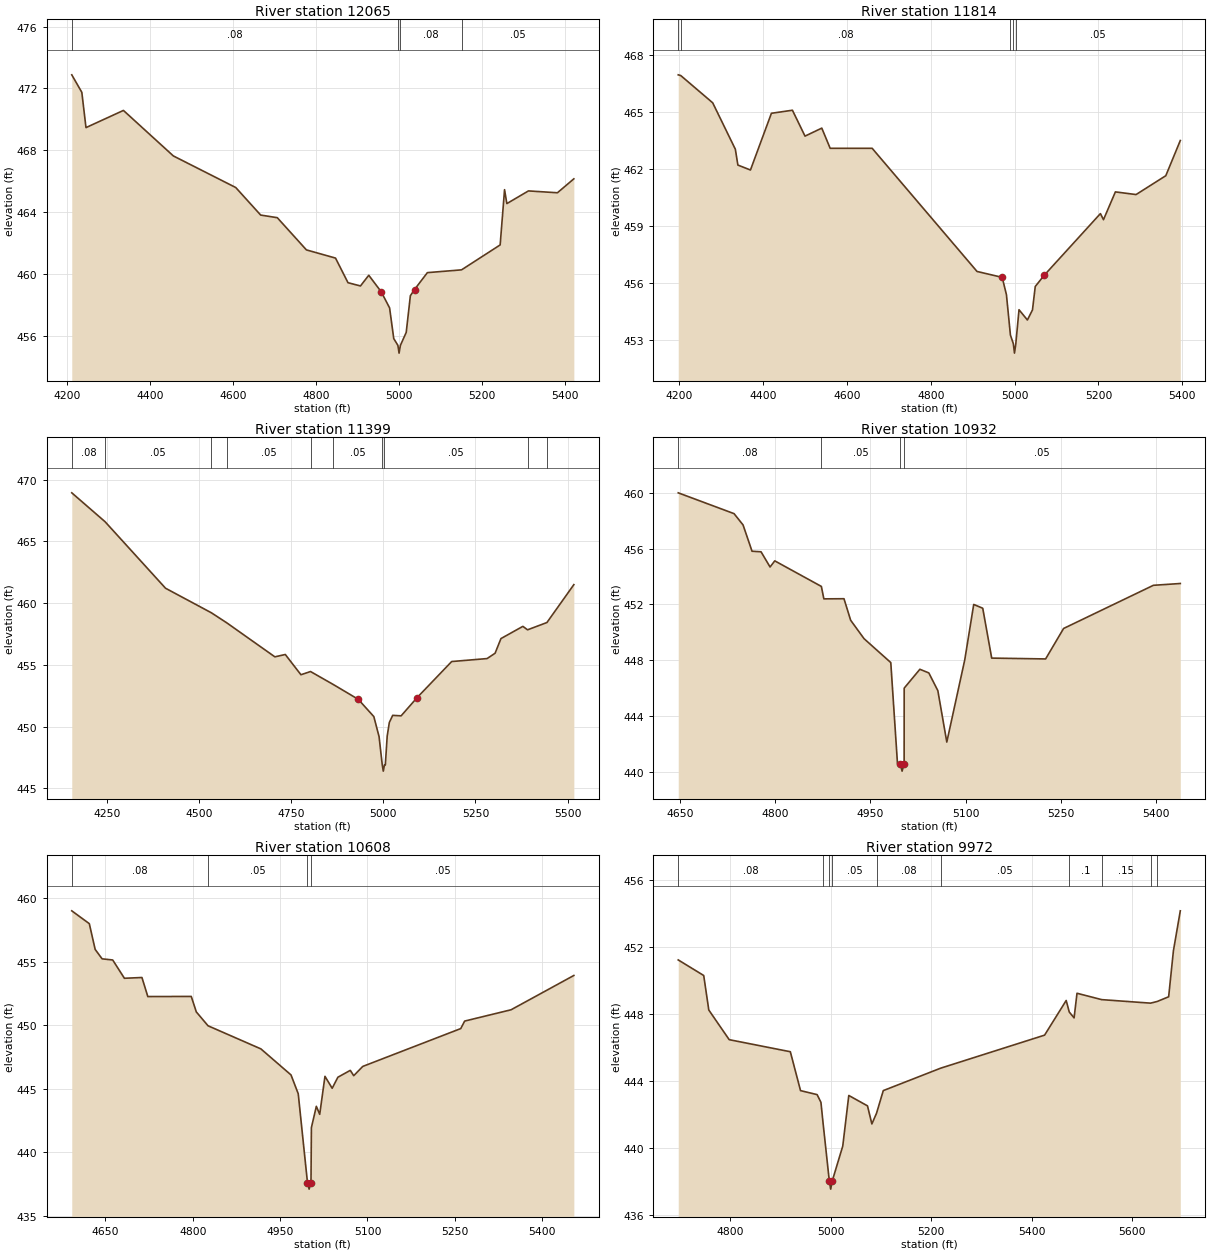
Type RM Length L Ch R = 1 ,12065   ,251,251,251
BEGIN DESCRIPTION:
Mapping XS asdf4567
END DESCRIPTION:
XS GIS Cut Line= 3
      3589374.46     10616085.96      3589402.68     10616930.17
      3589550.23     10617262.17
#Sta/Elev= 30
  4212.3  472.88  4236.5  471.75  4246.5  469.47  4336.6  470.58  4456.7  467.64
  4606.8   465.6  4666.8  463.82  4706.8  463.65  4776.8  461.57  4846.9  461.04
  4876.9  459.45  4906.9  459.24  4926.9  459.93  4956.9  458.86    4977  457.82
    4987  455.84    4997   455.4  4999.8   454.9    5003   455.4    5017  456.24
    5027  458.61    5037  459.01  5067.9   460.1  5150.1  460.28    5243  461.89
  5253.6  465.46  5259.1  464.56  5311.1  465.38  5380.8  465.26  5420.3  466.16
#Mann= 4 ,-1 , 0
  4212.3     .08       0    4997     .07       0    5003     .08       0
  5150.1     .05       0
Bank Sta=4956.9,5037
XS Rating Curve= 0 ,0
Exp/Cntr=0.3,0.1

Type RM Length L Ch R = 1 ,11814   ,415,415,415
BEGIN DESCRIPTION:
Mapping XS qwer4567
END DESCRIPTION:
XS GIS Cut Line= 3
      3589140.09     10616138.07       3589168.3     10616982.25
      3589407.86     10617240.91
#Sta/Elev= 30
    4198  466.95  4204.1  466.91  4280.2  465.48  4334.2  463.04  4340.2  462.21
  4370.2  461.95  4420.2  464.93  4470.3  465.09  4500.3  463.73  4540.3  464.15
  4560.3  463.09  4660.4  463.09  4910.5  456.62  4970.5  456.31  4980.6   455.4
  4990.1  453.28    4997  452.83  4999.8  452.33    5003  452.83  5010.6  454.61
  5030.6  454.07  5042.7   454.6  5049.3  455.83  5070.3  456.41  5204.7  459.66
    5212  459.34  5240.4   460.8  5289.7  460.66  5360.6  461.65  5395.2   463.5
#Mann= 5 ,-1 , 0
    4198     .05       0  4204.1     .08       0  4990.1     .05       0
    4997     .04       0    5003     .05       0
Bank Sta=4970.5,5070.3
XS Rating Curve= 0 ,0
Exp/Cntr=0.3,0.1

Type RM Length L Ch R = 1 ,11399   ,467,467,467
BEGIN DESCRIPTION:
UNT205 IN CCTC 23.0
END DESCRIPTION:
XS GIS Cut Line= 3
      3588199.61     10616410.19      3588799.61     10617010.19
       3589249.6     10617260.18
#Sta/Elev= 30
  4153.9  468.94  4244.3   466.6  4408.5  461.21    4533  459.22  4574.1  458.42
  4705.4  455.65  4733.7  455.84  4776.2   454.2  4802.2  454.46  4862.8  453.43
  4931.7  452.21  4974.1  450.81  4988.3  449.19    4997  446.89  4999.8  446.39
    5003  446.89  5005.3  446.89  5010.4  449.23  5016.2  450.33  5025.3  450.91
  5048.2  450.87  5091.7  452.35  5185.5  455.27  5281.6  455.51  5303.3  455.94
  5319.3  457.13  5378.8  458.12  5391.5  457.84  5444.1  458.43  5517.2   461.5
#Mann= 10 ,-1 , 0
  4153.9     .08       0  4244.3     .05       0    4533     .08       0
  4574.1     .05       0  4802.2     .08       0  4862.8     .05       0
    4997     .03       0    5003     .05       0  5391.5     .08       0
  5444.1     .05       0
Bank Sta=4931.7,5091.7
XS Rating Curve= 0 ,0
Exp/Cntr=0.3,0.1

Type RM Length L Ch R = 1 ,10932   ,324,324,324
BEGIN DESCRIPTION:
UNT205 IN CCTC 22.0
END DESCRIPTION:
XS GIS Cut Line= 4
      3588196.33     10617119.03      3588351.16     10617260.66
      3588499.61     10617310.19      3588799.61     10617610.19
#Sta/Elev= 30
  4647.3  459.99  4735.2   458.5  4749.4  457.69  4763.5  455.81  4777.7  455.77
  4791.9  454.68  4799.3  455.12  4872.7  453.29  4876.6   452.4  4908.3  452.41
  4918.8  450.87  4939.9  449.55    4982  447.84  4992.6  440.57    4997  440.57
  4999.8  440.07    5003  440.57  5003.1  446.01  5027.8  447.36  5041.9   447.1
  5056.1  445.83  5070.2  442.15  5098.5  448.04  5112.6     452  5126.8  451.73
  5140.9  448.16  5225.8   448.1  5254.1  450.28  5395.5  453.37  5437.9   453.5
#Mann= 4 ,-1 , 0
  4647.3     .08       0  4872.7     .05       0    4997     .03       0
    5003     .05       0
Bank Sta=4997,5003
XS Rating Curve= 0 ,0
Exp/Cntr=0.3,0.1

Type RM Length L Ch R = 1 ,10608   ,636,636,636
BEGIN DESCRIPTION:
UNT205 IN CCTC 21.0
END DESCRIPTION:
XS GIS Cut Line= 3
      3588189.05     10617240.17      3588170.63     10617442.18
      3588736.19     10617781.11
#Sta/Elev= 30
  4592.2  459.02  4622.3  458.01  4632.4  455.98  4644.3  455.24  4662.5  455.15
  4682.6  453.71  4712.7  453.77  4722.8  452.27  4797.4  452.28  4806.1  451.06
  4826.2  449.97    4917  448.15  4968.7   446.1  4981.1  444.62    4997  437.61
  4999.8  437.11    5003  437.61  5003.7  441.95  5012.2  443.63    5018     443
    5027  445.99  5039.4  445.05  5049.2  445.92  5070.5  446.46  5076.4  446.04
  5091.9  446.77  5260.2  449.75  5266.9  450.34  5346.6  451.23  5454.4  453.93
#Mann= 4 ,-1 , 0
  4592.2     .08       0  4826.2     .05       0    4997     .04       0
    5003     .05       0
Bank Sta=4997,5003
XS Rating Curve= 0 ,0
Exp/Cntr=0.3,0.1

Type RM Length L Ch R = 1 ,9972    ,496,496,496
BEGIN DESCRIPTION:
UNT205 IN CCTC 20.0
END DESCRIPTION:
XS GIS Cut Line= 3
      3587899.61     10617460.17      3587949.61     10617760.19
      3588549.63      10618110.2
#Sta/Elev= 30
  4696.5  451.24  4747.2  450.31  4757.3  448.25  4797.9  446.48  4919.5  445.76
  4939.8  443.44  4972.8   443.2  4980.4  442.74  4984.7  441.48    4997  438.06
  4999.8  437.56    5003  438.06  5023.8  440.13  5035.8  443.15    5073  442.53
  5081.7  441.45    5091  442.09  5104.4  443.44  5218.7  444.78  5425.3  446.75
  5468.3  448.82  5474.4  448.13    5484  447.78  5489.8  449.25  5538.9  448.87
  5636.1  448.66  5649.4  448.76  5672.1  449.04  5681.6  451.79  5695.3  454.17
#Mann= 10 ,-1 , 0
  4696.5     .08       0  4984.7     .05       0    4997     .03       0
    5003     .05       0    5091     .08       0  5218.7     .05       0
  5474.4      .1       0  5538.9     .15       0  5636.1      .1       0
  5649.4     .05       0
Bank Sta=4997,5003
XS Rating Curve= 0 ,0
Exp/Cntr=0.3,0.1

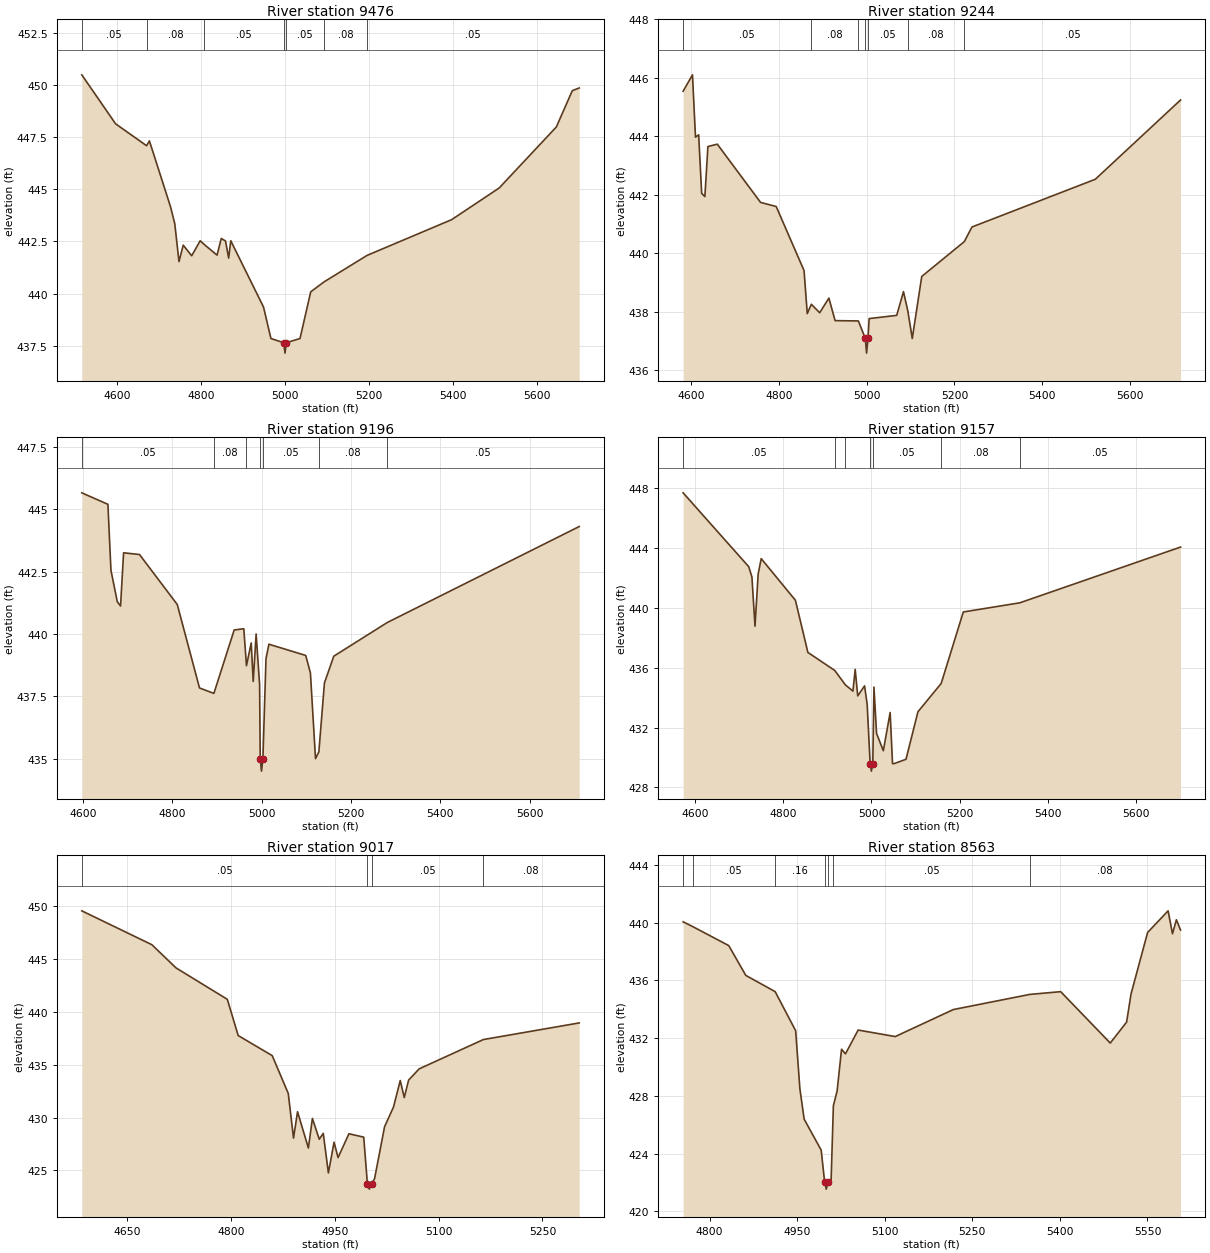
Type RM Length L Ch R = 1 ,9476    ,232,232,232
BEGIN DESCRIPTION:
UNT205 IN CCTC 19.0
END DESCRIPTION:
XS GIS Cut Line= 3
      3587599.61      10617560.2      3587649.61     10618060.19
      3588299.65      10618260.2
#Sta/Elev= 30
  4516.7  450.49  4597.1  448.14  4670.7  447.09  4677.5  447.32  4727.7  444.16
  4737.8  443.35  4747.8  441.53  4757.9  442.32    4778  441.81  4798.1  442.53
    4808  442.35  4838.3  441.84  4848.3  442.64  4858.4  442.52  4865.9   441.7
  4870.9  442.53  4948.8  439.35  4966.4  437.84    4997  437.64  4999.8  437.14
    5003  437.64  5035.5  437.84    5061  440.08  5092.9  440.56  5195.2  441.83
  5395.8  443.54    5509  445.06    5645  447.99  5682.9  449.73  5699.3  449.86
#Mann= 7 ,-1 , 0
  4516.7     .05       0  4670.7     .08       0    4808     .05       0
    4997     .03       0    5003     .05       0  5092.9     .08       0
  5195.2     .05       0
Bank Sta=4997,5003
XS Rating Curve= 0 ,0
Exp/Cntr=0.3,0.1

Type RM Length L Ch R = 1 ,9244    ,48,48,48
BEGIN DESCRIPTION:
Mapping XS b1ad21cb
END DESCRIPTION:
XS GIS Cut Line= 5
      3587146.44     10617823.46      3587417.27     10618108.19
      3587462.41     10618149.85      3587504.08      10618156.8
      3588116.34      10618333.9
#Sta/Elev= 30
  4581.6  445.54  4602.9   446.1  4609.8  443.97    4617  444.05  4623.9  442.05
  4631.2  441.94  4638.1  443.65  4659.5  443.73  4758.2  441.74  4793.8   441.6
  4857.3  439.41  4864.6  437.94  4873.9  438.26  4892.9  437.97  4913.9  438.47
  4928.1   437.7  4981.1  437.69    4997  437.09  4999.8  436.59    5003  437.09
  5005.7  437.77  5068.5  437.88    5084  438.69  5093.9  438.03    5104  437.09
  5125.6  439.21  5222.6   440.4  5240.1   440.9  5521.2  442.53  5715.6  445.24
#Mann= 7 ,-1 , 0
  4581.6     .05       0  4873.9     .08       0  4981.1     .05       0
    4997    .033       0    5003     .05       0  5093.9     .08       0
  5222.6     .05       0
Bank Sta=4997,5003
XS Rating Curve= 0 ,0
Exp/Cntr=0.3,0.1

Type RM Length L Ch R = 1 ,9196    ,39,39,39
BEGIN DESCRIPTION:
Mapping XS ef531a40
END DESCRIPTION:
XS GIS Cut Line= 5
      3587122.17     10617865.17      3587379.08     10618139.44
      3587424.22     10618177.63      3587483.25     10618188.05
      3588074.54     10618371.25
#Sta/Elev= 30
  4597.4  445.65  4655.9  445.19  4662.7  442.55  4676.9  441.29  4684.2  441.12
    4691  443.25  4726.7  443.18  4811.2  441.18    4861  437.84  4893.2  437.62
  4938.7  440.16  4960.2  440.21  4966.2  438.73  4976.8  439.64  4981.3   438.1
  4987.8     440  4995.6  437.98    4997  435.01  4999.8  434.51    5003  435.01
  5009.9  439.01  5016.4  439.59  5098.9  439.14  5109.4  438.44  5120.8  435.01
  5128.3  435.28  5140.8  438.04  5161.7  439.11  5281.6  440.46  5711.3   444.3
#Mann= 7 ,-1 , 0
  4597.4     .05       0  4893.2     .08       0  4966.2     .05       0
    4997     .03       0    5003     .05       0  5128.3     .08       0
  5281.6     .05       0
Bank Sta=4997,5003
XS Rating Curve= 0 ,0
Exp/Cntr=0.3,0.1

Type RM Length L Ch R = 1 ,9157    ,140,140,140
BEGIN DESCRIPTION:
Mapping XS d5498852
END DESCRIPTION:
XS GIS Cut Line= 4
      3587056.15      10617892.9      3587333.94     10618160.27
       3587413.8     10618208.88      3588035.08     10618401.51
#Sta/Elev= 30
  4572.3  447.66  4721.3  442.73  4728.5  442.05  4735.5  438.76  4742.7  442.24
  4749.6  443.27  4827.3  440.49  4855.6  437.01  4916.5  435.81  4940.9  434.84
  4957.9  434.43    4963  435.88  4968.8  434.11  4984.3  434.78  4990.2  433.55
    4997  429.59  4999.8  429.09    5003  429.59  5005.6   434.7  5011.5  431.61
  5026.9  430.45  5042.4     433  5047.8  429.59  5051.3  429.59  5078.4  429.88
  5105.5  433.05  5158.3  434.94  5208.5  439.71  5336.8  440.32  5701.8  444.04
#Mann= 7 ,-1 , 0
  4572.3     .05       0  4916.5     .08       0  4940.9     .05       0
    4997     .03       0    5003     .05       0  5158.3     .08       0
  5336.8     .05       0
Bank Sta=4997,5003
XS Rating Curve= 0 ,0
Exp/Cntr=0.3,0.1

Type RM Length L Ch R = 1 ,9017    ,454,454,454
BEGIN DESCRIPTION:
UNT205 IN CCTC 18.0
END DESCRIPTION:
XS GIS Cut Line= 2
       3586902.3     10618059.05      3587522.12     10618423.65
#Sta/Elev= 30
  4584.1  449.53  4685.4  446.33  4720.3  444.14  4794.5  441.17  4810.2  437.75
  4859.4  435.85  4882.6  432.28  4890.2  428.06    4896  430.55  4911.7  427.12
  4917.5  429.92  4927.4  427.95  4933.2  428.51  4940.6  424.77  4948.8  427.67
  4954.6  426.22  4970.3  428.47  4991.7  428.15    4997  423.74  4999.8  423.24
    5003  423.74  5007.4  424.23  5021.8  429.13  5034.7  430.99  5044.5   433.5
  5050.3  431.89  5056.6  433.54  5071.8   434.6  5164.7  437.37  5303.2  438.94
#Mann= 4 ,-1 , 0
  4584.1     .05       0    4997     .03       0    5003     .05       0
  5164.7     .08       0
Bank Sta=4997,5003
XS Rating Curve= 0 ,0
Exp/Cntr=0.3,0.1

Type RM Length L Ch R = 1 ,8563    ,463,463,463
BEGIN DESCRIPTION:
UNT205 IN CCTC 17.0
END DESCRIPTION:
XS GIS Cut Line= 3
      3586899.57     10618460.16      3587099.61     10618610.19
      3587549.59     10619010.17
#Sta/Elev= 30
  4754.6  440.06  4771.9  439.71  4832.8  438.41  4861.9  436.35  4912.3  435.22
  4947.4  432.51  4954.6   428.5  4961.9  426.39  4991.1  424.24    4997  422.04
  4999.8  421.54    5003  422.04    5008  422.04    5012  427.32  5018.4  428.34
    5026  431.23  5032.7  430.91  5054.4  432.56    5118  432.11  5217.5  433.98
  5348.5  435.03  5401.4  435.22  5486.3  431.66  5514.3  433.11  5521.9  435.06
  5550.3  439.32  5585.4  440.82  5592.9  439.23  5599.6   440.2  5606.7  439.49
#Mann= 7 ,-1 , 0
  4754.6     .08       0  4771.9     .05       0  4912.3     .16       0
    4997     .07       0    5003     .16       0    5012     .05       0
  5348.5     .08       0
Bank Sta=4997,5003
XS Rating Curve= 0 ,0
Exp/Cntr=0.3,0.1

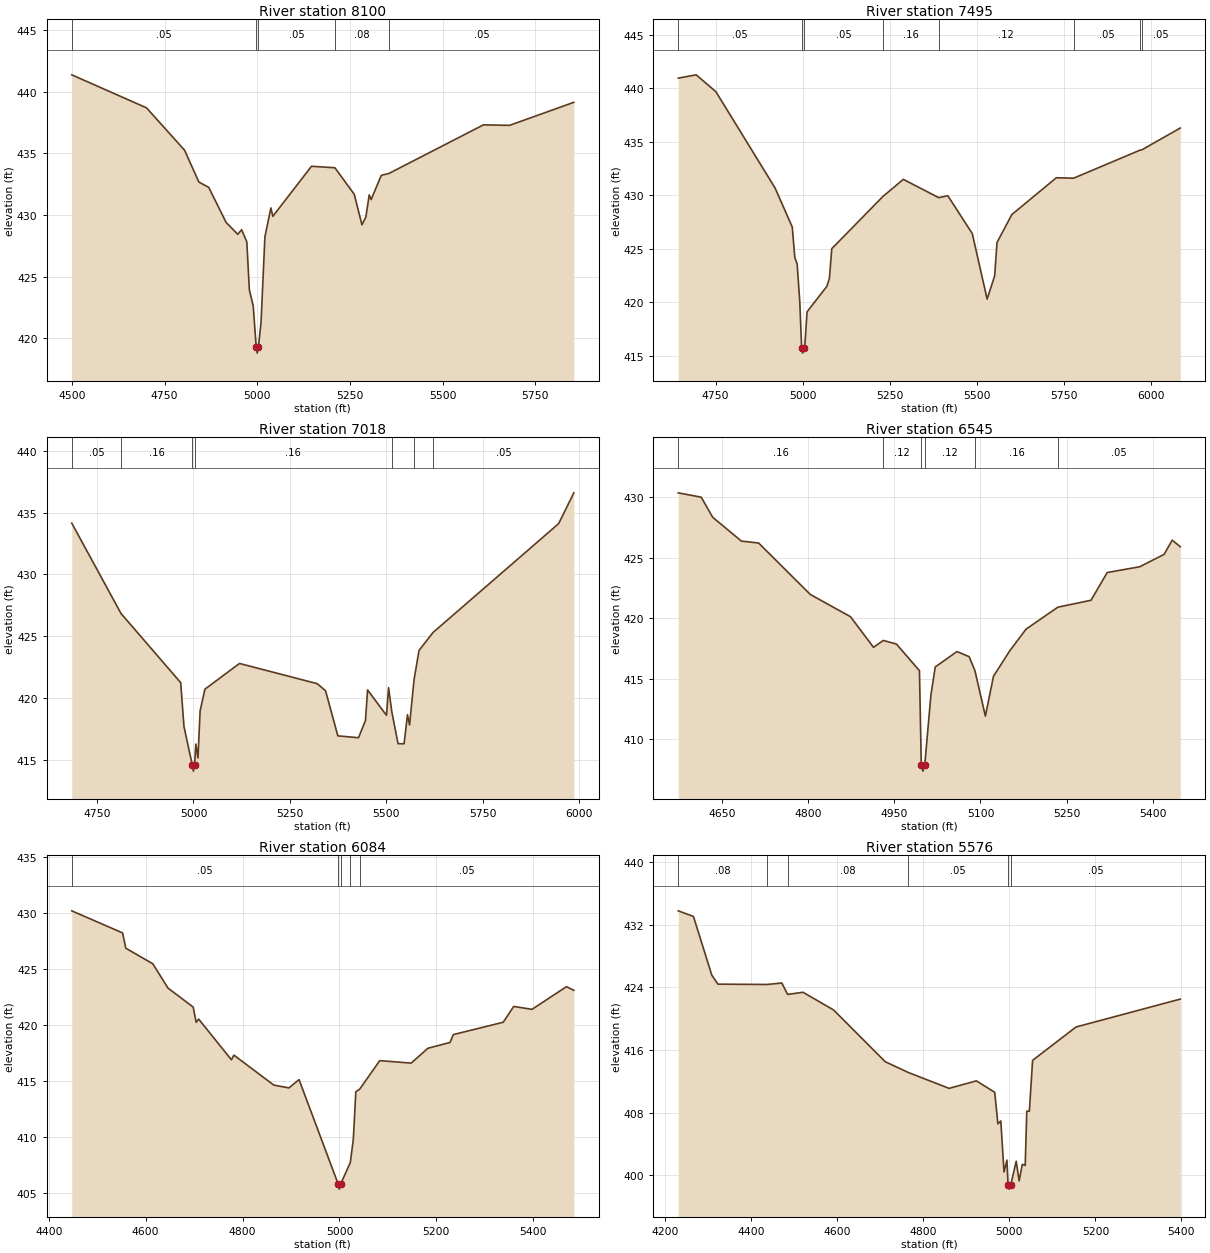
Type RM Length L Ch R = 1 ,8100    ,605,605,605
BEGIN DESCRIPTION:
UNT205 IN CCTC 16.0
END DESCRIPTION:
XS GIS Cut Line= 2
      3586642.24     10618835.05      3587935.14     10619238.54
#Sta/Elev= 30
  4499.5  441.37  4701.2  438.69  4803.9  435.25  4842.4  432.67  4868.9  432.24
  4915.8   429.4  4947.2  428.43  4957.7   428.8  4971.7  427.82  4978.6  423.92
  4989.1   422.6    4997  419.29  4999.8  418.79    5003  419.29  5010.1  421.29
  5020.5  428.22  5036.6  430.57  5041.9  429.89  5146.2  433.95  5209.3  433.83
  5261.5  431.68  5282.4   429.2  5292.9  429.84  5301.9  431.63  5307.1  431.25
  5334.4  433.21  5355.2  433.37    5610  437.31  5680.5  437.27  5853.9  439.14
#Mann= 5 ,-1 , 0
  4499.5     .05       0    4997     .03       0    5003     .05       0
  5209.3     .08       0  5355.2     .05       0
Bank Sta=4997,5003
XS Rating Curve= 0 ,0
Exp/Cntr=0.3,0.1

Type RM Length L Ch R = 1 ,7495    ,477,477,477
BEGIN DESCRIPTION:
UNT205 IN CCTC 15.0
END DESCRIPTION:
XS GIS Cut Line= 2
      3586468.57     10619008.63        3587532.      10619980.9
#Sta/Elev= 30
  4642.8  440.94  4694.3  441.25    4751  439.67  4920.6  430.68    4970  427.03
  4977.4  424.18  4984.1  423.56  4991.6  420.05    4997  415.74  4999.8  415.24
    5003  415.74  5005.7  415.74  5012.5   419.1  5069.3  421.48  5076.7  422.23
  5083.4     425  5230.2  429.88  5288.8  431.48  5390.5  429.77  5416.5  429.95
  5486.7  426.41  5529.3  420.29  5550.9  422.46  5557.7  425.58  5600.2  428.19
  5727.9  431.63  5777.5  431.59  5967.4   434.2  5973.4  434.24  6083.7  436.28
#Mann= 8 ,-1 , 0
  4642.8     .05       0    4997     .03       0    5003     .05       0
  5230.2     .16       0  5390.5     .12       0  5777.5     .05       0
  5967.4     .08       0  5973.4     .05       0
Bank Sta=4997,5003
XS Rating Curve= 0 ,0
Exp/Cntr=0.3,0.1

Type RM Length L Ch R = 1 ,7018    ,473,473,473
BEGIN DESCRIPTION:
UNT205 IN CCTC 14.0
END DESCRIPTION:
XS GIS Cut Line= 3
      3586399.62     10619310.22      3586549.61     10619610.19
      3586899.59     10620510.15
#Sta/Elev= 30
  4684.7  434.15  4812.3  426.85    4967  421.26  4975.4  417.72    4997  414.61
  4999.8  414.11    5003  414.61  5006.1   416.3  5011.7  415.18  5017.3  418.99
  5029.7  420.73  5119.3  422.81  5320.5  421.18  5342.3  420.61  5374.2  416.96
  5427.8  416.81  5445.8  418.21  5451.2  420.67  5500.2  418.62  5505.6  420.85
  5513.9  418.93  5530.1  416.33  5545.8  416.32  5554.6  418.67    5560  417.84
  5571.7  421.51  5584.5  423.86  5620.7  425.31  5946.3  434.11  5985.7   436.6
#Mann= 7 ,-1 , 0
  4684.7     .05       0  4812.3     .16       0    4997     .07       0
    5003     .16       0  5513.9     .05       0  5571.7     .16       0
  5620.7     .05       0
Bank Sta=4997,5003
XS Rating Curve= 0 ,0
Exp/Cntr=0.3,0.1

Type RM Length L Ch R = 1 ,6545    ,461,461,461
BEGIN DESCRIPTION:
UNT205 IN CCTC 13.0
END DESCRIPTION:
XS GIS Cut Line= 3
      3586299.61     10619460.24      3586299.61     10619910.19
       3586599.6     10620210.18
#Sta/Elev= 30
  4573.8  430.36  4613.8     430  4633.8  428.34  4683.8  426.37  4713.8  426.21
  4803.8  421.96  4873.8  420.12  4913.8  417.59  4930.8  418.16  4953.8  417.86
  4993.8  415.66    4997  407.86  4999.8  407.36    5003  407.86  5013.8  413.66
  5021.3  415.97  5059.1  417.24  5080.3  416.82  5090.4  415.66  5108.6  411.91
  5122.7   415.2    5151   417.3  5179.3  419.09  5234.8  420.91  5292.5  421.48
  5320.7  423.77  5377.3  424.25  5419.7  425.27  5433.9  426.45    5448   425.9
#Mann= 6 ,-1 , 0
  4573.8     .16       0  4930.8     .12       0    4997     .07       0
    5003     .12       0  5090.4     .16       0  5234.8     .05       0
Bank Sta=4997,5003
XS Rating Curve= 0 ,0
Exp/Cntr=0.3,0.1

Type RM Length L Ch R = 1 ,6084    ,508,508,508
BEGIN DESCRIPTION:
UNT205 IN CCTC 12.0
END DESCRIPTION:
XS GIS Cut Line= 3
      3585803.46     10619469.37      3585990.96     10620122.16
      3586302.96     10620295.49
#Sta/Elev= 30
  4447.6  430.17  4552.5   428.2  4559.1  426.84  4614.9  425.45  4646.1  423.29
  4698.2  421.59  4704.3  420.24  4709.5  420.52    4777   416.9  4782.2  417.31
  4864.6  414.64  4895.8  414.39  4916.6  415.13    4997  405.87  4999.8  405.37
    5003  405.87  5022.4  407.74  5028.6   409.8  5033.8  414.05  5041.8  414.28
  5083.1  416.82    5148   416.6  5182.4  417.92  5228.2  418.44  5234.9  419.14
  5337.9  420.24  5359.6  421.65  5397.4  421.39  5468.4  423.41  5483.7  423.09
#Mann= 5 ,-1 , 0
  4447.6     .05       0    4997     .03       0    5003     .05       0
  5022.4     .12       0  5041.8     .05       0
Bank Sta=4997,5003
XS Rating Curve= 0 ,0
Exp/Cntr=0.3,0.1

Type RM Length L Ch R = 1 ,5576    ,351,351,351
BEGIN DESCRIPTION:
UNT205 IN CCTC 11.0
END DESCRIPTION:
XS GIS Cut Line= 3
      3585149.62     10619760.19      3585749.61     10620310.19
      3586099.62     10620360.19
#Sta/Elev= 30
    4230   433.8  4265.4  433.08    4308  425.58  4322.2  424.42  4437.1  424.38
  4470.8  424.57  4484.4  423.11  4520.1  423.38    4591  421.13  4711.3   414.5
  4765.4  413.11  4859.9  411.09  4923.4  412.05  4965.9  410.59  4973.3  406.56
  4980.1  406.92  4987.5   400.4  4994.3  401.91    4997   398.7  4999.8   398.2
    5003   398.7  5015.9  401.77  5022.7  399.25  5030.1  401.36  5036.8  401.23
  5040.5  408.17  5046.5  408.17    5054  414.67    5155  418.94  5397.5  422.51
#Mann= 6 ,-1 , 0
    4230     .08       0  4437.1      .1       0  4484.4     .08       0
  4765.4     .05       0    4997     .03       0    5003     .05       0
Bank Sta=4997,5003
XS Rating Curve= 0 ,0
Exp/Cntr=0.3,0.1

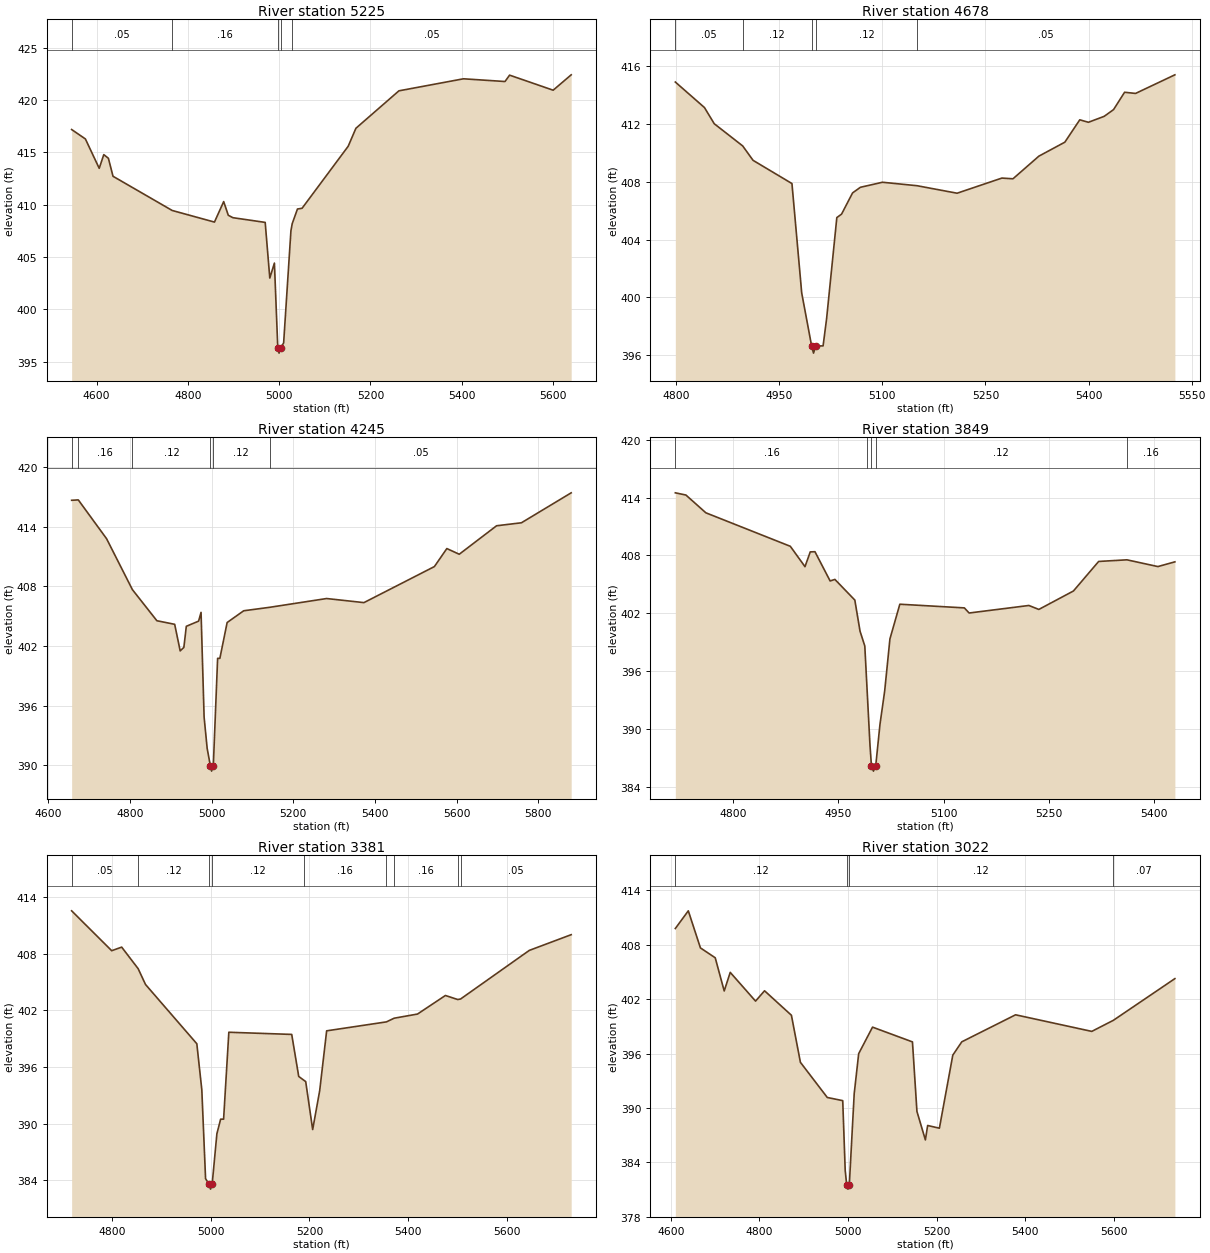
Type RM Length L Ch R = 1 ,5225    ,547,547,547
BEGIN DESCRIPTION:
UNT205 IN CCTC 10.0
END DESCRIPTION:
XS GIS Cut Line= 2
      3585129.85     10620517.99      3586213.23     10620670.78
#Sta/Elev= 30
  4545.5  417.19  4575.6  416.29  4605.9  413.48  4615.9  414.79    4626  414.44
  4636.1  412.72  4765.7  409.45  4858.3  408.34  4878.5   410.3  4888.6  408.99
  4898.7  408.76  4969.4  408.31  4979.5  402.99  4989.6  404.42    4997  396.31
  4999.8  395.81    5003  396.31  5009.8  396.78  5025.8  407.52  5028.6  408.19
  5040.1  409.59  5050.2  409.66  5151.2  415.59  5168.1  417.31  5262.3  420.89
  5403.7  422.04  5494.6  421.78  5504.7  422.39  5600.1  420.95  5639.6  422.42
#Mann= 5 ,-1 , 0
  4545.5     .05       0  4765.7     .16       0    4997     .07       0
    5003     .16       0  5028.6     .05       0
Bank Sta=4997,5003
XS Rating Curve= 0 ,0
Exp/Cntr=0.3,0.1

Type RM Length L Ch R = 1 ,4678    ,433,433,433
BEGIN DESCRIPTION:
UNT205 IN CCTC 9.0
END DESCRIPTION:
XS GIS Cut Line= 3
      3585149.61     10620860.19      3585299.61     10621010.19
      3585749.59     10621260.18
#Sta/Elev= 30
  4798.7  414.92  4841.1  413.15  4855.3  412.03  4896.7  410.49  4911.8  409.49
  4968.4  407.88  4982.6  400.29    4997  396.62  4999.8  396.12    5003  396.62
  5013.7  396.62  5018.8   398.5  5033.7  405.52  5040.6  405.76  5056.6  407.23
    5068  407.62  5100.1  407.97  5150.4  407.73  5208.7  407.21  5273.9  408.26
    5290  408.21  5327.7  409.78  5365.5  410.75  5387.2   412.3  5399.8  412.13
  5422.7  412.54  5436.4  413.01  5452.4  414.21  5468.4  414.13  5525.6  415.42
#Mann= 5 ,-1 , 0
  4798.7     .05       0  4896.7     .12       0    4997     .07       0
    5003     .12       0  5150.4     .05       0
Bank Sta=4997,5003
XS Rating Curve= 0 ,0
Exp/Cntr=0.3,0.1

Type RM Length L Ch R = 1 ,4245    ,396,396,396
BEGIN DESCRIPTION:
UNT205 IN CCTC 8.0
END DESCRIPTION:
XS GIS Cut Line= 3
       3584749.6     10620960.18      3584949.61     10621260.19
      3585799.61     10621410.19
#Sta/Elev= 30
    4657  416.64  4673.3  416.68  4742.6  412.78  4805.9  407.66  4865.8  404.54
  4909.4  404.18  4922.9  401.51  4931.9  401.86  4937.9  403.98    4968   404.5
    4974  405.38  4981.5  394.85    4989  391.71    4997  389.93  4999.8  389.43
    5003  389.93    5004  389.93  5014.6  400.76  5020.1  400.76  5037.9  404.36
  5078.5  405.54  5142.4  405.89  5281.6  406.77    5373  406.36  5545.6  409.98
  5576.1  411.79  5606.5  411.22  5697.9  414.08  5758.8  414.38  5880.7  417.39
#Mann= 6 ,-1 , 0
    4657     .05       0  4673.3     .16       0  4805.9     .12       0
    4997     .07       0    5003     .12       0  5142.4     .05       0
Bank Sta=4997,5003
XS Rating Curve= 0 ,0
Exp/Cntr=0.3,0.1

Type RM Length L Ch R = 1 ,3849    ,468,468,468
BEGIN DESCRIPTION:
UNT205 IN CCTC 7.0
END DESCRIPTION:
XS GIS Cut Line= 2
      3584473.21      10621345.2      3584999.27      10621824.4
#Sta/Elev= 30
  4717.6  414.49  4732.7  414.26  4761.1  412.42  4881.4  408.95  4902.3  406.84
  4909.8  408.37  4916.5  408.39  4938.1  405.36  4944.9  405.52  4973.3  403.38
  4980.7  400.16  4987.5  398.62  4991.3  393.34  4994.9  388.33    4997  386.16
  4999.8  385.66    5003  386.16  5009.1   390.5  5015.8  393.95  5023.3  399.36
  5037.4  402.95  5129.3  402.57  5136.1  402.04  5221.2  402.82  5235.4  402.41
  5284.7  404.32  5320.6  407.38  5360.9  407.55    5405  406.85  5429.2  407.34
#Mann= 5 ,-1 , 0
  4717.6     .16       0  4991.3     .12       0    4997     .07       0
    5003     .12       0  5360.9     .16       0
Bank Sta=4997,5003
XS Rating Curve= 0 ,0
Exp/Cntr=0.3,0.1

Type RM Length L Ch R = 1 ,3381    ,359,359,359
BEGIN DESCRIPTION:
UNT205 IN CCTC 6.0
END DESCRIPTION:
XS GIS Cut Line= 3
      3584299.62     10621510.24      3584349.61     10621810.19
      3584849.61     10622310.19
#Sta/Elev= 30
  4718.6  412.56  4799.7  408.33  4819.9  408.71  4853.3  406.42  4868.1  404.75
    4972  398.46  4982.1  393.58  4989.7  384.15    4997  383.54  4999.8  383.04
    5003  383.54  5012.6  388.91  5020.2  390.46  5026.2  390.46  5036.8  399.68
  5164.1  399.45  5178.3  394.99  5189.4  394.56  5192.4  394.45  5206.5  389.36
  5220.7  393.48  5234.8  399.83  5355.8  400.78  5371.4  401.17  5418.7  401.61
  5475.2  403.58  5500.2  403.15    5506  403.21  5644.9  408.36  5729.8  410.03
#Mann= 9 ,-1 , 0
  4718.6     .05       0  4853.3     .12       0    4997     .07       0
    5003     .12       0  5189.4     .16       0  5355.8     .12       0
  5371.4     .16       0  5500.2     .08       0    5506     .05       0
Bank Sta=4997,5003
XS Rating Curve= 0 ,0
Exp/Cntr=0.3,0.1

Type RM Length L Ch R = 1 ,3022    ,460,460,460
BEGIN DESCRIPTION:
UNT205 IN CCTC 5.0
END DESCRIPTION:
XS GIS Cut Line= 2
      3584113.84      10621371.2       3583936.8     10622485.53
#Sta/Elev= 30
    4610   409.8  4639.3  411.75  4666.7  407.66  4700.1  406.57  4720.4  402.91
    4734  404.96  4791.2  401.79  4811.5  402.93  4872.2  400.23  4892.5  395.04
  4953.2  391.16  4988.1  390.81  4993.7  383.11    4997  381.55  4999.8  381.05
    5003  381.55    5014  391.57  5024.1  395.99  5055.4  398.92  5145.6  397.29
  5155.7  389.62  5174.8  386.48  5179.9  388.07  5206.4  387.77  5236.7  395.83
    5257   397.3  5378.5  400.28  5550.6  398.45  5599.3  399.67  5738.3  404.27
#Mann= 4 ,-1 , 0
    4610     .12       0    4997     .07       0    5003     .12       0
  5599.3     .07       0
Bank Sta=4997,5003
XS Rating Curve= 0 ,0
Exp/Cntr=0.3,0.1

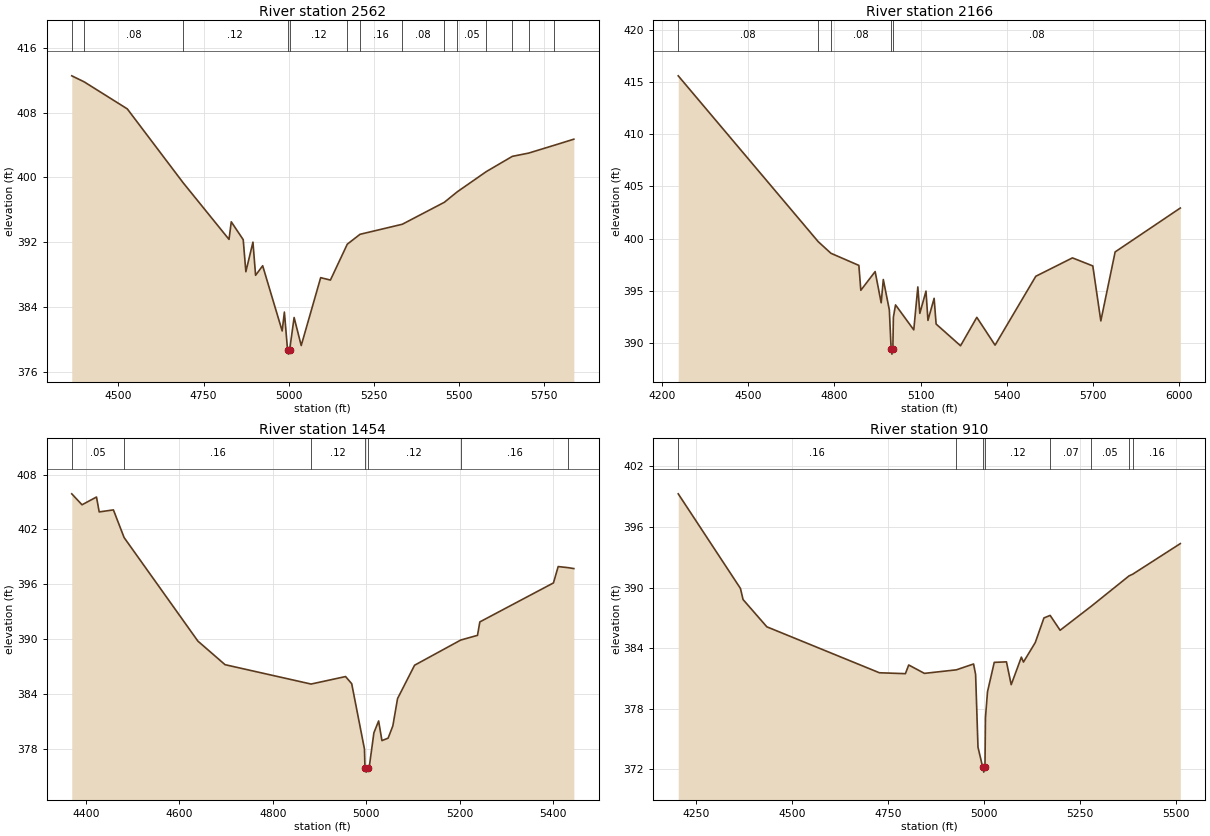
Type RM Length L Ch R = 1 ,2562    ,396,396,396
BEGIN DESCRIPTION:
UNT205 IN CCTC 4.0
END DESCRIPTION:
XS GIS Cut Line= 2
       3584034.9     10621255.02      3583087.62     10622386.55
#Sta/Elev= 30
  4362.7  412.54    4399   411.8  4525.9  408.46  4690.1  399.34  4824.9  392.35
  4831.5  394.52  4866.6  392.32  4874.4  388.36  4895.2  392.01    4903  387.92
  4923.8   389.1  4981.1  381.05  4987.6  383.38    4997  378.69  4999.8  378.19
    5003  378.69  5016.2  382.71  5037.1  379.25  5094.3  387.63  5122.9  387.33
  5172.5  391.76    5210  392.98  5334.2  394.22  5457.7  396.93  5495.9  398.23
  5581.5  400.73  5657.6   402.6  5705.3     403  5780.9  403.97  5838.4  404.72
#Mann= 14 ,-1 , 0
  4362.7     .12       0    4399     .08       0  4690.1     .12       0
    4997     .07       0    5003     .12       0  5172.5     .08       0
    5210     .16       0  5334.2     .08       0  5457.7     .16       0
  5495.9     .05       0  5581.5     .16       0  5657.6     .08       0
  5705.3     .16       0  5780.9     .05       0
Bank Sta=4997,5003
XS Rating Curve= 0 ,0
Exp/Cntr=0.3,0.1

Type RM Length L Ch R = 1 ,2166    ,712,712,712
BEGIN DESCRIPTION:
UNT205 IN CCTC 3.0
END DESCRIPTION:
XS GIS Cut Line= 2
      3583744.02     10621126.48      3582551.36     10622402.47
#Sta/Elev= 30
  4256.4  415.57  4743.4   399.7  4787.6  398.59  4884.8  397.43  4891.6  395.05
  4941.4  396.84  4962.4  393.85  4969.8  396.08  4990.8  393.17    4997  389.44
  4999.8  388.94    5003  389.44  5004.9  392.48  5012.3  393.65  5075.8  391.26
  5089.9  395.37  5096.8  392.84  5118.3  394.97  5125.1  392.17  5146.6  394.28
  5153.5  391.82  5238.5  389.74  5295.1  392.46  5358.6   389.8  5500.3  396.39
  5627.8  398.15  5698.6  397.38  5726.5  392.12  5776.3  398.72    6003  402.92
#Mann= 5 ,-1 , 0
  4256.4     .08       0  4743.4     .05       0  4787.6     .08       0
    4997     .07       0    5003     .08       0
Bank Sta=4997,5003
XS Rating Curve= 0 ,0
Exp/Cntr=0.3,0.1

Type RM Length L Ch R = 1 ,1454    ,544,544,544
BEGIN DESCRIPTION:
UNT205 IN CCTC 2.0
END DESCRIPTION:
XS GIS Cut Line= 3
       3583035.7     10621345.21      3582608.62     10621605.62
      3582525.29     10622173.32
#Sta/Elev= 30
  4369.8   405.9  4391.7   404.7  4422.7  405.55  4428.5  403.92  4458.9  404.14
  4481.8  401.11  4639.6  389.78  4697.7   387.2  4881.7  385.08  4955.5   385.9
  4968.6  385.12  4995.9  377.97    4997  375.94  4999.8  375.44    5003  375.94
    5006  375.94  5016.1  379.75  5026.2  381.04  5033.3  378.89  5046.5  379.16
  5056.6   380.5  5066.7  383.49  5103.1  387.14    5202   389.9  5237.7  390.41
  5242.7  391.88  5400.2  396.15  5410.3  397.94  5431.4  397.82  5443.8  397.72
#Mann= 7 ,-1 , 0
  4369.8     .05       0  4481.8     .16       0  4881.7     .12       0
    4997     .07       0    5003     .12       0    5202     .16       0
  5431.4     .05       0
Bank Sta=4997,5003
XS Rating Curve= 0 ,0
Exp/Cntr=0.3,0.1

Type RM Length L Ch R = 1 ,910     ,0,0,0
BEGIN DESCRIPTION:
UNT205 IN CCTC 1.0
END DESCRIPTION:
XS GIS Cut Line= 4
      3582853.38     10621225.42      3582181.54     10621397.29
      3582119.04     10621574.37      3582280.52     10621970.25
#Sta/Elev= 30
  4203.4  399.28  4365.6  389.91  4372.4  388.81  4434.4  386.11  4727.8  381.56
  4795.6  381.47  4804.2  382.33  4845.1   381.5  4928.4  381.85  4973.3  382.43
  4978.6  381.39  4984.8  374.19    4997  372.22  4999.8  371.72    5003  372.22
  5004.3  377.13  5009.6  379.68  5027.2  382.59    5059  382.64  5071.4  380.38
  5097.9  383.11  5103.3  382.62  5134.1  384.55  5156.7  386.99  5172.9  387.24
  5198.9  385.77  5280.5  388.16  5378.8  391.16  5388.1  391.32  5512.2  394.35
#Mann= 8 ,-1 , 0
  4203.4     .16       0  4928.4     .12       0    4997     .07       0
    5003     .12       0  5172.9     .07       0  5280.5     .05       0
  5378.8     .07       0  5388.1     .16       0
Bank Sta=4997,5003
XS Rating Curve= 0 ,0
Exp/Cntr=0.3,0.1

Chan Stop Cuts=-1
Use User Specified Reach Order=0
Composite Channel Slope=5