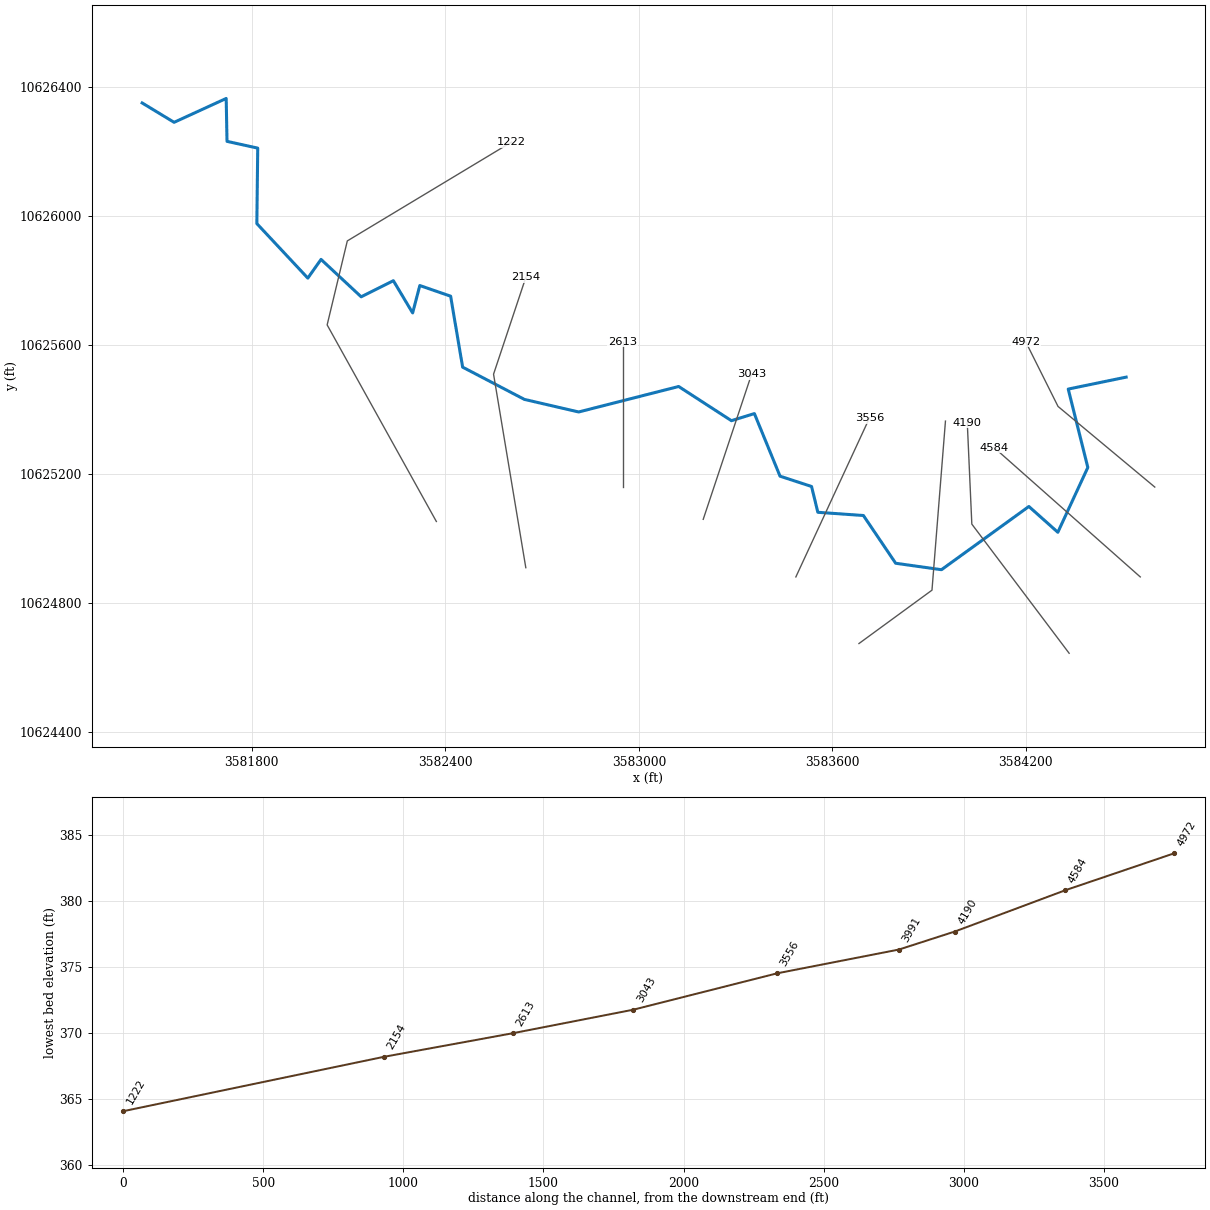
--- UNT207 IN CCTC.prj (project) ---

Proj Title=UNT207 IN CCTC Base Level Engineering
Current Plan=p01
Default Exp/Contr=0.3,0.1
English Units
Geom File=g01
Flow File=f01
Plan File=p01
Y Axis Title=Elevation
X Axis Title(PF)=Main Channel Distance
X Axis Title(XS)=Station
BEGIN DESCRIPTION:
UNT207 IN CCTC
END DESCRIPTION:
DSS Export Rating Curves= 0
DSS Export Rating Curve Sorted= 0
DSS Export Volume Flow Curves= 0
DXF OffsetX= 0
DXF OffsetY= 0
DXF ScaleX= 1
DXF ScaleY= 10

--- UNT207 IN CCTC.p01 (plan) ---

Plan Title=Multiple Run
Short Identifier=Multiple
Geom File=g01
Flow File=f01
Subcritical Flow
K Sum by GR= 0
Std Step Tol= 0.01
Critical Tol= 0.01
Num of Std Step Trials= 20
Max Error Tol= 0.3
Flow Tol Ratio= 0.001
Split Flow NTrial= 30
Split Flow Tol= 0.02
Split Flow Ratio= 0.02
Log Output Level= 0
Friction Slope Method= 1
Unsteady Friction Slope Method= 2
Unsteady Bridges Friction Slope Method= 1
Parabolic Critical Depth
Global Vel Dist=  1 , 1 , 1
Global Log Level= 0
CheckData=True
Encroach Param= -1, 0, 0, 0
BEGIN DESCRIPTION:
Multiple Run
END DESCRIPTION:

--- UNT207 IN CCTC.f01 (steady flow) ---

Flow Title=Multiple
Number of Profiles=7
Profile Names=10-year,25-year,50-year,1pct_min,100-year,1pct_plu,500-year
River Rch & RM= UNT207 IN CCTC,Reach-1,4972
     889    1187    1426    1254    1695    2293    2383
Boundary for River Rch & Prof#=UNT207 IN CCTC,Reach-1,1
Up Type=0
Dn Type=3
Dn Slope=0.005
Boundary for River Rch & Prof#=UNT207 IN CCTC,Reach-1,2
Up Type=0
Dn Type=3
Dn Slope=0.005
Boundary for River Rch & Prof#=UNT207 IN CCTC,Reach-1,3
Up Type=0
Dn Type=3
Dn Slope=0.005
Boundary for River Rch & Prof#=UNT207 IN CCTC,Reach-1,4
Up Type=0
Dn Type=3
Dn Slope=0.005
Boundary for River Rch & Prof#=UNT207 IN CCTC,Reach-1,5
Up Type=0
Dn Type=3
Dn Slope=0.005
Boundary for River Rch & Prof#=UNT207 IN CCTC,Reach-1,6
Up Type=0
Dn Type=3
Dn Slope=0.005
Boundary for River Rch & Prof#=UNT207 IN CCTC,Reach-1,7
Up Type=0
Dn Type=3
Dn Slope=0.005

--- UNT207 IN CCTC.g01 (geometry) ---

Geom Title=Existing Conditions
Program Version=4.10

River Reach=UNT207 IN CCTC  ,Reach-1
Reach XY= 30
      3584510.75       10625501.      3584331.25       10625464.
        3584392.       10625221.        3584299.       10625020.
      3584209.25       10625100.      3583938.25       10624904.
      3583796.25       10624924.      3583696.25       10625072.
        3583555.       10625082.       3583535.5       10625162.
      3583437.75       10625194.      3583358.25       10625388.
        3583287.       10625366.       3583123.5       10625472.
       3582813.5       10625393.      3582645.25       10625432.
      3582453.75       10625532.       3582416.5       10625752.
        3582321.       10625785.      3582298.75       10625700.
        3582239.       10625800.      3582139.25       10625750.
      3582014.75       10625866.      3581973.75       10625808.
      3581815.75       10625977.       3581818.5       10626211.
      3581723.25       10626232.      3581720.75       10626365.
      3581559.25       10626291.      3581460.25       10626351.

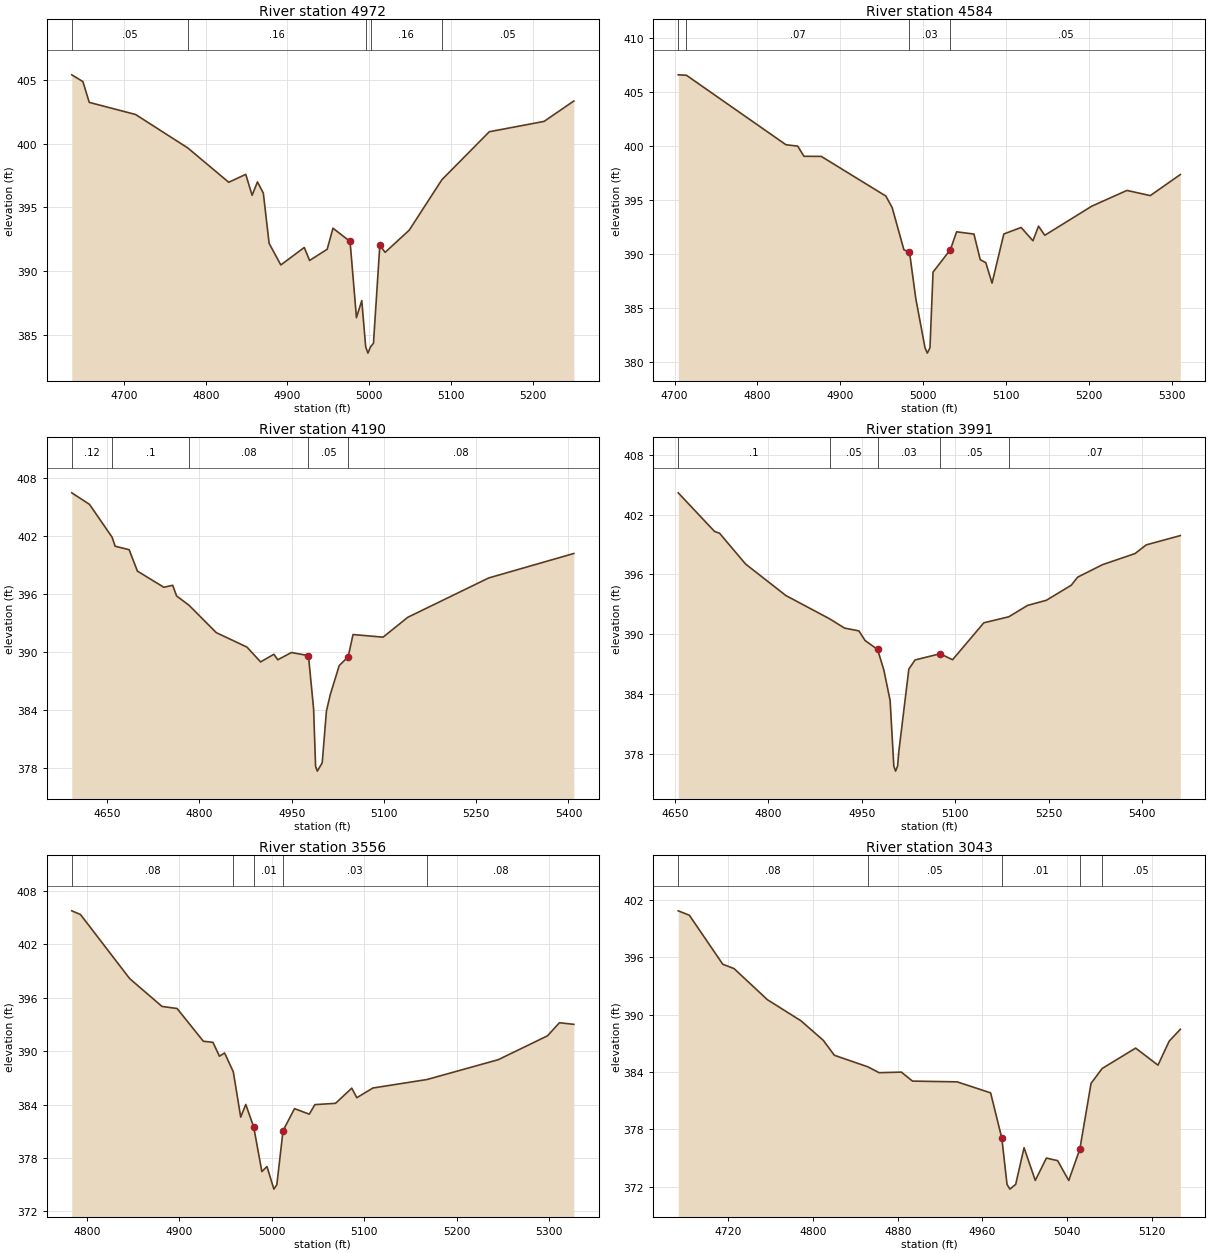
Type RM Length L Ch R = 1 ,4972    ,388,388,388
BEGIN DESCRIPTION:
UNT207 IN CCTC 8.0
END DESCRIPTION:
XS GIS Cut Line= 3
      3584599.58     10625160.22      3584299.61     10625410.19
       3584199.6     10625610.21
#Sta/Elev= 30
  4636.2  405.39  4649.8  404.86  4657.6  403.23  4714.3  402.28  4778.1  399.66
  4828.2  396.97    4849  397.59  4856.8  395.95  4863.3     397  4870.5  396.12
  4877.6  392.18  4891.9  390.49  4920.6  391.86  4927.1  390.84  4948.6  391.72
  4955.7  393.37  4976.6  392.33  4984.4  386.36  4990.9   387.7  4995.7  384.08
  4998.4  383.58  5001.7  384.08  5005.2  384.35    5013  392.03  5019.5  391.48
    5049  393.22  5088.9  397.17  5146.9  400.93  5213.9  401.74  5250.3  403.34
#Mann= 5 ,-1 , 0
  4636.2     .05       0  4778.1     .16       0  4995.7     .07       0
  5001.7     .16       0  5088.9     .05       0
Bank Sta=4976.6,5013
XS Rating Curve= 0 ,0
Exp/Cntr=0.3,0.1

Type RM Length L Ch R = 1 ,4584    ,394,394,394
BEGIN DESCRIPTION:
UNT207 IN CCTC 7.0
END DESCRIPTION:
XS GIS Cut Line= 2
      3584554.56     10624881.65      3584101.44     10625282.68
#Sta/Elev= 30
  4704.5  406.55  4714.4  406.51  4834.3  400.08  4848.5  399.95    4856  399.01
  4876.9     399  4954.7  395.33  4962.3  394.27  4976.5  390.35  4983.2  390.16
  4990.7  385.89  5001.9  381.29  5004.7  380.79  5007.9  381.29  5011.6  388.29
  5032.5  390.37    5040  392.02  5060.9  391.81  5068.5  389.44  5075.2  389.16
  5082.7  387.27  5096.9  391.82  5117.8  392.42    5132  391.19  5138.7  392.54
  5146.3   391.7  5203.1   394.4  5245.3  395.85  5273.4  395.37  5309.6  397.32
#Mann= 4 ,-1 , 0
  4704.5     .05       0  4714.4     .07       0  4983.2     .03       0
  5032.5     .05       0
Bank Sta=4983.2,5032.5
XS Rating Curve= 0 ,0
Exp/Cntr=0.3,0.1

Type RM Length L Ch R = 1 ,4190    ,199,199,199
BEGIN DESCRIPTION:
Mapping XS 0683020d
END DESCRIPTION:
XS GIS Cut Line= 3
      3584334.04     10624644.96      3584032.37     10625045.38
      3584018.26     10625360.02
#Sta/Elev= 30
  4592.4  406.44  4621.2  405.25    4658  401.85  4662.9  400.92  4685.7  400.56
  4699.1  398.35    4742  396.68  4756.5  396.88  4762.8  395.78    4783  394.82
  4827.3  391.99  4877.3  390.49  4899.4  388.96    4921  389.75  4927.3  389.18
  4949.5  389.93  4977.2  389.61  4985.6   384.1  4988.8  378.17  4991.6  377.67
  4999.6  378.53  5006.4  383.86  5012.6  385.56  5027.2  388.58  5041.8  389.49
  5049.7  391.79  5098.6  391.52  5138.6  393.57  5270.3  397.64  5408.7  400.17
#Mann= 5 ,-1 , 0
  4592.4     .12       0    4658      .1       0    4783     .08       0
  4977.2     .05       0  5041.8     .08       0
Bank Sta=4977.2,5041.8
XS Rating Curve= 0 ,0
Exp/Cntr=0.3,0.1

Type RM Length L Ch R = 1 ,3991    ,435,435,435
BEGIN DESCRIPTION:
UNT207 IN CCTC 6.0
END DESCRIPTION:
XS GIS Cut Line= 3
      3583682.45     10624675.11      3583908.82     10624840.54
      3583950.62      10625364.7
#Sta/Elev= 30
  4655.2  404.17  4713.6   400.3  4721.5  400.13  4763.2  397.05    4828  393.89
  4898.2  391.56  4922.2  390.63  4945.3  390.35  4955.3  389.38  4975.3  388.49
  4985.4  386.42  4995.4  383.39  5001.4  376.81  5004.2  376.31  5007.4  376.81
  5009.4  378.26  5025.5  386.53  5035.5  387.44  5075.7  388.06  5095.7  387.46
  5145.9  391.16    5186  391.76  5216.1   392.9  5246.2  393.41  5286.3  394.92
  5296.4  395.72  5336.5  396.98  5388.7  398.09  5406.7  398.96  5461.4  399.89
#Mann= 5 ,-1 , 0
  4655.2      .1       0  4898.2     .05       0  4975.3     .03       0
  5075.7     .05       0    5186     .07       0
Bank Sta=4975.3,5075.7
XS Rating Curve= 0 ,0
Exp/Cntr=0.3,0.1

Type RM Length L Ch R = 1 ,3556    ,513,513,513
BEGIN DESCRIPTION:
UNT207 IN CCTC 5.0
END DESCRIPTION:
XS GIS Cut Line= 2
      3583486.83     10624881.63      3583715.04     10625374.35
#Sta/Elev= 30
  4783.8  405.77  4793.2  405.36  4846.4  398.16  4881.4  395.03  4897.7   394.8
  4926.1  391.12  4936.5     391  4943.5  389.44  4949.1   389.8  4958.5  387.69
  4966.5   382.6    4972  384.02  4980.6  381.48  4989.4  376.48  4994.9  377.05
  5002.4  374.51  5005.6  375.01  5012.3  381.08  5024.7  383.55  5040.7  382.93
  5046.7     384  5069.1  384.15  5086.6  385.85  5092.1  384.78  5109.5  385.87
  5167.9  386.82  5245.1  389.05  5298.3  391.73  5311.2   393.2  5326.8  393.02
#Mann= 5 ,-1 , 0
  4783.8     .08       0  4958.5     .03       0  4980.6     .01       0
  5012.3     .03       0  5167.9     .08       0
Bank Sta=4980.6,5012.3
XS Rating Curve= 0 ,0
Exp/Cntr=0.3,0.1

Type RM Length L Ch R = 1 ,3043    ,430,430,430
BEGIN DESCRIPTION:
UNT207 IN CCTC 4.0
END DESCRIPTION:
XS GIS Cut Line= 3
      3583199.62     10625060.22      3583299.61     10625360.19
      3583349.61     10625510.18
#Sta/Elev= 30
  4672.6  400.87  4683.1  400.41  4714.7  395.28  4725.3  394.83  4756.9  391.57
  4788.5  389.37  4809.6  387.33  4820.1  385.76  4851.8  384.55  4862.3  383.94
  4883.4     384  4893.9  383.06  4936.1  382.98  4967.7  381.83  4978.3  377.08
  4983.2  372.26  4985.9  371.76  4991.4  372.26  4999.3  376.09  5009.9  372.67
  5020.4  375.01    5031  374.74  5041.5  372.66    5052  375.95  5062.6  382.83
  5073.1  384.38  5104.7  386.51  5125.8  384.73  5136.4  387.24  5146.9  388.48
#Mann= 5 ,-1 , 0
  4672.6     .08       0  4851.8     .05       0  4978.3     .01       0
    5052     .03       0  5073.1     .05       0
Bank Sta=4978.3,5052
XS Rating Curve= 0 ,0
Exp/Cntr=0.3,0.1

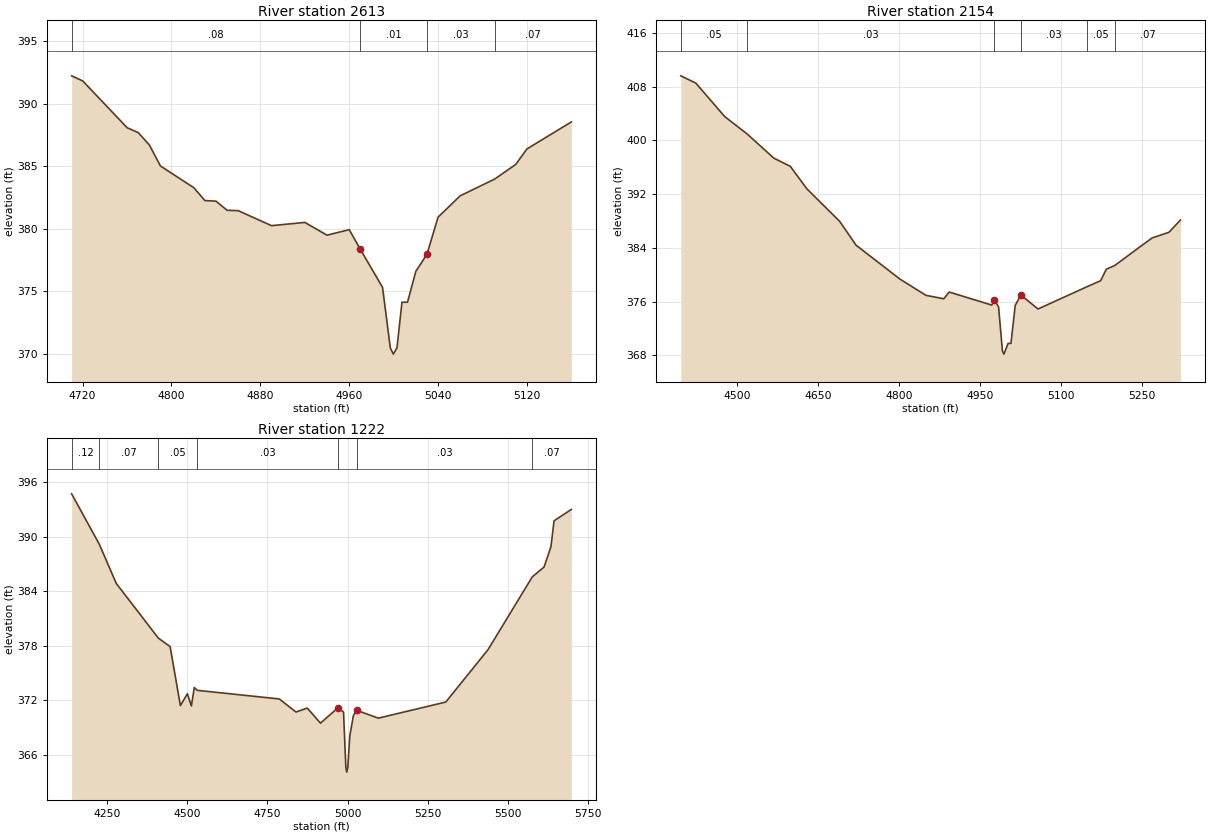
Type RM Length L Ch R = 1 ,2613    ,459,459,459
BEGIN DESCRIPTION:
UNT207 IN CCTC 3.0
END DESCRIPTION:
XS GIS Cut Line= 3
      3582949.61      10625160.2      3582949.61     10625460.19
      3582949.61      10625610.2
#Sta/Elev= 30
  4710.2  392.23  4720.2  391.82  4760.2  388.08  4770.2  387.69  4780.2   386.7
  4790.2  385.02  4820.2  383.29  4830.2  382.26  4840.2  382.21  4850.2  381.48
  4860.2  381.45  4890.2  380.25  4920.2  380.51  4940.2  379.49  4960.2  379.93
  4970.2  378.36  4990.2  375.32  4997.2  370.48  4999.9  369.98  5003.2  370.48
  5007.7  374.13  5012.7  374.13  5020.2   376.6  5030.2  377.96  5040.2  380.93
  5060.2  382.64  5091.3  383.98  5110.2  385.15  5120.2  386.38  5160.2  388.54
#Mann= 4 ,-1 , 0
  4710.2     .08       0  4970.2     .01       0  5030.2     .03       0
  5091.3     .07       0
Bank Sta=4970.2,5030.2
XS Rating Curve= 0 ,0
Exp/Cntr=0.3,0.1

Type RM Length L Ch R = 1 ,2154    ,932,932,932
BEGIN DESCRIPTION:
UNT207 IN CCTC 2.0
END DESCRIPTION:
XS GIS Cut Line= 3
       3582649.6     10624910.22      3582549.61     10625510.19
      3582649.62     10625810.21
#Sta/Elev= 30
  4396.3  409.62  4424.1  408.54  4477.4  403.57  4519.6  400.93  4568.6  397.36
    4599  396.15  4629.4  392.82  4690.3  387.96  4720.7  384.41  4801.8  379.37
  4849.9  376.95  4882.9  376.44    4893  377.44  4971.6   375.5  4976.7  376.23
  4984.3  375.24  4991.4   368.7  4994.2   368.2    5002   369.8  5007.2   369.8
  5015.1  375.45  5025.6  376.99  5057.3  374.92  5147.1   378.2  5173.2  379.13
  5183.7  380.84  5199.2  381.39  5268.1  385.48  5299.7  386.34  5320.8  388.16
#Mann= 6 ,-1 , 0
  4396.3     .05       0  4519.6     .03       0  4976.7     .01       0
  5025.6     .03       0  5147.1     .05       0  5199.2     .07       0
Bank Sta=4976.7,5025.6
XS Rating Curve= 0 ,0
Exp/Cntr=0.3,0.1

Type RM Length L Ch R = 1 ,1222    ,0,0,0
BEGIN DESCRIPTION:
UNT207 IN CCTC 1.0
END DESCRIPTION:
XS GIS Cut Line= 4
      3582372.27     10625053.51      3582033.72     10625662.91
      3582096.22     10625923.32      3582605.59     10626229.99
#Sta/Elev= 30
  4138.8   394.7    4225  389.16  4278.1  384.84  4409.6  378.82  4446.2  377.89
  4478.2   371.4    4500   372.7  4512.5  371.36  4521.7  373.39  4530.9  373.08
  4787.1  372.13    4839  370.69  4874.3  371.13  4915.4  369.47 4970.57  371.17
  4987.4  370.69  4994.7  364.58  4997.4  364.08  5000.7  364.58    5007  368.07
  5018.2   370.3  5028.5  370.88  5096.1  370.02  5306.6  371.79  5438.7  377.57
  5576.5  385.56  5613.4  386.65  5634.8  388.89  5644.5  391.73  5698.3  392.98
#Mann= 7 ,-1 , 0
  4138.8     .12       0    4225     .07       0  4409.6     .05       0
  4530.9     .03       0  4970.1     .01       0  5028.5     .03       0
  5576.5     .07       0
Bank Sta=4970.57,5028.5
XS Rating Curve= 0 ,0
Exp/Cntr=0.3,0.1

Chan Stop Cuts=-1
Use User Specified Reach Order=0
Composite Channel Slope=5