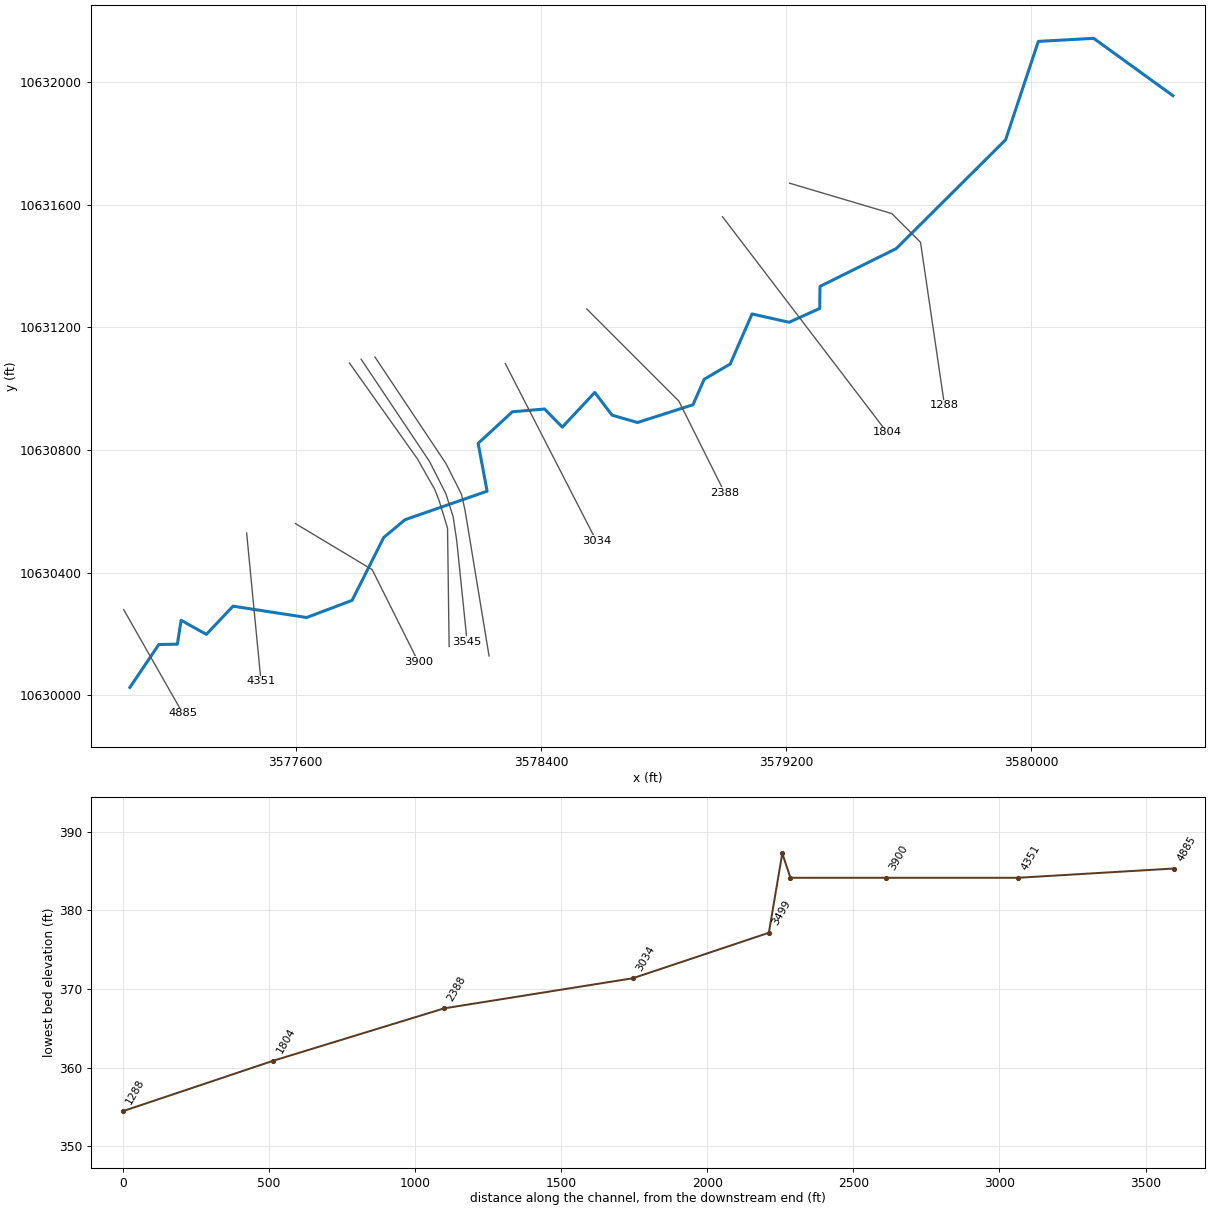
--- UNT208 IN CCTC.prj (project) ---

Proj Title=UNT208 IN CCTC Base Level Engineering
Current Plan=p01
Default Exp/Contr=0.3,0.1
English Units
Geom File=g01
Flow File=f01
Plan File=p01
Y Axis Title=Elevation
X Axis Title(PF)=Main Channel Distance
X Axis Title(XS)=Station
BEGIN DESCRIPTION:
UNT208 IN CCTC
END DESCRIPTION:
DSS Export Rating Curves= 0
DSS Export Rating Curve Sorted= 0
DSS Export Volume Flow Curves= 0
DXF OffsetX= 0
DXF OffsetY= 0
DXF ScaleX= 1
DXF ScaleY= 10

--- UNT208 IN CCTC.p01 (plan) ---

Plan Title=Multiple Run
Short Identifier=Multiple
Geom File=g01
Flow File=f01
Subcritical Flow
K Sum by GR= 0
Std Step Tol= 0.01
Critical Tol= 0.01
Num of Std Step Trials= 20
Max Error Tol= 0.3
Flow Tol Ratio= 0.001
Split Flow NTrial= 30
Split Flow Tol= 0.02
Split Flow Ratio= 0.02
Log Output Level= 0
Friction Slope Method= 1
Unsteady Friction Slope Method= 2
Unsteady Bridges Friction Slope Method= 1
Parabolic Critical Depth
Global Vel Dist=  1 , 1 , 1
Global Log Level= 0
CheckData=True
Encroach Param= -1, 0, 0, 0
BEGIN DESCRIPTION:
Multiple Run
END DESCRIPTION:

--- UNT208 IN CCTC.f01 (steady flow) ---

Flow Title=Multiple
Number of Profiles=7
Profile Names=10-year,25-year,50-year,1pct_min,100-year,1pct_plu,500-year
River Rch & RM= UNT208 IN CCTC,Reach-1,4885
     708     932    1109     968    1308    1770    1809
Boundary for River Rch & Prof#=UNT208 IN CCTC,Reach-1,1
Up Type=0
Dn Type=3
Dn Slope=0.005
Boundary for River Rch & Prof#=UNT208 IN CCTC,Reach-1,2
Up Type=0
Dn Type=3
Dn Slope=0.005
Boundary for River Rch & Prof#=UNT208 IN CCTC,Reach-1,3
Up Type=0
Dn Type=3
Dn Slope=0.005
Boundary for River Rch & Prof#=UNT208 IN CCTC,Reach-1,4
Up Type=0
Dn Type=3
Dn Slope=0.005
Boundary for River Rch & Prof#=UNT208 IN CCTC,Reach-1,5
Up Type=0
Dn Type=3
Dn Slope=0.005
Boundary for River Rch & Prof#=UNT208 IN CCTC,Reach-1,6
Up Type=0
Dn Type=3
Dn Slope=0.005
Boundary for River Rch & Prof#=UNT208 IN CCTC,Reach-1,7
Up Type=0
Dn Type=3
Dn Slope=0.005

--- UNT208 IN CCTC.g01 (geometry) ---

Geom Title=Existing Conditions
Program Version=4.10

River Reach=UNT208 IN CCTC  ,Reach-1
Reach XY= 30
       3577059.5       10630026.      3577153.75       10630166.
      3577214.25       10630167.       3577226.5       10630245.
      3577308.75       10630199.      3577395.75       10630291.
        3577636.       10630254.      3577784.25       10630310.
      3577887.25       10630515.      3577956.75       10630573.
       3578224.5       10630666.      3578195.25       10630822.
        3578307.       10630925.        3578412.       10630934.
      3578469.75       10630875.       3578575.5       10630988.
        3578632.       10630914.        3578715.       10630890.
        3578896.       10630948.       3578932.5       10631031.
       3579017.5       10631081.       3579088.5       10631244.
       3579209.5       10631217.      3579309.25       10631262.
      3579310.25       10631334.       3579558.5       10631457.
       3579915.5       10631812.      3580022.25       10632133.
      3580202.75       10632143.      3580461.25       10631956.

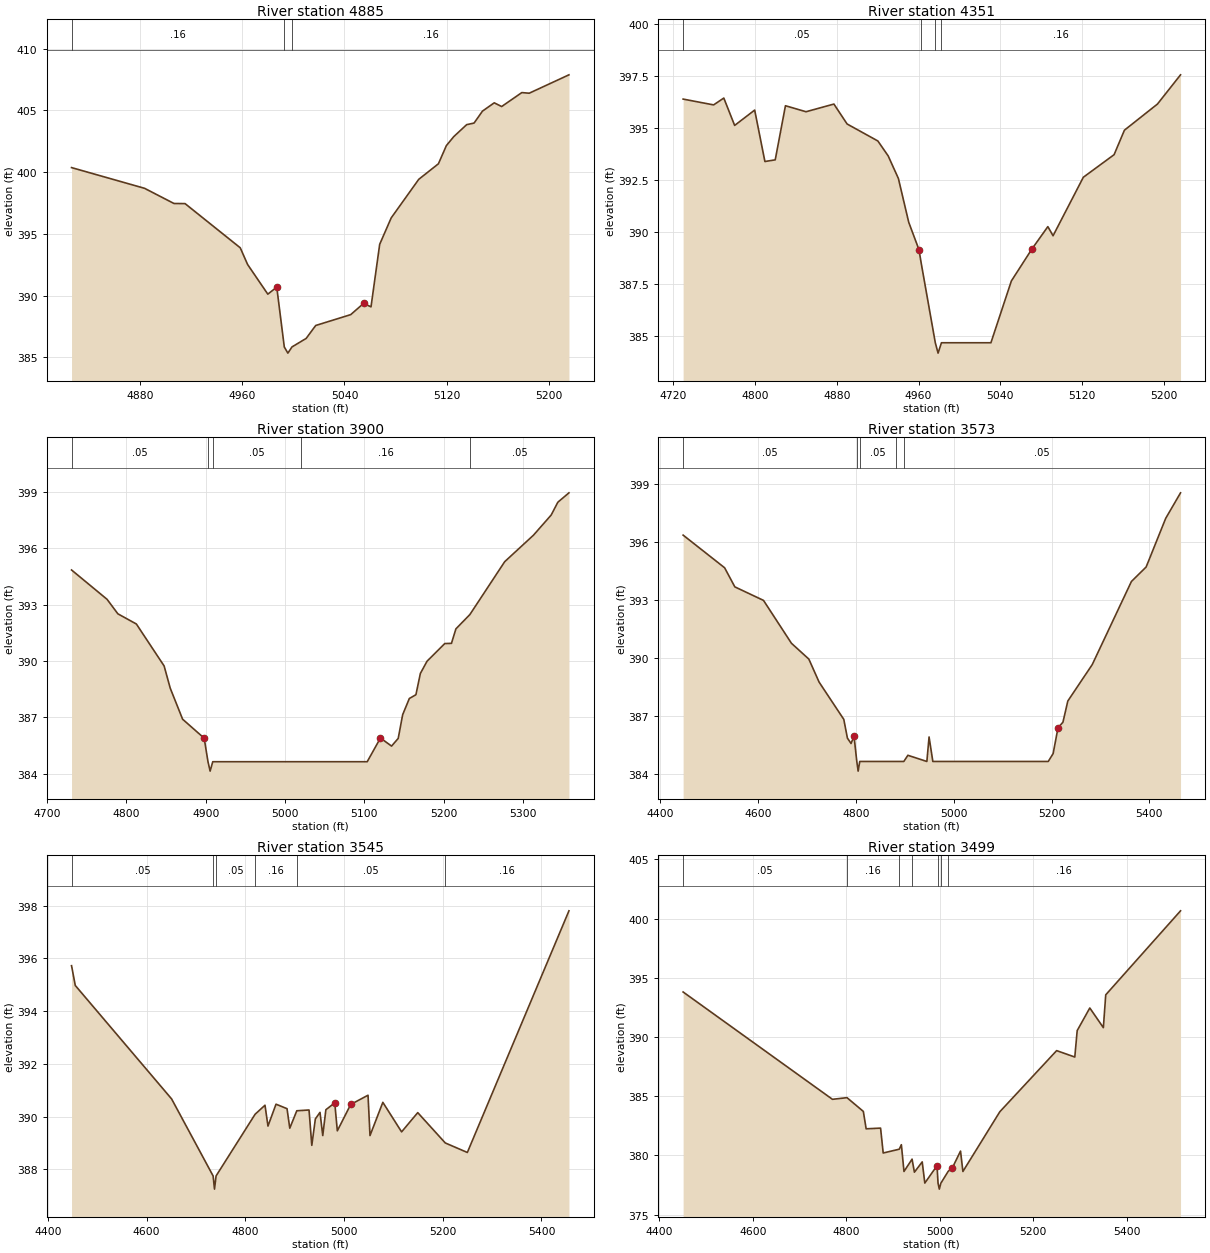
Type RM Length L Ch R = 1 ,4885    ,534,534,534
BEGIN DESCRIPTION:
UNT208 IN CCTC 8.0
END DESCRIPTION:
XS GIS Cut Line= 2
      3577039.15     10630279.86      3577231.84     10629941.36
#Sta/Elev= 30
  4826.3  400.37  4883.5  398.69  4906.5  397.46  4915.2  397.45  4958.4  393.87
  4964.2  392.51    4980  390.11    4987  390.68  4992.9  385.83  4995.7  385.33
  4998.9  385.83    5010  386.52  5017.5  387.57  5044.9  388.45    5055  389.36
  5060.8  389.08  5067.6  394.15  5076.6  396.29  5098.2  399.42  5113.6  400.68
  5119.8  402.15  5125.6  402.88  5135.7  403.85  5141.5  403.98  5148.1  404.95
  5157.3  405.62  5163.1  405.32  5178.9  406.45  5184.7   406.4  5215.8  407.89
#Mann= 3 ,-1 , 0
  4826.3     .16       0  4992.9     .07       0  4998.9     .16       0
Bank Sta=4987,5055
XS Rating Curve= 0 ,0
Exp/Cntr=0.3,0.1

Type RM Length L Ch R = 1 ,4351    ,451,451,451
BEGIN DESCRIPTION:
Mapping XS fc7091c1
END DESCRIPTION:
XS GIS Cut Line= 2
      3577440.19     10630529.85      3577487.06     10630045.51
#Sta/Elev= 30
  4729.7   396.4  4759.5  396.12  4769.5  396.45  4780.1  395.13  4799.7  395.87
  4809.7  393.39  4819.8  393.47  4829.8  396.08  4849.9  395.79  4877.2  396.16
  4890.1   395.2  4920.2  394.38  4930.3  393.66  4940.3  392.57  4950.4  390.46
  4960.4  389.14  4962.7  388.46  4976.4  384.65  4979.1  384.15  4982.4  384.65
  5030.8  384.65  5050.8  387.63  5070.9  389.17  5086.5  390.25  5091.6  389.81
  5121.2  392.63  5151.3  393.72  5161.4   394.9  5193.7  396.16  5216.3  397.57
#Mann= 4 ,-1 , 0
  4729.7     .05       0  4962.7     .16       0  4976.4     .07       0
  4982.4     .16       0
Bank Sta=4960.4,5070.9
XS Rating Curve= 0 ,0
Exp/Cntr=0.3,0.1

Type RM Length L Ch R = 1 ,3900    ,327,327,327
BEGIN DESCRIPTION:
UNT208 IN CCTC 7.0
END DESCRIPTION:
XS GIS Cut Line= 3
      3577599.57     10630560.21      3577849.61     10630410.19
      3577999.61      10630110.2
#Sta/Elev= 30
  4730.9  394.84  4775.7  393.28  4789.3  392.51  4812.6  391.97  4847.6  389.74
  4855.3  388.56  4870.9  386.91  4898.1   385.9  4902.9  384.65  4905.6  384.15
  4908.9  384.65  5020.7  384.65  5103.6  384.65  5120.3  385.91  5134.3  385.48
  5142.7  385.89  5148.3  387.15  5156.7  388.01    5165  388.21  5170.6  389.34
    5179  389.99  5201.4  390.93  5209.8  390.94  5215.4  391.71    5233  392.47
  5276.9  395.28  5313.2  396.69  5335.5  397.76  5343.9  398.44  5357.9  398.94
#Mann= 5 ,-1 , 0
  4730.9     .05       0  4902.9    .035       0  4908.9     .05       0
  5020.7     .16       0    5233     .05       0
Bank Sta=4898.1,5120.3
XS Rating Curve= 0 ,0
Exp/Cntr=0.3,0.1

Type RM Length L Ch R = 1 ,3573    ,28,28,28
BEGIN DESCRIPTION:
Mapping XS 2d52bd13
END DESCRIPTION:
XS GIS Cut Line= 6
      3577775.48      10631084.2      3577997.79     10630770.51
      3578053.78     10630671.56       3578068.1      10630635.1
      3578095.45     10630545.25      3578100.65     10630159.85
#Sta/Elev= 30
    4447  396.37  4531.8  394.68  4552.7  393.69  4611.3  392.99  4668.4  390.77
    4704  389.95  4724.9  388.76  4775.4  386.83  4782.8  385.86  4790.2  385.58
  4796.3  385.96    4802  384.65  4804.7  384.15    4808  384.65  4882.4  384.65
  4898.1  384.65  4906.4  384.97  4945.2  384.65  4949.7  385.92  4957.4  384.65
  5193.3  384.65  5203.3  385.06  5213.3   386.4  5223.3  386.68  5233.3  387.78
  5283.3  389.67  5363.3  393.97  5393.4  394.72  5433.4  397.24  5463.7  398.56
#Mann= 5 ,-1 , 0
    4447     .05       0    4802    .035       0    4808     .05       0
  4882.4     .16       0  4898.1     .05       0
Bank Sta=4796.3,5213.3
XS Rating Curve= 0 ,0
Exp/Cntr=0.3,0.1

Type RM Length L Ch R = 1 ,3545    ,46,46,46
BEGIN DESCRIPTION:
Mapping XS b3343f05
END DESCRIPTION:
XS GIS Cut Line= 6
      3577813.67     10631096.36      3578036.85      10630762.7
      3578090.24     10630657.23      3578113.68     10630583.01
      3578125.39     10630504.89      3578159.25     10630175.48
#Sta/Elev= 30
  4448.1  395.72  4455.7  394.97  4650.8  390.67  4734.9  387.75  4737.7  387.25
  4740.9  387.75    4820  390.09    4840  390.43    4846  389.64  4862.3  390.47
  4884.6   390.3  4890.2  389.56  4904.4  390.22  4929.2  390.25  4934.8  388.91
    4942  389.91  4951.4  390.16    4957  389.28  4963.3  390.26  4981.3  390.52
  4986.5  389.46  5013.6  390.46  5048.7  390.81  5052.7  389.28  5078.7  390.54
  5116.7  389.42  5149.4  390.15  5205.2     389  5249.9  388.64  5455.7   397.8
#Mann= 6 ,-1 , 0
  4448.1     .05       0  4734.9    .035       0  4740.9     .05       0
    4820     .16       0  4904.4     .05       0  5205.2     .16       0
Bank Sta=4981.3,5013.6
XS Rating Curve= 0 ,0
Exp/Cntr=0.3,0.1

Type RM Length L Ch R = 1 ,3499    ,465,465,465
BEGIN DESCRIPTION:
UNT208 IN CCTC 6.0
END DESCRIPTION:
XS GIS Cut Line= 5
      3577858.81      10631103.3      3578090.24     10630756.19
      3578141.02     10630655.93      3578152.74     10630602.54
      3578230.87     10630128.57
#Sta/Elev= 30
    4451   393.8  4770.6  384.74  4801.7  384.88  4836.7  383.72  4842.7  382.25
  4873.6  382.31  4879.2  380.21  4913.6  380.53  4918.1  380.91  4923.7  378.65
    4941  379.69    4946  378.59  4962.7  379.46  4968.3  377.67  4994.4  379.14
  4996.6  377.66  4999.3  377.16  5002.6  377.66  5018.3  378.66  5027.4  378.97
  5044.7  380.37  5049.8  378.65  5128.8  383.69  5250.4  388.85  5289.3  388.31
  5294.4  390.54  5321.4  392.45  5350.4  390.79  5355.5  393.56  5515.6  400.65
#Mann= 7 ,-1 , 0
    4451     .05       0  4801.7     .16       0  4913.6     .05       0
    4941     .07       0  4996.6     .07       0  5002.6     .07       0
  5018.3     .16       0
Bank Sta=4994.4,5027.4
XS Rating Curve= 0 ,0
Exp/Cntr=0.3,0.1

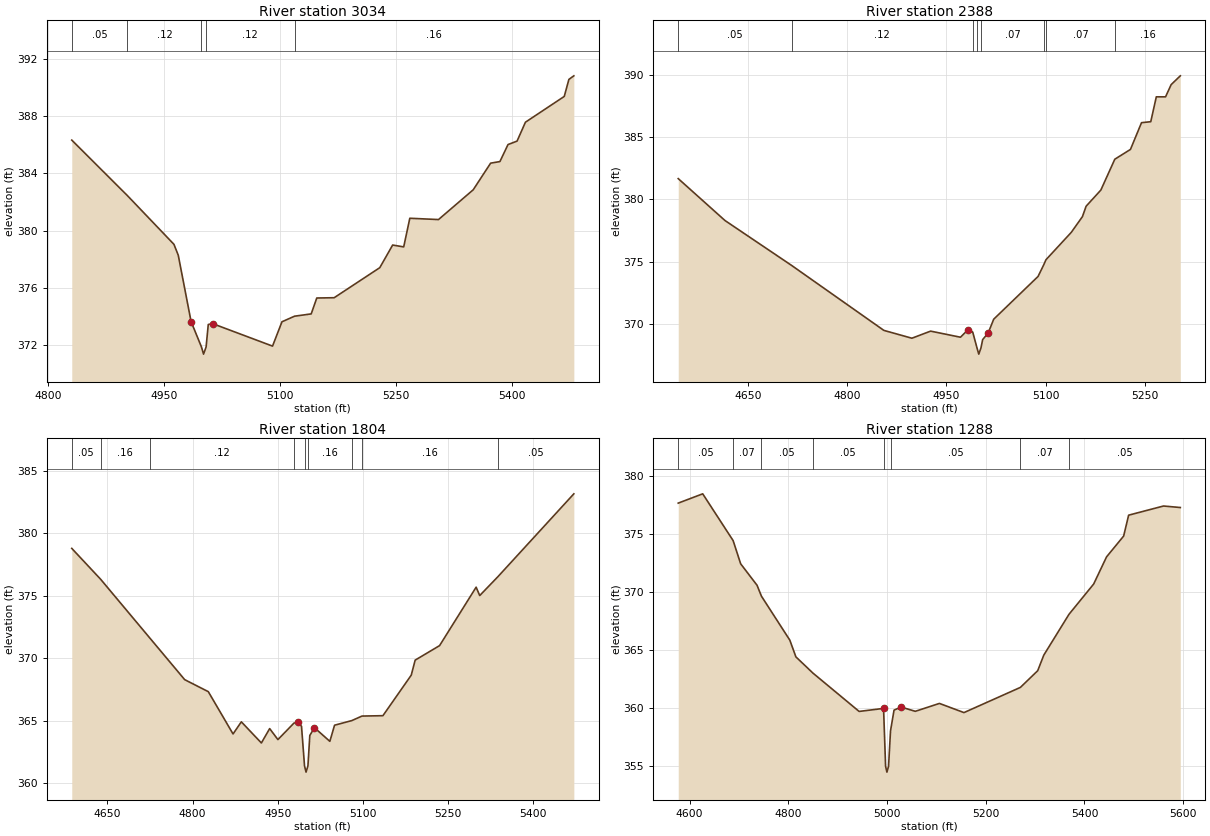
Type RM Length L Ch R = 1 ,3034    ,646,646,646
BEGIN DESCRIPTION:
UNT208 IN CCTC 5.0
END DESCRIPTION:
XS GIS Cut Line= 2
      3578283.91       10631082.      3578580.47      10630504.5
#Sta/Elev= 30
    4831  386.33    4903  382.45  4963.1  379.05  4968.7  378.29  4985.3  373.65
  4998.7  371.88  5001.4  371.38  5004.7  371.88  5007.5  373.45  5013.1  373.51
  5090.6  371.94  5102.8  373.64  5119.1  374.03  5140.6  374.19  5147.8   375.3
  5170.3  375.32  5229.3  377.42  5245.9     379  5260.2  378.87  5268.1  380.87
  5305.2  380.78  5350.1  382.86  5372.6  384.72  5384.6  384.83  5395.1  386.02
  5406.8  386.26  5417.6  387.58  5467.8  389.38  5473.8  390.57  5480.2  390.82
#Mann= 5 ,-1 , 0
    4831     .05       0    4903     .12       0  4998.7     .07       0
  5004.7     .12       0  5119.1     .16       0
Bank Sta=4985.3,5013.1
XS Rating Curve= 0 ,0
Exp/Cntr=0.3,0.1

Type RM Length L Ch R = 1 ,2388    ,584,584,584
BEGIN DESCRIPTION:
UNT208 IN CCTC 4.0
END DESCRIPTION:
XS GIS Cut Line= 3
      3578549.64     10631260.16      3578849.61     10630960.19
       3578999.6     10630660.22
#Sta/Elev= 30
  4544.2  381.67  4614.9   378.3  4715.9  374.68  4855.3  369.46  4897.7  368.83
    4926   369.4  4971.2  368.91  4982.4   369.5  4989.7  369.33  4996.2  368.05
  4998.9  367.55  5002.2  368.05  5004.8  368.72  5013.1  369.25  5021.5  370.36
  5088.6   373.8  5097.2  374.74  5100.5  375.14  5138.9  377.35  5155.7  378.61
  5161.3  379.45  5183.6  380.75  5204.7  383.23  5228.4  384.02  5245.1  386.17
  5259.1  386.25  5267.5  388.25  5281.5  388.25  5289.9  389.23  5303.8  389.94
#Mann= 8 ,-1 , 0
  4544.2     .05       0  4715.9     .12       0  4989.7     .07       0
  4996.2     .07       0  5002.2     .07       0  5097.2     .05       0
  5100.5     .07       0  5204.7     .16       0
Bank Sta=4982.4,5013.1
XS Rating Curve= 0 ,0
Exp/Cntr=0.3,0.1

Type RM Length L Ch R = 1 ,1804    ,516,516,516
BEGIN DESCRIPTION:
UNT208 IN CCTC 3.0
END DESCRIPTION:
XS GIS Cut Line= 2
      3578992.28     10631561.11      3579528.74     10630857.99
#Sta/Elev= 30
  4587.2  378.78  4638.1  376.31    4725   371.6  4786.1  368.29  4827.7  367.33
  4871.3  363.95  4885.9  364.92  4921.2  363.23  4935.8  364.38  4950.3   363.5
  4978.6  364.82  4985.6  364.89  4991.9  364.56  4997.2   361.4  4999.9   360.9
  5003.2   361.4  5006.5  363.83  5014.7  364.45  5041.8  363.36  5050.1  364.65
  5080.6  365.02  5098.4  365.38  5135.3  365.41  5185.2  368.65  5192.1  369.85
  5235.1  371.01  5299.5  375.68  5305.8  375.01  5337.9  376.52  5471.6  383.14
#Mann= 9 ,-1 , 0
  4587.2     .05       0  4638.1     .16       0    4725     .12       0
  4978.6     .16       0  4997.2     .07       0  5003.2     .16       0
  5080.6     .12       0  5098.4     .16       0  5337.9     .05       0
Bank Sta=4985.6,5014.7
XS Rating Curve= 0 ,0
Exp/Cntr=0.3,0.1

Type RM Length L Ch R = 1 ,1288    ,0,0,0
BEGIN DESCRIPTION:
UNT208 IN CCTC 2.0
END DESCRIPTION:
XS GIS Cut Line= 4
      3579211.04      10631670.5      3579544.35     10631571.54
       3579638.1     10631477.79      3579716.22     10630946.58
#Sta/Elev= 30
    4577  377.65  4626.6  378.45  4688.2  374.42  4703.5  372.42  4736.7  370.57
  4745.6  369.63  4803.1  365.84  4815.4   364.4    4850     363  4943.5   359.7
    4993  359.96  4997.1  354.97  4999.8  354.47  5003.1  354.97  5007.1  358.03
  5014.2  359.81  5028.4  360.08  5057.3  359.71  5106.2  360.39  5155.9   359.6
  5270.2  361.77  5305.3  363.21  5317.6  364.55  5368.7  368.07  5418.7  370.68
  5444.8  373.02  5479.4  374.81  5489.5  376.61  5560.2   377.4  5594.2  377.27
#Mann= 8 ,-1 , 0
    4577     .05       0  4688.2     .07       0  4745.6     .05       0
    4850     .05       0    4993     .03       0  5007.1     .05       0
  5270.2     .07       0  5368.7     .05       0
Bank Sta=4993,5028.4
XS Rating Curve= 0 ,0
Exp/Cntr=0.3,0.1

Chan Stop Cuts=-1
Use User Specified Reach Order=0
Composite Channel Slope=5