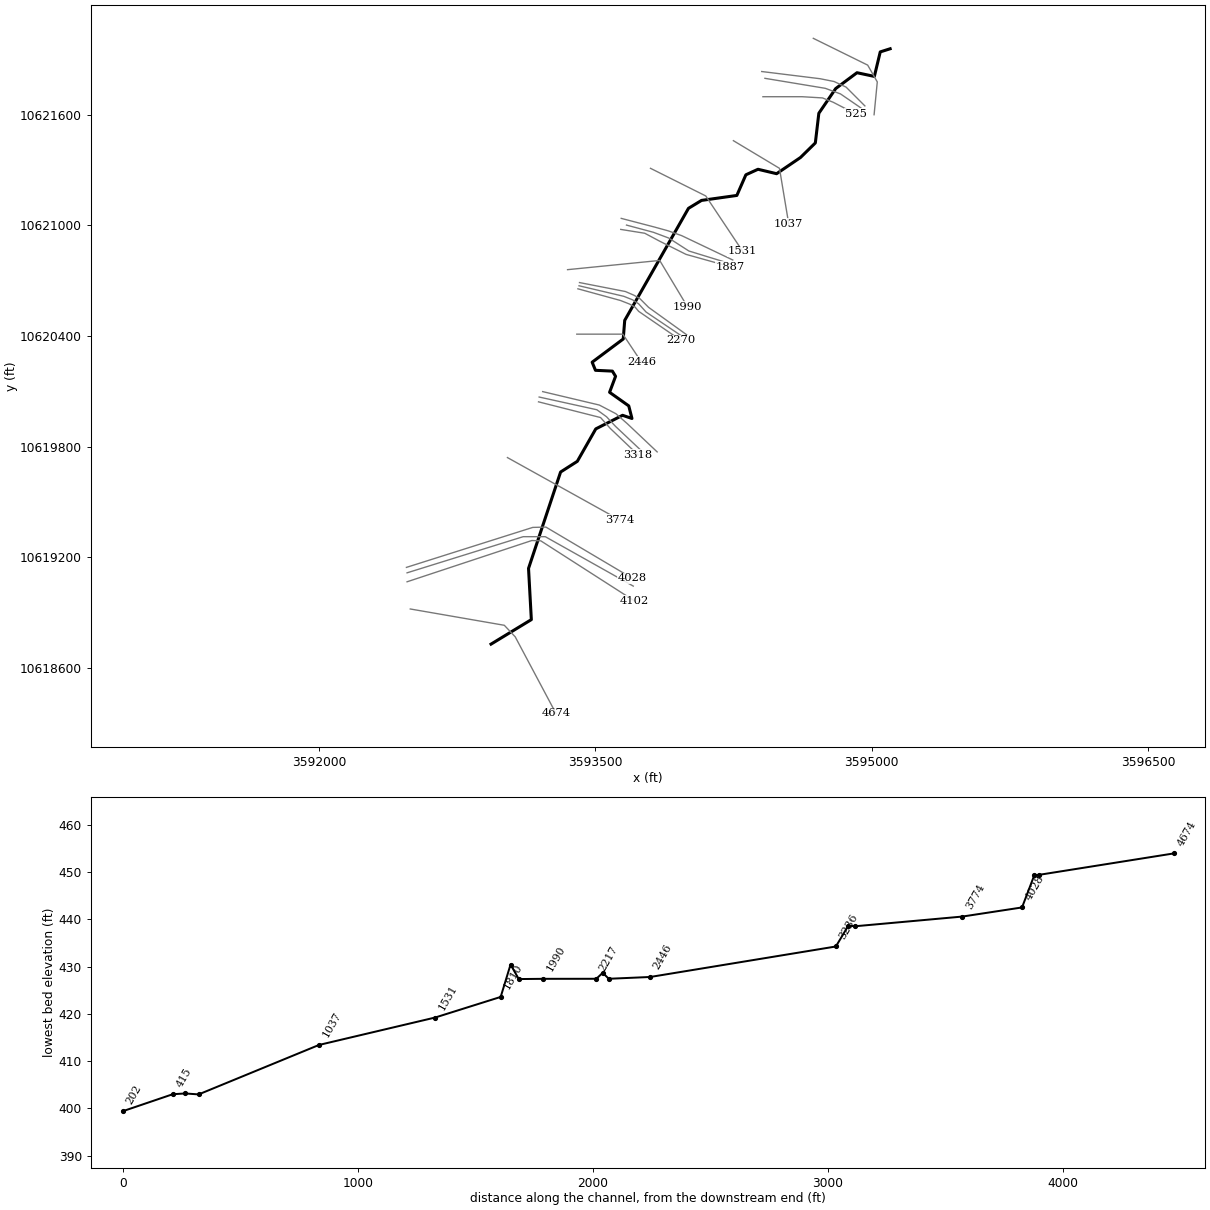
--- UNT210 IN CCTC.prj (project) ---

Proj Title=UNT210 IN CCTC Base Level Engineering
Current Plan=p01
Default Exp/Contr=0.3,0.1
English Units
Geom File=g01
Flow File=f01
Plan File=p01
BEGIN DESCRIPTION:
UNT210 IN CCTC
END DESCRIPTION:

--- UNT210 IN CCTC.p01 (plan) ---

Plan Title=Multiple Run
Short Identifier=Multiple
Geom File=g01
Flow File=f01
Subcritical Flow
K Sum by GR= 0
Std Step Tol= 0.01
Critical Tol= 0.01
Num of Std Step Trials= 20
Max Error Tol= 0.3
Flow Tol Ratio= 0.001
Split Flow NTrial= 30
Split Flow Tol= 0.02
Split Flow Ratio= 0.02
Log Output Level= 0
Friction Slope Method= 1
Unsteady Friction Slope Method= 2
Unsteady Bridges Friction Slope Method= 1
Parabolic Critical Depth
Global Vel Dist=  1 , 1 , 1
Global Log Level= 0
CheckData=True
Encroach Param= -1, 0, 0, 0
BEGIN DESCRIPTION:
Multiple Run
END DESCRIPTION:

--- UNT210 IN CCTC.f01 (steady flow) ---

Flow Title=Multiple
Number of Profiles=7
Profile Names=10-year,25-year,50-year,1pct_min,100-year,1pct_plu,500-year
River Rch & RM= UNT210 IN CCTC,Reach-1,4674
     496     638     748     643     870    1176    1168
Boundary for River Rch & Prof#=UNT210 IN CCTC,Reach-1,1
Up Type=0
Dn Type=3
Dn Slope=0.005
Boundary for River Rch & Prof#=UNT210 IN CCTC,Reach-1,2
Up Type=0
Dn Type=3
Dn Slope=0.005
Boundary for River Rch & Prof#=UNT210 IN CCTC,Reach-1,3
Up Type=0
Dn Type=3
Dn Slope=0.005
Boundary for River Rch & Prof#=UNT210 IN CCTC,Reach-1,4
Up Type=0
Dn Type=3
Dn Slope=0.005
Boundary for River Rch & Prof#=UNT210 IN CCTC,Reach-1,5
Up Type=0
Dn Type=3
Dn Slope=0.005
Boundary for River Rch & Prof#=UNT210 IN CCTC,Reach-1,6
Up Type=0
Dn Type=3
Dn Slope=0.005
Boundary for River Rch & Prof#=UNT210 IN CCTC,Reach-1,7
Up Type=0
Dn Type=3
Dn Slope=0.005

--- UNT210 IN CCTC.g01 (geometry) ---

Geom Title=Existing Conditions

River Reach=UNT210 IN CCTC,Reach-1
Reach XY= 30
      3592934.25     10618728.00      3593153.00     10618861.00
      3593137.75     10619139.00      3593311.75     10619662.00
      3593402.50     10619720.00      3593502.71     10619896.04
      3593648.11     10619969.82      3593699.11     10619952.46
      3593681.74     10620020.82      3593577.58     10620094.60
      3593610.13     10620181.41      3593592.77     10620209.62
      3593501.00     10620214.00      3593483.00     10620258.00
      3593651.75     10620384.00      3593659.75     10620485.00
      3594005.75     10621093.00      3594076.50     10621136.00
      3594268.25     10621163.00      3594317.25     10621275.00
      3594383.00     10621305.00      3594484.00     10621281.00
      3594613.75     10621369.00      3594694.25     10621448.00
      3594713.25     10621609.00      3594804.75     10621743.00
      3594920.25     10621829.00      3595014.50     10621809.00
      3595046.50     10621942.00      3595100.25     10621959.00

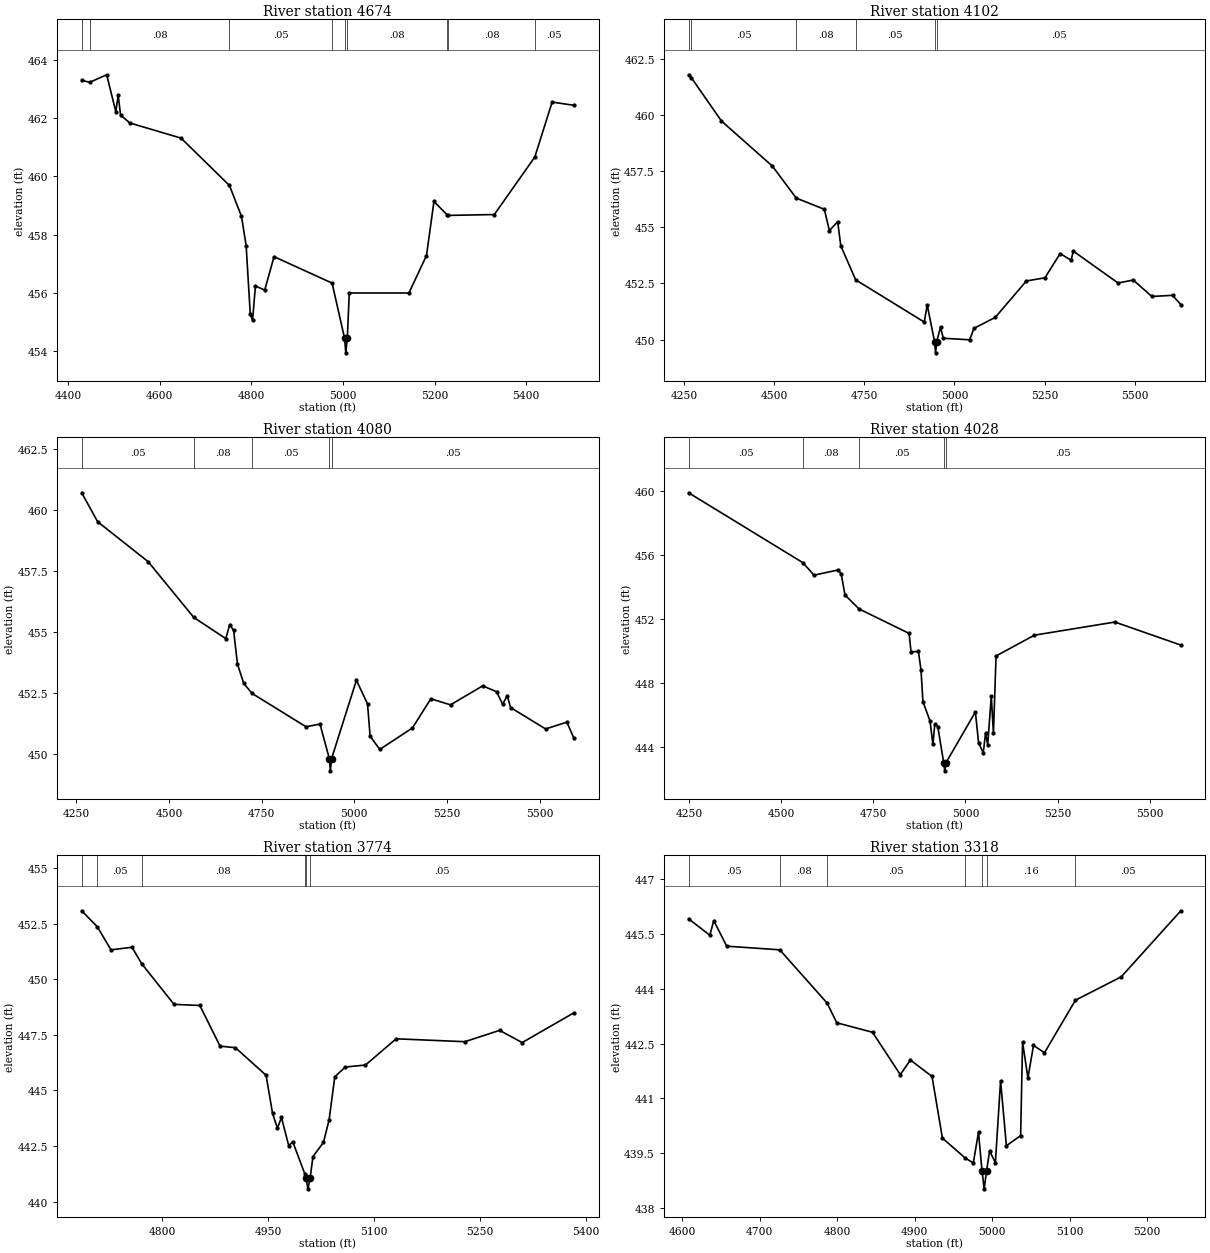
Type RM Length L Ch R = 1,4674,572,572,572
BEGIN DESCRIPTION:
UNT210 IN CCTC 8.0
END DESCRIPTION:
XS GIS Cut Line= 4
      3592495.92     10618918.75      3593006.36     10618830.21
      3593065.39     10618767.71      3593286.46     10618352.18
#Sta/Elev= 30
  4429.4  463.31  4446.8  463.24  4483.9  463.50  4503.9  462.23  4509.0  462.80
  4514.3  462.11  4534.6  461.84  4646.3  461.32  4752.0  459.69  4778.2  458.63
  4788.4  457.62  4797.4  455.27  4802.4  455.05  4808.7  456.23  4829.0  456.09
  4849.3  457.24  4976.1  456.33  5003.3  454.43  5006.0  453.93  5009.3  454.43
  5013.6  455.99  5143.9  455.99  5182.2  457.28  5198.5  459.14  5227.9  458.67
  5230.2  458.66  5330.3  458.69  5418.7  460.67  5456.5  462.56  5504.1  462.45
#Mann=9,-1,0
  4429.4    0.05       0  4446.8    0.08       0  4752.0    0.05       0
  4976.1    0.08       0  5003.3    0.07       0  5009.3    0.08       0
  5227.9    0.05       0  5230.2    0.08       0  5418.7    0.05       0
Bank Sta=5003.3,5009.3
Exp/Cntr=0.3,0.1

Type RM Length L Ch R = 1,4102,22,22,22
BEGIN DESCRIPTION:
Mapping XS 141a6598
END DESCRIPTION:
XS GIS Cut Line= 4
      3592478.56     10619066.31      3593155.67     10619290.28
      3593204.28     10619288.54      3593712.94     10618962.16
#Sta/Elev= 30
  4262.0  461.79  4270.0  461.65  4353.3  459.73  4494.8  457.72  4560.8  456.30
  4638.8  455.80  4652.8  454.85  4675.8  455.25  4684.4  454.18  4725.7  452.66
  4916.1  450.78  4924.3  451.54  4944.7  449.91  4947.5  449.41  4950.7  449.91
  4961.3  450.56  4968.8  450.06  5042.0  449.99  5054.2  450.50  5113.3  450.99
  5199.6  452.61  5251.1  452.75  5293.4  453.83  5323.8  453.53  5329.7  453.94
  5453.9  452.52  5496.2  452.65  5547.8  451.92  5605.2  451.97  5628.2  451.56
#Mann=6,-1,0
  4262.0    0.08       0  4270.0    0.05       0  4560.8    0.08       0
  4725.7    0.05       0  4944.7    0.03       0  4950.7    0.05       0
Bank Sta=4944.7,4950.7
Exp/Cntr=0.3,0.1

Type RM Length L Ch R = 1,4080,52,52,52
BEGIN DESCRIPTION:
Mapping XS 3b414636
END DESCRIPTION:
XS GIS Cut Line= 4
      3592478.54     10619114.92      3593108.79     10619311.11
      3593228.58     10619311.11      3593706.15     10619042.91
#Sta/Elev= 30
  4264.6  460.71  4307.6  459.52  4443.8  457.88  4566.9  455.59  4653.2  454.72
  4663.7  455.29  4674.3  455.06  4684.6  453.68  4701.6  452.88  4724.1  452.47
  4869.5  451.10  4907.3  451.21  4932.5  449.79  4935.2  449.29  4938.5  449.79
  5005.5  453.01  5035.5  452.04  5042.5  450.71  5068.6  450.17  5156.6  451.05
  5206.2  452.25  5259.3  452.00  5346.0  452.78  5383.7  452.54  5399.6  452.03
  5412.7  452.37  5421.3  451.89  5515.9  451.01  5573.2  451.29  5592.2  450.63
#Mann=5,-1,0
  4264.6    0.05       0  4566.9    0.08       0  4724.1    0.05       0
  4932.5    0.03       0  4938.5    0.05       0
Bank Sta=4932.5,4938.5
Exp/Cntr=0.3,0.1

Type RM Length L Ch R = 1,4028,254,254,254
BEGIN DESCRIPTION:
Mapping XS 8412810f
END DESCRIPTION:
XS GIS Cut Line= 4
      3592475.12     10619144.45      3593160.87     10619361.46
      3593232.05     10619363.19      3593700.77     10619085.44
#Sta/Elev= 30
  4248.9  459.88  4559.0  455.51  4589.2  454.73  4653.3  455.05  4662.7  454.83
  4673.2  453.49  4711.3  452.62  4847.1  451.09  4852.3  449.94  4872.4  449.96
  4879.4  448.79  4884.6  446.83  4903.9  445.61  4911.7  444.15  4916.9  445.44
  4924.9  445.27  4941.0  443.00  4943.8  442.50  4947.0  443.00  5026.9  446.18
  5035.6  444.26  5048.2  443.62  5054.5  444.85  5060.3  444.14  5070.1  447.15
  5075.9  444.84  5083.0  449.68  5187.1  450.98  5405.4  451.80  5584.2  450.36
#Mann=5,-1,0
  4248.9    0.05       0  4559.0    0.08       0  4711.3    0.05       0
  4941.0    0.03       0  4947.0    0.05       0
Bank Sta=4941,4947
Exp/Cntr=0.3,0.1

Type RM Length L Ch R = 1,3774,456,456,456
BEGIN DESCRIPTION:
UNT210 IN CCTC 7.0
END DESCRIPTION:
XS GIS Cut Line= 2
      3593023.34     10619740.36      3593632.72     10619401.82
#Sta/Elev= 30
  4686.3  453.08  4708.4  452.36  4727.8  451.32  4757.6  451.44  4771.2  450.70
  4817.0  448.87  4853.6  448.82  4882.2  446.99  4904.0  446.92  4947.4  445.68
  4956.6  443.96  4963.5  443.30  4969.2  443.78  4979.5  442.51  4985.2  442.69
  5002.5  441.22  5003.9  441.07  5006.7  440.57  5009.9  441.07  5013.8  442.02
  5028.7  442.66  5036.7  443.68  5044.7  445.61  5059.5  446.05  5088.2  446.14
  5131.6  447.32  5228.9  447.19  5278.1  447.70  5310.1  447.15  5383.4  448.49
#Mann=6,-1,0
  4686.3    0.08       0  4708.4    0.05       0  4771.2    0.08       0
  5002.5    0.05       0  5003.9    0.07       0  5009.9    0.05       0
Bank Sta=5003.9,5009.9
Exp/Cntr=0.3,0.1

Type RM Length L Ch R = 1,3318,29,29,29
BEGIN DESCRIPTION:
Mapping XS a401e188
END DESCRIPTION:
XS GIS Cut Line= 4
      3593191.93     10620042.89      3593528.65     10619957.59
      3593581.42     10619898.56      3593732.60     10619754.29
#Sta/Elev= 30
  4608.0  445.92  4635.4  445.47  4640.5  445.87  4657.2  445.17  4725.7  445.07
  4786.9  443.61  4799.3  443.07  4845.5  442.81  4881.3  441.65  4894.4  442.05
  4922.3  441.60  4935.7  439.91  4965.4  439.36  4975.6  439.23  4982.3  440.07
  4986.8  439.02  4989.6  438.52  4992.8  439.02  4996.6  439.56  5004.1  439.24
  5010.8  441.48  5018.3  439.70  5036.7  439.98  5039.2  442.54  5046.1  441.56
  5053.3  442.45  5067.5  442.25  5107.5  443.69  5166.6  444.33  5243.5  446.14
#Mann=7,-1,0
  4608.0    0.05       0  4725.7    0.08       0  4786.9    0.05       0
  4965.4    0.16       0  4986.8    0.07       0  4992.8    0.16       0
  5107.5    0.05       0
Bank Sta=4986.8,4992.8
Exp/Cntr=0.3,0.1

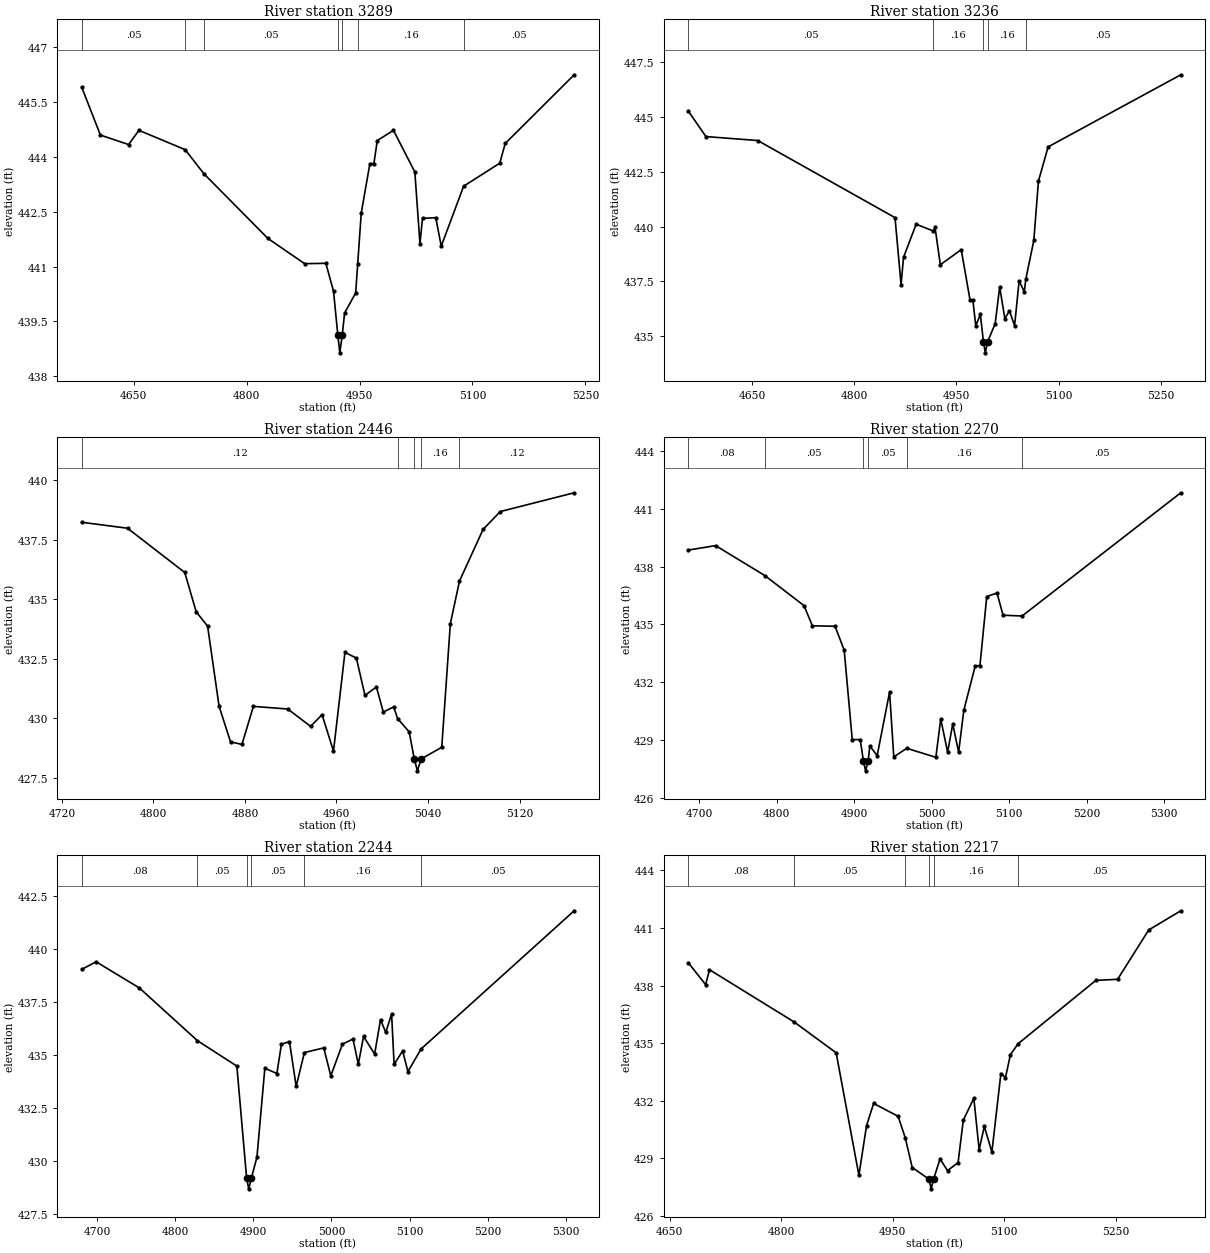
Type RM Length L Ch R = 1,3289,53,53,53
BEGIN DESCRIPTION:
Mapping XS 1866e69f
END DESCRIPTION:
XS GIS Cut Line= 5
      3593195.37     10620068.94      3593508.51     10619999.95
      3593561.28     10619961.76      3593609.20     10619910.37
      3593753.46     10619774.39
#Sta/Elev= 30
  4580.8  445.91  4605.6  444.60  4643.1  444.34  4656.8  444.73  4718.3  444.20
  4743.2  443.54  4828.2  441.77  4877.0  441.08  4905.2  441.09  4915.4  440.32
  4921.0  439.14  4923.7  438.64  4927.0  439.14  4930.1  439.73  4944.8  440.28
  4947.5  441.08  4952.2  442.47  4963.7  443.82  4969.0  443.82  4973.5  444.45
  4995.0  444.73  5023.4  443.59  5030.2  441.63  5033.6  442.32  5051.2  442.34
  5058.5  441.56  5088.2  443.20  5136.2  443.83  5143.5  444.37  5235.1  446.25
#Mann=7,-1,0
  4580.8    0.05       0  4718.3    0.08       0  4743.2    0.05       0
  4921.0    0.07       0  4927.0    0.05       0  4947.5    0.16       0
  5088.2    0.05       0
Bank Sta=4921,4927
Exp/Cntr=0.3,0.1

Type RM Length L Ch R = 1,3236,790,790,790
BEGIN DESCRIPTION:
UNT210 IN CCTC 6.0
END DESCRIPTION:
XS GIS Cut Line= 5
      3593214.46     10620098.45      3593521.75     10620025.54
      3593611.98     10619978.42      3593673.09     10619924.95
      3593835.82     10619771.18
#Sta/Elev= 30
  4556.5  445.27  4582.3  444.11  4658.3  443.93  4859.8  440.41  4868.7  437.35
  4872.3  438.60  4890.8  440.11  4916.1  439.80  4918.5  439.97  4926.3  438.26
  4957.0  438.95  4970.0  436.63  4974.1  436.63  4978.3  435.48  4985.0  435.99
  4989.6  434.74  4992.3  434.24  4995.6  434.74  5006.8  435.57  5013.4  437.25
  5021.0  435.80  5027.7  436.16  5035.3  435.48  5041.9  437.52  5049.5  437.03
  5051.8  437.61  5063.5  439.37  5070.3  442.08  5084.5  443.64  5279.2  446.93
#Mann=5,-1,0
  4556.5    0.05       0  4916.1    0.16       0  4989.6    0.07       0
  4995.6    0.16       0  5051.8    0.05       0
Bank Sta=4989.6,4995.6
Exp/Cntr=0.3,0.1

Type RM Length L Ch R = 1,2446,176,176,176
BEGIN DESCRIPTION:
UNT210 IN CCTC 5.0
END DESCRIPTION:
XS GIS Cut Line= 3
      3593399.59     10620410.19      3593649.61     10620410.19
      3593749.61     10620260.19
#Sta/Elev= 30
  4737.4  438.24  4777.4  437.99  4827.4  436.13  4837.4  434.48  4847.4  433.87
  4857.4  430.51  4867.4  429.01  4877.4  428.90  4887.4  430.50  4917.4  430.39
  4937.4  429.66  4947.4  430.15  4957.4  428.62  4967.4  432.77  4977.4  432.53
  4984.9  430.96  4994.9  431.32  5000.9  430.26  5010.0  430.48  5013.4  429.99
  5023.5  429.43  5028.0  428.29  5030.7  427.79  5034.0  428.29  5052.0  428.78
  5059.5  433.98  5067.5  435.77  5088.1  437.94  5103.1  438.69  5167.7  439.48
#Mann=5,-1,0
  4737.4    0.12       0  5013.4    0.16       0  5028.0    0.07       0
  5034.0    0.16       0  5067.5    0.12       0
Bank Sta=5028,5034
Exp/Cntr=0.3,0.1

Type RM Length L Ch R = 1,2270,26,26,26
BEGIN DESCRIPTION:
Mapping XS eabd68d8
END DESCRIPTION:
XS GIS Cut Line= 6
      3593405.68     10620656.31      3593636.58     10620592.94
      3593685.19     10620573.84      3593715.57     10620557.35
      3593735.53     10620533.91      3593965.09     10620376.26
#Sta/Elev= 30
  4686.1  438.86  4721.3  439.09  4784.7  437.54  4835.3  435.98  4846.2  434.93
  4875.4  434.91  4887.2  433.67  4897.6  429.03  4907.9  429.03  4912.1  427.91
  4914.8  427.41  4918.1  427.91  4920.3  428.70  4929.8  428.20  4945.8  431.50
  4951.2  428.13  4967.9  428.58  5005.5  428.11  5011.8  430.10  5020.7  428.38
  5027.3  429.84  5034.9  428.38  5041.6  430.55  5056.3  432.85  5062.4  432.87
  5071.2  436.45  5084.5  436.63  5092.2  435.48  5116.8  435.44  5321.6  441.83
#Mann=6,-1,0
  4686.1    0.08       0  4784.7    0.05       0  4912.1    0.07       0
  4918.1    0.05       0  4967.9    0.16       0  5116.8    0.05       0
Bank Sta=4912.1,4918.1
Exp/Cntr=0.3,0.1

Type RM Length L Ch R = 1,2244,27,27,27
BEGIN DESCRIPTION:
Mapping XS 9e12515b
END DESCRIPTION:
XS GIS Cut Line= 6
      3593411.72     10620672.81      3593654.80     10620615.51
      3593702.55     10620596.41      3593735.53     10620574.71
      3593775.46     10620530.44      3593965.97     10620402.00
#Sta/Elev= 30
  4680.5  439.04  4698.9  439.40  4754.4  438.16  4828.6  435.67  4879.0  434.47
  4891.5  429.17  4894.2  428.67  4897.5  429.17  4904.7  430.17  4914.8  434.37
  4930.2  434.12  4936.0  435.50  4946.3  435.63  4954.9  433.51  4965.4  435.11
  4990.2  435.33  4999.2  434.01  5014.1  435.51  5027.6  435.75  5034.4  434.56
  5041.1  435.87  5055.3  435.04  5062.8  436.67  5069.5  436.06  5077.0  436.93
  5080.2  434.55  5091.1  435.19  5097.9  434.21  5114.7  435.28  5310.6  441.81
#Mann=6,-1,0
  4680.5    0.08       0  4828.6    0.05       0  4891.5    0.07       0
  4897.5    0.05       0  4965.4    0.16       0  5114.7    0.05       0
Bank Sta=4891.5,4897.5
Exp/Cntr=0.3,0.1

Type RM Length L Ch R = 1,2217,227,227,227
BEGIN DESCRIPTION:
Mapping XS 0c288e9f
END DESCRIPTION:
XS GIS Cut Line= 6
      3593414.38     10620690.16      3593663.49     10620641.55
      3593709.49     10620621.59      3593740.74     10620604.23
      3593789.35     10620555.62      3593995.72     10620407.10
#Sta/Elev= 30
  4674.9  439.19  4698.2  438.05  4703.3  438.83  4817.5  436.10  4873.8  434.50
  4904.4  428.12  4914.7  430.70  4924.2  431.86  4957.2  431.19  4966.7  430.08
  4976.2  428.52  4998.9  427.91  5001.6  427.41  5004.9  427.91  5013.6  428.97
  5023.7  428.36  5037.9  428.78  5044.9  430.99  5059.1  432.13  5066.2  429.46
  5073.2  430.66  5083.4  429.33  5095.5  433.42  5101.7  433.21  5108.3  434.40
  5118.6  434.97  5223.2  438.27  5252.6  438.33  5294.4  440.90  5337.6  441.90
#Mann=6,-1,0
  4674.9    0.08       0  4817.5    0.05       0  4966.7    0.16       0
  4998.9    0.07       0  5004.9    0.16       0  5118.6    0.05       0
Bank Sta=4998.9,5004.9
Exp/Cntr=0.3,0.1

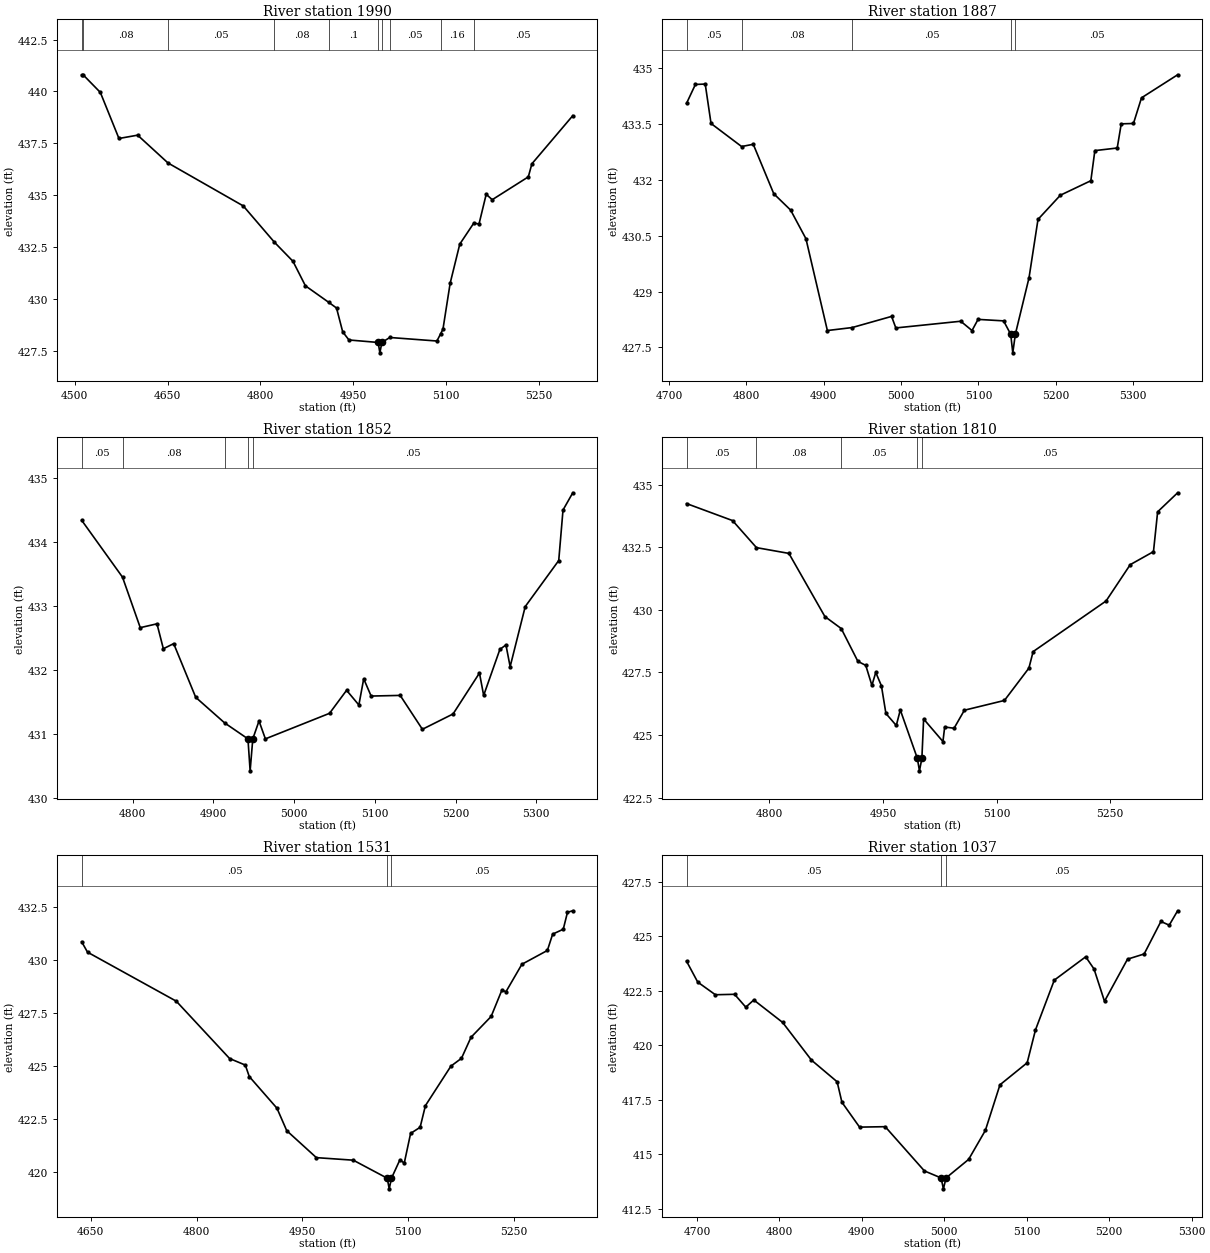
Type RM Length L Ch R = 1,1990,103,103,103
BEGIN DESCRIPTION:
UNT210 IN CCTC 4.0
END DESCRIPTION:
XS GIS Cut Line= 3
      3593349.58     10620760.19      3593849.61     10620810.19
      3593999.62     10620560.17
#Sta/Elev= 30
  4511.2  440.80  4513.5  440.80  4541.4  439.95  4571.5  437.73  4601.7  437.89
  4650.8  436.55  4772.5  434.48  4822.9  432.73  4852.9  431.81  4873.0  430.63
  4910.4  429.84  4923.3  429.56  4933.3  428.41  4943.4  428.02  4990.6  427.90
  4993.4  427.40  4996.6  427.90  5009.4  428.14  5085.6  427.97  5091.5  428.31
  5095.4  428.54  5107.0  430.75  5122.6  432.64  5145.2  433.65  5153.7  433.61
  5165.3  435.04  5175.1  434.78  5233.4  435.88  5239.2  436.51  5305.3  438.83
#Mann=10,-1,0
  4511.2    0.05       0  4513.5    0.08       0  4650.8    0.05       0
  4822.9    0.08       0  4910.4     0.1       0  4990.6    0.07       0
  4996.6     0.1       0  5009.4    0.05       0  5091.5    0.16       0
  5145.2    0.05       0
Bank Sta=4990.6,4996.6
Exp/Cntr=0.3,0.1

Type RM Length L Ch R = 1,1887,35,35,35
BEGIN DESCRIPTION:
Mapping XS cd69191f
END DESCRIPTION:
XS GIS Cut Line= 5
      3593638.26     10620978.63      3593768.42     10620957.81
      3593851.75     10620913.54      3593992.38     10620843.22
      3594234.59     10620775.51
#Sta/Elev= 30
  4722.6  434.06  4734.1  434.57  4746.8  434.58  4754.3  433.52  4793.8  432.90
  4808.9  432.96  4835.4  431.63  4857.2  431.19  4877.0  430.42  4904.7  427.95
  4936.7  428.03  4987.7  428.33  4993.2  428.02  5077.1  428.20  5091.7  427.95
  5099.5  428.25  5132.5  428.21  5141.7  427.85  5144.4  427.35  5147.7  427.85
  5165.4  429.37  5177.0  430.94  5205.9  431.59  5245.3  431.98  5250.5  432.79
  5279.4  432.86  5284.6  433.51  5300.4  433.52  5310.8  434.21  5357.5  434.83
#Mann=5,-1,0
  4722.6    0.05       0  4793.8    0.08       0  4936.7    0.05       0
  5141.7    0.03       0  5147.7    0.05       0
Bank Sta=5141.7,5147.7
Exp/Cntr=0.3,0.1

Type RM Length L Ch R = 1,1852,42,42,42
BEGIN DESCRIPTION:
Mapping XS a4e751ec
END DESCRIPTION:
XS GIS Cut Line= 5
      3593669.45     10621002.08      3593815.29     10620963.02
      3593898.63     10620931.77      3594008.00     10620861.45
      3594235.90     10620791.53
#Sta/Elev= 30
  4736.8  434.34  4787.4  433.45  4809.4  432.66  4830.1  432.72  4838.0  432.33
  4850.8  432.41  4878.1  431.57  4913.9  431.17  4942.8  430.92  4945.5  430.42
  4948.8  430.92  4956.5  431.20  4964.4  430.92  5043.9  431.32  5065.0  431.68
  5080.2  431.45  5086.2  431.86  5095.4  431.59  5131.4  431.60  5158.9  431.07
  5196.9  431.31  5229.6  431.95  5234.8  431.60  5254.9  432.32  5262.4  432.39
  5267.6  432.05  5286.3  432.99  5327.8  433.71  5333.1  434.50  5345.2  434.77
#Mann=5,-1,0
  4736.8    0.05       0  4787.4    0.08       0  4913.9    0.05       0
  4942.8    0.03       0  4948.8    0.05       0
Bank Sta=4942.8,4948.8
Exp/Cntr=0.3,0.1

Type RM Length L Ch R = 1,1810,279,279,279
BEGIN DESCRIPTION:
Mapping XS 5c10d8c9
END DESCRIPTION:
XS GIS Cut Line= 5
      3593640.79     10621038.54      3593820.50     10620991.66
      3593896.02     10620970.83      3593968.94     10620944.79
      3594246.07     10620812.69
#Sta/Elev= 30
  4690.6  434.24  4751.4  433.56  4783.0  432.48  4825.8  432.25  4873.3  429.73
  4894.9  429.25  4916.9  427.94  4927.3  427.78  4935.4  426.98  4940.5  427.50
  4948.0  426.96  4953.9  425.86  4967.6  425.38  4972.9  426.00  4995.4  424.07
  4998.2  423.57  5001.4  424.07  5003.7  425.64  5029.2  424.74  5031.5  425.32
  5043.9  425.27  5057.5  425.99  5110.4  426.38  5142.7  427.67  5148.3  428.33
  5244.6  430.35  5276.5  431.80  5307.2  432.32  5312.7  433.91  5339.1  434.67
#Mann=5,-1,0
  4690.6    0.05       0  4783.0    0.08       0  4894.9    0.05       0
  4995.4    0.03       0  5001.4    0.05       0
Bank Sta=4995.4,5001.4
Exp/Cntr=0.3,0.1

Type RM Length L Ch R = 1,1531,494,494,494
BEGIN DESCRIPTION:
UNT210 IN CCTC 3.0
END DESCRIPTION:
XS GIS Cut Line= 3
      3593799.65     10621310.17      3594099.61     10621160.19
      3594299.60     10620860.21
#Sta/Elev= 30
  4637.2  430.85  4645.5  430.36  4771.3  428.05  4846.8  425.35  4869.1  425.04
  4874.7  424.50  4913.9  423.01  4927.8  421.95  4969.8  420.68  5022.1  420.56
  5070.2  419.71  5073.0  419.21  5076.2  419.71  5088.2  420.58  5094.3  420.42
  5103.3  421.82  5116.8  422.11  5124.3  423.13  5160.4  424.99  5175.4  425.36
  5188.9  426.35  5217.4  427.33  5232.5  428.56  5238.5  428.50  5261.0  429.79
  5297.1  430.44  5304.6  431.21  5319.6  431.44  5325.6  432.24  5333.1  432.31
#Mann=3,-1,0
  4637.2    0.05       0  5070.2    0.03       0  5076.2    0.05       0
Bank Sta=5070.2,5076.2
Exp/Cntr=0.3,0.1

Type RM Length L Ch R = 1,1037,512,512,512
BEGIN DESCRIPTION:
UNT210 IN CCTC 2.0
END DESCRIPTION:
XS GIS Cut Line= 3
      3594249.62     10621460.18      3594499.61     10621310.19
      3594549.61     10621010.17
#Sta/Elev= 30
  4687.3  423.85  4700.9  422.89  4722.3  422.31  4745.6  422.33  4759.2  421.74
  4768.9  422.07  4803.9  421.04  4838.9  419.31  4870.0  418.32  4875.8  417.38
  4897.2  416.24  4928.3  416.26  4975.9  414.23  4996.1  413.91  4998.9  413.41
  5002.1  413.91  5029.5  414.76  5049.8  416.09  5067.5  418.18  5100.5  419.19
  5110.6  420.70  5133.4  422.98  5171.5  424.05  5181.6  423.49  5194.3  422.01
  5222.2  423.94  5242.4  424.18  5262.7  425.67  5272.8  425.50  5283.0  426.16
#Mann=3,-1,0
  4687.3    0.05       0  4996.1    0.03       0  5002.1    0.05       0
Bank Sta=4996.1,5002.1
Exp/Cntr=0.3,0.1

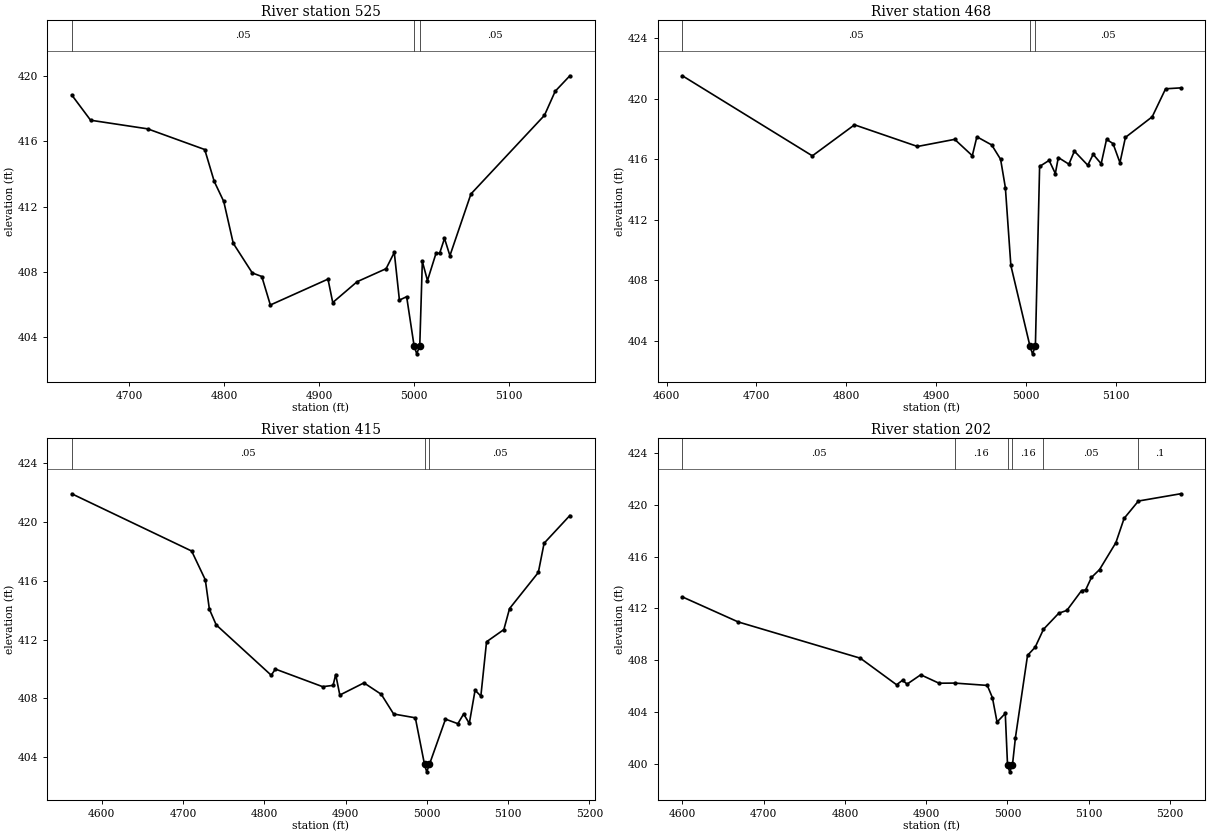
Type RM Length L Ch R = 1,525,57,57,57
BEGIN DESCRIPTION:
Mapping XS 3cf4ec83
END DESCRIPTION:
XS GIS Cut Line= 5
      3594409.77     10621698.78      3594622.46     10621698.78
      3594733.13     10621692.27      3594791.73     10621668.40
      3594913.28     10621605.45
#Sta/Elev= 30
  4639.9  418.85  4659.7  417.30  4719.7  416.77  4779.7  415.50  4789.7  413.54
  4799.7  412.31  4809.7  409.74  4829.7  407.92  4839.7  407.70  4848.7  405.95
  4909.3  407.54  4914.3  406.10  4939.9  407.38  4970.4  408.18  4979.0  409.18
  4984.4  406.25  4992.0  406.46  4999.8  403.45  5002.6  402.95  5005.8  403.45
  5008.5  408.63  5013.9  407.45  5022.9  409.13  5026.7  409.13  5031.8  410.04
  5037.5  408.98  5059.6  412.77  5136.9  417.60  5148.2  419.08  5163.6  420.03
#Mann=3,-1,0
  4639.9    0.05       0  4999.8   0.035       0  5005.8    0.05       0
Bank Sta=4999.8,5005.8
Exp/Cntr=0.3,0.1

Type RM Length L Ch R = 1,468,53,53,53
BEGIN DESCRIPTION:
Mapping XS 35921aa4
END DESCRIPTION:
XS GIS Cut Line= 4
      3594420.64     10621798.60      3594748.32     10621744.35
      3594830.79     10621713.97      3594941.50     10621637.99
#Sta/Elev= 30
  4617.7  421.52  4762.3  416.23  4809.2  418.28  4879.3  416.85  4920.7  417.32
  4940.3  416.24  4945.4  417.49  4961.9  416.95  4971.8  416.00  4977.1  414.13
  4983.2  408.99  5004.5  403.65  5007.3  403.15  5010.5  403.65  5015.2  415.53
  5025.8  415.93  5032.7  415.06  5036.0  416.12  5047.8  415.68  5053.9  416.54
  5068.8  415.61  5074.8  416.33  5083.7  415.71  5089.7  417.32  5096.9  417.04
  5104.6  415.78  5110.7  417.45  5140.5  418.81  5155.4  420.66  5172.0  420.72
#Mann=3,-1,0
  4617.7    0.05       0  5004.5   0.035       0  5010.5    0.05       0
Bank Sta=5004.5,5010.5
Exp/Cntr=0.3,0.1

Type RM Length L Ch R = 1,415,213,213,213
BEGIN DESCRIPTION:
Mapping XS 2f0b27e2
END DESCRIPTION:
XS GIS Cut Line= 5
      3594403.27     10621835.50      3594720.11     10621796.44
      3594796.07     10621781.24      3594861.17     10621750.86
      3594963.17     10621648.86
#Sta/Elev= 30
  4563.1  421.93  4710.6  418.03  4727.4  416.07  4732.4  414.07  4740.8  413.00
  4808.5  409.57  4813.6  409.99  4871.8  408.79  4884.6  408.88  4887.8  409.62
  4892.9  408.22  4922.6  409.05  4943.9  408.27  4959.1  406.93  4985.8  406.67
  4997.1  403.49  4999.8  402.99  5003.1  403.49  5022.9  406.58  5038.1  406.27
  5045.2  406.93  5052.2  406.29  5059.3  408.55  5066.4  408.15  5073.4  411.85
  5094.7  412.68  5101.7  414.11  5137.1  416.57  5144.2  418.56  5175.9  420.45
#Mann=3,-1,0
  4563.1    0.05       0  4997.1   0.035       0  5003.1    0.05       0
Bank Sta=4997.1,5003.1
Exp/Cntr=0.3,0.1

Type RM Length L Ch R = 1,202,0,0,0
BEGIN DESCRIPTION:
UNT210 IN CCTC 1.0
END DESCRIPTION:
XS GIS Cut Line= 4
      3594683.23     10622015.61      3594978.36     10621870.22
      3595030.44     10621779.07      3595013.08     10621601.09
#Sta/Elev= 30
  4600.1  412.89  4668.7  410.96  4819.0  408.16  4863.6  406.11  4870.9  406.46
  4876.5  406.16  4893.3  406.88  4915.8  406.23  4935.0  406.24  4975.2  406.06
  4981.5  405.11  4987.2  403.23  4997.3  403.90  5000.1  399.89  5002.8  399.39
  5006.1  399.89  5009.8  402.03  5024.7  408.38  5034.1  409.01  5044.3  410.39
  5063.1  411.63  5073.1  411.85  5091.2  413.38  5096.2  413.43  5103.3  414.39
  5113.3  415.00  5133.4  417.08  5143.5  418.95  5161.1  420.29  5212.9  420.85
#Mann=6,-1,0
  4600.1    0.05       0  4935.0    0.16       0  5000.1    0.07       0
  5006.1    0.16       0  5044.3    0.05       0  5161.1     0.1       0
Bank Sta=5000.1,5006.1
Exp/Cntr=0.3,0.1

Chan Stop Cuts=-1