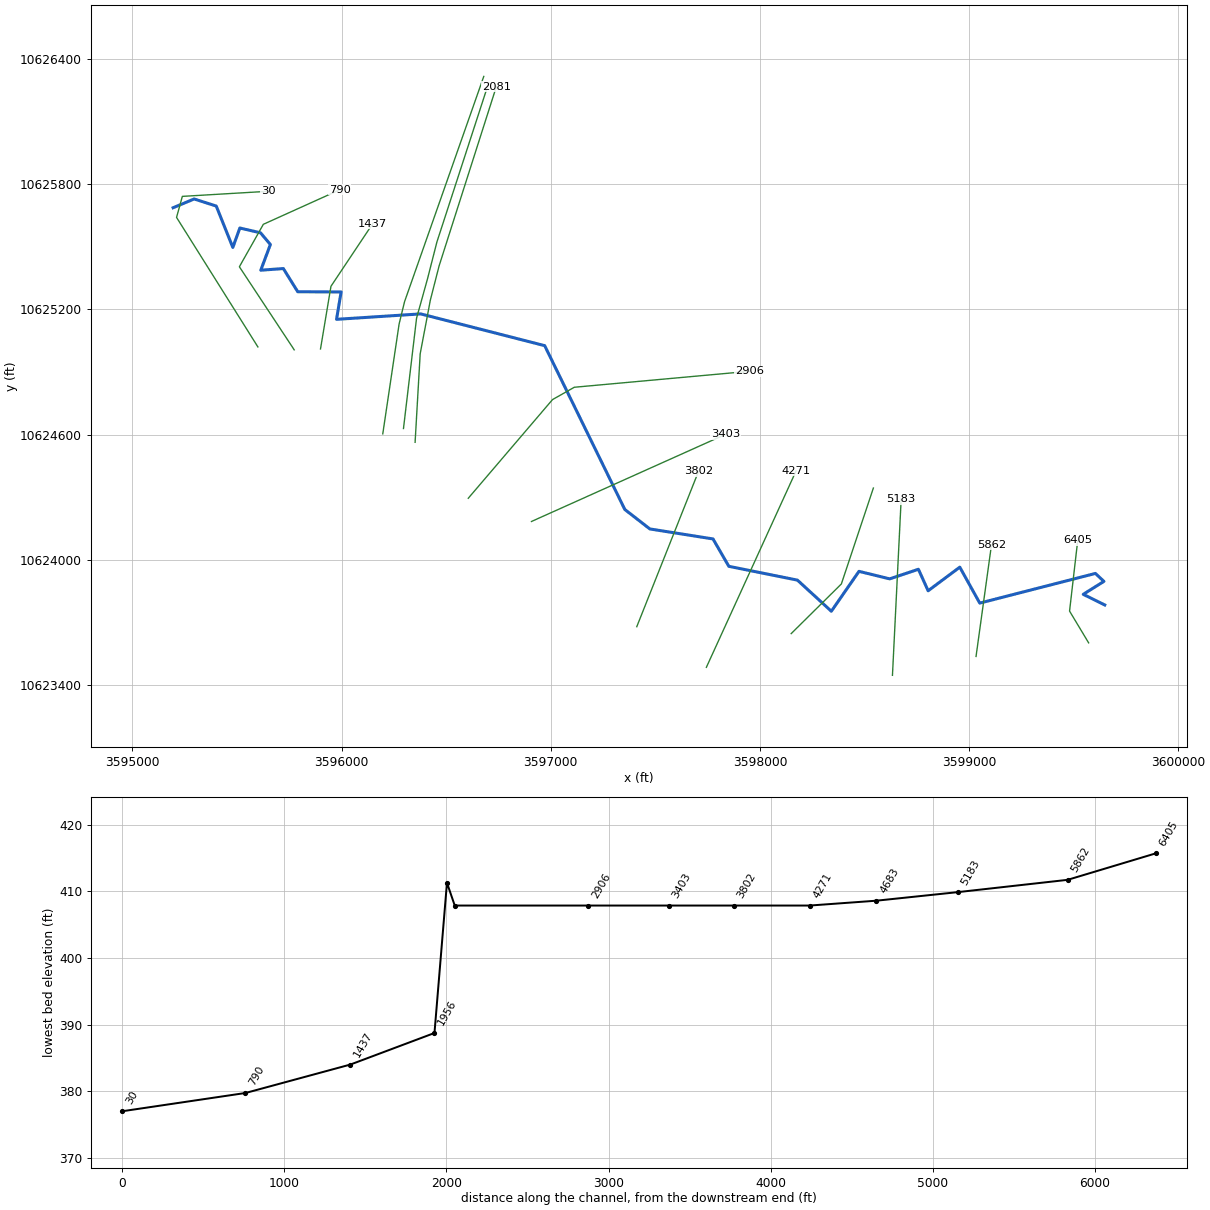
--- UNT211 IN CCTC.prj (project) ---

Proj Title=UNT211 IN CCTC Base Level Engineering
Current Plan=p01
Default Exp/Contr=0.3,0.1
English Units
Geom File=g01
Flow File=f01
Plan File=p01
Y Axis Title=Elevation
X Axis Title(PF)=Main Channel Distance
X Axis Title(XS)=Station
BEGIN DESCRIPTION:
UNT211 IN CCTC
END DESCRIPTION:
DSS Export Rating Curves= 0
DSS Export Rating Curve Sorted= 0
DSS Export Volume Flow Curves= 0
DXF OffsetX= 0
DXF OffsetY= 0
DXF ScaleX= 1
DXF ScaleY= 10

--- UNT211 IN CCTC.p01 (plan) ---

Plan Title=Multiple Run
Short Identifier=Multiple
Geom File=g01
Flow File=f01
Subcritical Flow
K Sum by GR= 0
Std Step Tol= 0.01
Critical Tol= 0.01
Num of Std Step Trials= 20
Max Error Tol= 0.3
Flow Tol Ratio= 0.001
Split Flow NTrial= 30
Split Flow Tol= 0.02
Split Flow Ratio= 0.02
Log Output Level= 0
Friction Slope Method= 1
Unsteady Friction Slope Method= 2
Unsteady Bridges Friction Slope Method= 1
Parabolic Critical Depth
Global Vel Dist=  1 , 1 , 1
Global Log Level= 0
CheckData=True
Encroach Param= -1, 0, 0, 0
BEGIN DESCRIPTION:
Multiple Run
END DESCRIPTION:

--- UNT211 IN CCTC.f01 (steady flow) ---

Flow Title=Multiple
Number of Profiles=7
Profile Names=10-year,25-year,50-year,1pct_min,100-year,1pct_plu,500-year
River Rch & RM= UNT211 IN CCTC,Reach-1,6405
    1346    1838    2242    1997    2700    3652    3901
River Rch & RM= UNT211 IN CCTC,Reach-1,30
    2936    4165    5210    4743    6414    8675    9694
Boundary for River Rch & Prof#=UNT211 IN CCTC,Reach-1,1
Up Type=0
Dn Type=3
Dn Slope=0.005
Boundary for River Rch & Prof#=UNT211 IN CCTC,Reach-1,2
Up Type=0
Dn Type=3
Dn Slope=0.005
Boundary for River Rch & Prof#=UNT211 IN CCTC,Reach-1,3
Up Type=0
Dn Type=3
Dn Slope=0.005
Boundary for River Rch & Prof#=UNT211 IN CCTC,Reach-1,4
Up Type=0
Dn Type=3
Dn Slope=0.005
Boundary for River Rch & Prof#=UNT211 IN CCTC,Reach-1,5
Up Type=0
Dn Type=3
Dn Slope=0.005
Boundary for River Rch & Prof#=UNT211 IN CCTC,Reach-1,6
Up Type=0
Dn Type=3
Dn Slope=0.005
Boundary for River Rch & Prof#=UNT211 IN CCTC,Reach-1,7
Up Type=0
Dn Type=3
Dn Slope=0.005

--- UNT211 IN CCTC.g01 (geometry) ---

Geom Title=Existing Conditions
Program Version=4.10

River Reach=UNT211 IN CCTC  ,Reach-1
Reach XY= 30
      3599648.75       10623785.      3599545.75       10623836.
       3599644.5       10623898.      3599603.75       10623936.
        3599051.       10623794.       3598955.5       10623966.
      3598804.25       10623853.      3598757.75       10623956.
       3598620.5       10623910.      3598473.75       10623946.
       3598341.5       10623755.       3598179.5       10623904.
       3597851.5       10623970.        3597776.       10624101.
      3597473.75       10624149.      3597354.25       10624242.
      3596971.25       10625026.       3596378.5       10625178.
      3595976.25       10625152.      3595998.25       10625283.
      3595790.75       10625284.        3595722.       10625395.
        3595614.       10625387.        3595660.       10625510.
        3595613.       10625566.        3595514.       10625589.
       3595480.5       10625496.      3595401.25       10625694.
      3595295.75       10625728.        3595195.       10625686.

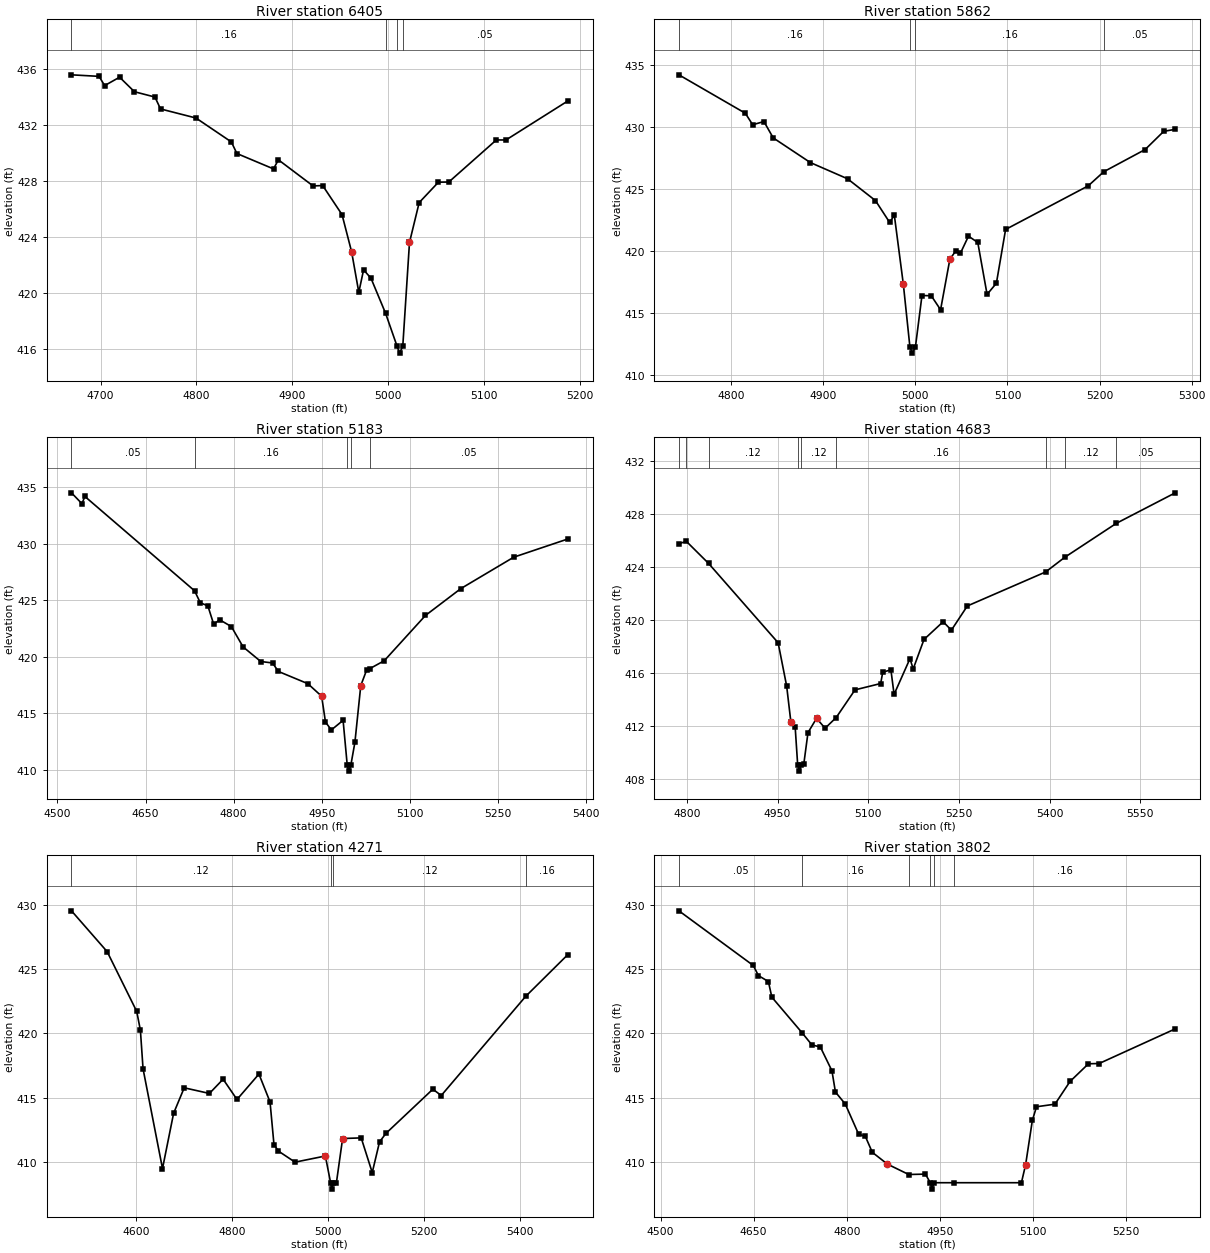
Type RM Length L Ch R = 1 ,6405    ,543,543,543
BEGIN DESCRIPTION:
UNT211 IN CCTC 12.0
END DESCRIPTION:
XS GIS Cut Line= 3
      3599571.43     10623603.86      3599480.28     10623755.77
      3599519.34     10624094.26
#Sta/Elev= 30
  4669.6  435.61  4698.4   435.5  4704.2  434.84  4719.8  435.44  4735.3   434.4
  4756.7  434.02  4762.5  433.17  4799.5  432.52  4836.4  430.81  4842.2  429.98
  4880.4  428.88  4885.5  429.53  4921.7  427.66  4931.7  427.69  4951.9  425.61
  4961.9  422.95  4969.4  420.05  4974.4  421.66  4982.1  421.06  4997.4  418.54
  5009.3   416.2    5012   415.7  5015.3   416.2  5022.3  423.62  5032.4  426.47
  5052.5  427.93  5063.3  427.94  5112.9  430.95    5123  430.95  5187.5  433.74
#Mann= 4 ,-1 , 0
  4669.6     .16       0  4997.4     .05       0  5009.3     .03       0
  5015.3     .05       0
Bank Sta=4961.9,5022.3
XS Rating Curve= 0 ,0
Exp/Cntr=0.3,0.1

Type RM Length L Ch R = 1 ,5862    ,679,679,679
BEGIN DESCRIPTION:
UNT211 IN CCTC 11.0
END DESCRIPTION:
XS GIS Cut Line= 2
      3599033.24     10623538.78      3599107.02     10624072.61
#Sta/Elev= 30
  4743.3  434.19  4815.4  431.09  4823.4  430.16  4835.6  430.42  4845.7   429.1
    4886  427.11  4926.4   425.8  4956.7  424.04  4972.1  422.28  4977.2  422.86
    4987  417.27  4994.1  412.23  4996.8  411.73  5000.1  412.23  5007.2  416.38
  5017.3  416.36  5027.4  415.23  5037.5  419.31    5044  419.99    5049   419.8
  5057.7  421.17  5067.8  420.66  5077.9  416.47    5088  417.37    5098  421.71
  5187.7  425.23  5204.6  426.37  5249.5  428.16  5269.7  429.63  5282.2  429.79
#Mann= 4 ,-1 , 0
  4743.3     .16       0  4994.1     .07       0  5000.1     .16       0
  5204.6     .05       0
Bank Sta=4987,5037.5
XS Rating Curve= 0 ,0
Exp/Cntr=0.3,0.1

Type RM Length L Ch R = 1 ,5183    ,500,500,500
BEGIN DESCRIPTION:
UNT211 IN CCTC 10.0
END DESCRIPTION:
XS GIS Cut Line= 2
      3598633.69     10623448.41      3598675.35     10624292.18
#Sta/Elev= 30
    4524  434.48  4541.8  433.52  4546.8  434.16  4733.5  425.82  4743.3  424.76
  4756.1  424.49  4766.1  422.86  4776.1  423.26  4796.1  422.66  4816.1  420.86
  4846.2  419.57  4866.2  419.44  4876.2  418.69  4926.3  417.61  4949.8   416.5
  4956.3  414.22  4966.3  413.52  4986.3  414.37  4993.4  410.38  4996.1  409.88
  4999.4  410.38  5006.4  412.42  5016.4  417.44  5026.4  418.82  5031.8  418.94
  5056.4  419.64  5126.5  423.64  5186.6  426.01  5276.7  428.79  5368.8   430.4
#Mann= 5 ,-1 , 0
    4524     .05       0  4733.5     .16       0  4993.4     .07       0
  4999.4     .16       0  5031.8     .05       0
Bank Sta=4949.8,5016.4
XS Rating Curve= 0 ,0
Exp/Cntr=0.3,0.1

Type RM Length L Ch R = 1 ,4683    ,412,412,412
BEGIN DESCRIPTION:
UNT211 IN CCTC 9.0
END DESCRIPTION:
XS GIS Cut Line= 3
      3598149.64     10623648.02      3598389.43     10623885.64
      3598542.43     10624344.62
#Sta/Elev= 30
  4786.7  425.79  4799.1  425.96  4835.7   424.3  4950.9   418.3    4965  415.03
    4972  412.31  4979.1  411.93  4983.2   409.1  4985.9   408.6  4989.2   409.1
  4993.3  409.11  5000.3  411.51  5014.5  412.59  5028.6  411.84    5047  412.65
  5078.1  414.74  5120.6  415.22    5124  416.07  5137.5  416.26  5142.8   414.4
  5169.1   417.1  5174.4  416.32  5192.3  418.55    5224  419.89  5237.6  419.25
    5264  421.08  5393.6  423.65  5425.3  424.76  5510.8  427.33  5608.1  429.63
#Mann= 9 ,-1 , 0
  4786.7     .16       0  4799.1     .05       0  4835.7     .12       0
  4983.2     .07       0  4989.2     .12       0    5047     .16       0
  5393.6     .05       0  5425.3     .12       0  5510.8     .05       0
Bank Sta=4972,5014.5
XS Rating Curve= 0 ,0
Exp/Cntr=0.3,0.1

Type RM Length L Ch R = 1 ,4271    ,469,469,469
BEGIN DESCRIPTION:
UNT211 IN CCTC 8.0
END DESCRIPTION:
XS GIS Cut Line= 2
      3597744.16     10623486.65      3598173.09     10624426.83
#Sta/Elev= 30
  4465.7  429.54    4540  426.36  4601.5  421.71  4609.2  420.24  4614.7  417.24
  4655.2  409.47  4678.3  413.77  4700.4  415.76  4752.9  415.32  4781.4  416.43
  4810.3  414.85    4856  416.83  4879.1  414.66  4887.3  411.34  4896.6  410.83
  4931.2  409.97  4994.3  410.45  5005.2  408.37  5007.9  407.87  5011.2  408.37
  5017.3  408.37  5030.2  411.81  5068.9  411.86  5091.9  409.16  5107.1  411.55
  5120.4  412.21  5218.1  415.65  5235.6  415.16  5411.4  422.88  5499.1  426.13
#Mann= 4 ,-1 , 0
  4465.7     .12       0  5005.2     .07       0  5011.2     .12       0
  5411.4     .16       0
Bank Sta=4994.3,5030.2
XS Rating Curve= 0 ,0
Exp/Cntr=0.3,0.1

Type RM Length L Ch R = 1 ,3802    ,399,399,399
BEGIN DESCRIPTION:
UNT211 IN CCTC 7.0
END DESCRIPTION:
XS GIS Cut Line= 2
      3597411.47      10623681.1       3597706.6     10624424.14
#Sta/Elev= 30
  4529.6  429.56  4649.4   425.3  4657.7  424.51  4673.7  424.05  4679.3  422.83
  4728.1  420.05  4743.8  419.11  4757.4  418.95  4776.1  417.09  4781.7  415.44
  4797.6   414.5  4819.1  412.15  4829.9  411.98  4841.1  410.74  4865.4  409.82
  4899.8  409.01  4926.7  409.04  4934.5  408.37  4937.2  407.87  4940.5  408.37
    4972  408.37  5081.3  408.37  5088.1  409.78  5098.9  413.22  5105.6  414.29
  5135.3  414.49  5159.6  416.26  5189.3  417.64  5206.5  417.66  5329.1  420.36
#Mann= 6 ,-1 , 0
  4529.6     .05       0  4728.1     .16       0  4899.8     .12       0
  4934.5     .07       0  4940.5     .12       0    4972     .16       0
Bank Sta=4865.4,5088.1
XS Rating Curve= 0 ,0
Exp/Cntr=0.3,0.1

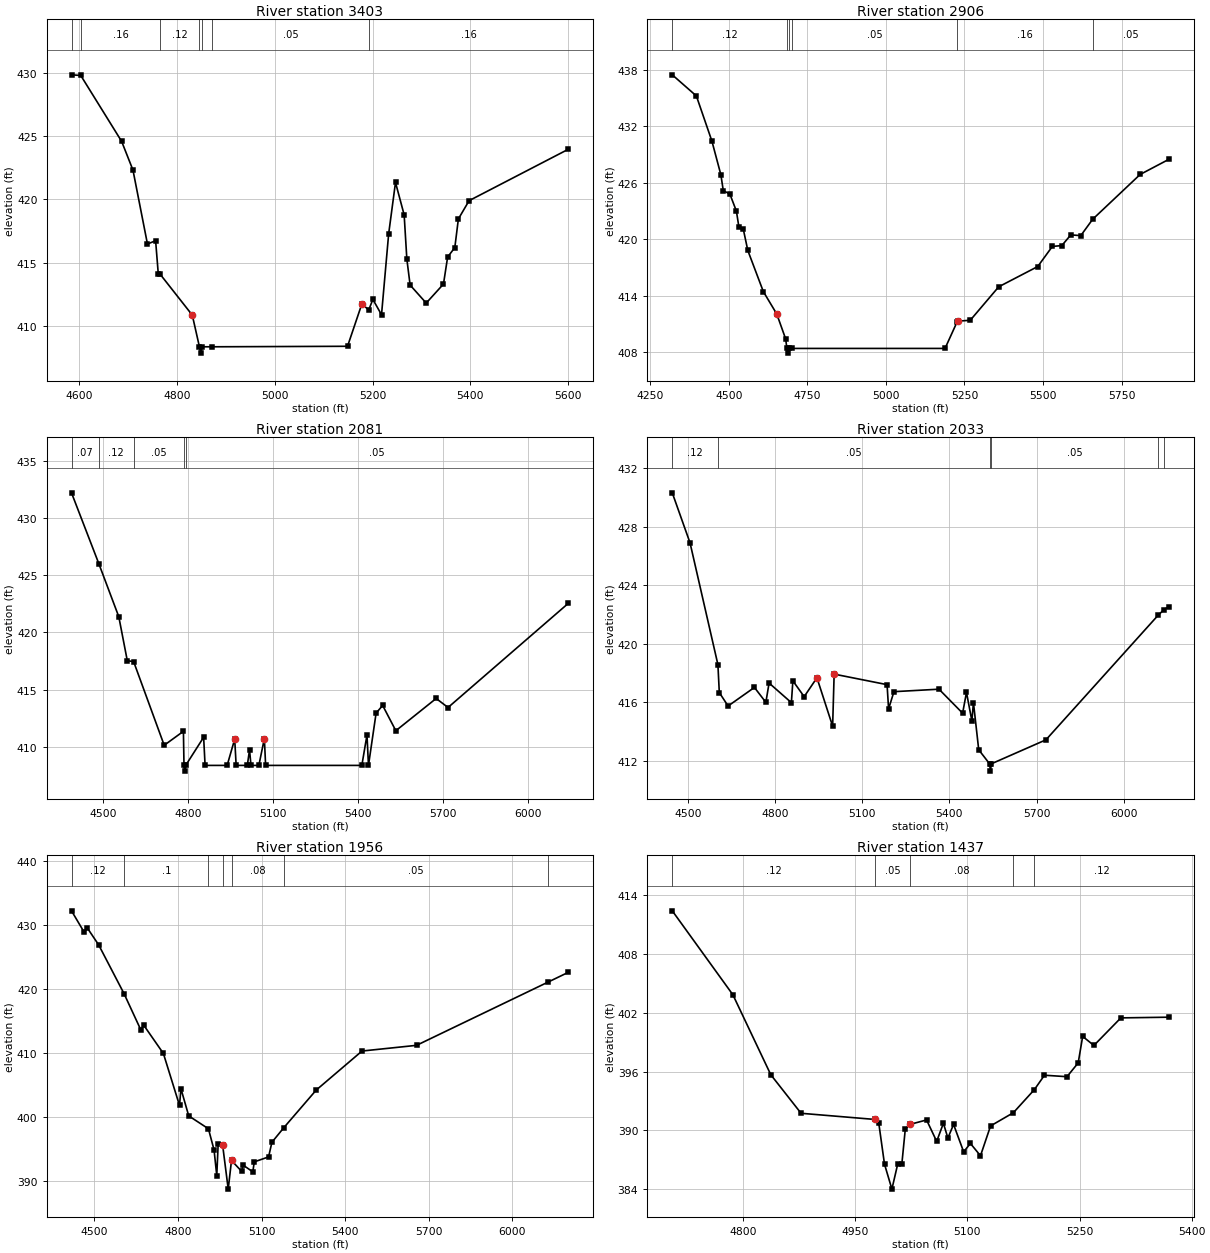
Type RM Length L Ch R = 1 ,3403    ,497,497,497
BEGIN DESCRIPTION:
UNT211 IN CCTC 6.0
END DESCRIPTION:
XS GIS Cut Line= 2
      3596907.99     10624184.56      3597834.87     10624601.14
#Sta/Elev= 30
  4584.3  429.83  4603.2  429.78  4686.8  424.58    4710  422.31  4739.6  416.48
  4756.3  416.74  4761.8   414.1  4765.9  414.08  4831.3  410.87  4845.9  408.37
  4848.7  407.87  4851.9  408.37  4872.5  408.37  5148.8  408.41  5178.1  411.75
  5192.2  411.28  5200.6  412.11  5218.3   410.9  5232.9  417.28  5246.9  421.34
  5264.6  418.78  5270.1  415.29  5276.8  413.24  5309.7  411.82    5345  413.32
  5353.5  415.45  5368.2   416.2  5375.5  418.46  5397.4   419.9  5600.5  423.96
#Mann= 7 ,-1 , 0
  4584.3     .12       0  4603.2     .16       0  4765.9     .12       0
  4845.9    .033       0  4851.9     .12       0  4872.5     .05       0
  5192.2     .16       0
Bank Sta=4831.3,5178.1
XS Rating Curve= 0 ,0
Exp/Cntr=0.3,0.1

Type RM Length L Ch R = 1 ,2906    ,825,825,825
BEGIN DESCRIPTION:
UNT211 IN CCTC 5.0
END DESCRIPTION:
XS GIS Cut Line= 4
      3596605.89     10624295.66      3597008.69      10624767.9
      3597112.86     10624826.93      3597949.66     10624903.31
#Sta/Elev= 30
  4320.4   437.5  4397.1  435.25  4446.5  430.44    4475  426.86  4482.7  425.17
  4503.6  424.81  4524.4  422.99  4532.1  421.35  4546.4  421.06  4560.7   418.8
  4610.1  414.42  4652.9  412.03  4681.2  409.37    4685  408.37  4687.8  407.87
    4691  408.37  4702.4  408.37  5188.1  408.37  5225.9  411.15  5228.3  411.27
  5268.4  411.37  5358.8  414.93    5483  417.09  5529.5  419.23  5559.6  419.32
  5588.2  420.46  5619.9  420.38    5658  422.13  5808.7  426.89  5901.1  428.52
#Mann= 6 ,-1 , 0
  4320.4     .12       0    4685    .033       0    4691     .12       0
  4702.4     .05       0  5225.9     .16       0    5658     .05       0
Bank Sta=4652.9,5228.3
XS Rating Curve= 0 ,0
Exp/Cntr=0.3,0.1

Type RM Length L Ch R = 1 ,2081    ,48,48,48
BEGIN DESCRIPTION:
UNT211 IN CCTC 4.0
END DESCRIPTION:
XS GIS Cut Line= 5
      3596351.81     10624563.46      3596376.12      10624987.1
      3596424.73     10625244.05      3596466.39     10625407.24
      3596740.03     10626265.09
#Sta/Elev= 30
  4387.7  432.19  4484.3  425.99  4554.7  421.36  4584.7  417.52  4607.1  417.44
    4715  410.13  4782.9  411.35  4784.9  408.37  4787.7  407.87  4790.9  408.37
  4854.3  410.83  4859.4  408.37  4937.3  408.37    4964  410.67  4969.1  408.37
  5008.5  408.37  5016.4  409.73  5021.5  408.37  5049.3  408.37  5068.7  410.72
  5073.2  408.37    5413  408.37  5431.1  411.03  5436.4  408.37  5463.3  412.94
  5486.5  413.61    5533   411.4  5675.4  414.22  5717.4  413.43  6142.4  422.54
#Mann= 5 ,-1 , 0
  4387.7     .07       0  4484.3     .12       0  4607.1     .05       0
  4784.9     .03       0  4790.9     .05       0
Bank Sta=4964,5068.7
XS Rating Curve= 0 ,0
Exp/Cntr=0.3,0.1

Type RM Length L Ch R = 1 ,2033    ,77,77,77
BEGIN DESCRIPTION:
Mapping XS 8e97bdcc
END DESCRIPTION:
XS GIS Cut Line= 5
      3596296.26     10624629.51      3596358.75     10625157.24
      3596410.84     10625344.74      3596455.98     10625521.83
      3596703.57     10626283.32
#Sta/Elev= 30
  4446.7  430.31  4507.8  426.89  4603.7  418.57  4608.5  416.66  4638.7  415.74
  4729.3  417.01  4768.7  415.99  4779.7  417.31  4856.5  415.97  4861.6  417.46
  4900.5  416.38  4944.4  417.67  4998.4  414.36  5003.6  417.92  5185.7   417.2
  5190.9  415.54  5209.3  416.72  5364.3  416.89  5445.6  415.25  5458.9  416.67
  5477.5  414.72  5482.8  415.98    5501  412.75  5538.4  411.79  5541.2  411.29
  5544.4  411.79  5732.3  413.43  6118.1  421.94  6138.5  422.33  6156.2  422.54
#Mann= 6 ,-1 , 0
  4446.7     .12       0  4603.7     .05       0  5538.4     .03       0
  5544.4     .05       0  6118.1     .16       0  6138.5     .08       0
Bank Sta=4944.4,5003.6
XS Rating Curve= 0 ,0
Exp/Cntr=0.3,0.1

Type RM Length L Ch R = 1 ,1956    ,519,519,519
BEGIN DESCRIPTION:
UNT211 IN CCTC 3.0
END DESCRIPTION:
XS GIS Cut Line= 4
       3596197.3     10624603.87      3596275.42      10625129.9
      3596301.46     10625236.67      3596680.14     10626314.59
#Sta/Elev= 30
  4417.5   432.2  4463.3  428.83  4474.4  429.51  4514.9  426.89  4606.5  419.23
  4666.5  413.59  4676.6  414.35  4747.4  409.92  4805.3   401.8  4810.4  404.42
  4838.4  400.17  4909.1  398.16  4929.4  394.84  4939.1  390.83  4944.1   395.8
  4959.9  395.68  4980.2  388.73    4992  393.21  5028.5   391.5  5033.7  392.48
  5068.5  391.43  5073.8  392.99  5125.1  393.76  5137.1  396.05  5179.5  398.31
  5296.1   404.2  5460.6   410.3  5656.5  411.19  6128.7  421.07  6201.7   422.6
#Mann= 7 ,-1 , 0
  4417.5     .12       0  4606.5      .1       0  4909.1     .08       0
  4959.9     .05       0    4992     .08       0  5179.5     .05       0
  6128.7     .16       0
Bank Sta=4959.9,4992
XS Rating Curve= 0 ,0
Exp/Cntr=0.3,0.1

Type RM Length L Ch R = 1 ,1437    ,647,647,647
BEGIN DESCRIPTION:
UNT211 IN CCTC 2.0
END DESCRIPTION:
XS GIS Cut Line= 3
      3595899.61     10625010.19      3595949.61     10625310.19
      3596149.61     10625610.19
#Sta/Elev= 30
  4705.2  412.43  4786.3  403.85    4837  395.68  4877.5  391.74  4976.4  391.11
  4981.5   390.7  4989.1  386.54    4999  383.99  5006.8  386.56  5012.3  386.56
  5016.9  390.11  5022.9   390.6  5045.4  391.06  5058.9  388.87  5067.9  390.72
  5073.9  389.21  5081.5   390.6    5095   387.8    5104  388.66  5117.5   387.4
    5131  390.45  5161.5   391.8  5189.6  394.16  5203.1  395.63  5233.2  395.48
  5248.2  396.89  5254.2   399.6  5269.2  398.67  5305.3  401.49  5369.9  401.56
#Mann= 5 ,-1 , 0
  4705.2     .12       0  4976.4     .05       0  5022.9     .08       0
  5161.5     .05       0  5189.6     .12       0
Bank Sta=4976.4,5022.9
XS Rating Curve= 0 ,0
Exp/Cntr=0.3,0.1

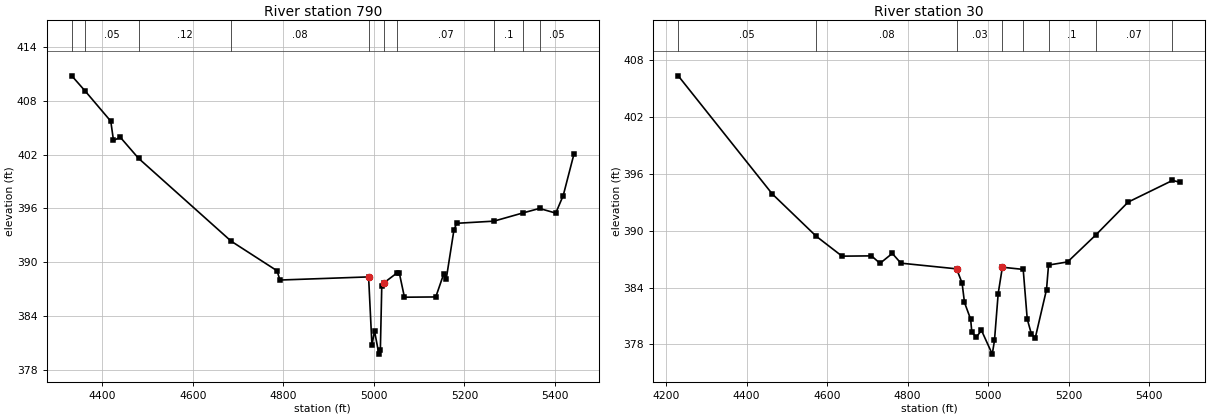
Type RM Length L Ch R = 1 ,790     ,760,760,760
BEGIN DESCRIPTION:
Mapping XS ea914bb5
END DESCRIPTION:
XS GIS Cut Line= 4
      3595773.93     10625006.04       3595511.8     10625403.59
      3595626.38     10625606.71      3595991.01     10625771.66
#Sta/Elev= 30
  4332.3  410.82  4362.6  409.08  4418.5  405.75  4424.5   403.6  4439.6  403.95
  4479.9   401.6  4684.6  392.34  4785.8  389.04  4792.4     388  4988.3  388.35
  4995.7   380.7  5001.4  382.32    5011  379.72  5014.3  380.22  5017.4  387.32
  5023.1  387.72  5051.8  388.82  5056.2  388.78  5067.5  386.08  5136.8  386.11
  5154.4   388.7  5159.9  388.12  5176.9  393.59    5183  394.34  5265.2  394.58
  5329.4   395.5    5366     396  5401.9  395.48  5418.4  397.44  5441.9  402.03
#Mann= 10 ,-1 , 0
  4332.3     .16       0  4362.6     .05       0  4479.9     .12       0
  4684.6     .08       0  4988.3     .05       0  5023.1     .08       0
  5051.8     .07       0  5265.2      .1       0  5329.4     .16       0
    5366     .05       0
Bank Sta=4988.3,5023.1
XS Rating Curve= 0 ,0
Exp/Cntr=0.3,0.1

Type RM Length L Ch R = 1 ,30      ,0,0,0
BEGIN DESCRIPTION:
UNT211 IN CCTC 1.0
END DESCRIPTION:
XS GIS Cut Line= 4
      3595600.32     10625019.93      3595211.45      10625639.7
      3595239.23     10625740.39      3595648.99      10625764.7
#Sta/Elev= 30
  4230.3  406.38  4463.8   393.9    4573  389.43    4637  387.33  4710.1  387.36
  4731.3  386.57  4761.8  387.62  4783.1  386.59 4921.48  385.99  4935.1  384.48
    4941  382.44  4956.3  380.67  4959.3  379.27  4970.7  378.79  4983.2  379.49
    5010  376.98  5015.5  378.42  5024.7  383.38  5035.1  386.16  5086.8  385.93
  5096.8  380.69  5106.9  379.14  5116.9  378.72  5144.7   383.8  5149.7  386.39
    5197  386.72  5267.1  389.57  5347.3  393.04  5457.5  395.33  5476.9  395.13
#Mann= 8 ,-1 , 0
  4230.3     .05       0    4573     .08       0 4921.48     .03       0
  5035.1     .05       0  5086.8     .07       0  5149.7      .1       0
  5267.1     .07       0  5457.5     .16       0
Bank Sta=4921.48,5035.1
XS Rating Curve= 0 ,0
Exp/Cntr=0.3,0.1

Chan Stop Cuts=-1
Use User Specified Reach Order=0
Composite Channel Slope=5