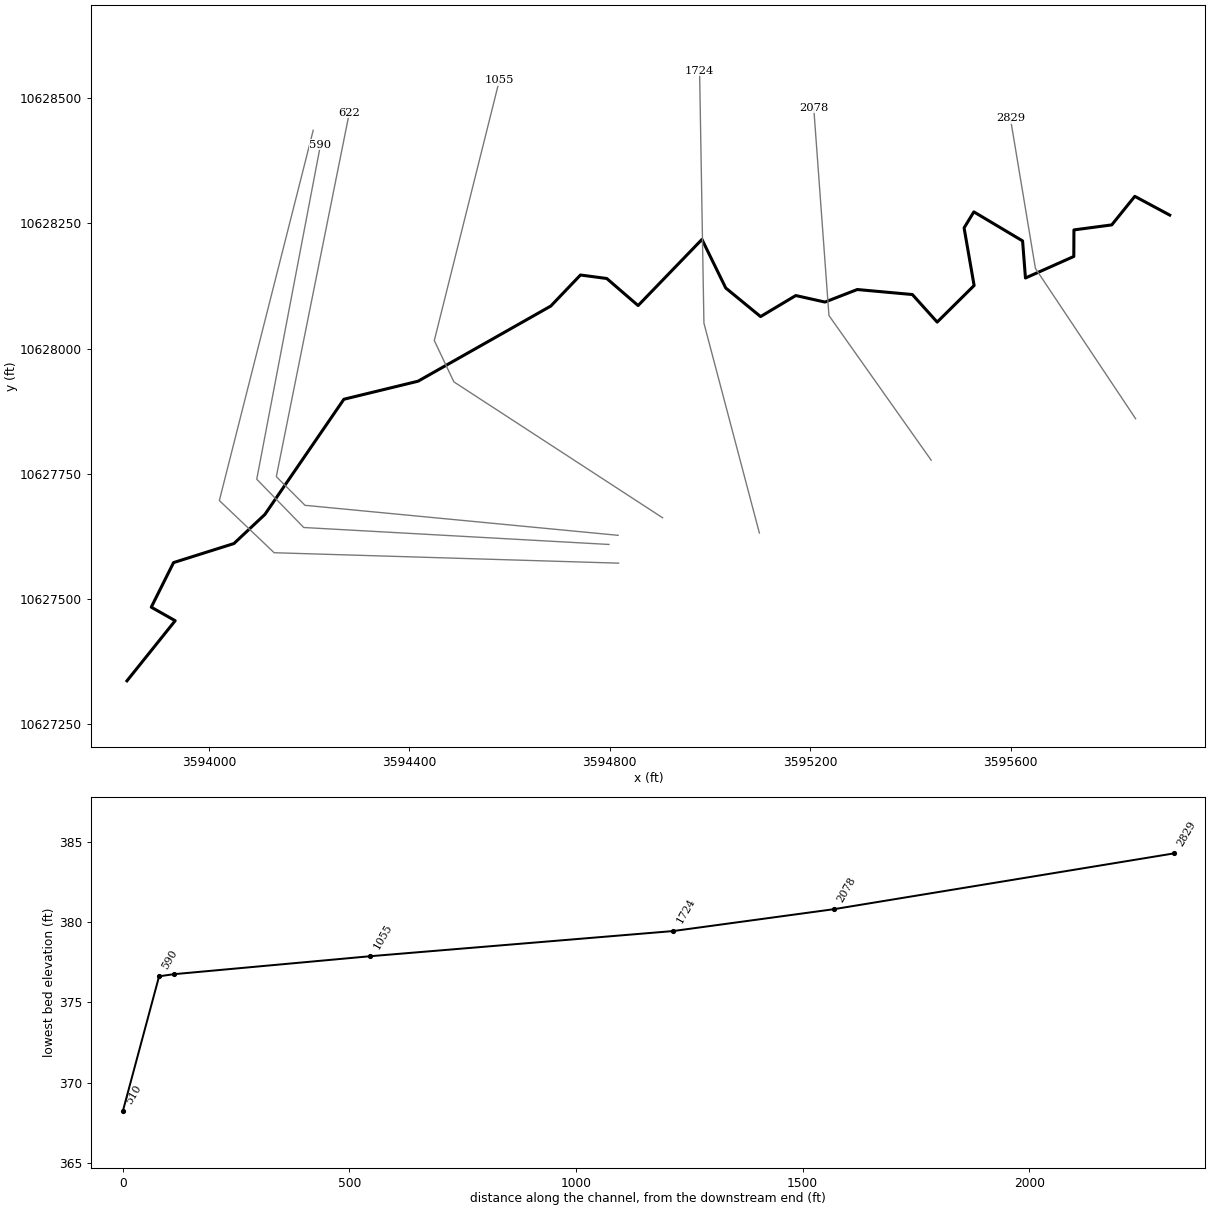
--- UNT212 IN CCTC.prj (project) ---

Proj Title=UNT212 IN CCTC Base Level Engineering
Current Plan=p01
Default Exp/Contr=0.3,0.1
English Units
Geom File=g01
Flow File=f01
Plan File=p01
BEGIN DESCRIPTION:
UNT212 IN CCTC
END DESCRIPTION:

--- UNT212 IN CCTC.p01 (plan) ---

Plan Title=Multiple Run
Short Identifier=Multiple
Geom File=g01
Flow File=f01
Subcritical Flow
K Sum by GR= 0
Std Step Tol= 0.01
Critical Tol= 0.01
Num of Std Step Trials= 20
Max Error Tol= 0.3
Flow Tol Ratio= 0.001
Split Flow NTrial= 30
Split Flow Tol= 0.02
Split Flow Ratio= 0.02
Log Output Level= 0
Friction Slope Method= 1
Unsteady Friction Slope Method= 2
Unsteady Bridges Friction Slope Method= 1
Parabolic Critical Depth
Global Vel Dist=  1 , 1 , 1
Global Log Level= 0
CheckData=True
Encroach Param= -1, 0, 0, 0
BEGIN DESCRIPTION:
Multiple Run
END DESCRIPTION:

--- UNT212 IN CCTC.f01 (steady flow) ---

Flow Title=Multiple
Number of Profiles=7
Profile Names=10-year,25-year,50-year,1pct_min,100-year,1pct_plu,500-year
River Rch & RM= UNT212 IN CCTC,Reach-1,2829
     431     547     637     543     735     994     972
Boundary for River Rch & Prof#=UNT212 IN CCTC,Reach-1,1
Up Type=0
Dn Type=3
Dn Slope=0.005
Boundary for River Rch & Prof#=UNT212 IN CCTC,Reach-1,2
Up Type=0
Dn Type=3
Dn Slope=0.005
Boundary for River Rch & Prof#=UNT212 IN CCTC,Reach-1,3
Up Type=0
Dn Type=3
Dn Slope=0.005
Boundary for River Rch & Prof#=UNT212 IN CCTC,Reach-1,4
Up Type=0
Dn Type=3
Dn Slope=0.005
Boundary for River Rch & Prof#=UNT212 IN CCTC,Reach-1,5
Up Type=0
Dn Type=3
Dn Slope=0.005
Boundary for River Rch & Prof#=UNT212 IN CCTC,Reach-1,6
Up Type=0
Dn Type=3
Dn Slope=0.005
Boundary for River Rch & Prof#=UNT212 IN CCTC,Reach-1,7
Up Type=0
Dn Type=3
Dn Slope=0.005

--- UNT212 IN CCTC.g01 (geometry) ---

Geom Title=Existing Conditions

River Reach=UNT212 IN CCTC,Reach-1
Reach XY= 30
      3595917.75     10628266.54      3595848.00     10628304.00
      3595802.00     10628247.00      3595726.50     10628237.00
      3595726.25     10628184.00      3595629.75     10628141.00
      3595624.00     10628215.00      3595526.75     10628273.00
      3595507.25     10628241.00      3595527.25     10628126.00
      3595453.50     10628053.00      3595404.00     10628108.00
      3595294.00     10628118.00      3595229.50     10628093.00
      3595171.25     10628106.00      3595101.00     10628064.00
      3595031.50     10628121.00      3594984.00     10628218.00
      3594856.50     10628086.00      3594794.00     10628140.00
      3594741.50     10628147.00      3594682.25     10628085.00
      3594417.25     10627935.00      3594269.25     10627899.00
      3594111.50     10627669.00      3594049.75     10627611.00
      3593929.25     10627573.00      3593884.75     10627484.00
      3593932.50     10627457.00      3593836.25     10627337.00

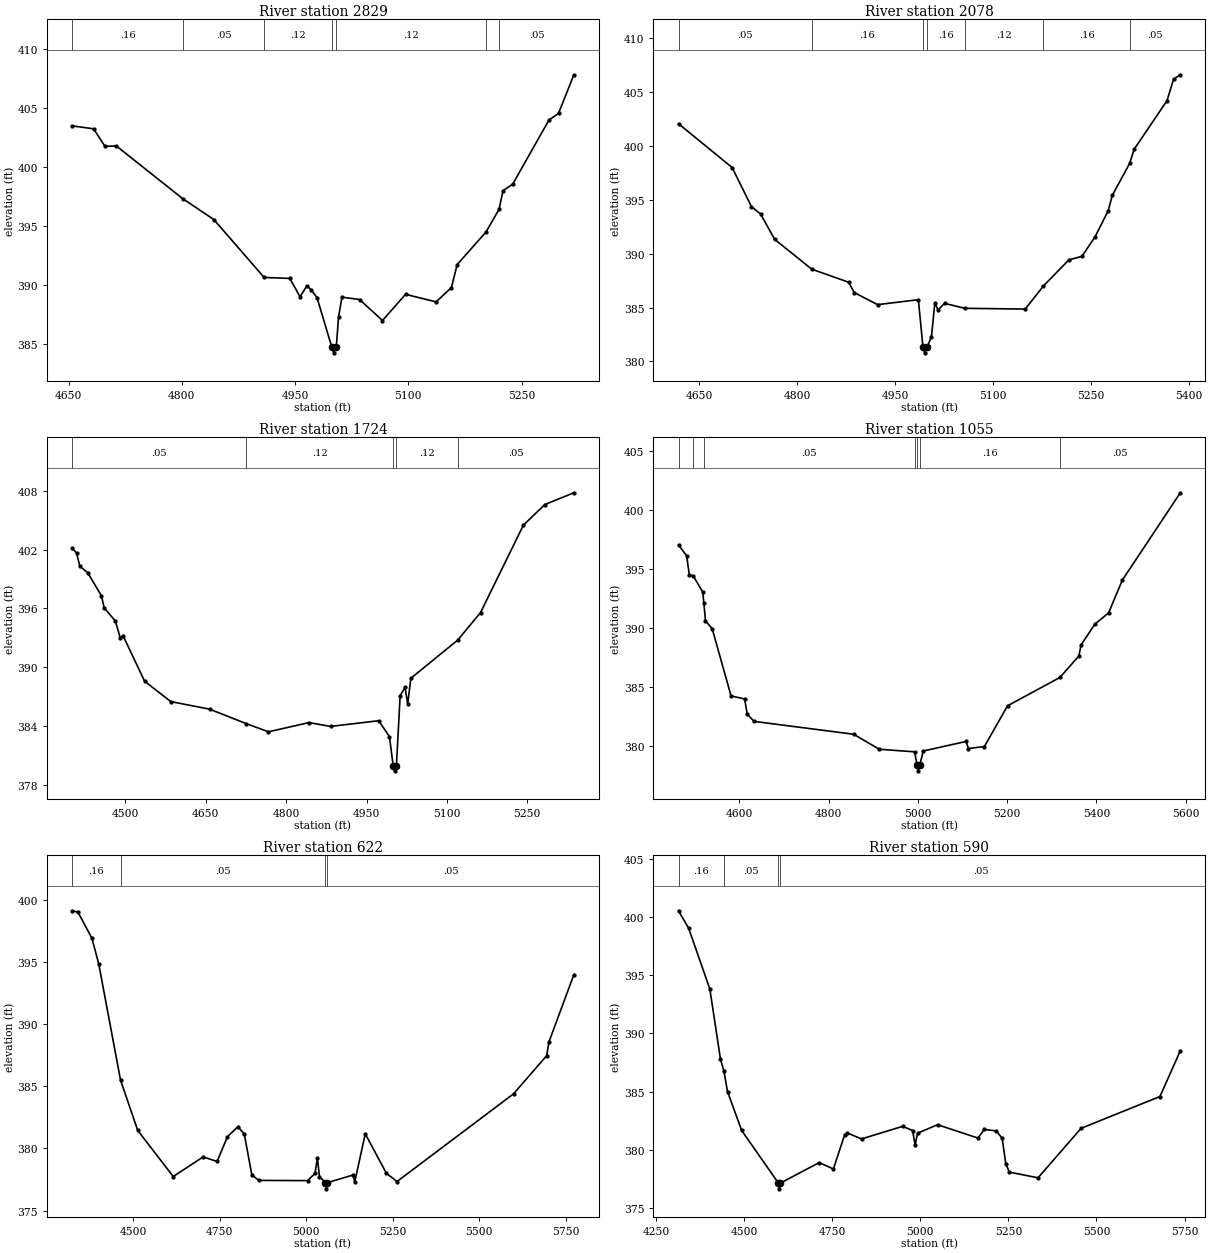
Type RM Length L Ch R = 1,2829,751,751,751
BEGIN DESCRIPTION:
UNT212 IN CCTC 5.0
END DESCRIPTION:
XS GIS Cut Line= 3
      3595849.61     10627860.19      3595649.61     10628160.19
      3595599.61     10628460.20
#Sta/Elev= 30
  4654.6  403.52  4683.1  403.27  4698.2  401.78  4713.2  401.82  4801.4  397.34
  4842.4  395.58  4909.0  390.67  4943.0  390.59  4956.6  389.03  4965.6  389.96
  4971.6  389.61  4979.1  388.95  4998.6  384.78  5001.4  384.28  5004.6  384.78
  5007.6  387.32  5012.1  389.00  5035.4  388.80  5065.8  387.02  5096.3  389.24
  5136.8  388.60  5157.1  389.81  5164.7  391.76  5203.1  394.54  5220.2  396.45
  5225.5  398.03  5238.2  398.57  5286.3  404.01  5299.0  404.58  5319.3  407.85
#Mann=7,-1,0
  4654.6    0.16       0  4801.4    0.05       0  4909.0    0.12       0
  4998.6    0.07       0  5004.6    0.12       0  5203.1    0.16       0
  5220.2    0.05       0
Bank Sta=4998.6,5004.6
Exp/Cntr=0.3,0.1

Type RM Length L Ch R = 1,2078,354,354,354
BEGIN DESCRIPTION:
UNT212 IN CCTC 4.0
END DESCRIPTION:
XS GIS Cut Line= 3
      3595441.51     10627777.41      3595237.49     10628066.07
      3595207.11     10628480.58
#Sta/Elev= 30
  4618.1  402.05  4700.2  397.99  4729.8  394.37  4744.0  393.66  4765.5  391.32
  4822.3  388.56  4878.7  387.35  4887.4  386.39  4923.1  385.27  4985.7  385.73
  4992.8  381.30  4995.5  380.80  4998.8  381.30  5005.8  382.30  5010.9  385.42
  5015.9  384.78  5025.8  385.39  5057.0  384.93  5149.5  384.86  5177.2  386.99
  5216.3  389.42  5236.4  389.75  5256.5  391.56  5276.5  393.96  5283.1  395.42
  5309.5  398.37  5316.6  399.70  5366.8  404.19  5376.8  406.18  5387.2  406.59
#Mann=7,-1,0
  4618.1    0.05       0  4822.3    0.16       0  4992.8    0.07       0
  4998.8    0.16       0  5057.0    0.12       0  5177.2    0.16       0
  5309.5    0.05       0
Bank Sta=4992.8,4998.8
Exp/Cntr=0.3,0.1

Type RM Length L Ch R = 1,1724,669,669,669
BEGIN DESCRIPTION:
UNT212 IN CCTC 3.0
END DESCRIPTION:
XS GIS Cut Line= 3
      3595098.60     10627632.05      3594987.93     10628050.88
      3594979.25     10628554.39
#Sta/Elev= 30
  4400.3  402.16  4408.7  401.64  4414.9  400.29  4429.4  399.65  4455.2  397.28
  4460.4  396.04  4481.1  394.72  4490.3  392.98  4495.4  393.23  4535.7  388.58
  4584.6  386.50  4657.0  385.73  4725.7  384.25  4766.9  383.42  4842.8  384.36
  4882.8  383.97  4972.8  384.55  4992.8  382.93  4999.8  379.94  5002.6  379.44
  5005.8  379.94  5012.8  387.11  5021.9  387.94  5026.9  386.27  5032.8  388.88
  5120.3  392.77  5162.9  395.58  5242.9  404.49  5282.9  406.59  5337.1  407.79
#Mann=5,-1,0
  4400.3    0.05       0  4725.7    0.12       0  4999.8    0.07       0
  5005.8    0.12       0  5120.3    0.05       0
Bank Sta=4999.8,5005.8
Exp/Cntr=0.3,0.1

Type RM Length L Ch R = 1,1055,433,433,433
BEGIN DESCRIPTION:
UNT212 IN CCTC 2.0
END DESCRIPTION:
XS GIS Cut Line= 4
      3594905.50     10627662.41      3594488.80     10627933.70
      3594449.73     10628016.16      3594579.71     10628536.08
#Sta/Elev= 30
  4463.6  397.01  4481.8  396.09  4487.8  394.46  4496.4  394.40  4518.0  393.01
  4520.2  392.12  4524.0  390.59  4539.1  389.90  4581.3  384.22  4611.6  383.96
  4617.6  382.68  4632.7  382.06  4856.0  380.97  4913.3  379.70  4992.5  379.48
  4998.2  378.37  5001.0  377.87  5004.2  378.37  5012.0  379.55  5107.8  380.36
  5113.2  379.76  5149.0  379.93  5200.8  383.38  5318.1  385.78  5360.6  387.60
  5365.7  388.55  5396.4  390.29  5427.3  391.26  5458.2  394.04  5588.0  401.43
#Mann=7,-1,0
  4463.6    0.05       0  4496.4    0.16       0  4520.2    0.05       0
  4992.5    0.16       0  4998.2    0.07       0  5004.2    0.16       0
  5318.1    0.05       0
Bank Sta=4998.2,5004.2
Exp/Cntr=0.3,0.1

Type RM Length L Ch R = 1,622,32,32,32
BEGIN DESCRIPTION:
Mapping XS 28e5628e
END DESCRIPTION:
XS GIS Cut Line= 4
      3594816.65     10627627.41      3594191.67     10627687.30
      3594134.38     10627744.59      3594280.20     10628471.13
#Sta/Elev= 30
  4323.2  399.12  4340.3  399.01  4380.5  396.91  4400.2  394.85  4463.3  385.49
  4512.9  381.45  4615.5  377.74  4702.0  379.32  4742.2  378.95  4772.3  380.95
  4802.4  381.75  4820.8  381.16  4842.6  377.88  4862.7  377.43  5004.0  377.41
  5025.3  378.00  5031.9  379.23  5038.1  377.74  5055.2  377.25  5057.9  376.75
  5061.2  377.25  5134.8  377.86  5139.9  377.31  5170.4  381.17  5231.5  378.00
  5262.2  377.34  5598.7  384.39  5694.7  387.47  5700.7  388.54  5773.1  393.98
#Mann=4,-1,0
  4323.2    0.16       0  4463.3    0.05       0  5055.2    0.03       0
  5061.2    0.05       0
Bank Sta=5055.2,5061.2
Exp/Cntr=0.3,0.1

Type RM Length L Ch R = 1,590,80,80,80
BEGIN DESCRIPTION:
Mapping XS acccc8d8
END DESCRIPTION:
XS GIS Cut Line= 4
      3594798.40     10627609.18      3594189.06     10627643.03
      3594095.31     10627739.39      3594222.59     10628406.94
#Sta/Elev= 30
  4313.7  400.56  4342.5  399.05  4402.6  393.82  4432.7  387.79  4442.4  386.77
  4452.7  385.00  4492.8  381.65  4597.1  377.12  4599.9  376.62  4603.1  377.12
  4713.1  378.88  4753.2  378.33  4785.4  381.29  4793.2  381.42  4833.3  380.92
  4949.8  382.00  4978.1  381.64  4985.3  380.39  4992.2  381.41  5048.8  382.14
  5163.8  380.99  5181.4  381.74  5215.9  381.60  5232.3  380.97  5242.5  378.79
  5252.7  378.06  5334.1  377.57  5456.3  381.83  5680.2  384.57  5738.0  388.51
#Mann=4,-1,0
  4313.7    0.16       0  4442.4    0.05       0  4597.1    0.03       0
  4603.1    0.05       0
Bank Sta=4597.1,4603.1
Exp/Cntr=0.3,0.1

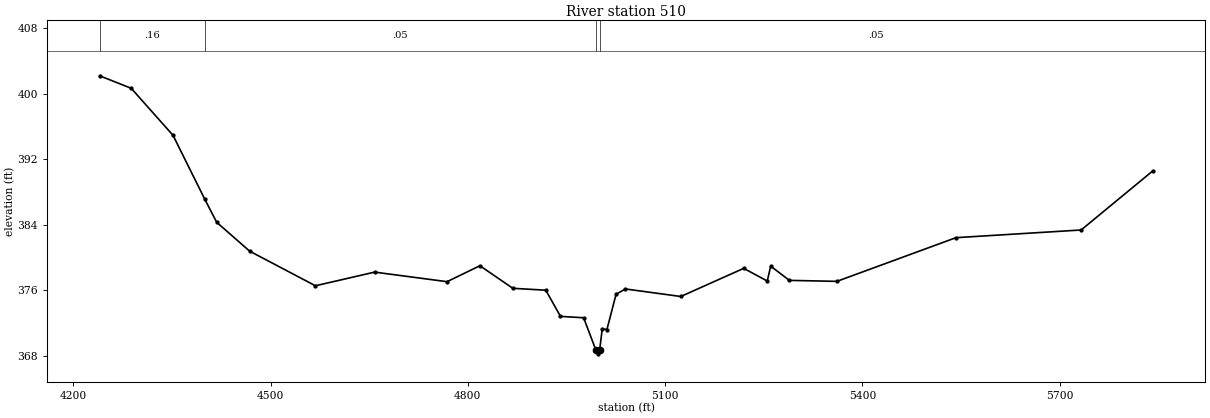
Type RM Length L Ch R = 1,510,0,0,0
BEGIN DESCRIPTION:
UNT212 IN CCTC 1.0
END DESCRIPTION:
XS GIS Cut Line= 4
      3594817.56     10627571.85      3594130.04     10627592.69
      3594020.66     10627696.85      3594208.00     10628435.79
#Sta/Elev= 30
  4240.2  402.20  4288.2  400.67  4351.8  394.92  4399.8  387.15  4418.2  384.29
  4468.3  380.76  4568.3  376.53  4658.3  378.20  4768.4  377.03  4818.4  378.98
  4868.4  376.22  4918.5  375.99  4940.9  372.79  4976.1  372.62  4994.5  368.71
  4997.2  368.21  5000.5  368.71  5004.4  371.28  5011.5  371.18  5025.4  375.49
  5039.6  376.14  5123.8  375.22  5219.5  378.66  5255.3  377.11  5260.5  378.93
  5288.9  377.19  5361.1  377.07  5542.2  382.41  5732.5  383.35  5841.4  390.57
#Mann=4,-1,0
  4240.2    0.16       0  4399.8    0.05       0  4994.5    0.03       0
  5000.5    0.05       0
Bank Sta=4994.5,5000.5
Exp/Cntr=0.3,0.1

Chan Stop Cuts=-1