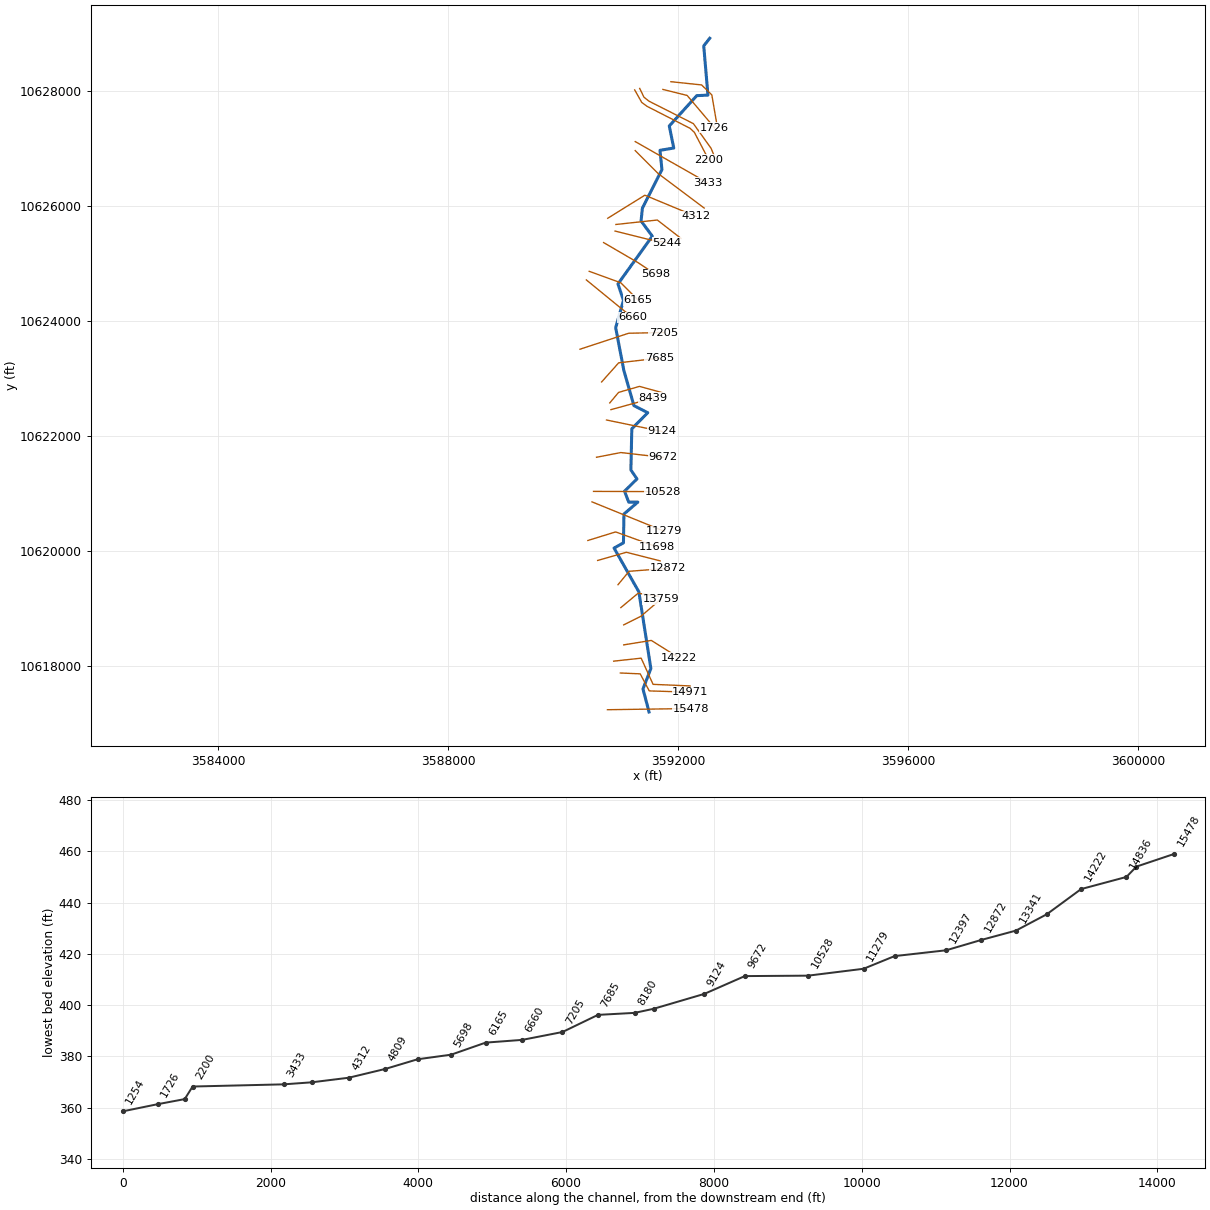
--- UNT213 IN CCTC.prj (project) ---

Proj Title=UNT213 IN CCTC Base Level Engineering
Current Plan=p01
Default Exp/Contr=0.3,0.1
English Units
Geom File=g01
Flow File=f01
Plan File=p01
Y Axis Title=Elevation
X Axis Title(PF)=Main Channel Distance
X Axis Title(XS)=Station
BEGIN DESCRIPTION:
UNT213 IN CCTC
END DESCRIPTION:
DSS Export Rating Curves= 0
DSS Export Rating Curve Sorted= 0
DSS Export Volume Flow Curves= 0
DXF OffsetX= 0
DXF OffsetY= 0
DXF ScaleX= 1
DXF ScaleY= 10

--- UNT213 IN CCTC.p01 (plan) ---

Plan Title=Multiple Run
Short Identifier=Multiple
Geom File=g01
Flow File=f01
Subcritical Flow
K Sum by GR= 0
Std Step Tol= 0.01
Critical Tol= 0.01
Num of Std Step Trials= 20
Max Error Tol= 0.3
Flow Tol Ratio= 0.001
Split Flow NTrial= 30
Split Flow Tol= 0.02
Split Flow Ratio= 0.02
Log Output Level= 0
Friction Slope Method= 1
Unsteady Friction Slope Method= 2
Unsteady Bridges Friction Slope Method= 1
Parabolic Critical Depth
Global Vel Dist=  1 , 1 , 1
Global Log Level= 0
CheckData=True
Encroach Param= -1, 0, 0, 0
BEGIN DESCRIPTION:
Multiple Run
END DESCRIPTION:

--- UNT213 IN CCTC.f01 (steady flow) ---

Flow Title=Multiple
Number of Profiles=7
Profile Names=10-year,25-year,50-year,1pct_min,100-year,1pct_plu,500-year
River Rch & RM= UNT213 IN CCTC,Reach-1,15478
    1576    2173    2669    2391    3234    4373    4730
River Rch & RM= UNT213 IN CCTC,Reach-1,4312
    2287    3214    3997    3621    4897    6622    7326
Boundary for River Rch & Prof#=UNT213 IN CCTC,Reach-1,1
Up Type=0
Dn Type=3
Dn Slope=0.005
Boundary for River Rch & Prof#=UNT213 IN CCTC,Reach-1,2
Up Type=0
Dn Type=3
Dn Slope=0.005
Boundary for River Rch & Prof#=UNT213 IN CCTC,Reach-1,3
Up Type=0
Dn Type=3
Dn Slope=0.005
Boundary for River Rch & Prof#=UNT213 IN CCTC,Reach-1,4
Up Type=0
Dn Type=3
Dn Slope=0.005
Boundary for River Rch & Prof#=UNT213 IN CCTC,Reach-1,5
Up Type=0
Dn Type=3
Dn Slope=0.005
Boundary for River Rch & Prof#=UNT213 IN CCTC,Reach-1,6
Up Type=0
Dn Type=3
Dn Slope=0.005
Boundary for River Rch & Prof#=UNT213 IN CCTC,Reach-1,7
Up Type=0
Dn Type=3
Dn Slope=0.005

--- UNT213 IN CCTC.g01 (geometry) ---

Geom Title=Existing Conditions
Program Version=4.10

River Reach=UNT213 IN CCTC  ,Reach-1
Reach XY= 30
        3591490.       10617195.      3591384.75       10617595.
      3591521.75       10617951.        3591313.       10619284.
      3590881.75       10620046.        3591045.       10620137.
       3591053.5       10620638.      3591295.25       10620846.
      3591137.25       10620845.       3591063.5       10621035.
        3591280.       10621249.      3591174.25       10621405.
      3591190.25       10622121.      3591467.75       10622400.
       3591227.5       10622524.      3591051.75       10623136.
      3590909.75       10623879.      3591045.25       10624355.
       3590949.5       10624640.       3591546.5       10625472.
      3591351.25       10625736.      3591374.75       10625959.
      3591714.25       10626630.      3591680.25       10626965.
        3591920.       10627005.        3591842.       10627388.
        3592320.       10627916.       3592514.5       10627925.
      3592441.25       10628781.       3592545.5       10628914.

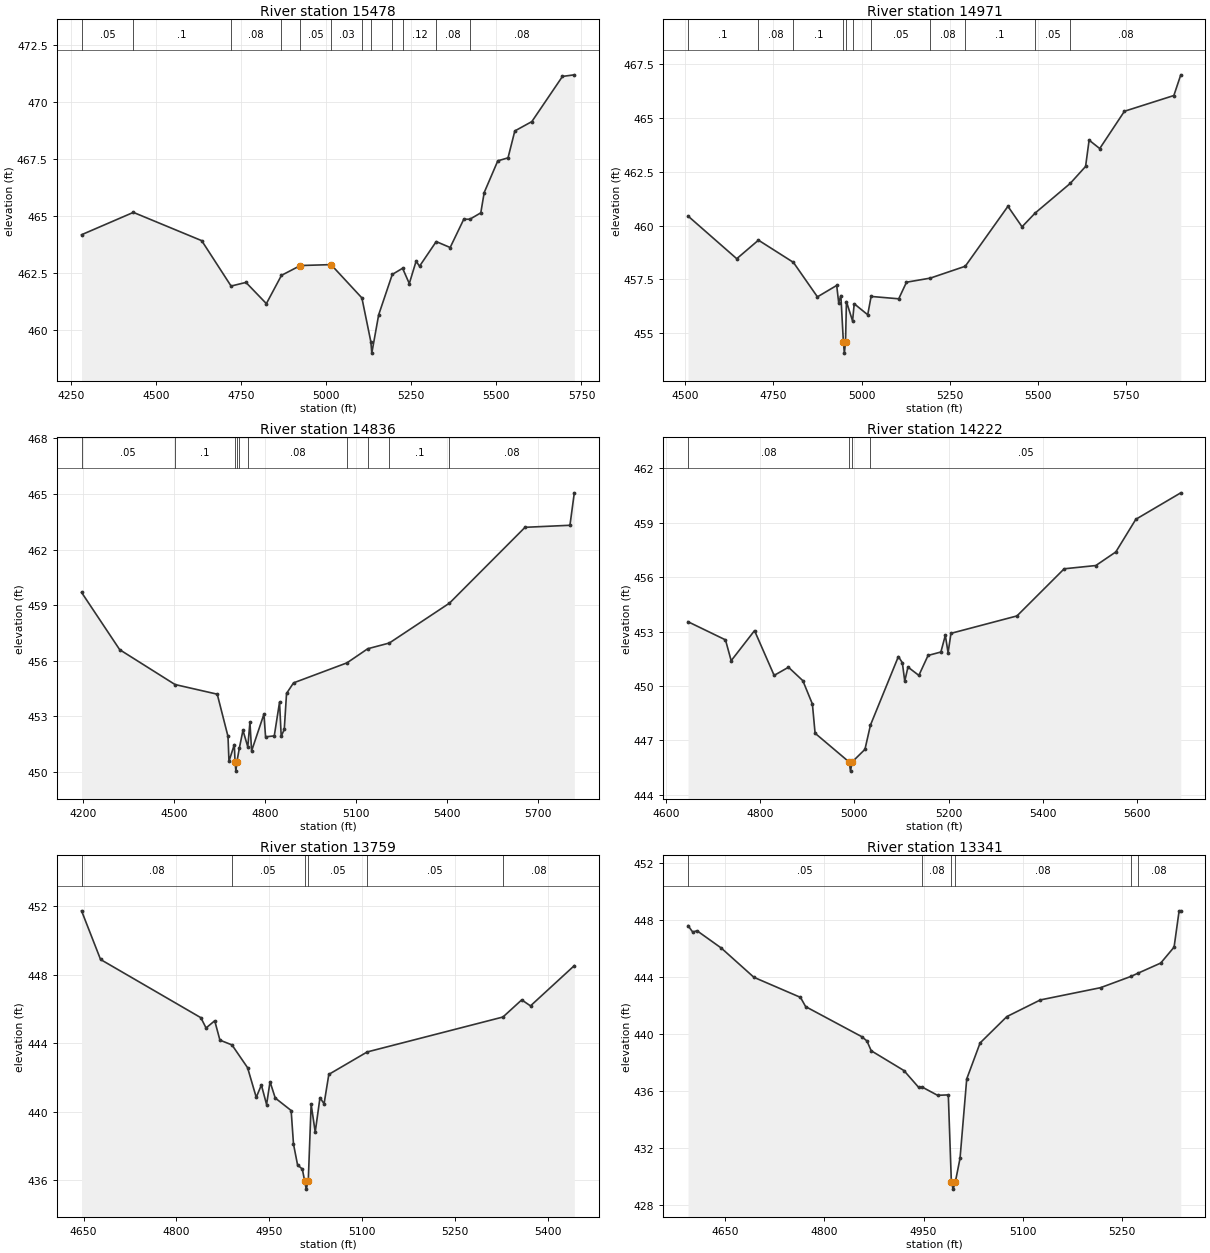
Type RM Length L Ch R = 1 ,15478   ,507,507,507
BEGIN DESCRIPTION:
UNT213 IN CCTC 28.0
END DESCRIPTION:
XS GIS Cut Line= 2
      3590766.56     10617234.13      3592214.41     10617254.96
#Sta/Elev= 30
  4280.9  464.18  4433.2  465.16    4634  463.92  4720.3  461.93    4764  462.09
    4824  461.16  4868.4   462.4    4924  462.83    5014  462.87  5104.7  461.41
    5131  459.49  5133.8  458.99    5154  460.67    5194  462.44  5224.3  462.71
    5244  462.04    5264  463.02  5274.1   462.8  5323.1  463.88  5364.1  463.62
  5404.1  464.86    5422  464.86  5454.1  465.14  5464.1  466.03  5504.1  467.42
  5534.1  467.55  5554.1  468.73  5604.1  469.14  5694.1  471.12  5728.9  471.19
#Mann= 12 ,-1 , 0
  4280.9     .05       0  4433.2      .1       0  4720.3     .08       0
  4868.4     .07       0    4924     .05       0    5014     .03       0
  5104.7     .05       0    5131     .07       0    5194     .05       0
  5224.3     .12       0  5323.1     .08       0    5422     .08       0
Bank Sta=4924,5014
XS Rating Curve= 0 ,0
Exp/Cntr=0.3,0.1

Type RM Length L Ch R = 1 ,14971   ,135,135,135
BEGIN DESCRIPTION:
Mapping XS eda8f95c
END DESCRIPTION:
XS GIS Cut Line= 4
      3590991.63     10617873.09      3591336.41     10617857.99
        3591494.     10617561.36      3592209.24     10617538.81
#Sta/Elev= 30
  4508.1  460.44  4646.2  458.46  4707.7  459.32  4806.8  458.29  4874.9  456.69
  4929.5  457.22  4935.1  456.42  4941.3  456.75  4948.5  454.58  4951.2  454.08
  4954.5  454.58  4957.1  456.47  4974.5  455.57  4979.1  456.37  5017.4  455.86
    5027  456.71  5105.3   456.6  5127.3  457.37  5194.8  457.56  5293.9  458.11
  5414.8  460.89  5454.8  459.94  5492.1  460.58  5591.2  461.95  5634.9  462.74
  5644.9  463.96    5675  463.57    5745   465.3  5885.1  466.03  5904.7  466.99
#Mann= 11 ,-1 , 0
  4508.1      .1       0  4707.7     .08       0  4806.8      .1       0
  4948.5     .07       0  4954.5      .1       0  4974.5     .08       0
    5027     .05       0  5194.8     .08       0  5293.9      .1       0
  5492.1     .05       0  5591.2     .08       0
Bank Sta=4948.5,4954.5
XS Rating Curve= 0 ,0
Exp/Cntr=0.3,0.1

Type RM Length L Ch R = 1 ,14836   ,614,614,614
BEGIN DESCRIPTION:
Mapping XS 3c9fe756
END DESCRIPTION:
XS GIS Cut Line= 4
      3590874.49     10618078.82      3591352.93     10618131.05
      3591560.24      10617675.4      3592203.98     10617648.19
#Sta/Elev= 30
    4194  459.69  4319.9   456.6  4502.6  454.72  4641.8   454.2  4677.3  451.92
  4680.5  450.58  4698.1  451.48  4700.6  450.55  4703.3  450.05  4706.6  450.55
    4715  451.31  4726.7  452.25  4742.6  451.36  4749.7  452.69  4755.2  451.14
  4795.8  453.12  4801.3   451.9    4830  451.95  4847.4  453.77  4852.9  451.93
    4863   452.3  4870.5  454.24  4893.6  454.81    5070  455.89  5138.4  456.65
  5209.8  456.96  5408.2  459.11  5657.6   463.2  5805.8  463.31  5820.2  465.06
#Mann= 10 ,-1 , 0
    4194     .05       0  4502.6      .1       0  4700.6     .07       0
  4706.6      .1       0    4715     .15       0  4742.6     .08       0
    5070      .1       0  5138.4     .08       0  5209.8      .1       0
  5408.2     .08       0
Bank Sta=4700.6,4706.6
XS Rating Curve= 0 ,0
Exp/Cntr=0.3,0.1

Type RM Length L Ch R = 1 ,14222   ,463,463,463
BEGIN DESCRIPTION:
UNT213 IN CCTC 27.0
END DESCRIPTION:
XS GIS Cut Line= 3
      3591049.32     10618362.01      3591529.32     10618439.74
      3592002.07     10618142.47
#Sta/Elev= 30
  4647.2  453.54  4726.6  452.54  4738.7  451.39  4788.2  453.05  4829.8  450.58
  4860.2  451.03  4890.6  450.29  4910.9     449  4916.6  447.39  4988.9   445.8
  4991.7   445.3  4994.9   445.8  5022.3   446.5    5034  447.84  5093.2  451.62
  5101.6  451.28  5106.7  450.26  5113.5  451.04  5136.6  450.58  5156.1  451.68
  5183.3  451.87  5192.7  452.79  5198.6  451.83  5204.7   452.9  5344.6  453.86
  5444.7  456.46  5511.8  456.64  5554.2  457.39  5596.6  459.19  5691.9  460.65
#Mann= 4 ,-1 , 0
  4647.2     .08       0  4988.9     .07       0  4994.9     .08       0
    5034     .05       0
Bank Sta=4988.9,4994.9
XS Rating Curve= 0 ,0
Exp/Cntr=0.3,0.1

Type RM Length L Ch R = 1 ,13759   ,418,418,418
BEGIN DESCRIPTION:
UNT213 IN CCTC 26.0
END DESCRIPTION:
XS GIS Cut Line= 3
      3591049.65     10618710.21      3591349.61     10618860.19
      3591699.58     10619160.16
#Sta/Elev= 30
  4646.7  451.74  4677.4   448.9  4839.5   445.5  4847.9   444.9  4861.9  445.32
  4870.3  444.19  4889.8  443.91    4915  442.58    4929  440.85  4937.3  441.57
  4945.7  440.43  4951.3  441.76  4959.7  440.81  4985.4  440.08  4989.2  438.12
  4995.8   436.9  5003.5  436.66  5007.1  435.99  5009.8  435.49  5013.1  435.99
  5017.7  440.45  5024.3  438.82    5032  440.83  5038.6  440.47  5046.3  442.19
  5108.3   443.5  5327.7  445.54    5358  446.54  5372.2  446.19    5443  448.54
#Mann= 6 ,-1 , 0
  4646.7     .08       0  4889.8     .05       0  5007.1     .04       0
  5013.1     .05       0  5108.3     .05       0  5327.7     .08       0
Bank Sta=5007.1,5013.1
XS Rating Curve= 0 ,0
Exp/Cntr=0.3,0.1

Type RM Length L Ch R = 1 ,13341   ,469,469,469
BEGIN DESCRIPTION:
UNT213 IN CCTC 25.0
END DESCRIPTION:
XS GIS Cut Line= 3
      3590999.64     10619010.22      3591299.61     10619260.19
      3591649.59     10619210.19
#Sta/Elev= 30
  4594.4  447.61  4601.5  447.16    4608  447.25  4644.5  446.04  4693.9  443.98
  4764.2  442.57    4772  441.92  4856.7  439.81  4864.5  439.51    4871  438.82
  4920.4  437.43  4942.6  436.25  4947.9  436.27  4971.2  435.69  4987.4  435.72
    4992   429.6  4994.7   429.1    4998   429.6  5005.1  431.26  5015.2  436.84
  5035.4  439.37  5075.8  441.22  5126.3  442.39  5217.2  443.25    5263  444.04
  5273.4  444.26  5308.1  444.98  5328.3   446.1  5335.9  448.65  5338.4  448.65
#Mann= 6 ,-1 , 0
  4594.4     .05       0  4947.9     .08       0    4992     .07       0
    4998     .08       0    5263     .05       0  5273.4     .08       0
Bank Sta=4992,4998
XS Rating Curve= 0 ,0
Exp/Cntr=0.3,0.1

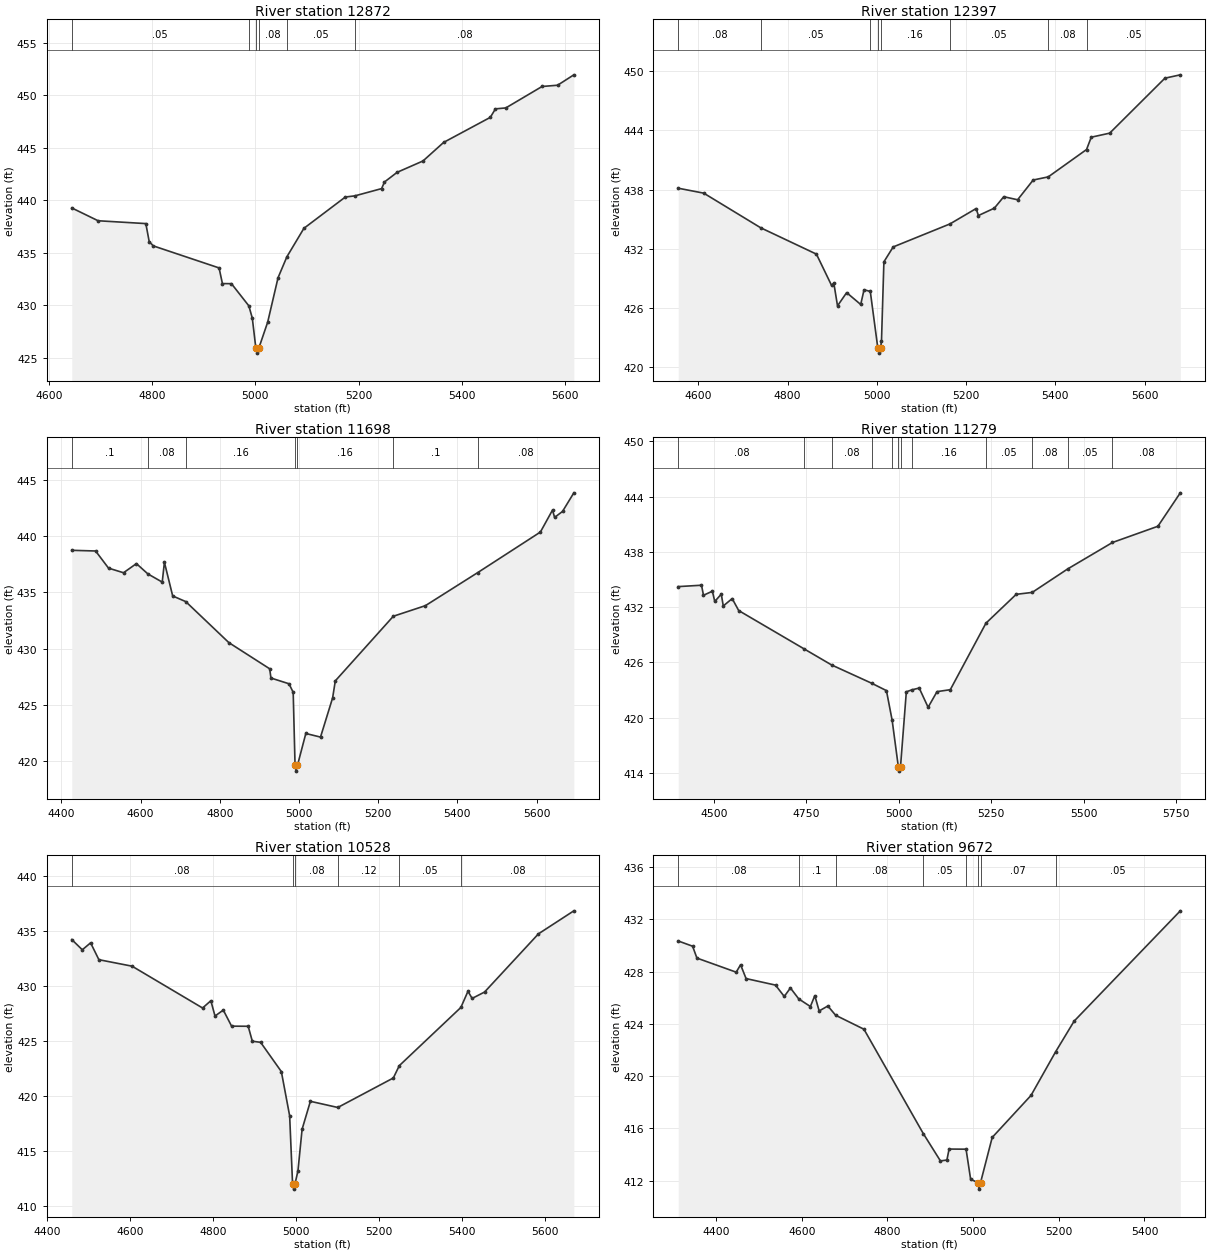
Type RM Length L Ch R = 1 ,12872   ,475,475,475
BEGIN DESCRIPTION:
UNT213 IN CCTC 24.0
END DESCRIPTION:
XS GIS Cut Line= 3
      3590949.95     10619408.48      3591143.54       10619642.
      3591811.04     10619693.21
#Sta/Elev= 30
  4644.2  439.27  4695.2  438.05  4787.7  437.78  4794.2  436.07    4802  435.66
  4929.6  433.56  4936.1  432.07  4953.6  432.06  4987.3  429.95    4994  428.78
  5000.8  425.95  5003.5  425.45  5006.8  425.95  5023.8   428.4  5043.9  432.63
    5061  434.62    5094  437.33  5174.3  440.31  5192.8  440.42  5244.5  441.11
  5250.1  441.74  5274.6  442.66  5324.7  443.74  5364.8  445.51  5455.1  447.89
  5465.1   448.7  5485.2  448.79  5555.4  450.83  5585.5  450.95    5617  451.94
#Mann= 6 ,-1 , 0
  4644.2     .05       0  4987.3     .08       0  5000.8     .07       0
  5006.8     .08       0    5061     .05       0  5192.8     .08       0
Bank Sta=5000.8,5006.8
XS Rating Curve= 0 ,0
Exp/Cntr=0.3,0.1

Type RM Length L Ch R = 1 ,12397   ,699,699,699
BEGIN DESCRIPTION:
UNT213 IN CCTC 23.0
END DESCRIPTION:
XS GIS Cut Line= 3
      3590596.22     10619830.49      3591096.25     10619972.86
      3591683.05     10619823.56
#Sta/Elev= 30
  4554.8  438.13    4612  437.63  4739.7  434.12  4864.6  431.45  4898.4  428.29
  4903.6  428.51  4911.8  426.21  4932.3  427.55  4963.8  426.35  4971.3  427.84
  4985.3  427.67  5002.2  421.92  5004.9  421.42  5008.2  421.92  5010.4  422.68
  5015.8  430.67  5036.6  432.18  5163.8  434.51  5222.5  436.07  5227.6  435.36
  5263.4  436.11  5284.5  437.27  5315.5  436.96  5350.4  438.96  5384.2  439.28
    5470  442.05  5480.6   443.3  5521.9  443.71  5645.7  449.28  5680.2  449.62
#Mann= 8 ,-1 , 0
  4554.8     .08       0  4739.7     .05       0  4985.3     .16       0
  5002.2     .07       0  5008.2     .16       0  5163.8     .05       0
  5384.2     .08       0    5470     .05       0
Bank Sta=5002.2,5008.2
XS Rating Curve= 0 ,0
Exp/Cntr=0.3,0.1

Type RM Length L Ch R = 1 ,11698   ,419,419,419
BEGIN DESCRIPTION:
UNT213 IN CCTC 22.0
END DESCRIPTION:
XS GIS Cut Line= 3
       3590426.1     10620177.72      3590908.75     10620327.03
       3591626.1     10620067.12
#Sta/Elev= 30
    4426  438.73  4486.2  438.67  4518.8  437.15  4556.7  436.74  4589.3  437.55
  4618.1  436.64  4654.5  435.91    4660  437.67  4680.9  434.68  4713.9  434.18
  4822.8  430.54  4925.9  428.22  4929.1   427.4  4974.7  426.89  4985.3  426.13
    4990  419.64  4992.7  419.14    4996  419.64  5017.2  422.48  5054.3  422.16
  5084.9  425.64  5091.7  427.15  5238.2  432.88  5319.3  433.82  5451.7  436.76
  5609.7  440.35  5640.3   442.3  5645.6  441.65  5665.6  442.18  5694.2  443.83
#Mann= 7 ,-1 , 0
    4426      .1       0  4618.1     .08       0  4713.9     .16       0
    4990     .07       0    4996     .16       0  5238.2      .1       0
  5451.7     .08       0
Bank Sta=4990,4996
XS Rating Curve= 0 ,0
Exp/Cntr=0.3,0.1

Type RM Length L Ch R = 1 ,11279   ,751,751,751
BEGIN DESCRIPTION:
UNT213 IN CCTC 21.0
END DESCRIPTION:
XS GIS Cut Line= 2
      3590498.14     10620849.61      3591755.72      10620337.9
#Sta/Elev= 30
  4403.7  434.23  4466.6  434.38    4472  433.29    4496  433.73  4502.5  432.62
  4520.1  433.41  4525.5  432.13  4549.6  432.93  4567.2  431.63  4744.9  427.45
  4818.2  425.73  4926.8  423.74  4966.7  422.94  4982.2  419.71  4998.8   414.7
  5001.6   414.2  5004.8   414.7  5020.5  422.81  5035.3  423.02  5055.3  423.22
  5079.4  421.13  5103.5  422.83  5139.4  423.04  5235.8  430.26  5317.6  433.39
  5360.9   433.6  5456.9  436.15    5578  439.02  5700.8  440.78  5761.4  444.41
#Mann= 12 ,-1 , 0
  4403.7     .08       0  4744.9     .05       0  4818.2     .08       0
  4926.8      .1       0  4982.2     .05       0  4998.8     .04       0
  5004.8     .05       0  5035.3     .16       0  5235.8     .05       0
  5360.9     .08       0  5456.9     .05       0    5578     .08       0
Bank Sta=4998.8,5004.8
XS Rating Curve= 0 ,0
Exp/Cntr=0.3,0.1

Type RM Length L Ch R = 1 ,10528   ,856,856,856
BEGIN DESCRIPTION:
UNT213 IN CCTC 20.0
END DESCRIPTION:
XS GIS Cut Line= 2
      3590524.23     10621031.89      3591734.92     10621027.55
#Sta/Elev= 30
  4459.5  434.19  4484.9  433.26  4504.9  433.89  4524.9  432.36  4604.9  431.77
  4774.9  427.97  4794.9  428.63  4804.9  427.24  4824.9  427.78  4844.9  426.32
  4884.9  426.31  4894.9  424.95  4914.9  424.85  4964.9  422.19  4984.9  418.17
  4991.9  412.01  4994.6  411.51  4997.9  412.01  5004.9  413.16  5014.9  416.95
  5034.9  419.49    5101  418.93  5234.9  421.61  5249.3  422.73  5397.8  428.02
  5414.9  429.49  5424.9  428.84  5454.9  429.42  5584.9  434.71  5670.2   436.8
#Mann= 6 ,-1 , 0
  4459.5     .08       0  4991.9     .07       0  4997.9     .08       0
    5101     .12       0  5249.3     .05       0  5397.8     .08       0
Bank Sta=4991.9,4997.9
XS Rating Curve= 0 ,0
Exp/Cntr=0.3,0.1

Type RM Length L Ch R = 1 ,9672    ,548,548,548
BEGIN DESCRIPTION:
Mapping XS 3eea1c26
END DESCRIPTION:
XS GIS Cut Line= 3
      3590576.76     10621625.54      3590999.89     10621707.56
      3591735.75     10621623.05
#Sta/Elev= 30
  4311.9  430.35  4345.4  429.95  4355.5  429.04  4447.2  427.96  4457.4  428.53
  4470.2  427.47  4538.9  426.97  4559.3   426.1  4573.7  426.75  4593.2  425.91
  4620.3  425.33  4630.6  426.16  4640.8  424.99  4661.1  425.37  4679.2  424.66
  4745.3  423.59  4883.7   415.6  4923.8   413.5  4938.9  413.57    4944  414.41
  4983.6   414.4  4994.3  412.09  5011.4  411.84  5014.1  411.34  5017.4  411.84
  5044.6   415.3  5135.2  418.52  5192.4  421.85  5235.8  424.21  5483.6  432.66
#Mann= 8 ,-1 , 0
  4311.9     .08       0  4593.2      .1       0  4679.2     .08       0
  4883.7     .05       0  4983.6     .07       0  5011.4     .07       0
  5017.4     .07       0  5192.4     .05       0
Bank Sta=5011.4,5017.4
XS Rating Curve= 0 ,0
Exp/Cntr=0.3,0.1

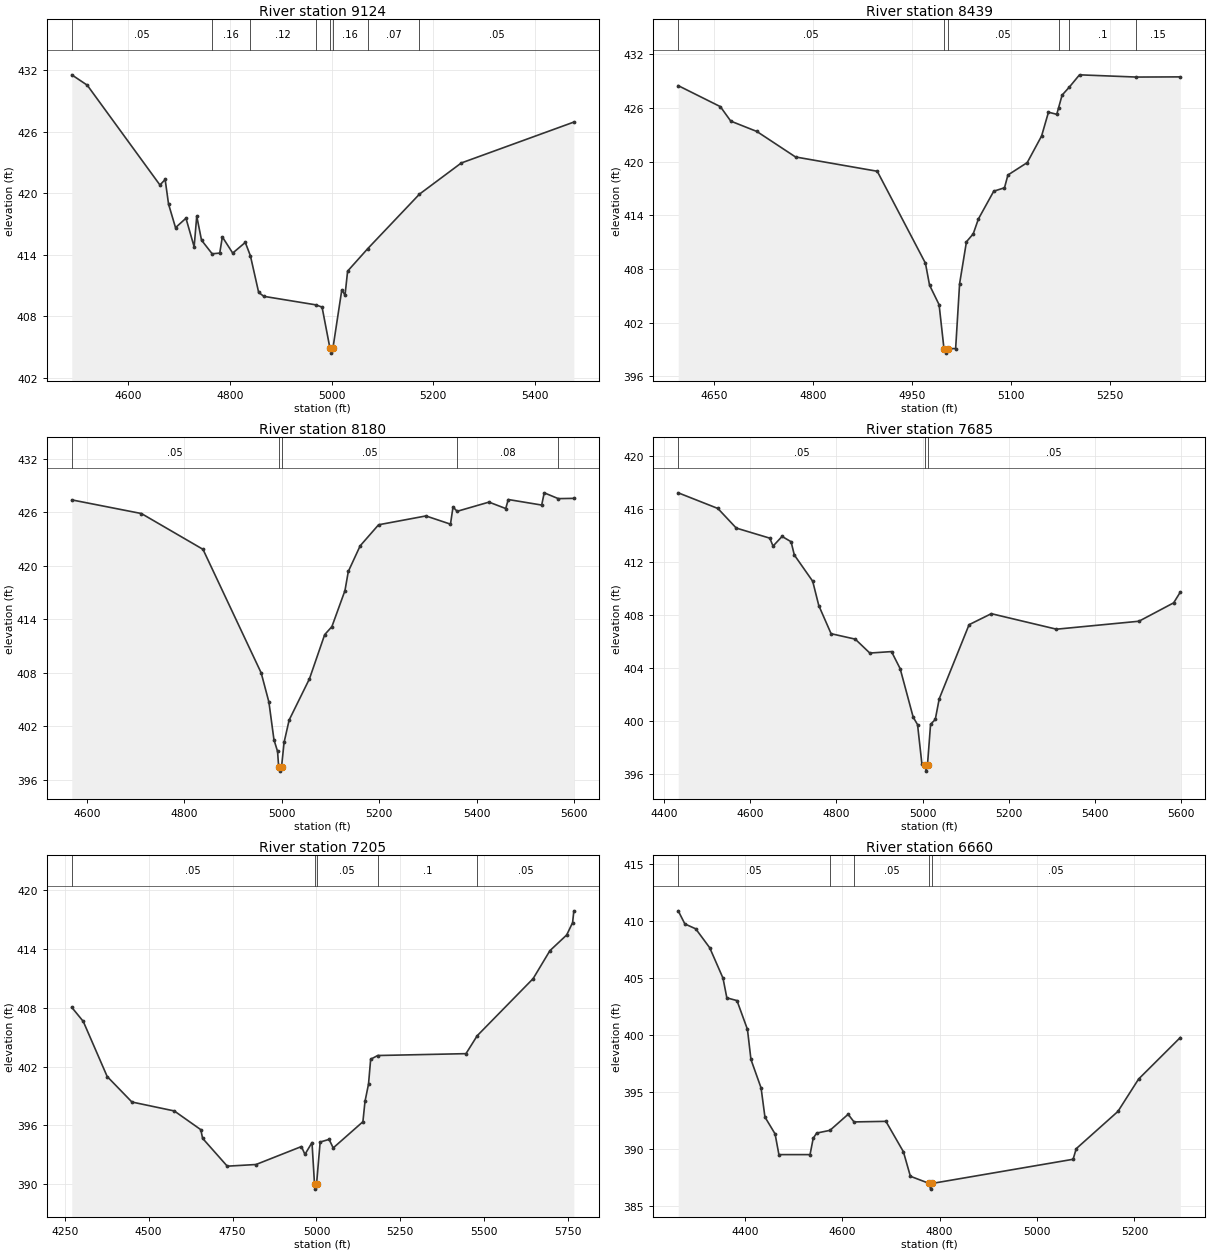
Type RM Length L Ch R = 1 ,9124    ,685,685,685
BEGIN DESCRIPTION:
UNT213 IN CCTC 17.0
END DESCRIPTION:
XS GIS Cut Line= 2
      3590749.88     10622273.94      3591716.23      10622074.6
#Sta/Elev= 30
  4489.5  431.54  4519.9  430.53  4662.8  420.79    4673  421.33  4679.7  418.93
  4693.4  416.63  4713.9  417.55    4730  414.76  4735.1  417.75  4744.5  415.41
  4765.4  414.08  4780.3  414.15  4785.4  415.73  4805.8  414.15  4830.5  415.19
  4840.6  413.88  4856.8  410.31    4867  409.93  4969.1   409.1  4981.4  408.88
  4996.8  404.89  4999.5  404.39  5002.8  404.89  5020.2  410.57  5026.5  410.04
  5031.6  412.39  5070.9  414.57  5172.8   419.9    5255  422.94  5476.2  426.93
#Mann= 8 ,-1 , 0
  4489.5     .05       0  4765.4     .16       0  4840.6     .12       0
  4969.1     .16       0  4996.8     .07       0  5002.8     .16       0
  5070.9     .07       0  5172.8     .05       0
Bank Sta=4996.8,5002.8
XS Rating Curve= 0 ,0
Exp/Cntr=0.3,0.1

Type RM Length L Ch R = 1 ,8439    ,259,259,259
BEGIN DESCRIPTION:
UNT213 IN CCTC 16.0
END DESCRIPTION:
XS GIS Cut Line= 2
      3590828.01     10622454.05      3591562.48     10622655.54
#Sta/Elev= 30
  4595.1  428.51    4659  426.16  4674.8  424.54  4714.4  423.38    4773  420.53
    4897  418.93  4970.1  408.64  4976.3  406.19  4990.8     404  4998.2  399.08
  5000.9  398.58  5004.2  399.08  5015.9  399.09  5021.9  406.35  5032.3  411.04
  5042.6  411.93  5050.4  413.59  5073.7   416.7    5090  417.08  5095.2  418.51
  5124.5   419.9  5146.3  422.88  5156.7  425.54  5169.3   425.3    5172  426.02
  5177.4  427.45  5188.6  428.37  5203.8  429.72  5290.1  429.47  5356.7  429.49
#Mann= 6 ,-1 , 0
  4595.1     .05       0  4998.2     .03       0  5004.2     .05       0
    5172     .08       0  5188.6      .1       0  5290.1     .15       0
Bank Sta=4998.2,5004.2
XS Rating Curve= 0 ,0
Exp/Cntr=0.3,0.1

Type RM Length L Ch R = 1 ,8180    ,495,495,495
BEGIN DESCRIPTION:
UNT213 IN CCTC 15.0
END DESCRIPTION:
XS GIS Cut Line= 4
      3590807.06     10622570.68      3590959.96     10622753.69
      3591324.66     10622858.66      3591722.25     10622748.72
#Sta/Elev= 30
  4568.9  427.37  4711.8  425.84  4838.2  421.83  4957.7  407.98  4973.5  404.72
  4983.9  400.49  4991.3  399.19  4993.5  397.48  4996.3  396.98  4999.5  397.48
  5004.7  400.21  5015.1  402.71  5056.8  407.33    5088  412.27  5102.8  413.17
  5129.6   417.2  5136.5  419.35  5160.8  422.22  5198.6  424.58  5295.8  425.57
  5346.2  424.65  5351.4  426.57  5359.9  426.09  5425.2  427.12  5459.6   426.4
  5464.8  427.41  5533.4  426.79  5538.6  428.16  5567.5  427.51  5599.4  427.54
#Mann= 5 ,-1 , 0
  4568.9     .05       0  4993.5     .04       0  4999.5     .05       0
  5359.9     .08       0  5567.5     .05       0
Bank Sta=4993.5,4999.5
XS Rating Curve= 0 ,0
Exp/Cntr=0.3,0.1

Type RM Length L Ch R = 1 ,7685    ,480,480,480
BEGIN DESCRIPTION:
UNT213 IN CCTC 14.0
END DESCRIPTION:
XS GIS Cut Line= 3
      3590664.85     10622934.98       3590961.7     10623268.29
      3591674.91     10623351.59
#Sta/Elev= 30
  4433.2   417.2  4525.1  416.02  4567.8  414.54  4645.5  413.78  4653.1  413.18
    4674  413.91  4694.9  413.51  4702.4  412.51    4745  410.53  4759.2  408.69
  4787.7  406.57  4843.7  406.16  4877.5  405.11  4927.8  405.22  4947.9  403.93
  4978.1  400.27  4988.2  399.71  4998.2  396.77  5005.3   396.7  5008.1   396.2
  5011.3   396.7  5018.4  399.73  5029.3   400.1  5038.5  401.66  5107.7  407.25
  5159.3  408.08  5310.4  406.91  5501.6  407.51  5582.2   408.9  5597.6  409.71
#Mann= 3 ,-1 , 0
  4433.2     .05       0  5005.3     .03       0  5011.3     .05       0
Bank Sta=5005.3,5011.3
XS Rating Curve= 0 ,0
Exp/Cntr=0.3,0.1

Type RM Length L Ch R = 1 ,7205    ,545,545,545
BEGIN DESCRIPTION:
UNT213 IN CCTC 13.0
END DESCRIPTION:
XS GIS Cut Line= 3
      3590289.35     10623505.43      3591136.76     10623783.01
      3591740.92     10623795.21
#Sta/Elev= 30
  4270.9  408.04  4305.1  406.61  4376.4  400.99  4450.1  398.39  4576.3  397.48
  4655.4  395.57  4660.7  394.69  4734.2  391.85  4819.9  392.02  4955.2  393.85
  4965.7  393.05  4986.7  394.26  4994.2  390.01    4997  389.51  5000.2  390.01
    5011  394.31  5037.6  394.58  5049.9  393.71  5138.4  396.38  5144.6  398.45
  5155.1  400.22  5161.5  402.75  5182.4  403.13  5445.5  403.32    5479  405.15
  5645.6  410.97  5695.6  413.82  5745.6  415.42  5763.2  416.68  5766.9  417.88
#Mann= 5 ,-1 , 0
  4270.9     .05       0  4994.2     .03       0  5000.2     .05       0
  5182.4      .1       0    5479     .05       0
Bank Sta=4994.2,5000.2
XS Rating Curve= 0 ,0
Exp/Cntr=0.3,0.1

Type RM Length L Ch R = 1 ,6660    ,495,495,495
BEGIN DESCRIPTION:
UNT213 IN CCTC 12.0
END DESCRIPTION:
XS GIS Cut Line= 3
      3590399.62     10624710.18      3590949.61     10624260.19
      3591199.63     10624060.17
#Sta/Elev= 30
  4263.5  410.87  4277.1  409.72  4299.4  409.29  4328.1  407.63  4355.4  404.96
  4363.3  403.23  4384.1  402.99  4405.6  400.46  4412.8  397.82  4433.6  395.32
  4441.5  392.77  4462.3  391.29  4470.2  389.47  4534.1  389.47  4540.6   390.9
  4547.7  391.36    4575   391.6  4612.3  393.01  4624.4  392.34  4689.9  392.39
  4725.8  389.72  4740.1  387.57  4778.7  386.94  4781.5  386.44  4784.7  386.94
  5074.2  389.06  5080.6  389.99  5166.2  393.26  5208.6   396.1  5294.3  399.75
#Mann= 5 ,-1 , 0
  4263.5     .05       0    4575     .12       0  4624.4     .05       0
  4778.7     .03       0  4784.7     .05       0
Bank Sta=4778.7,4784.7
XS Rating Curve= 0 ,0
Exp/Cntr=0.3,0.1

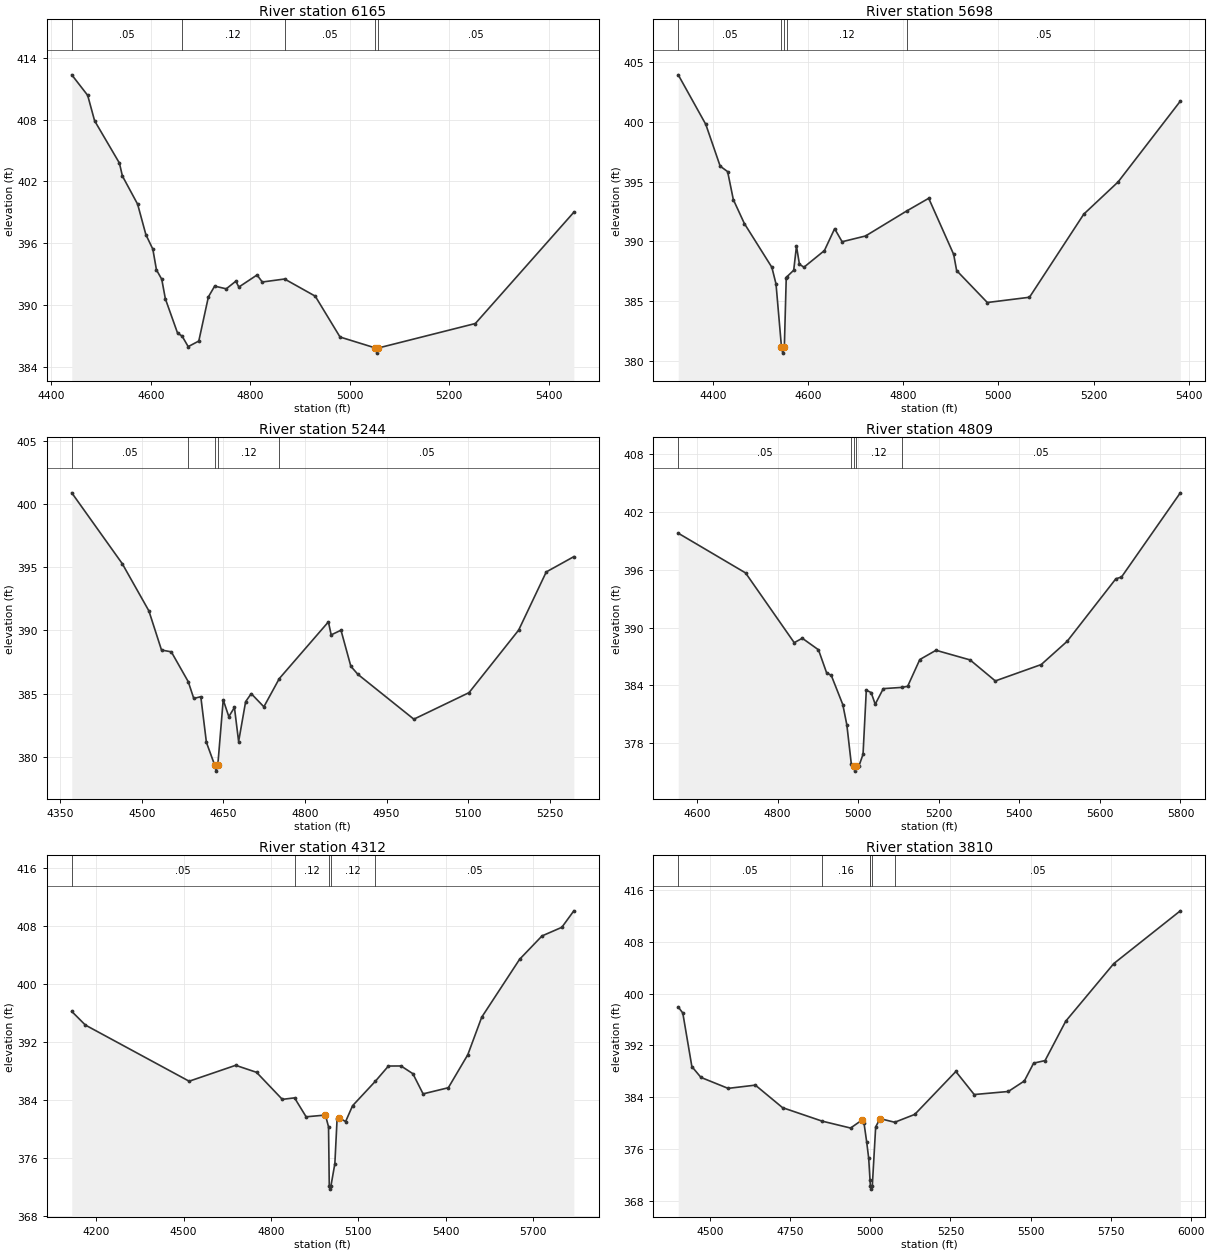
Type RM Length L Ch R = 1 ,6165    ,467,467,467
BEGIN DESCRIPTION:
UNT213 IN CCTC 11.0
END DESCRIPTION:
XS GIS Cut Line= 3
      3590449.58      10624860.2      3590999.61     10624660.19
      3591299.59     10624360.21
#Sta/Elev= 30
  4440.8  412.33  4472.8  410.34  4486.7  407.88  4536.6  403.78  4542.6  402.53
  4573.2   399.8  4589.8  396.85  4603.8  395.44  4611.1  393.43  4621.7  392.53
    4629  390.63  4653.6   387.3  4662.5  387.03  4674.9     386  4696.2  386.54
  4715.5  390.82  4728.1  391.86  4751.4   391.6  4770.7  392.34  4776.7  391.77
  4813.3  392.94  4823.9  392.26  4868.7  392.55  4930.3  390.89  4980.2  386.93
  5051.3  385.87  5054.1  385.37  5057.3  385.87  5252.3  388.24  5450.3  399.02
#Mann= 5 ,-1 , 0
  4440.8     .05       0  4662.5     .12       0  4868.7     .05       0
  5051.3     .03       0  5057.3     .05       0
Bank Sta=5051.3,5057.3
XS Rating Curve= 0 ,0
Exp/Cntr=0.3,0.1

Type RM Length L Ch R = 1 ,5698    ,454,454,454
BEGIN DESCRIPTION:
UNT213 IN CCTC 10.0
END DESCRIPTION:
XS GIS Cut Line= 3
      3590699.58      10625360.2      3591299.61     10625010.19
       3591599.6     10624810.19
#Sta/Elev= 30
  4327.2  403.92  4385.1  399.78  4415.3  396.29    4431  395.83    4443  393.49
  4466.2  391.49    4524  387.83  4532.7  386.44  4544.2  381.16  4546.9  380.66
  4550.2  381.16  4554.2  386.96    4555  387.02  4569.9  387.59  4575.7   389.6
  4581.9  388.09  4591.4  387.84  4634.4  389.23  4655.9  391.06  4671.6  389.97
  4720.8  390.45  4807.3  392.54  4853.6   393.6  4906.1  388.91  4912.3  387.56
  4976.8  384.89  5065.4  385.33  5179.6  392.28  5251.7  394.97  5382.4  401.72
#Mann= 5 ,-1 , 0
  4327.2     .05       0  4544.2     .03       0  4550.2     .05       0
    4555     .12       0  4807.3     .05       0
Bank Sta=4544.2,4550.2
XS Rating Curve= 0 ,0
Exp/Cntr=0.3,0.1

Type RM Length L Ch R = 1 ,5244    ,435,435,435
BEGIN DESCRIPTION:
UNT213 IN CCTC 9.0
END DESCRIPTION:
XS GIS Cut Line= 3
      3590899.63     10625560.18      3591499.61     10625410.19
      3591799.63     10625360.19
#Sta/Elev= 30
  4371.5  400.89  4464.2  395.29  4513.2  391.55  4536.4  388.45  4554.4  388.31
  4585.5  385.95  4595.7  384.62  4608.6  384.76  4618.9  381.15  4633.9  379.37
  4636.7  378.87  4639.9  379.37  4649.8  384.51  4660.1  383.18  4670.4  383.91
  4678.1  381.21    4691  384.37  4701.3     385  4724.5  383.96  4752.8  386.19
  4843.1  390.68  4848.2  389.65  4866.2  390.02  4884.3  387.17  4897.2  386.53
  5000.1  382.98  5101.5  385.08  5192.7  390.03  5243.4  394.63  5294.1  395.84
#Mann= 5 ,-1 , 0
  4371.5     .05       0  4585.5     .12       0  4633.9     .03       0
  4639.9     .12       0  4752.8     .05       0
Bank Sta=4633.9,4639.9
XS Rating Curve= 0 ,0
Exp/Cntr=0.3,0.1

Type RM Length L Ch R = 1 ,4809    ,497,497,497
BEGIN DESCRIPTION:
UNT213 IN CCTC 8.0
END DESCRIPTION:
XS GIS Cut Line= 3
       3590913.5     10625674.87      3591633.72     10625752.45
      3592046.08     10625432.68
#Sta/Elev= 30
  4553.4   399.8  4720.5  395.68  4841.3  388.44  4861.3   388.9  4901.5   387.7
  4921.6  385.32  4933.3  385.04  4961.9  382.01  4971.9  379.91    4983  375.84
    4989  375.61  4991.8  375.11    4995  375.61  5002.1  375.66  5012.1  376.86
  5020.2  383.51  5032.3  383.26  5042.3  382.05  5062.4  383.67  5108.5   383.8
  5122.8  383.91    5153  386.69  5193.2  387.65  5277.8  386.65  5340.4  384.47
  5454.4  386.17  5518.7  388.58  5639.6  395.07  5653.6  395.25  5799.6  403.99
#Mann= 5 ,-1 , 0
  4553.4     .05       0    4983     .12       0    4989     .07       0
    4995     .12       0  5108.5     .05       0
Bank Sta=4989,4995
XS Rating Curve= 0 ,0
Exp/Cntr=0.3,0.1

Type RM Length L Ch R = 1 ,4312    ,502,502,502
BEGIN DESCRIPTION:
UNT213 IN CCTC 7.0
END DESCRIPTION:
XS GIS Cut Line= 3
       3590771.3     10625782.96      3591417.13       10626184.
      3592307.79      10625814.2
#Sta/Elev= 30
  4116.1  396.23  4162.7  394.35  4519.3  386.58  4679.1  388.78  4750.8  387.81
  4839.3  384.07  4881.3  384.28  4921.1  381.66  4987.3   381.9  4998.1  380.27
  5000.6  372.16  5003.3  371.66  5006.6  372.16  5019.8  375.18  5027.4  381.32
  5032.9  381.56  5056.7     381  5080.6  383.19    5159  386.58  5203.8  388.68
  5247.1  388.69  5287.8  387.62  5322.9  384.83  5409.6  385.68  5476.5  390.25
  5524.2  395.43  5654.4  403.44  5731.4  406.67  5799.4  407.86  5840.7  410.14
#Mann= 5 ,-1 , 0
  4116.1     .05       0  4881.3     .12       0  5000.6     .07       0
  5006.6     .12       0    5159     .05       0
Bank Sta=4987.3,5032.9
XS Rating Curve= 0 ,0
Exp/Cntr=0.3,0.1

Type RM Length L Ch R = 1 ,3810    ,377,377,377
BEGIN DESCRIPTION:
UNT213 IN CCTC 6.0
END DESCRIPTION:
XS GIS Cut Line= 3
      3591249.57     10626960.22      3591649.61     10626560.19
      3592449.58     10625960.21
#Sta/Elev= 30
  4401.3  397.93  4415.5     397  4443.8  388.75  4472.1  387.08  4556.9  385.39
  4641.8  385.89  4726.6  382.42  4849.6  380.35  4938.8  379.28  4974.3  380.51
  4980.6  380.06  4988.9  377.16  4995.2  374.65  4999.3  371.34  5000.5  370.37
  5003.2  369.87  5006.5  370.37    5017  379.45  5030.6  380.73  5076.4  380.17
  5138.9  381.38    5267  387.99  5324.3  384.44  5430.6  384.91  5480.6  386.53
  5509.7  389.28  5545.2  389.67  5609.7  395.74  5759.7  404.62    5967  412.74
#Mann= 6 ,-1 , 0
  4401.3     .05       0  4849.6     .16       0  4999.3     .12       0
  5000.5     .07       0  5006.5     .12       0  5076.4     .05       0
Bank Sta=4974.3,5030.6
XS Rating Curve= 0 ,0
Exp/Cntr=0.3,0.1

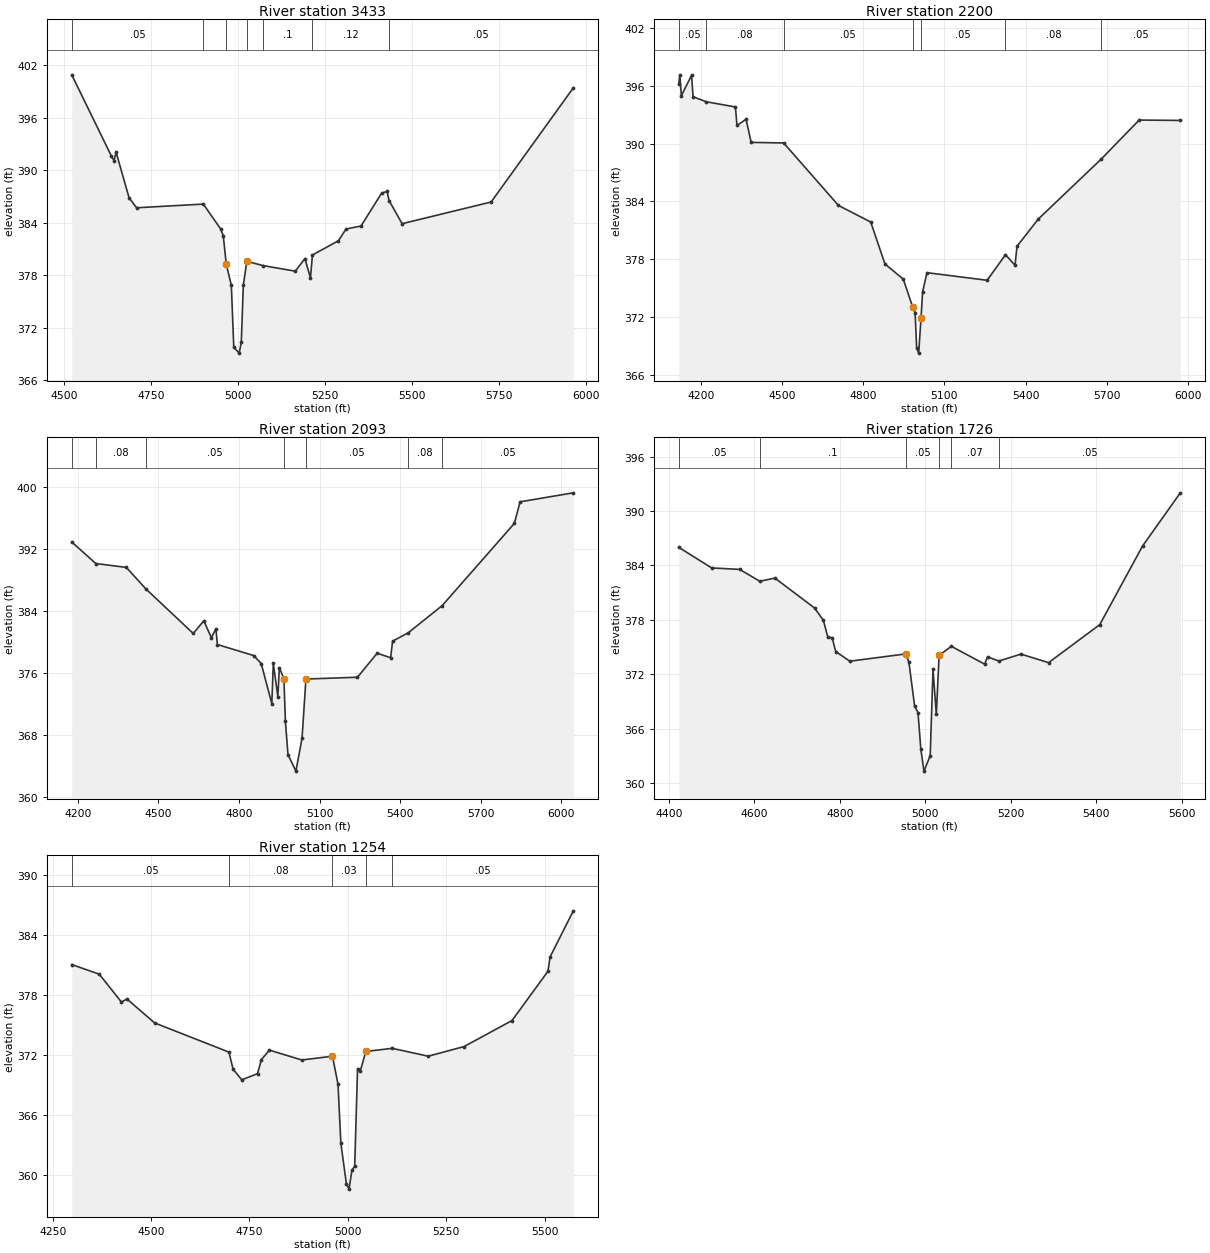
Type RM Length L Ch R = 1 ,3433    ,1233,1233,1233
BEGIN DESCRIPTION:
UNT213 IN CCTC 5.0
END DESCRIPTION:
XS GIS Cut Line= 2
      3591250.45      10627116.3      3592505.18     10626403.03
#Sta/Elev= 30
    4521   400.9  4635.1  391.61  4642.7  391.09  4648.5  392.07    4686  386.84
  4707.6   385.7  4899.6  386.12  4949.8  383.26  4957.1  382.48  4965.7  379.23
  4980.2  376.85  4987.3  369.76  5002.9  369.08  5008.9  370.32  5014.7  376.83
  5024.8  379.58  5071.4  379.09  5164.2  378.45    5192  379.89  5207.9  377.68
  5213.6   380.3  5288.6  381.93  5310.2  383.27  5353.4  383.61  5412.6  387.37
  5428.4  387.57  5434.2  386.52  5471.7  383.88  5727.8  386.36  5964.3  399.41
#Mann= 7 ,-1 , 0
    4521     .05       0  4899.6     .07       0  4965.7     .05       0
  5024.8     .08       0  5071.4      .1       0  5213.6     .12       0
  5434.2     .05       0
Bank Sta=4965.7,5024.8
XS Rating Curve= 0 ,0
Exp/Cntr=0.3,0.1

Type RM Length L Ch R = 1 ,2200    ,107,107,107
BEGIN DESCRIPTION:
UNT213 IN CCTC 4.0
END DESCRIPTION:
XS GIS Cut Line= 6
      3591240.95     10628015.33      3591362.46     10627798.35
      3591457.95     10627728.91      3592204.47     10627346.96
      3592278.26     10627277.52      3592530.01     10626795.72
#Sta/Elev= 30
  4119.2  396.19    4123  397.15  4128.8  394.98  4166.4   397.1  4172.1  394.87
  4221.1  394.35  4328.5  393.81  4334.2  391.89  4367.9  392.53  4386.6  390.13
  4506.6  390.07    4709  383.58  4828.3  381.85  4880.7   377.5  4948.4  375.92
  4982.9  373.05  4992.2   372.4  4997.9  368.78  5005.4  368.23  5014.1   371.9
  5019.8  374.58    5036  376.59  5258.4   375.8    5326  378.46  5361.3  377.36
  5368.6  379.33  5447.1  382.16  5680.6  388.42  5819.8  392.45  5971.9  392.41
#Mann= 7 ,-1 , 0
  4119.2     .05       0  4221.1     .08       0  4506.6     .05       0
  4982.9     .04       0  5014.1     .05       0    5326     .08       0
  5680.6     .05       0
Bank Sta=4982.9,5014.1
XS Rating Curve= 0 ,0
Exp/Cntr=0.3,0.1

Type RM Length L Ch R = 1 ,2093    ,367,367,367
BEGIN DESCRIPTION:
UNT213 IN CCTC 3.0
END DESCRIPTION:
XS GIS Cut Line= 6
      3591327.73     10628041.42      3591401.52      10627889.5
      3591488.33     10627820.05       3592260.9     10627429.43
      3592569.06     10626999.74      3592642.07     10626823.46
#Sta/Elev= 30
  4177.4  392.88    4267   390.1  4380.5   389.6  4453.8  386.81  4629.6  381.08
    4669  382.71  4697.1  380.53    4714  381.67  4719.6  379.65  4854.6  378.23
  4882.6   377.2  4922.1  372.03  4927.6  377.21  4944.6  372.93  4950.1  376.66
  4967.1  375.25  4972.6  369.75  4982.3  365.45  5011.8  363.32  5034.6  367.57
  5049.1   375.2  5240.9  375.43  5314.2  378.53  5364.3  377.95  5371.7  380.09
  5429.4  381.15  5556.1  384.67    5825  395.28  5846.1  398.06  6044.3  399.22
#Mann= 7 ,-1 , 0
  4177.4     .05       0    4267     .08       0  4453.8     .05       0
  4967.1     .04       0  5049.1     .05       0  5429.4     .08       0
  5556.1     .05       0
Bank Sta=4967.1,5049.1
XS Rating Curve= 0 ,0
Exp/Cntr=0.3,0.1

Type RM Length L Ch R = 1 ,1726    ,472,472,472
BEGIN DESCRIPTION:
UNT213 IN CCTC 2.0
END DESCRIPTION:
XS GIS Cut Line= 3
      3591731.35     10628024.06      3592152.39     10627919.88
      3592629.84     10627355.62
#Sta/Elev= 30
  4423.5     386  4500.5  383.73  4565.9  383.57  4612.9  382.26  4648.3  382.61
  4741.1  379.31  4761.7  377.95    4772  376.12  4782.3  376.03  4790.5  374.51
  4823.5  373.45  4954.3  374.25  4961.6  373.35  4975.2  368.46  4982.9  367.79
  4989.5  363.78  4996.9  361.33  5011.5  363.04    5018  372.54  5025.8  367.62
  5032.3  374.09  5060.9  375.09  5138.9  373.12  5145.5  373.93  5171.9  373.47
  5223.6  374.23  5288.4  373.29    5408  377.48  5508.1  386.15  5596.4  392.01
#Mann= 6 ,-1 , 0
  4423.5     .05       0  4612.9      .1       0  4954.3     .05       0
  5032.3      .1       0  5060.9     .07       0  5171.9     .05       0
Bank Sta=4954.3,5032.3
XS Rating Curve= 0 ,0
Exp/Cntr=0.3,0.1

Type RM Length L Ch R = 1 ,1254    ,0,0,0
BEGIN DESCRIPTION:
UNT213 IN CCTC 1.0
END DESCRIPTION:
XS GIS Cut Line= 4
      3591870.23      10628158.6      3592404.13     10628102.17
      3592582.08     10627928.56      3592664.55     10627446.75
#Sta/Elev= 30
  4298.4  381.06  4368.2   380.1  4424.7   377.3  4438.6  377.61  4508.9  375.21
  4697.8  372.28  4708.2  370.58  4730.2   369.5  4770.4  370.12  4780.4  371.54
  4800.6  372.48    4883  371.49  4960.8  371.87  4974.9  369.06  4982.1  363.15
  4996.2  359.07  5002.9  358.54  5010.3  360.45  5017.3  360.84  5024.5  370.58
  5031.5  370.39  5045.1  372.28  5045.6  372.35  5112.7  372.66    5204  371.87
  5295.3  372.84    5417  375.45  5508.3  380.39  5513.6  381.82  5572.7  386.45
#Mann= 5 ,-1 , 0
  4298.4     .05       0  4697.8     .08       0  4960.8     .03       0
  5045.1     .07       0  5112.7     .05       0
Bank Sta=4960.8,5045.6
XS Rating Curve= 0 ,0
Exp/Cntr=0.3,0.1

Chan Stop Cuts=-1
Use User Specified Reach Order=0
Composite Channel Slope=5