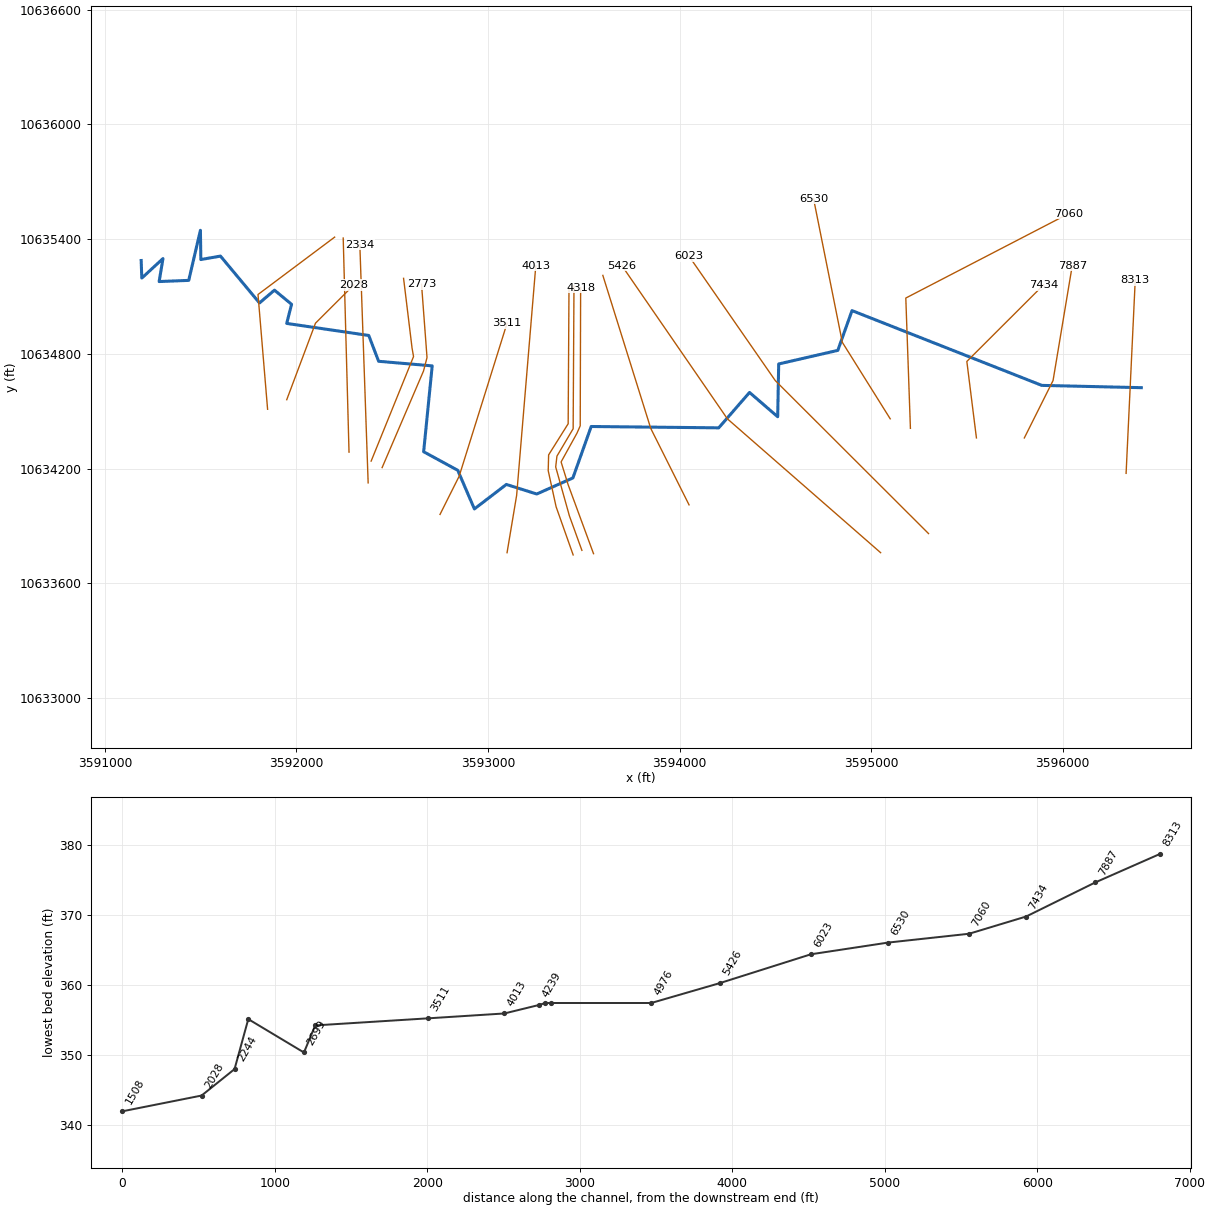
--- UNT214 IN CCTC.prj (project) ---

Proj Title=UNT214 IN CCTC Base Level Engineering
Current Plan=p01
Default Exp/Contr=0.3,0.1
English Units
Geom File=g01
Flow File=f01
Plan File=p01
Y Axis Title=Elevation
X Axis Title(PF)=Main Channel Distance
X Axis Title(XS)=Station
BEGIN DESCRIPTION:
UNT214 IN CCTC
END DESCRIPTION:
DSS Export Rating Curves= 0
DSS Export Rating Curve Sorted= 0
DSS Export Volume Flow Curves= 0
DXF OffsetX= 0
DXF OffsetY= 0
DXF ScaleX= 1
DXF ScaleY= 10

--- UNT214 IN CCTC.p01 (plan) ---

Plan Title=Multiple Run
Short Identifier=Multiple
Geom File=g01
Flow File=f01
Subcritical Flow
K Sum by GR= 0
Std Step Tol= 0.01
Critical Tol= 0.01
Num of Std Step Trials= 20
Max Error Tol= 0.3
Flow Tol Ratio= 0.001
Split Flow NTrial= 30
Split Flow Tol= 0.02
Split Flow Ratio= 0.02
Log Output Level= 0
Friction Slope Method= 1
Unsteady Friction Slope Method= 2
Unsteady Bridges Friction Slope Method= 1
Parabolic Critical Depth
Global Vel Dist=  1 , 1 , 1
Global Log Level= 0
CheckData=True
Encroach Param= -1, 0, 0, 0
BEGIN DESCRIPTION:
Multiple Run
END DESCRIPTION:

--- UNT214 IN CCTC.f01 (steady flow) ---

Flow Title=Multiple
Number of Profiles=7
Profile Names=10-year,25-year,50-year,1pct_min,100-year,1pct_plu,500-year
River Rch & RM= UNT214 IN CCTC,Reach-1,8313
    1325    1810    2208    1966    2659    3596    3841
River Rch & RM= UNT214 IN CCTC,Reach-1,7887
    2253    3159    3922    3546    4795    6485    7148
Boundary for River Rch & Prof#=UNT214 IN CCTC,Reach-1,1
Up Type=0
Dn Type=3
Dn Slope=0.005
Boundary for River Rch & Prof#=UNT214 IN CCTC,Reach-1,2
Up Type=0
Dn Type=3
Dn Slope=0.005
Boundary for River Rch & Prof#=UNT214 IN CCTC,Reach-1,3
Up Type=0
Dn Type=3
Dn Slope=0.005
Boundary for River Rch & Prof#=UNT214 IN CCTC,Reach-1,4
Up Type=0
Dn Type=3
Dn Slope=0.005
Boundary for River Rch & Prof#=UNT214 IN CCTC,Reach-1,5
Up Type=0
Dn Type=3
Dn Slope=0.005
Boundary for River Rch & Prof#=UNT214 IN CCTC,Reach-1,6
Up Type=0
Dn Type=3
Dn Slope=0.005
Boundary for River Rch & Prof#=UNT214 IN CCTC,Reach-1,7
Up Type=0
Dn Type=3
Dn Slope=0.005

--- UNT214 IN CCTC.g01 (geometry) ---

Geom Title=Existing Conditions
Program Version=4.10

River Reach=UNT214 IN CCTC  ,Reach-1
Reach XY= 30
      3596410.25       10634623.      3595890.75       10634635.
      3594900.25       10635026.        3594826.       10634818.
       3594517.5       10634747.      3594512.25       10634471.
      3594365.25       10634598.       3594204.5       10634413.
      3593538.75       10634420.      3593443.25       10634151.
       3593254.5       10634067.        3593096.       10634117.
        3592929.       10633989.      3592842.25       10634191.
      3592664.25       10634288.      3592708.75       10634737.
      3592429.25       10634761.      3592377.75       10634896.
       3591949.5       10634959.      3591974.75       10635059.
       3591885.5       10635133.      3591807.25       10635066.
      3591603.75       10635311.      3591501.25       10635293.
        3591499.       10635446.        3591438.       10635184.
       3591283.5       10635178.       3591303.5       10635298.
        3591193.       10635196.      3591189.75       10635288.

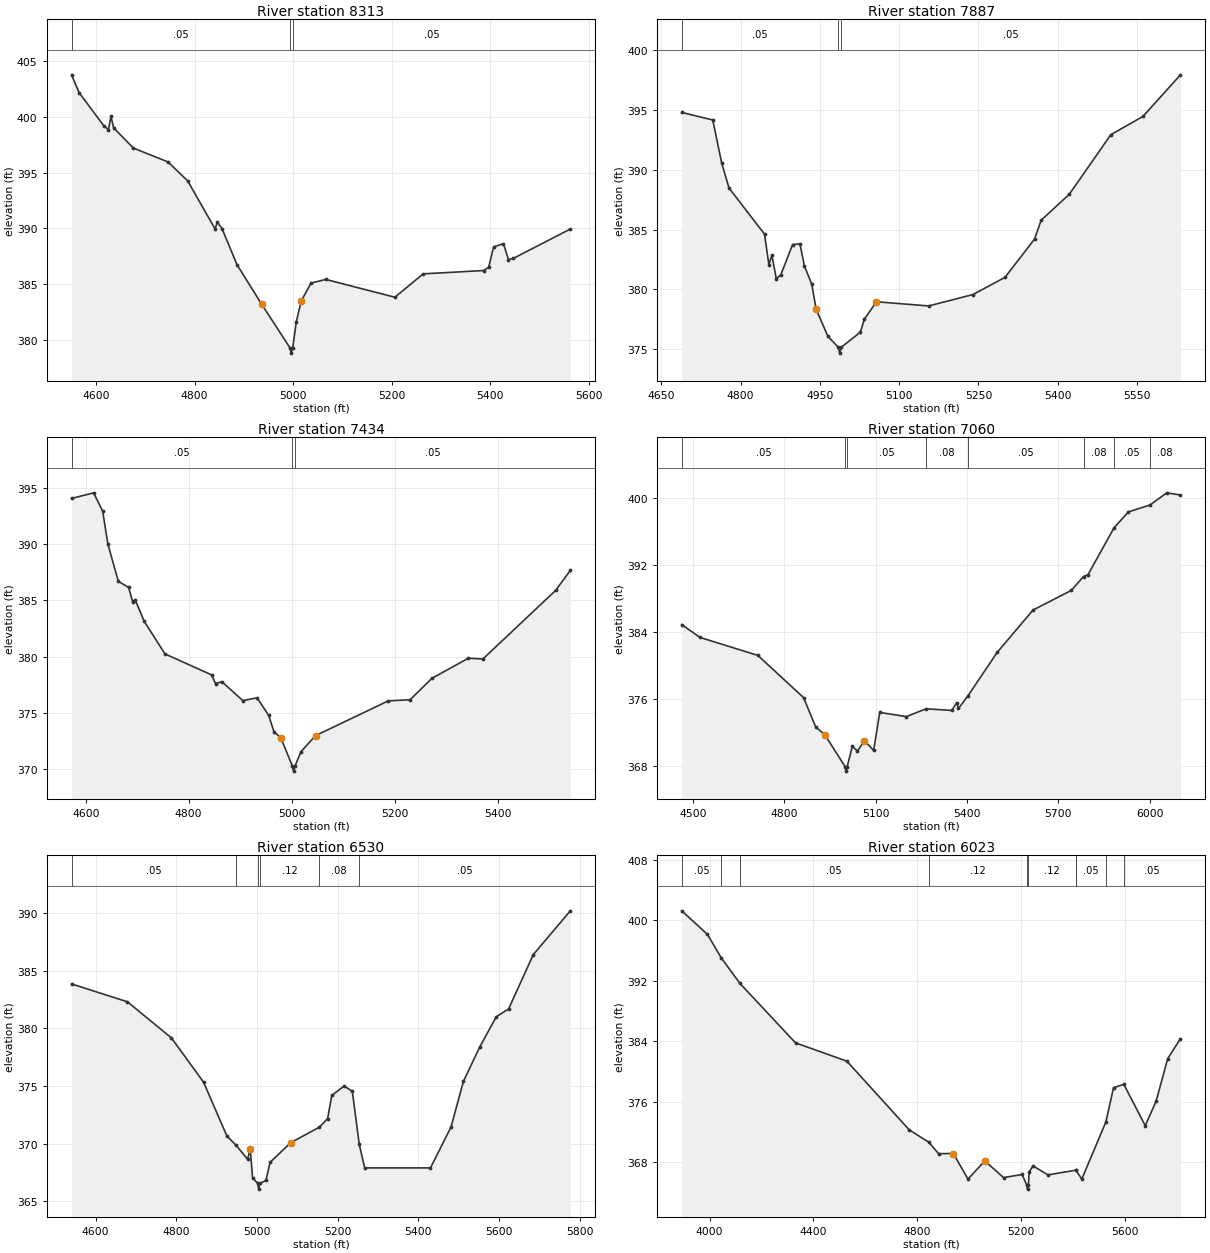
Type RM Length L Ch R = 1 ,8313    ,426,426,426
BEGIN DESCRIPTION:
UNT214 IN CCTC 15.0
END DESCRIPTION:
XS GIS Cut Line= 2
      3596330.87     10634175.02      3596378.59      10635185.7
#Sta/Elev= 30
  4550.6  403.78  4565.8  402.18  4615.8  399.21  4625.3  398.86  4630.4  400.04
  4635.9  399.02  4675.9   397.2    4746  395.96    4786  394.26  4841.5  389.95
  4846.5  390.55  4856.1  389.93  4886.1  386.73  4936.2  383.17  4993.3  379.28
    4996  378.78  4999.3  379.28  5006.3  381.55  5016.3  383.45  5036.3  385.07
  5066.3   385.4  5206.5   383.8  5263.8   385.9  5386.7   386.2  5396.7  386.49
  5406.7  388.32  5426.7  388.62  5436.8  387.19  5446.8  387.29  5562.4  389.93
#Mann= 3 ,-1 , 0
  4550.6     .05       0  4993.3     .03       0  4999.3     .05       0
Bank Sta=4936.2,5016.3
XS Rating Curve= 0 ,0
Exp/Cntr=0.3,0.1

Type RM Length L Ch R = 1 ,7887    ,453,453,453
BEGIN DESCRIPTION:
UNT214 IN CCTC 14.0
END DESCRIPTION:
XS GIS Cut Line= 3
      3595799.59     10634360.16      3595949.61     10634660.19
      3596049.61     10635260.17
#Sta/Elev= 30
  4688.7  394.78  4747.4  394.15  4764.2  390.57  4778.2  388.46  4845.3  384.62
  4853.6  382.06  4859.2  382.86  4867.6   380.9    4876   381.2  4898.4  383.74
  4912.3  383.81  4920.7  381.98  4934.7  380.43  4943.1  378.33  4965.4  376.07
  4984.8  375.18  4987.6  374.68  4990.8  375.18  5026.7  376.43  5034.3  377.52
  5057.1  378.97  5155.9  378.62  5239.6  379.57  5300.4  381.01  5356.2   384.2
  5368.8  385.78  5422.1  387.95  5500.6  392.92  5561.5  394.45  5632.4  397.92
#Mann= 3 ,-1 , 0
  4688.7     .05       0  4984.8     .03       0  4990.8     .05       0
Bank Sta=4943.1,5057.1
XS Rating Curve= 0 ,0
Exp/Cntr=0.3,0.1

Type RM Length L Ch R = 1 ,7434    ,374,374,374
BEGIN DESCRIPTION:
UNT214 IN CCTC 13.0
END DESCRIPTION:
XS GIS Cut Line= 3
       3595549.6     10634360.24      3595499.61     10634760.19
      3595899.64     10635160.22
#Sta/Elev= 30
  4572.6  394.09  4615.4  394.59    4633  392.94  4643.1  390.02  4663.3  386.71
  4683.4  386.16    4691   384.9    4696  385.07  4713.6  383.15    4754  380.24
  4844.7  378.37  4852.2   377.6  4864.8  377.76  4905.1  376.08  4932.8  376.33
  4955.5  374.76  4965.6  373.32  4979.2  372.75    5001   370.3  5003.7   369.8
    5007   370.3  5018.1  371.53  5046.4  372.96  5187.8  376.06  5230.2  376.16
  5272.7  378.07  5343.4  379.86  5371.6  379.79  5513.1  385.91  5541.4  387.68
#Mann= 3 ,-1 , 0
  4572.6     .05       0    5001     .03       0    5007     .05       0
Bank Sta=4979.2,5046.4
XS Rating Curve= 0 ,0
Exp/Cntr=0.3,0.1

Type RM Length L Ch R = 1 ,7060    ,530,530,530
BEGIN DESCRIPTION:
UNT214 IN CCTC 12.0
END DESCRIPTION:
XS GIS Cut Line= 3
      3595205.05     10634410.45      3595180.98     10635091.71
      3596029.44     10635532.23
#Sta/Elev= 30
  4463.1  384.85  4522.9  383.32    4713  381.17  4863.1  376.12  4903.1   372.6
  4933.1  371.67  5000.2  367.83  5002.9  367.33  5006.2  367.83  5023.2   370.3
  5040.1  369.74  5063.2  370.97  5093.2   369.8  5113.2  374.35  5200.5  373.85
  5265.2  374.78  5349.7  374.59  5366.2  375.51  5371.8  374.82  5403.2  376.35
  5498.9  381.53  5616.5  386.59  5742.2  388.94  5782.4   390.6  5796.8   390.8
  5882.7  396.43    5930  398.33  6000.9  399.16  6055.9  400.61  6100.8  400.35
#Mann= 8 ,-1 , 0
  4463.1     .05       0  5000.2     .03       0  5006.2     .05       0
  5265.2     .08       0  5403.2     .05       0  5782.4     .08       0
  5882.7     .05       0  6000.9     .08       0
Bank Sta=4933.1,5063.2
XS Rating Curve= 0 ,0
Exp/Cntr=0.3,0.1

Type RM Length L Ch R = 1 ,6530    ,507,507,507
BEGIN DESCRIPTION:
UNT214 IN CCTC 11.0
END DESCRIPTION:
XS GIS Cut Line= 3
      3595099.59     10634460.22      3594849.61     10634860.19
      3594699.61     10635610.17
#Sta/Elev= 30
  4540.5  383.84    4679  382.29  4788.1  379.16  4867.7  375.33  4925.5  370.67
  4948.3  369.87  4976.8  368.66  4983.3  369.55  4989.2  367.06  5001.5  366.57
  5004.3  366.07  5007.5  366.57  5022.4  366.83  5032.6  368.39  5083.6  370.09
  5154.5  371.43  5175.3  372.18  5185.5  374.18  5216.1     375  5236.5  374.54
  5253.7  369.94  5267.1  367.91  5430.3  367.91  5481.3  371.46  5511.9   375.4
  5552.7   378.4  5593.5     381    5624  381.68  5685.2  386.38    5777  390.17
#Mann= 6 ,-1 , 0
  4540.5     .05       0  4948.3     .12       0  5001.5     .07       0
  5007.5     .12       0  5154.5     .08       0  5253.7     .05       0
Bank Sta=4983.3,5083.6
XS Rating Curve= 0 ,0
Exp/Cntr=0.3,0.1

Type RM Length L Ch R = 1 ,6023    ,597,597,597
BEGIN DESCRIPTION:
UNT214 IN CCTC 10.0
END DESCRIPTION:
XS GIS Cut Line= 3
      3595299.64     10633860.16      3594499.61     10634660.19
       3594049.6      10635310.2
#Sta/Elev= 30
  3892.8  401.28  3991.8  398.16  4044.6  395.07    4117  391.66  4331.2  383.78
  4529.2  381.35  4769.7  372.24  4843.9  370.63  4882.8  369.09  4939.4  369.11
  4995.9  365.72  5060.7  368.13    5133  365.92  5204.6  366.33  5222.6  364.89
  5225.3  364.39  5228.6  364.89  5231.7  366.66  5246.5  367.47    5304  366.28
  5411.3   366.9  5412.2  366.89  5434.4  365.72  5527.4   373.3  5556.7  377.82
  5596.4  378.29    5679   372.8  5720.9  376.04  5765.5  381.68  5814.8  384.34
#Mann= 10 ,-1 , 0
  3892.8     .05       0  4044.6     .08       0    4117     .05       0
  4843.9     .12       0  5222.6     .07       0  5228.6     .12       0
  5411.3     .08       0  5412.2     .05       0  5527.4     .08       0
  5596.4     .05       0
Bank Sta=4939.4,5060.7
XS Rating Curve= 0 ,0
Exp/Cntr=0.3,0.1

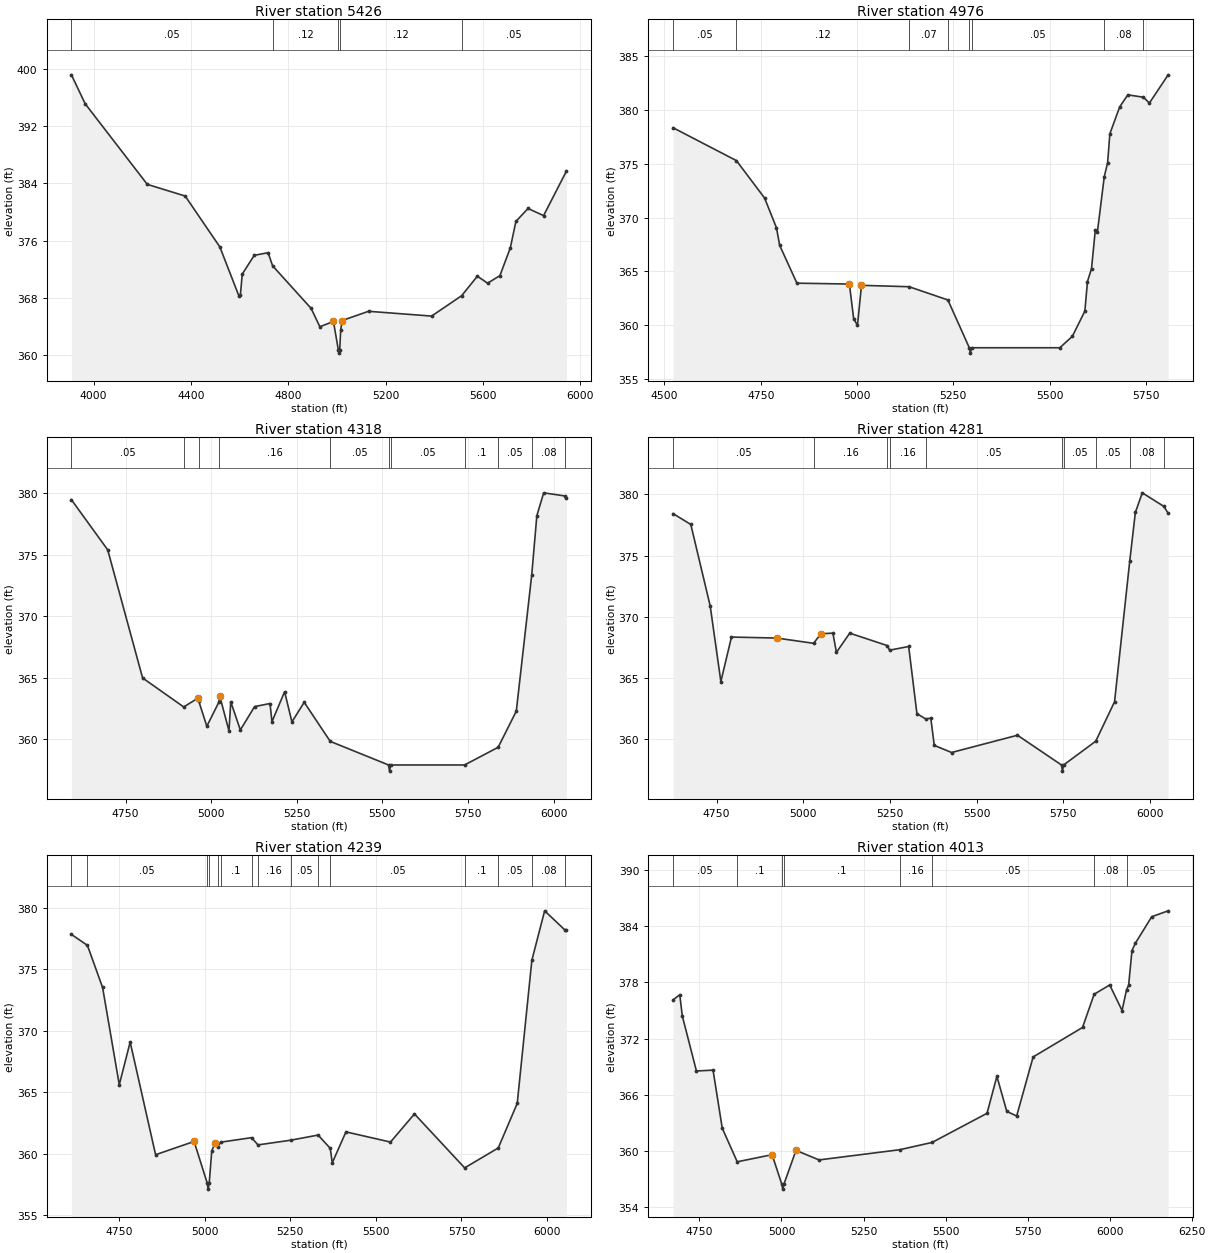
Type RM Length L Ch R = 1 ,5426    ,450,450,450
BEGIN DESCRIPTION:
UNT214 IN CCTC 9.0
END DESCRIPTION:
XS GIS Cut Line= 3
      3595049.58     10633760.21      3594249.61     10634460.19
      3593699.61     10635260.19
#Sta/Elev= 30
  3908.9  399.18  3965.3  395.14  4220.6  383.86  4376.3  382.23  4518.7  375.11
  4596.5   368.3  4603.1   368.4  4610.7  371.31  4660.1  373.94    4717   374.3
  4735.4  372.47  4893.6  366.52  4929.6  363.95  4985.4  364.69  5005.3  360.76
    5008  360.26  5011.3  360.76  5015.2  363.53  5021.2  364.82  5129.6  366.11
  5388.6  365.44  5512.1  368.29  5576.7  371.02  5618.6  370.04  5669.4   371.1
  5712.1  374.99    5735  378.68  5784.9  380.49  5848.7  379.49  5942.7  385.72
#Mann= 5 ,-1 , 0
  3908.9     .05       0  4735.4     .12       0  5005.3     .07       0
  5011.3     .12       0  5512.1     .05       0
Bank Sta=4985.4,5021.2
XS Rating Curve= 0 ,0
Exp/Cntr=0.3,0.1

Type RM Length L Ch R = 1 ,4976    ,658,658,658
BEGIN DESCRIPTION:
UNT214 IN CCTC 8.0
END DESCRIPTION:
XS GIS Cut Line= 3
      3594049.59     10634010.22      3593849.61     10634410.19
      3593599.62     10635210.16
#Sta/Elev= 30
  4522.6  378.35  4686.9   375.3  4760.1  371.82  4790.9  369.06  4799.3  367.42
    4844  363.91  4980.3  363.83  4991.3  360.62  5001.2  359.99  5011.7  363.71
  5135.3  363.58    5236  362.35  5291.6  357.91  5294.3  357.41  5297.6  357.91
  5526.6  357.91  5559.1  358.97  5591.6  361.31  5598.4  364.06  5608.9  365.27
  5618.8  368.86  5624.1  368.64    5642   373.8  5650.8  375.12  5656.5  377.79
  5682.2   380.3  5703.2  381.41  5743.5  381.19  5759.2  380.65  5807.9  383.27
#Mann= 8 ,-1 , 0
  4522.6     .05       0  4686.9     .12       0  5135.3     .07       0
    5236     .05       0  5291.6     .07       0  5297.6     .05       0
    5642     .08       0  5743.5     .05       0
Bank Sta=4980.3,5011.7
XS Rating Curve= 0 ,0
Exp/Cntr=0.3,0.1

Type RM Length L Ch R = 1 ,4318    ,37,37,37
BEGIN DESCRIPTION:
UNT214 IN CCTC 7.0
END DESCRIPTION:
XS GIS Cut Line= 6
      3593550.93     10633755.05      3593418.56      10634115.3
      3593381.66     10634234.65      3593464.13     10634384.39
      3593481.49     10634423.46      3593483.65     10635146.73
#Sta/Elev= 30
  4591.7  379.49  4697.7  375.41  4799.6  364.99  4919.7  362.63  4961.3  363.35
  4963.5  363.12  4987.2  361.06    5022     363  5024.8  363.53  5051.9  360.68
  5057.1  363.05  5085.1  360.76  5126.7  362.66  5171.8  362.91  5177.4  361.43
  5214.4  363.87  5235.7  361.41  5271.6  363.01  5347.7  359.83  5518.1  357.91
  5520.8  357.41  5524.1  357.91    5740  357.91  5838.1  359.35  5891.1  362.29
  5936.2  373.38  5951.1  378.19  5971.1  380.05  6034.3  379.79  6037.6  379.65
#Mann= 11 ,-1 , 0
  4591.7     .05       0  4919.7     .16       0  4963.5     .05       0
    5022     .16       0  5347.7     .05       0  5518.1     .03       0
  5524.1     .05       0    5740      .1       0  5838.1     .05       0
  5936.2     .08       0  6034.3     .05       0
Bank Sta=4961.3,5024.8
XS Rating Curve= 0 ,0
Exp/Cntr=0.3,0.1

Type RM Length L Ch R = 1 ,4281    ,42,42,42
BEGIN DESCRIPTION:
Mapping XS bf11db99
END DESCRIPTION:
XS GIS Cut Line= 6
      3593490.18     10633772.37      3593425.07     10633952.54
      3593353.45     10634208.61      3593359.96     10634265.04
       3593444.6     10634408.27      3593448.94     10635154.79
#Sta/Elev= 30
  4624.7  378.42  4675.7  377.54  4731.7  370.88  4762.4  364.72    4793  368.35
  4923.3  368.27  5029.8  367.84    5051  368.62  5085.6  368.67  5095.7   367.1
  5134.1  368.67  5242.9  367.65  5248.8  367.28  5304.1  367.58  5327.9   362.1
  5353.1  361.67  5367.9  361.73  5377.9  359.51  5427.9  358.93  5617.9  360.34
  5744.9  357.91  5747.6  357.41  5750.9  357.91  5843.6  359.85  5897.9  363.07
  5941.7  374.55  5957.9  378.52  5977.9  380.12  6039.7  379.02  6052.5  378.46
#Mann= 10 ,-1 , 0
  4624.7     .05       0  5029.8     .16       0  5242.9     .05       0
  5248.8     .16       0  5353.1     .05       0  5744.9     .03       0
  5750.9     .05       0  5843.6     .05       0  5941.7     .08       0
  6039.7     .05       0
Bank Sta=4923.3,5051
XS Rating Curve= 0 ,0
Exp/Cntr=0.3,0.1

Type RM Length L Ch R = 1 ,4239    ,226,226,226
BEGIN DESCRIPTION:
Mapping XS 0562cd6f
END DESCRIPTION:
XS GIS Cut Line= 6
      3593444.61     10633748.52      3593355.62     10634000.28
      3593314.39     10634189.08      3593316.56     10634271.55
      3593418.56     10634434.31       3593422.9     10635143.91
#Sta/Elev= 30
  4611.4  377.85  4658.1  376.96  4702.4  373.53  4751.1  365.62  4782.9  369.09
  4857.1  359.92  4969.5     361  5007.7  357.62  5010.5  357.12  5013.7  357.62
  5021.1  360.24  5030.8  360.88  5038.1  360.53  5046.9  360.94  5137.3  361.31
  5155.9  360.72  5251.2   361.1  5331.5  361.52    5367  360.44  5372.8  359.26
  5412.8  361.78  5542.8  360.95  5612.8  363.24  5759.3  358.85  5857.4  360.47
  5912.8   364.1  5955.5  375.75  5992.8  379.77  6053.6  378.17  6056.5  378.17
#Mann= 15 ,-1 , 0
  4611.4     .08       0  4658.1     .05       0  5007.7     .03       0
  5013.7     .05       0  5038.1     .16       0  5046.9      .1       0
  5137.3     .05       0  5155.9     .16       0  5251.2     .05       0
  5331.5     .16       0    5367     .05       0  5759.3      .1       0
  5857.4     .05       0  5955.5     .08       0  6053.6     .05       0
Bank Sta=4969.5,5030.8
XS Rating Curve= 0 ,0
Exp/Cntr=0.3,0.1

Type RM Length L Ch R = 1 ,4013    ,502,502,502
BEGIN DESCRIPTION:
UNT214 IN CCTC 6.0
END DESCRIPTION:
XS GIS Cut Line= 3
       3593099.6     10633760.15      3593149.61     10634060.19
      3593249.61     10635260.15
#Sta/Elev= 30
  4669.9  376.13  4690.2  376.68  4697.8  374.42  4740.9  368.53  4791.6  368.62
  4819.5  362.43  4865.2  358.83  4971.5  359.59  5001.2  356.41  5003.9  355.91
  5007.2  356.41  5044.3  360.05  5114.6  359.03  5360.3  360.12  5459.1   360.9
  5626.3  364.01  5656.4  367.96  5686.5  364.22  5716.6  363.72  5766.8  370.03
  5917.3  373.18  5952.7  376.73  6000.1  377.72  6037.8  374.99  6051.4   377.2
  6057.8   377.7  6067.9  381.38  6077.9  382.16  6128.1  385.01  6178.2  385.64
#Mann= 8 ,-1 , 0
  4669.9     .05       0  4865.2      .1       0  5001.2     .07       0
  5007.2      .1       0  5360.3     .16       0  5459.1     .05       0
  5952.7     .08       0  6051.4     .05       0
Bank Sta=4971.5,5044.3
XS Rating Curve= 0 ,0
Exp/Cntr=0.3,0.1

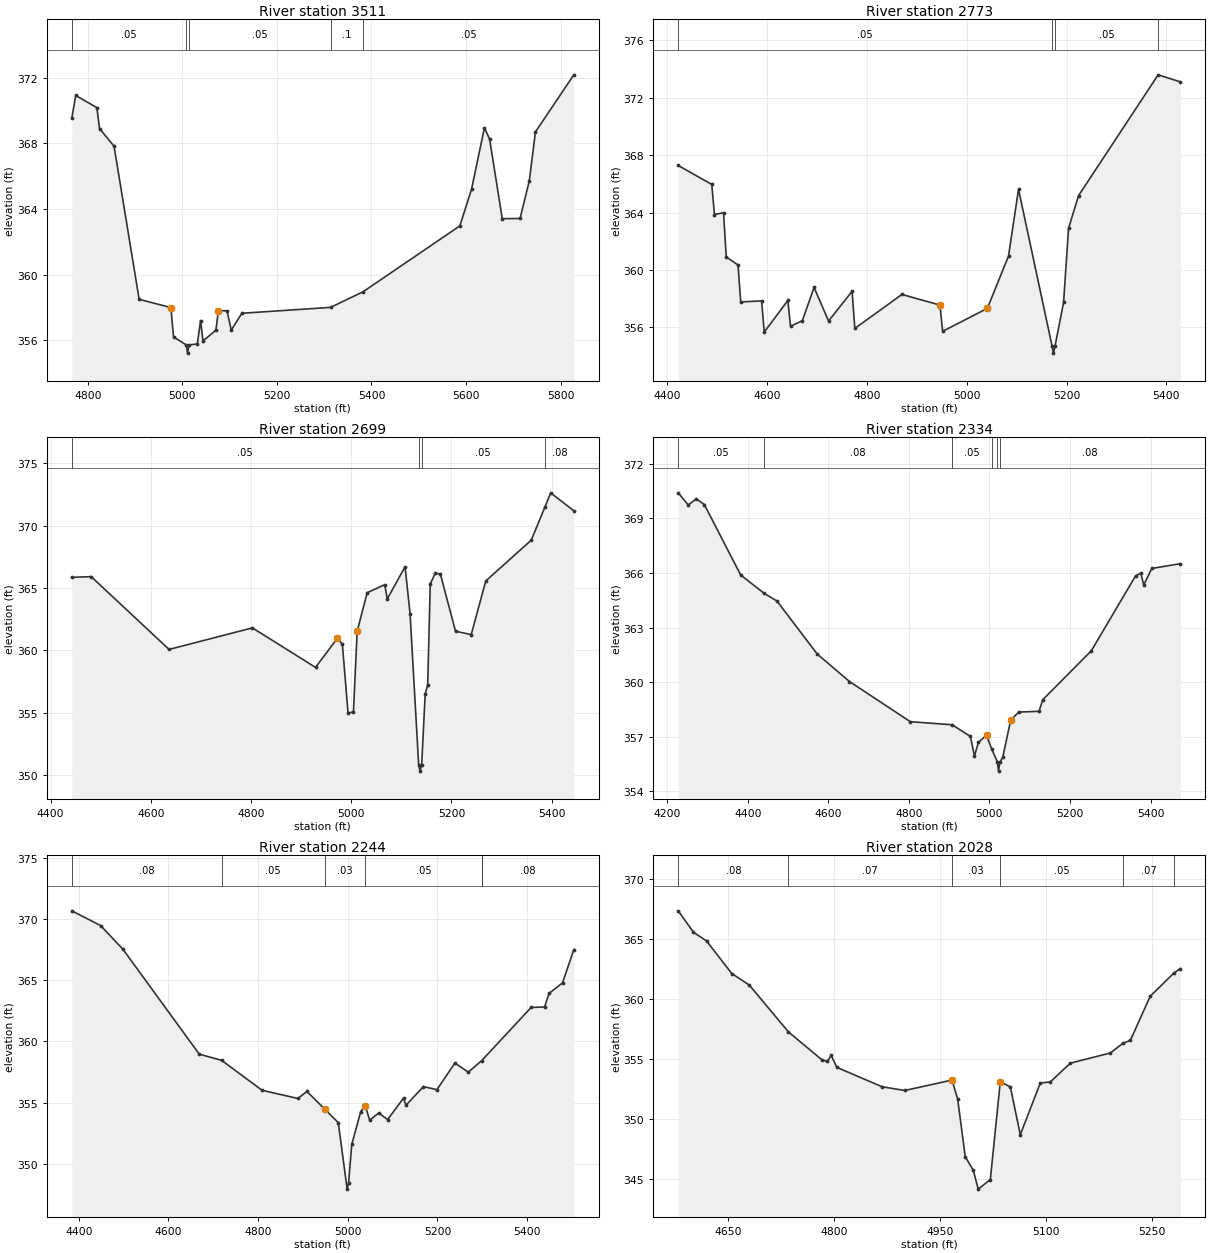
Type RM Length L Ch R = 1 ,3511    ,738,738,738
BEGIN DESCRIPTION:
UNT214 IN CCTC 5.0
END DESCRIPTION:
XS GIS Cut Line= 3
      3592749.63     10633960.23      3592849.61     10634160.19
       3593099.6     10634960.17
#Sta/Elev= 30
  4766.2  369.52  4774.5  370.92  4819.3  370.18  4824.9   368.9  4855.6  367.83
  4908.7  358.49  4975.8  357.99  4981.4   356.2  5008.2  355.71    5011  355.21
  5014.2  355.71  5031.7  355.77  5038.5  357.19  5043.7  355.95    5071  356.61
  5076.2   357.8  5094.5  357.79  5103.4  356.62    5126  357.64  5313.5     358
  5382.2  358.95  5586.9  362.97  5611.6  365.21  5638.8  368.95  5649.8  368.26
  5676.5  363.41  5714.2  363.42  5733.6   365.7  5746.7   368.7  5827.9  372.18
#Mann= 5 ,-1 , 0
  4766.2     .05       0  5008.2    .035       0  5014.2     .05       0
  5313.5      .1       0  5382.2     .05       0
Bank Sta=4975.8,5076.2
XS Rating Curve= 0 ,0
Exp/Cntr=0.3,0.1

Type RM Length L Ch R = 1 ,2773    ,74,74,74
BEGIN DESCRIPTION:
Mapping XS 60d8ad99
END DESCRIPTION:
XS GIS Cut Line= 4
      3592447.45     10634205.16      3592663.59     10634710.35
      3592681.82     10634780.66      3592653.17     10635163.48
#Sta/Elev= 30
  4421.9  367.28  4489.1  365.96  4494.5  363.86  4512.6  363.99  4518.1  360.91
  4541.7  360.34  4547.1  357.77  4588.9  357.84  4594.3  355.67  4641.5  357.87
  4646.9  356.07  4670.5  356.46  4694.1  358.78  4723.1  356.44  4770.3  358.51
  4775.7  355.92  4870.1  358.29  4946.3  357.55  4951.7  355.72  5041.2  357.32
  5083.7  360.97  5103.7  365.62  5170.9   354.7  5173.7   354.2  5176.9   354.7
    5194  357.73    5204   362.9    5224  365.18  5383.5   373.6  5427.9  373.11
#Mann= 4 ,-1 , 0
  4421.9     .05       0  5170.9     .03       0  5176.9     .05       0
  5383.5     .08       0
Bank Sta=4946.3,5041.2
XS Rating Curve= 0 ,0
Exp/Cntr=0.3,0.1

Type RM Length L Ch R = 1 ,2699    ,365,365,365
BEGIN DESCRIPTION:
Mapping XS 94992cc1
END DESCRIPTION:
XS GIS Cut Line= 5
      3592390.17     10634239.03      3592611.51     10634785.87
      3592603.69     10634830.14      3592572.44     10635087.95
      3592559.43     10635194.67
#Sta/Elev= 30
  4442.2  365.86  4480.9  365.92  4636.4  360.08  4802.7  361.81  4928.7  358.64
  4972.1  360.96  4982.3   360.5  4993.6     355  5004.4  355.05  5011.8  361.53
  5031.8  364.63  5066.9  365.27  5071.9  364.13  5107.4  366.71  5117.4  362.96
  5134.6  350.82  5137.3  350.32  5140.6  350.82  5147.6  356.53  5152.6  357.21
  5157.7  365.33  5167.8   366.2  5177.9  366.13  5208.1  361.54  5239.5  361.27
  5268.5  365.57  5359.2  368.84  5386.6   371.5    5398  372.64  5444.3   371.2
#Mann= 4 ,-1 , 0
  4442.2     .05       0  5134.6     .03       0  5140.6     .05       0
  5386.6     .08       0
Bank Sta=4972.1,5011.8
XS Rating Curve= 0 ,0
Exp/Cntr=0.3,0.1

Type RM Length L Ch R = 1 ,2334    ,90,90,90
BEGIN DESCRIPTION:
UNT214 IN CCTC 4.0
END DESCRIPTION:
XS GIS Cut Line= 2
      3592374.53     10634125.31      3592331.12     10635370.96
#Sta/Elev= 30
  4227.5  370.41  4252.4  369.74  4272.4  370.08  4292.4  369.76  4382.5  365.89
  4440.8  364.88  4472.5  364.46  4572.6  361.54  4652.6  360.03  4803.6  357.82
  4907.4  357.65  4952.8  357.01  4962.8  355.93  4972.8  356.69  4992.8  357.07
  5005.4  356.33  5019.9   355.6  5022.6   355.1  5025.9   355.6  5032.9  355.85
  5052.9  357.91  5072.9  358.35  5122.9  358.39  5132.9  359.04    5253  361.72
  5363.1  365.85    5376  365.98  5383.1  365.34  5403.1  366.25  5473.9  366.51
#Mann= 6 ,-1 , 0
  4227.5     .05       0  4440.8     .08       0  4907.4     .05       0
  5005.4     .08       0  5019.9     .04       0  5025.9     .08       0
Bank Sta=4992.8,5052.9
XS Rating Curve= 0 ,0
Exp/Cntr=0.3,0.1

Type RM Length L Ch R = 1 ,2244    ,216,216,216
BEGIN DESCRIPTION:
UNT214 IN CCTC 3.0
END DESCRIPTION:
XS GIS Cut Line= 2
       3592274.7     10634285.87      3592244.33     10635405.46
#Sta/Elev= 30
  4384.3  370.66  4448.6  369.46  4498.7  367.51  4668.7  358.96  4718.7  358.45
  4808.8  356.01  4888.8  355.34  4908.8  355.92  4948.8  354.46  4978.8  353.37
  4998.6  347.94  5001.8  348.44  5008.9  351.59  5028.9  354.27  5038.9  354.76
  5048.9  353.57  5068.9  354.15  5088.9  353.62  5124.5  355.38  5129.5  354.78
  5168.9  356.31  5198.9  356.06  5238.9  358.23  5268.9  357.49    5299  358.44
    5409  362.77    5439  362.81    5449  363.92    5479  364.78  5504.3   367.5
#Mann= 6 ,-1 , 0
  4384.3     .08       0  4718.7     .05       0  4948.8     .03       0
  5038.9     .05       0    5299     .05       0    5299     .08       0
Bank Sta=4948.8,5038.9
XS Rating Curve= 0 ,0
Exp/Cntr=0.3,0.1

Type RM Length L Ch R = 1 ,2028    ,520,520,520
BEGIN DESCRIPTION:
UNT214 IN CCTC 2.0
END DESCRIPTION:
XS GIS Cut Line= 3
       3591949.6     10634560.16      3592099.61     10634960.19
      3592299.63     10635160.21
#Sta/Elev= 30
  4579.7  367.37  4601.1  365.59  4619.8  364.85  4655.4  362.14  4680.3  361.17
  4735.5  357.27  4782.7  354.95  4790.7   354.8    4796  355.32    4804  354.31
  4868.1  352.69  4900.1  352.38  4966.9  353.25  4974.9  351.67  4985.6  346.86
  4997.1  345.71    5004  344.15  5021.1  344.95  5035.2  353.11  5049.4  352.68
  5063.5  348.69  5091.8  353.01  5105.9  353.09  5134.2  354.66  5190.8  355.51
  5208.9  356.33  5219.1  356.56  5247.3  360.25  5280.8  362.18  5289.8  362.55
#Mann= 6 ,-1 , 0
  4579.7     .08       0  4735.5     .07       0  4966.9     .03       0
  5035.2     .05       0  5208.9     .07       0  5280.8     .08       0
Bank Sta=4966.9,5035.2
XS Rating Curve= 0 ,0
Exp/Cntr=0.3,0.1

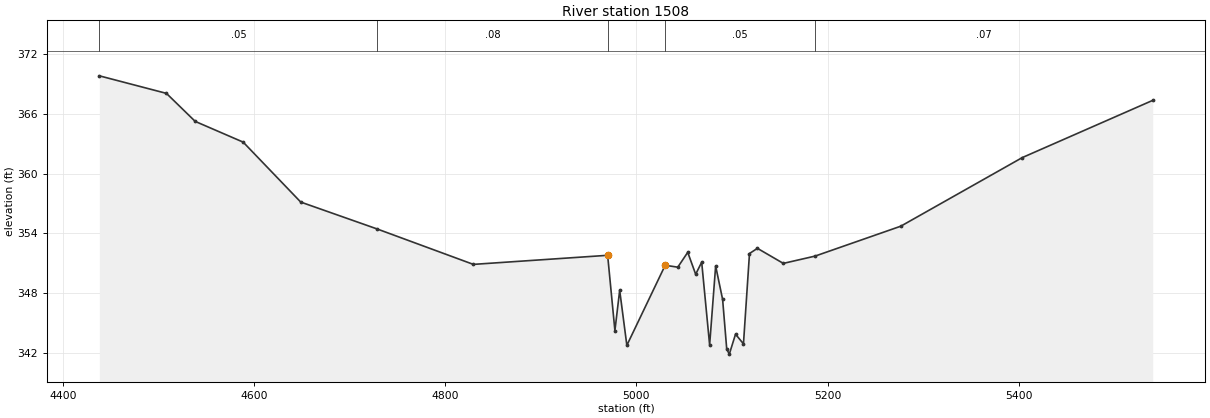
Type RM Length L Ch R = 1 ,1508    ,0,0,0
BEGIN DESCRIPTION:
UNT214 IN CCTC 1.0
END DESCRIPTION:
XS GIS Cut Line= 3
      3591849.61      10634510.2      3591799.61     10635110.19
      3592199.63     10635410.21
#Sta/Elev= 30
  4438.1   369.8  4508.3  368.04  4538.4  365.23  4588.6  363.15  4648.8  357.14
  4729.1  354.43  4829.4  350.89  4969.9   351.8  4977.5  344.25  4982.5  348.29
    4990  342.77  5030.1   350.8  5043.3  350.61  5053.7   352.1    5062   349.9
  5068.3  351.11  5076.6  342.81  5082.9  350.73  5090.2  347.37  5094.5  342.39
  5097.2  341.89  5103.7  343.89    5112  342.92  5118.3  351.98  5126.6   352.5
  5153.7  350.99  5186.9  351.72  5276.6  354.72  5403.7   361.6  5540.2  367.34
#Mann= 5 ,-1 , 0
  4438.1     .05       0  4729.1     .08       0  4969.9     .03       0
  5030.1     .05       0  5186.9     .07       0
Bank Sta=4969.9,5030.1
XS Rating Curve= 0 ,0
Exp/Cntr=0.3,0.1

Chan Stop Cuts=-1
Use User Specified Reach Order=0
Composite Channel Slope=5