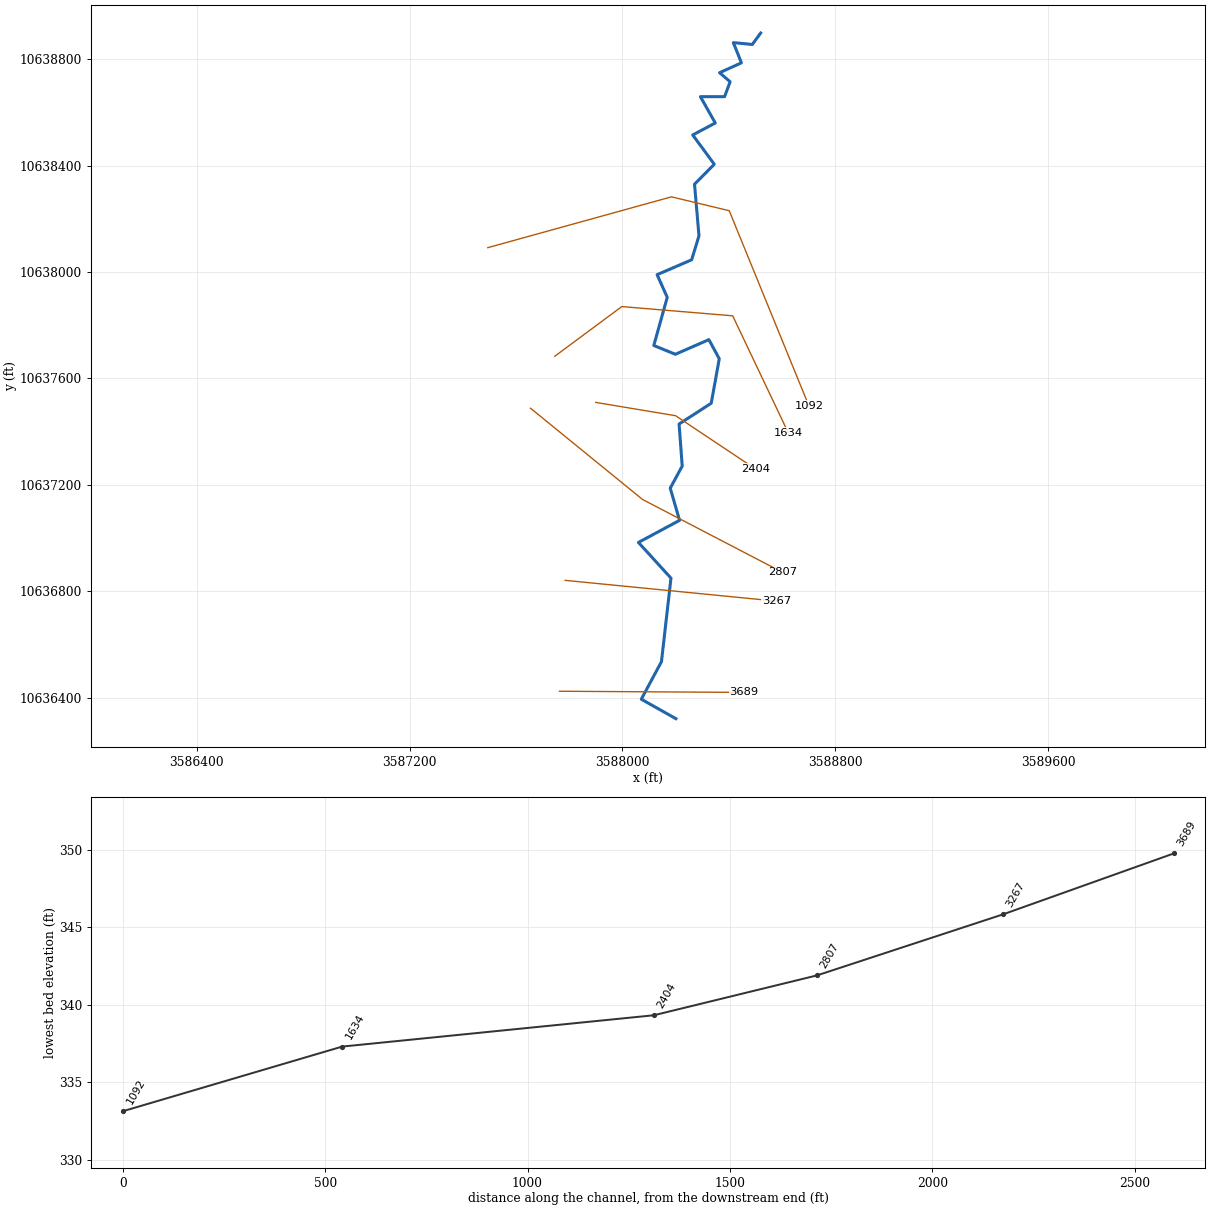
--- UNT215 IN CCTC.prj (project) ---

Proj Title=UNT215 IN CCTC Base Level Engineering
Current Plan=p01
Default Exp/Contr=0.3,0.1
English Units
Geom File=g01
Flow File=f01
Plan File=p01
BEGIN DESCRIPTION:
UNT215 IN CCTC
END DESCRIPTION:

--- UNT215 IN CCTC.p01 (plan) ---

Plan Title=Multiple Run
Short Identifier=Multiple
Geom File=g01
Flow File=f01
Subcritical Flow
K Sum by GR= 0
Std Step Tol= 0.01
Critical Tol= 0.01
Num of Std Step Trials= 20
Max Error Tol= 0.3
Flow Tol Ratio= 0.001
Split Flow NTrial= 30
Split Flow Tol= 0.02
Split Flow Ratio= 0.02
Log Output Level= 0
Friction Slope Method= 1
Unsteady Friction Slope Method= 2
Unsteady Bridges Friction Slope Method= 1
Parabolic Critical Depth
Global Vel Dist=  1 , 1 , 1
Global Log Level= 0
CheckData=True
Encroach Param= -1, 0, 0, 0
BEGIN DESCRIPTION:
Multiple Run
END DESCRIPTION:

--- UNT215 IN CCTC.f01 (steady flow) ---

Flow Title=Multiple
Number of Profiles=7
Profile Names=10-year,25-year,50-year,1pct_min,100-year,1pct_plu,500-year
River Rch & RM= UNT215 IN CCTC,Reach-1,3689
    1171    1585    1923    1703    2303    3115    3291
Boundary for River Rch & Prof#=UNT215 IN CCTC,Reach-1,1
Up Type=0
Dn Type=3
Dn Slope=0.005
Boundary for River Rch & Prof#=UNT215 IN CCTC,Reach-1,2
Up Type=0
Dn Type=3
Dn Slope=0.005
Boundary for River Rch & Prof#=UNT215 IN CCTC,Reach-1,3
Up Type=0
Dn Type=3
Dn Slope=0.005
Boundary for River Rch & Prof#=UNT215 IN CCTC,Reach-1,4
Up Type=0
Dn Type=3
Dn Slope=0.005
Boundary for River Rch & Prof#=UNT215 IN CCTC,Reach-1,5
Up Type=0
Dn Type=3
Dn Slope=0.005
Boundary for River Rch & Prof#=UNT215 IN CCTC,Reach-1,6
Up Type=0
Dn Type=3
Dn Slope=0.005
Boundary for River Rch & Prof#=UNT215 IN CCTC,Reach-1,7
Up Type=0
Dn Type=3
Dn Slope=0.005

--- UNT215 IN CCTC.g01 (geometry) ---

Geom Title=Existing Conditions

River Reach=UNT215 IN CCTC,Reach-1
Reach XY= 30
      3588200.81     10636321.86      3588070.75     10636395.00
      3588146.50     10636536.00      3588182.25     10636850.00
      3588060.00     10636984.00      3588214.50     10637067.00
      3588179.50     10637188.00      3588224.50     10637271.00
      3588212.75     10637429.00      3588333.50     10637507.00
      3588363.75     10637674.00      3588324.75     10637746.00
      3588198.75     10637691.00      3588117.75     10637724.00
      3588168.25     10637905.00      3588130.25     10637990.00
      3588260.00     10638046.00      3588287.50     10638136.00
      3588270.75     10638330.00      3588345.00     10638405.00
      3588264.00     10638515.00      3588348.75     10638560.00
      3588292.75     10638659.00      3588383.75     10638659.00
      3588404.50     10638715.00      3588365.00     10638749.00
      3588447.00     10638786.00      3588416.50     10638862.00
      3588487.75     10638855.00      3588519.25     10638898.00

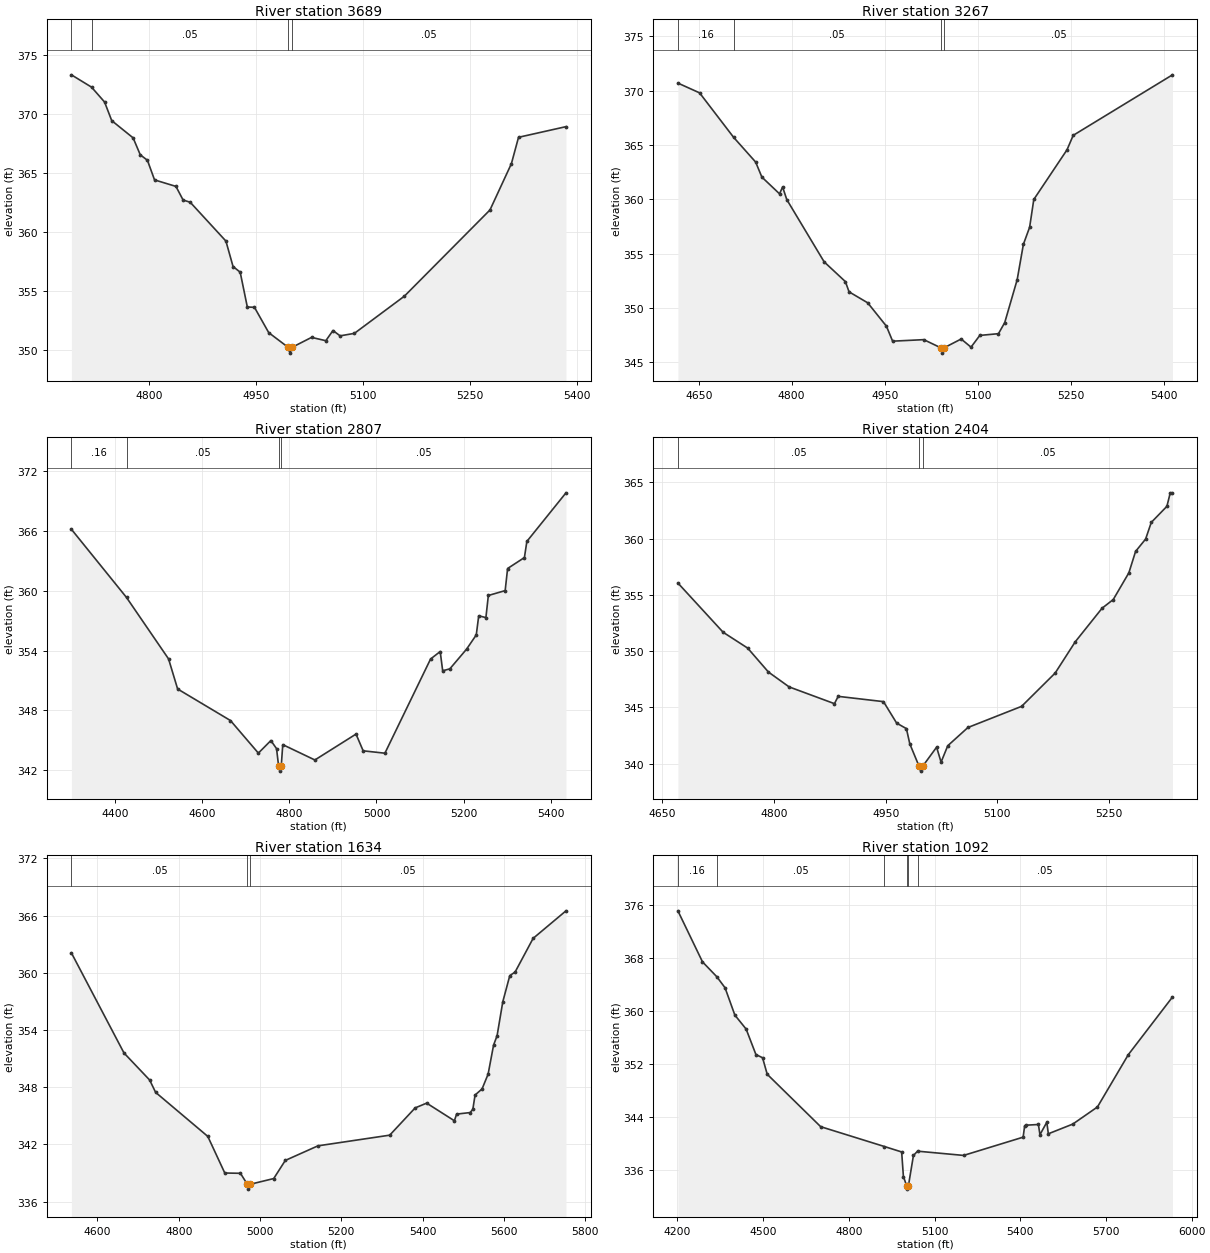
Type RM Length L Ch R = 1,3689,422,422,422
BEGIN DESCRIPTION:
UNT215 IN CCTC 4.0
END DESCRIPTION:
XS GIS Cut Line= 2
      3587763.08     10636424.90      3588456.07     10636420.57
#Sta/Elev= 30
  4691.5  373.29  4719.7  372.25  4738.0  370.99  4748.0  369.42  4778.0  367.96
  4788.0  366.53  4798.0  366.07  4808.0  364.41  4838.0  363.86  4848.0  362.71
  4858.0  362.52  4908.0  359.24  4918.0  357.09  4928.0  356.61  4938.0  353.67
  4948.0  353.64  4968.0  351.50  4995.0  350.27  4997.8  349.77  5001.0  350.27
  5028.0  351.10  5048.0  350.82  5058.0  351.68  5068.0  351.23  5088.0  351.44
  5158.0  354.58  5278.0  361.87  5308.0  365.78  5318.0  368.01  5384.5  368.91
#Mann=4,-1,0
  4691.5    0.16       0  4719.7    0.05       0  4995.0   0.035       0
  5001.0    0.05       0
Bank Sta=4995,5001
Exp/Cntr=0.3,0.1

Type RM Length L Ch R = 1,3267,460,460,460
BEGIN DESCRIPTION:
UNT215 IN CCTC 3.0
END DESCRIPTION:
XS GIS Cut Line= 2
      3587784.75     10636841.57      3588579.02     10636763.45
#Sta/Elev= 30
  4616.4  370.69  4651.4  369.79  4706.3  365.70  4741.9  363.42  4751.9  362.04
  4780.4  360.50  4785.4  361.13  4792.1  359.97  4852.4  354.24  4886.7  352.42
  4892.6  351.48  4922.7  350.47  4952.9  348.32  4962.9  346.94  5013.2  347.08
  5040.3  346.34  5043.1  345.84  5046.3  346.34  5073.5  347.14  5089.4  346.39
  5103.6  347.47  5133.7  347.63  5143.8  348.65  5163.9  352.60  5173.9  355.85
  5184.0  357.43  5190.7  359.98  5244.3  364.55  5254.3  365.88  5414.5  371.45
#Mann=4,-1,0
  4616.4    0.16       0  4706.3    0.05       0  5040.3    0.03       0
  5046.3    0.05       0
Bank Sta=5040.3,5046.3
Exp/Cntr=0.3,0.1

Type RM Length L Ch R = 1,2807,403,403,403
BEGIN DESCRIPTION:
Mapping XS fd31a1f1
END DESCRIPTION:
XS GIS Cut Line= 3
      3587654.56     10637488.29      3588075.59     10637145.39
      3588600.77     10636871.95
#Sta/Elev= 30
  4299.8  366.19  4426.3  359.34  4522.8  353.17  4543.6  350.15  4664.9  346.98
  4728.9  343.71  4757.6  344.97  4770.6  344.16  4775.4  342.40  4778.2  341.90
  4781.4  342.40  4784.9  344.56  4858.6  343.02  4953.0  345.62  4969.4  343.94
  5019.3  343.70  5124.1  353.16  5146.2  353.91  5151.9  351.98  5168.3  352.17
  5206.9  354.16  5229.0  355.58  5234.6  357.50  5251.1  357.32  5256.7  359.54
  5295.3  360.03  5300.9  362.25  5339.5  363.35  5345.1  364.97  5434.9  369.85
#Mann=4,-1,0
  4299.8    0.16       0  4426.3    0.05       0  4775.4    0.03       0
  4781.4    0.05       0
Bank Sta=4775.4,4781.4
Exp/Cntr=0.3,0.1

Type RM Length L Ch R = 1,2404,770,770,770
BEGIN DESCRIPTION:
UNT215 IN CCTC 2.0
END DESCRIPTION:
XS GIS Cut Line= 3
      3587899.61     10637510.19      3588199.61     10637460.19
      3588499.61     10637260.19
#Sta/Elev= 30
  4670.8  356.06  4731.6  351.68  4764.6  350.27  4792.5  348.14  4820.3  346.82
  4881.2  345.33  4886.2  345.98  4947.1  345.51  4964.8  343.60  4977.9  343.11
  4982.5  341.75  4994.5  339.83  4997.2  339.33  5000.5  339.83  5018.5  341.46
  5024.5  340.13  5033.5  341.59  5060.6  343.21  5132.7  345.09  5177.8  348.05
  5204.8  350.83  5240.9  353.82  5255.9  354.59  5276.9  356.97  5285.9  358.87
  5299.4  359.97  5307.0  361.45  5328.0  362.88  5332.5  364.08  5335.5  364.08
#Mann=3,-1,0
  4670.8    0.05       0  4994.5    0.03       0  5000.5    0.05       0
Bank Sta=4994.5,5000.5
Exp/Cntr=0.3,0.1

Type RM Length L Ch R = 1,1634,542,542,542
BEGIN DESCRIPTION:
Mapping XS f216db03
END DESCRIPTION:
XS GIS Cut Line= 4
      3587745.70     10637683.56      3587997.47     10637870.21
      3588414.13     10637835.49      3588622.48     10637397.10
#Sta/Elev= 30
  4535.8  362.09  4665.2  351.59  4728.4  348.75  4743.0  347.46  4871.4  342.84
  4913.2  339.00  4951.7  338.97  4968.8  337.81  4971.5  337.31  4974.8  337.81
  5033.6  338.42  5062.1  340.32  5142.4  341.85  5319.0  342.97  5381.6  345.83
  5409.9  346.33  5478.1  344.48  5483.6  345.18  5516.8  345.34  5523.5  345.68
  5529.0  347.18  5546.2  347.82  5561.1  349.37  5574.5  352.41  5583.2  353.41
  5597.2  356.96  5614.4  359.70  5627.5  360.08  5671.8  363.61  5752.7  366.50
#Mann=3,-1,0
  4535.8    0.05       0  4968.8    0.03       0  4974.8    0.05       0
Bank Sta=4968.8,4974.8
Exp/Cntr=0.3,0.1

Type RM Length L Ch R = 1,1092,0,0,0
BEGIN DESCRIPTION:
UNT215 IN CCTC 1.0
END DESCRIPTION:
XS GIS Cut Line= 4
      3587493.97     10638091.56      3588184.10     10638282.54
      3588401.11     10638230.46      3588700.58     10637496.97
#Sta/Elev= 30
  4201.4  375.08  4287.5  367.39  4337.8  365.14  4366.5  363.48  4400.8  359.37
  4440.3  357.26  4474.6  353.42  4497.8  352.94  4514.1  350.45  4701.3  342.55
  4924.5  339.56  4984.8  338.74  4990.9  335.03  5002.4  333.64  5005.1  333.14
  5008.4  333.64  5026.0  338.21  5040.4  338.86  5201.6  338.22  5410.0  340.97
  5415.4  342.67  5421.8  342.78  5463.5  342.88  5468.9  341.34  5492.9  343.22
  5498.3  341.48  5583.8  342.94  5670.2  345.52  5778.2  353.40  5932.9  362.09
#Mann=6,-1,0
  4201.4    0.16       0  4337.8    0.05       0  4924.5    0.12       0
  5002.4    0.07       0  5008.4    0.12       0  5040.4    0.05       0
Bank Sta=5002.4,5008.4
Exp/Cntr=0.3,0.1

Chan Stop Cuts=-1