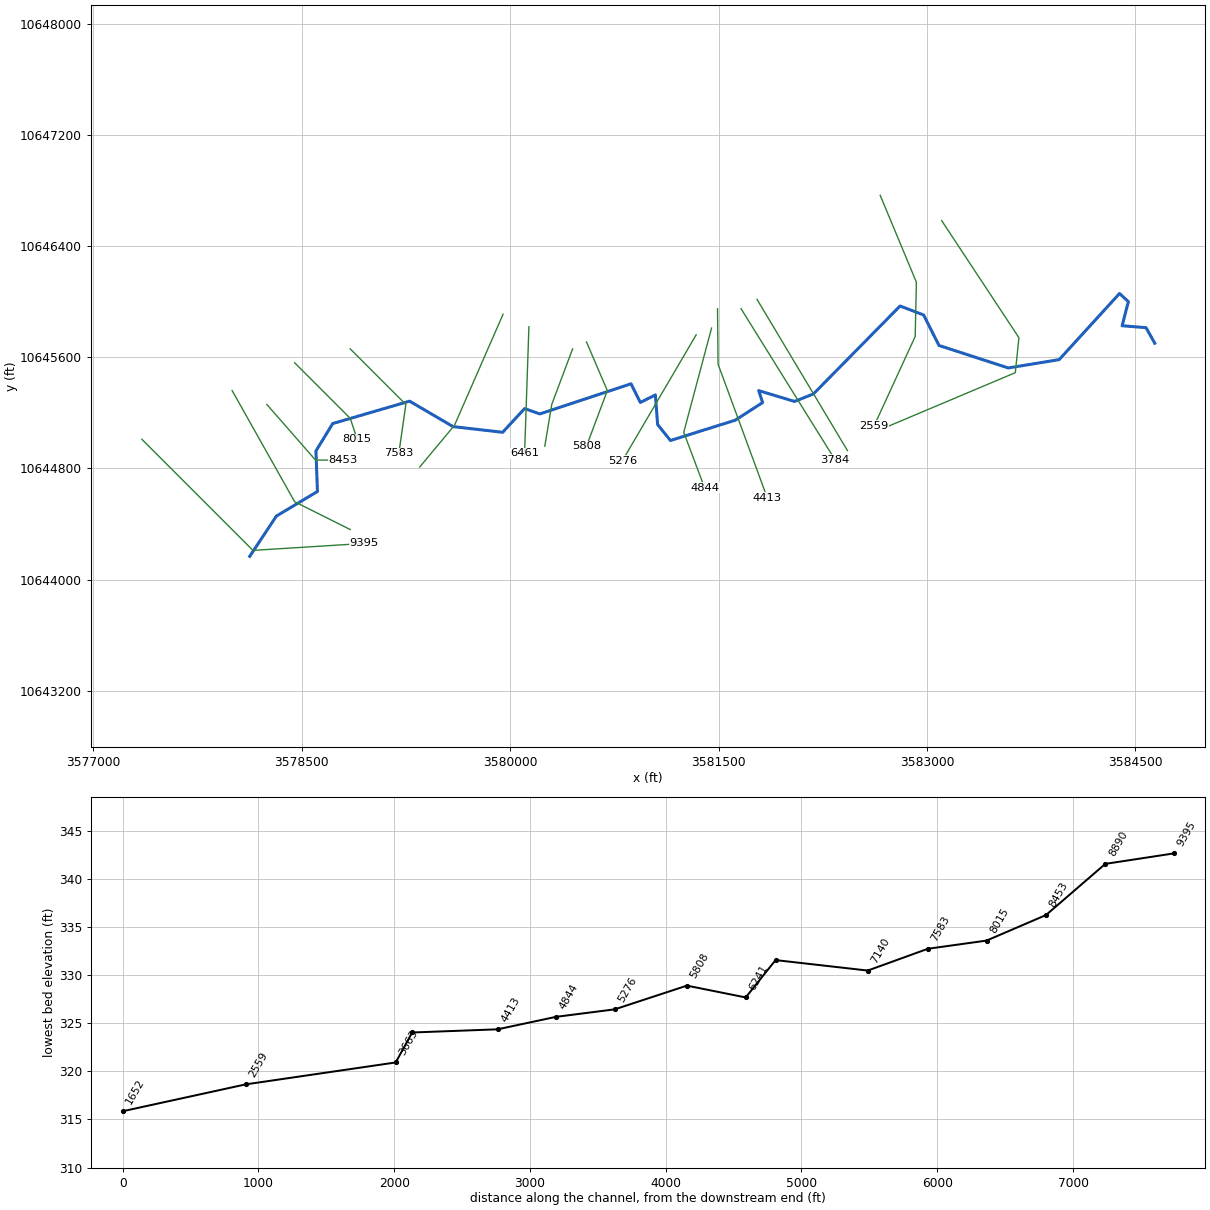
--- UNT217 IN CCTC.prj (project) ---

Proj Title=UNT217 IN CCTC Base Level Engineering
Current Plan=p01
Default Exp/Contr=0.3,0.1
English Units
Geom File=g01
Flow File=f01
Plan File=p01
BEGIN DESCRIPTION:
UNT217 IN CCTC
END DESCRIPTION:

--- UNT217 IN CCTC.p01 (plan) ---

Plan Title=Multiple Run
Short Identifier=Multiple
Geom File=g01
Flow File=f01
Subcritical Flow
K Sum by GR= 0
Std Step Tol= 0.01
Critical Tol= 0.01
Num of Std Step Trials= 20
Max Error Tol= 0.3
Flow Tol Ratio= 0.001
Split Flow NTrial= 30
Split Flow Tol= 0.02
Split Flow Ratio= 0.02
Log Output Level= 0
Friction Slope Method= 1
Unsteady Friction Slope Method= 2
Unsteady Bridges Friction Slope Method= 1
Parabolic Critical Depth
Global Vel Dist=  1 , 1 , 1
Global Log Level= 0
CheckData=True
Encroach Param= -1, 0, 0, 0
BEGIN DESCRIPTION:
Multiple Run
END DESCRIPTION:

--- UNT217 IN CCTC.f01 (steady flow) ---

Flow Title=Multiple
Number of Profiles=7
Profile Names=10-year,25-year,50-year,1pct_min,100-year,1pct_plu,500-year
River Rch & RM= UNT217 IN CCTC,Reach-1,9395
    2255    3172    3945    3574    4833    6536    7234
Boundary for River Rch & Prof#=UNT217 IN CCTC,Reach-1,1
Up Type=0
Dn Type=3
Dn Slope=0.005
Boundary for River Rch & Prof#=UNT217 IN CCTC,Reach-1,2
Up Type=0
Dn Type=3
Dn Slope=0.005
Boundary for River Rch & Prof#=UNT217 IN CCTC,Reach-1,3
Up Type=0
Dn Type=3
Dn Slope=0.005
Boundary for River Rch & Prof#=UNT217 IN CCTC,Reach-1,4
Up Type=0
Dn Type=3
Dn Slope=0.005
Boundary for River Rch & Prof#=UNT217 IN CCTC,Reach-1,5
Up Type=0
Dn Type=3
Dn Slope=0.005
Boundary for River Rch & Prof#=UNT217 IN CCTC,Reach-1,6
Up Type=0
Dn Type=3
Dn Slope=0.005
Boundary for River Rch & Prof#=UNT217 IN CCTC,Reach-1,7
Up Type=0
Dn Type=3
Dn Slope=0.005

--- UNT217 IN CCTC.g01 (geometry) ---

Geom Title=Existing Conditions

River Reach=UNT217 IN CCTC,Reach-1
Reach XY= 30
      3578126.24     10644167.23      3578318.00     10644457.00
      3578613.50     10644634.00      3578602.75     10644926.00
      3578723.50     10645123.00      3579276.75     10645284.00
      3579589.50     10645101.00      3579946.25     10645060.00
      3580104.50     10645231.00      3580213.75     10645192.00
      3580869.75     10645409.00      3580937.00     10645275.00
      3581045.50     10645329.00      3581061.50     10645116.00
      3581154.00     10645001.00      3581620.25     10645147.00
      3581817.00     10645274.00      3581788.75     10645360.00
      3582047.00     10645282.00      3582182.75     10645336.00
      3582806.25     10645969.00      3582976.25     10645904.00
      3583086.50     10645685.00      3583585.00     10645523.00
      3583951.25     10645583.00      3584385.75     10646059.00
      3584449.25     10646000.00      3584404.25     10645827.00
      3584576.25     10645813.00      3584639.25     10645701.00

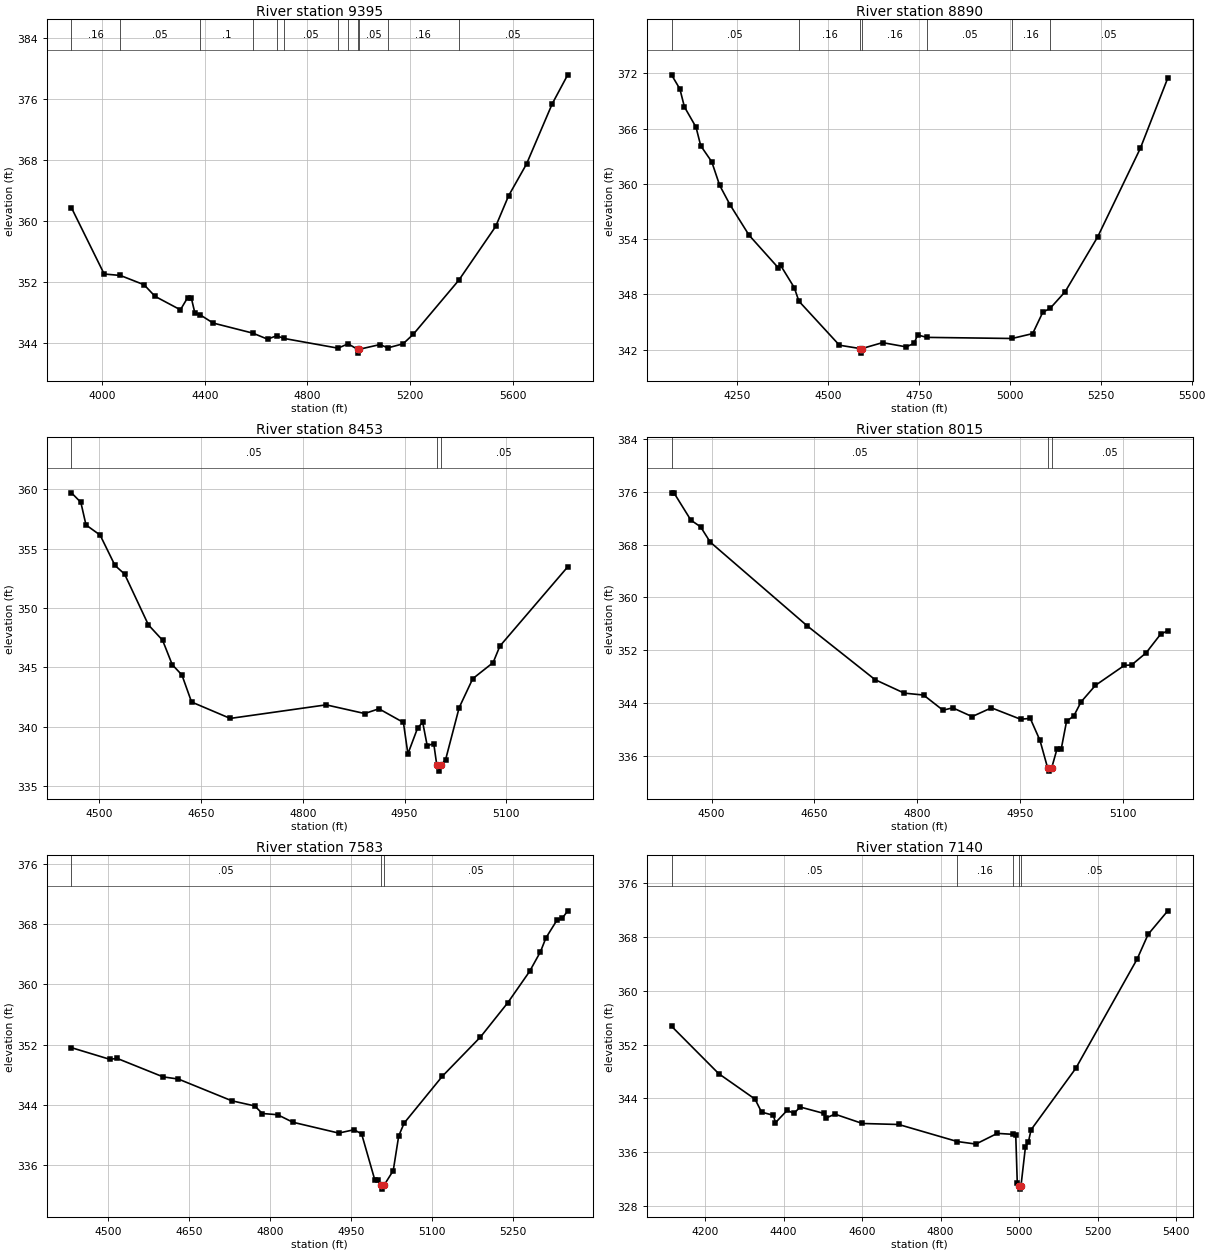
Type RM Length L Ch R = 1,9395,505,505,505
BEGIN DESCRIPTION:
UNT217 IN CCTC 15.0
END DESCRIPTION:
XS GIS Cut Line= 3
      3577349.59     10645010.21      3578149.61     10644210.19
      3578949.65     10644260.19
#Sta/Elev= 30
  3880.8  361.74  4008.1  353.07  4071.2  352.88  4163.7  351.66  4206.1  350.15
  4305.1  348.38  4333.4  349.98  4347.5  349.94  4361.7  347.93  4381.8  347.73
  4432.4  346.65  4586.9  345.33  4644.5  344.54  4679.7  344.98  4709.0  344.63
  4919.1  343.36  4958.2  343.93  4995.1  343.21  4997.8  342.71  5001.1  343.21
  5082.3  343.83  5113.2  343.40  5172.5  343.93  5212.6  345.19  5389.6  352.26
  5533.2  359.30  5583.3  363.30  5653.4  367.48  5753.6  375.37  5813.8  379.15
#Mann=12,-1,0
  3880.8    0.16       0  4071.2    0.05       0  4381.8     0.1       0
  4586.9    0.05       0  4679.7     0.1       0  4709.0    0.05       0
  4919.1    0.16       0  4958.2    0.05       0  4995.1   0.035       0
  5001.1    0.05       0  5113.2    0.16       0  5389.6    0.05       0
Bank Sta=4995.1,5001.1
Exp/Cntr=0.3,0.1

Type RM Length L Ch R = 1,8890,437,437,437
BEGIN DESCRIPTION:
UNT217 IN CCTC 14.0
END DESCRIPTION:
XS GIS Cut Line= 3
      3577999.60     10645360.21      3578449.61     10644560.19
      3578849.60     10644360.19
#Sta/Elev= 30
  4069.2  371.84  4092.2  370.30  4104.6  368.36  4136.5  366.16  4149.5  364.14
  4179.8  362.40  4201.5  359.85  4229.8  357.75  4282.4  354.43  4363.4  350.86
  4369.1  351.16  4406.7  348.74  4419.6  347.26  4531.0  342.48  4587.3  342.12
  4590.1  341.62  4593.3  342.12  4649.6  342.76  4714.6  342.30  4736.3  342.68
  4746.2  343.59  4771.8  343.33  5005.8  343.21  5062.6  343.74  5090.5  346.06
  5110.9  346.49  5152.0  348.29  5241.4  354.24  5358.8  363.86  5434.3  371.49
#Mann=7,-1,0
  4069.2    0.05       0  4419.6    0.16       0  4587.3   0.035       0
  4593.3    0.16       0  4771.8    0.05       0  5005.8    0.16       0
  5110.9    0.05       0
Bank Sta=4587.3,4593.3
Exp/Cntr=0.3,0.1

Type RM Length L Ch R = 1,8453,438,438,438
BEGIN DESCRIPTION:
UNT217 IN CCTC 13.0
END DESCRIPTION:
XS GIS Cut Line= 3
      3578249.61     10645260.19      3578599.61     10644860.19
      3578799.60     10644860.19
#Sta/Elev= 30
  4459.1  359.68  4472.9  358.88  4480.5  356.98  4501.3  356.13  4523.2  353.58
  4537.4  352.85  4572.5  348.58  4593.4  347.29  4607.6  345.24  4621.9  344.37
  4636.1  342.10  4693.1  340.72  4834.5  341.86  4891.4  341.13  4912.3  341.53
  4948.4  340.38  4955.0  337.74  4969.3  339.91  4976.8  340.40  4983.5  338.42
  4993.1  338.61  4997.6  336.79  5000.4  336.29  5003.6  336.79  5010.6  337.26
  5030.6  341.63  5050.6  344.06  5080.6  345.41  5090.6  346.80  5190.6  353.46
#Mann=3,-1,0
  4459.1    0.05       0  4997.6    0.03       0  5003.6    0.05       0
Bank Sta=4997.6,5003.6
Exp/Cntr=0.3,0.1

Type RM Length L Ch R = 1,8015,432,432,432
BEGIN DESCRIPTION:
UNT217 IN CCTC 12.0
END DESCRIPTION:
XS GIS Cut Line= 3
      3578449.64     10645560.15      3578849.61     10645160.19
      3578899.62     10645010.14
#Sta/Elev= 30
  4441.5  375.84  4445.0  375.84  4469.7  371.70  4483.9  370.68  4498.0  368.36
  4639.4  355.66  4738.4  347.50  4780.9  345.46  4809.1  345.17  4837.4  342.87
  4851.6  343.23  4879.9  341.90  4908.1  343.23  4950.6  341.50  4964.7  341.63
  4978.9  338.29  4990.0  334.13  4992.7  333.63  4996.0  334.13  5003.6  336.94
  5009.8  336.94  5017.7  341.21  5028.2  341.99  5038.8  344.13  5059.8  346.64
  5102.0  349.67  5112.5  349.73  5133.6  351.56  5154.7  354.38  5165.3  354.93
#Mann=3,-1,0
  4441.5    0.05       0  4990.0    0.03       0  4996.0    0.05       0
Bank Sta=4990,4996
Exp/Cntr=0.3,0.1

Type RM Length L Ch R = 1,7583,443,443,443
BEGIN DESCRIPTION:
UNT217 IN CCTC 11.0
END DESCRIPTION:
XS GIS Cut Line= 3
      3578849.62     10645660.18      3579249.61     10645260.19
      3579199.61     10644910.21
#Sta/Elev= 30
  4432.7  351.58  4503.4  350.04  4517.5  350.15  4602.4  347.70  4630.7  347.41
  4729.7  344.52  4772.1  343.84  4786.2  342.83  4814.5  342.67  4842.8  341.67
  4927.7  340.23  4955.9  340.67  4970.1  340.13  4994.8  333.94  5000.9  333.94
  5005.5  333.28  5008.2  332.78  5011.5  333.28  5028.7  335.24  5038.8  339.84
  5048.9  341.56  5119.6  347.78  5190.3  353.00  5240.8  357.55  5281.2  361.71
  5301.4  364.33  5311.5  366.17  5331.7  368.50  5341.8  368.78  5351.9  369.77
#Mann=3,-1,0
  4432.7    0.05       0  5005.5    0.03       0  5011.5    0.05       0
Bank Sta=5005.5,5011.5
Exp/Cntr=0.3,0.1

Type RM Length L Ch R = 1,7140,679,679,679
BEGIN DESCRIPTION:
UNT217 IN CCTC 10.0
END DESCRIPTION:
XS GIS Cut Line= 3
      3579949.62     10645910.20      3579599.61     10645110.19
      3579349.64     10644810.22
#Sta/Elev= 30
  4114.7  354.73  4234.8  347.68  4327.2  343.90  4343.9  341.97  4374.0  341.48
  4379.4  340.39  4409.4  342.24  4426.2  341.76  4442.2  342.72  4501.8  341.78
  4507.7  341.07  4530.7  341.66  4600.8  340.27  4693.2  340.12  4842.1  337.59
  4889.7  337.21  4944.3  338.80  4983.2  338.66  4991.2  338.62  4995.1  331.49
  4998.6  331.01  5001.3  330.51  5004.6  331.01  5015.9  336.77  5023.7  337.57
  5030.2  339.33  5144.1  348.47  5300.3  364.71  5328.3  368.39  5378.4  371.89
#Mann=5,-1,0
  4114.7    0.05       0  4842.1    0.16       0  4983.2    0.05       0
  4998.6    0.03       0  5004.6    0.05       0
Bank Sta=4998.6,5004.6
Exp/Cntr=0.3,0.1

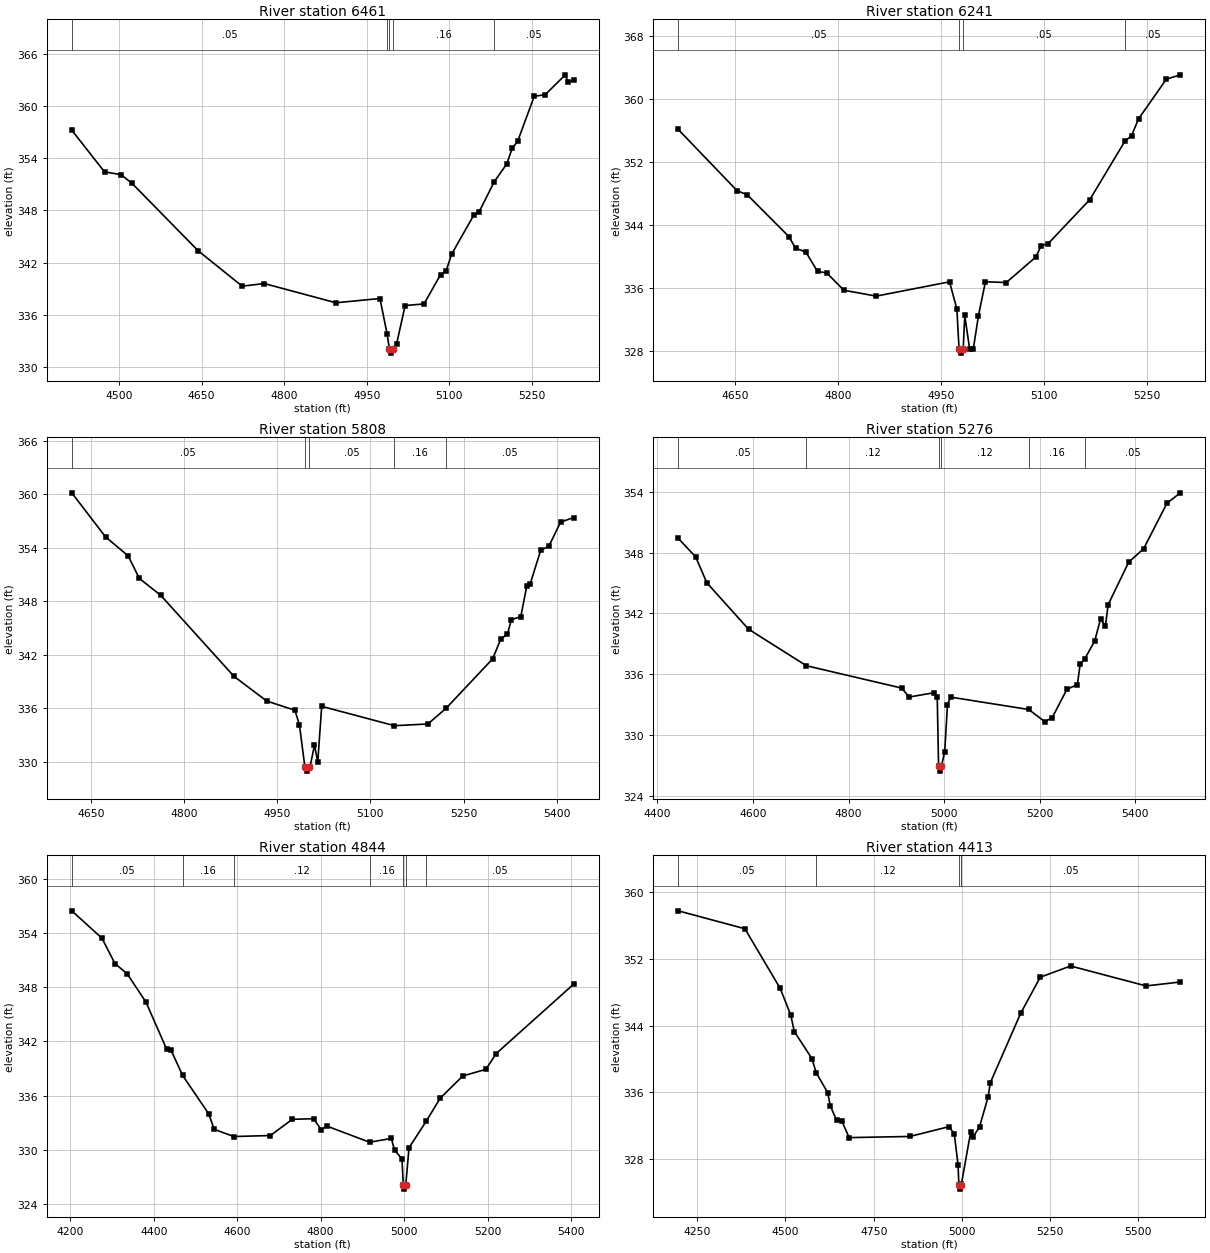
Type RM Length L Ch R = 1,6461,220,220,220
BEGIN DESCRIPTION:
UNT217 IN CCTC 9.0
END DESCRIPTION:
XS GIS Cut Line= 2
      3580135.38     10645819.70      3580104.13     10644908.23
#Sta/Elev= 30
  4414.2  357.24  4473.7  352.44  4503.8  352.12  4523.8  351.11  4643.8  343.37
  4723.7  339.30  4763.9  339.60  4894.0  337.39  4974.0  337.88  4986.9  333.83
  4991.1  332.10  4993.8  331.60  4997.1  332.10  5004.1  332.62  5019.7  337.07
  5054.1  337.26  5084.1  340.63  5094.1  341.03  5104.1  342.97  5144.1  347.43
  5154.1  347.84  5181.6  351.31  5204.2  353.34  5214.2  355.14  5224.2  355.97
  5254.2  361.13  5274.2  361.32  5310.7  363.60  5315.7  362.76  5326.2  362.97
#Mann=5,-1,0
  4414.2    0.05       0  4986.9    0.16       0  4991.1    0.07       0
  4997.1    0.16       0  5181.6    0.05       0
Bank Sta=4991.1,4997.1
Exp/Cntr=0.3,0.1

Type RM Length L Ch R = 1,6241,433,433,433
BEGIN DESCRIPTION:
UNT217 IN CCTC 8.0
END DESCRIPTION:
XS GIS Cut Line= 3
      3580449.61     10645660.20      3580299.61     10645260.19
      3580249.60     10644960.14
#Sta/Elev= 30
  4567.6  356.16  4653.1  348.39  4668.2  347.84  4728.7  342.54  4738.5  341.06
  4753.6  340.56  4770.5  338.10  4783.9  337.92  4808.8  335.71  4856.0  334.96
  4962.8  336.78  4973.5  333.32  4976.7  328.21  4979.4  327.71  4982.7  328.21
  4985.0  332.50  4992.1  328.22  4997.4  328.22  5005.0  332.49  5015.1  336.79
  5045.5  336.69  5088.6  339.94  5096.2  341.37  5106.3  341.62  5167.2  347.24
  5218.1  354.64  5228.0  355.38  5238.1  357.50  5278.7  362.56  5299.0  363.11
#Mann=4,-1,0
  4567.6    0.05       0  4976.7    0.07       0  4982.7    0.05       0
  5218.1    0.05       0
Bank Sta=4976.7,4982.7
Exp/Cntr=0.3,0.1

Type RM Length L Ch R = 1,5808,532,532,532
BEGIN DESCRIPTION:
UNT217 IN CCTC 7.0
END DESCRIPTION:
XS GIS Cut Line= 3
      3580549.60     10645710.21      3580699.61     10645360.19
      3580549.61     10644960.20
#Sta/Elev= 30
  4619.4  360.17  4673.8  355.22  4710.1  353.10  4728.2  350.56  4762.7  348.66
  4880.5  339.57  4933.1  336.81  4978.5  335.77  4985.7  334.16  4994.5  329.44
  4997.2  328.94  5000.5  329.44  5002.9  329.44  5010.0  331.85  5015.3  329.97
  5021.6  336.21  5138.6  334.04  5192.5  334.23  5221.9  336.00  5296.6  341.53
  5309.9  343.77  5320.6  344.31  5326.8  345.93  5342.0  346.28  5351.8  349.75
  5357.1  349.95  5374.0  353.70  5387.4  354.21  5406.1  356.89  5427.4  357.40
#Mann=5,-1,0
  4619.4    0.05       0  4994.5    0.07       0  5000.5    0.05       0
  5138.6    0.16       0  5221.9    0.05       0
Bank Sta=4994.5,5000.5
Exp/Cntr=0.3,0.1

Type RM Length L Ch R = 1,5276,432,432,432
BEGIN DESCRIPTION:
UNT217 IN CCTC 6.0
END DESCRIPTION:
XS GIS Cut Line= 2
      3581339.17     10645761.74      3580807.92     10644855.48
#Sta/Elev= 30
  4443.4  349.40  4480.0  347.56  4503.2  345.02  4590.5  340.45  4711.6  336.85
  4910.9  334.65  4926.6  333.77  4978.4  334.19  4985.3  333.80  4988.1  326.97
  4990.8  326.47  4994.1  326.97  5000.9  328.34  5006.7  333.00  5013.2  333.76
  5176.7  332.54  5210.2  331.35  5225.6  331.71  5256.6  334.53  5278.5  334.99
  5284.3  336.98  5294.2  337.55  5314.6  339.26  5327.2  341.49  5337.1  340.72
  5342.9  342.87  5385.9  347.05  5417.2  348.38  5466.0  352.86  5493.9  353.88
#Mann=6,-1,0
  4443.4    0.05       0  4711.6    0.12       0  4988.1    0.07       0
  4994.1    0.12       0  5176.7    0.16       0  5294.2    0.05       0
Bank Sta=4988.1,4994.1
Exp/Cntr=0.3,0.1

Type RM Length L Ch R = 1,4844,431,431,431
BEGIN DESCRIPTION:
UNT217 IN CCTC 5.0
END DESCRIPTION:
XS GIS Cut Line= 3
      3581449.61     10645810.20      3581249.61     10645060.19
      3581399.60     10644660.21
#Sta/Elev= 30
  4203.5  356.43  4276.0  353.40  4307.0  350.60  4336.1  349.49  4381.4  346.34
  4431.2  341.12  4441.5  341.03  4469.2  338.25  4531.5  334.02  4545.0  332.29
  4592.0  331.50  4679.6  331.61  4732.0  333.40  4783.1  333.47  4801.8  332.23
  4814.1  332.67  4917.3  330.87  4969.4  331.29  4977.1  330.00  4994.9  329.03
  4998.1  326.19  5000.8  325.69  5004.1  326.19  5011.8  330.26  5053.1  333.19
  5086.5  335.73  5140.8  338.19  5196.0  338.92  5220.9  340.67  5406.9  348.35
#Mann=7,-1,0
  4203.5    0.05       0  4469.2    0.16       0  4592.0    0.12       0
  4917.3    0.16       0  4998.1    0.07       0  5004.1    0.16       0
  5053.1    0.05       0
Bank Sta=4998.1,5004.1
Exp/Cntr=0.3,0.1

Type RM Length L Ch R = 1,4413,629,629,629
BEGIN DESCRIPTION:
UNT217 IN CCTC 4.0
END DESCRIPTION:
XS GIS Cut Line= 3
      3581492.67     10645949.04      3581496.59     10645550.41
      3581850.40     10644589.10
#Sta/Elev= 30
  4196.0  357.78  4384.9  355.63  4484.9  348.48  4514.9  345.28  4524.9  343.30
  4574.9  340.05  4587.1  338.36  4619.7  335.95  4626.9  334.39  4644.8  332.65
  4658.8  332.62  4680.6  330.57  4852.7  330.71  4963.9  331.89  4978.5  330.98
  4989.0  327.34  4991.4  324.89  4994.1  324.39  4997.4  324.89  4998.7  325.03
  5024.8  331.23  5031.8  330.65  5050.0  331.87  5074.4  335.47  5080.4  337.15
  5166.5  345.48  5222.1  349.82  5308.1  351.16  5521.9  348.77  5619.0  349.24
#Mann=5,-1,0
  4196.0    0.05       0  4587.1    0.12       0  4991.4    0.03       0
  4997.4    0.12       0  4998.7    0.05       0
Bank Sta=4991.4,4997.4
Exp/Cntr=0.3,0.1

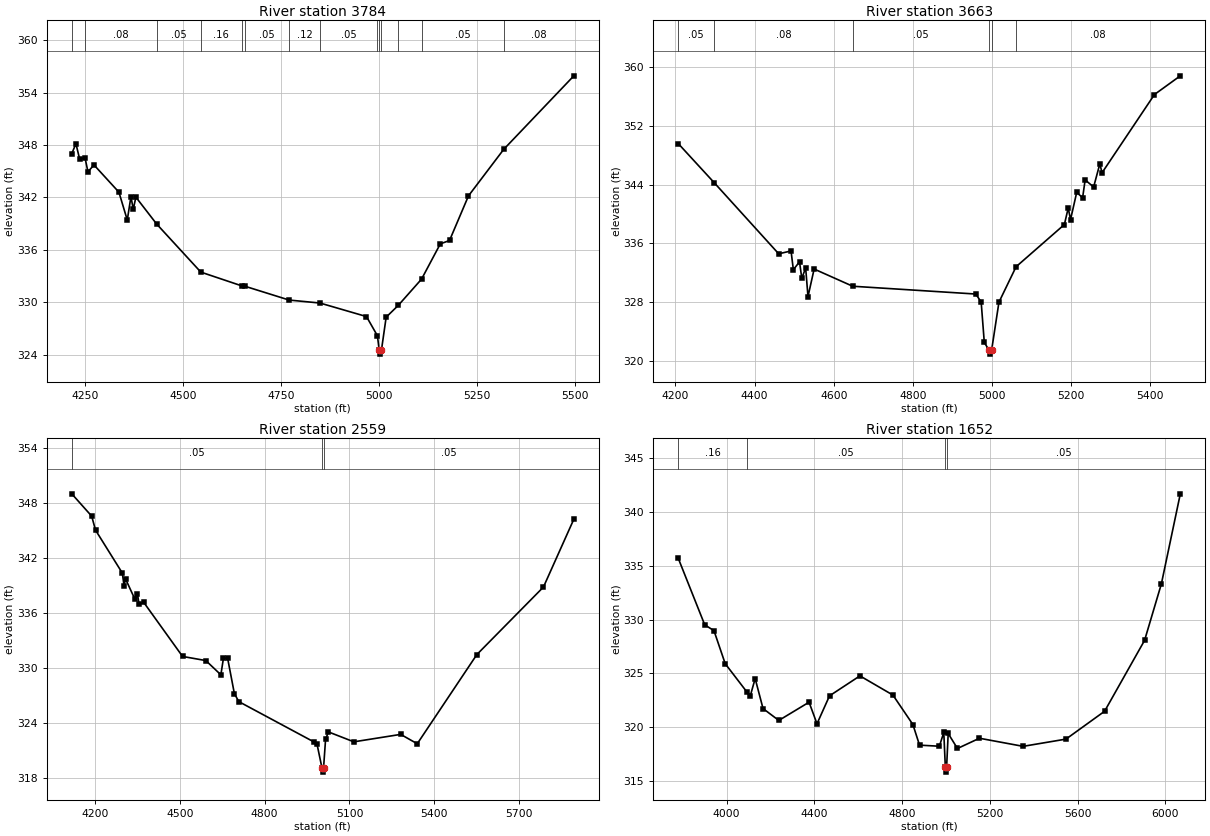
Type RM Length L Ch R = 1,3784,121,121,121
BEGIN DESCRIPTION:
UNT217 IN CCTC 3.0
END DESCRIPTION:
XS GIS Cut Line= 2
      3581662.09     10645949.18      3582339.15     10644860.67
#Sta/Elev= 30
  4216.2  347.01  4226.8  348.15  4236.3  346.39  4250.0  346.54  4257.5  344.93
  4272.9  345.72  4336.6  342.60  4357.9  339.41  4367.3  342.09  4373.2  340.64
  4379.9  342.03  4433.0  338.95  4545.7  333.45  4649.9  331.88  4658.4  331.83
  4771.2  330.25  4849.8  329.91  4968.7  328.36  4996.6  326.16  5001.0  324.56
  5003.8  324.06  5007.0  324.56  5018.9  328.29  5049.8  329.64  5109.3  332.65
  5157.1  336.68  5180.7  337.07  5229.1  342.18  5319.0  347.50  5498.1  355.92
#Mann=14,-1,0
  4216.2    0.05       0  4250.0    0.08       0  4433.0    0.05       0
  4545.7    0.16       0  4649.9    0.08       0  4658.4    0.05       0
  4771.2    0.12       0  4849.8    0.05       0  4996.6    0.12       0
  5001.0    0.07       0  5007.0    0.12       0  5049.8    0.08       0
  5109.3    0.05       0  5319.0    0.08       0
Bank Sta=5001,5007
Exp/Cntr=0.3,0.1

Type RM Length L Ch R = 1,3663,1104,1104,1104
BEGIN DESCRIPTION:
Mapping XS 5b9c5505
END DESCRIPTION:
XS GIS Cut Line= 2
      3581776.64     10646016.94      3582427.69     10644928.38
#Sta/Elev= 30
  4207.2  349.57  4298.4  344.23  4461.0  334.58  4492.2  334.97  4498.0  332.42
  4513.6  333.49  4519.4  331.24  4529.1  332.67  4535.0  328.76  4550.5  332.51
  4648.0  330.17  4959.0  329.11  4972.5  328.02  4980.4  322.53  4992.8  321.44
  4995.5  320.94  4998.8  321.44  5017.4  328.00  5060.7  332.82  5182.7  338.56
  5192.4  340.80  5198.3  339.24  5213.8  342.92  5228.8  342.22  5235.2  344.63
  5256.6  343.66  5272.2  346.80  5278.0  345.61  5410.3  356.24  5475.6  358.78
#Mann=6,-1,0
  4207.2    0.05       0  4298.4    0.08       0  4648.0    0.05       0
  4992.8    0.03       0  4998.8    0.05       0  5060.7    0.08       0
Bank Sta=4992.8,4998.8
Exp/Cntr=0.3,0.1

Type RM Length L Ch R = 1,2559,907,907,907
BEGIN DESCRIPTION:
UNT217 IN CCTC 2.0
END DESCRIPTION:
XS GIS Cut Line= 4
      3582663.38     10646765.16      3582923.79     10646140.18
      3582915.11     10645749.55      3582619.97     10645107.20
#Sta/Elev= 30
  4118.4  348.97  4188.8  346.54  4202.3  345.02  4297.1  340.34  4303.1  338.98
  4308.5  339.70  4340.5  337.56  4350.7  338.07  4356.1  336.93  4373.0  337.14
  4510.0  331.26  4592.3  330.81  4645.4  329.26  4654.6  331.08  4669.2  331.08
  4693.1  327.22  4708.8  326.34  4975.5  321.93  4985.5  321.68  5002.5  319.16
  5005.3  318.66  5008.5  319.16  5015.5  322.22  5025.5  323.04  5115.5  321.96
  5281.1  322.77  5339.6  321.75  5550.4  331.47  5785.7  338.82  5893.1  346.21
#Mann=3,-1,0
  4118.4    0.05       0  5002.5    0.03       0  5008.5    0.05       0
Bank Sta=5002.5,5008.5
Exp/Cntr=0.3,0.1

Type RM Length L Ch R = 1,1652,0,0,0
BEGIN DESCRIPTION:
UNT217 IN CCTC 1.0
END DESCRIPTION:
XS GIS Cut Line= 4
      3583106.07     10646582.91      3583661.64     10645740.87
      3583635.60     10645489.14      3582689.38     10645089.82
#Sta/Elev= 30
  3779.2  335.68  3900.0  329.51  3942.1  328.97  3993.3  325.91  4093.6  323.25
  4107.7  322.93  4129.9  324.53  4165.8  321.75  4237.7  320.65  4375.6  322.34
  4411.8  320.34  4468.9  322.93  4607.5  324.78  4758.0  323.00  4849.0  320.27
  4879.2  318.36  4969.7  318.26  4989.8  319.54  4996.8  316.36  4999.6  315.86
  5002.8  316.36  5009.9  319.44  5052.1  318.05  5152.4  319.00  5351.5  318.25
  5546.9  318.92  5722.9  321.50  5905.2  328.07  5981.8  333.31  6068.1  341.65
#Mann=4,-1,0
  3779.2    0.16       0  4093.6    0.05       0  4996.8    0.03       0
  5002.8    0.05       0
Bank Sta=4996.8,5002.8
Exp/Cntr=0.3,0.1

Chan Stop Cuts=-1