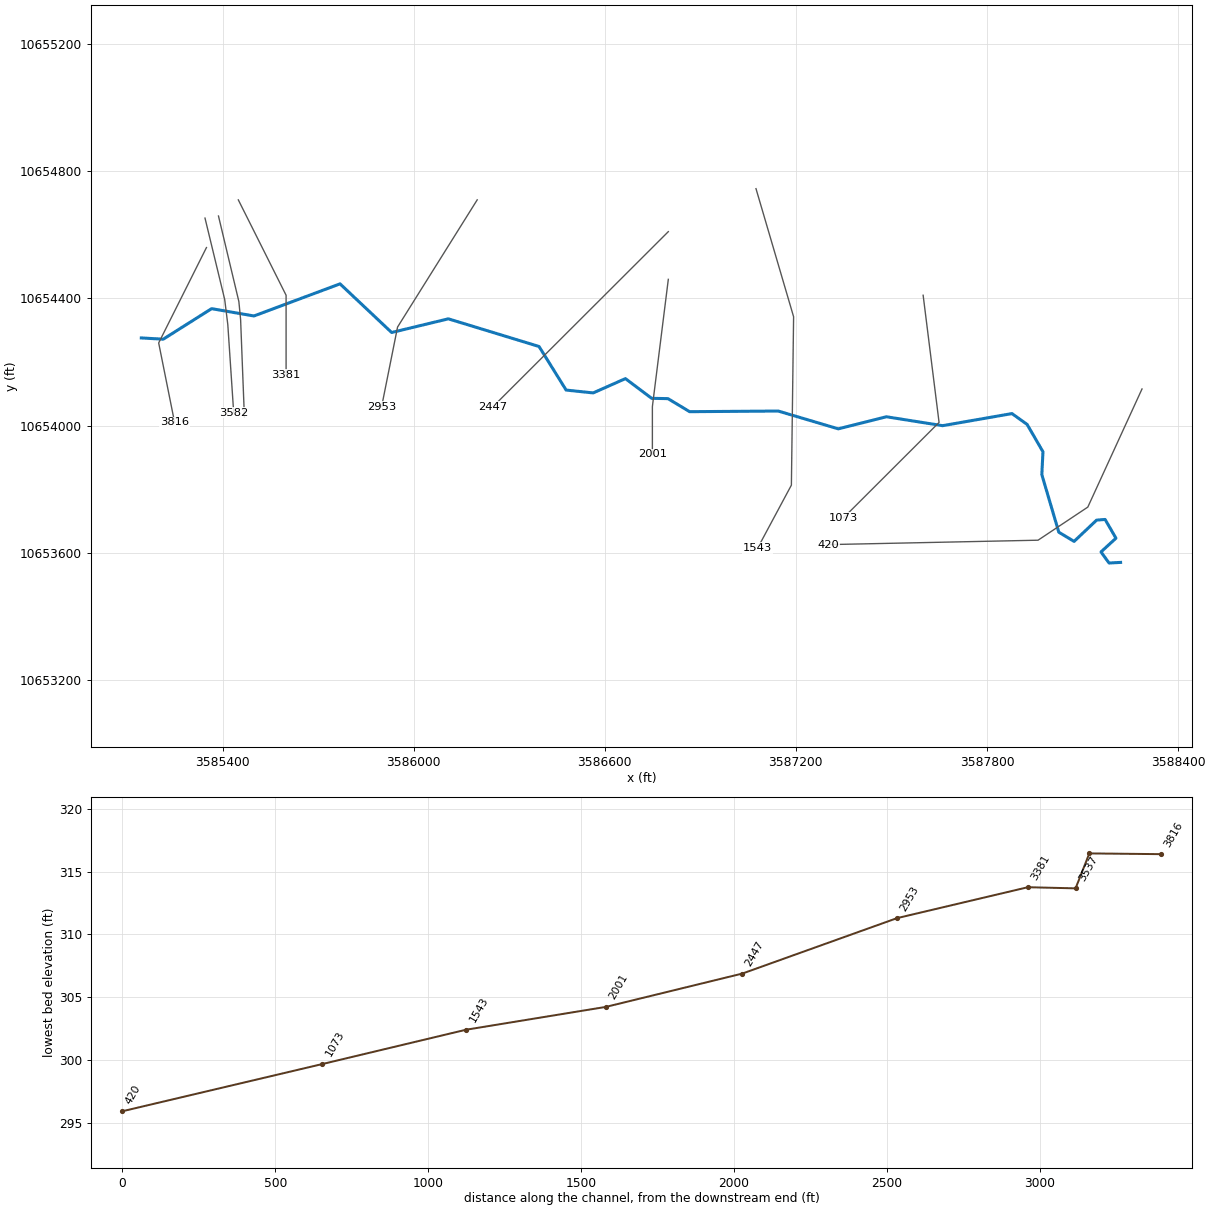
--- UNT220 IN CCTC.prj (project) ---

Proj Title=UNT220 IN CCTC Base Level Engineering
Current Plan=p01
Default Exp/Contr=0.3,0.1
English Units
Geom File=g01
Flow File=f01
Plan File=p01
BEGIN DESCRIPTION:
UNT220 IN CCTC
END DESCRIPTION:

--- UNT220 IN CCTC.p01 (plan) ---

Plan Title=Multiple Run
Short Identifier=Multiple
Geom File=g01
Flow File=f01
Subcritical Flow
K Sum by GR= 0
Std Step Tol= 0.01
Critical Tol= 0.01
Num of Std Step Trials= 20
Max Error Tol= 0.3
Flow Tol Ratio= 0.001
Split Flow NTrial= 30
Split Flow Tol= 0.02
Split Flow Ratio= 0.02
Log Output Level= 0
Friction Slope Method= 1
Unsteady Friction Slope Method= 2
Unsteady Bridges Friction Slope Method= 1
Parabolic Critical Depth
Global Vel Dist=  1 , 1 , 1
Global Log Level= 0
CheckData=True
Encroach Param= -1, 0, 0, 0
BEGIN DESCRIPTION:
Multiple Run
END DESCRIPTION:

--- UNT220 IN CCTC.f01 (steady flow) ---

Flow Title=Multiple
Number of Profiles=7
Profile Names=10-year,25-year,50-year,1pct_min,100-year,1pct_plu,500-year
River Rch & RM= UNT220 IN CCTC,Reach-1,3816
    1511    2100    2593    2339    3163    4277    4687
River Rch & RM= UNT220 IN CCTC,Reach-1,3582
    1901    2670    3318    3008    4068    5501    6095
Boundary for River Rch & Prof#=UNT220 IN CCTC,Reach-1,1
Up Type=0
Dn Type=3
Dn Slope=0.005
Boundary for River Rch & Prof#=UNT220 IN CCTC,Reach-1,2
Up Type=0
Dn Type=3
Dn Slope=0.005
Boundary for River Rch & Prof#=UNT220 IN CCTC,Reach-1,3
Up Type=0
Dn Type=3
Dn Slope=0.005
Boundary for River Rch & Prof#=UNT220 IN CCTC,Reach-1,4
Up Type=0
Dn Type=3
Dn Slope=0.005
Boundary for River Rch & Prof#=UNT220 IN CCTC,Reach-1,5
Up Type=0
Dn Type=3
Dn Slope=0.005
Boundary for River Rch & Prof#=UNT220 IN CCTC,Reach-1,6
Up Type=0
Dn Type=3
Dn Slope=0.005
Boundary for River Rch & Prof#=UNT220 IN CCTC,Reach-1,7
Up Type=0
Dn Type=3
Dn Slope=0.005

--- UNT220 IN CCTC.g01 (geometry) ---

Geom Title=Existing Conditions

River Reach=UNT220 IN CCTC,Reach-1
Reach XY= 30
      3585145.13     10654275.88      3585214.00     10654272.00
      3585365.75     10654368.00      3585498.75     10654345.00
      3585769.00     10654446.00      3585931.00     10654293.00
      3586109.00     10654336.00      3586393.75     10654249.00
      3586478.75     10654112.00      3586563.75     10654103.00
      3586665.00     10654148.00      3586747.25     10654086.00
      3586798.50     10654085.00      3586866.50     10654044.00
      3587144.75     10654046.00      3587333.25     10653990.00
      3587484.25     10654028.00      3587660.75     10654000.00
      3587878.50     10654038.00      3587926.00     10654004.00
      3587975.75     10653918.00      3587972.25     10653846.00
      3588025.50     10653665.00      3588073.50     10653636.00
      3588144.25     10653703.00      3588171.00     10653705.00
      3588205.00     10653646.00      3588158.00     10653603.00
      3588183.25     10653568.00      3588219.50     10653570.00

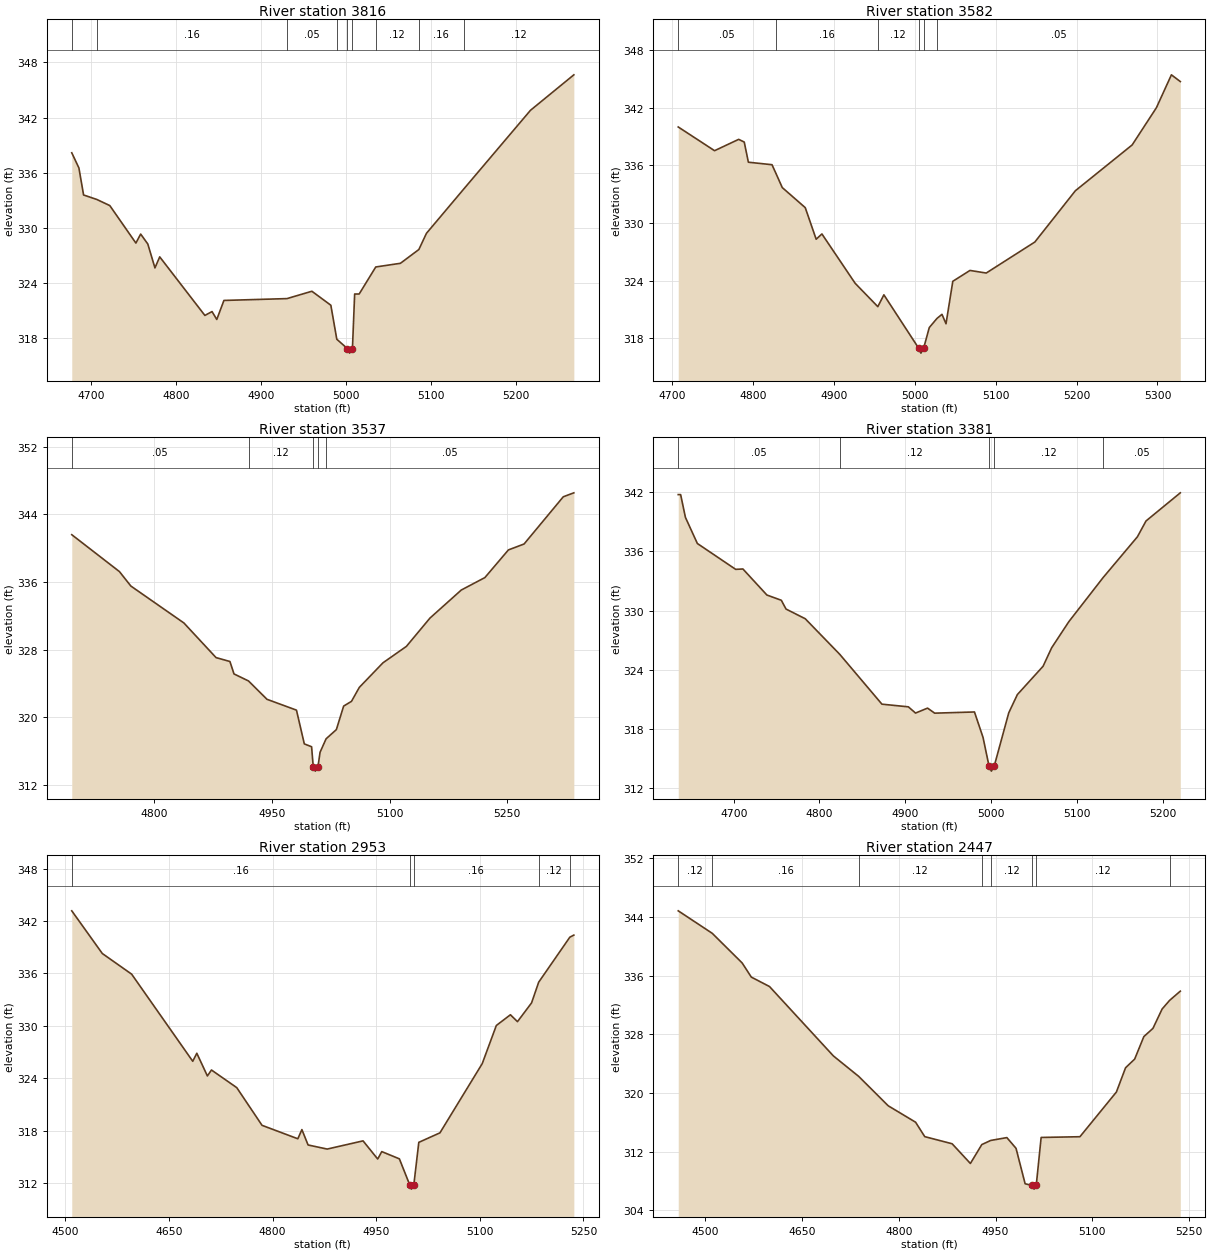
Type RM Length L Ch R = 1,3816,234,234,234
BEGIN DESCRIPTION:
UNT220 IN CCTC 8.0
END DESCRIPTION:
XS GIS Cut Line= 3
      3585349.60     10654560.16      3585199.61     10654260.19
      3585249.60     10654010.22
#Sta/Elev= 30
  4677.4  338.17  4685.8  336.52  4691.3  333.58  4706.7  333.10  4722.1  332.43
  4752.8  328.35  4758.4  329.33  4766.8  328.25  4775.2  325.65  4780.8  326.85
  4833.9  320.48  4842.3  320.90  4847.9  320.04  4856.3  322.11  4930.4  322.31
  4959.7  323.11  4982.0  321.59  4989.0  317.89  5001.4  316.88  5004.1  316.38
  5007.4  316.88  5010.0  322.81  5015.3  322.81  5034.8  325.75  5063.8  326.15
  5085.5  327.65  5094.4  329.41  5138.1  334.21  5216.7  342.79  5267.7  346.65
#Mann=9,-1,0
  4677.4    0.05       0  4706.7    0.16       0  4930.4    0.05       0
  4989.0    0.16       0  5001.4    0.07       0  5007.4    0.16       0
  5034.8    0.12       0  5085.5    0.16       0  5138.1    0.12       0
Bank Sta=5001.4,5007.4
Exp/Cntr=0.3,0.1

Type RM Length L Ch R = 1,3582,45,45,45
BEGIN DESCRIPTION:
Mapping XS f923161a
END DESCRIPTION:
XS GIS Cut Line= 4
      3585345.04     10654652.82      3585406.90     10654396.72
      3585416.66     10654317.51      3585435.11     10654040.80
#Sta/Elev= 30
  4707.6  339.99  4752.5  337.52  4782.3  338.70  4789.2  338.42  4794.3  336.32
  4823.5  336.06  4828.4  335.15  4836.2  333.68  4864.6  331.59  4878.1  328.30
  4885.2  328.85  4926.3  323.71  4954.3  321.28  4961.8  322.51  5004.9  316.94
  5007.6  316.44  5010.9  316.94  5017.9  319.10  5027.4  320.05  5033.6  320.48
  5038.6  319.50  5047.0  323.92  5068.2  325.05  5088.3  324.78  5148.4  328.01
  5198.5  333.35  5268.7  338.12  5298.7  342.00  5317.2  345.42  5328.2  344.72
#Mann=6,-1,0
  4707.6    0.05       0  4828.4    0.16       0  4954.3    0.12       0
  5004.9    0.07       0  5010.9    0.12       0  5027.4    0.05       0
Bank Sta=5004.9,5010.9
Exp/Cntr=0.3,0.1

Type RM Length L Ch R = 1,3537,156,156,156
BEGIN DESCRIPTION:
Mapping XS 47a9c460
END DESCRIPTION:
XS GIS Cut Line= 4
      3585387.36     10654659.32      3585451.39     10654390.21
      3585456.81     10654333.78      3585468.75     10654026.72
#Sta/Elev= 30
  4694.6  341.61  4755.4  337.25  4770.0  335.54  4837.6  331.18  4878.7  327.08
  4896.4  326.62  4901.6  325.15  4920.1  324.32  4943.7  322.15  4981.3  320.87
  4991.3  316.88  5000.6  316.54  5002.7  314.16  5005.4  313.66  5008.7  314.16
  5011.4  315.89  5019.1  317.48  5032.2  318.57  5041.5  321.35  5051.5  321.91
  5061.5  323.56  5091.6  326.46  5121.6  328.41  5151.6  331.75  5191.6  335.07
  5221.7  336.54  5251.7  339.81  5271.7  340.51  5321.7  346.09  5335.2  346.56
#Mann=5,-1,0
  4694.6    0.05       0  4920.1    0.12       0  5002.7    0.07       0
  5008.7    0.12       0  5019.1    0.05       0
Bank Sta=5002.7,5008.7
Exp/Cntr=0.3,0.1

Type RM Length L Ch R = 1,3381,428,428,428
BEGIN DESCRIPTION:
UNT220 IN CCTC 7.0
END DESCRIPTION:
XS GIS Cut Line= 3
      3585449.62     10654710.16      3585599.61     10654410.19
      3585599.61     10654160.16
#Sta/Elev= 30
  4635.3  341.75  4638.1  341.75  4643.7  339.44  4657.6  336.80  4702.3  334.18
  4710.7  334.22  4738.7  331.58  4755.5  331.05  4761.0  330.16  4783.4  329.18
  4823.7  325.57  4872.8  320.53  4903.6  320.26  4912.0  319.63  4926.0  320.13
  4934.3  319.62  4980.7  319.74  4990.7  317.16  4997.7  314.25  5000.4  313.75
  5003.7  314.25  5020.7  319.66  5030.7  321.50  5060.7  324.37  5070.7  326.24
  5090.7  328.88  5130.8  333.36  5170.7  337.48  5180.7  339.08  5220.7  341.93
#Mann=5,-1,0
  4635.3    0.05       0  4823.7    0.12       0  4997.7    0.07       0
  5003.7    0.12       0  5130.8    0.05       0
Bank Sta=4997.7,5003.7
Exp/Cntr=0.3,0.1

Type RM Length L Ch R = 1,2953,506,506,506
BEGIN DESCRIPTION:
UNT220 IN CCTC 6.0
END DESCRIPTION:
XS GIS Cut Line= 3
      3586199.61     10654710.19      3585949.61     10654310.19
      3585899.60     10654060.14
#Sta/Elev= 30
  4509.4  343.18  4553.6  338.29  4596.1  335.92  4684.5  325.94  4690.4  326.86
  4705.7  324.26  4711.6  324.94  4748.2  322.92  4784.8  318.60  4836.6  317.06
  4842.5  318.11  4851.4  316.35  4879.1  315.88  4931.0  316.82  4952.2  314.74
  4958.1  315.59  4983.6  314.76  4998.5  311.79  5001.2  311.29  5004.5  311.79
  5011.7  316.65  5042.3  317.74  5103.5  325.67  5123.9  330.04  5144.3  331.27
  5154.5  330.48  5174.9  332.63  5185.2  335.00  5230.3  340.16  5236.1  340.40
#Mann=5,-1,0
  4509.4    0.16       0  4998.5    0.07       0  5004.5    0.16       0
  5185.2    0.12       0  5230.3    0.16       0
Bank Sta=4998.5,5004.5
Exp/Cntr=0.3,0.1

Type RM Length L Ch R = 1,2447,446,446,446
BEGIN DESCRIPTION:
UNT220 IN CCTC 5.0
END DESCRIPTION:
XS GIS Cut Line= 3
      3586799.62     10654610.20      3586399.61     10654210.19
      3586249.64     10654060.22
#Sta/Elev= 30
  4458.4  344.85  4511.1  341.78  4557.4  337.74  4571.6  335.81  4599.8  334.52
  4698.8  325.05  4738.0  322.26  4783.7  318.25  4826.1  316.01  4840.3  314.04
  4882.7  313.07  4911.0  310.38  4928.7  312.96  4942.4  313.52  4967.5  313.91
  4981.7  312.45  4995.8  307.61  5007.0  307.38  5009.7  306.88  5013.0  307.38
  5020.6  313.93  5080.7  314.03  5137.2  320.13  5151.4  323.44  5165.5  324.62
  5179.7  327.69  5193.8  328.81  5208.0  331.45  5219.6  332.63  5236.2  333.89
#Mann=8,-1,0
  4458.4    0.12       0  4511.1    0.16       0  4738.0    0.12       0
  4928.7    0.16       0  4942.4    0.12       0  5007.0    0.07       0
  5013.0    0.12       0  5219.6    0.05       0
Bank Sta=5007,5013
Exp/Cntr=0.3,0.1

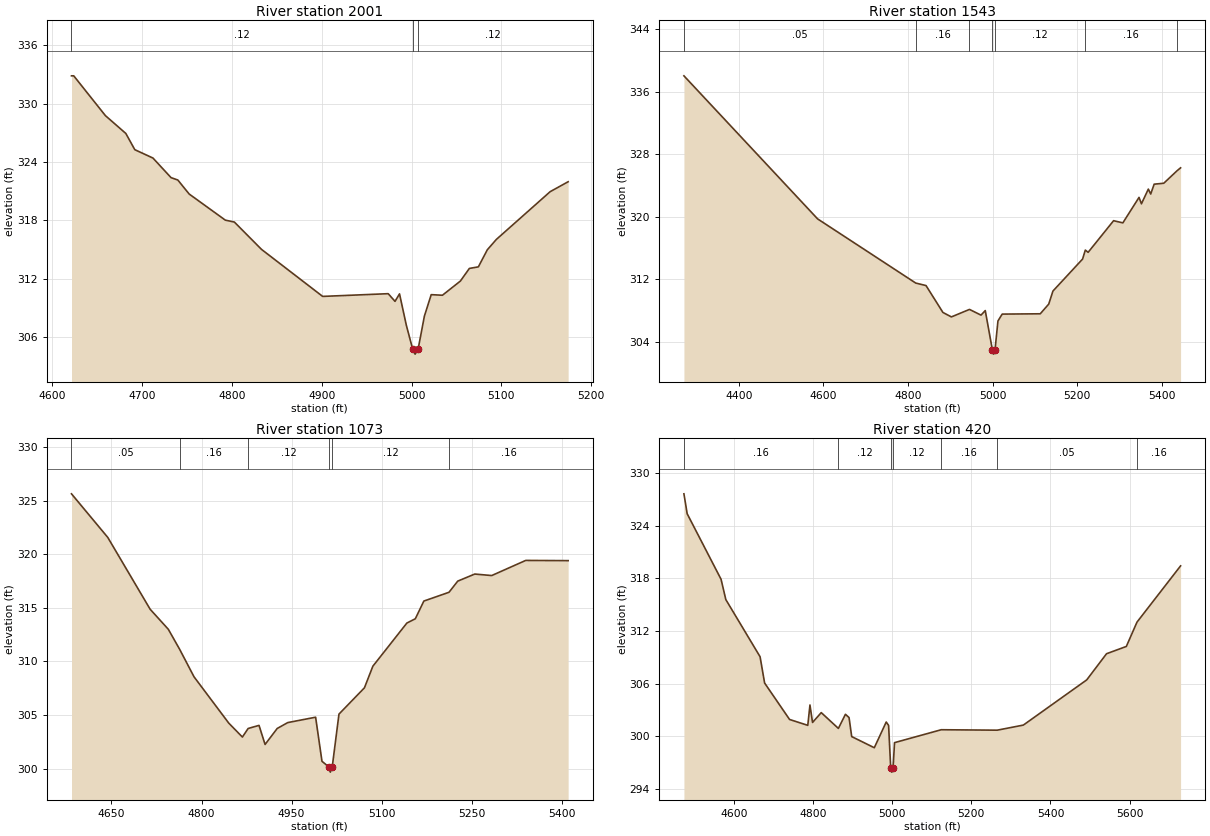
Type RM Length L Ch R = 1,2001,458,458,458
BEGIN DESCRIPTION:
UNT220 IN CCTC 4.0
END DESCRIPTION:
XS GIS Cut Line= 3
      3586799.61     10654460.19      3586749.61     10654060.19
      3586749.61     10653910.20
#Sta/Elev= 30
  4621.2  332.87  4623.7  332.87  4659.0  328.77  4681.7  326.94  4691.7  325.27
  4711.9  324.41  4732.1  322.39  4739.6  322.15  4752.2  320.71  4792.5  318.02
  4802.6  317.82  4832.8  315.01  4900.9  310.17  4973.9  310.45  4981.5  309.66
  4986.5  310.43  4994.1  307.20  5001.2  304.73  5003.9  304.23  5007.2  304.73
  5014.2  308.14  5021.8  310.35  5034.3  310.29  5054.3  311.75  5064.3  313.05
  5074.3  313.21  5084.3  314.97  5094.3  316.03  5154.3  320.95  5174.3  321.97
#Mann=3,-1,0
  4621.2    0.12       0  5001.2    0.07       0  5007.2    0.12       0
Bank Sta=5001.2,5007.2
Exp/Cntr=0.3,0.1

Type RM Length L Ch R = 1,1543,470,470,470
BEGIN DESCRIPTION:
UNT220 IN CCTC 3.0
END DESCRIPTION:
XS GIS Cut Line= 4
      3587074.88     10654745.32      3587192.94     10654342.51
      3587186.00     10653813.00      3587080.14     10653615.16
#Sta/Elev= 30
  4270.5  338.01  4586.4  319.71  4818.3  311.50  4842.6  311.18  4882.6  307.74
  4902.6  307.17  4945.3  308.13  4972.6  307.40  4982.6  307.98  4999.6  302.91
  5002.4  302.41  5005.6  302.91  5012.6  306.65  5022.6  307.53  5112.6  307.57
  5132.6  308.81  5142.6  310.48  5212.6  314.57  5219.1  315.72  5225.7  315.43
  5285.9  319.48  5307.8  319.20  5346.0  322.46  5351.7  321.64  5368.0  323.52
  5373.6  322.89  5381.8  324.15  5404.5  324.27  5435.9  325.87  5444.2  326.24
#Mann=7,-1,0
  4270.5    0.05       0  4818.3    0.16       0  4945.3    0.12       0
  4999.6    0.07       0  5005.6    0.12       0  5219.1    0.16       0
  5435.9    0.12       0
Bank Sta=4999.6,5005.6
Exp/Cntr=0.3,0.1

Type RM Length L Ch R = 1,1073,653,653,653
BEGIN DESCRIPTION:
UNT220 IN CCTC 2.0
END DESCRIPTION:
XS GIS Cut Line= 3
      3587599.61     10654410.20      3587649.61     10654010.19
      3587349.60     10653710.18
#Sta/Elev= 30
  4583.4  325.63  4643.9  321.56  4714.4  314.87  4744.7  313.00  4763.6  311.13
  4787.5  308.57  4845.4  304.25  4868.1  302.95  4877.7  303.75  4895.8  304.04
  4905.9  302.26  4926.1  303.75  4943.7  304.30  4990.1  304.80  5000.7  300.69
  5011.8  300.18  5014.6  299.68  5017.8  300.18  5029.0  305.09  5071.4  307.54
  5085.5  309.56  5142.1  313.58  5156.2  313.98  5170.4  315.63  5212.3  316.45
  5226.9  317.49  5255.2  318.15  5283.5  318.01  5340.1  319.42  5410.8  319.40
#Mann=6,-1,0
  4583.4    0.05       0  4763.6    0.16       0  4877.7    0.12       0
  5011.8    0.07       0  5017.8    0.12       0  5212.3    0.16       0
Bank Sta=5011.8,5017.8
Exp/Cntr=0.3,0.1

Type RM Length L Ch R = 1,420,0,0,0
BEGIN DESCRIPTION:
UNT220 IN CCTC 1.0
END DESCRIPTION:
XS GIS Cut Line= 4
      3588286.76     10654115.45      3588116.63     10653743.96
      3587960.38     10653639.79      3587302.62     10653625.94
#Sta/Elev= 30
  4474.3  327.64  4482.5  325.37  4568.1  317.90  4580.1  315.59  4666.6  309.08
  4678.1  306.08  4741.1  301.93  4787.1  301.26  4792.6  303.58  4799.1  301.59
  4821.1  302.71  4864.4  300.91  4882.2  302.52  4891.3  302.15  4898.0  299.98
  4955.1  298.71  4985.2  301.64  4991.2  301.25  4996.5  296.43  4999.3  295.93
  5002.5  296.43  5006.2  299.29  5124.1  300.76  5265.6  300.71  5331.5  301.29
  5491.6  306.44  5541.6  309.42  5591.6  310.25  5618.5  313.02  5728.6  319.43
#Mann=7,-1,0
  4474.3    0.16       0  4864.4    0.12       0  4996.5    0.07       0
  5002.5    0.12       0  5124.1    0.16       0  5265.6    0.05       0
  5618.5    0.16       0
Bank Sta=4996.5,5002.5
Exp/Cntr=0.3,0.1

Chan Stop Cuts=-1