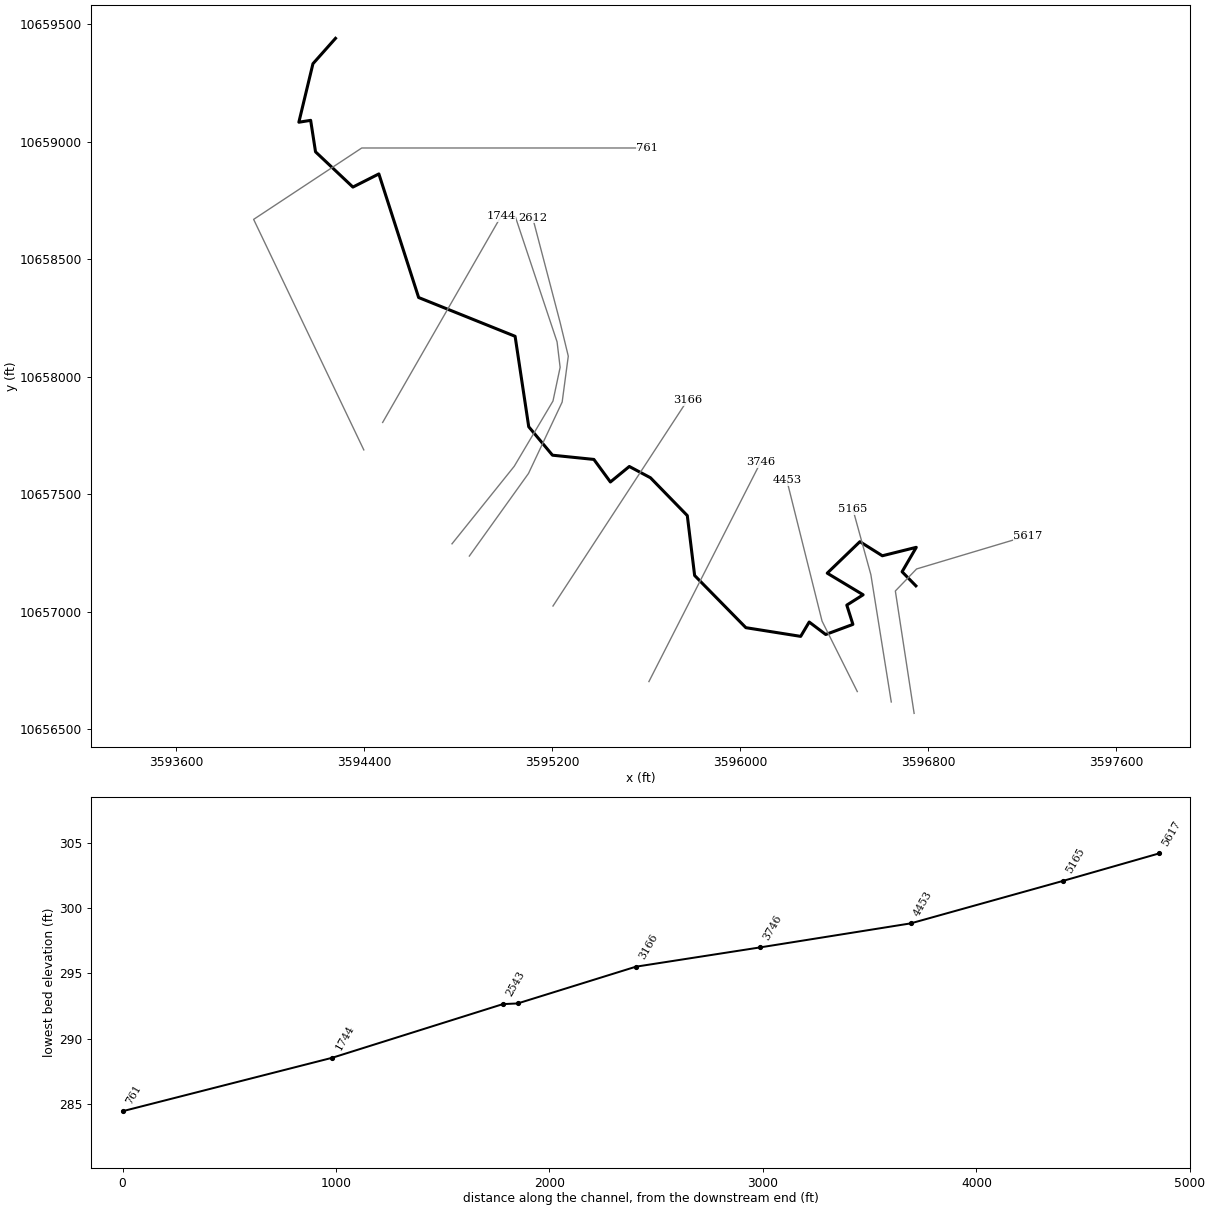
--- UNT222 IN CCTC.prj (project) ---

Proj Title=UNT222 IN CCTC Base Level Engineering
Current Plan=p01
Default Exp/Contr=0.3,0.1
English Units
Geom File=g01
Flow File=f01
Plan File=p01
BEGIN DESCRIPTION:
UNT222 IN CCTC
END DESCRIPTION:

--- UNT222 IN CCTC.p01 (plan) ---

Plan Title=Multiple Run
Short Identifier=Multiple
Geom File=g01
Flow File=f01
Subcritical Flow
K Sum by GR= 0
Std Step Tol= 0.01
Critical Tol= 0.01
Num of Std Step Trials= 20
Max Error Tol= 0.3
Flow Tol Ratio= 0.001
Split Flow NTrial= 30
Split Flow Tol= 0.02
Split Flow Ratio= 0.02
Log Output Level= 0
Friction Slope Method= 1
Unsteady Friction Slope Method= 2
Unsteady Bridges Friction Slope Method= 1
Parabolic Critical Depth
Global Vel Dist=  1 , 1 , 1
Global Log Level= 0
CheckData=True
Encroach Param= -1, 0, 0, 0
BEGIN DESCRIPTION:
Multiple Run
END DESCRIPTION:

--- UNT222 IN CCTC.f01 (steady flow) ---

Flow Title=Multiple
Number of Profiles=7
Profile Names=10-year,25-year,50-year,1pct_min,100-year,1pct_plu,500-year
River Rch & RM= UNT222 IN CCTC,Reach-1,5617
    1506    2081    2558    2296    3105    4199    4557
Boundary for River Rch & Prof#=UNT222 IN CCTC,Reach-1,1
Up Type=0
Dn Type=3
Dn Slope=0.005
Boundary for River Rch & Prof#=UNT222 IN CCTC,Reach-1,2
Up Type=0
Dn Type=3
Dn Slope=0.005
Boundary for River Rch & Prof#=UNT222 IN CCTC,Reach-1,3
Up Type=0
Dn Type=3
Dn Slope=0.005
Boundary for River Rch & Prof#=UNT222 IN CCTC,Reach-1,4
Up Type=0
Dn Type=3
Dn Slope=0.005
Boundary for River Rch & Prof#=UNT222 IN CCTC,Reach-1,5
Up Type=0
Dn Type=3
Dn Slope=0.005
Boundary for River Rch & Prof#=UNT222 IN CCTC,Reach-1,6
Up Type=0
Dn Type=3
Dn Slope=0.005
Boundary for River Rch & Prof#=UNT222 IN CCTC,Reach-1,7
Up Type=0
Dn Type=3
Dn Slope=0.005

--- UNT222 IN CCTC.g01 (geometry) ---

Geom Title=Existing Conditions

River Reach=UNT222 IN CCTC,Reach-1
Reach XY= 30
      3596749.00     10657110.00      3596690.25     10657170.00
      3596750.75     10657274.00      3596606.25     10657238.00
      3596510.75     10657298.00      3596371.75     10657164.00
      3596524.50     10657072.00      3596455.00     10657028.00
      3596481.00     10656946.00      3596365.25     10656903.00
      3596295.00     10656956.00      3596258.75     10656895.00
      3596025.50     10656932.00      3595807.50     10657154.00
      3595776.25     10657409.00      3595619.50     10657570.00
      3595529.50     10657618.00      3595449.00     10657552.00
      3595378.75     10657648.00      3595202.50     10657666.00
      3595101.50     10657787.00      3595043.50     10658172.00
      3594633.00     10658337.00      3594463.75     10658863.00
      3594353.25     10658807.00      3594194.25     10658957.00
      3594173.50     10659091.00      3594123.25     10659083.00
      3594183.25     10659332.00      3594279.25     10659440.00

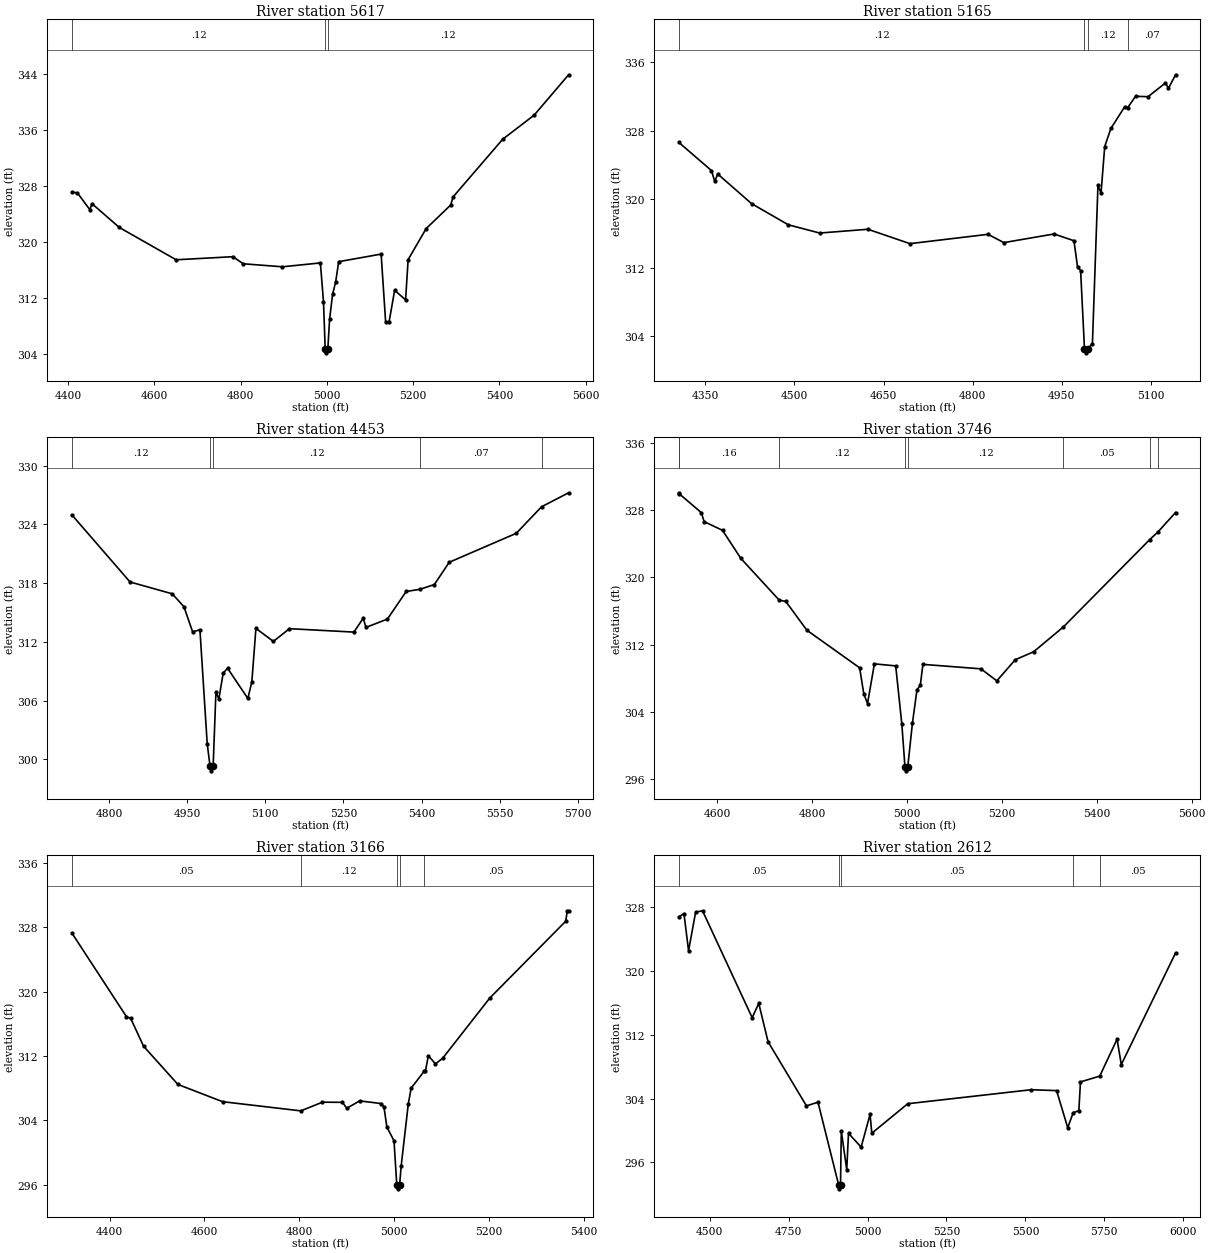
Type RM Length L Ch R = 1,5617,452,452,452
BEGIN DESCRIPTION:
UNT222 IN CCTC 9.0
END DESCRIPTION:
XS GIS Cut Line= 4
      3596741.45     10656567.30      3596661.59     10657088.10
      3596751.87     10657181.85      3597226.06     10657323.76
#Sta/Elev= 30
  4408.4  327.09  4421.4  326.98  4450.1  324.59  4455.2  325.44  4518.5  322.05
  4650.3  317.44  4782.0  317.88  4805.9  316.87  4896.9  316.44  4984.8  316.99
  4992.0  311.48  4996.0  304.67  4998.7  304.17  5002.0  304.67  5006.2  308.97
  5013.1  312.51  5020.3  314.31  5027.3  317.17  5125.7  318.25  5136.1  308.59
  5144.1  308.57  5157.0  313.09  5182.4  311.72  5188.3  317.46  5230.1  321.89
  5286.9  325.24  5292.7  326.42  5407.5  334.62  5480.6  338.07  5560.4  343.82
#Mann=3,-1,0
  4408.4    0.12       0  4996.0    0.07       0  5002.0    0.12       0
Bank Sta=4996,5002
Exp/Cntr=0.3,0.1

Type RM Length L Ch R = 1,5165,712,712,712
BEGIN DESCRIPTION:
UNT222 IN CCTC 8.0
END DESCRIPTION:
XS GIS Cut Line= 3
      3596644.24     10656615.83      3596557.43     10657157.54
      3596481.07     10657435.21
#Sta/Elev= 30
  4305.2  326.64  4360.3  323.34  4365.7  322.07  4370.8  322.94  4427.7  319.49
  4489.7  317.01  4542.5  316.05  4623.7  316.49  4694.5  314.81  4826.1  315.90
  4852.6  314.93  4937.1  315.94  4970.7  315.15  4976.7  312.11  4981.9  311.66
  4988.4  302.56  4991.1  302.06  4994.4  302.56  5001.8  303.15  5011.1  321.61
  5016.3  320.72  5022.5  326.15  5032.9  328.26  5055.9  330.77  5061.3  330.70
  5074.4  332.02  5095.5  331.97  5124.7  333.57  5129.9  332.96  5141.8  334.53
#Mann=4,-1,0
  4305.2    0.12       0  4988.4    0.07       0  4994.4    0.12       0
  5061.3    0.07       0
Bank Sta=4988.4,4994.4
Exp/Cntr=0.3,0.1

Type RM Length L Ch R = 1,4453,707,707,707
BEGIN DESCRIPTION:
UNT222 IN CCTC 7.0
END DESCRIPTION:
XS GIS Cut Line= 3
      3596499.62     10656660.16      3596349.61     10656960.19
      3596199.61     10657560.18
#Sta/Elev= 30
  4728.5  324.97  4840.3  318.11  4921.4  316.90  4943.8  315.58  4960.5  313.01
  4974.5  313.23  4988.5  301.57  4993.9  299.32  4996.6  298.82  4999.9  299.32
  5005.2  306.86  5010.8  306.16  5019.2  308.81  5027.6  309.30  5066.5  306.21
  5074.2  307.92  5082.0  313.37  5115.5  312.04  5146.4  313.34  5270.1  312.99
  5288.1  314.41  5293.3  313.47  5334.5  314.32  5370.6  317.14  5397.0  317.36
  5424.7  317.85  5453.1  320.12  5581.9  323.08  5630.5  325.79  5682.4  327.22
#Mann=5,-1,0
  4728.5    0.12       0  4993.9    0.07       0  4999.9    0.12       0
  5397.0    0.07       0  5630.5    0.12       0
Bank Sta=4993.9,4999.9
Exp/Cntr=0.3,0.1

Type RM Length L Ch R = 1,3746,580,580,580
BEGIN DESCRIPTION:
UNT222 IN CCTC 6.0
END DESCRIPTION:
XS GIS Cut Line= 2
      3595612.98     10656702.67      3596088.27     10657635.91
#Sta/Elev= 30
  4518.8  330.07  4519.6  329.96  4566.5  327.70  4572.1  326.64  4611.0  325.60
  4649.8  322.25  4730.6  317.29  4744.4  317.14  4788.9  313.71  4900.1  309.24
  4908.8  306.16  4916.7  304.98  4931.2  309.71  4976.1  309.47  4989.0  302.57
  4995.6  297.48  4998.3  296.98  5001.6  297.48  5011.3  302.62  5021.0  306.64
  5027.9  307.14  5033.5  309.65  5155.7  309.12  5189.3  307.69  5228.1  310.20
  5266.9  311.15  5329.7  314.11  5511.3  324.48  5528.5  325.38  5566.1  327.72
#Mann=8,-1,0
  4518.8    0.12       0  4519.6    0.16       0  4730.6    0.12       0
  4995.6    0.07       0  5001.6    0.12       0  5329.7    0.05       0
  5511.3    0.12       0  5528.5    0.16       0
Bank Sta=4995.6,5001.6
Exp/Cntr=0.3,0.1

Type RM Length L Ch R = 1,3166,554,554,554
BEGIN DESCRIPTION:
UNT222 IN CCTC 5.0
END DESCRIPTION:
XS GIS Cut Line= 2
      3595204.71     10657024.16      3595777.61     10657900.87
#Sta/Elev= 30
  4320.4  327.28  4435.5  316.89  4444.6  316.66  4471.7  313.21  4544.1  308.47
  4638.2  306.33  4803.2  305.19  4848.8  306.27  4891.0  306.25  4900.1  305.51
  4927.2  306.43  4972.5  306.10  4978.5  305.64  4984.6  303.20  4999.6  301.47
  5005.5  296.01  5008.3  295.51  5011.5  296.01  5014.7  298.33  5029.8  306.07
  5035.8  308.01  5062.8  310.08  5066.0  310.16  5072.0  312.03  5087.1  311.02
  5102.2  311.72  5201.6  319.20  5361.6  328.73  5365.0  330.03  5367.7  330.03
#Mann=5,-1,0
  4320.4    0.05       0  4803.2    0.12       0  5005.5    0.07       0
  5011.5    0.12       0  5062.8    0.05       0
Bank Sta=5005.5,5011.5
Exp/Cntr=0.3,0.1

Type RM Length L Ch R = 1,2612,69,69,69
BEGIN DESCRIPTION:
UNT222 IN CCTC 4.0
END DESCRIPTION:
XS GIS Cut Line= 6
      3594848.82     10657236.84      3595100.54     10657588.39
      3595243.77     10657892.21      3595269.81     10658087.52
      3595235.09     10658230.75      3595118.24     10658676.50
#Sta/Elev= 30
  4402.1  326.72  4418.5  327.14  4433.1  322.49  4455.4  327.32  4477.3  327.49
  4634.6  314.11  4655.4  315.91  4684.9  311.10  4806.5  303.08  4843.0  303.54
  4908.4  293.20  4911.1  292.70  4914.4  293.20  4916.9  299.93  4934.1  295.10
  4939.7  299.65  4979.7  297.92  5008.0  302.02  5013.5  299.66  5127.4  303.35
  5518.0  305.10  5598.8  304.99  5634.0  300.35  5651.3  302.21  5669.3  302.49
  5674.4  306.08  5735.4  306.80  5790.4  311.42  5803.7  308.25  5975.6  322.21
#Mann=5,-1,0
  4402.1    0.05       0  4908.4    0.03       0  4914.4    0.05       0
  5651.3    0.16       0  5735.4    0.05       0
Bank Sta=4908.4,4914.4
Exp/Cntr=0.3,0.1

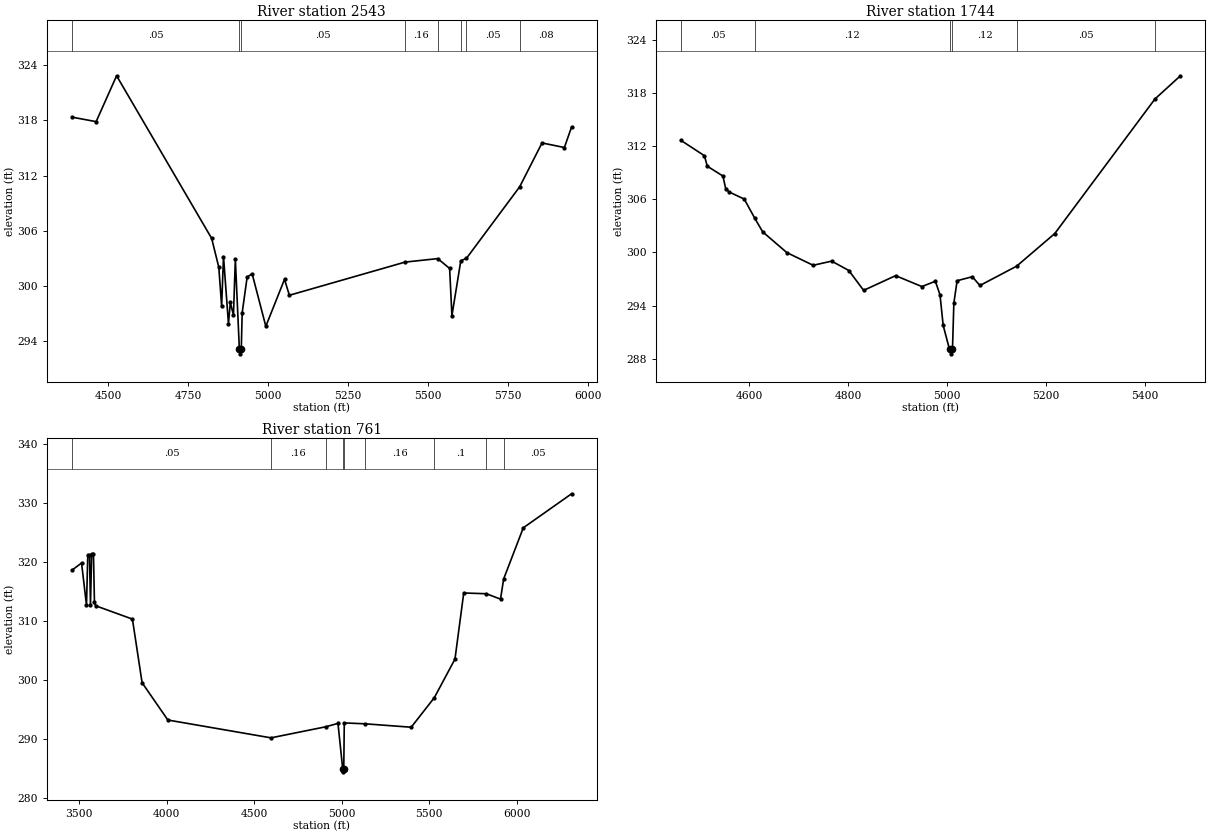
Type RM Length L Ch R = 1,2543,799,799,799
BEGIN DESCRIPTION:
UNT222 IN CCTC 3.0
END DESCRIPTION:
XS GIS Cut Line= 6
      3594775.00     10657288.88      3595039.78     10657618.77
      3595204.71     10657896.55      3595235.09     10658039.77
      3595222.07     10658148.28      3595044.35     10658681.45
#Sta/Elev= 30
  4386.1  318.35  4461.8  317.86  4525.8  322.84  4823.4  305.18  4845.7  302.05
  4854.6  297.84  4860.4  303.21  4876.0  295.91  4881.8  298.23  4891.6  296.85
  4897.5  302.93  4910.1  293.15  4912.8  292.65  4916.1  293.15  4918.9  297.11
  4934.5  301.00  4950.1  301.34  4992.9  295.64  5051.4  300.74  5066.6  299.01
  5428.7  302.61  5531.0  302.99  5568.2  301.92  5575.4  296.80  5603.2  302.76
  5620.9  303.02  5787.5  310.79  5857.4  315.55  5927.4  315.05  5949.9  317.28
#Mann=8,-1,0
  4386.1    0.05       0  4910.1    0.03       0  4916.1    0.05       0
  5428.7    0.16       0  5531.0    0.05       0  5603.2    0.16       0
  5620.9    0.05       0  5787.5    0.08       0
Bank Sta=4910.1,4916.1
Exp/Cntr=0.3,0.1

Type RM Length L Ch R = 1,1744,983,983,983
BEGIN DESCRIPTION:
UNT222 IN CCTC 2.0
END DESCRIPTION:
XS GIS Cut Line= 2
      3594479.87     10657805.39      3594983.34     10658682.11
#Sta/Elev= 30
  4461.5  312.64  4509.3  310.90  4515.0  309.72  4546.7  308.61  4552.4  307.16
  4559.3  306.81  4589.8  306.01  4611.1  303.85  4627.2  302.31  4676.1  299.97
  4729.3  298.54  4766.7  299.01  4801.5  297.95  4831.4  295.71  4896.1  297.37
  4949.3  296.14  4976.6  296.74  4986.0  295.20  4992.4  291.76  5005.2  289.05
  5008.0  288.55  5011.2  289.05  5014.0  294.26  5020.6  296.80  5051.4  297.25
  5066.7  296.26  5141.0  298.44  5218.2  302.12  5420.9  317.30  5472.5  319.92
#Mann=6,-1,0
  4461.5    0.05       0  4611.1    0.12       0  5005.2    0.07       0
  5011.2    0.12       0  5141.0    0.05       0  5420.9     0.1       0
Bank Sta=5005.2,5011.2
Exp/Cntr=0.3,0.1

Type RM Length L Ch R = 1,761,0,0,0
BEGIN DESCRIPTION:
UNT222 IN CCTC 1.0
END DESCRIPTION:
XS GIS Cut Line= 4
      3594399.60     10657688.61      3593930.84     10658669.55
      3594390.91     10658973.37      3595605.38     10658973.37
#Sta/Elev= 30
  3459.3  318.63  3514.1  319.85  3542.3  312.71  3549.7  321.15  3559.5  321.16
  3565.0  312.80  3571.9  321.40  3582.1  321.41  3587.7  313.24  3594.0  312.61
  3804.6  310.34  3859.8  299.56  4007.0  293.24  4595.9  290.22  4907.6  292.09
  4978.3  292.67  5005.4  284.96  5008.1  284.46  5011.4  284.96  5014.4  292.75
  5132.8  292.60  5396.5  292.02  5528.6  297.03  5646.5  303.57  5696.5  314.77
  5825.5  314.64  5906.5  313.73  5924.4  317.14  6036.5  325.81  6312.3  331.58
#Mann=9,-1,0
  3459.3    0.05       0  4595.9    0.16       0  4907.6    0.12       0
  5005.4    0.07       0  5011.4    0.12       0  5132.8    0.16       0
  5528.6     0.1       0  5825.5    0.08       0  5924.4    0.05       0
Bank Sta=5005.4,5011.4
Exp/Cntr=0.3,0.1

Chan Stop Cuts=-1