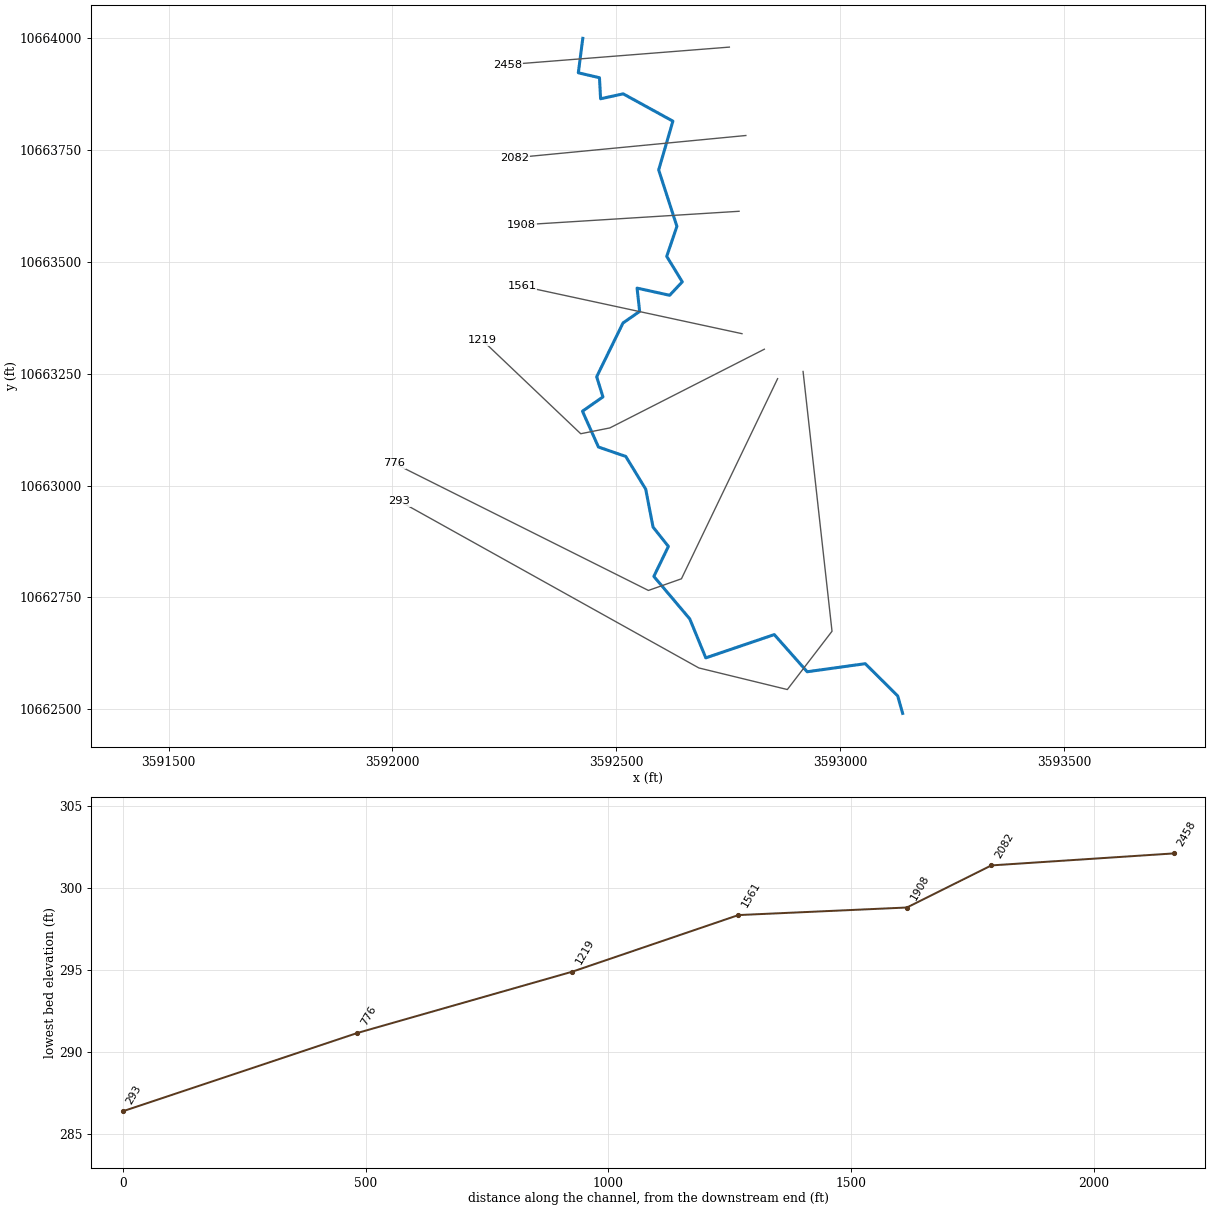
--- UNT224 IN CCTC.prj (project) ---

Proj Title=UNT224 IN CCTC Base Level Engineering
Current Plan=p01
Default Exp/Contr=0.3,0.1
English Units
Geom File=g01
Flow File=f01
Plan File=p01
BEGIN DESCRIPTION:
UNT224 IN CCTC
END DESCRIPTION:

--- UNT224 IN CCTC.p01 (plan) ---

Plan Title=Multiple Run
Short Identifier=Multiple
Geom File=g01
Flow File=f01
Subcritical Flow
K Sum by GR= 0
Std Step Tol= 0.01
Critical Tol= 0.01
Num of Std Step Trials= 20
Max Error Tol= 0.3
Flow Tol Ratio= 0.001
Split Flow NTrial= 30
Split Flow Tol= 0.02
Split Flow Ratio= 0.02
Log Output Level= 0
Friction Slope Method= 1
Unsteady Friction Slope Method= 2
Unsteady Bridges Friction Slope Method= 1
Parabolic Critical Depth
Global Vel Dist=  1 , 1 , 1
Global Log Level= 0
CheckData=True
Encroach Param= -1, 0, 0, 0
BEGIN DESCRIPTION:
Multiple Run
END DESCRIPTION:

--- UNT224 IN CCTC.f01 (steady flow) ---

Flow Title=Multiple
Number of Profiles=7
Profile Names=10-year,25-year,50-year,1pct_min,100-year,1pct_plu,500-year
River Rch & RM= UNT224 IN CCTC,Reach-1,2458
     560     726     856     738     999    1351    1352
Boundary for River Rch & Prof#=UNT224 IN CCTC,Reach-1,1
Up Type=0
Dn Type=3
Dn Slope=0.005
Boundary for River Rch & Prof#=UNT224 IN CCTC,Reach-1,2
Up Type=0
Dn Type=3
Dn Slope=0.005
Boundary for River Rch & Prof#=UNT224 IN CCTC,Reach-1,3
Up Type=0
Dn Type=3
Dn Slope=0.005
Boundary for River Rch & Prof#=UNT224 IN CCTC,Reach-1,4
Up Type=0
Dn Type=3
Dn Slope=0.005
Boundary for River Rch & Prof#=UNT224 IN CCTC,Reach-1,5
Up Type=0
Dn Type=3
Dn Slope=0.005
Boundary for River Rch & Prof#=UNT224 IN CCTC,Reach-1,6
Up Type=0
Dn Type=3
Dn Slope=0.005
Boundary for River Rch & Prof#=UNT224 IN CCTC,Reach-1,7
Up Type=0
Dn Type=3
Dn Slope=0.005

--- UNT224 IN CCTC.g01 (geometry) ---

Geom Title=Existing Conditions

River Reach=UNT224 IN CCTC,Reach-1
Reach XY= 30
      3592425.25     10663999.00      3592415.25     10663922.00
      3592462.50     10663911.00      3592465.00     10663864.00
      3592515.50     10663875.00      3592626.50     10663814.00
      3592594.75     10663705.00      3592635.50     10663579.00
      3592612.75     10663512.00      3592647.50     10663455.00
      3592619.25     10663425.00      3592546.50     10663441.00
      3592552.25     10663389.00      3592515.00     10663363.00
      3592456.25     10663243.00      3592470.25     10663198.00
      3592424.50     10663166.00      3592460.25     10663086.00
      3592521.25     10663065.00      3592565.75     10662992.00
      3592582.25     10662907.00      3592616.50     10662864.00
      3592584.00     10662797.00      3592664.25     10662702.00
      3592700.00     10662615.00      3592853.00     10662667.00
      3592926.50     10662584.00      3593056.25     10662602.00
      3593128.75     10662530.00      3593139.75     10662491.00

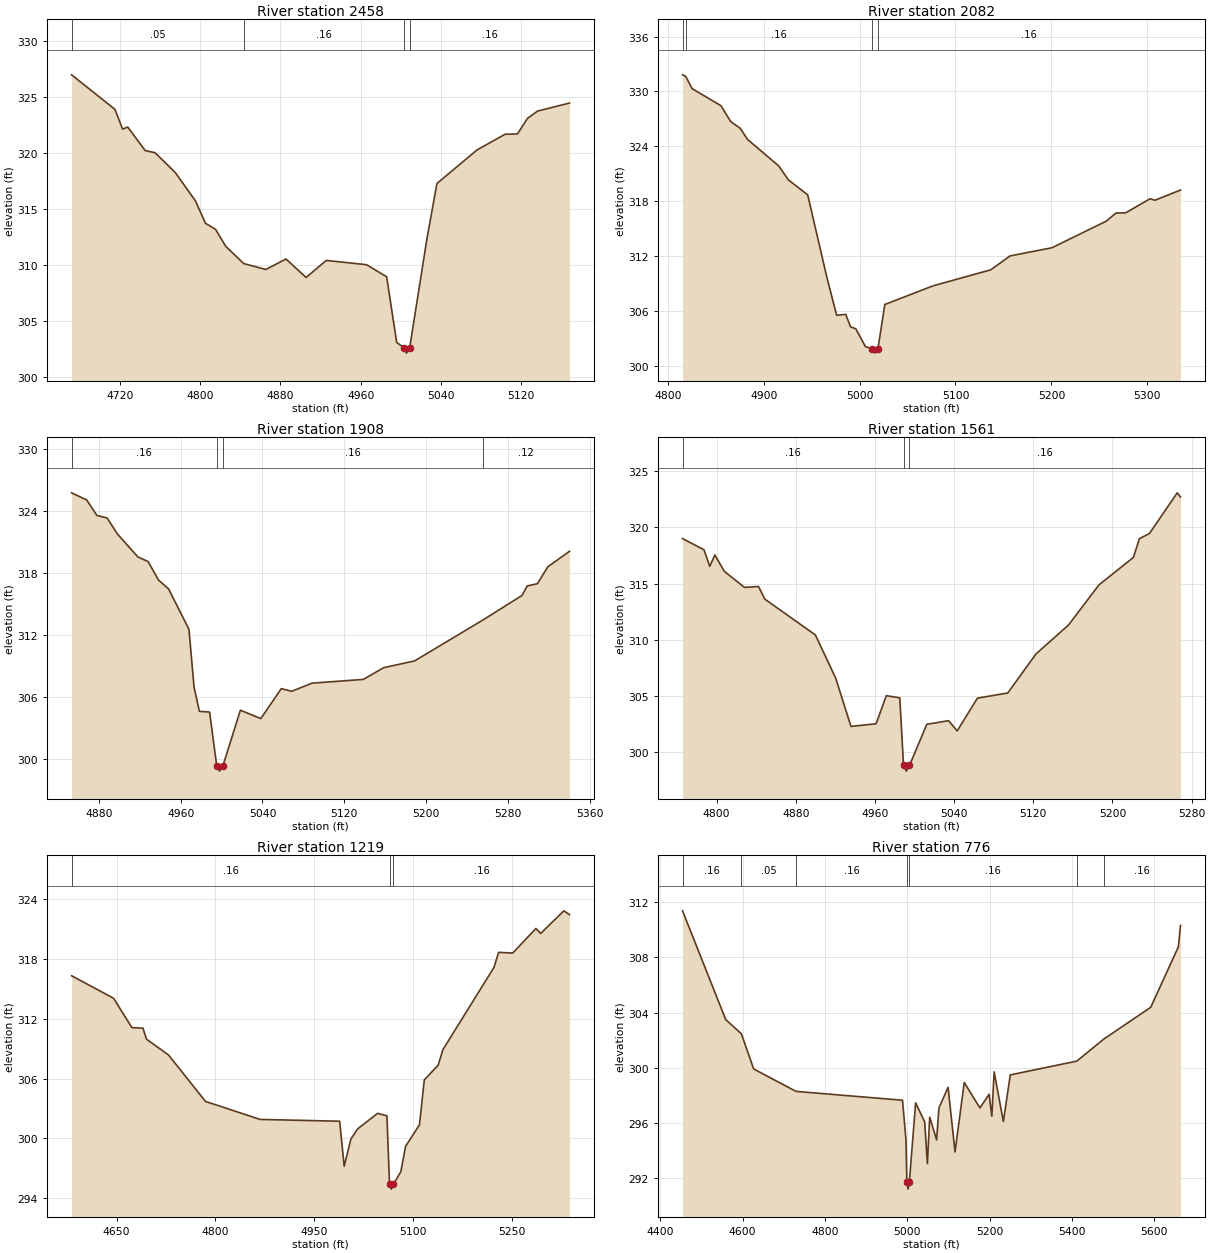
Type RM Length L Ch R = 1,2458,376,376,376
BEGIN DESCRIPTION:
UNT224 IN CCTC 2.0
END DESCRIPTION:
XS GIS Cut Line= 2
      3592752.69     10663979.41      3592257.83     10663940.34
#Sta/Elev= 30
  4671.8  326.95  4715.0  323.87  4722.7  322.10  4727.8  322.29  4745.1  320.19
  4755.1  319.99  4775.2  318.22  4795.3  315.69  4805.3  313.69  4815.3  313.15
  4825.4  311.64  4843.4  310.09  4865.5  309.56  4885.5  310.50  4905.6  308.85
  4925.7  310.37  4965.8  309.99  4985.9  308.91  4995.9  303.05  5002.9  302.59
  5005.7  302.09  5008.9  302.59  5026.0  312.27  5036.0  317.24  5076.1  320.25
  5103.9  321.64  5116.3  321.67  5126.3  323.06  5136.3  323.71  5168.2  324.43
#Mann=4,-1,0
  4671.8    0.05       0  4843.4    0.16       0  5002.9    0.07       0
  5008.9    0.16       0
Bank Sta=5002.9,5008.9
Exp/Cntr=0.3,0.1

Type RM Length L Ch R = 1,2082,174,174,174
BEGIN DESCRIPTION:
Mapping XS d9789fd2
END DESCRIPTION:
XS GIS Cut Line= 2
      3592789.53     10663781.92      3592272.71     10663732.19
#Sta/Elev= 30
  4815.4  331.82  4818.7  331.66  4825.4  330.31  4855.5  328.44  4865.5  326.72
  4875.6  325.96  4883.2  324.75  4915.8  321.84  4925.8  320.32  4945.9  318.69
  4966.0  309.61  4976.1  305.50  4985.6  305.60  4990.6  304.24  4996.1  304.02
  5006.2  302.06  5013.2  301.86  5016.0  301.36  5019.2  301.86  5026.3  306.68
  5076.5  308.72  5136.8  310.48  5156.9  312.00  5200.5  312.89  5257.3  315.81
  5267.4  316.70  5277.4  316.71  5302.9  318.26  5307.9  318.09  5334.6  319.21
#Mann=4,-1,0
  4815.4    0.05       0  4818.7    0.16       0  5013.2    0.07       0
  5019.2    0.16       0
Bank Sta=5013.2,5019.2
Exp/Cntr=0.3,0.1

Type RM Length L Ch R = 1,1908,347,347,347
BEGIN DESCRIPTION:
Mapping XS 2be78ba6
END DESCRIPTION:
XS GIS Cut Line= 2
      3592774.36     10663612.65      3592288.31     10663582.28
#Sta/Elev= 30
  4853.3  325.75  4868.1  325.06  4878.1  323.56  4888.1  323.31  4898.1  321.77
  4918.2  319.54  4928.2  319.09  4938.2  317.32  4948.2  316.44  4968.1  312.54
  4973.1  306.93  4978.3  304.59  4988.3  304.52  4995.3  299.30  4998.1  298.80
  5001.3  299.30  5018.4  304.70  5038.4  303.89  5058.4  306.79  5068.5  306.53
  5088.5  307.32  5138.6  307.68  5158.6  308.82  5188.7  309.47  5255.7  313.44
  5293.8  315.81  5298.9  316.73  5308.9  316.95  5319.0  318.58  5340.3  320.09
#Mann=4,-1,0
  4853.3    0.16       0  4995.3    0.07       0  5001.3    0.16       0
  5255.7    0.12       0
Bank Sta=4995.3,5001.3
Exp/Cntr=0.3,0.1

Type RM Length L Ch R = 1,1561,342,342,342
BEGIN DESCRIPTION:
Mapping XS 4216ffb8
END DESCRIPTION:
XS GIS Cut Line= 2
      3592780.83     10663339.23      3592289.06     10663445.38
#Sta/Elev= 30
  4765.6  319.00  4787.3  318.00  4793.1  316.53  4798.3  317.54  4807.8  316.09
  4828.2  314.66  4842.4  314.74  4848.7  313.62  4899.8  310.44  4920.3  306.61
  4935.8  302.31  4961.2  302.55  4971.5  305.04  4985.1  304.85  4988.9  298.84
  4991.7  298.34  4994.9  298.84  5012.4  302.50  5034.4  302.82  5043.1  301.91
  5063.5  304.82  5094.2  305.28  5122.7  308.75  5155.6  311.32  5186.3  314.88
  5221.2  317.33  5227.2  318.99  5237.4  319.45  5265.4  323.06  5268.7  322.69
#Mann=3,-1,0
  4765.6    0.16       0  4988.9    0.07       0  4994.9    0.16       0
Bank Sta=4988.9,4994.9
Exp/Cntr=0.3,0.1

Type RM Length L Ch R = 1,1219,443,443,443
BEGIN DESCRIPTION:
Mapping XS d30d9813
END DESCRIPTION:
XS GIS Cut Line= 4
      3592830.78     10663304.49      3592485.74     10663128.71
      3592420.64     10663115.69      3592201.47     10663324.01
#Sta/Elev= 30
  4581.5  316.33  4645.3  314.07  4673.1  311.12  4689.8  311.07  4695.4  309.95
  4728.6  308.38  4784.8  303.71  4867.7  301.90  4988.5  301.72  4995.4  297.21
  5005.6  299.93  5015.8  300.95  5046.2  302.51  5060.3  302.26  5064.2  295.40
  5067.0  294.90  5070.2  295.40  5081.4  296.65  5088.6  299.20  5109.7  301.36
  5117.0  305.87  5138.0  307.34  5145.3  308.91  5222.9  317.18  5229.8  318.68
  5251.3  318.61  5286.5  321.08  5293.7  320.58  5328.9  322.85  5337.5  322.47
#Mann=3,-1,0
  4581.5    0.16       0  5064.2    0.07       0  5070.2    0.16       0
Bank Sta=5064.2,5070.2
Exp/Cntr=0.3,0.1

Type RM Length L Ch R = 1,776,483,483,483
BEGIN DESCRIPTION:
Mapping XS 4f2155ee
END DESCRIPTION:
XS GIS Cut Line= 4
      3592860.49     10663238.73      3592645.63     10662791.65
      3592571.85     10662765.61      3592003.95     10663049.55
#Sta/Elev= 30
  4454.2  311.39  4559.1  303.49  4597.2  302.45  4627.0  299.90  4730.0  298.27
  4988.4  297.63  4996.7  294.78  4999.0  291.67  5001.8  291.17  5005.0  291.67
  5020.2  297.44  5042.2  296.06  5048.8  293.02  5054.4  296.40  5071.2  294.75
  5076.8  297.07  5099.1  298.57  5115.9  293.87  5138.3  298.92  5176.3  297.07
  5198.7  298.06  5205.3  296.47  5210.9  299.69  5233.3  296.08  5250.1  299.47
  5411.6  300.47  5476.6  302.06  5591.1  304.38  5658.2  308.77  5663.4  310.33
#Mann=7,-1,0
  4454.2    0.16       0  4597.2    0.05       0  4730.0    0.16       0
  4999.0    0.07       0  5005.0    0.16       0  5411.6    0.05       0
  5476.6    0.16       0
Bank Sta=4999,5005
Exp/Cntr=0.3,0.1

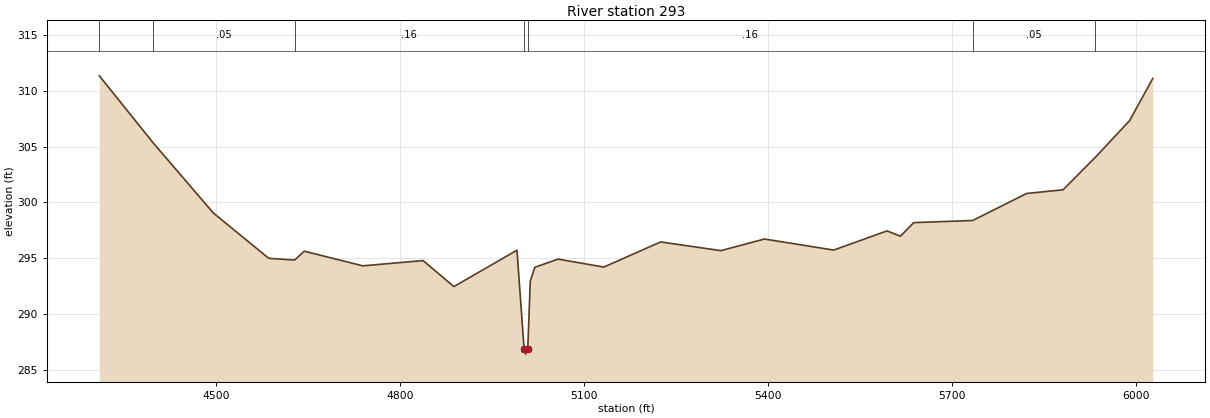
Type RM Length L Ch R = 1,293,0,0,0
BEGIN DESCRIPTION:
UNT224 IN CCTC 1.0
END DESCRIPTION:
XS GIS Cut Line= 5
      3592917.33     10663254.80      3592982.00     10662674.46
      3592882.18     10662544.25      3592684.55     10662592.47
      3592015.19     10662965.49
#Sta/Elev= 30
  4310.1  311.34  4398.3  305.31  4495.9  299.06  4586.4  294.99  4628.6  294.84
  4644.2  295.63  4739.7  294.32  4838.0  294.79  4888.3  292.46  4991.1  295.72
  5002.7  286.91  5005.4  286.41  5008.7  286.91  5012.8  292.95  5020.2  294.19
  5058.1  294.92  5132.8  294.21  5225.4  296.46  5323.7  295.68  5394.6  296.72
  5507.6  295.73  5594.6  297.45  5616.3  296.97  5638.1  298.19  5734.2  298.38
  5822.1  300.80  5881.5  301.13  5934.2  304.04  5990.1  307.33  6027.8  311.10
#Mann=7,-1,0
  4310.1    0.16       0  4398.3    0.05       0  4628.6    0.16       0
  5002.7    0.07       0  5008.7    0.16       0  5734.2    0.05       0
  5934.2    0.16       0
Bank Sta=5002.7,5008.7
Exp/Cntr=0.3,0.1

Chan Stop Cuts=-1