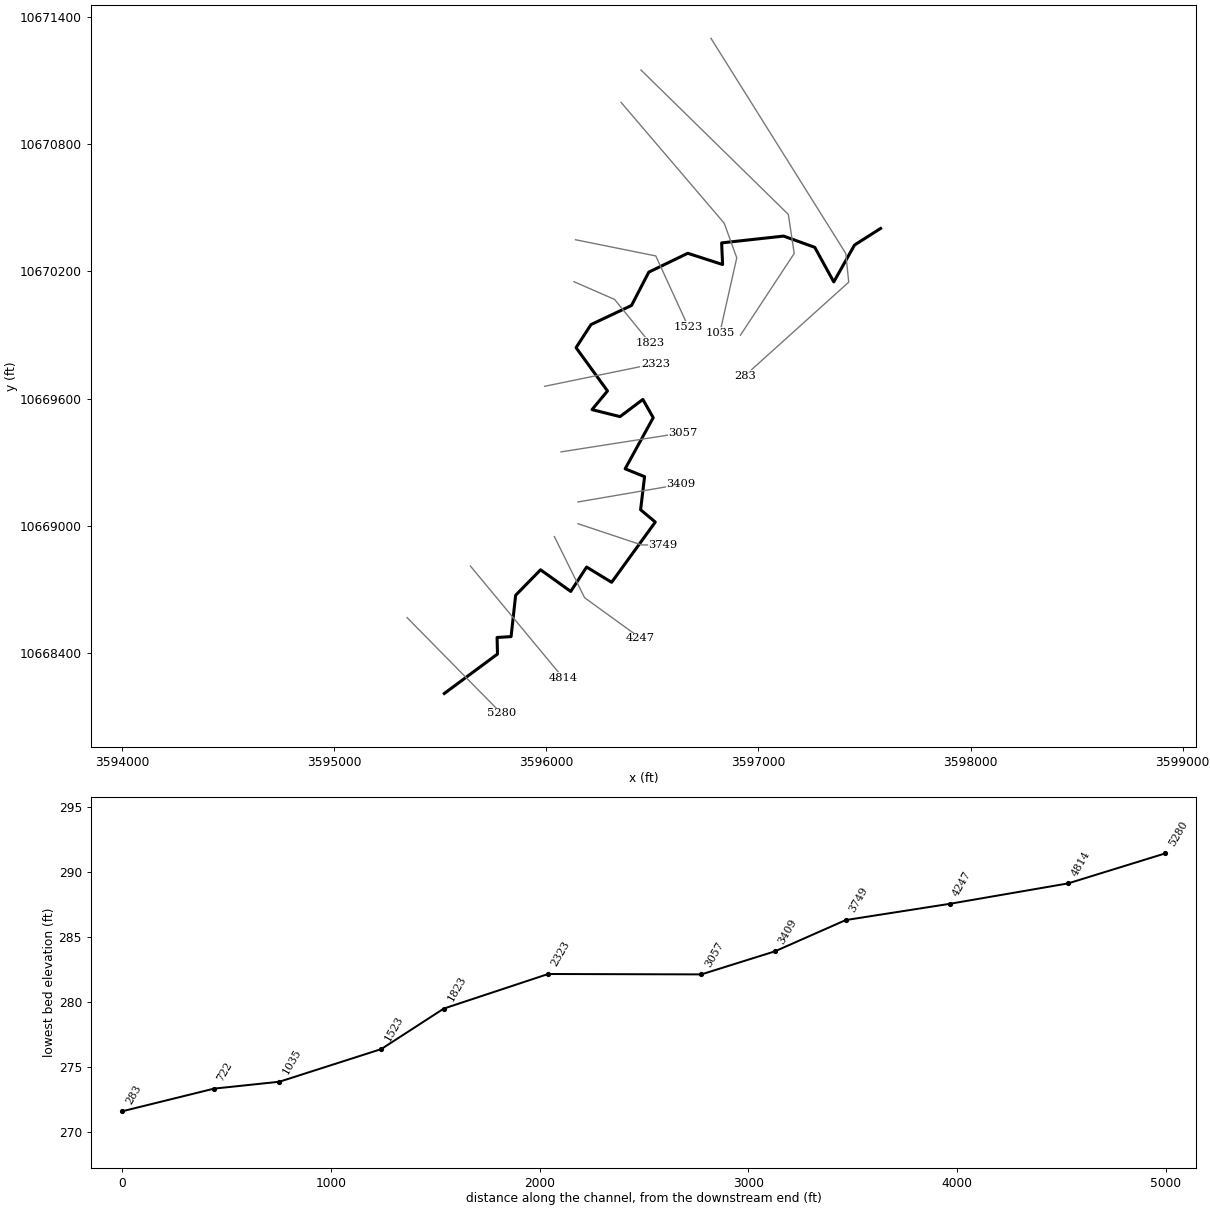
--- UNT227 IN CCTC.prj (project) ---

Proj Title=UNT227 IN CCTC Base Level Engineering
Current Plan=p01
Default Exp/Contr=0.3,0.1
English Units
Geom File=g01
Flow File=f01
Plan File=p01
BEGIN DESCRIPTION:
UNT227 IN CCTC
END DESCRIPTION:

--- UNT227 IN CCTC.p01 (plan) ---

Plan Title=Multiple Run
Short Identifier=Multiple
Geom File=g01
Flow File=f01
Subcritical Flow
K Sum by GR= 0
Std Step Tol= 0.01
Critical Tol= 0.01
Num of Std Step Trials= 20
Max Error Tol= 0.3
Flow Tol Ratio= 0.001
Split Flow NTrial= 30
Split Flow Tol= 0.02
Split Flow Ratio= 0.02
Log Output Level= 0
Friction Slope Method= 1
Unsteady Friction Slope Method= 2
Unsteady Bridges Friction Slope Method= 1
Parabolic Critical Depth
Global Vel Dist=  1 , 1 , 1
Global Log Level= 0
CheckData=True
Encroach Param= -1, 0, 0, 0
BEGIN DESCRIPTION:
Multiple Run
END DESCRIPTION:

--- UNT227 IN CCTC.f01 (steady flow) ---

Flow Title=Multiple
Number of Profiles=7
Profile Names=10-year,25-year,50-year,1pct_min,100-year,1pct_plu,500-year
River Rch & RM= UNT227 IN CCTC,Reach-1,5280
    1234    1679    2042    1812    2450    3314    3517
Boundary for River Rch & Prof#=UNT227 IN CCTC,Reach-1,1
Up Type=0
Dn Type=3
Dn Slope=0.005
Boundary for River Rch & Prof#=UNT227 IN CCTC,Reach-1,2
Up Type=0
Dn Type=3
Dn Slope=0.005
Boundary for River Rch & Prof#=UNT227 IN CCTC,Reach-1,3
Up Type=0
Dn Type=3
Dn Slope=0.005
Boundary for River Rch & Prof#=UNT227 IN CCTC,Reach-1,4
Up Type=0
Dn Type=3
Dn Slope=0.005
Boundary for River Rch & Prof#=UNT227 IN CCTC,Reach-1,5
Up Type=0
Dn Type=3
Dn Slope=0.005
Boundary for River Rch & Prof#=UNT227 IN CCTC,Reach-1,6
Up Type=0
Dn Type=3
Dn Slope=0.005
Boundary for River Rch & Prof#=UNT227 IN CCTC,Reach-1,7
Up Type=0
Dn Type=3
Dn Slope=0.005

--- UNT227 IN CCTC.g01 (geometry) ---

Geom Title=Existing Conditions

River Reach=UNT227 IN CCTC,Reach-1
Reach XY= 30
      3595519.50     10668210.00      3595770.25     10668396.00
      3595768.25     10668474.00      3595834.25     10668478.00
      3595855.75     10668673.00      3595973.25     10668793.00
      3596115.50     10668691.00      3596190.25     10668806.00
      3596308.25     10668734.00      3596514.00     10669018.00
      3596444.75     10669076.00      3596463.50     10669232.00
      3596372.00     10669269.00      3596504.25     10669510.00
      3596455.50     10669596.00      3596347.75     10669515.00
      3596215.75     10669548.00      3596288.75     10669636.00
      3596140.50     10669840.00      3596211.00     10669949.00
      3596402.00     10670039.00      3596483.25     10670196.00
      3596667.00     10670285.00      3596831.25     10670232.00
      3596826.75     10670334.00      3597118.75     10670366.00
      3597265.75     10670313.00      3597355.25     10670150.00
      3597453.25     10670324.00      3597576.00     10670402.00

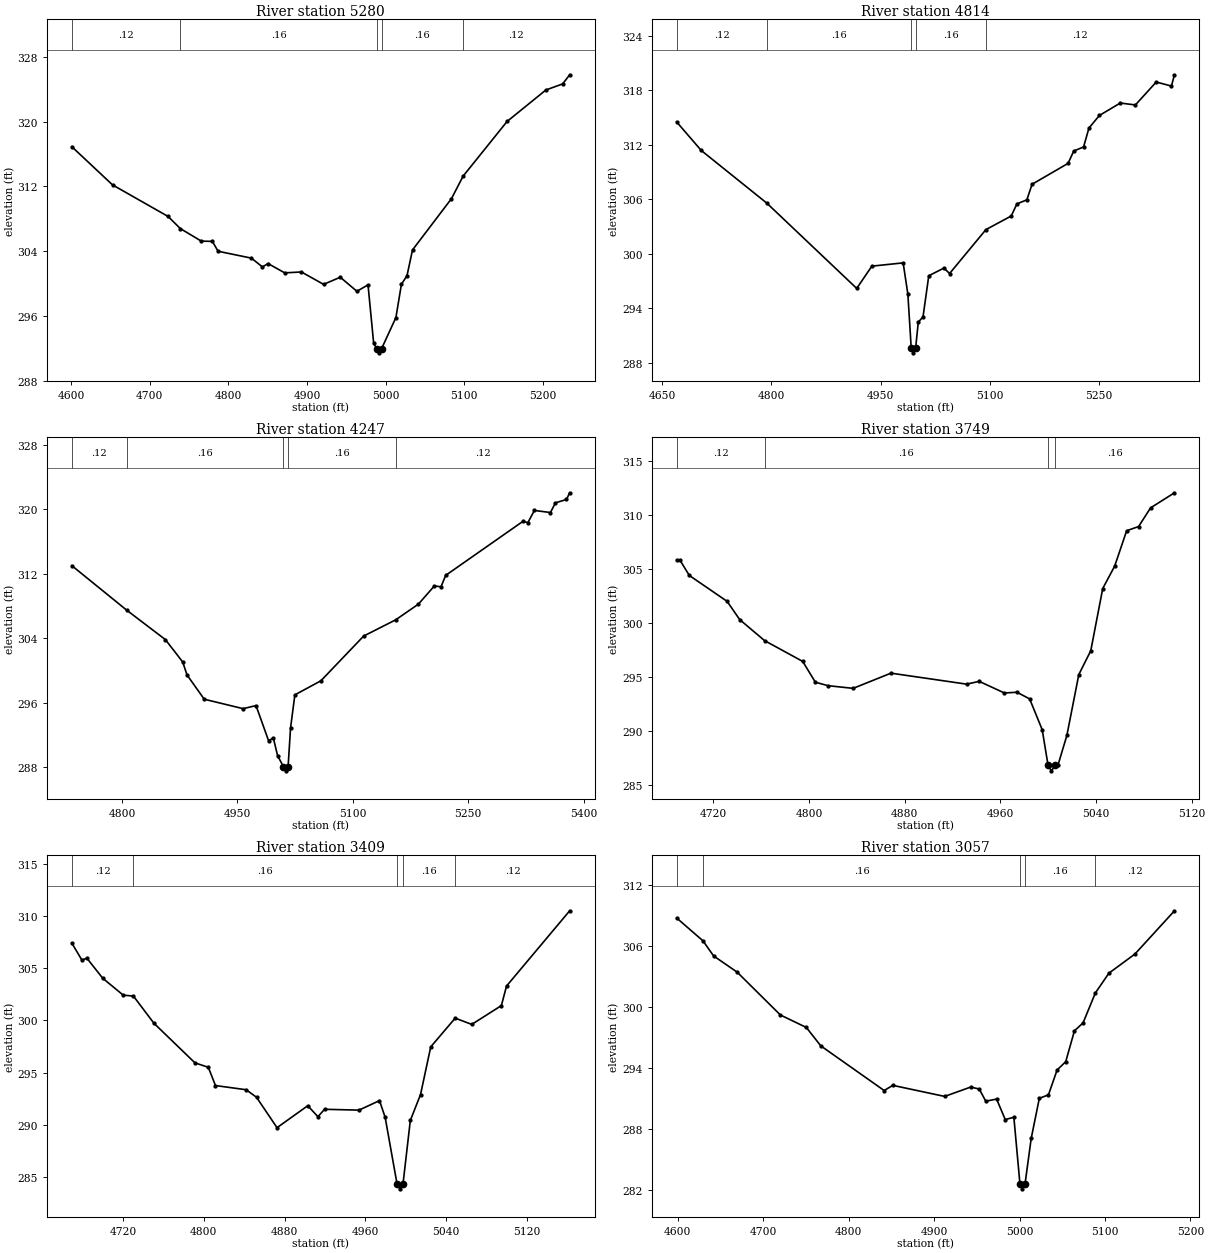
Type RM Length L Ch R = 1,5280,466,466,466
BEGIN DESCRIPTION:
UNT227 IN CCTC 10.0
END DESCRIPTION:
XS GIS Cut Line= 2
      3595343.99     10668567.55      3595788.39     10668116.21
#Sta/Elev= 30
  4600.9  316.89  4652.6  312.18  4723.3  308.28  4738.9  306.78  4765.6  305.23
  4779.7  305.20  4786.9  303.98  4829.3  303.13  4843.4  302.04  4850.5  302.46
  4871.7  301.31  4892.9  301.42  4921.2  299.89  4942.4  300.77  4963.6  299.03
  4977.7  299.83  4984.9  292.60  4988.9  291.93  4991.6  291.43  4994.9  291.93
  5013.2  295.79  5020.2  299.90  5027.3  300.96  5034.3  304.14  5083.9  310.48
  5098.7  313.26  5154.6  320.01  5204.0  323.90  5225.3  324.65  5234.3  325.78
#Mann=5,-1,0
  4600.9    0.12       0  4738.9    0.16       0  4988.9    0.07       0
  4994.9    0.16       0  5098.7    0.12       0
Bank Sta=4988.9,4994.9
Exp/Cntr=0.3,0.1

Type RM Length L Ch R = 1,4814,567,567,567
BEGIN DESCRIPTION:
UNT227 IN CCTC 9.0
END DESCRIPTION:
XS GIS Cut Line= 2
      3595642.56     10668810.65      3596079.08     10668284.06
#Sta/Elev= 30
  4669.9  314.53  4703.7  311.39  4793.7  305.60  4917.3  296.21  4938.1  298.66
  4981.1  299.02  4987.6  295.56  4992.2  289.62  4995.0  289.12  4998.2  289.62
  5001.9  292.50  5008.4  293.08  5016.3  297.60  5037.1  298.45  5044.9  297.85
  5094.8  302.68  5129.6  304.18  5137.4  305.51  5151.1  305.96  5158.2  307.67
  5207.7  309.97  5215.5  311.33  5229.0  311.78  5236.4  313.86  5250.7  315.24
  5279.4  316.61  5300.2  316.40  5328.8  318.92  5349.7  318.48  5353.9  319.72
#Mann=5,-1,0
  4669.9    0.12       0  4793.7    0.16       0  4992.2    0.07       0
  4998.2    0.16       0  5094.8    0.12       0
Bank Sta=4992.2,4998.2
Exp/Cntr=0.3,0.1

Type RM Length L Ch R = 1,4247,498,498,498
BEGIN DESCRIPTION:
UNT227 IN CCTC 8.0
END DESCRIPTION:
XS GIS Cut Line= 3
      3596038.41     10668949.53      3596180.78     10668661.32
      3596444.67     10668470.35
#Sta/Elev= 30
  4734.8  312.99  4806.0  307.48  4856.4  303.82  4878.9  301.05  4884.5  299.44
  4906.9  296.43  4957.4  295.26  4974.2  295.64  4990.6  291.27  4996.7  291.64
  5002.2  289.45  5009.9  288.05  5012.7  287.55  5015.9  288.05  5019.1  292.87
  5024.7  296.97  5058.6  298.72  5114.1  304.26  5155.7  306.27  5185.3  308.22
  5206.1  310.48  5214.7  310.37  5220.8  311.79  5321.4  318.50  5327.6  318.32
  5336.1  319.84  5357.0  319.58  5363.4  320.78  5377.8  321.20  5382.0  322.03
#Mann=5,-1,0
  4734.8    0.12       0  4806.0    0.16       0  5009.9    0.07       0
  5015.9    0.16       0  5155.7    0.12       0
Bank Sta=5009.9,5015.9
Exp/Cntr=0.3,0.1

Type RM Length L Ch R = 1,3749,340,340,340
BEGIN DESCRIPTION:
UNT227 IN CCTC 7.0
END DESCRIPTION:
XS GIS Cut Line= 3
      3596149.58     10669010.20      3596449.61     10668910.19
      3596549.65     10668910.19
#Sta/Elev= 30
  4689.3  305.85  4692.0  305.85  4699.9  304.42  4731.5  302.02  4742.0  300.33
  4762.8  298.38  4794.7  296.45  4805.3  294.52  4815.8  294.20  4836.9  293.95
  4868.5  295.36  4931.8  294.34  4942.3  294.60  4963.4  293.52  4973.9  293.59
  4984.5  292.97  4995.0  290.11  4999.9  286.80  5002.7  286.30  5005.9  286.80
  5008.1  286.80  5015.6  289.58  5025.6  295.23  5035.6  297.44  5045.6  303.21
  5055.6  305.29  5065.6  308.57  5075.6  308.96  5085.6  310.69  5105.6  312.09
#Mann=4,-1,0
  4689.3    0.12       0  4762.8    0.16       0  4999.9    0.07       0
  5005.9    0.16       0
Bank Sta=4999.9,5005.9
Exp/Cntr=0.3,0.1

Type RM Length L Ch R = 1,3409,352,352,352
BEGIN DESCRIPTION:
UNT227 IN CCTC 6.0
END DESCRIPTION:
XS GIS Cut Line= 2
      3596149.57     10669112.72      3596635.09     10669195.95
#Sta/Elev= 30
  4669.5  307.39  4679.4  305.78  4684.4  305.95  4700.0  304.04  4720.3  302.42
  4730.4  302.33  4750.7  299.73  4791.3  295.94  4804.5  295.52  4811.6  293.77
  4842.0  293.37  4852.2  292.65  4872.5  289.74  4902.9  291.84  4913.0  290.79
  4919.5  291.50  4953.6  291.42  4973.9  292.33  4979.5  290.73  4991.2  284.39
  4994.0  283.89  4997.2  284.39  5004.4  290.43  5014.5  292.91  5024.6  297.47
  5048.8  300.22  5065.2  299.62  5094.5  301.42  5099.6  303.29  5162.1  310.49
#Mann=5,-1,0
  4669.5    0.12       0  4730.4    0.16       0  4991.2    0.07       0
  4997.2    0.16       0  5048.8    0.12       0
Bank Sta=4991.2,4997.2
Exp/Cntr=0.3,0.1

Type RM Length L Ch R = 1,3057,734,734,734
BEGIN DESCRIPTION:
UNT227 IN CCTC 5.0
END DESCRIPTION:
XS GIS Cut Line= 2
      3596069.65     10669348.82      3596645.34     10669438.99
#Sta/Elev= 30
  4598.6  308.79  4629.4  306.54  4641.9  305.05  4669.4  303.46  4720.0  299.24
  4750.4  298.01  4767.3  296.20  4841.5  291.80  4851.6  292.31  4912.3  291.22
  4942.7  292.14  4952.8  291.95  4960.4  290.75  4973.1  290.96  4983.2  288.94
  4993.3  289.17  5000.4  282.62  5003.2  282.12  5006.4  282.62  5013.6  287.09
  5023.1  291.03  5033.8  291.38  5043.9  293.82  5054.0  294.64  5064.2  297.68
  5074.3  298.46  5088.7  301.41  5104.6  303.36  5135.0  305.24  5181.3  309.50
#Mann=5,-1,0
  4598.6    0.12       0  4629.4    0.16       0  5000.4    0.07       0
  5006.4    0.16       0  5088.7    0.12       0
Bank Sta=5000.4,5006.4
Exp/Cntr=0.3,0.1

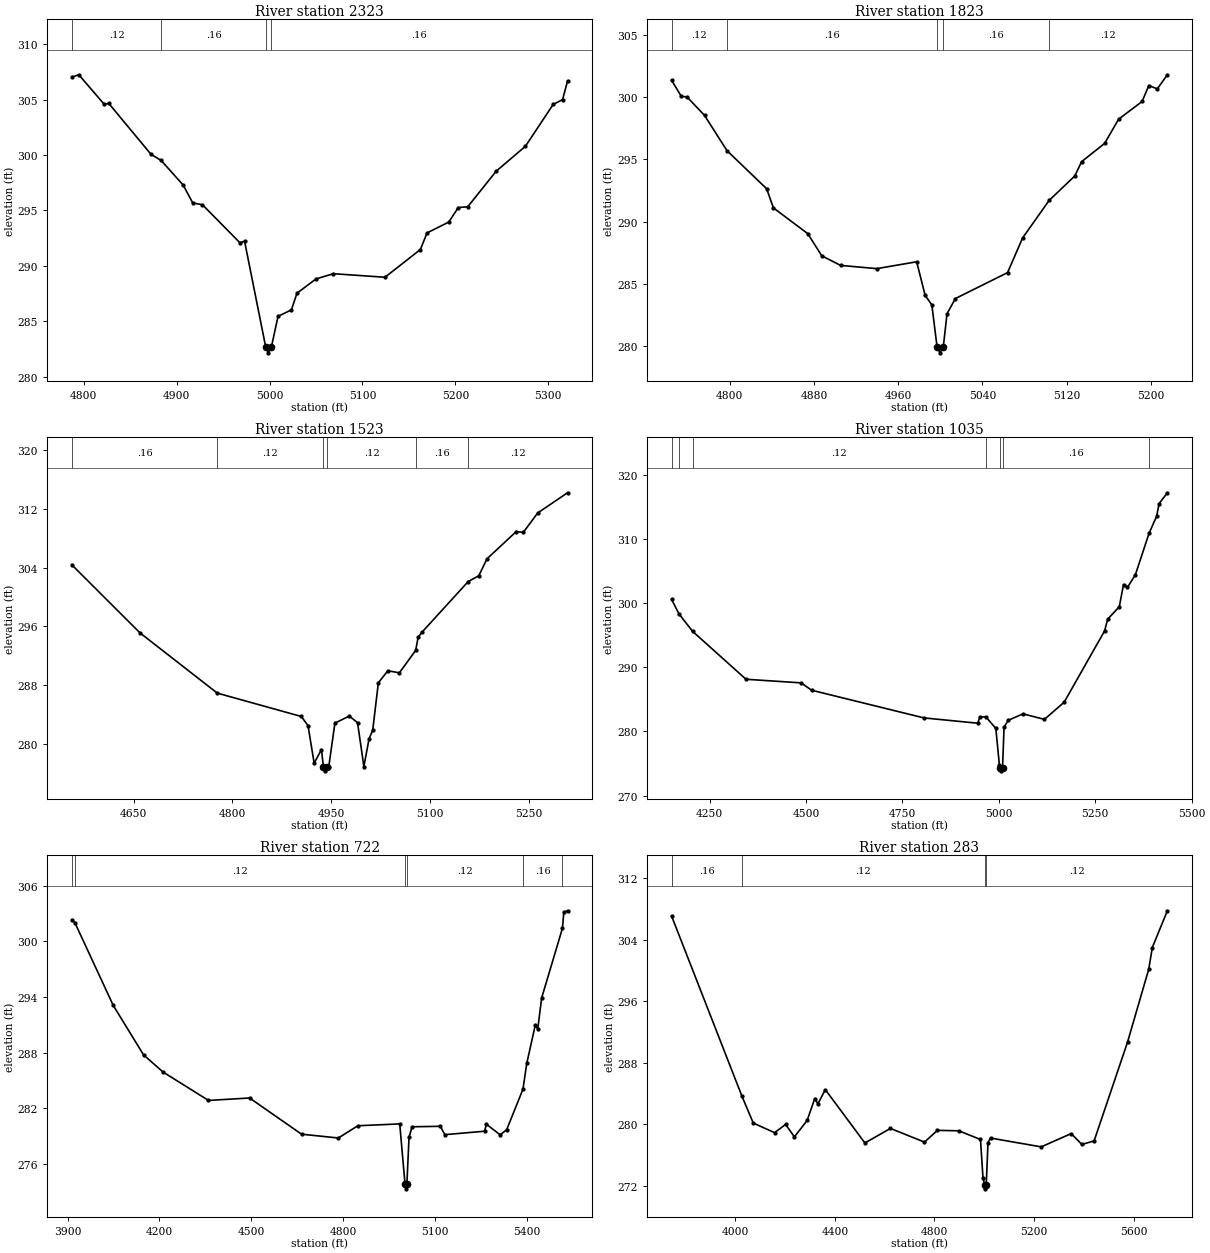
Type RM Length L Ch R = 1,2323,500,500,500
BEGIN DESCRIPTION:
UNT227 IN CCTC 4.0
END DESCRIPTION:
XS GIS Cut Line= 2
      3595992.12     10669657.85      3596514.81     10669765.16
#Sta/Elev= 30
  4787.1  307.02  4794.7  307.24  4821.9  304.59  4827.0  304.65  4872.3  300.07
  4883.3  299.51  4907.0  297.29  4917.3  295.68  4927.8  295.51  4968.0  292.09
  4973.1  292.22  4995.9  282.65  4998.7  282.15  5001.9  282.65  5009.1  285.44
  5023.5  286.03  5029.5  287.53  5050.0  288.82  5068.7  289.29  5124.2  288.97
  5162.3  291.47  5169.5  292.97  5192.9  293.95  5203.1  295.26  5213.3  295.33
  5243.9  298.54  5275.4  300.79  5305.2  304.56  5315.4  305.00  5320.7  306.68
#Mann=4,-1,0
  4787.1    0.12       0  4883.3    0.16       0  4995.9    0.07       0
  5001.9    0.16       0
Bank Sta=4995.9,5001.9
Exp/Cntr=0.3,0.1

Type RM Length L Ch R = 1,1823,300,300,300
BEGIN DESCRIPTION:
UNT227 IN CCTC 3.0
END DESCRIPTION:
XS GIS Cut Line= 3
      3596130.97     10670150.93      3596321.98     10670067.57
      3596487.64     10669863.96
#Sta/Elev= 30
  4744.7  301.34  4753.9  300.05  4759.3  300.01  4776.0  298.52  4797.3  295.70
  4835.0  292.64  4841.4  291.11  4874.1  289.04  4887.3  287.27  4905.2  286.50
  4939.6  286.24  4977.5  286.79  4985.5  284.10  4991.9  283.33  4996.8  279.99
  4999.6  279.49  5002.8  279.99  5006.3  282.62  5014.2  283.84  5063.8  285.92
  5078.1  288.70  5103.3  291.71  5127.7  293.67  5134.1  294.81  5156.0  296.28
  5169.3  298.22  5191.6  299.64  5198.0  300.92  5206.0  300.65  5215.6  301.78
#Mann=5,-1,0
  4744.7    0.12       0  4797.3    0.16       0  4996.8    0.07       0
  5002.8    0.16       0  5103.3    0.12       0
Bank Sta=4996.8,5002.8
Exp/Cntr=0.3,0.1

Type RM Length L Ch R = 1,1523,488,488,488
BEGIN DESCRIPTION:
UNT227 IN CCTC 2.0
END DESCRIPTION:
XS GIS Cut Line= 3
      3596137.99     10670348.82      3596516.43     10670272.44
      3596669.18     10669939.14
#Sta/Elev= 30
  4556.1  304.39  4659.8  295.12  4777.0  286.94  4904.6  283.76  4914.8  282.52
  4924.1  277.41  4935.2  279.26  4938.2  276.87  4941.0  276.37  4944.2  276.87
  4946.2  276.87  4955.6  282.86  4977.6  283.82  4990.0  282.91  4999.6  276.96
  5007.5  280.74  5013.0  281.89  5021.6  288.35  5036.0  289.98  5053.5  289.70
  5078.2  292.74  5082.0  294.54  5087.6  295.20  5158.0  302.11  5174.0  302.89
  5186.6  305.21  5231.0  308.91  5241.6  308.79  5263.6  311.44  5308.8  314.18
#Mann=6,-1,0
  4556.1    0.16       0  4777.0    0.12       0  4938.2    0.07       0
  4944.2    0.12       0  5078.2    0.16       0  5158.0    0.12       0
Bank Sta=4938.2,4944.2
Exp/Cntr=0.3,0.1

Type RM Length L Ch R = 1,1035,313,313,313
BEGIN DESCRIPTION:
Mapping XS 6d3bbf1e
END DESCRIPTION:
XS GIS Cut Line= 4
      3596352.87     10670996.06      3596839.00     10670426.60
      3596898.02     10670263.41      3596818.17     10669909.27
#Sta/Elev= 30
  4151.7  300.56  4170.9  298.31  4206.2  295.59  4344.6  288.13  4487.4  287.57
  4514.8  286.42  4805.8  282.11  4945.4  281.28  4950.7  282.21  4966.0  282.30
  4992.3  280.47  5001.4  274.84  5003.7  274.36  5006.5  273.86  5009.7  274.36
  5013.6  280.64  5024.2  281.73  5062.7  282.74  5118.3  281.88  5169.5  284.56
  5274.3  295.67  5282.3  297.49  5312.4  299.44  5323.3  302.89  5333.6  302.45
  5354.1  304.42  5389.5  310.87  5409.1  313.52  5415.6  315.50  5437.0  317.19
#Mann=7,-1,0
  4151.7    0.12       0  4170.9    0.16       0  4206.2    0.12       0
  4966.0    0.16       0  5003.7    0.07       0  5009.7    0.16       0
  5389.5    0.12       0
Bank Sta=5003.7,5009.7
Exp/Cntr=0.3,0.1

Type RM Length L Ch R = 1,722,439,439,439
BEGIN DESCRIPTION:
Mapping XS f6035ab5
END DESCRIPTION:
XS GIS Cut Line= 4
      3596446.62     10671148.83      3597141.08     10670468.27
      3597168.86     10670284.24      3596915.41     10669898.86
#Sta/Elev= 30
  3913.7  302.34  3923.7  302.03  4049.2  293.10  4148.2  287.77  4211.9  285.92
  4360.4  282.86  4494.7  283.12  4664.4  279.22  4784.7  278.81  4848.3  280.13
  4985.2  280.33  5002.5  273.83  5005.2  273.33  5008.5  273.83  5015.6  278.91
  5025.7  280.02  5117.6  280.07  5132.7  279.17  5262.2  279.54  5268.5  280.29
  5313.4  279.15  5334.5  279.70  5387.7  284.06  5400.2  286.85  5427.9  290.96
  5436.1  290.57  5448.9  293.91  5516.9  301.42  5521.2  303.14  5533.4  303.30
#Mann=6,-1,0
  3913.7    0.16       0  3923.7    0.12       0  5002.5    0.07       0
  5008.5    0.12       0  5387.7    0.16       0  5516.9    0.12       0
Bank Sta=5002.5,5008.5
Exp/Cntr=0.3,0.1

Type RM Length L Ch R = 1,283,0,0,0
BEGIN DESCRIPTION:
UNT227 IN CCTC 1.0
END DESCRIPTION:
XS GIS Cut Line= 4
      3596776.48     10671298.15      3597411.91     10670284.24
      3597425.80     10670148.82      3596936.22     10669707.85
#Sta/Elev= 30
  3744.3  307.08  4026.6  283.67  4072.3  280.15  4158.0  278.90  4202.2  279.97
  4237.6  278.35  4288.8  280.49  4319.4  283.34  4332.0  282.64  4361.8  284.50
  4520.8  277.56  4623.5  279.45  4760.2  277.67  4812.0  279.20  4898.4  279.14
  4985.2  278.01  4995.2  273.01  5002.3  272.09  5005.0  271.59  5008.3  272.09
  5015.3  277.61  5025.4  278.20  5229.2  277.05  5349.6  278.78  5392.2  277.37
  5441.5  277.82  5576.0  290.69  5661.2  300.18  5675.4  302.99  5735.9  307.77
#Mann=4,-1,0
  3744.3    0.16       0  4026.6    0.12       0  5002.3    0.07       0
  5008.3    0.12       0
Bank Sta=5002.3,5008.3
Exp/Cntr=0.3,0.1

Chan Stop Cuts=-1