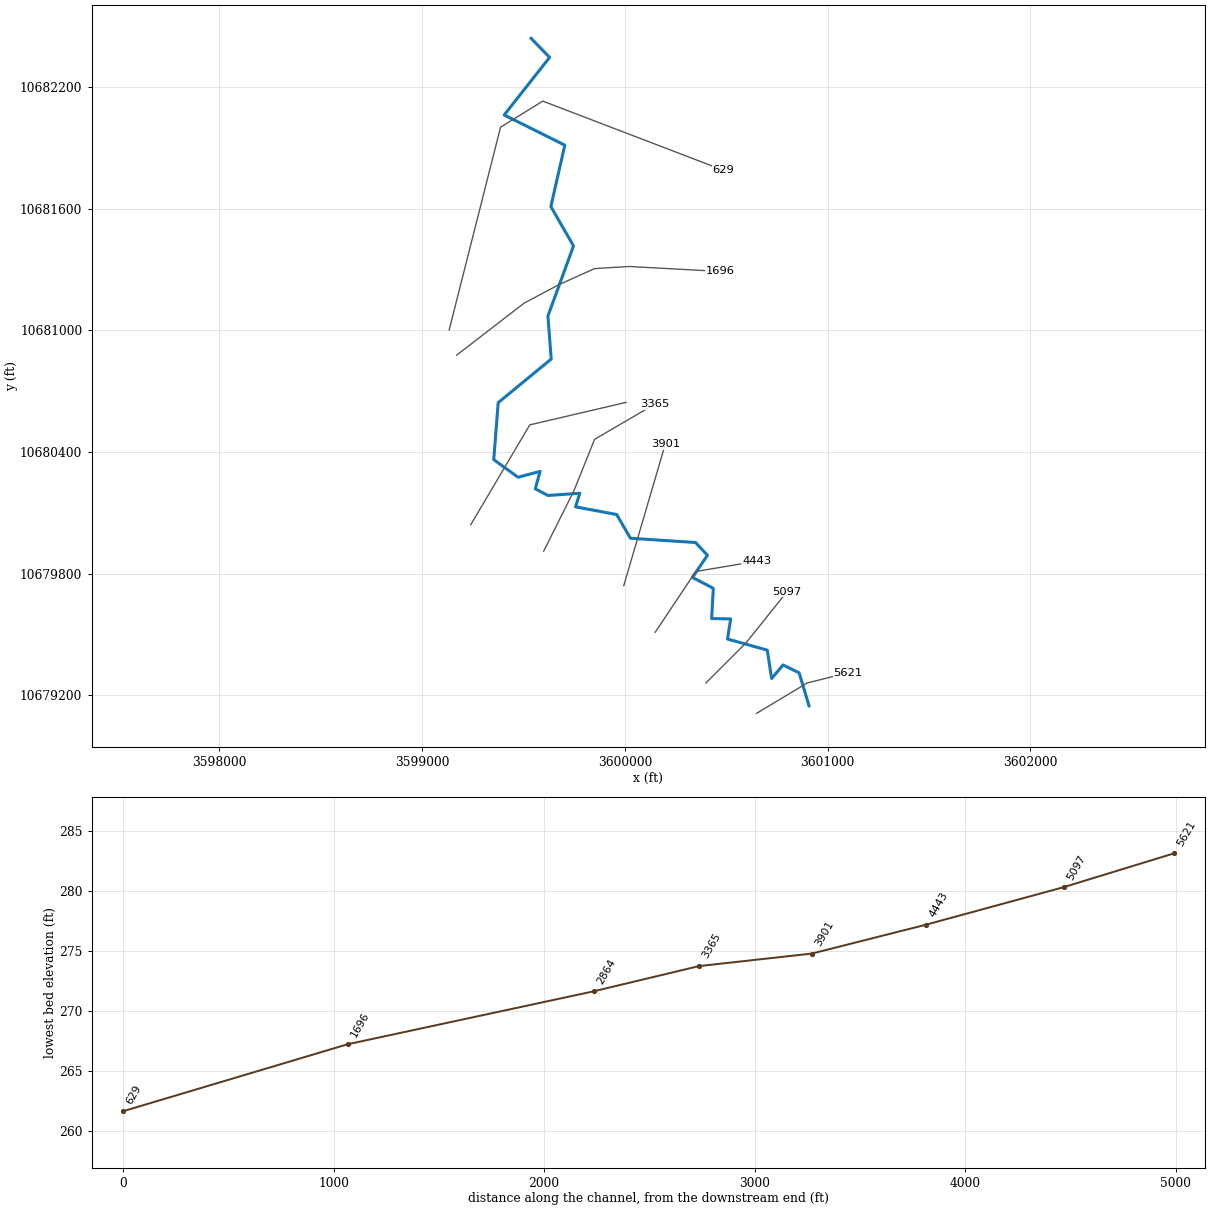
--- UNT230 IN CCTC.prj (project) ---

Proj Title=UNT230 IN CCTC Base Level Engineering
Current Plan=p01
Default Exp/Contr=0.3,0.1
English Units
Geom File=g01
Flow File=f01
Plan File=p01
BEGIN DESCRIPTION:
UNT230 IN CCTC
END DESCRIPTION:

--- UNT230 IN CCTC.p01 (plan) ---

Plan Title=Multiple Run
Short Identifier=Multiple
Geom File=g01
Flow File=f01
Subcritical Flow
K Sum by GR= 0
Std Step Tol= 0.01
Critical Tol= 0.01
Num of Std Step Trials= 20
Max Error Tol= 0.3
Flow Tol Ratio= 0.001
Split Flow NTrial= 30
Split Flow Tol= 0.02
Split Flow Ratio= 0.02
Log Output Level= 0
Friction Slope Method= 1
Unsteady Friction Slope Method= 2
Unsteady Bridges Friction Slope Method= 1
Parabolic Critical Depth
Global Vel Dist=  1 , 1 , 1
Global Log Level= 0
CheckData=True
Encroach Param= -1, 0, 0, 0
BEGIN DESCRIPTION:
Multiple Run
END DESCRIPTION:

--- UNT230 IN CCTC.f01 (steady flow) ---

Flow Title=Multiple
Number of Profiles=7
Profile Names=10-year,25-year,50-year,1pct_min,100-year,1pct_plu,500-year
River Rch & RM= UNT230 IN CCTC,Reach-1,5621
    1159    1570    1904    1685    2279    3082    3251
Boundary for River Rch & Prof#=UNT230 IN CCTC,Reach-1,1
Up Type=0
Dn Type=3
Dn Slope=0.005
Boundary for River Rch & Prof#=UNT230 IN CCTC,Reach-1,2
Up Type=0
Dn Type=3
Dn Slope=0.005
Boundary for River Rch & Prof#=UNT230 IN CCTC,Reach-1,3
Up Type=0
Dn Type=3
Dn Slope=0.005
Boundary for River Rch & Prof#=UNT230 IN CCTC,Reach-1,4
Up Type=0
Dn Type=3
Dn Slope=0.005
Boundary for River Rch & Prof#=UNT230 IN CCTC,Reach-1,5
Up Type=0
Dn Type=3
Dn Slope=0.005
Boundary for River Rch & Prof#=UNT230 IN CCTC,Reach-1,6
Up Type=0
Dn Type=3
Dn Slope=0.005
Boundary for River Rch & Prof#=UNT230 IN CCTC,Reach-1,7
Up Type=0
Dn Type=3
Dn Slope=0.005

--- UNT230 IN CCTC.g01 (geometry) ---

Geom Title=Existing Conditions

River Reach=UNT230 IN CCTC,Reach-1
Reach XY= 30
      3600908.50     10679147.00      3600859.75     10679310.00
      3600780.25     10679349.00      3600724.00     10679282.00
      3600702.50     10679422.00      3600506.25     10679477.00
      3600522.00     10679576.00      3600428.00     10679578.00
      3600436.25     10679727.00      3600333.25     10679781.00
      3600407.50     10679890.00      3600348.75     10679953.00
      3600027.50     10679974.00      3599959.75     10680091.00
      3599756.75     10680129.00      3599777.75     10680196.00
      3599620.50     10680185.00      3599558.25     10680218.00
      3599582.00     10680304.00      3599473.00     10680275.00
      3599353.25     10680362.00      3599375.25     10680643.00
      3599636.75     10680858.00      3599620.50     10681070.00
      3599746.75     10681416.00      3599635.00     10681610.00
      3599703.75     10681913.00      3599404.75     10682062.00
      3599628.75     10682346.00      3599537.50     10682440.00

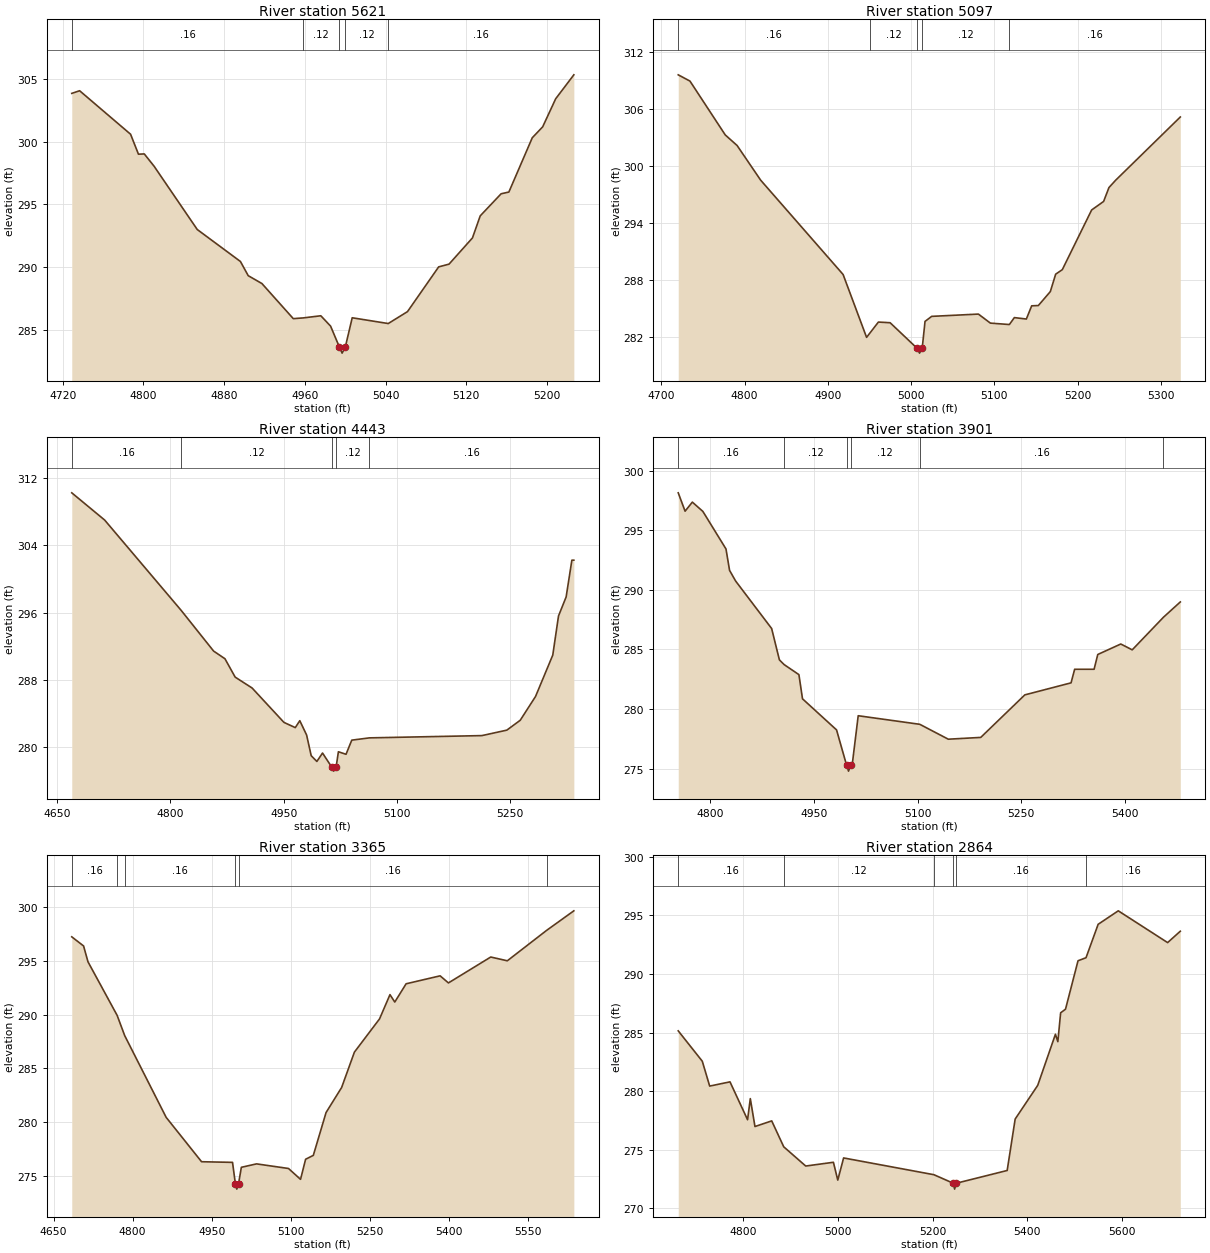
Type RM Length L Ch R = 1,5621,524,524,524
BEGIN DESCRIPTION:
UNT230 IN CCTC 7.0
END DESCRIPTION:
XS GIS Cut Line= 3
      3600649.60     10679110.18      3600899.61     10679260.19
      3601099.59     10679310.18
#Sta/Elev= 30
  4729.0  303.84  4736.8  304.05  4787.3  300.58  4795.1  298.99  4800.9  299.01
  4810.6  298.03  4853.4  292.98  4896.2  290.43  4903.9  289.30  4917.5  288.67
  4948.6  285.87  4958.5  285.93  4975.9  286.10  4985.6  285.27  4994.2  283.62
  4997.0  283.12  5000.2  283.62  5007.0  285.94  5042.7  285.48  5061.8  286.43
  5092.7  290.00  5103.0  290.22  5126.2  292.31  5133.9  294.07  5154.6  295.83
  5162.3  295.97  5185.5  300.30  5195.8  301.17  5208.7  303.41  5226.7  305.32
#Mann=5,-1,0
  4729.0    0.16       0  4958.5    0.12       0  4994.2    0.07       0
  5000.2    0.12       0  5042.7    0.16       0
Bank Sta=4994.2,5000.2
Exp/Cntr=0.3,0.1

Type RM Length L Ch R = 1,5097,654,654,654
BEGIN DESCRIPTION:
UNT230 IN CCTC 6.0
END DESCRIPTION:
XS GIS Cut Line= 3
      3600399.63     10679260.21      3600599.61     10679460.19
      3600799.63     10679710.21
#Sta/Elev= 30
  4720.4  309.61  4734.5  308.95  4776.9  303.28  4791.1  302.17  4819.4  298.52
  4918.4  288.59  4946.6  281.97  4950.4  282.40  4960.8  283.58  4974.9  283.51
  5007.4  280.81  5010.2  280.31  5013.4  280.81  5016.8  283.65  5024.8  284.18
  5080.9  284.42  5095.3  283.47  5118.1  283.32  5124.1  284.05  5138.5  283.90
  5144.9  285.29  5152.9  285.32  5167.3  286.79  5173.7  288.62  5181.7  289.10
  5216.9  295.38  5231.3  296.28  5237.7  297.74  5245.7  298.51  5323.4  305.17
#Mann=5,-1,0
  4720.4    0.16       0  4950.4    0.12       0  5007.4    0.07       0
  5013.4    0.12       0  5118.1    0.16       0
Bank Sta=5007.4,5013.4
Exp/Cntr=0.3,0.1

Type RM Length L Ch R = 1,4443,542,542,542
BEGIN DESCRIPTION:
UNT230 IN CCTC 5.0
END DESCRIPTION:
XS GIS Cut Line= 3
      3600149.63     10679510.22      3600349.61     10679810.19
      3600649.65     10679860.20
#Sta/Elev= 30
  4669.4  310.25  4712.9  307.02  4814.2  296.29  4857.2  291.45  4872.2  290.54
  4885.7  288.36  4908.2  287.06  4950.3  282.98  4965.3  282.36  4971.3  283.18
  4980.3  281.48  4986.4  279.02  4993.9  278.34  5001.4  279.34  5013.4  277.69
  5016.2  277.19  5019.4  277.69  5022.4  279.49  5032.5  279.19  5040.1  280.87
  5063.4  281.14  5212.4  281.41  5245.4  282.06  5263.1  283.23  5283.4  286.06
  5306.2  290.97  5313.8  295.62  5323.9  297.88  5331.5  302.25  5334.1  302.25
#Mann=5,-1,0
  4669.4    0.16       0  4814.2    0.12       0  5013.4    0.07       0
  5019.4    0.12       0  5063.4    0.16       0
Bank Sta=5013.4,5019.4
Exp/Cntr=0.3,0.1

Type RM Length L Ch R = 1,3901,536,536,536
BEGIN DESCRIPTION:
UNT230 IN CCTC 4.0
END DESCRIPTION:
XS GIS Cut Line= 2
      3599994.68     10679740.66      3600199.05     10680436.88
#Sta/Elev= 30
  4754.1  298.15  4764.0  296.61  4774.5  297.37  4789.7  296.59  4823.1  293.44
  4828.3  291.64  4837.0  290.75  4889.1  286.76  4900.3  284.13  4907.2  283.73
  4928.5  282.89  4933.7  280.86  4982.9  278.25  4997.4  275.29  5000.2  274.79
  5003.4  275.29  5005.7  275.41  5014.2  279.44  5103.2  278.72  5144.4  277.47
  5191.3  277.62  5255.0  281.19  5321.8  282.20  5327.0  283.34  5355.1  283.34
  5360.4  284.58  5393.7  285.46  5410.2  284.97  5455.4  287.71  5479.7  288.99
#Mann=6,-1,0
  4754.1    0.16       0  4907.2    0.12       0  4997.4    0.07       0
  5003.4    0.12       0  5103.2    0.16       0  5455.4    0.12       0
Bank Sta=4997.4,5003.4
Exp/Cntr=0.3,0.1

Type RM Length L Ch R = 1,3365,501,501,501
BEGIN DESCRIPTION:
UNT230 IN CCTC 3.0
END DESCRIPTION:
XS GIS Cut Line= 4
      3599599.61     10679910.19      3599749.61     10680210.19
      3599850.73     10680462.06      3600148.51     10680635.85
#Sta/Elev= 30
  4684.6  297.23  4707.0  296.38  4715.3  294.91  4770.6  289.92  4784.9  288.04
  4863.5  280.43  4930.6  276.30  4989.3  276.24  4994.7  274.25  4997.4  273.75
  5000.7  274.25  5006.0  275.78  5034.8  276.10  5095.4  275.67  5118.2  274.66
  5127.8  276.53  5142.4  276.89  5166.6  280.88  5196.1  283.21  5220.3  286.50
  5267.9  289.59  5287.7  291.85  5296.8  291.16  5318.3  292.86  5382.8  293.60
  5398.5  292.94  5478.7  295.35  5510.1  295.00  5584.6  297.83  5636.2  299.65
#Mann=6,-1,0
  4684.6    0.16       0  4770.6    0.12       0  4784.9    0.16       0
  4994.7    0.07       0  5000.7    0.16       0  5584.6    0.12       0
Bank Sta=4994.7,5000.7
Exp/Cntr=0.3,0.1

Type RM Length L Ch R = 1,2864,1168,1168,1168
BEGIN DESCRIPTION:
Mapping XS d00fdccc
END DESCRIPTION:
XS GIS Cut Line= 3
      3599239.45     10680040.25      3599531.13     10680533.33
      3600005.67     10680644.17
#Sta/Elev= 30
  4662.9  285.15  4713.7  282.56  4729.3  280.44  4772.2  280.80  4809.3  277.57
  4815.1  279.37  4824.9  276.99  4860.3  277.47  4885.7  275.26  4932.1  273.62
  4990.6  273.94  4999.8  272.42  5012.1  274.31  5202.8  272.88  5243.8  272.15
  5246.5  271.65  5249.8  272.15  5357.5  273.24  5374.4  277.63  5422.0  280.50
  5459.4  284.86  5464.5  284.23  5470.4  286.69  5480.7  287.00  5507.1  291.13
  5524.0  291.39  5549.6  294.24  5592.1  295.39  5696.3  292.68  5723.1  293.65
#Mann=6,-1,0
  4662.9    0.16       0  4885.7    0.12       0  5202.8    0.16       0
  5243.8    0.07       0  5249.8    0.16       0  5524.0    0.16       0
Bank Sta=5243.8,5249.8
Exp/Cntr=0.3,0.1

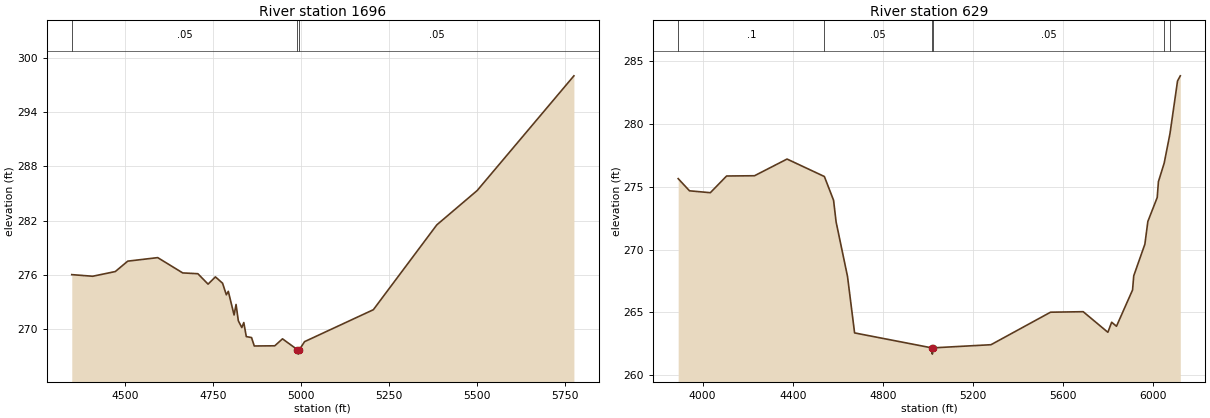
Type RM Length L Ch R = 1,1696,1067,1067,1067
BEGIN DESCRIPTION:
UNT230 IN CCTC 2.0
END DESCRIPTION:
XS GIS Cut Line= 6
      3599169.99     10680877.06      3599503.35     10681134.03
      3599673.49     10681224.30      3599850.58     10681304.16
      3600020.71     10681314.58      3600468.63     10681290.28
#Sta/Elev= 30
  4348.2  276.04  4407.6  275.86  4471.9  276.38  4507.2  277.53  4592.4  277.92
  4663.4  276.23  4706.5  276.14  4735.5  274.99  4756.4  275.79  4776.7  275.09
  4787.4  273.81  4793.0  274.19  4809.4  271.58  4815.0  272.74  4821.5  270.93
  4831.4  270.19  4837.0  270.74  4844.1  269.19  4859.0  269.08  4866.8  268.15
  4925.0  268.17  4947.0  268.94  4989.0  267.75  4991.8  267.25  4995.0  267.75
  5009.7  268.63  5205.1  272.16  5385.4  281.54  5500.2  285.34  5775.0  298.02
#Mann=3,-1,0
  4348.2    0.05       0  4989.0    0.03       0  4995.0    0.05       0
Bank Sta=4989,4995
Exp/Cntr=0.3,0.1

Type RM Length L Ch R = 1,629,0,0,0
BEGIN DESCRIPTION:
UNT230 IN CCTC 1.0
END DESCRIPTION:
XS GIS Cut Line= 4
      3599133.42     10681001.86      3599386.88     10682001.81
      3599595.21     10682130.29      3600484.07     10681790.02
#Sta/Elev= 30
  3891.6  275.66  3941.9  274.69  4034.3  274.54  4106.5  275.87  4230.3  275.89
  4374.7  277.22  4540.3  275.83  4581.1  273.94  4592.4  272.21  4643.0  267.87
  4674.4  263.37  5016.7  262.18  5019.4  261.68  5022.7  262.18  5279.7  262.43
  5543.9  265.02  5688.8  265.06  5798.3  263.42  5815.1  264.22  5836.5  263.90
  5907.8  266.79  5913.1  267.92  5962.5  270.44  5975.7  272.25  6017.3  274.16
  6022.6  275.42  6048.2  276.90  6073.8  279.24  6107.4  283.44  6119.7  283.85
#Mann=6,-1,0
  3891.6     0.1       0  4540.3    0.05       0  5016.7   0.035       0
  5022.7    0.05       0  6048.2    0.16       0  6073.8    0.05       0
Bank Sta=5016.7,5022.7
Exp/Cntr=0.3,0.1

Chan Stop Cuts=-1