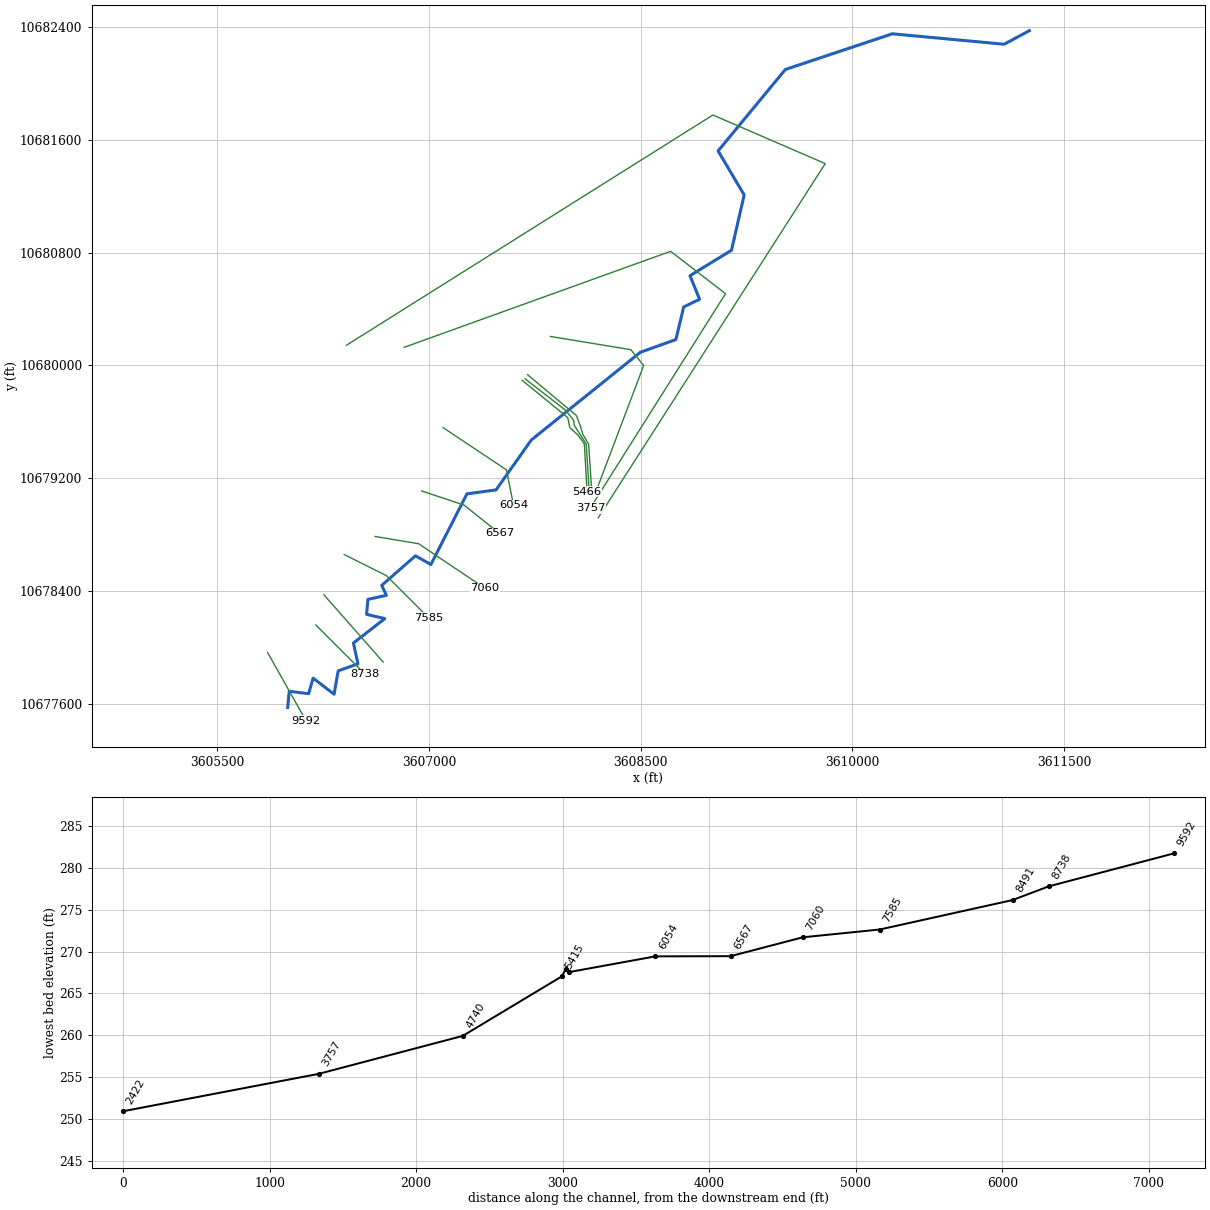
--- UNT231 IN CCTC.prj (project) ---

Proj Title=UNT231 IN CCTC Base Level Engineering
Current Plan=p01
Default Exp/Contr=0.3,0.1
English Units
Geom File=g01
Flow File=f01
Plan File=p01
BEGIN DESCRIPTION:
UNT231 IN CCTC
END DESCRIPTION:

--- UNT231 IN CCTC.p01 (plan) ---

Plan Title=Multiple Run
Short Identifier=Multiple
Geom File=g01
Flow File=f01
Subcritical Flow
K Sum by GR= 0
Std Step Tol= 0.01
Critical Tol= 0.01
Num of Std Step Trials= 20
Max Error Tol= 0.3
Flow Tol Ratio= 0.001
Split Flow NTrial= 30
Split Flow Tol= 0.02
Split Flow Ratio= 0.02
Log Output Level= 0
Friction Slope Method= 1
Unsteady Friction Slope Method= 2
Unsteady Bridges Friction Slope Method= 1
Parabolic Critical Depth
Global Vel Dist=  1 , 1 , 1
Global Log Level= 0
CheckData=True
Encroach Param= -1, 0, 0, 0
BEGIN DESCRIPTION:
Multiple Run
END DESCRIPTION:

--- UNT231 IN CCTC.f01 (steady flow) ---

Flow Title=Multiple
Number of Profiles=7
Profile Names=10-year,25-year,50-year,1pct_min,100-year,1pct_plu,500-year
River Rch & RM= UNT231 IN CCTC,Reach-1,9592
    1304    1772    2154    1909    2582    3491    3696
Boundary for River Rch & Prof#=UNT231 IN CCTC,Reach-1,1
Up Type=0
Dn Type=3
Dn Slope=0.005
Boundary for River Rch & Prof#=UNT231 IN CCTC,Reach-1,2
Up Type=0
Dn Type=3
Dn Slope=0.005
Boundary for River Rch & Prof#=UNT231 IN CCTC,Reach-1,3
Up Type=0
Dn Type=3
Dn Slope=0.005
Boundary for River Rch & Prof#=UNT231 IN CCTC,Reach-1,4
Up Type=0
Dn Type=3
Dn Slope=0.005
Boundary for River Rch & Prof#=UNT231 IN CCTC,Reach-1,5
Up Type=0
Dn Type=3
Dn Slope=0.005
Boundary for River Rch & Prof#=UNT231 IN CCTC,Reach-1,6
Up Type=0
Dn Type=3
Dn Slope=0.005
Boundary for River Rch & Prof#=UNT231 IN CCTC,Reach-1,7
Up Type=0
Dn Type=3
Dn Slope=0.005

--- UNT231 IN CCTC.g01 (geometry) ---

Geom Title=Existing Conditions

River Reach=UNT231 IN CCTC,Reach-1
Reach XY= 30
      3605999.64     10677576.13      3606010.00     10677691.00
      3606147.75     10677674.00      3606180.00     10677784.00
      3606328.25     10677670.00      3606357.50     10677836.00
      3606497.50     10677885.00      3606465.25     10678033.00
      3606688.00     10678206.00      3606558.75     10678236.00
      3606567.75     10678342.00      3606699.00     10678371.00
      3606665.75     10678441.00      3606905.00     10678651.00
      3607014.25     10678589.00      3607269.75     10679090.00
      3607476.00     10679118.00      3607725.25     10679471.00
      3608498.34     10680093.11      3608750.42     10680183.39
      3608805.69     10680414.62      3608918.54     10680468.88
      3608850.27     10680635.89      3609144.32     10680816.01
      3609234.25     10681208.00      3609049.50     10681520.00
      3609526.00     10682097.00      3610284.00     10682350.00
      3611076.25     10682276.00      3611255.50     10682372.00

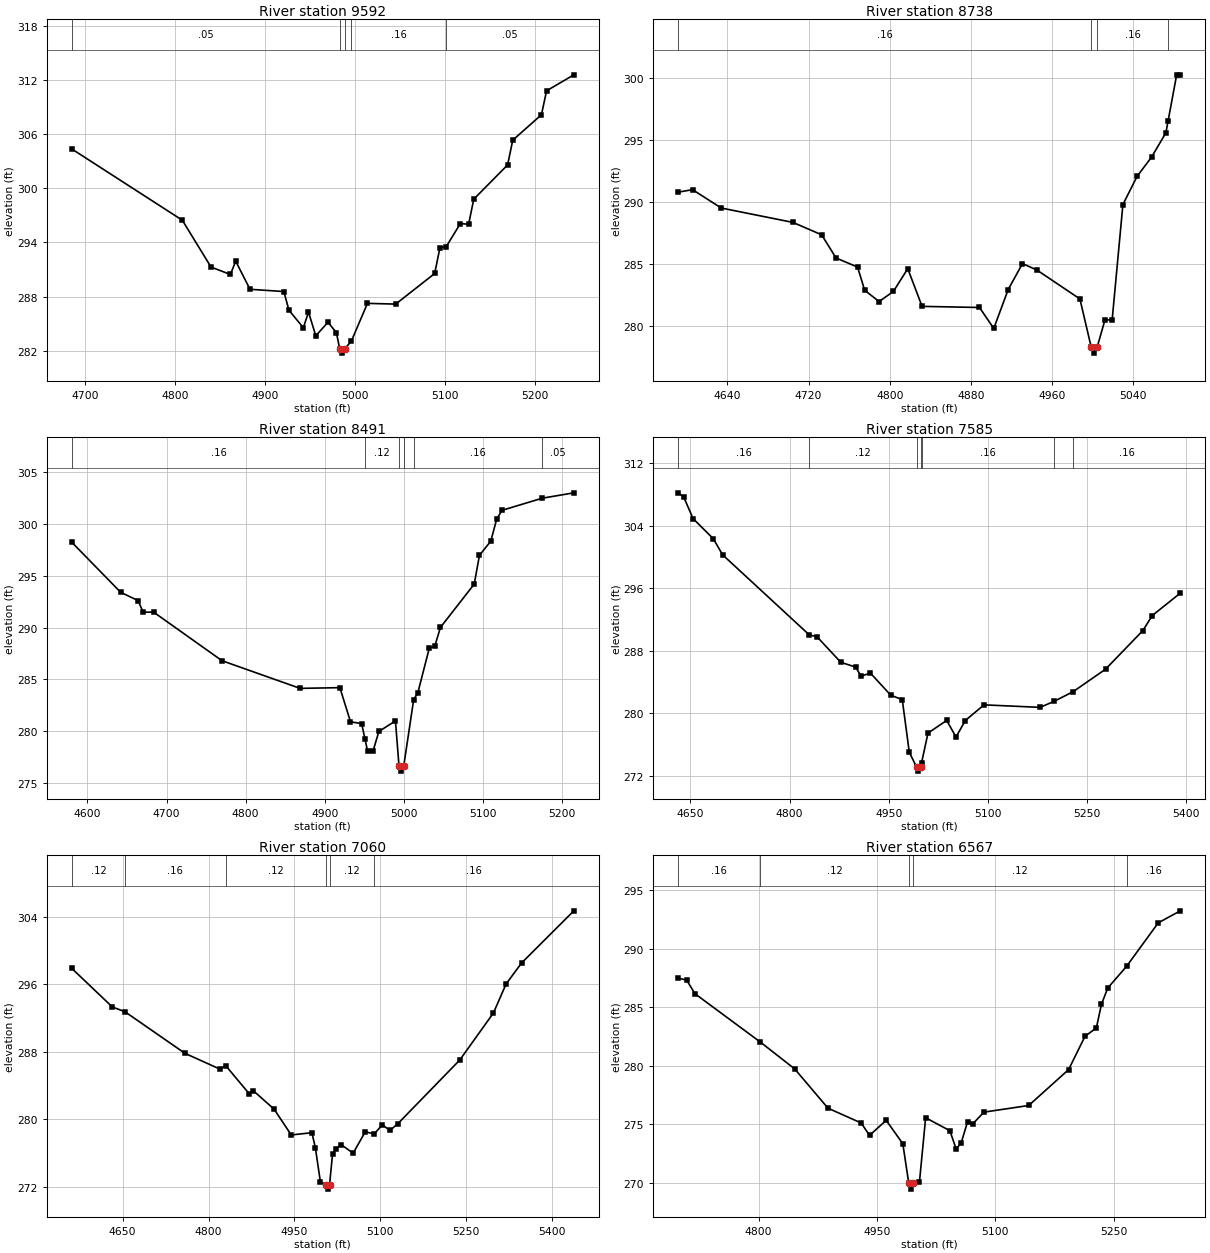
Type RM Length L Ch R = 1,9592,854,854,854
BEGIN DESCRIPTION:
UNT231 IN CCTC 10.0
END DESCRIPTION:
XS GIS Cut Line= 2
      3605856.81     10677966.47      3606130.28     10677480.30
#Sta/Elev= 30
  4685.0  304.34  4807.8  296.45  4839.7  291.26  4861.3  290.44  4867.1  291.92
  4883.0  288.80  4920.6  288.55  4926.3  286.48  4942.3  284.54  4948.0  286.28
  4956.1  283.65  4969.7  285.15  4979.0  284.00  4982.6  282.23  4985.4  281.73
  4988.6  282.23  4995.7  283.08  5013.5  287.24  5044.9  287.16  5088.2  290.55
  5094.0  293.40  5101.0  293.52  5116.7  296.08  5125.9  296.00  5131.6  298.78
  5169.2  302.57  5174.9  305.31  5206.8  308.13  5212.5  310.78  5242.8  312.55
#Mann=5,-1,0
  4685.0    0.05       0  4982.6    0.07       0  4988.6    0.05       0
  4995.7    0.16       0  5101.0    0.05       0
Bank Sta=4982.6,4988.6
Exp/Cntr=0.3,0.1

Type RM Length L Ch R = 1,8738,247,247,247
BEGIN DESCRIPTION:
UNT231 IN CCTC 9.0
END DESCRIPTION:
XS GIS Cut Line= 3
      3606199.61     10678160.19      3606499.61     10677860.19
      3606549.63     10677810.17
#Sta/Elev= 30
  4591.5  290.77  4605.6  290.97  4633.9  289.49  4704.6  288.33  4732.9  287.33
  4747.1  285.46  4768.3  284.73  4775.3  282.86  4789.5  281.95  4803.6  282.76
  4817.8  284.60  4831.9  281.56  4888.5  281.47  4902.6  279.78  4916.8  282.92
  4930.9  285.01  4945.1  284.49  4987.5  282.16  4998.6  278.29  5001.4  277.79
  5004.6  278.29  5012.2  280.47  5019.3  280.47  5029.9  289.77  5044.0  292.06
  5058.2  293.60  5072.3  295.56  5074.4  296.49  5082.9  300.23  5086.5  300.23
#Mann=4,-1,0
  4591.5    0.16       0  4998.6    0.07       0  5004.6    0.16       0
  5074.4    0.05       0
Bank Sta=4998.6,5004.6
Exp/Cntr=0.3,0.1

Type RM Length L Ch R = 1,8491,906,906,906
BEGIN DESCRIPTION:
UNT231 IN CCTC 8.0
END DESCRIPTION:
XS GIS Cut Line= 2
      3606256.15     10678374.41      3606675.87     10677898.44
#Sta/Elev= 30
  4580.2  298.25  4642.1  293.41  4663.9  292.62  4670.5  291.50  4683.7  291.50
  4770.1  286.81  4868.8  284.14  4919.1  284.21  4932.5  280.91  4946.6  280.74
  4950.9  279.22  4954.2  278.05  4960.8  278.05  4968.4  279.98  4989.3  281.00
  4993.8  276.65  4996.6  276.15  4999.8  276.65  5012.3  283.03  5017.7  283.74
  5032.0  288.00  5039.1  288.23  5046.2  290.03  5088.9  294.21  5095.5  296.99
  5109.8  298.35  5117.3  300.49  5124.0  301.33  5174.8  302.50  5214.8  303.02
#Mann=6,-1,0
  4580.2    0.16       0  4950.9    0.12       0  4993.8    0.07       0
  4999.8    0.12       0  5012.3    0.16       0  5174.8    0.05       0
Bank Sta=4993.8,4999.8
Exp/Cntr=0.3,0.1

Type RM Length L Ch R = 1,7585,525,525,525
BEGIN DESCRIPTION:
UNT231 IN CCTC 7.0
END DESCRIPTION:
XS GIS Cut Line= 3
      3606399.57     10678660.21      3606699.61     10678510.19
      3606999.60     10678210.20
#Sta/Elev= 30
  4631.6  308.20  4640.0  307.65  4654.0  304.91  4684.7  302.33  4698.7  300.28
  4830.2  290.02  4841.3  289.83  4877.6  286.54  4900.0  285.93  4908.4  284.76
  4922.3  285.17  4953.1  282.34  4970.6  281.76  4981.2  275.05  4992.3  273.13
  4995.1  272.63  4998.3  273.13  4999.8  273.71  5009.5  277.49  5037.8  279.11
  5051.9  276.99  5066.0  279.10  5094.3  281.10  5179.2  280.78  5200.6  281.56
  5229.2  282.79  5278.2  285.66  5334.7  290.60  5348.9  292.52  5391.3  295.38
#Mann=7,-1,0
  4631.6    0.16       0  4830.2    0.12       0  4992.3    0.07       0
  4998.3    0.12       0  4999.8    0.16       0  5200.6    0.12       0
  5229.2    0.16       0
Bank Sta=4992.3,4998.3
Exp/Cntr=0.3,0.1

Type RM Length L Ch R = 1,7060,493,493,493
BEGIN DESCRIPTION:
UNT231 IN CCTC 6.0
END DESCRIPTION:
XS GIS Cut Line= 3
      3606619.85     10678787.76      3606927.14     10678736.54
      3607396.15     10678421.56
#Sta/Elev= 30
  4561.2  297.87  4631.9  293.30  4654.2  292.72  4759.0  287.79  4819.8  285.93
  4829.8  286.35  4871.4  282.97  4878.4  283.35  4914.4  281.18  4944.4  278.12
  4980.4  278.39  4986.5  276.59  4995.4  272.49  5005.2  272.20  5008.0  271.70
  5011.2  272.20  5016.4  275.82  5022.5  276.50  5031.4  276.98  5052.4  275.96
  5073.5  278.49  5089.3  278.25  5103.4  279.33  5116.6  278.65  5130.5  279.46
  5238.5  287.00  5297.3  292.58  5319.5  296.03  5346.5  298.51  5437.7  304.69
#Mann=6,-1,0
  4561.2    0.12       0  4654.2    0.16       0  4829.8    0.12       0
  5005.2    0.07       0  5011.2    0.12       0  5089.3    0.16       0
Bank Sta=5005.2,5011.2
Exp/Cntr=0.3,0.1

Type RM Length L Ch R = 1,6567,513,513,513
BEGIN DESCRIPTION:
UNT231 IN CCTC 5.0
END DESCRIPTION:
XS GIS Cut Line= 3
      3606949.56     10679110.20      3607249.61     10679010.19
      3607499.58     10678810.21
#Sta/Elev= 30
  4698.1  287.49  4708.7  287.34  4719.2  286.17  4802.3  282.02  4845.7  279.73
  4887.9  276.37  4930.0  275.10  4940.6  274.04  4961.7  275.33  4982.8  273.32
  4990.3  269.94  4993.0  269.44  4996.3  269.94  5003.8  270.02  5011.7  275.55
  5042.4  274.44  5050.4  272.87  5056.8  273.41  5064.8  275.20  5071.2  275.01
  5085.6  276.03  5142.4  276.60  5192.9  279.67  5213.7  282.52  5228.1  283.24
  5234.5  285.25  5242.5  286.65  5266.5  288.52  5306.5  292.23  5334.5  293.26
#Mann=5,-1,0
  4698.1    0.16       0  4802.3    0.12       0  4990.3    0.07       0
  4996.3    0.12       0  5266.5    0.16       0
Bank Sta=4990.3,4996.3
Exp/Cntr=0.3,0.1

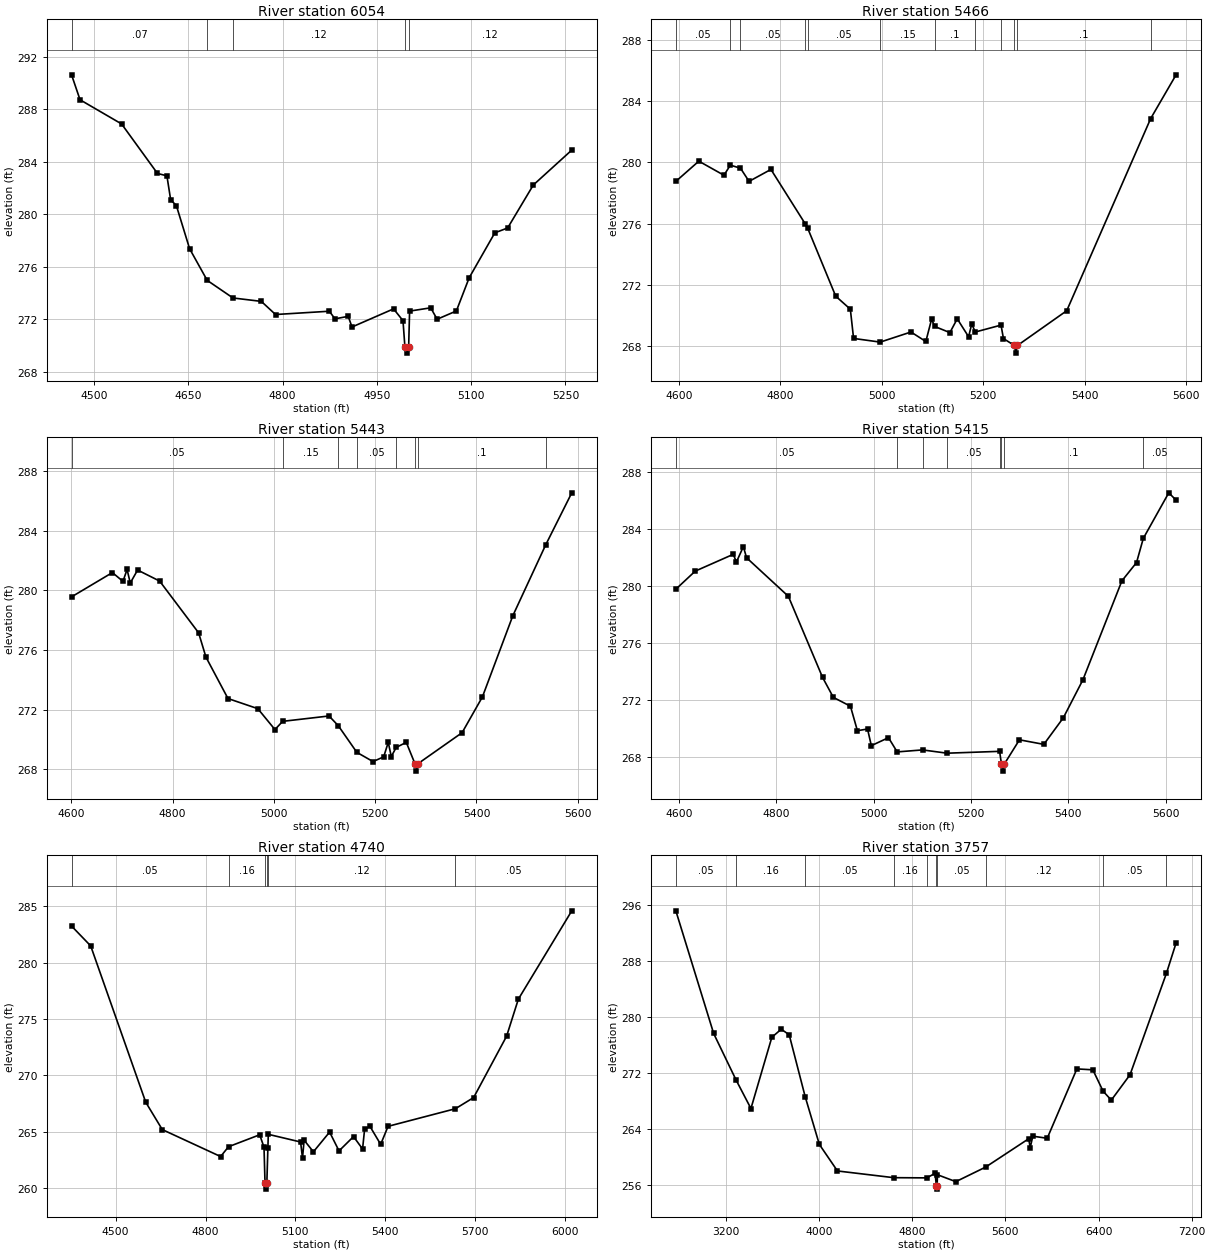
Type RM Length L Ch R = 1,6054,588,588,588
BEGIN DESCRIPTION:
UNT231 IN CCTC 4.0
END DESCRIPTION:
XS GIS Cut Line= 3
      3607099.63     10679560.17      3607549.61     10679260.19
      3607599.62     10679010.15
#Sta/Elev= 30
  4464.2  290.61  4477.7  288.71  4543.8  286.87  4600.9  283.10  4615.9  282.92
  4621.9  281.09  4630.9  280.66  4652.0  277.37  4680.0  274.96  4721.0  273.62
  4766.1  273.36  4788.7  272.36  4874.3  272.61  4883.3  272.03  4904.3  272.22
  4910.4  271.41  4976.5  272.79  4991.5  271.89  4994.5  269.92  4997.2  269.42
  5000.5  269.92  5002.0  272.62  5035.6  272.87  5045.8  272.00  5076.4  272.63
  5096.8  275.16  5137.6  278.58  5158.0  278.95  5198.8  282.22  5260.0  284.88
#Mann=5,-1,0
  4464.2    0.07       0  4680.0    0.16       0  4721.0    0.12       0
  4994.5    0.07       0  5000.5    0.12       0
Bank Sta=4994.5,5000.5
Exp/Cntr=0.3,0.1

Type RM Length L Ch R = 1,5466,23,23,23
BEGIN DESCRIPTION:
UNT231 IN CCTC 3.0
END DESCRIPTION:
XS GIS Cut Line= 6
      3607660.72     10679894.80      3607984.30     10679629.88
      3607998.62     10679559.57      3608057.47     10679505.40
      3608101.74     10679443.94      3608120.80     10679105.06
#Sta/Elev= 30
  4594.0  278.76  4639.3  280.08  4688.8  279.16  4701.4  279.82  4721.4  279.62
  4738.3  278.76  4781.4  279.54  4849.1  275.98  4853.6  275.72  4909.1  271.26
  4937.9  270.41  4944.3  268.50  4996.8  268.26  5057.4  268.92  5086.7  268.30
  5098.0  269.75  5104.3  269.28  5134.1  268.88  5148.6  269.78  5171.0  268.61
  5177.1  269.44  5184.3  268.92  5234.9  269.37  5239.7  268.49  5261.3  268.04
  5264.0  267.54  5267.3  268.04  5364.4  270.31  5529.8  282.86  5579.9  285.72
#Mann=12,-1,0
  4594.0    0.05       0  4701.4    0.16       0  4721.4    0.05       0
  4849.1     0.1       0  4853.6    0.05       0  4996.8    0.15       0
  5104.3     0.1       0  5184.3    0.05       0  5234.9     0.1       0
  5261.3    0.07       0  5267.3     0.1       0  5529.8    0.05       0
Bank Sta=5261.3,5267.3
Exp/Cntr=0.3,0.1

Type RM Length L Ch R = 1,5443,28,28,28
BEGIN DESCRIPTION:
Mapping XS f9a4eefe
END DESCRIPTION:
XS GIS Cut Line= 6
      3607681.61     10679905.17      3607968.24     10679683.00
      3608025.53     10679611.82      3608030.74     10679574.50
      3608114.94     10679443.42      3608136.37     10679104.15
#Sta/Elev= 30
  4600.6  279.57  4681.2  281.20  4702.1  280.61  4710.2  281.41  4716.5  280.50
  4731.0  281.37  4774.5  280.63  4851.4  277.16  4865.9  275.53  4909.4  272.75
  4968.3  272.07  5002.1  270.67  5017.4  271.22  5108.9  271.58  5127.1  270.93
  5163.8  269.14  5195.8  268.52  5216.8  268.84  5225.8  269.81  5231.8  268.86
  5241.5  269.47  5261.4  269.81  5278.5  268.38  5281.2  267.88  5284.5  268.38
  5371.6  270.46  5411.7  272.86  5471.8  278.31  5536.5  283.05  5588.1  286.55
#Mann=8,-1,0
  4600.6    0.05       0  5017.4    0.15       0  5127.1     0.1       0
  5163.8    0.05       0  5241.5     0.1       0  5278.5    0.03       0
  5284.5     0.1       0  5536.5    0.05       0
Bank Sta=5278.5,5284.5
Exp/Cntr=0.3,0.1

Type RM Length L Ch R = 1,5415,675,675,675
BEGIN DESCRIPTION:
UNT231 IN CCTC 2.0
END DESCRIPTION:
XS GIS Cut Line= 6
      3607698.90     10679934.75      3608046.36     10679643.94
      3608074.14     10679568.42      3608091.50     10679509.39
      3608132.06     10679442.59      3608155.53     10679089.22
#Sta/Elev= 30
  4593.7  279.80  4633.5  281.07  4711.6  282.25  4718.1  281.71  4732.4  282.79
  4738.9  282.01  4824.8  279.30  4895.1  273.60  4917.2  272.20  4952.3  271.58
  4966.6  269.86  4987.4  269.98  4995.2  268.81  5030.4  269.37  5048.3  268.37
  5100.3  268.51  5150.8  268.28  5258.7  268.41  5262.4  267.52  5265.2  267.02
  5268.4  267.52  5299.4  269.22  5349.5  268.90  5389.6  270.77  5429.7  273.43
  5509.9  280.39  5539.9  281.67  5553.8  283.37  5606.1  286.57  5621.1  286.06
#Mann=8,-1,0
  4593.7    0.05       0  5048.3    0.15       0  5100.3    0.12       0
  5150.8    0.05       0  5258.7     0.1       0  5262.4    0.03       0
  5268.4     0.1       0  5553.8    0.05       0
Bank Sta=5262.4,5268.4
Exp/Cntr=0.3,0.1

Type RM Length L Ch R = 1,4740,983,983,983
BEGIN DESCRIPTION:
Mapping XS 85860e12
END DESCRIPTION:
XS GIS Cut Line= 4
      3607860.70     10680205.41      3608431.04     10680111.66
      3608522.19     10679999.68      3608186.93     10679113.46
#Sta/Elev= 30
  4352.8  283.24  4416.7  281.48  4600.4  267.62  4655.7  265.19  4850.4  262.80
  4876.8  263.67  4980.9  264.73  4995.3  263.62  4998.7  260.41  5001.5  259.91
  5004.7  260.41  5008.2  263.52  5009.6  264.77  5117.4  264.09  5123.8  262.66
  5129.2  264.25  5160.2  263.22  5214.3  264.97  5245.7  263.30  5294.1  264.57
  5324.3  263.47  5331.2  265.24  5349.1  265.47  5384.7  263.88  5409.5  265.48
  5634.2  267.04  5695.1  268.03  5805.1  273.47  5844.4  276.76  6022.7  284.59
#Mann=6,-1,0
  4352.8    0.05       0  4876.8    0.16       0  4998.7    0.07       0
  5004.7    0.16       0  5008.2    0.12       0  5634.2    0.05       0
Bank Sta=4998.7,5004.7
Exp/Cntr=0.3,0.1

Type RM Length L Ch R = 1,3757,1335,1335,1335
BEGIN DESCRIPTION:
Mapping XS 24935403
END DESCRIPTION:
XS GIS Cut Line= 4
      3606824.25     10680128.11      3608713.17     10680808.68
      3609102.06     10680508.33      3608144.19     10678989.97
#Sta/Elev= 30
  2771.3  295.21  3095.9  277.65  3288.1  271.00  3415.9  266.91  3595.4  277.11
  3676.2  278.26  3744.3  277.47  3881.2  268.63  4003.2  261.77  4158.8  257.97
  4641.4  257.01  4926.0  256.98  4996.6  257.63  5008.1  255.87  5010.8  255.37
  5014.1  255.87  5017.4  257.43  5175.0  256.44  5430.4  258.52  5800.3  262.58
  5813.6  261.32  5835.8  262.95  5959.5  262.65  6214.1  272.58  6351.4  272.45
  6438.8  269.40  6509.7  268.11  6670.3  271.74  6983.2  286.28  7065.7  290.60
#Mann=10,-1,0
  2771.3    0.05       0  3288.1    0.16       0  3881.2    0.05       0
  4641.4    0.16       0  4926.0    0.05       0  5008.1    0.03       0
  5014.1    0.05       0  5430.4    0.12       0  6438.8    0.05       0
  6983.2    0.16       0
Bank Sta=5008.1,5014.1
Exp/Cntr=0.3,0.1

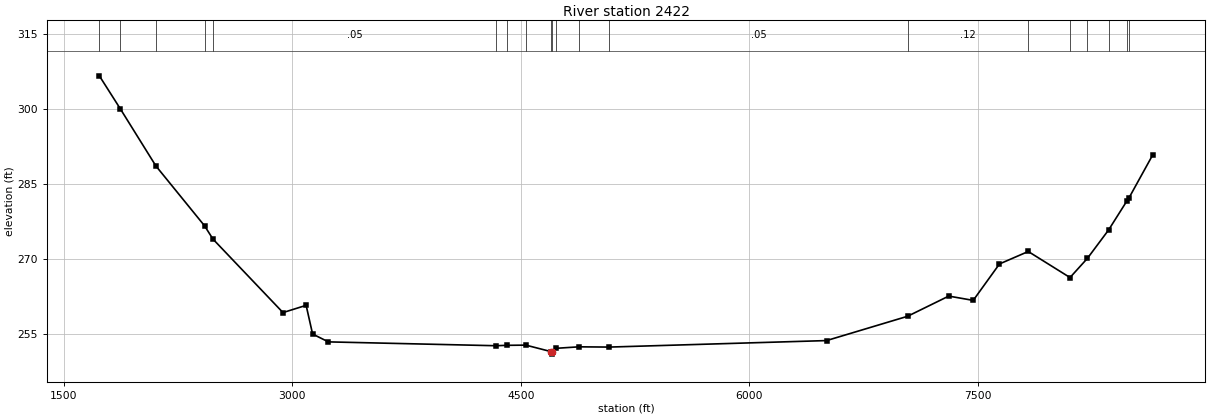
Type RM Length L Ch R = 1,2422,0,0,0
BEGIN DESCRIPTION:
UNT231 IN CCTC 1.0
END DESCRIPTION:
XS GIS Cut Line= 4
      3606415.46     10680142.65      3609012.65     10681774.58
      3609808.66     10681430.20      3608200.17     10678920.45
#Sta/Elev= 30
  1733.5  306.57  1870.0  300.03  2104.8  288.54  2423.9  276.58  2479.5  273.91
  2939.2  259.21  3091.1  260.66  3133.5  254.92  3237.2  253.35  4337.1  252.58
  4408.4  252.66  4533.6  252.70  4699.4  251.40  4702.2  250.90  4705.4  251.40
  4730.1  252.06  4882.3  252.36  5081.5  252.31  6507.6  253.61  7039.5  258.47
  7309.9  262.51  7470.5  261.65  7642.9  268.94  7831.8  271.43  8106.0  266.22
  8220.5  270.07  8359.3  275.74  8478.8  281.51  8493.8  282.19  8649.1  290.76
#Mann=20,-1,0
  1733.5    0.16       0  1870.0    0.12       0  2104.8    0.12       0
  2423.9    0.16       0  2479.5    0.05       0  4337.1    0.08       0
  4408.4    0.05       0  4533.6    0.08       0  4699.4    0.07       0
  4705.4    0.08       0  4730.1    0.05       0  4882.3    0.08       0
  5081.5    0.05       0  7039.5    0.12       0  7831.8    0.05       0
  8106.0    0.16       0  8220.5    0.05       0  8359.3    0.16       0
  8478.8    0.05       0  8493.8    0.16       0
Bank Sta=4699.4,4705.4
Exp/Cntr=0.3,0.1

Chan Stop Cuts=-1