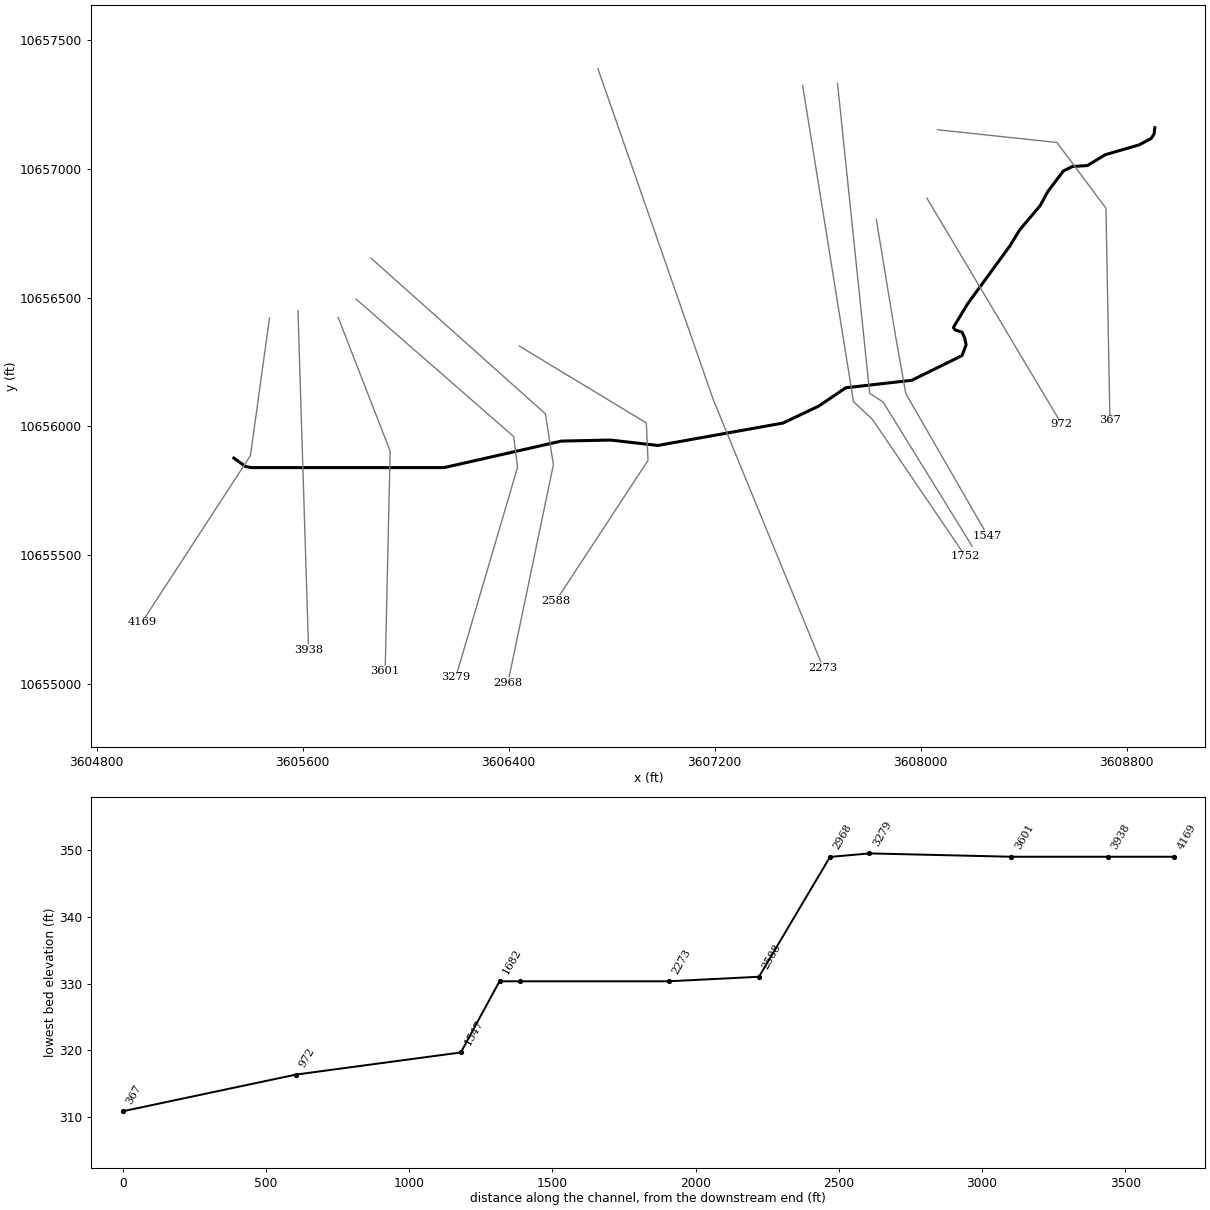
--- UNT235 IN CCTC.prj (project) ---

Proj Title=UNT235 IN CCTC Base Level Engineering
Current Plan=p01
Default Exp/Contr=0.3,0.1
English Units
Geom File=g01
Flow File=f01
Plan File=p01
Y Axis Title=Elevation
X Axis Title(PF)=Main Channel Distance
X Axis Title(XS)=Station
BEGIN DESCRIPTION:
UNT235 IN CCTC
END DESCRIPTION:
DSS Export Rating Curves= 0
DSS Export Rating Curve Sorted= 0
DSS Export Volume Flow Curves= 0
DXF OffsetX= 0
DXF OffsetY= 0
DXF ScaleX= 1
DXF ScaleY= 10

--- UNT235 IN CCTC.p01 (plan) ---

Plan Title=Multiple Run
Short Identifier=Multiple
Geom File=g01
Flow File=f01
Subcritical Flow
K Sum by GR= 0
Std Step Tol= 0.01
Critical Tol= 0.01
Num of Std Step Trials= 20
Max Error Tol= 0.3
Flow Tol Ratio= 0.001
Split Flow NTrial= 30
Split Flow Tol= 0.02
Split Flow Ratio= 0.02
Log Output Level= 0
Friction Slope Method= 1
Unsteady Friction Slope Method= 2
Unsteady Bridges Friction Slope Method= 1
Parabolic Critical Depth
Global Vel Dist=  1 , 1 , 1
Global Log Level= 0
CheckData=True
Encroach Param= -1, 0, 0, 0
BEGIN DESCRIPTION:
Multiple Run
END DESCRIPTION:

--- UNT235 IN CCTC.f01 (steady flow) ---

Flow Title=Multiple
Number of Profiles=7
Profile Names=10-year,25-year,50-year,1pct_min,100-year,1pct_plu,500-year
River Rch & RM= UNT235 IN CCTC,Reach-1,4169
    1340    1842    2257    2020    2731    3694    3985
Boundary for River Rch & Prof#=UNT235 IN CCTC,Reach-1,1
Up Type=0
Dn Type=3
Dn Slope=0.005
Boundary for River Rch & Prof#=UNT235 IN CCTC,Reach-1,2
Up Type=0
Dn Type=3
Dn Slope=0.005
Boundary for River Rch & Prof#=UNT235 IN CCTC,Reach-1,3
Up Type=0
Dn Type=3
Dn Slope=0.005
Boundary for River Rch & Prof#=UNT235 IN CCTC,Reach-1,4
Up Type=0
Dn Type=3
Dn Slope=0.005
Boundary for River Rch & Prof#=UNT235 IN CCTC,Reach-1,5
Up Type=0
Dn Type=3
Dn Slope=0.005
Boundary for River Rch & Prof#=UNT235 IN CCTC,Reach-1,6
Up Type=0
Dn Type=3
Dn Slope=0.005
Boundary for River Rch & Prof#=UNT235 IN CCTC,Reach-1,7
Up Type=0
Dn Type=3
Dn Slope=0.005

--- UNT235 IN CCTC.g01 (geometry) ---

Geom Title=Existing Conditions
Program Version=4.10

River Reach=UNT235 IN CCTC  ,Reach-1
Reach XY= 30
        3605333.       10655877.        3605377.       10655845.
      3605399.75       10655840.       3606149.5       10655840.
      3606604.75       10655943.      3606795.75       10655947.
      3606979.75       10655926.      3607465.75       10656013.
      3607604.75       10656079.       3607709.5       10656150.
      3607965.75       10656179.        3608161.       10656275.
      3608176.75       10656317.       3608171.5       10656343.
        3608161.       10656366.        3608135.       10656374.
      3608127.25       10656384.        3608182.       10656475.
        3608347.       10656701.      3608384.75       10656763.
      3608464.25       10656857.      3608494.75       10656913.
      3608554.75       10656992.      3608589.25       10657009.
      3608648.25       10657013.      3608717.25       10657055.
      3608848.25       10657093.       3608895.5       10657118.
        3608907.       10657136.       3608909.5       10657160.

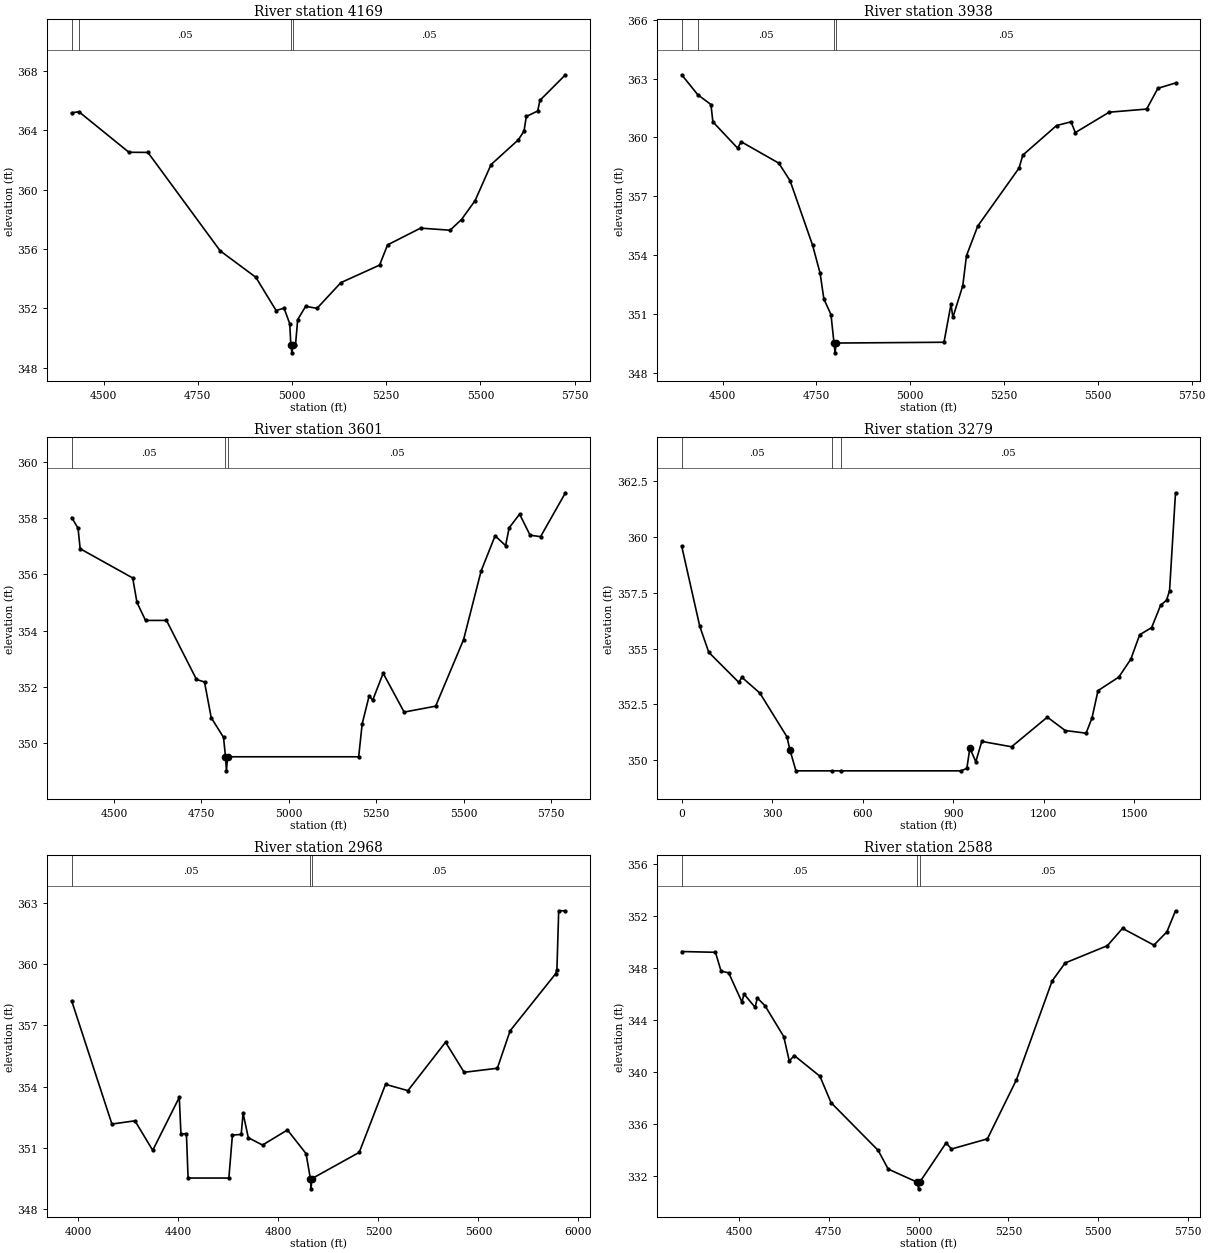
Type RM Length L Ch R = 1 ,4169    ,231,231,231
BEGIN DESCRIPTION:
UNT235 IN CCTC 8.0
END DESCRIPTION:
XS GIS Cut Line= 3
      3605471.36     10656420.67      3605397.57     10655886.81
      3604976.57     10655240.11
#Sta/Elev= 30
  4415.2  365.18  4434.5  365.25  4567.1  362.52  4617.6  362.51  4809.4  355.88
    4904   354.1  4957.8  351.86  4978.9  352.02    4994  350.97    4997  349.51
  4999.8  349.01    5003  349.51  5009.2  349.51  5015.1  351.25  5036.2  352.14
  5066.5  352.01  5129.8  353.74  5232.5  354.92  5253.6  356.28  5341.2  357.41
  5419.6  357.27  5449.9  357.99  5486.1  359.27  5528.3  361.69  5600.8  363.36
  5615.9  363.95  5621.9  364.93  5652.1   365.3  5658.1  366.02  5725.8  367.74
#Mann= 4 ,-1 , 0
  4415.2     .08       0  4434.5     .05       0    4997     .03       0
    5003     .05       0
Bank Sta=4997,5003
XS Rating Curve= 0 ,0
Exp/Cntr=0.3,0.1

Type RM Length L Ch R = 1 ,3938    ,337,337,337
BEGIN DESCRIPTION:
Mapping XS f4481fbd
END DESCRIPTION:
XS GIS Cut Line= 2
      3605582.03      10656448.9      3605623.21     10655133.35
#Sta/Elev= 30
  4390.8   363.2  4433.7  362.18  4468.8  361.68  4473.8   360.8  4539.6  359.46
  4549.6  359.78  4649.6  358.69  4679.7  357.79  4739.7   354.5  4759.7  353.07
  4769.7  351.76  4788.7  350.96  4796.7  349.51  4799.5  349.01  4802.7  349.51
  5089.9  349.55  5108.6  351.49  5113.6  350.82  5139.9  352.43  5149.9  353.97
  5179.9  355.48    5290  358.44    5300   359.1    5390  360.61  5428.5   360.8
    5440  360.25  5530.1  361.29  5630.1  361.45  5660.1  362.51    5707  362.78
#Mann= 4 ,-1 , 0
  4390.8     .08       0  4433.7     .05       0  4796.7    .033       0
  4802.7     .05       0
Bank Sta=4796.7,4802.7
XS Rating Curve= 0 ,0
Exp/Cntr=0.3,0.1

Type RM Length L Ch R = 1 ,3601    ,495,495,495
BEGIN DESCRIPTION:
UNT235 IN CCTC 7.0
END DESCRIPTION:
XS GIS Cut Line= 3
       3605738.3      10656422.8      3605940.11     10655904.17
      3605920.58     10655049.11
#Sta/Elev= 30
  4379.3  358.02  4397.5  357.64  4403.6  356.91  4553.8  355.87    4566     355
  4590.5  354.36  4650.4  354.36  4736.2  352.26  4759.1  352.17  4778.3   350.9
  4813.5   350.2  4819.1  349.51  4821.8  349.01  4825.1  349.51  5199.9  349.51
  5209.9  350.68  5229.9  351.68  5239.9  351.52  5269.9  352.48  5329.9   351.1
  5419.9  351.31  5499.9  353.68    5550  356.12    5590  357.37    5620  357.02
    5630  357.65    5660  358.14    5690  357.39    5720  357.34  5791.1   358.9
#Mann= 3 ,-1 , 0
  4379.3     .05       0  4819.1    .033       0  4825.1     .05       0
Bank Sta=4819.1,4825.1
XS Rating Curve= 0 ,0
Exp/Cntr=0.3,0.1

Type RM Length L Ch R = 1 ,3279    ,138,138,138
BEGIN DESCRIPTION:
UNT235 IN CCTC 6.0
END DESCRIPTION:
XS GIS Cut Line= 4
      3605807.72     10656494.45      3606419.71     10655960.59
       3606434.9     10655841.23      3606194.61     10655025.11
#Sta/Elev= 30
       0  359.59   59.77     356   89.66  354.83  189.28  353.48  199.24  353.71
  259.01     353  348.67  351.04  358.63  350.45  378.56  349.51   498.1  349.51
  527.99  349.51  925.28  349.51  945.04  349.62  954.92  350.53  974.67  349.92
  994.43  350.83 1093.21  350.59 1211.74  351.92 1271.01  351.32 1340.16   351.2
 1359.91  351.89 1379.67  353.11 1448.82  353.72 1488.33  354.52 1517.96  355.62
 1557.47  355.94 1587.11  356.94 1606.86  357.17 1616.74  357.59  1636.5  361.99
#Mann= 3 ,-1 , 0
       0     .05       0   498.1     .03       0  527.99     .05       0
Bank Sta=358.63,954.92
XS Rating Curve= 0 ,0
Exp/Cntr=0.3,0.1

Type RM Length L Ch R = 1 ,2968    ,248,248,248
BEGIN DESCRIPTION:
Mapping XS d7f0d6a2
END DESCRIPTION:
XS GIS Cut Line= 4
      3605865.69     10656653.36      3606542.79     10656049.18
      3606574.04     10655851.27      3606397.26     10655003.74
#Sta/Elev= 30
  3974.3  358.21  4135.2  352.16  4227.2  352.32  4298.3  350.87  4404.4  353.47
  4411.1  351.67  4432.9  351.69  4439.6  349.51  4602.6  349.51  4616.8  351.62
  4651.9  351.65  4659.4  352.69  4680.3  351.49  4737.2  351.13  4836.7  351.87
  4911.1  350.71  4928.4  349.48  4931.1  348.98  4934.4  349.48  5123.7  350.77
  5228.8  354.11  5318.2   353.8  5468.7  356.18  5542.9   354.7  5675.7   354.9
  5726.8  356.74  5908.7  359.54  5913.8  359.73  5920.9  362.63  5947.9  362.63
#Mann= 3 ,-1 , 0
  3974.3     .05       0  4928.4     .03       0  4934.4     .05       0
Bank Sta=4928.4,4934.4
XS Rating Curve= 0 ,0
Exp/Cntr=0.3,0.1

Type RM Length L Ch R = 1 ,2588    ,315,315,315
BEGIN DESCRIPTION:
UNT235 IN CCTC 5.0
END DESCRIPTION:
XS GIS Cut Line= 4
      3606441.39     10656312.16      3606934.93     10656013.38
      3606941.44     10655867.98      3606583.53     10655322.01
#Sta/Elev= 30
  4340.3  349.25  4434.3  349.19  4449.8  347.75  4471.1  347.61    4508  345.37
  4513.8  345.99  4544.8  344.96  4550.7  345.68    4572   345.1  4624.4  342.72
  4639.9  340.84  4653.8  341.26  4725.2  339.67  4756.2  337.64  4887.6  333.97
  4915.3  332.54    4997  331.52  4999.8  331.02    5003  331.52  5076.7  334.55
  5091.7  334.08  5191.7  334.86  5272.6   339.4    5372  346.99  5408.2  348.37
  5525.9   349.7    5568  351.03  5655.5  349.74  5691.6  350.76  5715.6  352.38
#Mann= 3 ,-1 , 0
  4340.3     .05       0    4997     .03       0    5003     .05       0
Bank Sta=4997,5003
XS Rating Curve= 0 ,0
Exp/Cntr=0.3,0.1

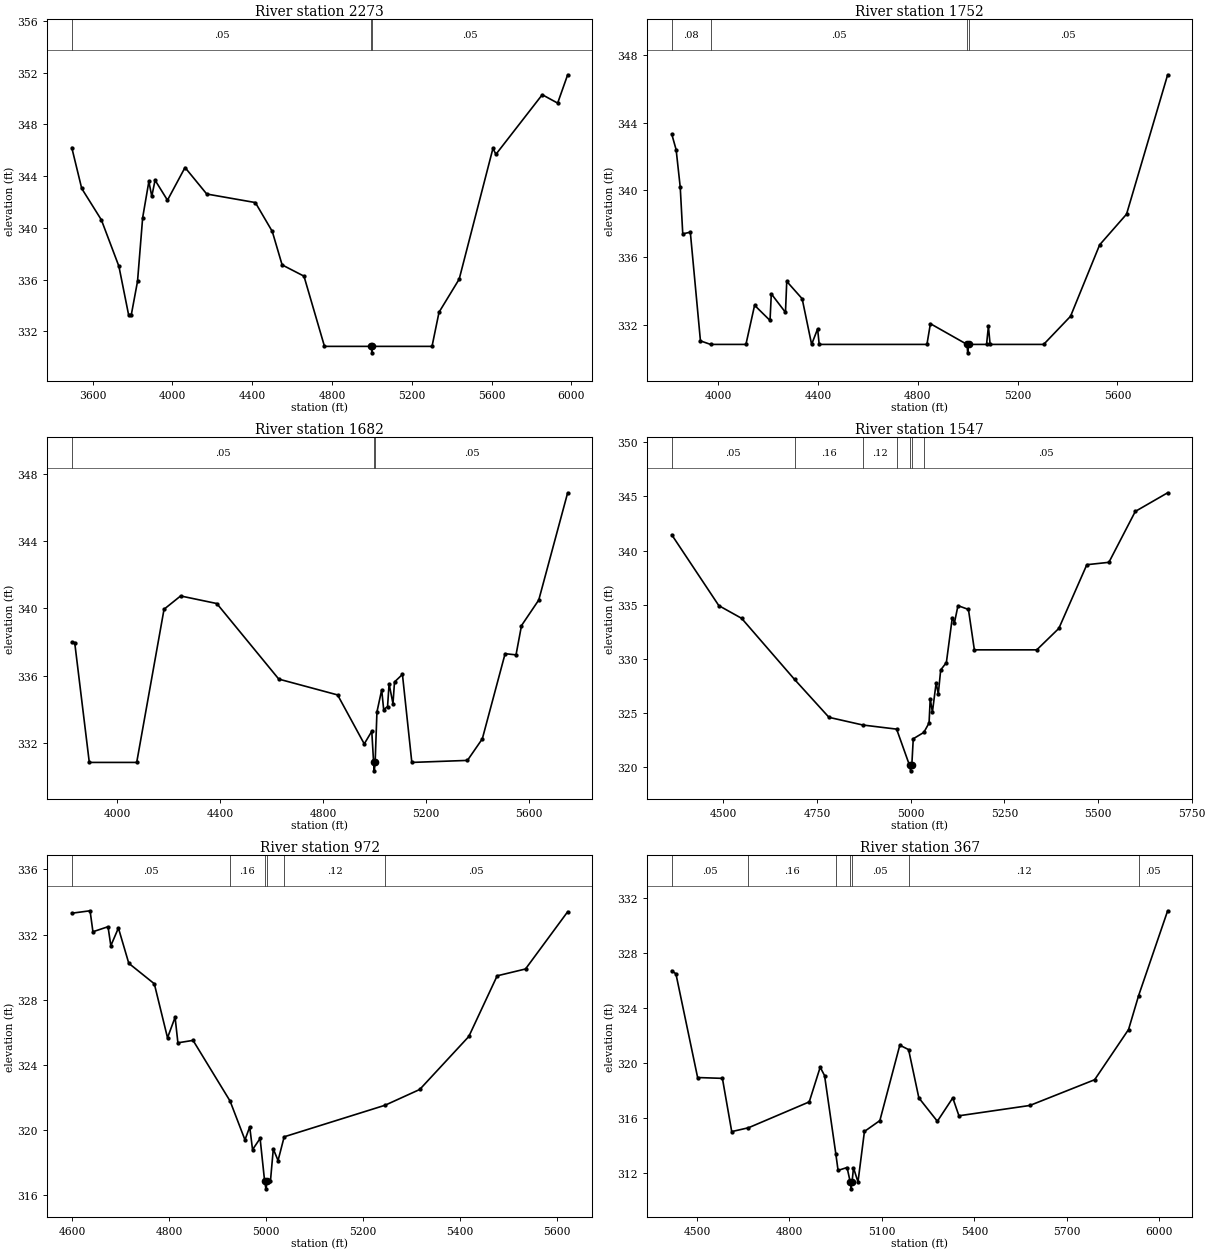
Type RM Length L Ch R = 1 ,2273    ,521,521,521
BEGIN DESCRIPTION:
UNT235 IN CCTC 4.0
END DESCRIPTION:
XS GIS Cut Line= 3
      3606747.02     10657388.78      3607194.92     10656104.09
      3607621.46     10655063.77
#Sta/Elev= 30
  3496.1  346.21  3545.9  343.05  3644.4  340.62  3732.3  337.03  3780.6   333.3
  3794.5  333.29  3825.6  335.87  3851.3  340.79  3882.4  343.59    3897  342.44
  3913.5  343.69  3975.6  342.14  4063.6  344.67  4172.4  342.62    4416  341.96
  4500.7  339.73  4550.1  337.14  4659.6  336.27  4762.4  330.84    4997  330.84
  4999.8  330.34    5003  330.84  5301.3  330.84  5336.4  333.48  5437.4  336.04
  5606.6  346.15  5621.5  345.69  5853.6   350.3  5930.8  349.65    5981  351.84
#Mann= 3 ,-1 , 0
  3496.1     .05       0    4997    .035       0    5003     .05       0
Bank Sta=4997,5003
XS Rating Curve= 0 ,0
Exp/Cntr=0.3,0.1

Type RM Length L Ch R = 1 ,1752    ,70,70,70
BEGIN DESCRIPTION:
UNT235 IN CCTC 3.0
END DESCRIPTION:
XS GIS Cut Line= 4
        3607542.     10657323.71      3607739.46     10656095.86
      3607812.38     10656028.15      3608174.49     10655495.04
#Sta/Elev= 30
  3813.6  343.32  3831.2  342.39  3847.6  340.17  3857.7   337.4    3888   337.5
  3928.6  331.05  3969.2  330.84  4110.9  330.84  4145.6  333.16  4207.5  332.26
  4212.6  333.84  4269.4  332.74  4274.5  334.58  4336.3  333.55  4374.2  330.84
  4398.2  331.76  4404.6  330.84  4836.4  330.84  4850.3  332.07    4997  330.84
  4999.8  330.34    5003  330.84  5075.4  330.84  5082.8  331.92  5089.6  330.84
  5304.2  330.84    5412  332.51  5528.7  336.75  5636.5  338.57  5801.2  346.84
#Mann= 4 ,-1 , 0
  3813.6     .08       0  3969.2     .05       0    4997     .03       0
    5003     .05       0
Bank Sta=4997,5003
XS Rating Curve= 0 ,0
Exp/Cntr=0.3,0.1

Type RM Length L Ch R = 1 ,1682    ,135,135,135
BEGIN DESCRIPTION:
Mapping XS 423a56cd
END DESCRIPTION:
XS GIS Cut Line= 4
      3607677.42     10657331.54      3607802.42      10656128.4
       3607854.5     10656094.54      3608200.34     10655534.45
#Sta/Elev= 30
  3822.3     338  3833.7  337.96  3890.5  330.84    4075  330.84  4181.4  339.94
  4245.9  340.73  4386.7  340.28    4628  335.79  4856.9  334.85  4960.6  331.94
  4989.9  332.69    4997  330.84  4999.8  330.34    5003  330.84    5010  333.84
  5028.5  335.15  5036.2  333.98  5051.3  334.16  5057.3  335.51  5072.4  334.33
  5078.4  335.62  5109.2  336.07  5145.8  330.84  5362.2  330.96  5420.1  332.24
  5508.8   337.3  5551.3  337.23  5572.6  338.97  5639.8  340.49  5752.3  346.86
#Mann= 3 ,-1 , 0
  3822.3     .05       0    4997     .03       0    5003     .05       0
Bank Sta=4997,5003
XS Rating Curve= 0 ,0
Exp/Cntr=0.3,0.1

Type RM Length L Ch R = 1 ,1547    ,575,575,575
BEGIN DESCRIPTION:
UNT235 IN CCTC 2.0
END DESCRIPTION:
XS GIS Cut Line= 4
        3607828.     10656804.22      3607900.92     10656361.49
      3607942.59     10656127.11      3608260.68     10655575.39
#Sta/Elev= 30
  4362.3  341.46    4488  334.92  4548.8  333.75    4690  328.11  4781.9  324.61
  4872.4   323.9  4962.5  323.52    4997  320.17  4999.8  319.67    5003  320.17
  5006.9  322.63  5035.2  323.22  5049.1  324.09  5052.2  326.33    5058  325.09
    5068   327.8  5073.7  326.77  5080.1  328.98  5095.3  329.67  5111.1  333.81
  5116.8  333.34  5126.3  334.92  5154.2  334.57    5170  330.84  5336.6  330.84
  5395.5  332.82  5470.2   338.7  5529.1  338.92  5599.6  343.62  5685.9  345.34
#Mann= 7 ,-1 , 0
  4362.3     .05       0    4690     .16       0  4872.4     .12       0
  4962.5     .16       0    4997     .07       0    5003     .16       0
  5035.2     .05       0
Bank Sta=4997,5003
XS Rating Curve= 0 ,0
Exp/Cntr=0.3,0.1

Type RM Length L Ch R = 1 ,972     ,605,605,605
BEGIN DESCRIPTION:
Mapping XS 80f71309
END DESCRIPTION:
XS GIS Cut Line= 2
      3608024.49     10656886.28      3608547.96     10656008.63
#Sta/Elev= 30
  4599.7  333.31  4637.4  333.46  4643.3  332.17  4674.4  332.48  4680.2  331.31
  4695.8   332.4  4717.2  330.23  4769.8  328.97    4797  325.65  4812.6  326.91
  4818.4  325.34  4849.6  325.49  4925.9  321.76  4956.6  319.37  4966.4  320.17
  4972.2  318.77  4987.8  319.46    4997  316.86  4999.8  316.36    5003  316.86
  5009.2  316.87    5015  318.81  5024.8   318.1  5037.4  319.56  5245.2   321.5
  5316.7  322.47  5417.9  325.73  5476.3  329.46  5534.7  329.88  5621.6   333.4
#Mann= 6 ,-1 , 0
  4599.7     .05       0  4925.9     .16       0    4997     .07       0
    5003     .16       0  5037.4     .12       0  5245.2     .05       0
Bank Sta=4997,5003
XS Rating Curve= 0 ,0
Exp/Cntr=0.3,0.1

Type RM Length L Ch R = 1 ,367     ,0,0,0
BEGIN DESCRIPTION:
UNT235 IN CCTC 1.0
END DESCRIPTION:
XS GIS Cut Line= 4
      3608066.19     10657151.86      3608529.72     10657102.39
      3608719.83     10656847.18      3608735.42     10656023.42
#Sta/Elev= 30
  4418.2  326.71  4431.7  326.49  4502.1  318.95  4582.5  318.89  4612.7  315.02
  4667.1   315.3  4864.1  317.18  4899.6   319.7  4913.8  319.09  4950.2  313.42
  4957.6   312.2  4986.8  312.41    4997  311.36  4999.8  310.86    5003  311.36
  5007.6  312.39  5022.2  311.36  5043.1  315.03  5093.1  315.82  5157.8   321.3
  5186.3  320.98  5219.6  317.47  5279.6  315.77  5329.6  317.47  5349.6  316.17
  5579.6  316.92  5789.7  318.79  5899.7  322.44  5932.4  324.91  6026.5  331.07
#Mann= 7 ,-1 , 0
  4418.2     .05       0  4667.1     .16       0  4950.2     .05       0
    4997     .03       0    5003     .05       0  5186.3     .12       0
  5932.4     .05       0
Bank Sta=4997,5003
XS Rating Curve= 0 ,0
Exp/Cntr=0.3,0.1

Chan Stop Cuts=-1
Use User Specified Reach Order=0
Composite Channel Slope=5