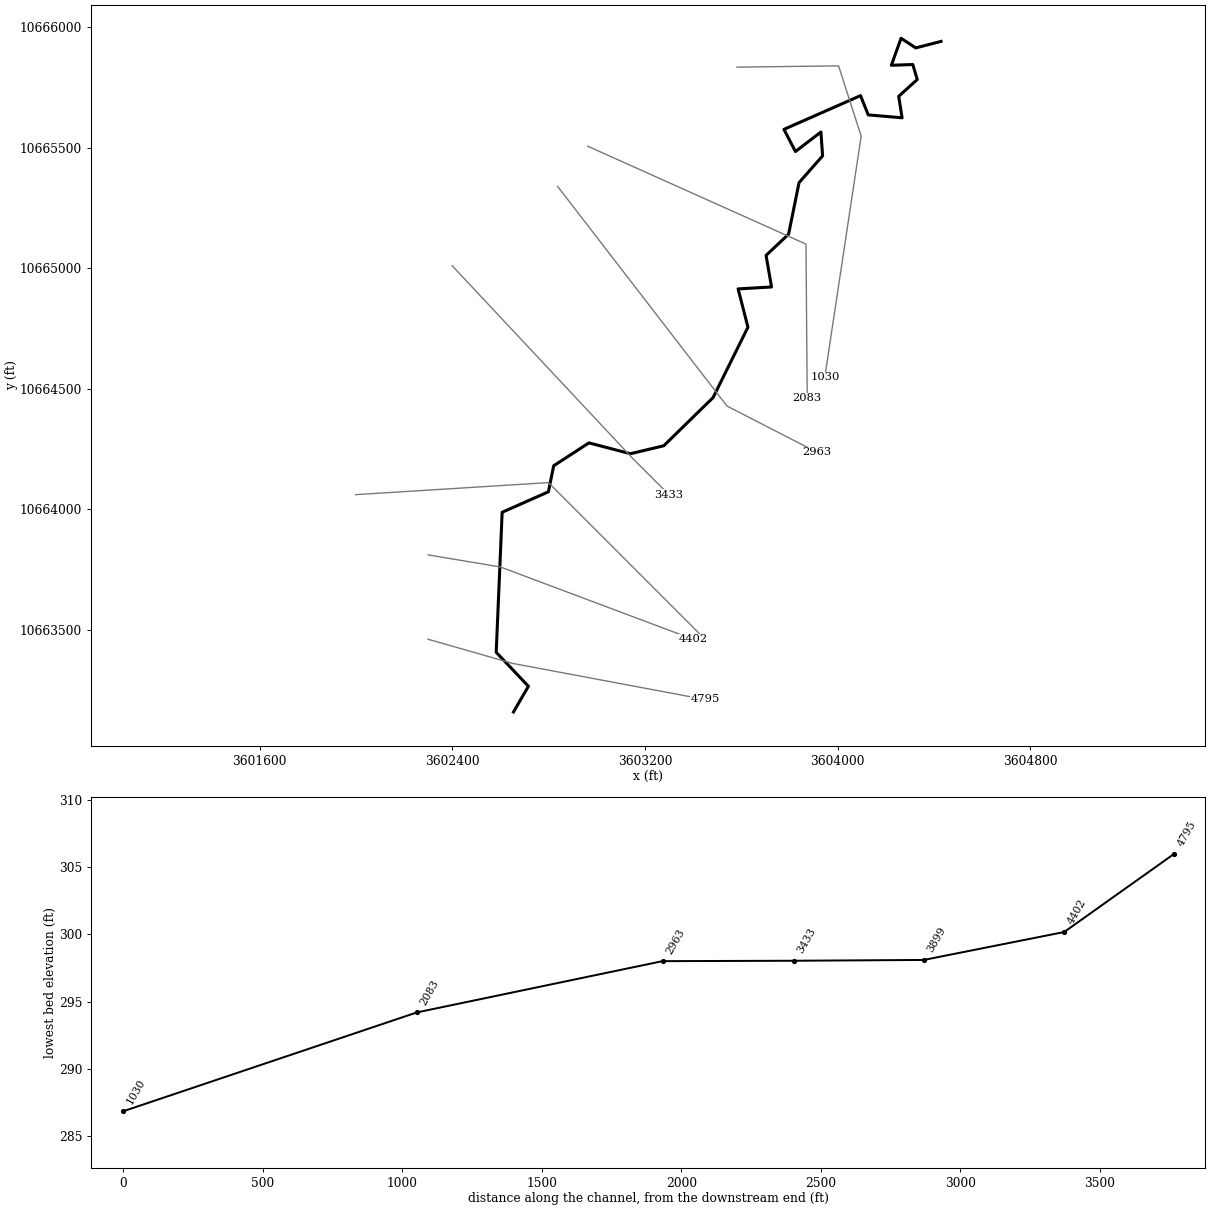
--- UNT236 IN CCTC.prj (project) ---

Proj Title=UNT236 IN CCTC Base Level Engineering
Current Plan=p01
Default Exp/Contr=0.3,0.1
English Units
Geom File=g01
Flow File=f01
Plan File=p01
BEGIN DESCRIPTION:
UNT236 IN CCTC
END DESCRIPTION:

--- UNT236 IN CCTC.p01 (plan) ---

Plan Title=Multiple Run
Short Identifier=Multiple
Geom File=g01
Flow File=f01
Subcritical Flow
K Sum by GR= 0
Std Step Tol= 0.01
Critical Tol= 0.01
Num of Std Step Trials= 20
Max Error Tol= 0.3
Flow Tol Ratio= 0.001
Split Flow NTrial= 30
Split Flow Tol= 0.02
Split Flow Ratio= 0.02
Log Output Level= 0
Friction Slope Method= 1
Unsteady Friction Slope Method= 2
Unsteady Bridges Friction Slope Method= 1
Parabolic Critical Depth
Global Vel Dist=  1 , 1 , 1
Global Log Level= 0
CheckData=True
Encroach Param= -1, 0, 0, 0
BEGIN DESCRIPTION:
Multiple Run
END DESCRIPTION:

--- UNT236 IN CCTC.f01 (steady flow) ---

Flow Title=Multiple
Number of Profiles=7
Profile Names=10-year,25-year,50-year,1pct_min,100-year,1pct_plu,500-year
River Rch & RM= UNT236 IN CCTC,Reach-1,4795
    1807    2513    3102    2791    3775    5105    5572
Boundary for River Rch & Prof#=UNT236 IN CCTC,Reach-1,1
Up Type=0
Dn Type=3
Dn Slope=0.005
Boundary for River Rch & Prof#=UNT236 IN CCTC,Reach-1,2
Up Type=0
Dn Type=3
Dn Slope=0.005
Boundary for River Rch & Prof#=UNT236 IN CCTC,Reach-1,3
Up Type=0
Dn Type=3
Dn Slope=0.005
Boundary for River Rch & Prof#=UNT236 IN CCTC,Reach-1,4
Up Type=0
Dn Type=3
Dn Slope=0.005
Boundary for River Rch & Prof#=UNT236 IN CCTC,Reach-1,5
Up Type=0
Dn Type=3
Dn Slope=0.005
Boundary for River Rch & Prof#=UNT236 IN CCTC,Reach-1,6
Up Type=0
Dn Type=3
Dn Slope=0.005
Boundary for River Rch & Prof#=UNT236 IN CCTC,Reach-1,7
Up Type=0
Dn Type=3
Dn Slope=0.005

--- UNT236 IN CCTC.g01 (geometry) ---

Geom Title=Existing Conditions

River Reach=UNT236 IN CCTC,Reach-1
Reach XY= 30
      3602654.34     10663158.40      3602716.25     10663265.00
      3602582.50     10663406.00      3602607.25     10663987.00
      3602799.25     10664072.00      3602821.25     10664180.00
      3602967.50     10664275.00      3603139.75     10664230.00
      3603278.25     10664263.00      3603483.00     10664463.00
      3603627.75     10664755.00      3603587.00     10664914.00
      3603725.75     10664922.00      3603703.00     10665053.00
      3603796.50     10665141.00      3603840.00     10665355.00
      3603937.75     10665466.00      3603930.75     10665565.00
      3603825.00     10665484.00      3603777.25     10665576.00
      3604095.25     10665716.00      3604127.25     10665636.00
      3604267.75     10665624.00      3604253.75     10665713.00
      3604330.75     10665783.00      3604312.25     10665845.00
      3604223.25     10665842.00      3604263.50     10665954.00
      3604324.50     10665914.00      3604429.50     10665941.00

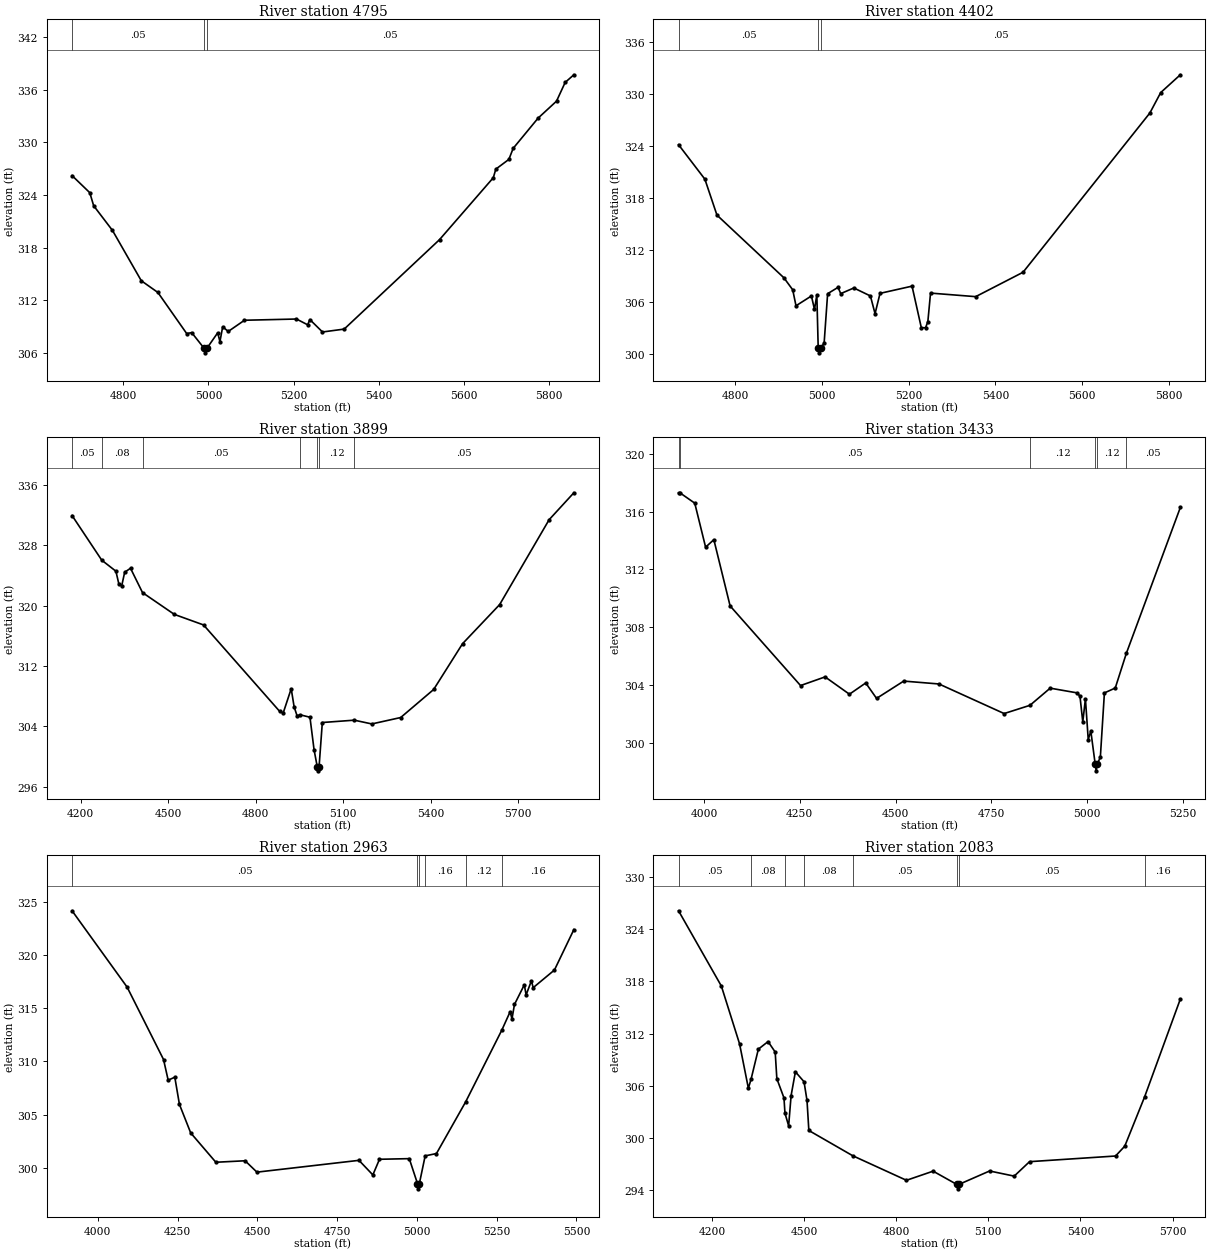
Type RM Length L Ch R = 1,4795,393,393,393
BEGIN DESCRIPTION:
UNT236 IN CCTC 6.0
END DESCRIPTION:
XS GIS Cut Line= 3
      3602299.57     10663460.20      3602649.61     10663360.19
      3603449.62     10663210.19
#Sta/Elev= 30
  4679.9  326.22  4721.5  324.27  4730.6  322.78  4774.8  319.96  4842.4  314.22
  4881.4  312.88  4949.0  308.19  4960.7  308.30  4990.2  306.49  4993.0  305.99
  4996.2  306.49  5021.8  308.28  5027.0  307.27  5033.5  308.97  5046.5  308.43
  5084.6  309.71  5206.7  309.85  5233.0  309.19  5238.1  309.79  5267.8  308.37
  5318.7  308.70  5542.5  318.91  5668.8  325.98  5674.7  326.96  5705.3  328.07
  5715.4  329.33  5773.9  332.78  5817.2  334.72  5837.5  336.86  5857.9  337.73
#Mann=3,-1,0
  4679.9    0.05       0  4990.2    0.03       0  4996.2    0.05       0
Bank Sta=4990.2,4996.2
Exp/Cntr=0.3,0.1

Type RM Length L Ch R = 1,4402,503,503,503
BEGIN DESCRIPTION:
UNT236 IN CCTC 5.0
END DESCRIPTION:
XS GIS Cut Line= 3
      3602299.60     10663810.19      3602599.61     10663760.19
      3603399.57     10663460.20
#Sta/Elev= 30
  4668.6  324.15  4729.4  320.18  4757.3  316.04  4911.9  308.82  4932.2  307.44
  4939.8  305.60  4975.4  306.73  4982.5  305.18  4987.9  306.86  4991.1  300.68
  4993.9  300.18  4997.1  300.68  5004.8  301.34  5012.8  306.99  5036.8  307.72
  5043.1  307.00  5073.3  307.65  5111.6  306.73  5122.3  304.69  5133.8  307.03
  5207.7  307.86  5229.1  303.08  5238.9  303.07  5244.2  303.77  5250.4  307.06
  5354.6  306.65  5464.0  309.46  5756.8  327.80  5781.8  330.15  5827.1  332.20
#Mann=3,-1,0
  4668.6    0.05       0  4991.1    0.03       0  4997.1    0.05       0
Bank Sta=4991.1,4997.1
Exp/Cntr=0.3,0.1

Type RM Length L Ch R = 1,3899,466,466,466
BEGIN DESCRIPTION:
UNT236 IN CCTC 4.0
END DESCRIPTION:
XS GIS Cut Line= 3
      3601999.56     10664060.19      3602799.61     10664110.19
      3603449.57     10663460.22
#Sta/Elev= 30
  4170.7  331.96  4272.5  326.04  4321.0  324.58  4331.1  322.89  4341.1  322.66
  4351.1  324.44  4371.1  324.97  4412.3  321.74  4521.4  318.85  4621.6  317.45
  4882.1  306.01  4894.7  305.77  4922.2  308.99  4932.2  306.59  4942.3  305.40
  4953.0  305.53  4986.5  305.21  5000.6  300.89  5011.7  298.60  5014.5  298.10
  5017.7  298.60  5028.9  304.51  5138.5  304.82  5198.6  304.32  5297.6  305.17
  5410.7  308.89  5509.7  314.96  5637.0  320.15  5806.7  331.41  5891.5  334.98
#Mann=7,-1,0
  4170.7    0.05       0  4272.5    0.08       0  4412.3    0.05       0
  4953.0    0.12       0  5011.7    0.07       0  5017.7    0.12       0
  5138.5    0.05       0
Bank Sta=5011.7,5017.7
Exp/Cntr=0.3,0.1

Type RM Length L Ch R = 1,3433,470,470,470
BEGIN DESCRIPTION:
UNT236 IN CCTC 3.0
END DESCRIPTION:
XS GIS Cut Line= 3
      3602399.62     10665010.18      3603149.61     10664210.19
      3603299.61     10664060.19
#Sta/Elev= 30
  3933.9  317.31  3937.4  317.31  3976.2  316.59  4004.5  313.54  4026.0  314.06
  4068.4  309.47  4252.1  303.95  4316.1  304.55  4379.6  303.35  4422.1  304.13
  4450.4  303.06  4521.2  304.26  4613.1  304.06  4783.1  302.01  4850.4  302.58
  4903.2  303.77  4974.0  303.44  4980.9  303.20  4988.2  301.43  4995.1  303.03
  5002.4  300.21  5009.2  300.79  5020.4  298.54  5023.1  298.04  5026.4  298.54
  5034.0  298.98  5044.6  303.44  5072.9  303.78  5101.9  306.19  5242.6  316.29
#Mann=6,-1,0
  3933.9    0.08       0  3937.4    0.05       0  4850.4    0.12       0
  5020.4    0.07       0  5026.4    0.12       0  5101.9    0.05       0
Bank Sta=5020.4,5026.4
Exp/Cntr=0.3,0.1

Type RM Length L Ch R = 1,2963,880,880,880
BEGIN DESCRIPTION:
Mapping XS 4f0426a8
END DESCRIPTION:
XS GIS Cut Line= 3
      3602837.49     10665339.43      3603540.61     10664427.98
      3603915.12     10664235.52
#Sta/Elev= 30
  3919.6  324.16  4092.1  316.98  4206.2  310.17  4220.7  308.23  4241.5  308.51
  4256.0  305.95  4291.3  303.27  4370.1  300.51  4461.7  300.65  4498.8  299.58
  4818.5  300.69  4862.0  299.32  4882.8  300.79  4976.1  300.85  5001.8  298.51
  5004.5  298.01  5007.8  298.51  5025.9  301.11  5061.3  301.33  5152.8  306.19
  5266.3  312.95  5292.2  314.67  5297.9  313.99  5305.7  315.35  5336.6  317.20
  5342.2  316.25  5358.8  317.57  5364.4  316.93  5431.0  318.59  5491.8  322.39
#Mann=6,-1,0
  3919.6    0.05       0  5001.8    0.03       0  5007.8    0.05       0
  5025.9    0.16       0  5152.8    0.12       0  5266.3    0.16       0
Bank Sta=5001.8,5007.8
Exp/Cntr=0.3,0.1

Type RM Length L Ch R = 1,2083,1053,1053,1053
BEGIN DESCRIPTION:
UNT236 IN CCTC 2.0
END DESCRIPTION:
XS GIS Cut Line= 3
      3602962.44     10665506.12      3603868.73     10665099.85
      3603873.94     10664459.26
#Sta/Elev= 30
  4091.6  326.12  4231.0  317.48  4290.3  310.84  4319.0  305.74  4327.7  306.77
  4351.5  310.23  4383.1  311.10  4406.3  309.90  4411.7  306.84  4434.9  304.63
  4438.1  302.88  4450.1  301.43  4458.1  304.90  4472.1  307.63  4500.2  306.49
  4509.9  304.34  4515.9  300.89  4658.8  297.99  4833.7  295.17  4920.5  296.22
  4998.0  294.69  5000.7  294.19  5004.0  294.69  5104.4  296.24  5184.5  295.65
  5234.5  297.31  5514.5  297.96  5544.5  299.09  5609.0  304.74  5725.4  315.98
#Mann=8,-1,0
  4091.6    0.05       0  4327.7    0.08       0  4438.1    0.15       0
  4500.2    0.08       0  4658.8    0.05       0  4998.0    0.03       0
  5004.0    0.05       0  5609.0    0.16       0
Bank Sta=4998,5004
Exp/Cntr=0.3,0.1

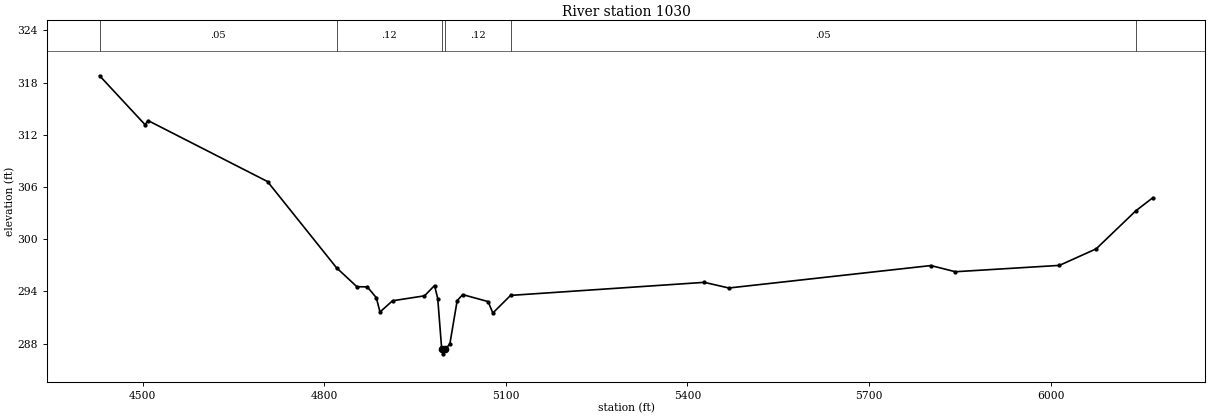
Type RM Length L Ch R = 1,1030,0,0,0
BEGIN DESCRIPTION:
UNT236 IN CCTC 1.0
END DESCRIPTION:
XS GIS Cut Line= 4
      3603582.31     10665834.23      3604004.15     10665839.44
      3604097.90     10665547.77      3603946.85     10664547.75
#Sta/Elev= 30
  4429.1  318.79  4504.1  313.17  4509.1  313.64  4706.4  306.63  4820.5  296.71
  4854.0  294.54  4871.2  294.52  4886.1  293.28  4892.2  291.63  4912.9  292.92
  4965.7  293.49  4982.3  294.67  4987.6  293.18  4994.2  287.32  4997.0  286.82
  5000.2  287.32  5007.7  288.00  5019.7  292.94  5028.8  293.63  5070.8  292.83
  5078.6  291.51  5107.9  293.54  5428.0  295.04  5468.4  294.39  5802.2  296.97
  5842.6  296.26  6014.5  296.99  6075.2  298.89  6140.8  303.27  6168.7  304.76
#Mann=6,-1,0
  4429.1    0.05       0  4820.5    0.12       0  4994.2    0.07       0
  5000.2    0.12       0  5107.9    0.05       0  6140.8    0.12       0
Bank Sta=4994.2,5000.2
Exp/Cntr=0.3,0.1

Chan Stop Cuts=-1