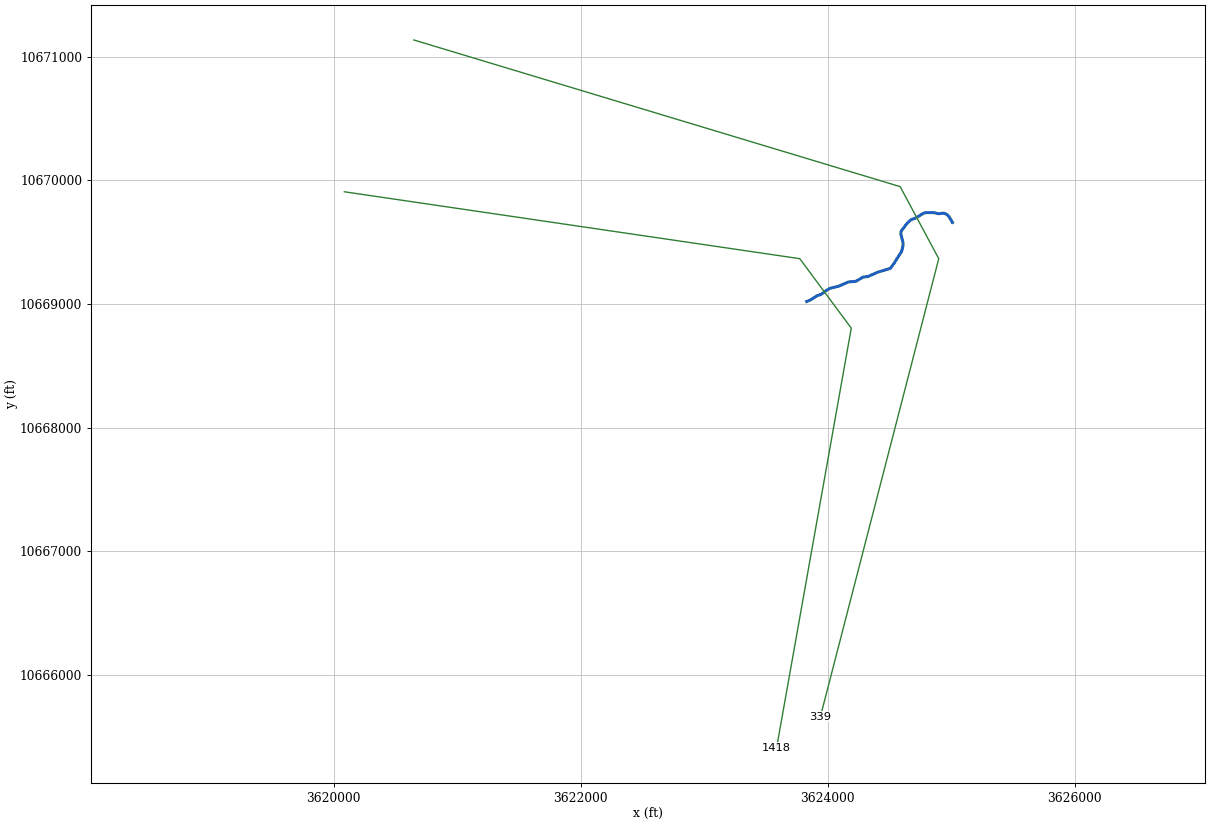
--- UNT237 IN CCTC.prj (project) ---

Proj Title=UNT237 IN CCTC Base Level Engineering
Current Plan=p01
Default Exp/Contr=0.3,0.1
English Units
Geom File=g01
Flow File=f01
Plan File=p01
BEGIN DESCRIPTION:
UNT237 IN CCTC
END DESCRIPTION:

--- UNT237 IN CCTC.p01 (plan) ---

Plan Title=Multiple Run
Short Identifier=Multiple
Geom File=g01
Flow File=f01
Subcritical Flow
K Sum by GR= 0
Std Step Tol= 0.01
Critical Tol= 0.01
Num of Std Step Trials= 20
Max Error Tol= 0.3
Flow Tol Ratio= 0.001
Split Flow NTrial= 30
Split Flow Tol= 0.02
Split Flow Ratio= 0.02
Log Output Level= 0
Friction Slope Method= 1
Unsteady Friction Slope Method= 2
Unsteady Bridges Friction Slope Method= 1
Parabolic Critical Depth
Global Vel Dist=  1 , 1 , 1
Global Log Level= 0
CheckData=True
Encroach Param= -1, 0, 0, 0
BEGIN DESCRIPTION:
Multiple Run
END DESCRIPTION:

--- UNT237 IN CCTC.f01 (steady flow) ---

Flow Title=Multiple
Number of Profiles=7
Profile Names=10-year,25-year,50-year,1pct_min,100-year,1pct_plu,500-year
River Rch & RM= UNT237 IN CCTC,Reach-1,1418
    1848    2399    2821    1926    3264    4603    4325
Boundary for River Rch & Prof#=UNT237 IN CCTC,Reach-1,1
Up Type=0
Dn Type=3
Dn Slope=0.005
Boundary for River Rch & Prof#=UNT237 IN CCTC,Reach-1,2
Up Type=0
Dn Type=3
Dn Slope=0.005
Boundary for River Rch & Prof#=UNT237 IN CCTC,Reach-1,3
Up Type=0
Dn Type=3
Dn Slope=0.005
Boundary for River Rch & Prof#=UNT237 IN CCTC,Reach-1,4
Up Type=0
Dn Type=3
Dn Slope=0.005
Boundary for River Rch & Prof#=UNT237 IN CCTC,Reach-1,5
Up Type=0
Dn Type=3
Dn Slope=0.005
Boundary for River Rch & Prof#=UNT237 IN CCTC,Reach-1,6
Up Type=0
Dn Type=3
Dn Slope=0.005
Boundary for River Rch & Prof#=UNT237 IN CCTC,Reach-1,7
Up Type=0
Dn Type=3
Dn Slope=0.005

--- UNT237 IN CCTC.g01 (geometry) ---

Geom Title=Existing Conditions

River Reach=UNT237 IN CCTC,Reach-1
Reach XY= 30
      3623828.75     10669020.00      3623861.00     10669033.00
      3623911.25     10669066.00      3623949.50     10669080.00
      3623993.25     10669113.00      3624020.75     10669128.00
      3624088.00     10669144.00      3624165.25     10669178.00
      3624228.00     10669184.00      3624285.75     10669218.00
      3624323.75     10669222.00      3624405.50     10669258.00
      3624505.50     10669288.00      3624532.50     10669323.00
      3624597.75     10669426.00      3624608.00     10669466.00
      3624609.75     10669495.00      3624591.25     10669566.00
      3624593.25     10669589.00      3624643.00     10669654.00
      3624673.50     10669682.00      3624715.75     10669698.00
      3624776.75     10669736.00      3624794.75     10669740.00
      3624854.25     10669740.00      3624897.75     10669731.00
      3624939.00     10669736.00      3624962.50     10669726.00
      3624979.00     10669711.00      3625009.50     10669660.00

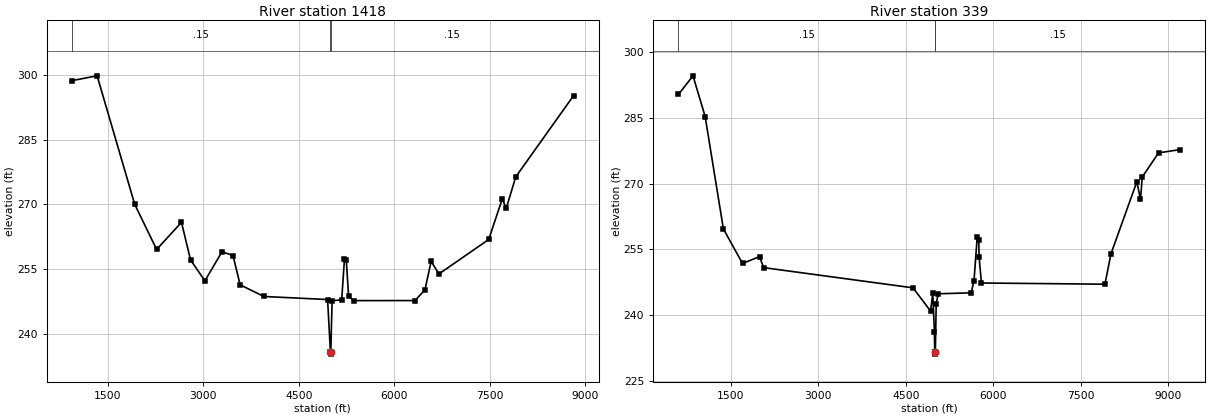
Type RM Length L Ch R = 1,1418,1079,1079,1079
BEGIN DESCRIPTION:
UNT237 IN CCTC 2.0
END DESCRIPTION:
XS GIS Cut Line= 4
      3620085.82     10669908.65      3623773.35     10669366.98
      3624190.01     10668804.48      3623585.84     10665408.62
#Sta/Elev= 30
   937.7  298.69  1335.7  299.81  1925.9  270.00  2269.7  259.54  2659.8  265.84
  2801.3  257.14  3027.2  252.27  3296.2  259.02  3468.4  258.14  3580.4  251.34
  3953.5  248.64  4952.9  247.93  4997.0  235.77  4999.8  235.27  5003.0  235.77
  5023.8  247.65  5174.1  247.86  5218.0  257.40  5245.7  257.19  5282.7  248.67
  5364.4  247.68  6323.9  247.69  6480.9  250.19  6577.9  256.79  6699.7  253.86
  7481.8  261.86  7695.1  271.31  7756.1  269.05  7905.5  276.37  8814.0  295.23
#Mann=3,-1,0
   937.7    0.15       0  4997.0    0.05       0  5003.0    0.15       0
Bank Sta=4997,5003
Exp/Cntr=0.3,0.1

Type RM Length L Ch R = 1,339,0,0,0
BEGIN DESCRIPTION:
UNT237 IN CCTC 1.0
END DESCRIPTION:
XS GIS Cut Line= 4
      3620648.37     10671137.81      3624585.85     10669950.31
      3624898.35     10669366.98      3623940.01     10665658.62
#Sta/Elev= 30
   604.1  290.29   853.2  294.51  1061.6  285.25  1374.1  259.67  1702.1  251.80
  1993.9  253.35  2065.1  250.85  4626.0  246.25  4926.3  240.96  4964.5  244.98
  4992.1  236.30  4997.0  231.66  4999.8  231.16  5003.0  231.66  5008.4  231.66
  5023.2  242.68  5057.9  244.90  5623.1  245.11  5671.4  247.90  5726.4  257.84
  5752.7  257.06  5757.8  253.36  5798.7  247.35  7916.3  247.08  8019.3  253.97
  8463.4  270.40  8525.4  266.37  8556.4  271.49  8835.5  276.97  9208.7  277.73
#Mann=3,-1,0
   604.1    0.15       0  4997.0    0.05       0  5003.0    0.15       0
Bank Sta=4997,5003
Exp/Cntr=0.3,0.1

Chan Stop Cuts=-1