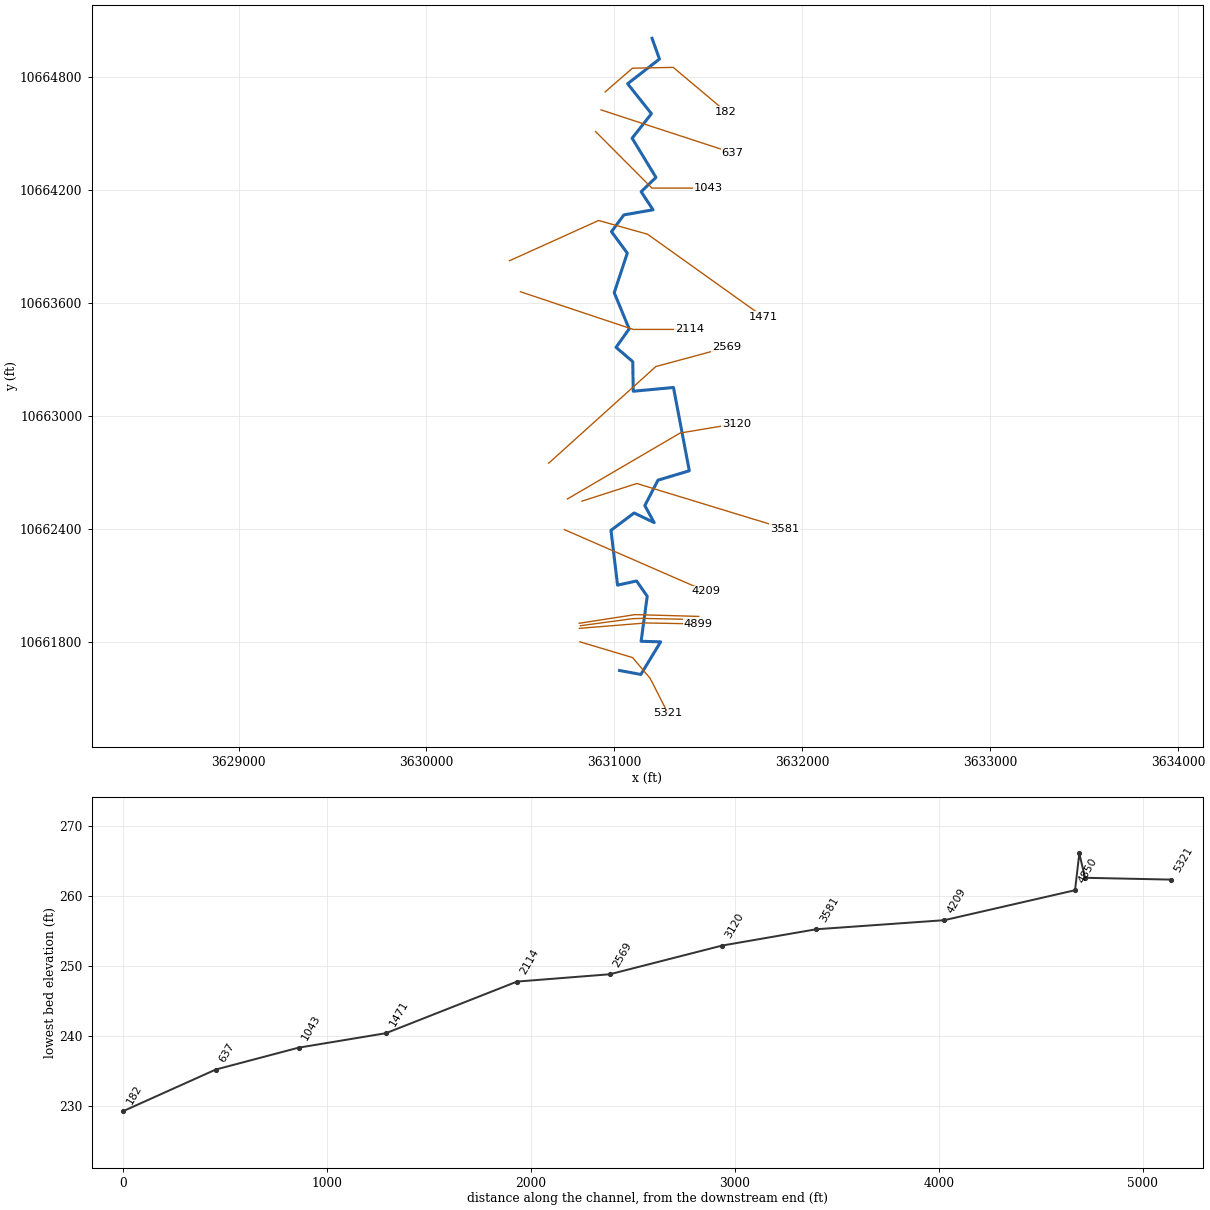
--- UNT239 IN CCTC.prj (project) ---

Proj Title=UNT239 IN CCTC Base Level Engineering
Current Plan=p01
Default Exp/Contr=0.3,0.1
English Units
Geom File=g01
Flow File=f01
Plan File=p01
Y Axis Title=Elevation
X Axis Title(PF)=Main Channel Distance
X Axis Title(XS)=Station
BEGIN DESCRIPTION:
UNT239 IN CCTC
END DESCRIPTION:
DSS Export Rating Curves= 0
DSS Export Rating Curve Sorted= 0
DSS Export Volume Flow Curves= 0
DXF OffsetX= 0
DXF OffsetY= 0
DXF ScaleX= 1
DXF ScaleY= 10

--- UNT239 IN CCTC.p01 (plan) ---

Plan Title=Multiple Run
Short Identifier=Multiple
Geom File=g01
Flow File=f01
Subcritical Flow
K Sum by GR= 0
Std Step Tol= 0.01
Critical Tol= 0.01
Num of Std Step Trials= 20
Max Error Tol= 0.3
Flow Tol Ratio= 0.001
Split Flow NTrial= 30
Split Flow Tol= 0.02
Split Flow Ratio= 0.02
Log Output Level= 0
Friction Slope Method= 1
Unsteady Friction Slope Method= 2
Unsteady Bridges Friction Slope Method= 1
Parabolic Critical Depth
Global Vel Dist=  1 , 1 , 1
Global Log Level= 0
CheckData=True
Encroach Param= -1, 0, 0, 0
BEGIN DESCRIPTION:
Multiple Run
END DESCRIPTION:

--- UNT239 IN CCTC.f01 (steady flow) ---

Flow Title=Multiple
Number of Profiles=7
Profile Names=10-year,25-year,50-year,1pct_min,100-year,1pct_plu,500-year
River Rch & RM= UNT239 IN CCTC,Reach-1,5321
     943    1260    1514    1329    1798    2431    2523
Boundary for River Rch & Prof#=UNT239 IN CCTC,Reach-1,1
Up Type=0
Dn Type=3
Dn Slope=0.005
Boundary for River Rch & Prof#=UNT239 IN CCTC,Reach-1,2
Up Type=0
Dn Type=3
Dn Slope=0.005
Boundary for River Rch & Prof#=UNT239 IN CCTC,Reach-1,3
Up Type=0
Dn Type=3
Dn Slope=0.005
Boundary for River Rch & Prof#=UNT239 IN CCTC,Reach-1,4
Up Type=0
Dn Type=3
Dn Slope=0.005
Boundary for River Rch & Prof#=UNT239 IN CCTC,Reach-1,5
Up Type=0
Dn Type=3
Dn Slope=0.005
Boundary for River Rch & Prof#=UNT239 IN CCTC,Reach-1,6
Up Type=0
Dn Type=3
Dn Slope=0.005
Boundary for River Rch & Prof#=UNT239 IN CCTC,Reach-1,7
Up Type=0
Dn Type=3
Dn Slope=0.005

--- UNT239 IN CCTC.g01 (geometry) ---

Geom Title=Existing Conditions
Program Version=4.10

River Reach=UNT239 IN CCTC  ,Reach-1
Reach XY= 30
      3631027.25       10661650.      3631140.75       10661629.
        3631246.       10661802.        3631142.       10661805.
       3631174.5       10662044.        3631118.       10662125.
      3631016.75       10662103.      3630981.75       10662394.
       3631104.5       10662486.       3631211.5       10662435.
      3631161.75       10662525.      3631231.75       10662660.
       3631398.5       10662710.      3631314.25       10663152.
      3631100.25       10663132.       3631097.5       10663289.
      3631008.75       10663365.       3631078.5       10663463.
        3630999.       10663655.       3631068.5       10663865.
      3630984.25       10663979.       3631050.5       10664068.
       3631205.5       10664095.      3631142.25       10664191.
        3631221.       10664267.      3631094.25       10664475.
        3631197.       10664605.      3631070.25       10664764.
      3631239.75       10664895.      3631200.25       10665005.

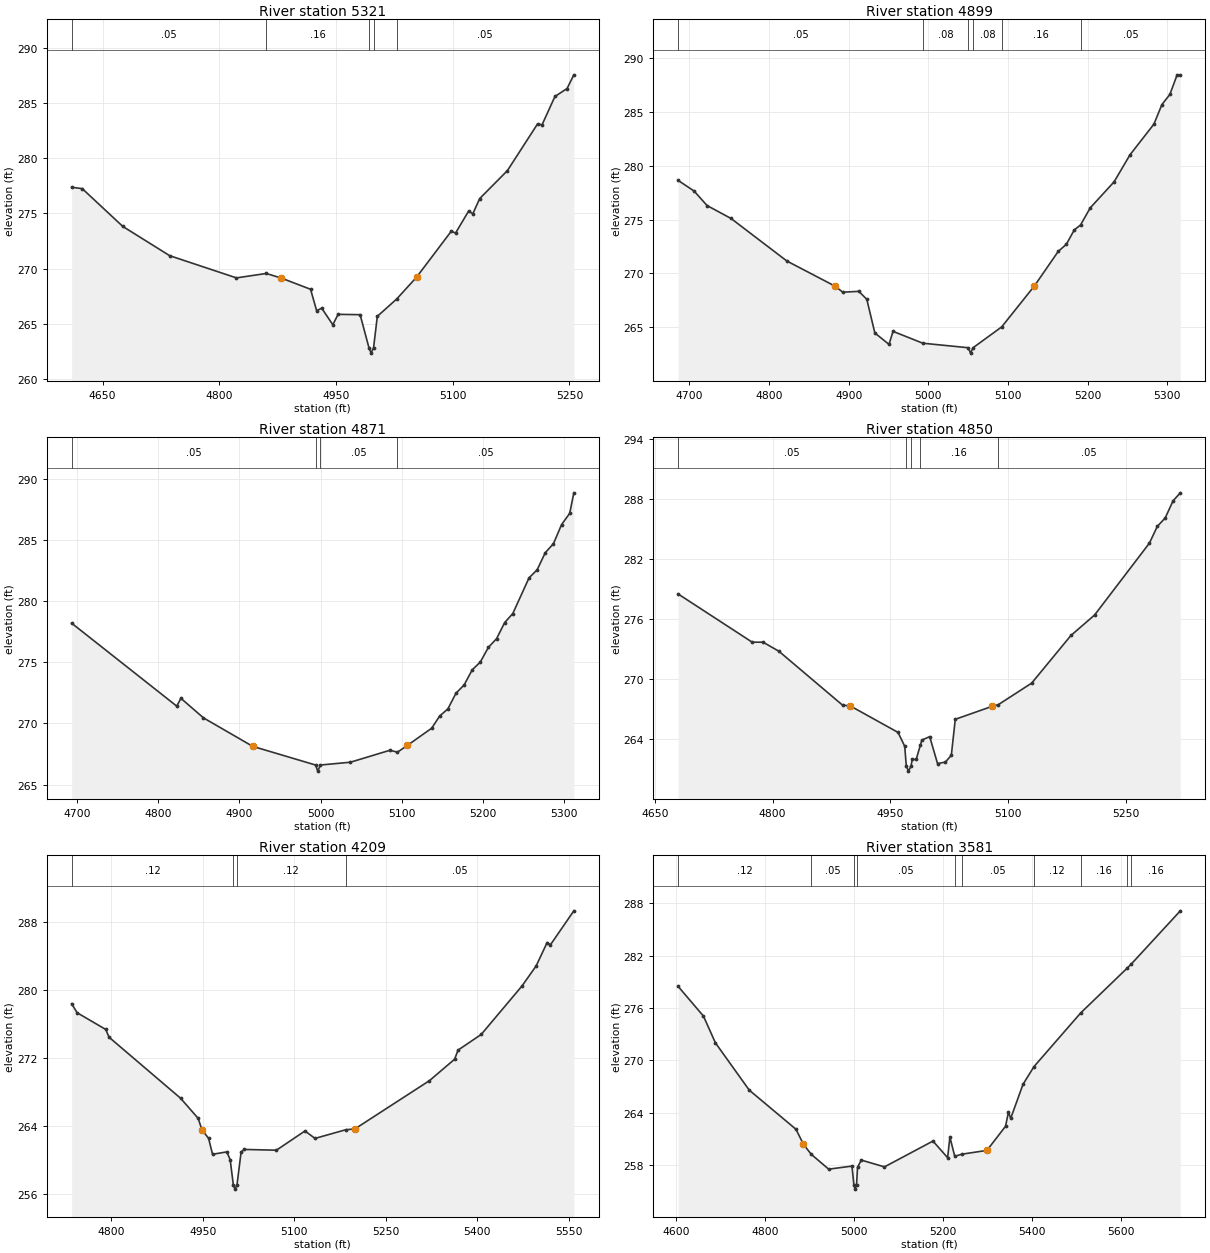
Type RM Length L Ch R = 1 ,5321    ,422,422,422
BEGIN DESCRIPTION:
UNT239 IN CCTC 10.0
END DESCRIPTION:
XS GIS Cut Line= 4
      3630816.61     10661801.98      3631096.54     10661718.65
      3631190.29     10661607.97      3631285.12     10661422.41
#Sta/Elev= 30
  4610.2  277.36  4623.8  277.24  4675.9  273.82  4736.2  271.17    4822  269.16
  4860.3  269.56  4879.4  269.15  4917.3  268.13  4925.1  266.19  4931.6  266.42
  4945.9  264.92  4952.7  265.86    4981  265.83  4992.3  262.85  4995.1  262.35
  4998.3  262.85  5003.1  265.68    5028  267.25  5053.6  269.23  5098.1  273.38
  5103.7  273.22  5120.3  275.19  5125.9  274.97  5134.7  276.34  5170.3  278.87
  5209.1   283.1  5214.8  283.01  5231.4  285.58    5247   286.3  5255.7  287.54
#Mann= 5 ,-1 , 0
  4610.2     .05       0  4860.3     .16       0  4992.3     .07       0
  4998.3     .16       0    5028     .05       0
Bank Sta=4879.4,5053.6
XS Rating Curve= 0 ,0
Exp/Cntr=0.3,0.1

Type RM Length L Ch R = 1 ,4899    ,28,28,28
BEGIN DESCRIPTION:
UNT239 IN CCTC 9.0
END DESCRIPTION:
XS GIS Cut Line= 3
      3630813.44     10661873.67      3631168.48     10661902.32
      3631442.73     10661897.11
#Sta/Elev= 30
  4685.8  278.63  4705.9  277.64  4722.1   276.3  4752.2   275.1  4822.4  271.15
  4882.6  268.83  4892.6  268.26  4912.7  268.34  4922.7   267.6  4932.8  264.48
  4950.6  263.42  4955.6  264.63    4993  263.53  5050.1  263.11  5052.9  262.61
  5056.1  263.11    5092  265.04  5133.1  268.84  5163.1  272.05  5173.2   272.7
  5183.2  274.04    5191  274.49  5203.2  276.08  5233.2   278.5  5253.2  281.01
  5283.2  283.85  5293.2  285.66  5303.2   286.6  5312.3  288.42  5316.3  288.42
#Mann= 6 ,-1 , 0
  4685.8     .05       0    4993     .08       0  5050.1     .07       0
  5056.1     .08       0    5092     .16       0    5191     .05       0
Bank Sta=4882.6,5133.1
XS Rating Curve= 0 ,0
Exp/Cntr=0.3,0.1

Type RM Length L Ch R = 1 ,4871    ,21,21,21
BEGIN DESCRIPTION:
Mapping XS 80d8ab09
END DESCRIPTION:
XS GIS Cut Line= 4
      3630818.65     10661887.56      3631095.56     10661924.88
       3631143.3     10661926.62      3631434.75     10661920.55
#Sta/Elev= 30
  4693.3  278.21  4822.8  271.42  4827.9  272.06  4855.7  270.46  4916.3  268.13
  4993.8   266.6  4996.5   266.1  4999.8   266.6  5036.8  266.83  5085.5  267.81
  5094.7  267.65  5106.8   268.2  5136.8  269.61  5146.8  270.62  5156.8  271.19
  5166.8  272.48  5176.8  273.15  5186.8  274.39  5196.8  275.03  5206.8  276.24
  5216.8  276.94  5226.8  278.26  5236.8     279  5256.8  281.92  5266.8  282.58
  5276.8  283.98  5286.9  284.72  5296.9  286.28  5306.9   287.2    5312  288.88
#Mann= 4 ,-1 , 0
  4693.3     .05       0  4993.8     .07       0  4999.8     .05       0
  5094.7     .05       0
Bank Sta=4916.3,5106.8
XS Rating Curve= 0 ,0
Exp/Cntr=0.3,0.1

Type RM Length L Ch R = 1 ,4850    ,641,641,641
BEGIN DESCRIPTION:
Mapping XS 28be823e
END DESCRIPTION:
XS GIS Cut Line= 3
      3630812.57     10661900.58      3631110.32     10661946.59
       3631448.9     10661937.04
#Sta/Elev= 30
  4679.7  278.54  4774.1  273.72    4788  273.72  4808.2  272.81  4889.2  267.43
  4899.3  267.34    4960   264.7  4968.5  263.31  4970.5  261.33  4973.3  260.83
  4976.5  261.33  4978.1     262  4983.1     262  4988.4  263.42  4990.3  263.93
  5000.3  264.28  5010.3  261.59  5020.3  261.73  5027.9  262.42  5032.9  266.01
  5080.3  267.32  5087.5  267.46  5130.3  269.63  5180.3  274.39  5210.4  276.43
  5280.4  283.63  5290.4   285.3  5300.4  286.13  5310.4  287.84  5319.7  288.65
#Mann= 5 ,-1 , 0
  4679.7     .05       0  4970.5     .07       0  4976.5     .05       0
  4988.4     .16       0  5087.5     .05       0
Bank Sta=4899.3,5080.3
XS Rating Curve= 0 ,0
Exp/Cntr=0.3,0.1

Type RM Length L Ch R = 1 ,4209    ,628,628,628
BEGIN DESCRIPTION:
UNT239 IN CCTC 8.0
END DESCRIPTION:
XS GIS Cut Line= 2
       3630733.7     10662397.65       3631488.9     10662069.53
#Sta/Elev= 30
  4735.1  278.41  4744.1  277.34    4791  275.37  4796.5  274.45  4913.7  267.26
  4942.6  264.88  4948.7  263.53  4959.6  262.53  4966.1  260.65  4989.5  260.93
    4995  260.02  5000.2  257.04    5003  256.54  5006.2  257.04    5013  260.93
  5018.4  261.22  5070.8  261.13  5117.7   263.4  5134.1  262.52  5184.3  263.54
  5199.5  263.64  5321.7  269.33    5363  271.86  5368.6  272.93  5406.6  274.78
  5473.3  280.48  5496.7  282.86  5514.7  285.62  5520.2  285.36  5558.5  289.36
#Mann= 4 ,-1 , 0
  4735.1     .12       0  5000.2     .07       0  5006.2     .12       0
  5184.3     .05       0
Bank Sta=4948.7,5199.5
XS Rating Curve= 0 ,0
Exp/Cntr=0.3,0.1

Type RM Length L Ch R = 1 ,3581    ,461,461,461
BEGIN DESCRIPTION:
UNT239 IN CCTC 7.0
END DESCRIPTION:
XS GIS Cut Line= 3
      3630827.47     10662548.71       3631119.1     10662642.45
      3631905.11       10662403.
#Sta/Elev= 30
  4605.3  278.49  4662.2  275.08  4689.1  272.01  4765.1  266.59  4870.1   262.1
  4886.9  260.37  4904.4  259.23  4943.5  257.53  4995.8  257.88  5000.1  255.74
  5002.8  255.24  5006.1  255.74  5008.3  257.74  5016.7  258.57  5068.8  257.79
  5177.7  260.75  5210.6  258.85  5215.8   261.2  5226.6  259.01  5243.1  259.25
  5298.9  259.68  5340.8  262.45  5347.2  264.07  5352.4  263.36    5380  267.26
  5404.8   269.3  5509.5  275.44  5614.2  280.59  5622.5  281.01  5733.3  287.15
#Mann= 10 ,-1 , 0
  4605.3     .12       0  4904.4     .05       0  5000.1     .03       0
  5006.1     .05       0  5226.6     .16       0  5243.1     .05       0
  5404.8     .12       0  5509.5     .16       0  5614.2     .12       0
  5622.5     .16       0
Bank Sta=4886.9,5298.9
XS Rating Curve= 0 ,0
Exp/Cntr=0.3,0.1

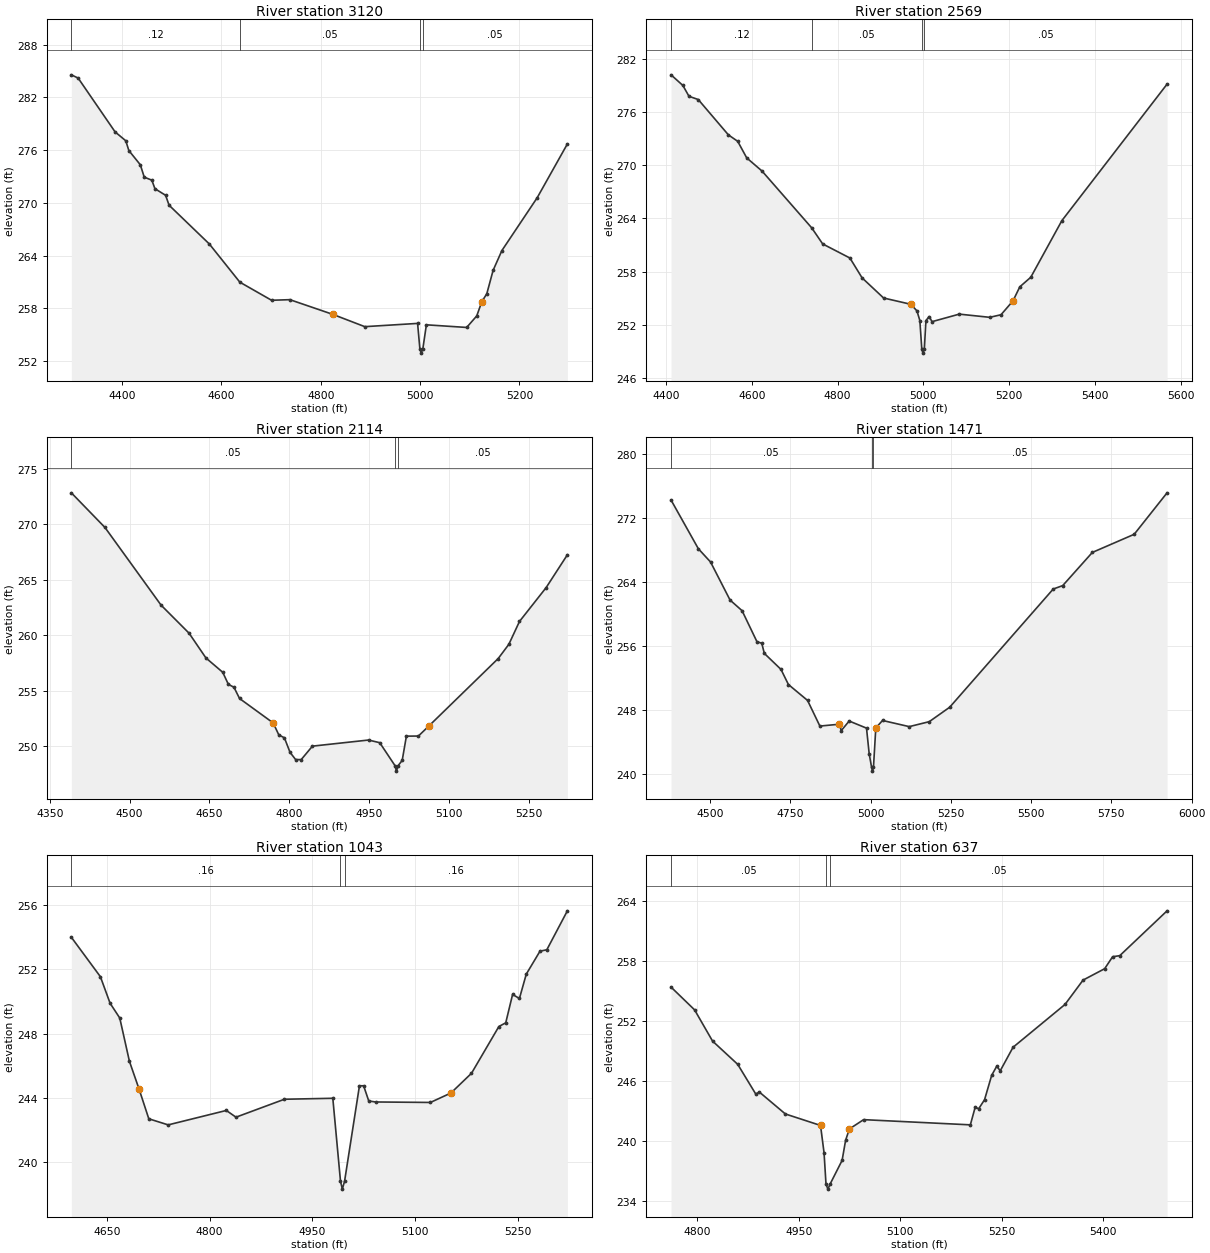
Type RM Length L Ch R = 1 ,3120    ,551,551,551
BEGIN DESCRIPTION:
UNT239 IN CCTC 6.0
END DESCRIPTION:
XS GIS Cut Line= 3
      3630749.59     10662560.18      3631349.61     10662910.19
      3631649.62     10662960.19
#Sta/Elev= 30
  4297.7  284.56  4311.4  284.19  4385.8  278.07  4407.3  277.06  4413.5  275.95
  4436.6  274.33  4444.5  272.92  4459.8  272.58    4466  271.61  4487.5  270.86
  4494.5  269.73  4575.6  265.32    4637  260.98  4700.9  258.92  4737.7  258.99
  4824.1  257.32  4888.6  255.92  4994.9  256.29  4999.5  253.41  5002.2  252.91
  5005.5  253.41  5012.6  256.13  5093.7  255.83    5114  257.14  5124.1  258.74
  5134.3  259.67    5147  262.33  5164.7  264.58  5235.7  270.58  5296.5   276.7
#Mann= 4 ,-1 , 0
  4297.7     .12       0    4637     .05       0  4999.5     .03       0
  5005.5     .05       0
Bank Sta=4824.1,5124.1
XS Rating Curve= 0 ,0
Exp/Cntr=0.3,0.1

Type RM Length L Ch R = 1 ,2569    ,455,455,455
BEGIN DESCRIPTION:
UNT239 IN CCTC 5.0
END DESCRIPTION:
XS GIS Cut Line= 3
      3630650.26     10662750.16      3631220.56     10663263.17
      3631596.42     10663364.26
#Sta/Elev= 30
  4411.9   280.2  4439.5     279  4453.7  277.78  4475.4  277.41  4545.7  273.42
  4567.3   272.7  4588.3  270.83  4624.1  269.34  4739.9  262.93  4765.4  261.12
  4828.9  259.53  4857.3  257.29  4907.4  255.02  4970.9  254.31  4985.1  253.57
  4991.9  252.48  4996.4   249.3  4999.1   248.8  5002.4   249.3  5006.1  252.47
  5013.6  252.93  5020.3  252.35  5083.8   253.2  5154.8  252.84  5181.1  253.13
  5209.1   254.7  5224.9  256.28  5250.5  257.36    5323  263.75  5568.2  279.15
#Mann= 4 ,-1 , 0
  4411.9     .12       0  4739.9     .05       0  4996.4     .03       0
  5002.4     .05       0
Bank Sta=4970.9,5209.1
XS Rating Curve= 0 ,0
Exp/Cntr=0.3,0.1

Type RM Length L Ch R = 1 ,2114    ,643,643,643
BEGIN DESCRIPTION:
UNT239 IN CCTC 4.0
END DESCRIPTION:
XS GIS Cut Line= 3
      3630499.64     10663660.18      3631099.61     10663460.19
      3631399.58     10663460.19
#Sta/Elev= 30
  4390.6  272.81  4453.8  269.69  4559.2   262.7  4611.9  260.17  4643.6  257.94
  4675.2  256.65  4685.7  255.57  4696.3   255.3  4706.8  254.29    4770  252.09
  4780.6  251.01  4791.1  250.75  4801.7  249.44  4812.2  248.79  4822.7  248.79
  4843.8     250  4949.2  250.55  4970.3  250.31  4998.9  248.25  5001.7  247.75
  5004.9  248.25  5012.5  248.71  5020.4   250.9    5043  250.91    5063  251.83
    5193  257.89    5213  259.17    5233  261.23    5283  264.27    5323  267.23
#Mann= 3 ,-1 , 0
  4390.6     .05       0  4998.9     .03       0  5004.9     .05       0
Bank Sta=4770,5063
XS Rating Curve= 0 ,0
Exp/Cntr=0.3,0.1

Type RM Length L Ch R = 1 ,1471    ,428,428,428
BEGIN DESCRIPTION:
UNT239 IN CCTC 3.0
END DESCRIPTION:
XS GIS Cut Line= 4
      3630442.04     10663824.75      3630915.97     10664038.28
      3631176.39     10663965.36      3631790.94     10663527.89
#Sta/Elev= 30
  4378.8  274.29  4463.9  268.19  4501.9  266.53  4562.6  261.77    4600  260.44
  4646.2  256.57  4661.3  256.36  4669.4  255.09  4721.2  253.09  4744.3   251.2
  4803.9  249.21  4842.3     246  4903.1  246.23  4908.8  245.43  4933.5  246.63
  4987.5  245.74  4995.8  242.54  5003.2  240.86    5006  240.36  5009.2  240.86
  5016.4  245.76  5037.4   246.7  5120.5  245.93  5182.9  246.55  5246.6  248.36
  5568.9  263.15  5598.5  263.58  5690.7  267.73    5821     270  5923.4  275.19
#Mann= 3 ,-1 , 0
  4378.8     .05       0  5003.2     .03       0  5009.2     .05       0
Bank Sta=4903.1,5016.4
XS Rating Curve= 0 ,0
Exp/Cntr=0.3,0.1

Type RM Length L Ch R = 1 ,1043    ,406,406,406
BEGIN DESCRIPTION:
UNT239 IN CCTC 2.0
END DESCRIPTION:
XS GIS Cut Line= 3
      3630899.61     10664510.19      3631199.61     10664210.19
      3631499.65     10664210.19
#Sta/Elev= 30
  4598.2  254.01  4640.6  251.55  4654.8  249.89  4668.9  248.97    4683  246.27
  4697.2  244.52  4711.3  242.68  4739.6   242.3  4824.5   243.2  4838.6  242.78
  4909.3   243.9    4980  243.96  4991.2  238.79  4993.9  238.29  4997.2  238.79
  5018.9  244.74    5025  244.74  5032.5  243.79  5042.5  243.73  5122.5   243.7
  5152.5  244.29  5182.5  245.52  5222.5  248.44  5232.5  248.67  5242.5  250.44
  5252.5  250.19  5262.5  251.71  5282.5  253.14  5292.5  253.23  5322.5  255.66
#Mann= 3 ,-1 , 0
  4598.2     .16       0  4991.2     .03       0  4997.2     .16       0
Bank Sta=4697.2,5152.5
XS Rating Curve= 0 ,0
Exp/Cntr=0.3,0.1

Type RM Length L Ch R = 1 ,637     ,455,455,455
BEGIN DESCRIPTION:
Mapping XS 5b3fc5b4
END DESCRIPTION:
XS GIS Cut Line= 2
      3630928.94     10664625.13      3631626.11     10664397.79
#Sta/Elev= 30
  4760.9   255.4  4795.7  253.12  4822.3  249.99  4859.5  247.66  4886.2  244.68
  4891.4  244.89  4929.9  242.69  4981.9  241.54  4987.1  238.81    4990  235.66
  4992.8  235.16    4996  235.66  5013.8  238.04    5019  240.06  5024.6  241.19
  5045.6  242.12  5203.4   241.6  5210.5  243.36  5215.7  243.21  5224.4  244.12
  5234.9  246.56  5242.4  247.47  5247.6  247.02  5266.5  249.37  5343.3  253.66
    5370   256.1  5401.9  257.24  5413.7  258.44  5424.3  258.55  5494.2  263.04
#Mann= 3 ,-1 , 0
  4760.9     .05       0    4990     .03       0    4996     .05       0
Bank Sta=4981.9,5024.6
XS Rating Curve= 0 ,0
Exp/Cntr=0.3,0.1

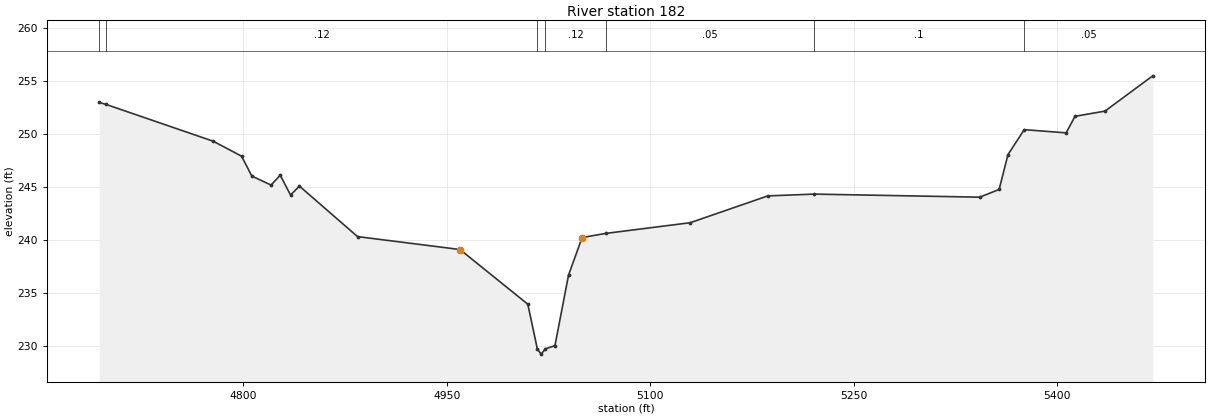
Type RM Length L Ch R = 1 ,182     ,0,0,0
BEGIN DESCRIPTION:
UNT239 IN CCTC 1.0
END DESCRIPTION:
XS GIS Cut Line= 4
      3630950.61     10664720.65      3631095.99      10664846.5
      3631313.01     10664850.84      3631594.35     10664614.94
#Sta/Elev= 30
  4693.9  252.94    4699  252.75  4777.9  249.28  4798.8  247.87  4806.4  245.99
  4820.6  245.14  4827.3  246.08  4834.9  244.21  4841.5  245.04  4884.3  240.28
  4959.8  239.06  5009.8   233.9  5016.8  229.69  5019.6  229.19  5022.8  229.69
  5029.8  229.99  5039.8  236.64  5049.8  240.19  5067.2  240.58  5129.5  241.59
  5186.7  244.12  5220.8  244.29  5342.9     244  5357.2  244.73  5363.7  248.02
  5375.7  250.37  5406.6  250.07  5413.1  251.63  5435.2  252.12  5470.4  255.45
#Mann= 7 ,-1 , 0
  4693.9     .05       0    4699     .12       0  5016.8     .07       0
  5022.8     .12       0  5067.2     .05       0  5220.8      .1       0
  5375.7     .05       0
Bank Sta=4959.8,5049.8
XS Rating Curve= 0 ,0
Exp/Cntr=0.3,0.1

Chan Stop Cuts=-1
Use User Specified Reach Order=0
Composite Channel Slope=5