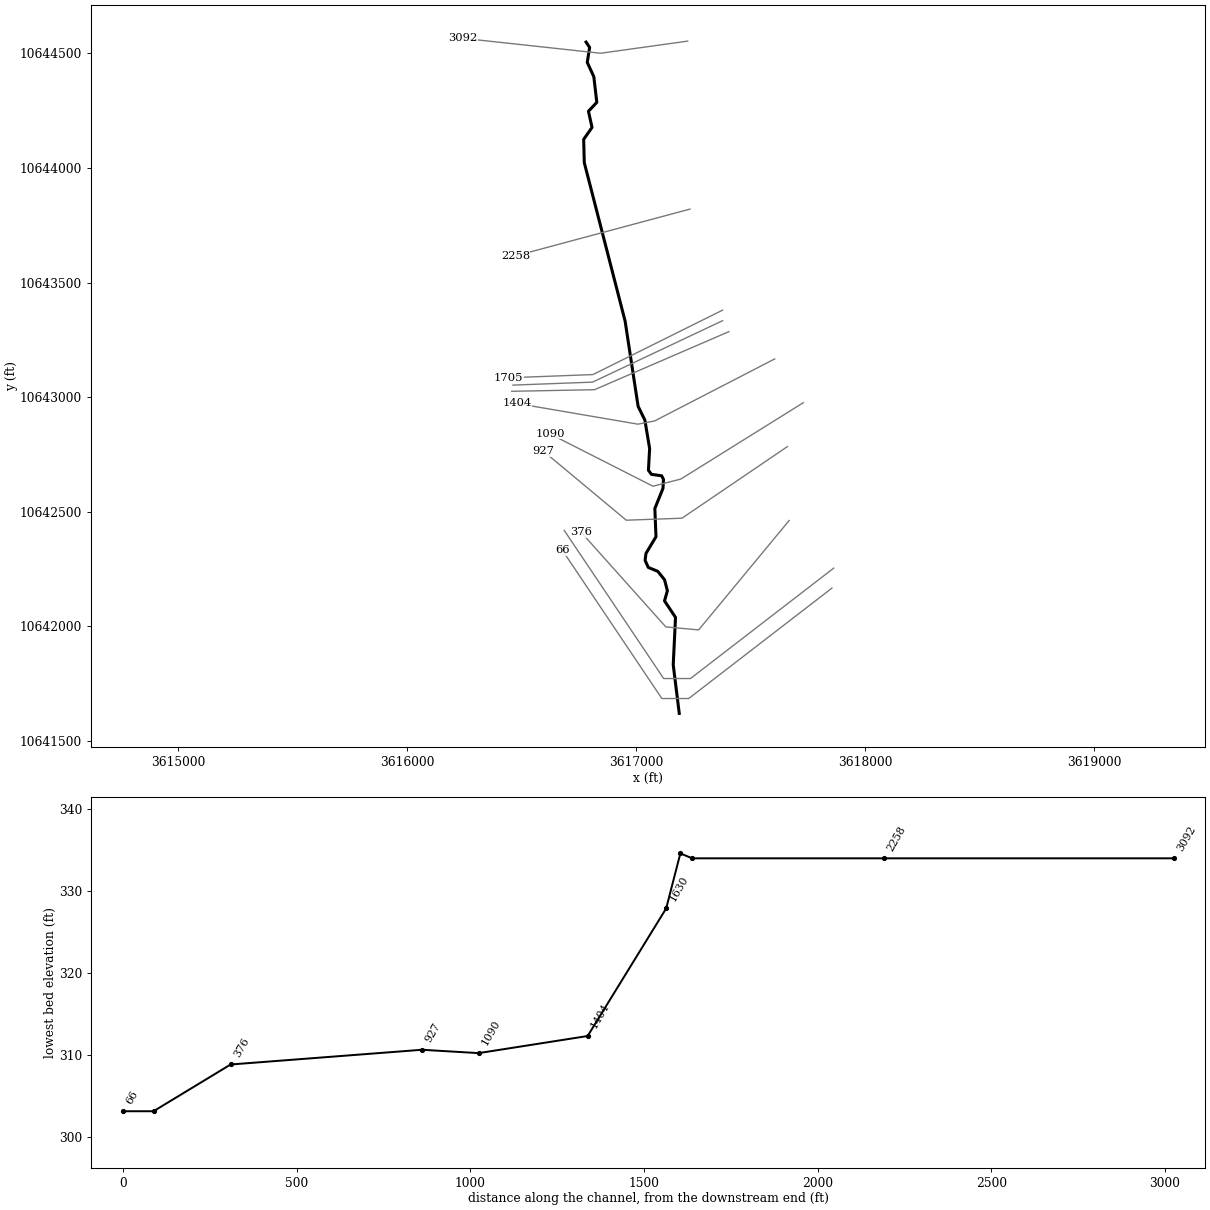
--- UNT245 IN CCTC.prj (project) ---

Proj Title=UNT245 IN CCTC Base Level Engineering
Current Plan=p01
Default Exp/Contr=0.3,0.1
English Units
Geom File=g01
Flow File=f01
Plan File=p01
Y Axis Title=Elevation
X Axis Title(PF)=Main Channel Distance
X Axis Title(XS)=Station
BEGIN DESCRIPTION:
UNT245 IN CCTC
END DESCRIPTION:
DSS Export Rating Curves= 0
DSS Export Rating Curve Sorted= 0
DSS Export Volume Flow Curves= 0
DXF OffsetX= 0
DXF OffsetY= 0
DXF ScaleX= 1
DXF ScaleY= 10

--- UNT245 IN CCTC.p01 (plan) ---

Plan Title=Multiple Run
Short Identifier=Multiple
Geom File=g01
Flow File=f01
Subcritical Flow
K Sum by GR= 0
Std Step Tol= 0.01
Critical Tol= 0.01
Num of Std Step Trials= 20
Max Error Tol= 0.3
Flow Tol Ratio= 0.001
Split Flow NTrial= 30
Split Flow Tol= 0.02
Split Flow Ratio= 0.02
Log Output Level= 0
Friction Slope Method= 1
Unsteady Friction Slope Method= 2
Unsteady Bridges Friction Slope Method= 1
Parabolic Critical Depth
Global Vel Dist=  1 , 1 , 1
Global Log Level= 0
CheckData=True
Encroach Param= -1, 0, 0, 0
BEGIN DESCRIPTION:
Multiple Run
END DESCRIPTION:

--- UNT245 IN CCTC.f01 (steady flow) ---

Flow Title=Multiple
Program Version=4.10
Number of Profiles= 7
Profile Names=10-year,25-year,50-year,1pct_min,100-year,1pct_plu,500-year
River Rch & RM=UNT245 IN CCTC,Reach-1         ,3092
   338.4  338.59  338.72  338.62  338.87  339.08  339.09
River Rch & RM=UNT245 IN CCTC,Reach-1         ,2258
     615     807     960     837    1131    1530    1562
River Rch & RM=UNT245 IN CCTC,Reach-1         ,66
    2901    4181    5289    4875    6593    8916   10215
Boundary for River Rch & Prof#=UNT245 IN CCTC,Reach-1         , 1
Up Type= 0
Dn Type= 3
Dn Slope=0.005
Boundary for River Rch & Prof#=UNT245 IN CCTC,Reach-1         , 2
Up Type= 0
Dn Type= 3
Dn Slope=0.005
Boundary for River Rch & Prof#=UNT245 IN CCTC,Reach-1         , 3
Up Type= 0
Dn Type= 3
Dn Slope=0.005
Boundary for River Rch & Prof#=UNT245 IN CCTC,Reach-1         , 4
Up Type= 0
Dn Type= 3
Dn Slope=0.005
Boundary for River Rch & Prof#=UNT245 IN CCTC,Reach-1         , 5
Up Type= 0
Dn Type= 3
Dn Slope=0.005
Boundary for River Rch & Prof#=UNT245 IN CCTC,Reach-1         , 6
Up Type= 0
Dn Type= 3
Dn Slope=0.005
Boundary for River Rch & Prof#=UNT245 IN CCTC,Reach-1         , 7
Up Type= 0
Dn Type= 3
Dn Slope=0.005
DSS Import GetInterval= 0
DSS Import GetPeak= 0
DSS Import FillOption= 0

--- UNT245 IN CCTC.g01 (geometry) ---

Geom Title=Existing Conditions
Program Version=4.10

River Reach=UNT245 IN CCTC  ,Reach-1
Reach XY= 30
      3616781.59     10644549.76      3616797.21     10644526.32
      3616786.79     10644461.21      3616815.44     10644398.71
      3616828.46     10644286.74        3616792.     10644247.67
      3616807.63     10644177.36      3616771.17     10644125.28
      3616773.77     10644023.71        3616952.       10643332.
      3617008.75       10642960.      3617038.25       10642900.
        3617059.       10642776.      3617053.75       10642681.
      3617067.25       10642663.       3617111.5       10642657.
       3617119.5       10642641.      3617117.25       10642602.
      3617081.75       10642514.      3617086.75       10642391.
        3617043.       10642318.      3617039.25       10642288.
        3617053.       10642257.       3617094.5       10642240.
      3617124.25       10642203.       3617136.5       10642155.
        3617124.       10642111.        3617172.       10642039.
        3617162.       10641832.      3617188.25       10641620.

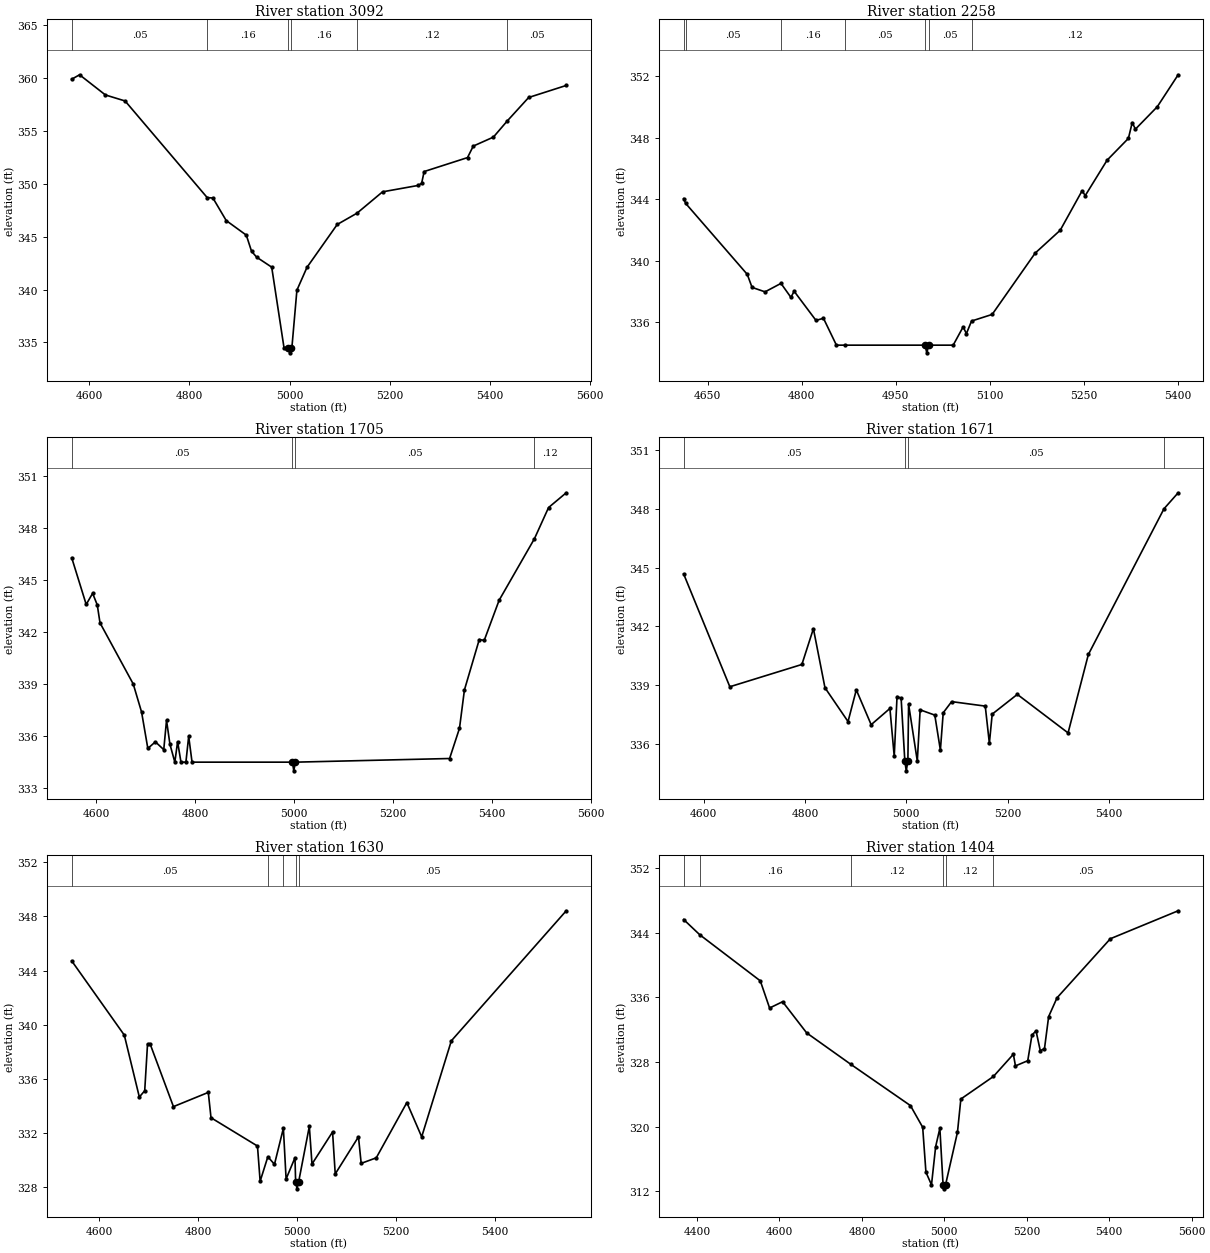
Type RM Length L Ch R = 1 ,3092    ,834,834,834
BEGIN DESCRIPTION:
Mapping XS 9b1546f7
END DESCRIPTION:
XS GIS Cut Line= 3
      3617225.17     10644553.92      3616844.94     10644500.97
      3616245.06     10644566.08
#Sta/Elev= 30
  4564.9  359.91  4580.6  360.33  4632.2  358.42  4671.5  357.85  4835.3  348.71
  4846.9  348.66  4873.4  346.53  4913.5  345.15  4923.9  343.63    4934  343.07
  4964.2  342.12  4988.7  334.51    4997  334.51  4999.8  334.01    5003  334.51
  5004.5  334.51  5014.5  339.94  5034.6   342.1    5095  346.16  5134.5  347.23
  5185.5  349.25  5255.9  349.85  5263.5  350.05  5268.5  351.17  5355.1  352.49
  5366.6  353.58  5406.8  354.43  5434.3  355.95  5477.2  358.18  5552.2  359.32
#Mann= 6 ,-1 , 0
  4564.9     .05       0  4835.3     .16       0    4997     .07       0
    5003     .16       0  5134.5     .12       0  5434.3     .05       0
Bank Sta=4997,5003
XS Rating Curve= 0 ,0
Exp/Cntr=0.3,0.1

Type RM Length L Ch R = 1 ,2258    ,553,553,553
BEGIN DESCRIPTION:
UNT245 IN CCTC 4.0
END DESCRIPTION:
XS GIS Cut Line= 2
      3617235.07     10643820.82       3616472.9     10643616.42
#Sta/Elev= 30
  4611.8  344.05    4615  343.74  4713.3  339.12    4721  338.27  4741.7  337.98
  4767.1  338.53    4783  337.62  4788.1  338.02    4823  336.12  4834.9  336.26
  4855.6  334.51  4868.5  334.51    4997  334.51  4999.8  334.01    5003  334.51
  5041.9  334.51  5057.8   335.7    5063  335.26  5071.2  336.08  5104.1  336.51
  5172.7   340.5  5212.7  341.99  5247.5  344.55  5252.7  344.25  5287.5  346.55
  5321.5  347.97  5327.6     349  5332.7  348.57  5367.6  350.03  5400.9  352.11
#Mann= 7 ,-1 , 0
  4611.8     .12       0    4615     .05       0  4767.1     .16       0
  4868.5     .05       0    4997    .033       0    5003     .05       0
  5071.2     .12       0
Bank Sta=4997,5003
XS Rating Curve= 0 ,0
Exp/Cntr=0.3,0.1

Type RM Length L Ch R = 1 ,1705    ,34,34,34
BEGIN DESCRIPTION:
UNT245 IN CCTC 3.0
END DESCRIPTION:
XS GIS Cut Line= 3
      3617377.46     10643379.87      3616811.45      10643098.6
      3616443.96     10643084.73
#Sta/Elev= 30
  4550.8  346.28  4580.1  343.59  4593.1  344.23  4602.5  343.56    4608  342.53
  4675.2  339.01  4692.1  337.39  4704.7   335.3    4720  335.68  4736.9  335.23
  4742.5  336.92  4749.4  335.54  4759.3  334.51  4764.9  335.69  4771.7  334.51
  4781.7  334.51  4787.3     336  4794.1  334.51    4997  334.51  4999.8  334.01
    5003  334.51  5314.8  334.72  5334.8  336.46  5344.8  338.67  5374.8  341.57
  5384.8  341.52  5414.9  343.83  5486.4  347.38  5514.9  349.17  5550.6  350.02
#Mann= 4 ,-1 , 0
  4550.8     .05       0    4997    .033       0    5003     .05       0
  5486.4     .12       0
Bank Sta=4997,5003
XS Rating Curve= 0 ,0
Exp/Cntr=0.3,0.1

Type RM Length L Ch R = 1 ,1671    ,41,41,41
BEGIN DESCRIPTION:
Mapping XS b5d38c61
END DESCRIPTION:
XS GIS Cut Line= 3
      3617377.45     10643333.85      3616809.72     10643065.61
      3616462.67     10643052.66
#Sta/Elev= 30
  4560.8  344.68  4651.9  338.91    4794  340.05  4816.7  341.88  4839.5  338.86
    4885  337.13  4901.3  338.75  4930.6  336.97  4967.6   337.8  4976.1  335.35
  4981.6  338.41  4989.7  338.32    4997  335.11  4999.8  334.61    5003  335.11
  5004.4  338.02  5021.6  335.11  5027.2  337.73  5056.1  337.46  5067.1  335.67
  5072.7  337.58  5089.3  338.15  5155.6  337.92  5163.7  336.02  5169.3  337.51
  5218.8  338.52  5318.9  336.55  5358.9  340.56    5508  348.01    5536  348.83
#Mann= 4 ,-1 , 0
  4560.8     .05       0    4997    .033       0    5003     .05       0
    5508     .12       0
Bank Sta=4997,5003
XS Rating Curve= 0 ,0
Exp/Cntr=0.3,0.1

Type RM Length L Ch R = 1 ,1630    ,226,226,226
BEGIN DESCRIPTION:
Mapping XS 9e6935a6
END DESCRIPTION:
XS GIS Cut Line= 3
       3617405.2      10643286.1       3616818.4     10643032.63
      3616457.27     10643025.68
#Sta/Elev= 30
    4544  344.71  4650.4  339.23  4680.8  334.66  4691.7  335.12  4697.4  338.58
  4702.8  338.56  4749.8  333.95  4820.3     335  4825.8  333.13  4919.8  331.04
  4925.2  328.44  4940.8  330.25  4954.2  329.69  4972.2  332.35  4977.7  328.61
  4995.7  330.18    4997  328.38  4999.8  327.88    5003  328.38  5024.7  332.49
  5030.1  329.71  5071.7  332.08  5077.1  328.98  5124.1  331.72  5129.6  329.76
  5160.1  330.17    5222  334.25    5252  331.72    5312  338.81  5544.4  348.41
#Mann= 5 ,-1 , 0
    4544     .05       0  4940.8     .16       0  4972.2     .05       0
    4997     .03       0    5003     .05       0
Bank Sta=4997,5003
XS Rating Curve= 0 ,0
Exp/Cntr=0.3,0.1

Type RM Length L Ch R = 1 ,1404    ,314,314,314
BEGIN DESCRIPTION:
Mapping XS 7fea7c23
END DESCRIPTION:
XS GIS Cut Line= 4
      3617604.85     10643166.93      3617080.59     10642896.12
      3617007.67     10642882.23      3616479.94      10642972.5
#Sta/Elev= 30
  4367.6  345.62  4406.8  343.73  4553.6  338.03  4576.1  334.67  4607.7  335.45
  4666.1  331.59  4773.3   327.7  4917.8   322.6  4947.5  319.92  4955.4  314.36
  4968.9   312.8    4979  317.53  4989.2  319.79    4997   312.8  4999.8   312.3
    5003   312.8  5031.9   319.3  5040.1  323.41  5119.1   326.2  5167.5  328.95
  5172.6  327.51  5202.4  328.15  5212.6  331.33  5222.5  331.84  5232.8  329.39
    5243  329.64  5253.1  333.61  5273.4  335.93  5402.8  343.24  5567.3   346.7
#Mann= 6 ,-1 , 0
  4367.6     .05       0  4406.8     .16       0  4773.3     .12       0
    4997     .07       0    5003     .12       0  5119.1     .05       0
Bank Sta=4997,5003
XS Rating Curve= 0 ,0
Exp/Cntr=0.3,0.1

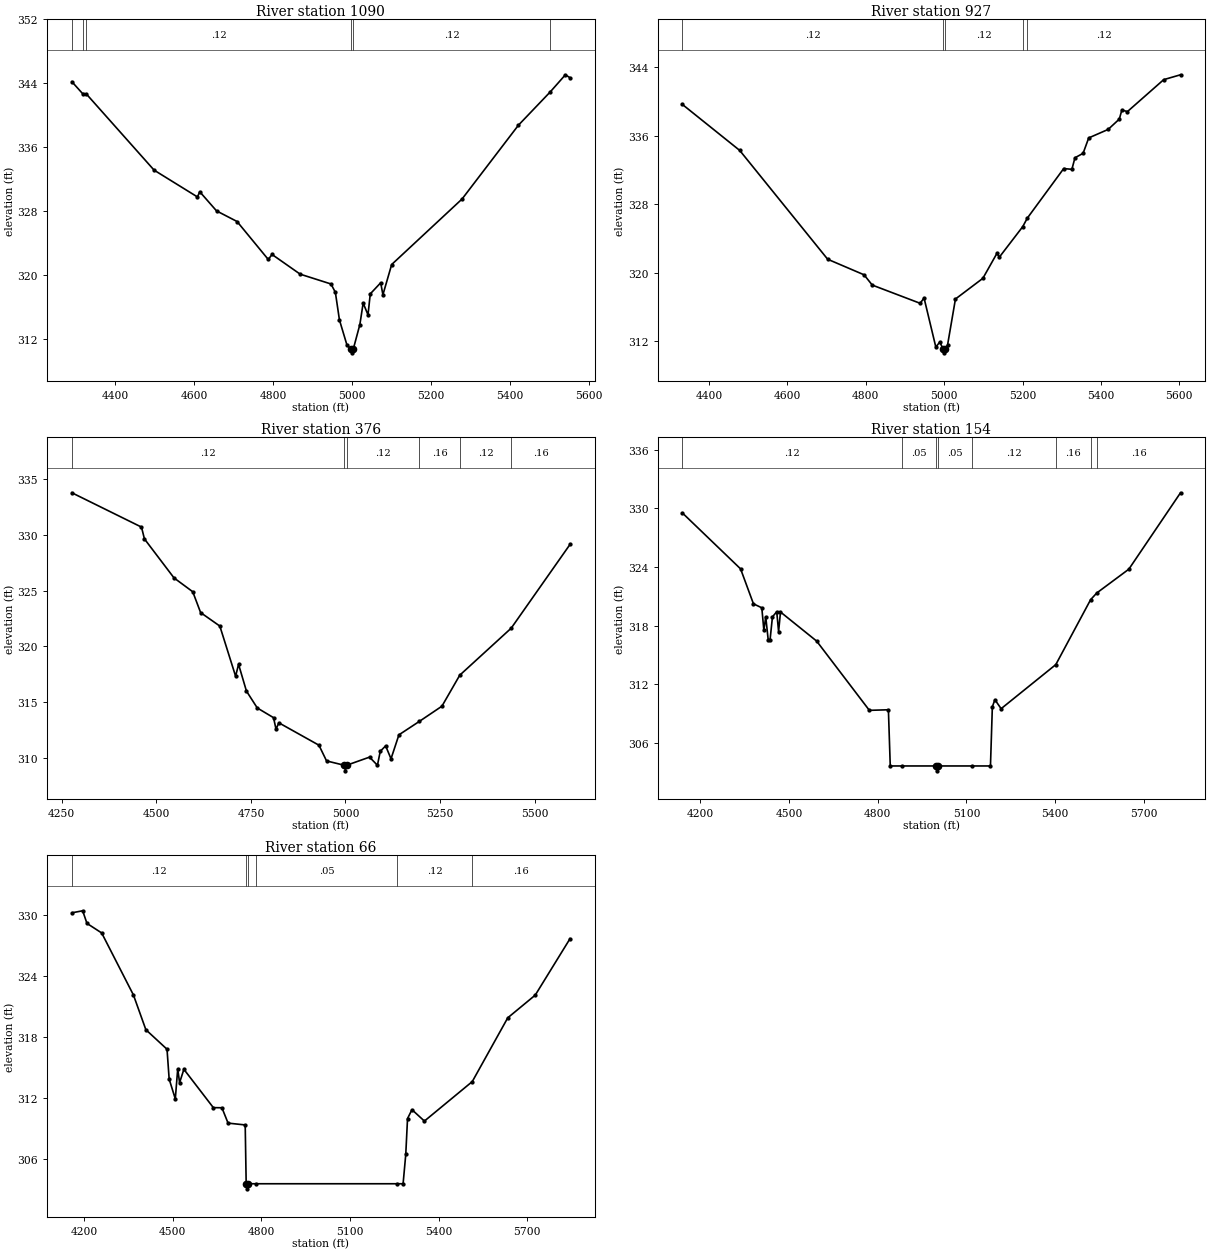
Type RM Length L Ch R = 1 ,1090    ,163,163,163
BEGIN DESCRIPTION:
Mapping XS 16f1214c
END DESCRIPTION:
XS GIS Cut Line= 4
      3617729.88     10642975.97      3617195.17     10642642.64
      3617073.64     10642611.39      3616623.42     10642839.97
#Sta/Elev= 30
  4290.7  344.19  4317.8   342.7    4327  342.67  4498.7  333.11  4608.4  329.75
  4614.3   330.4  4656.8     328  4708.7  326.67  4787.7  321.91  4797.2  322.54
  4868.4  320.07  4946.4  318.84  4957.5  317.79  4967.8  314.33  4987.1  311.14
    4997  310.71  4999.8  310.21    5003  310.71  5019.5  313.76  5027.8  316.45
  5040.1  314.97  5045.8   317.6  5072.2  318.99  5077.8  317.49    5100  321.28
  5278.1  329.49  5420.9  338.75  5501.2  342.91  5539.6  345.06  5551.2  344.69
#Mann= 6 ,-1 , 0
  4290.7     .05       0  4317.8     .16       0    4327     .12       0
    4997     .07       0    5003     .12       0  5501.2     .05       0
Bank Sta=4997,5003
XS Rating Curve= 0 ,0
Exp/Cntr=0.3,0.1

Type RM Length L Ch R = 1 ,927     ,551,551,551
BEGIN DESCRIPTION:
UNT245 IN CCTC 2.0
END DESCRIPTION:
XS GIS Cut Line= 4
      3617660.18     10642784.22      3617200.15     10642471.74
       3616957.1     10642463.06       3616594.6     10642765.15
#Sta/Elev= 30
    4332  339.65  4478.2  334.28  4702.7  321.56  4795.6  319.74  4816.5  318.54
  4938.7  316.41  4948.7  317.03  4978.7   311.3  4988.7  311.87    4997  311.12
  4999.8  310.62    5003  311.12  5008.7  311.54  5028.8  316.91  5098.8  319.33
  5134.6  322.24  5141.1  321.82  5200.4  325.36  5212.3  326.37  5305.1  332.16
    5326  332.07  5333.8  333.42  5354.6  333.94  5368.9  335.74  5418.4  336.73
    5447  337.94  5453.5     339  5467.8  338.82  5560.3  342.55  5603.2  343.12
#Mann= 5 ,-1 , 0
    4332     .12       0    4997     .07       0    5003     .12       0
  5200.4     .16       0  5212.3     .12       0
Bank Sta=4997,5003
XS Rating Curve= 0 ,0
Exp/Cntr=0.3,0.1

Type RM Length L Ch R = 1 ,376     ,222,222,222
BEGIN DESCRIPTION:
Mapping XS 2bdd6e73
END DESCRIPTION:
XS GIS Cut Line= 4
      3617667.93     10642461.73      3617272.97     10641984.31
      3617129.74     10641997.33      3616760.83     10642409.64
#Sta/Elev= 30
  4276.8  333.77  4460.8  330.69  4468.6  329.63  4546.8  326.13  4596.3  324.89
  4617.1  323.02  4667.9  321.81  4709.6  317.31  4717.4  318.38  4738.2  315.98
  4766.9  314.46  4809.9  313.59  4816.4  312.56  4823.9  313.13  4929.9  311.12
    4950  309.71    4997  309.32  4999.8  308.82    5003  309.32  5063.6  310.05
  5084.5  309.32    5092  310.57  5106.2  311.06  5120.4   309.9  5141.3  312.05
  5195.5  313.26    5255  314.62  5302.1   317.4  5438.1  321.62  5593.5  329.13
#Mann= 6 ,-1 , 0
  4276.8     .12       0    4997     .07       0    5003     .12       0
  5195.5     .16       0  5302.1     .12       0  5438.1     .16       0
Bank Sta=4997,5003
XS Rating Curve= 0 ,0
Exp/Cntr=0.3,0.1

Type RM Length L Ch R = 1 ,154     ,88,88,88
BEGIN DESCRIPTION:
UNT245 IN CCTC 1.0
END DESCRIPTION:
XS GIS Cut Line= 4
      3617862.37     10642253.83      3617237.38     10641772.07
      3617120.19     10641772.07      3616686.14      10642418.8
#Sta/Elev= 30
  4139.2  329.54    4336  323.81  4379.5  320.23  4407.8  319.82  4414.8  317.51
  4421.1   318.9  4429.3  316.57  4435.6   316.5  4443.8  318.89  4458.3  319.42
  4464.6  317.38    4471  319.39  4593.3  316.41  4771.7  309.31  4836.1  309.37
  4842.4  303.61  4881.4  303.61    4997  303.61  4999.8  303.11    5003  303.61
  5119.3  303.61  5181.4  303.61  5187.8  309.68  5196.4   310.4  5217.5  309.48
  5402.5     314  5520.2  320.65  5541.1  321.34  5649.6  323.78  5824.4  331.61
#Mann= 8 ,-1 , 0
  4139.2     .12       0  4881.4     .05       0    4997    .033       0
    5003     .05       0  5119.3     .12       0  5402.5     .16       0
  5520.2     .12       0  5541.1     .16       0
Bank Sta=4997,5003
XS Rating Curve= 0 ,0
Exp/Cntr=0.3,0.1

Type RM Length L Ch R = 1 ,66      ,0,0,0
BEGIN DESCRIPTION:
UNT245 IN CCTC 1.0
END DESCRIPTION:
XS GIS Cut Line= 4
       3617854.6     10642166.62      3617229.57     10641684.83
      3617112.38     10641684.83      3616678.35     10642331.53
#Sta/Elev= 30
    4159  330.24  4195.5  330.44    4210   329.2  4259.8  328.26  4367.3  322.16
  4409.3  318.75  4480.9  316.83  4488.1   313.9  4508.9  311.95  4517.1   314.9
  4523.4  313.54  4537.9  314.86  4637.6  311.09  4666.6  311.08  4687.4  309.57
  4745.4  309.39  4748.7  303.61  4751.5  303.11  4754.7  303.61  4782.1  303.61
  5259.2  303.61  5279.6  303.61  5288.6  306.49  5294.6  310.02  5309.6  310.89
  5351.7  309.77  5513.6  313.65  5633.7  319.92  5726.7  322.15  5844.2  327.69
#Mann= 6 ,-1 , 0
    4159     .12       0  4748.7    .033       0  4754.7     .12       0
  4782.1     .05       0  5259.2     .12       0  5513.6     .16       0
Bank Sta=4748.7,4754.7
XS Rating Curve= 0 ,0
Exp/Cntr=0.3,0.1

Chan Stop Cuts=-1
Use User Specified Reach Order=0
Composite Channel Slope=5