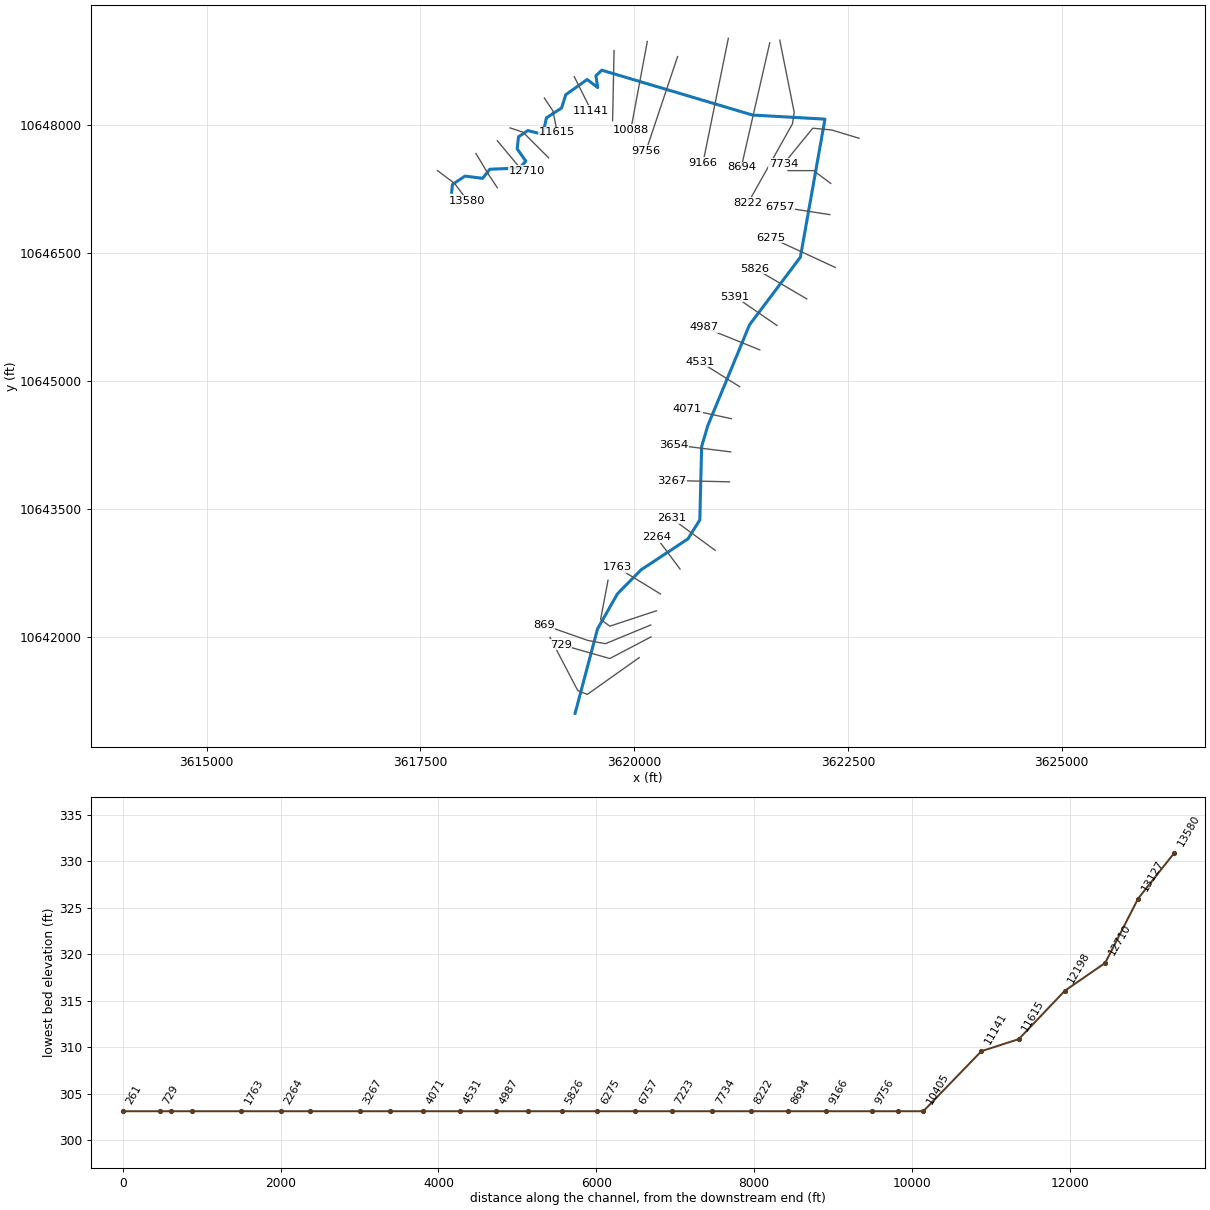
--- UNT246 IN CCTC.prj (project) ---

Proj Title=UNT246 IN CCTC Base Level Engineering
Current Plan=p01
Default Exp/Contr=0.3,0.1
English Units
Geom File=g01
Flow File=f01
Plan File=p01
BEGIN DESCRIPTION:
UNT246 IN CCTC
END DESCRIPTION:

--- UNT246 IN CCTC.p01 (plan) ---

Plan Title=Multiple Run
Short Identifier=Multiple
Geom File=g01
Flow File=f01
Subcritical Flow
K Sum by GR= 0
Std Step Tol= 0.01
Critical Tol= 0.01
Num of Std Step Trials= 20
Max Error Tol= 0.3
Flow Tol Ratio= 0.001
Split Flow NTrial= 30
Split Flow Tol= 0.02
Split Flow Ratio= 0.02
Log Output Level= 0
Friction Slope Method= 1
Unsteady Friction Slope Method= 2
Unsteady Bridges Friction Slope Method= 1
Parabolic Critical Depth
Global Vel Dist=  1 , 1 , 1
Global Log Level= 0
CheckData=True
Encroach Param= -1, 0, 0, 0
BEGIN DESCRIPTION:
Multiple Run
END DESCRIPTION:

--- UNT246 IN CCTC.f01 (steady flow) ---

Flow Title=Multiple
Number of Profiles=7
Profile Names=10-year,25-year,50-year,1pct_min,100-year,1pct_plu,500-year
River Rch & RM= UNT246 IN CCTC,Reach-1,13580
     814    1082    1297    1137    1537    2079    2149
River Rch & RM= UNT246 IN CCTC,Reach-1,7734
    1267    1717    2082    1842    2491    3369    3554
River Rch & RM= UNT246 IN CCTC,Reach-1,1135
    1407    1917    2332    2069    2798    3784    4014
Boundary for River Rch & Prof#=UNT246 IN CCTC,Reach-1,1
Up Type=0
Dn Type=3
Dn Slope=0.005
Boundary for River Rch & Prof#=UNT246 IN CCTC,Reach-1,2
Up Type=0
Dn Type=3
Dn Slope=0.005
Boundary for River Rch & Prof#=UNT246 IN CCTC,Reach-1,3
Up Type=0
Dn Type=3
Dn Slope=0.005
Boundary for River Rch & Prof#=UNT246 IN CCTC,Reach-1,4
Up Type=0
Dn Type=3
Dn Slope=0.005
Boundary for River Rch & Prof#=UNT246 IN CCTC,Reach-1,5
Up Type=0
Dn Type=3
Dn Slope=0.005
Boundary for River Rch & Prof#=UNT246 IN CCTC,Reach-1,6
Up Type=0
Dn Type=3
Dn Slope=0.005
Boundary for River Rch & Prof#=UNT246 IN CCTC,Reach-1,7
Up Type=0
Dn Type=3
Dn Slope=0.005

--- UNT246 IN CCTC.g01 (geometry) ---

Geom Title=Existing Conditions

River Reach=UNT246 IN CCTC,Reach-1
Reach XY= 30
      3617865.06     10647208.36      3617874.83     10647298.42
      3618021.31     10647396.08      3618227.48     10647370.04
      3618312.11     10647476.37      3618658.75     10647491.00
      3618733.00     10647570.00      3618631.50     10647716.00
      3618647.50     10647856.00      3618755.50     10647929.00
      3618931.00     10647886.00      3618974.25     10648078.00
      3619151.50     10648194.00      3619200.25     10648349.00
      3619450.50     10648527.00      3619573.75     10648433.00
      3619553.00     10648571.00      3619621.25     10648636.00
      3621384.75     10648111.00      3622232.25     10648063.00
      3621945.00     10646447.00      3621350.00     10645655.00
      3620861.75     10644475.00      3620789.75     10644230.00
      3620768.50     10643371.00      3620629.75     10643149.00
      3620080.75     10642786.00      3619805.00     10642506.00
      3619571.75     10642095.00      3619309.25     10641106.00

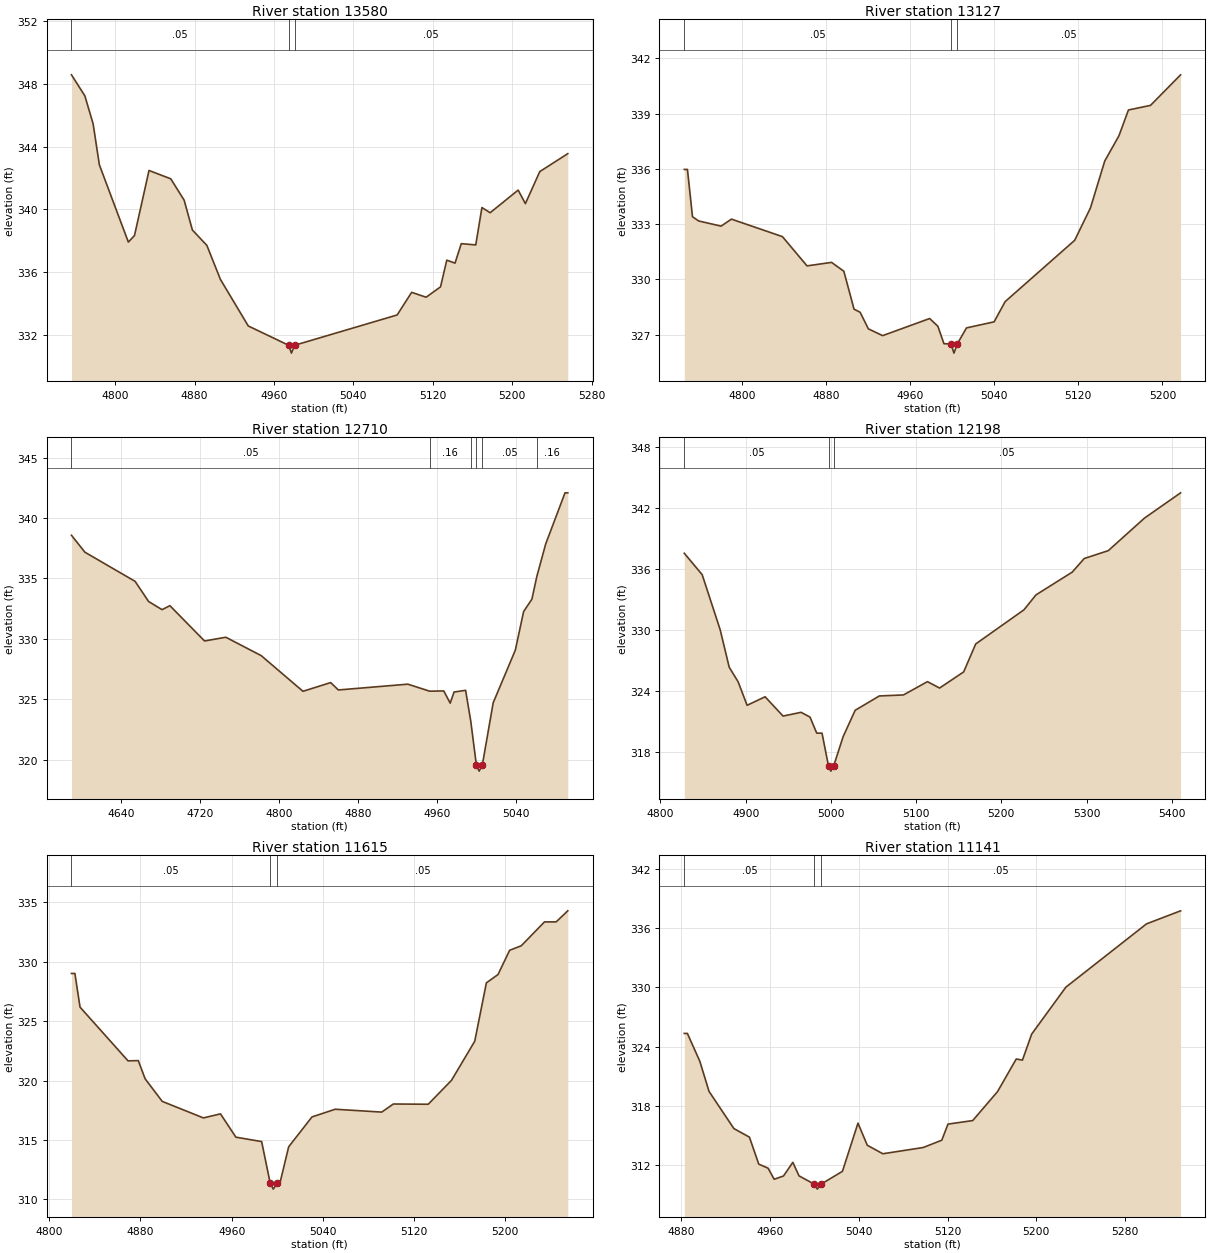
Type RM Length L Ch R = 1,13580,453,453,453
BEGIN DESCRIPTION:
UNT246 IN CCTC 29.0
END DESCRIPTION:
XS GIS Cut Line= 3
      3617699.64     10647460.16      3617899.61     10647310.19
      3618049.63     10647110.16
#Sta/Elev= 30
  4756.0  348.57  4769.5  347.23  4777.8  345.45  4784.1  342.84  4813.3  337.92
  4819.5  338.34  4834.1  342.48  4856.0  341.95  4869.5  340.59  4877.8  338.69
  4892.4  337.71  4906.0  335.55  4934.1  332.58  4974.8  331.35  4977.6  330.85
  4980.8  331.35  5084.1  333.28  5098.7  334.72  5113.3  334.41  5127.8  335.07
  5134.1  336.77  5142.4  336.58  5148.7  337.82  5163.3  337.74  5169.5  340.12
  5177.8  339.79  5206.0  341.23  5213.3  340.37  5227.8  342.41  5256.0  343.55
#Mann=3,-1,0
  4756.0    0.05       0  4974.8    0.03       0  4980.8    0.05       0
Bank Sta=4974.8,4980.8
Exp/Cntr=0.3,0.1

Type RM Length L Ch R = 1,13127,417,417,417
BEGIN DESCRIPTION:
UNT246 IN CCTC 28.0
END DESCRIPTION:
XS GIS Cut Line= 3
      3618149.59     10647660.23      3618299.61     10647410.19
      3618399.62     10647260.17
#Sta/Elev= 30
  4745.4  335.97  4748.4  335.97  4753.2  333.40  4759.1  333.17  4780.4  332.89
  4790.2  333.27  4838.7  332.32  4862.1  330.73  4885.4  330.92  4897.1  330.44
  4906.8  328.38  4912.6  328.21  4920.4  327.31  4934.0  326.94  4978.7  327.87
  4986.5  327.45  4992.3  326.50  4999.0  326.49  5001.8  325.99  5005.0  326.49
  5013.7  327.36  5040.0  327.69  5050.5  328.79  5116.6  332.12  5131.6  333.88
  5145.2  336.43  5158.7  337.80  5167.7  339.20  5188.7  339.45  5217.3  341.11
#Mann=3,-1,0
  4745.4    0.05       0  4999.0    0.03       0  5005.0    0.05       0
Bank Sta=4999,5005
Exp/Cntr=0.3,0.1

Type RM Length L Ch R = 1,12710,512,512,512
BEGIN DESCRIPTION:
UNT246 IN CCTC 27.0
END DESCRIPTION:
XS GIS Cut Line= 3
      3618399.63     10647810.17      3618649.61     10647510.19
      3618749.62     10647460.18
#Sta/Elev= 30
  4590.0  338.57  4603.6  337.17  4654.4  334.76  4668.1  333.09  4681.7  332.42
  4689.6  332.75  4724.7  329.83  4746.2  330.14  4782.0  328.62  4824.3  325.67
  4852.3  326.39  4860.1  325.78  4930.4  326.26  4952.5  325.68  4966.8  325.70
  4973.3  324.69  4977.2  325.61  4988.9  325.75  4994.1  323.21  4999.8  319.57
  5002.6  319.07  5005.8  319.57  5016.8  324.72  5039.2  329.07  5047.6  332.26
  5056.0  333.29  5060.9  335.14  5069.9  337.84  5089.5  342.08  5092.3  342.08
#Mann=6,-1,0
  4590.0    0.05       0  4952.5    0.16       0  4994.1    0.05       0
  4999.8    0.03       0  5005.8    0.05       0  5060.9    0.16       0
Bank Sta=4999.8,5005.8
Exp/Cntr=0.3,0.1

Type RM Length L Ch R = 1,12198,583,583,583
BEGIN DESCRIPTION:
UNT246 IN CCTC 26.0
END DESCRIPTION:
XS GIS Cut Line= 3
      3618549.65     10647960.17      3618699.61     10647910.19
      3618999.59     10647610.21
#Sta/Elev= 30
  4828.0  337.52  4849.0  335.41  4870.1  329.99  4880.7  326.30  4891.2  324.86
  4901.7  322.55  4922.8  323.39  4943.9  321.49  4965.0  321.86  4975.5  321.39
  4983.4  319.81  4989.6  319.81  4997.2  316.57  5000.0  316.07  5003.2  316.57
  5014.4  319.47  5028.5  322.06  5056.8  323.47  5085.1  323.57  5113.3  324.88
  5127.5  324.25  5155.8  325.84  5169.9  328.59  5226.5  331.95  5240.6  333.42
  5283.1  335.66  5297.2  337.00  5325.5  337.78  5367.9  340.98  5410.3  343.47
#Mann=3,-1,0
  4828.0    0.05       0  4997.2    0.03       0  5003.2    0.05       0
Bank Sta=4997.2,5003.2
Exp/Cntr=0.3,0.1

Type RM Length L Ch R = 1,11615,474,474,474
BEGIN DESCRIPTION:
UNT246 IN CCTC 25.0
END DESCRIPTION:
XS GIS Cut Line= 3
      3618949.60     10648310.21      3619049.61     10648160.19
      3619099.62     10647910.14
#Sta/Elev= 30
  4819.5  329.01  4822.5  329.01  4827.0  326.18  4869.1  321.66  4878.1  321.68
  4884.1  320.15  4899.1  318.25  4935.2  316.86  4950.2  317.20  4963.7  315.24
  4986.3  314.87  4993.8  311.37  4996.5  310.87  4999.8  311.37  5002.3  311.37
  5010.0  314.43  5030.4  316.94  5050.8  317.59  5091.6  317.35  5101.8  318.03
  5132.4  318.01  5152.8  320.02  5173.2  323.31  5183.4  328.22  5193.6  328.92
  5203.8  330.96  5214.0  331.34  5234.4  333.35  5244.6  333.35  5254.8  334.28
#Mann=3,-1,0
  4819.5    0.05       0  4993.8    0.03       0  4999.8    0.05       0
Bank Sta=4993.8,4999.8
Exp/Cntr=0.3,0.1

Type RM Length L Ch R = 1,11141,736,736,736
BEGIN DESCRIPTION:
UNT246 IN CCTC 24.0
END DESCRIPTION:
XS GIS Cut Line= 3
      3619299.62     10648560.18      3619349.61     10648460.19
      3619499.61     10648160.19
#Sta/Elev= 30
  4882.8  325.33  4885.6  325.33  4896.8  322.51  4905.1  319.46  4927.5  315.70
  4941.5  314.83  4949.9  312.10  4958.3  311.69  4963.8  310.57  4972.2  310.90
  4980.6  312.28  4986.2  310.91  5000.0  310.07  5002.7  309.57  5006.0  310.07
  5025.3  311.37  5039.3  316.25  5047.7  314.01  5061.7  313.15  5098.0  313.78
  5114.8  314.52  5120.4  316.15  5142.7  316.51  5165.1  319.45  5181.9  322.74
  5187.5  322.63  5195.8  325.26  5226.6  330.01  5299.3  336.42  5330.0  337.74
#Mann=3,-1,0
  4882.8    0.05       0  5000.0    0.03       0  5006.0    0.05       0
Bank Sta=5000,5006
Exp/Cntr=0.3,0.1

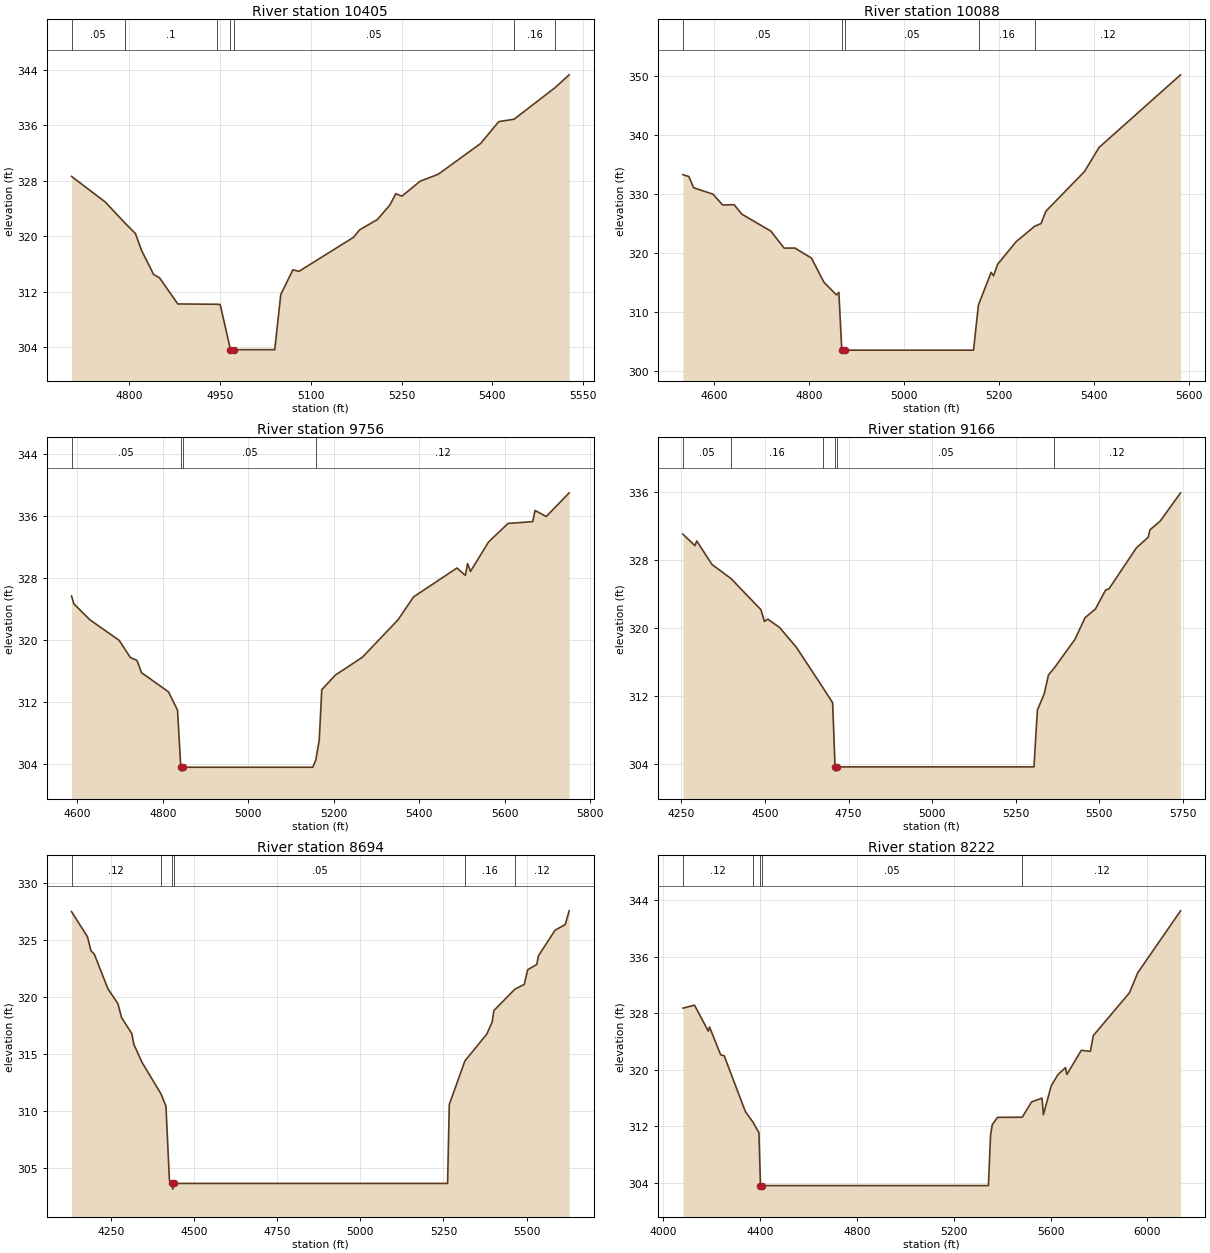
Type RM Length L Ch R = 1,10405,317,317,317
BEGIN DESCRIPTION:
UNT246 IN CCTC 23.0
END DESCRIPTION:
XS GIS Cut Line= 2
      3619765.37     10648865.68      3619748.04     10648043.96
#Sta/Elev= 30
  4704.9  328.63  4760.4  324.95  4793.1  321.90  4810.4  320.38  4820.4  317.97
  4840.4  314.48  4850.4  313.97  4880.4  310.21  4945.0  310.17  4950.4  310.13
  4967.4  303.61  4970.2  303.11  4973.4  303.61  5040.5  303.61  5050.5  311.58
  5070.5  315.14  5080.5  314.92  5170.5  319.83  5180.5  320.90  5210.3  322.42
  5230.5  324.48  5240.5  326.13  5250.5  325.77  5280.5  327.93  5310.5  328.94
  5380.5  333.38  5410.5  336.54  5435.8  336.89  5503.4  341.44  5526.8  343.30
#Mann=7,-1,0
  4704.9    0.05       0  4793.1     0.1       0  4945.0    0.05       0
  4967.4   0.035       0  4973.4    0.05       0  5435.8    0.16       0
  5503.4    0.12       0
Bank Sta=4967.4,4973.4
Exp/Cntr=0.3,0.1

Type RM Length L Ch R = 1,10088,332,332,332
BEGIN DESCRIPTION:
UNT246 IN CCTC 22.0
END DESCRIPTION:
XS GIS Cut Line= 2
      3620154.26     10648972.47      3619961.55     10647941.22
#Sta/Elev= 30
  4533.5  333.34  4546.0  333.03  4556.2  331.12  4596.9  330.04  4617.2  328.21
  4641.6  328.25  4657.9  326.64  4718.9  323.78  4746.9  320.90  4769.8  320.91
  4804.6  319.20  4830.8  315.12  4857.3  312.97  4862.3  313.41  4868.5  303.61
  4871.3  303.11  4874.5  303.61  5146.2  303.61  5156.4  311.19  5158.1  311.58
  5183.3  316.80  5188.4  316.21  5197.1  318.17  5236.0  321.99  5275.1  324.60
  5288.6  325.06  5298.8  327.15  5380.2  333.88  5410.7  337.94  5582.6  350.25
#Mann=5,-1,0
  4533.5    0.05       0  4868.5   0.033       0  4874.5    0.05       0
  5158.1    0.16       0  5275.1    0.12       0
Bank Sta=4868.5,4874.5
Exp/Cntr=0.3,0.1

Type RM Length L Ch R = 1,9756,590,590,590
BEGIN DESCRIPTION:
UNT246 IN CCTC 21.0
END DESCRIPTION:
XS GIS Cut Line= 2
      3620508.41     10648795.37      3620138.64     10647691.24
#Sta/Elev= 30
  4586.7  325.66  4592.2  324.65  4629.6  322.60  4698.0  319.96  4724.3  317.74
  4739.8  317.37  4750.4  315.79  4813.6  313.32  4834.7  310.96  4842.3  303.61
  4845.0  303.11  4848.3  303.61  5151.1  303.61  5158.1  304.52  5166.2  307.06
  5172.2  313.60  5203.8  315.47  5267.1  317.77  5350.3  322.58  5387.1  325.55
  5488.6  329.27  5508.1  328.32  5513.4  329.84  5520.2  328.83  5562.4  332.62
  5608.1  335.01  5665.9  335.24  5671.2  336.68  5697.5  335.90  5751.1  338.95
#Mann=4,-1,0
  4586.7    0.05       0  4842.3   0.033       0  4848.3    0.05       0
  5158.1    0.12       0
Bank Sta=4842.3,4848.3
Exp/Cntr=0.3,0.1

Type RM Length L Ch R = 1,9166,472,472,472
BEGIN DESCRIPTION:
UNT246 IN CCTC 20.0
END DESCRIPTION:
XS GIS Cut Line= 2
      3621102.18     10649008.96      3620805.31     10647550.67
#Sta/Elev= 30
  4254.6  331.05  4290.8  329.69  4295.9  330.25  4341.4  327.48  4398.5  325.81
  4488.0  322.14  4498.3  320.76  4508.5  321.03  4543.7  320.05  4594.3  317.69
  4672.1  313.03  4702.4  311.17  4709.6  303.61  4712.3  303.11  4715.6  303.61
  5304.5  303.61  5314.7  310.31  5335.1  312.21  5347.8  314.45  5364.7  315.24
  5426.9  318.64  5457.5  321.21  5488.2  322.22  5518.8  324.46  5529.0  324.61
  5610.6  329.42  5646.2  330.69  5651.4  331.56  5682.1  332.59  5742.8  335.92
#Mann=6,-1,0
  4254.6    0.05       0  4398.5    0.16       0  4672.1    0.05       0
  4709.6   0.033       0  4715.6    0.05       0  5364.7    0.12       0
Bank Sta=4709.6,4715.6
Exp/Cntr=0.3,0.1

Type RM Length L Ch R = 1,8694,472,472,472
BEGIN DESCRIPTION:
UNT246 IN CCTC 19.0
END DESCRIPTION:
XS GIS Cut Line= 2
      3621586.55     10648956.86      3621253.23     10647498.57
#Sta/Elev= 30
  4132.2  327.47  4180.1  325.26  4190.6  324.03  4200.6  323.74  4241.6  320.69
  4271.4  319.41  4282.7  318.16  4313.4  316.76  4319.5  315.82  4344.2  314.23
  4401.1  311.47  4416.0  310.40  4426.3  303.94  4433.5  303.61  4436.3  303.11
  4439.5  303.61  5262.6  303.61  5267.7  310.54  5314.6  314.36  5380.2  316.71
  5396.6  317.78  5401.7  318.78  5465.1  320.67  5493.1  321.08  5503.3  322.37
  5530.6  322.83  5535.7  323.59  5585.4  325.83  5616.2  326.34  5628.1  327.54
#Mann=6,-1,0
  4132.2    0.12       0  4401.1    0.05       0  4433.5   0.033       0
  4439.5    0.05       0  5314.6    0.16       0  5465.1    0.12       0
Bank Sta=4433.5,4439.5
Exp/Cntr=0.3,0.1

Type RM Length L Ch R = 1,8222,488,488,488
BEGIN DESCRIPTION:
UNT246 IN CCTC 18.0
END DESCRIPTION:
XS GIS Cut Line= 4
      3621703.86     10648987.23      3621873.12     10648140.91
      3621851.42     10648006.36      3621334.91     10647086.18
#Sta/Elev= 30
  4082.1  328.73  4130.1  329.15  4187.0  325.47  4192.1  326.07  4238.0  322.13
  4252.5  321.99  4340.0  314.10  4371.1  312.60  4396.1  311.10  4402.4  303.61
  4405.2  303.11  4408.4  303.61  5343.6  303.61  5352.3  310.75  5359.5  312.25
  5381.2  313.27  5483.2  313.29  5521.5  315.45  5564.9  315.99  5570.6  313.65
  5602.5  317.70  5629.9  319.30  5661.8  320.31  5667.5  319.35  5726.9  322.76
  5764.5  322.62  5776.6  324.85  5925.7  330.90  5960.1  333.74  6136.7  342.51
#Mann=5,-1,0
  4082.1    0.12       0  4371.1    0.05       0  4402.4   0.033       0
  4408.4    0.05       0  5483.2    0.12       0
Bank Sta=4402.4,4408.4
Exp/Cntr=0.3,0.1

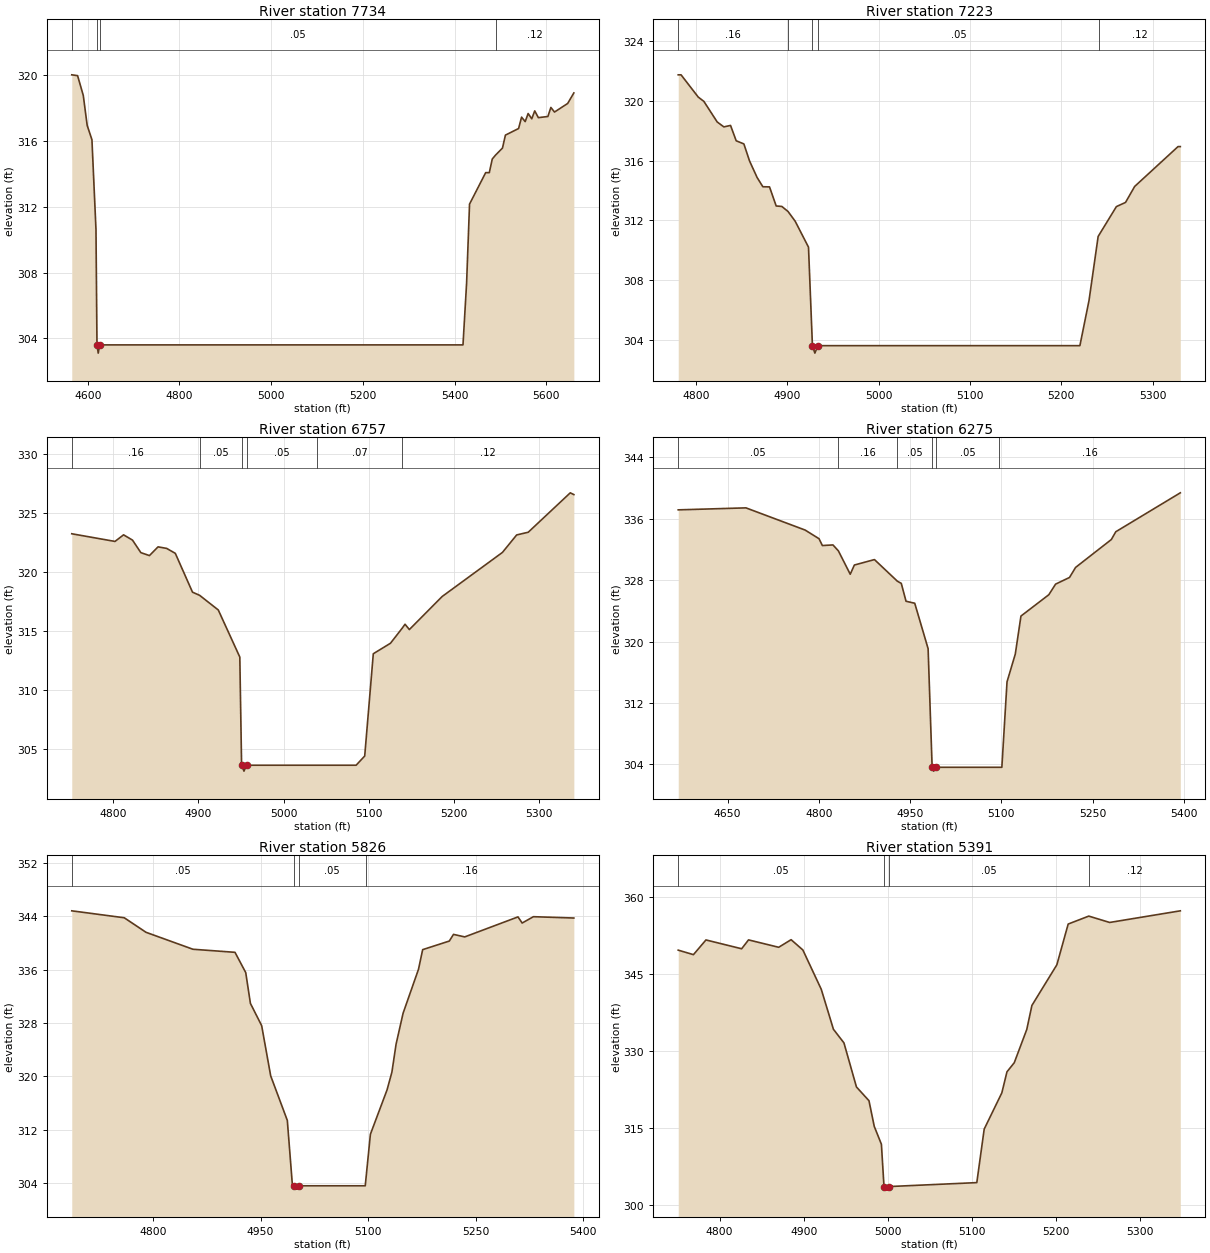
Type RM Length L Ch R = 1,7734,511,511,511
BEGIN DESCRIPTION:
UNT246 IN CCTC 17.0
END DESCRIPTION:
XS GIS Cut Line= 4
      3622631.74     10647838.80      3622312.25     10647936.04
      3622090.03     10647956.87      3621749.76     10647540.21
#Sta/Elev= 30
  4565.1  320.01  4577.8  319.96  4590.2  318.76  4598.7  316.94  4609.1  316.07
  4617.9  310.62  4620.1  303.61  4622.8  303.11  4626.1  303.61  5418.4  303.61
  5426.3  307.37  5432.7  312.16  5467.9  314.07  5475.8  314.07  5482.3  314.90
  5489.6  315.14  5504.5  315.56  5511.0  316.35  5539.7  316.75  5546.2  317.44
  5554.1  317.17  5560.5  317.66  5568.4  317.34  5574.9  317.82  5582.8  317.41
  5603.6  317.48  5610.1  318.03  5618.0  317.75  5646.7  318.27  5660.2  318.91
#Mann=4,-1,0
  4565.1    0.05       0  4620.1   0.033       0  4626.1    0.05       0
  5489.6    0.12       0
Bank Sta=4620.1,4626.1
Exp/Cntr=0.3,0.1

Type RM Length L Ch R = 1,7223,466,466,466
BEGIN DESCRIPTION:
UNT246 IN CCTC 16.0
END DESCRIPTION:
XS GIS Cut Line= 3
      3622299.59     10647310.20      3622099.61     10647460.19
      3621799.59     10647460.19
#Sta/Elev= 30
  4780.4  321.76  4783.5  321.76  4802.3  320.27  4808.5  319.98  4823.1  318.60
  4830.4  318.27  4837.7  318.37  4843.9  317.34  4852.3  317.13  4858.5  315.99
  4866.8  314.88  4873.1  314.26  4880.4  314.25  4887.7  312.97  4893.9  312.94
  4900.7  312.60  4908.5  311.95  4923.1  310.21  4927.4  303.61  4930.1  303.11
  4933.4  303.61  5220.4  303.61  5230.4  306.64  5240.4  310.93  5241.8  311.07
  5260.4  312.93  5270.4  313.21  5280.4  314.28  5327.9  316.95  5330.4  316.95
#Mann=5,-1,0
  4780.4    0.16       0  4900.7    0.05       0  4927.4   0.033       0
  4933.4    0.05       0  5241.8    0.12       0
Bank Sta=4927.4,4933.4
Exp/Cntr=0.3,0.1

Type RM Length L Ch R = 1,6757,482,482,482
BEGIN DESCRIPTION:
UNT246 IN CCTC 15.0
END DESCRIPTION:
XS GIS Cut Line= 2
      3622289.83     10646944.98      3621706.67     10647035.23
#Sta/Elev= 30
  4751.1  323.23  4801.9  322.58  4812.0  323.14  4822.5  322.69  4832.3  321.63
  4842.4  321.38  4852.5  322.12  4862.6  321.99  4872.8  321.57  4893.0  318.28
  4901.4  318.01  4923.3  316.77  4948.6  312.78  4950.7  303.61  4953.5  303.11
  4956.7  303.61  5038.8  303.61  5085.3  303.61  5095.4  304.39  5105.5  313.06
  5125.7  313.95  5139.5  315.23  5142.8  315.56  5147.9  315.11  5186.4  317.91
  5257.3  321.65  5274.0  323.13  5287.6  323.36  5337.0  326.70  5341.2  326.55
#Mann=6,-1,0
  4751.1    0.16       0  4901.4    0.05       0  4950.7   0.033       0
  4956.7    0.05       0  5038.8    0.07       0  5139.5    0.12       0
Bank Sta=4950.7,4956.7
Exp/Cntr=0.3,0.1

Type RM Length L Ch R = 1,6275,449,449,449
BEGIN DESCRIPTION:
UNT246 IN CCTC 14.0
END DESCRIPTION:
XS GIS Cut Line= 2
      3622352.30     10646326.93      3621603.46     10646673.62
#Sta/Elev= 30
  4568.8  337.16  4680.1  337.42  4777.3  334.53  4800.2  333.40  4805.7  332.51
  4823.1  332.59  4832.0  331.82  4851.5  328.77  4858.3  329.97  4891.3  330.68
  4929.0  327.86  4935.4  327.58  4943.2  325.25  4957.5  324.99  4979.5  319.07
  4986.1  303.61  4988.8  303.11  4992.1  303.61  5096.5  303.61  5100.7  303.61
  5109.2  314.75  5122.8  318.37  5132.1  323.32  5177.9  326.10  5189.0  327.48
  5211.9  328.35  5221.9  329.66  5280.6  333.29  5288.0  334.31  5394.0  339.38
#Mann=6,-1,0
  4568.8    0.05       0  4832.0    0.16       0  4929.0    0.05       0
  4986.1   0.033       0  4992.1    0.05       0  5096.5    0.16       0
Bank Sta=4986.1,4992.1
Exp/Cntr=0.3,0.1

Type RM Length L Ch R = 1,5826,435,435,435
BEGIN DESCRIPTION:
UNT246 IN CCTC 13.0
END DESCRIPTION:
XS GIS Cut Line= 2
      3622019.01     10645958.85      3621414.78     10646313.06
#Sta/Elev= 30
  4686.7  344.83  4759.9  343.79  4790.3  341.61  4855.7  339.07  4914.4  338.61
  4929.4  335.57  4935.9  330.96  4951.6  327.62  4964.2  320.09  4987.4  313.41
  4994.5  303.68  4997.3  303.61  5000.1  303.11  5003.3  303.61  5096.1  303.61
  5097.0  304.58  5103.3  311.34  5126.5  317.98  5133.3  320.65  5139.1  324.83
  5148.9  329.48  5170.4  336.07  5176.2  339.01  5213.4  340.30  5219.2  341.30
  5234.9  340.92  5309.2  343.92  5315.0  343.00  5330.7  343.95  5387.1  343.75
#Mann=4,-1,0
  4686.7    0.05       0  4997.3   0.035       0  5003.3    0.05       0
  5097.0    0.16       0
Bank Sta=4997.3,5003.3
Exp/Cntr=0.3,0.1

Type RM Length L Ch R = 1,5391,404,404,404
BEGIN DESCRIPTION:
UNT246 IN CCTC 12.0
END DESCRIPTION:
XS GIS Cut Line= 2
      3621671.72     10645646.39      3621179.72     10645985.95
#Sta/Elev= 30
  4750.7  349.73  4768.8  348.85  4783.7  351.72  4826.2  350.00  4834.4  351.73
  4870.3  350.29  4885.1  351.77  4899.1  349.76  4921.0  342.09  4935.5  334.29
  4948.0  331.64  4962.9  323.04  4977.8  320.36  4984.1  315.35  4992.6  311.87
  4995.7  303.61  4998.5  303.11  5001.7  303.61  5106.2  304.38  5115.0  314.82
  5136.0  321.89  5142.1  325.99  5150.8  327.77  5165.7  334.26  5171.8  338.94
  5201.5  346.87  5215.0  354.82  5239.5  356.37  5264.4  355.13  5348.5  357.40
#Mann=4,-1,0
  4750.7    0.05       0  4995.7   0.033       0  5001.7    0.05       0
  5239.5    0.12       0
Bank Sta=4995.7,5001.7
Exp/Cntr=0.3,0.1

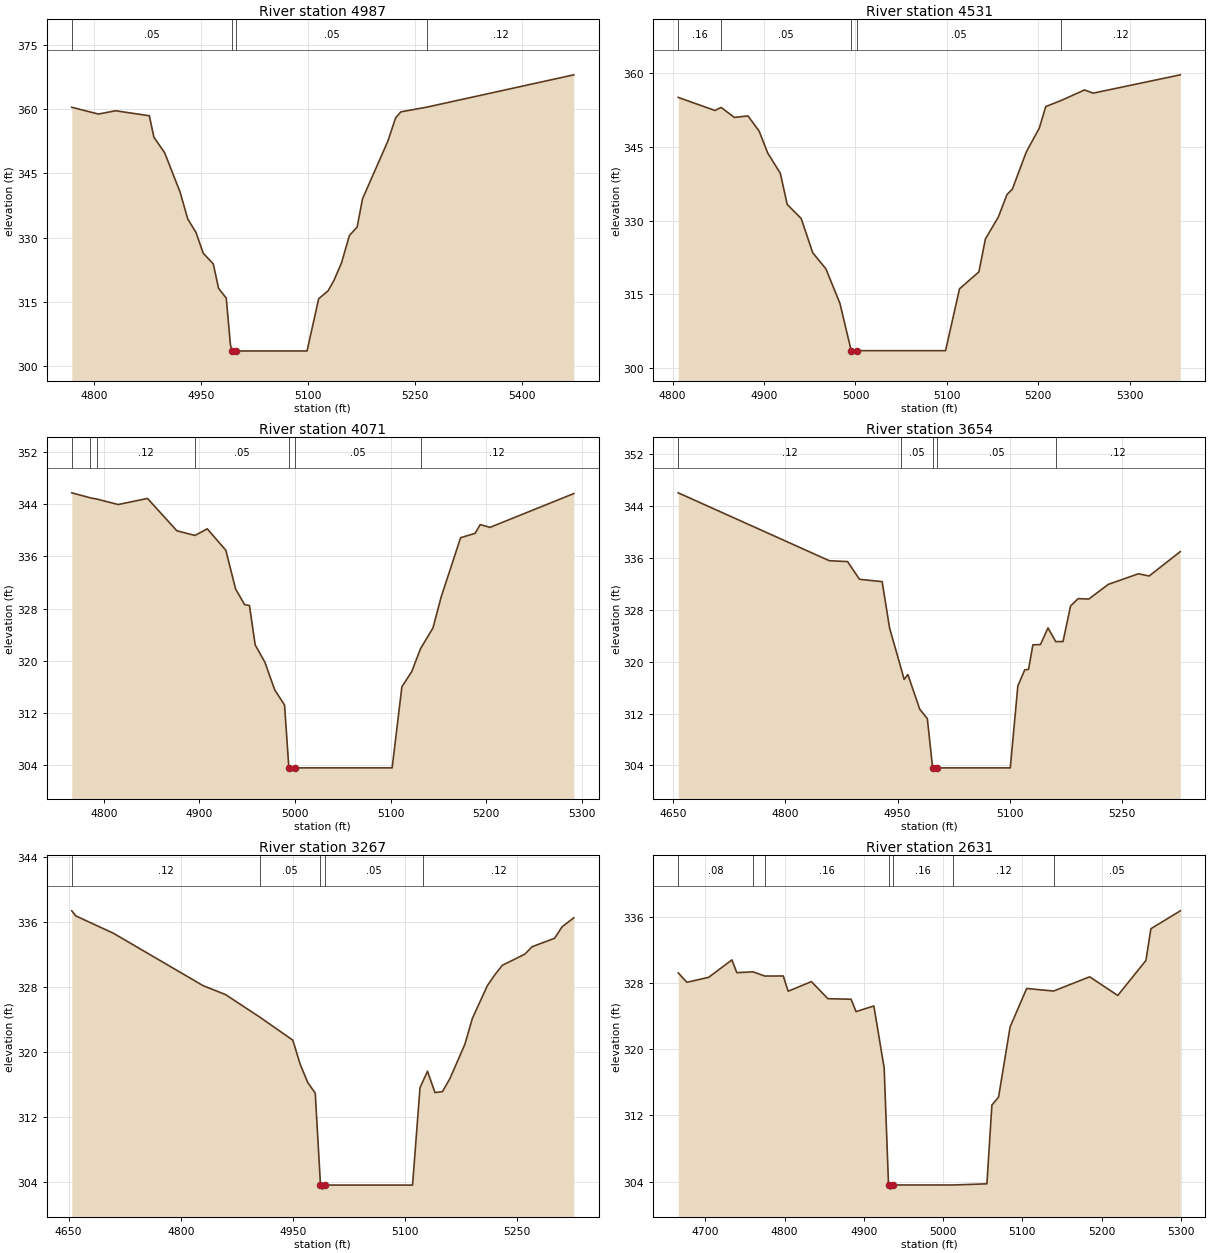
Type RM Length L Ch R = 1,4987,456,456,456
BEGIN DESCRIPTION:
UNT246 IN CCTC 11.0
END DESCRIPTION:
XS GIS Cut Line= 2
      3621470.34     10645361.66      3620818.03     10645625.36
#Sta/Elev= 30
  4768.8  360.39  4806.1  358.81  4830.2  359.58  4877.5  358.41  4883.9  353.42
  4899.0  349.78  4920.6  340.62  4931.4  334.34  4942.9  331.22  4953.0  326.39
  4967.1  323.90  4974.5  318.23  4985.3  315.92  4991.2  304.98  4993.6  303.61
  4996.3  303.11  4999.6  303.61  5098.5  303.61  5114.8  315.78  5128.0  317.62
  5136.3  320.09  5146.7  324.08  5157.9  330.52  5168.7  332.49  5176.3  339.08
  5211.8  352.51  5222.6  357.91  5229.9  359.32  5266.6  360.43  5472.4  367.95
#Mann=4,-1,0
  4768.8    0.05       0  4993.6   0.033       0  4999.6    0.05       0
  5266.6    0.12       0
Bank Sta=4993.6,4999.6
Exp/Cntr=0.3,0.1

Type RM Length L Ch R = 1,4531,460,460,460
BEGIN DESCRIPTION:
UNT246 IN CCTC 10.0
END DESCRIPTION:
XS GIS Cut Line= 2
      3621234.28     10644931.08      3620768.94     10645222.78
#Sta/Elev= 30
  4806.1  354.97  4846.3  352.32  4853.0  352.94  4867.5  350.91  4882.4  351.22
  4894.6  348.13  4904.0  343.69  4917.8  339.57  4925.3  333.27  4940.6  330.41
  4953.2  323.48  4967.7  320.18  4983.0  313.19  4995.3  303.61  4998.1  303.11
  5001.3  303.61  5098.5  303.61  5113.8  316.16  5135.0  319.59  5142.1  326.27
  5156.3  330.73  5165.7  335.27  5171.6  336.38  5186.9  343.94  5201.1  348.77
  5208.1  353.11  5224.6  354.32  5250.5  356.48  5259.9  355.83  5355.3  359.55
#Mann=5,-1,0
  4806.1    0.16       0  4853.0    0.05       0  4995.3   0.033       0
  5001.3    0.05       0  5224.6    0.12       0
Bank Sta=4995.3,5001.3
Exp/Cntr=0.3,0.1

Type RM Length L Ch R = 1,4071,417,417,417
BEGIN DESCRIPTION:
UNT246 IN CCTC 9.0
END DESCRIPTION:
XS GIS Cut Line= 2
      3621137.06     10644556.09      3620623.92     10644667.04
#Sta/Elev= 30
  4766.5  345.71  4786.0  344.94  4793.2  344.74  4815.0  343.92  4845.7  344.85
  4876.4  339.90  4895.3  339.19  4908.2  340.20  4927.6  336.92  4937.8  331.00
  4947.2  328.60  4952.3  328.46  4958.3  322.43  4968.5  319.76  4978.7  315.55
  4989.0  313.23  4993.5  303.61  4996.2  303.11  4999.5  303.61  5101.5  303.61
  5111.7  316.02  5122.0  318.35  5131.2  321.86  5144.2  325.03  5152.7  329.74
  5173.1  338.84  5188.3  339.51  5193.6  340.85  5203.8  340.42  5291.5  345.60
#Mann=7,-1,0
  4766.5    0.12       0  4786.0    0.16       0  4793.2    0.12       0
  4895.3    0.05       0  4993.5   0.033       0  4999.5    0.05       0
  5131.2    0.12       0
Bank Sta=4993.5,4999.5
Exp/Cntr=0.3,0.1

Type RM Length L Ch R = 1,3654,387,387,387
BEGIN DESCRIPTION:
UNT246 IN CCTC 8.0
END DESCRIPTION:
XS GIS Cut Line= 2
      3621130.06     10644167.21      3620464.04     10644250.46
#Sta/Elev= 30
  4656.8  346.06  4858.8  335.58  4883.2  335.45  4899.1  332.72  4929.4  332.35
  4939.4  325.17  4955.2  318.77  4958.8  317.26  4963.8  318.01  4979.7  312.66
  4989.8  311.22  4996.9  303.61  4999.6  303.11  5002.9  303.61  5100.7  303.61
  5110.8  316.25  5120.0  318.73  5125.1  318.81  5130.9  322.60  5141.0  322.64
  5151.1  325.21  5161.5  323.10  5171.2  323.11  5181.3  328.60  5191.4  329.73
  5205.7  329.67  5231.7  331.93  5272.0  333.57  5286.3  333.22  5328.0  336.99
#Mann=5,-1,0
  4656.8    0.12       0  4955.2    0.05       0  4996.9   0.033       0
  5002.9    0.05       0  5161.5    0.12       0
Bank Sta=4996.9,5002.9
Exp/Cntr=0.3,0.1

Type RM Length L Ch R = 1,3267,636,636,636
BEGIN DESCRIPTION:
UNT246 IN CCTC 7.0
END DESCRIPTION:
XS GIS Cut Line= 2
      3621115.15     10643816.73      3620443.94     10643832.34
#Sta/Elev= 30
  4654.2  337.41  4659.7  336.78  4709.8  334.65  4829.8  328.19  4859.8  327.09
  4905.6  324.31  4949.8  321.47  4959.8  318.46  4969.8  316.25  4979.8  314.94
  4986.8  303.61  4989.6  303.11  4992.8  303.61  5109.9  303.61  5119.9  315.62
  5124.5  316.55  5129.9  317.64  5139.9  315.01  5149.9  315.13  5159.9  316.74
  5179.9  320.96  5189.9  324.15  5209.9  328.18  5219.9  329.52  5229.9  330.69
  5259.9  332.06  5269.9  332.99  5299.9  334.03  5309.9  335.45  5325.6  336.55
#Mann=5,-1,0
  4654.2    0.12       0  4905.6    0.05       0  4986.8   0.033       0
  4992.8    0.05       0  5124.5    0.12       0
Bank Sta=4986.8,4992.8
Exp/Cntr=0.3,0.1

Type RM Length L Ch R = 1,2631,367,367,367
BEGIN DESCRIPTION:
UNT246 IN CCTC 6.0
END DESCRIPTION:
XS GIS Cut Line= 2
      3620948.47     10643014.63      3620438.03     10643389.65
#Sta/Elev= 30
  4665.9  329.20  4676.9  328.07  4704.3  328.67  4733.6  330.77  4739.8  329.23
  4760.2  329.33  4775.1  328.82  4798.4  328.83  4804.6  326.99  4833.9  328.15
  4854.7  326.09  4884.0  326.02  4890.2  324.53  4912.7  325.21  4925.7  317.72
  4931.2  303.61  4933.9  303.11  4937.2  303.61  5013.0  303.61  5055.3  303.75
  5061.6  313.25  5070.0  314.21  5084.6  322.69  5105.5  327.32  5139.4  327.01
  5184.9  328.73  5220.4  326.48  5255.9  330.70  5262.2  334.53  5299.3  336.69
#Mann=7,-1,0
  4665.9    0.08       0  4760.2    0.05       0  4775.1    0.16       0
  4931.2   0.033       0  4937.2    0.16       0  5013.0    0.12       0
  5139.4    0.05       0
Bank Sta=4931.2,4937.2
Exp/Cntr=0.3,0.1

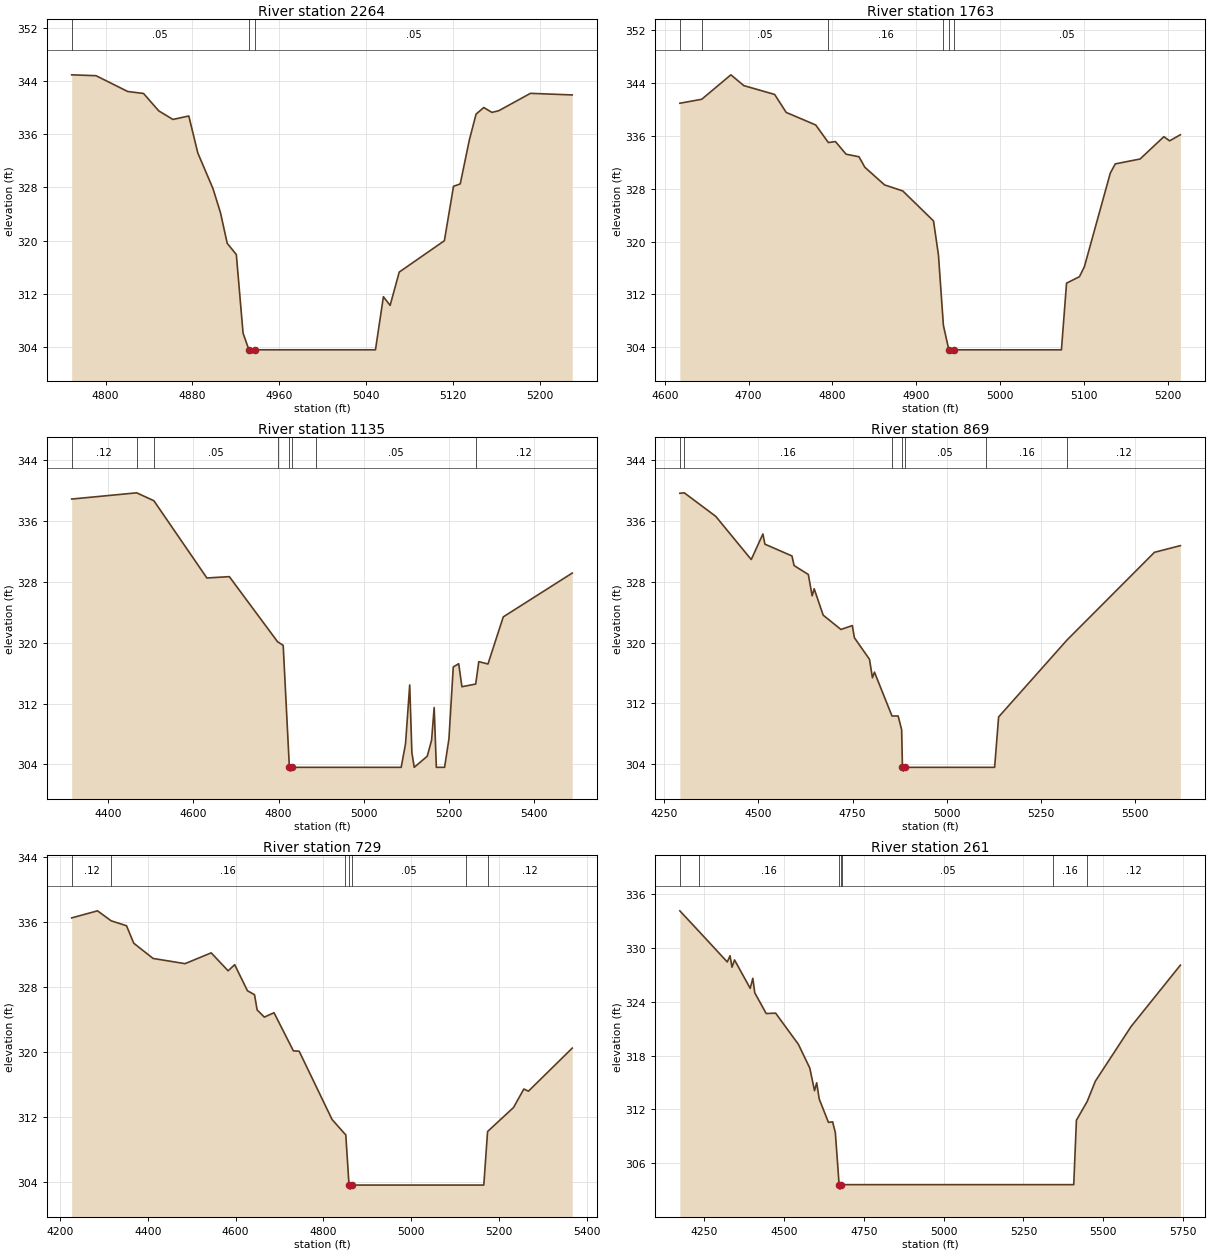
Type RM Length L Ch R = 1,2264,501,501,501
BEGIN DESCRIPTION:
UNT246 IN CCTC 5.0
END DESCRIPTION:
XS GIS Cut Line= 2
      3620536.99     10642795.89      3620261.10     10643165.47
#Sta/Elev= 30
  4768.7  344.90  4791.1  344.77  4820.3  342.40  4834.9  342.10  4848.9  339.49
  4862.0  338.20  4876.6  338.72  4884.9  333.17  4898.9  327.81  4905.8  324.19
  4912.0  319.60  4920.4  317.91  4926.6  306.11  4932.0  303.61  4934.7  303.11
  4938.0  303.61  5048.6  303.61  5055.9  311.58  5062.1  310.28  5070.5  315.28
  5112.1  319.99  5120.5  328.16  5126.7  328.52  5135.1  335.12  5141.3  339.00
  5148.4  339.99  5155.9  339.26  5162.2  339.51  5191.4  342.12  5229.9  341.88
#Mann=3,-1,0
  4768.7    0.05       0  4932.0   0.033       0  4938.0    0.05       0
Bank Sta=4932,4938
Exp/Cntr=0.3,0.1

Type RM Length L Ch R = 1,1763,628,628,628
BEGIN DESCRIPTION:
UNT246 IN CCTC 4.0
END DESCRIPTION:
XS GIS Cut Line= 2
      3620307.86     10642504.21      3619798.62     10642815.98
#Sta/Elev= 30
  4617.9  340.93  4644.0  341.53  4678.8  345.23  4694.2  343.60  4731.0  342.26
  4744.8  339.54  4780.0  337.64  4795.1  334.98  4803.5  335.13  4816.2  333.22
  4831.6  332.83  4838.6  331.24  4862.1  328.57  4883.8  327.66  4920.5  323.12
  4926.4  317.96  4932.3  307.30  4938.8  303.61  4941.6  303.11  4944.8  303.61
  5073.1  303.61  5079.2  313.70  5094.6  314.68  5100.5  316.20  5131.4  330.36
  5137.3  331.75  5166.9  332.49  5195.3  335.87  5202.1  335.24  5215.0  336.16
#Mann=6,-1,0
  4617.9    0.12       0  4644.0    0.05       0  4795.1    0.16       0
  4932.3    0.05       0  4938.8   0.033       0  4944.8    0.05       0
Bank Sta=4938.8,4944.8
Exp/Cntr=0.3,0.1

Type RM Length L Ch R = 1,1135,266,266,266
BEGIN DESCRIPTION:
UNT246 IN CCTC 3.0
END DESCRIPTION:
XS GIS Cut Line= 4
      3620260.69     10642307.20      3619715.59     10642126.66
      3619607.95     10642206.52      3619694.67     10642664.43
#Sta/Elev= 30
  4314.5  338.92  4467.0  339.74  4507.3  338.70  4631.7  328.53  4684.3  328.71
  4797.5  320.14  4810.7  319.66  4825.2  303.61  4827.9  303.11  4831.2  303.61
  4888.4  303.61  5087.5  303.61  5097.7  306.71  5107.5  314.45  5112.6  305.55
  5118.1  303.61  5148.6  305.07  5158.8  307.17  5164.9  311.48  5170.0  303.61
  5189.3  303.61  5199.5  307.34  5209.7  316.82  5222.4  317.25  5230.0  314.22
  5262.3  314.57  5269.6  317.52  5291.1  317.21  5327.0  323.41  5488.8  329.18
#Mann=8,-1,0
  4314.5    0.12       0  4467.0    0.16       0  4507.3    0.05       0
  4797.5    0.16       0  4825.2   0.033       0  4831.2    0.16       0
  4888.4    0.05       0  5262.3    0.12       0
Bank Sta=4825.2,4831.2
Exp/Cntr=0.3,0.1

Type RM Length L Ch R = 1,869,140,140,140
BEGIN DESCRIPTION:
Mapping XS 0e8fd0a6
END DESCRIPTION:
XS GIS Cut Line= 4
      3620194.74     10642140.55      3619663.50     10641921.80
      3619458.64     10641960.00      3618944.74     10642140.56
#Sta/Elev= 30
  4292.0  339.63  4303.8  339.69  4387.2  336.60  4481.4  330.92  4512.3  334.28
  4517.7  332.94  4589.5  331.39  4595.0  330.13  4632.8  328.96  4642.9  326.15
  4648.3  327.08  4672.2  323.61  4719.3  321.73  4749.5  322.24  4754.9  320.65
  4795.0  317.81  4802.8  315.38  4808.2  316.12  4854.7  310.36  4871.0  310.36
  4880.3  308.56  4882.4  303.61  4885.1  303.11  4888.4  303.61  5103.7  303.61
  5126.9  303.61  5137.5  310.23  5319.0  320.35  5550.8  331.87  5619.6  332.75
#Mann=7,-1,0
  4292.0    0.12       0  4303.8    0.16       0  4854.7    0.05       0
  4882.4   0.033       0  4888.4    0.05       0  5103.7    0.16       0
  5319.0    0.12       0
Bank Sta=4882.4,4888.4
Exp/Cntr=0.3,0.1

Type RM Length L Ch R = 1,729,468,468,468
BEGIN DESCRIPTION:
UNT246 IN CCTC 2.0
END DESCRIPTION:
XS GIS Cut Line= 3
      3620198.24     10642001.67      3619715.59     10641748.19
      3619143.61     10641911.12
#Sta/Elev= 30
  4226.8  336.54  4285.6  337.41  4316.7  336.18  4351.7  335.57  4368.1  333.42
  4412.2  331.54  4485.0  330.90  4544.5  332.23  4583.0  330.02  4598.0  330.77
  4627.1  327.56  4643.2  327.07  4649.1  325.20  4665.5  324.31  4687.6  324.85
  4731.7  320.15  4744.8  320.11  4819.8  311.69  4848.6  309.93  4851.0  309.81
  4858.4  303.61  4861.1  303.11  4864.4  303.61  5123.8  303.61  5165.3  303.61
  5173.9  310.21  5233.0  313.17  5256.5  315.45  5266.9  315.18  5366.7  320.49
#Mann=7,-1,0
  4226.8    0.12       0  4316.7    0.16       0  4848.6    0.05       0
  4858.4   0.033       0  4864.4    0.05       0  5123.8    0.16       0
  5173.9    0.12       0
Bank Sta=4858.4,4864.4
Exp/Cntr=0.3,0.1

Type RM Length L Ch R = 1,261,0,0,0
BEGIN DESCRIPTION:
UNT246 IN CCTC 1.0
END DESCRIPTION:
XS GIS Cut Line= 4
      3620059.35     10641758.62      3619451.70     10641328.05
      3619340.59     10641373.19      3619015.20     10641996.28
#Sta/Elev= 30
  4173.9  334.17  4233.8  331.88  4322.5  328.46  4331.1  329.16  4337.3  327.88
  4345.2  328.69  4394.2  325.52  4402.5  326.64  4408.6  325.02  4444.3  322.71
  4473.9  322.75  4545.2  319.27  4580.9  316.62  4595.7  314.09  4602.5  314.98
  4610.5  313.16  4639.3  310.56  4652.3  310.62  4660.9  309.42  4672.7  303.61
  4675.4  303.11  4678.7  303.61  4683.0  303.61  5341.3  303.61  5407.5  303.61
  5415.9  310.80  5449.7  312.90  5475.2  315.16  5586.9  321.25  5741.5  328.11
#Mann=7,-1,0
  4173.9    0.12       0  4233.8    0.16       0  4672.7   0.033       0
  4678.7    0.16       0  4683.0    0.05       0  5341.3    0.16       0
  5449.7    0.12       0
Bank Sta=4672.7,4678.7
Exp/Cntr=0.3,0.1

Chan Stop Cuts=-1