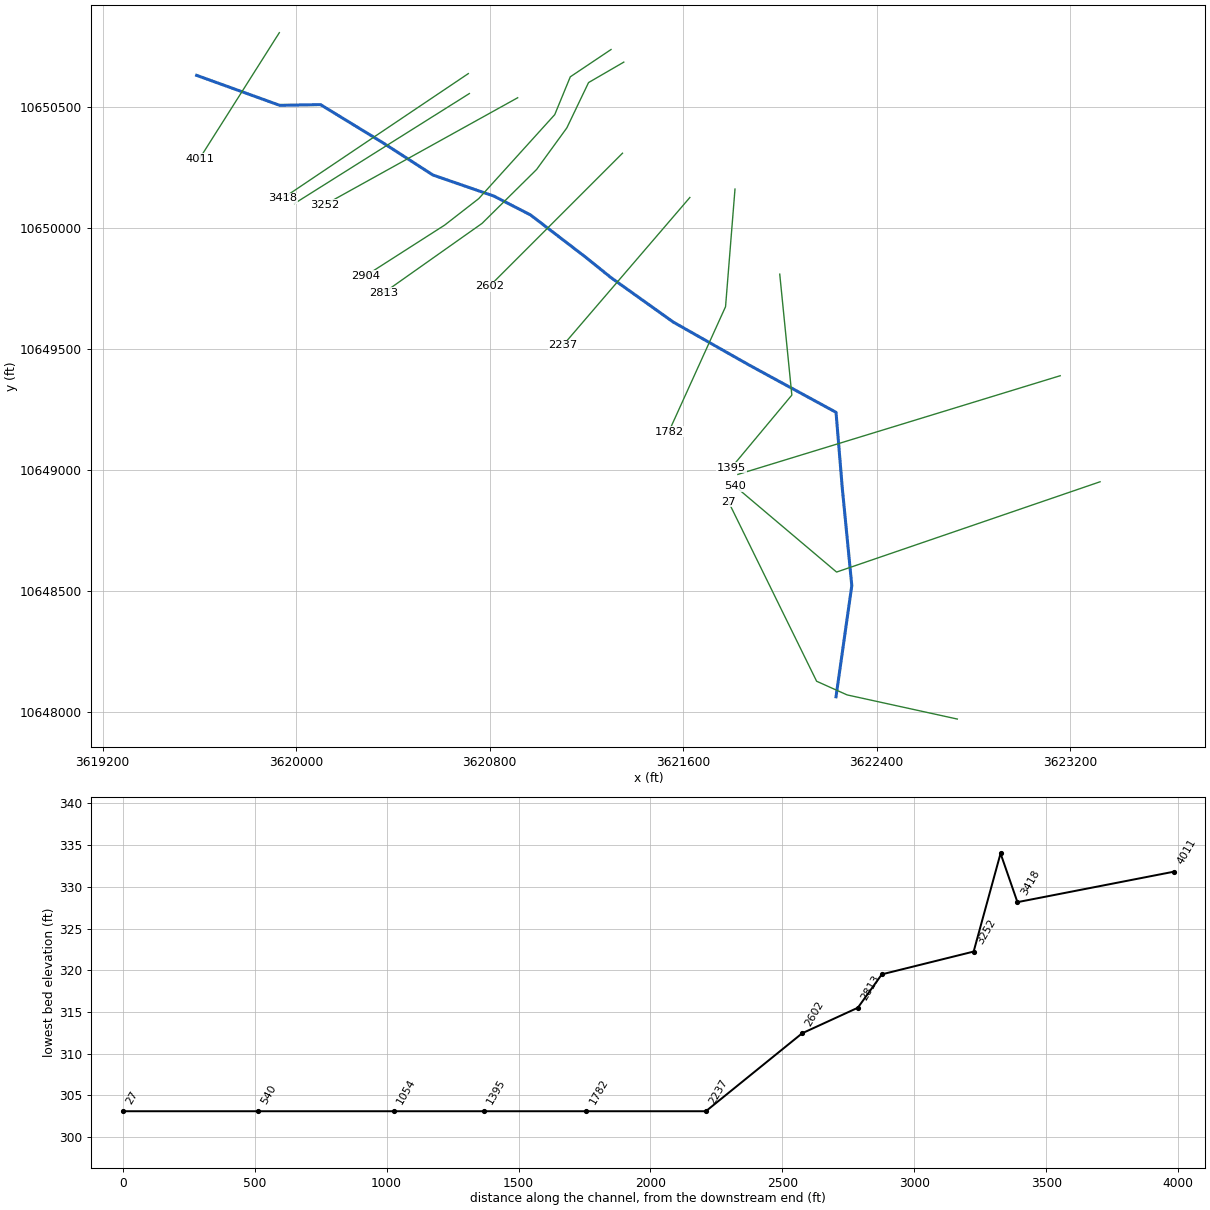
--- UNT247 IN CCTC.prj (project) ---

Proj Title=UNT247 IN CCTC Base Level Engineering
Current Plan=p01
Default Exp/Contr=0.3,0.1
English Units
Geom File=g01
Flow File=f01
Plan File=p01
Y Axis Title=Elevation
X Axis Title(PF)=Main Channel Distance
X Axis Title(XS)=Station
BEGIN DESCRIPTION:
UNT247 IN CCTC
END DESCRIPTION:
DSS Export Rating Curves= 0
DSS Export Rating Curve Sorted= 0
DSS Export Volume Flow Curves= 0
DXF OffsetX= 0
DXF OffsetY= 0
DXF ScaleX= 1
DXF ScaleY= 10

--- UNT247 IN CCTC.p01 (plan) ---

Plan Title=Multiple Run
Short Identifier=Multiple
Geom File=g01
Flow File=f01
Subcritical Flow
K Sum by GR= 0
Std Step Tol= 0.01
Critical Tol= 0.01
Num of Std Step Trials= 20
Max Error Tol= 0.3
Flow Tol Ratio= 0.001
Split Flow NTrial= 30
Split Flow Tol= 0.02
Split Flow Ratio= 0.02
Log Output Level= 0
Friction Slope Method= 1
Unsteady Friction Slope Method= 2
Unsteady Bridges Friction Slope Method= 1
Parabolic Critical Depth
Global Vel Dist=  1 , 1 , 1
Global Log Level= 0
CheckData=True
Encroach Param= -1, 0, 0, 0
BEGIN DESCRIPTION:
Multiple Run
END DESCRIPTION:

--- UNT247 IN CCTC.f01 (steady flow) ---

Flow Title=Multiple
Number of Profiles=7
Profile Names=10-year,25-year,50-year,1pct_min,100-year,1pct_plu,500-year
River Rch & RM= UNT247 IN CCTC,Reach-1,4011
     659     866    1031     899    1215    1644    1680
Boundary for River Rch & Prof#=UNT247 IN CCTC,Reach-1,1
Up Type=0
Dn Type=3
Dn Slope=0.005
Boundary for River Rch & Prof#=UNT247 IN CCTC,Reach-1,2
Up Type=0
Dn Type=3
Dn Slope=0.005
Boundary for River Rch & Prof#=UNT247 IN CCTC,Reach-1,3
Up Type=0
Dn Type=3
Dn Slope=0.005
Boundary for River Rch & Prof#=UNT247 IN CCTC,Reach-1,4
Up Type=0
Dn Type=3
Dn Slope=0.005
Boundary for River Rch & Prof#=UNT247 IN CCTC,Reach-1,5
Up Type=0
Dn Type=3
Dn Slope=0.005
Boundary for River Rch & Prof#=UNT247 IN CCTC,Reach-1,6
Up Type=0
Dn Type=3
Dn Slope=0.005
Boundary for River Rch & Prof#=UNT247 IN CCTC,Reach-1,7
Up Type=0
Dn Type=3
Dn Slope=0.005

--- UNT247 IN CCTC.g01 (geometry) ---

Geom Title=Existing Conditions
Program Version=4.10

River Reach=UNT247 IN CCTC  ,Reach-1
Reach XY= 15
        3619589.       10650632.       3619932.5       10650508.
      3620101.25       10650511.        3620358.       10650354.
      3620565.75       10650220.       3620817.5       10650133.
      3620969.25       10650055.        3621195.       10649882.
      3621301.75       10649796.       3621559.5       10649612.
        3621872.       10649435.      3622232.25       10649239.
       3622258.5       10648922.       3622297.5       10648523.
      3622232.25       10648063.

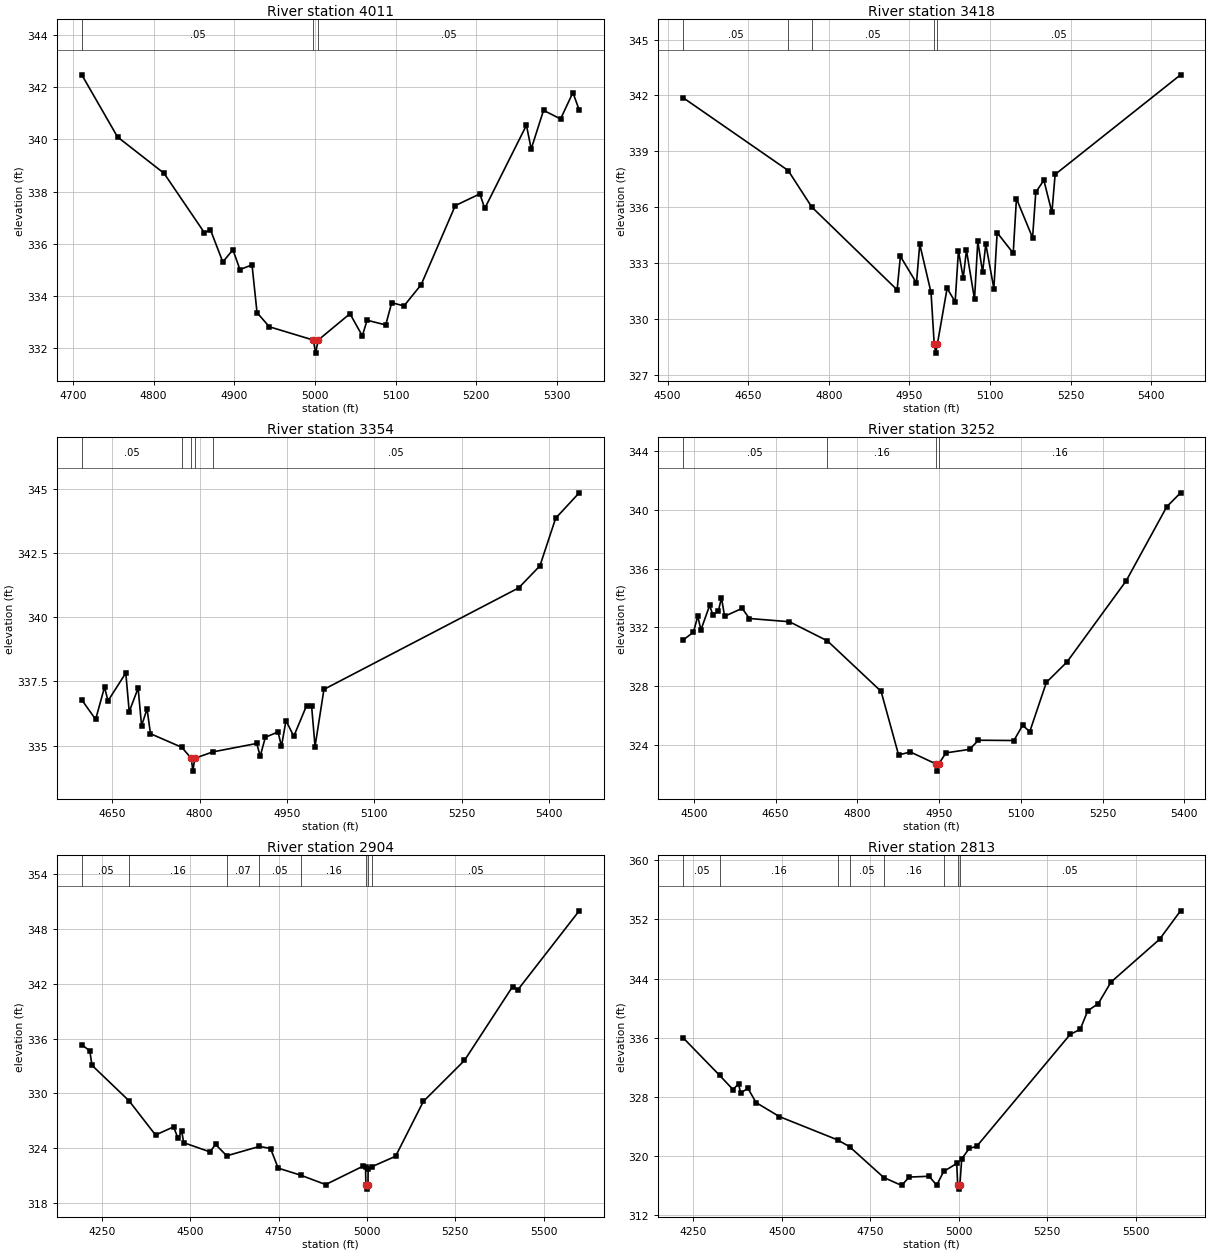
Type RM Length L Ch R = 1 ,4011    ,593,593,593
BEGIN DESCRIPTION:
UNT247 IN CCTC 8.0
END DESCRIPTION:
XS GIS Cut Line= 2
      3619930.93     10650808.44      3619601.07     10650287.61
#Sta/Elev= 30
  4711.1  342.47  4755.4  340.09    4813   338.7  4862.9  336.43  4870.6  336.53
  4885.9   335.3  4898.4  335.77  4907.1  335.01  4922.1  335.19  4928.3  333.36
  4943.5  332.82  4998.1  332.31  5000.9  331.81  5004.1  332.31  5043.5  333.32
  5058.8  332.47  5064.7  333.07  5087.8  332.89  5095.2  333.74  5110.5  333.62
  5131.7  334.43    5174  337.46  5204.5  337.91  5210.5  337.35  5262.2  340.54
  5268.1  339.63  5283.4  341.11  5304.5  340.78  5319.8  341.79  5327.6  341.12
#Mann= 3 ,-1 , 0
  4711.1     .05       0  4998.1     .03       0  5004.1     .05       0
Bank Sta=4998.1,5004.1
XS Rating Curve= 0 ,0
Exp/Cntr=0.3,0.1

Type RM Length L Ch R = 1 ,3418    ,64,64,64
BEGIN DESCRIPTION:
UNT247 IN CCTC 7.0
END DESCRIPTION:
XS GIS Cut Line= 2
      3620712.22      10650639.2      3619944.25     10650122.89
#Sta/Elev= 30
    4529  341.88  4724.4  337.97  4768.3  336.01  4927.1  331.56  4933.2  333.36
  4963.1  331.93  4969.2  334.01  4990.2  331.42  4996.1  328.66  4998.9  328.16
  5002.1  328.66  5020.1  331.64  5035.1  330.92  5041.2  333.66  5050.1   332.2
  5056.1  333.69  5071.1  331.05  5077.2  334.17  5086.1  332.51  5092.1  334.02
  5107.1  331.63  5113.2  334.63  5143.1  333.53  5149.1  336.46  5179.1  334.36
  5185.1   336.8  5200.1  337.45  5215.1  335.72  5221.1  337.76  5454.4  343.11
#Mann= 5 ,-1 , 0
    4529     .05       0  4724.4     .16       0  4768.3     .05       0
  4996.1     .03       0  5002.1     .05       0
Bank Sta=4996.1,5002.1
XS Rating Curve= 0 ,0
Exp/Cntr=0.3,0.1

Type RM Length L Ch R = 1 ,3354    ,102,102,102
BEGIN DESCRIPTION:
Mapping XS 2df97946
END DESCRIPTION:
XS GIS Cut Line= 2
      3620716.57     10650556.74      3619993.17     10650101.92
#Sta/Elev= 30
  4597.5  336.78  4621.3  336.02  4636.6  337.28  4642.5  336.74  4673.1  337.83
    4679  336.32  4694.3  337.24  4700.2  335.77  4709.6  336.43  4715.5  335.46
  4769.2  334.93  4785.6   334.5  4788.3     334  4791.6   334.5  4822.6  334.75
  4898.1  335.08    4904  334.58  4912.8  335.32  4934.6  335.53  4940.5  334.97
  4948.3  335.97  4961.7  335.36  4983.7  336.56  4992.3  336.54  4998.2  334.96
  5013.5  337.19    5348  341.15  5384.5  342.01  5411.6  343.87    5452  344.86
#Mann= 5 ,-1 , 0
  4597.5     .05       0  4769.2     .16       0  4785.6     .03       0
  4791.6     .16       0  4822.6     .05       0
Bank Sta=4785.6,4791.6
XS Rating Curve= 0 ,0
Exp/Cntr=0.3,0.1

Type RM Length L Ch R = 1 ,3252    ,348,348,348
BEGIN DESCRIPTION:
Mapping XS 588eac9e
END DESCRIPTION:
XS GIS Cut Line= 2
      3620916.15     10650539.34      3620117.55     10650096.64
#Sta/Elev= 30
  4480.1  331.15    4499  331.68    4507  332.77  4512.7  331.83  4528.8   333.5
  4534.5  332.87  4544.8  333.12  4550.5  334.02  4556.2  332.76  4588.3   333.3
  4601.9  332.61  4675.3  332.39    4745  331.09  4843.5  327.66  4875.6  323.34
  4897.3  323.54  4943.5  322.74  4946.3  322.24  4949.5  322.74  4962.6  323.48
  5006.1  323.72  5022.1  324.34  5087.3  324.32  5103.4  325.36  5116.4  324.92
  5146.9  328.27  5184.6  329.65  5293.4  335.17    5368  340.21  5393.2  341.15
#Mann= 4 ,-1 , 0
  4480.1     .05       0    4745     .16       0  4943.5     .03       0
  4949.5     .16       0
Bank Sta=4943.5,4949.5
XS Rating Curve= 0 ,0
Exp/Cntr=0.3,0.1

Type RM Length L Ch R = 1 ,2904    ,91,91,91
BEGIN DESCRIPTION:
Mapping XS fd84a018
END DESCRIPTION:
XS GIS Cut Line= 6
      3621302.18     10650738.75      3621133.75     10650625.88
      3621069.51     10650469.63      3620755.28     10650122.41
      3620614.65     10650013.04      3620286.52     10649802.96
#Sta/Elev= 30
  4192.8  335.34  4215.6  334.65  4221.6  333.08  4326.7  329.18  4401.5  325.44
  4452.7  326.33  4465.2  325.07  4475.7  325.86  4481.2   324.6  4555.6  323.59
  4571.5  324.41  4603.1  323.16  4695.8  324.19  4727.1  323.96  4748.8  321.81
    4813  321.03  4883.2  320.01  4989.2  322.03    4996  321.96    4997  320.01
  4999.8  319.51    5003  320.01  5003.4  321.75  5014.8  321.98  5081.1  323.11
  5159.8  329.12  5276.1  333.61  5412.2  341.69  5427.5  341.36  5600.9     350
#Mann= 8 ,-1 , 0
  4192.8     .05       0  4326.7     .16       0  4603.1     .07       0
  4695.8     .05       0    4813     .16       0    4997     .07       0
    5003     .16       0  5014.8     .05       0
Bank Sta=4997,5003
XS Rating Curve= 0 ,0
Exp/Cntr=0.3,0.1

Type RM Length L Ch R = 1 ,2813    ,211,211,211
BEGIN DESCRIPTION:
Mapping XS d12c6ffa
END DESCRIPTION:
XS GIS Cut Line= 6
        3621355.     10650686.71       3621209.2     10650602.09
      3621119.35     10650414.59      3620994.35     10650242.71
      3620769.09     10650020.05      3620363.03     10649733.27
#Sta/Elev= 30
  4221.7  335.98  4324.6  330.91  4362.5  328.98  4378.2  329.75  4384.1   328.5
  4404.6  329.16  4427.6  327.22  4493.7  325.32  4658.3  322.16  4691.6  321.25
  4788.3  317.08  4838.6  316.01  4859.9  317.14  4916.4  317.25  4937.6  316.03
  4957.3   317.9  4994.2  318.98    4997  316.01  4999.8  315.51    5003  316.01
  5008.3   319.6  5029.6  321.02  5050.7   321.3  5314.3  336.43  5343.1  337.14
    5364  339.63  5393.8   340.6  5429.6  343.51  5566.8   349.3  5626.2  353.16
#Mann= 8 ,-1 , 0
  4221.7     .05       0  4324.6     .16       0  4658.3     .07       0
  4691.6     .05       0  4788.3     .16       0  4957.3     .05       0
    4997     .03       0    5003     .05       0
Bank Sta=4997,5003
XS Rating Curve= 0 ,0
Exp/Cntr=0.3,0.1

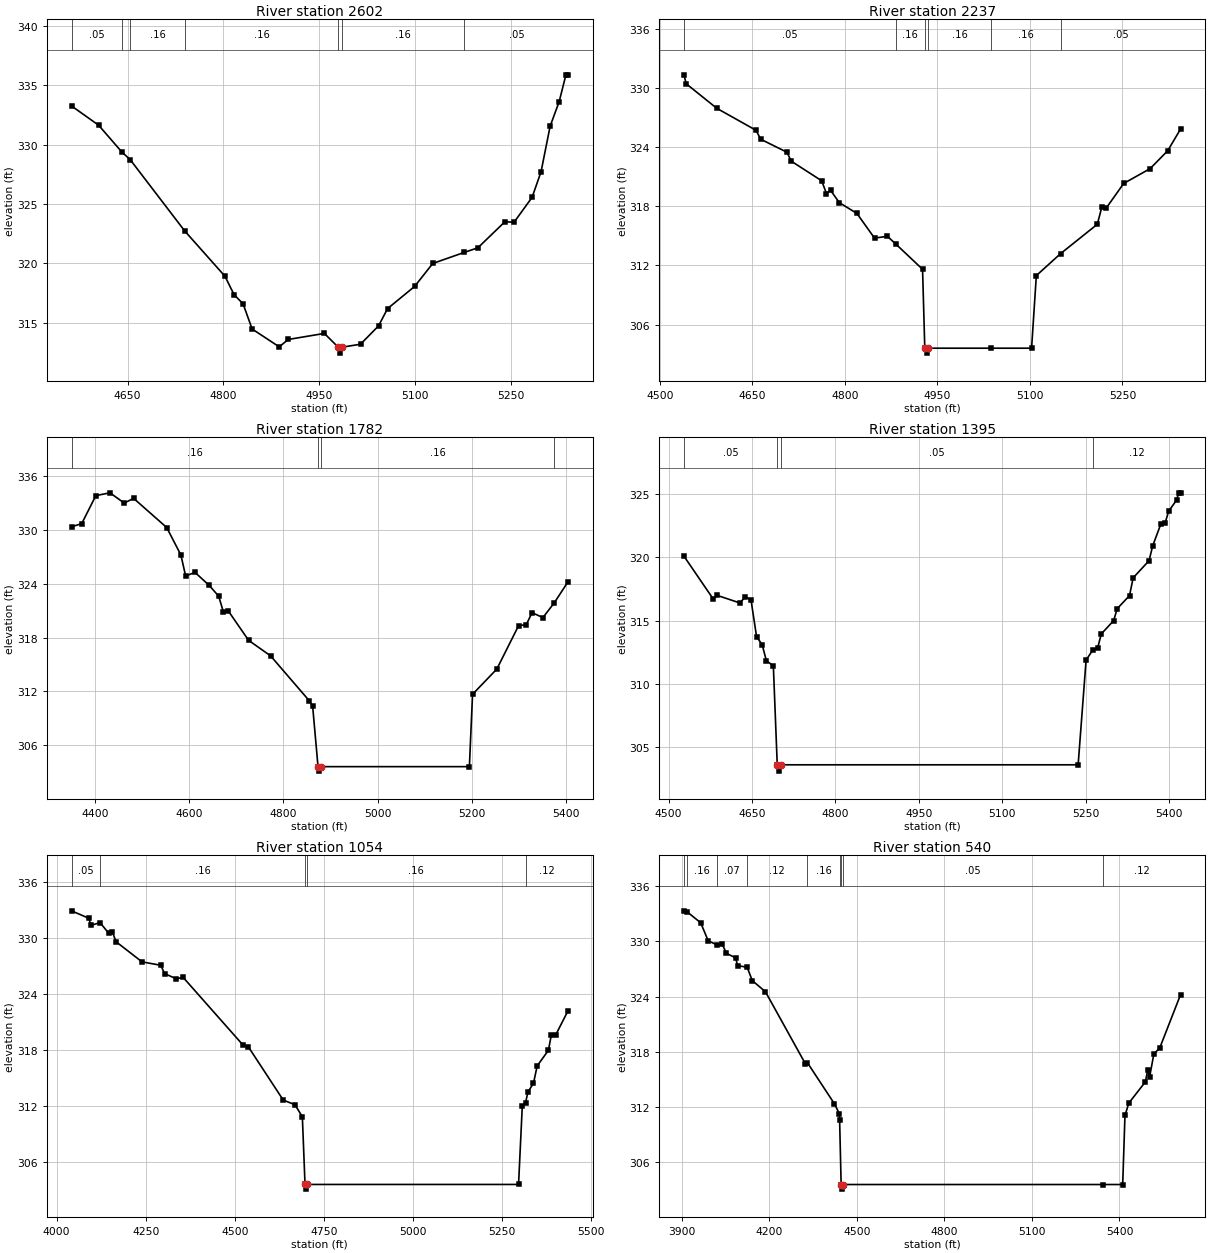
Type RM Length L Ch R = 1 ,2602    ,365,365,365
BEGIN DESCRIPTION:
UNT247 IN CCTC 6.0
END DESCRIPTION:
XS GIS Cut Line= 3
      3621349.62     10650310.19      3621049.61     10650010.19
      3620799.63     10649760.21
#Sta/Elev= 30
  4562.3  333.27  4604.7  331.65    4641   329.4  4654.3  328.74  4739.6  322.74
  4802.7  318.92  4816.9  317.37    4831   316.6  4845.2  314.48  4887.6  312.98
  4901.7   313.6  4958.3  314.11    4980  312.95  4982.8  312.45    4986  312.95
  5014.9   313.2  5043.1  314.74  5057.3   316.2  5099.7  318.07    5128     320
  5177.7  320.94  5198.7  321.32  5241.1  323.52  5255.3  323.47  5283.6  325.57
  5297.7  327.74  5311.8  331.55    5326  333.63  5336.6  335.89  5340.1  335.89
#Mann= 7 ,-1 , 0
  4562.3     .05       0    4641     .07       0  4654.3     .16       0
  4739.6     .16       0    4980     .07       0    4986     .16       0
  5177.7     .05       0
Bank Sta=4980,4986
XS Rating Curve= 0 ,0
Exp/Cntr=0.3,0.1

Type RM Length L Ch R = 1 ,2237    ,455,455,455
BEGIN DESCRIPTION:
UNT247 IN CCTC 5.0
END DESCRIPTION:
XS GIS Cut Line= 2
      3621627.98     10650127.03      3621103.74     10649516.13
#Sta/Elev= 30
  4539.2  331.32    4543  330.41  4592.4  327.93    4656   325.7  4663.7  324.79
  4706.3  323.47  4713.1  322.57  4762.5  320.58  4770.2  319.29  4776.8  319.62
    4791  318.37  4819.6  317.27  4848.1  314.77    4869  314.95  4882.4  314.18
    4926  311.61  4929.6  303.61  4932.4  303.11  4935.6  303.61  5036.7  303.61
  5102.7  303.61  5110.4  310.97  5149.8   313.2  5209.2  316.17  5216.8  317.97
  5223.4  317.79    5252  320.31  5294.8  321.81  5323.3  323.62  5344.2  325.83
#Mann= 6 ,-1 , 0
  4539.2     .05       0  4882.4     .16       0  4929.6     .07       0
  4935.6     .16       0  5036.7     .16       0  5149.8     .05       0
Bank Sta=4929.6,4935.6
XS Rating Curve= 0 ,0
Exp/Cntr=0.3,0.1

Type RM Length L Ch R = 1 ,1782    ,387,387,387
BEGIN DESCRIPTION:
UNT247 IN CCTC 4.0
END DESCRIPTION:
XS GIS Cut Line= 3
      3621814.62     10650161.77      3621775.56     10649675.64
      3621541.17     10649159.13
#Sta/Elev= 30
  4349.8  330.37  4371.5  330.72  4401.5  333.85  4431.6  334.16  4461.7  333.02
  4481.8  333.54    4552  330.29  4582.1  327.23  4592.2  324.89  4612.2  325.28
  4642.3  323.83  4662.4  322.63  4672.4  320.87  4682.5  321.01    4726   317.7
  4772.7  315.97  4854.5  310.98    4862  310.35  4873.4  303.61  4876.2  303.11
  4879.4  303.61  5194.9  303.61  5201.6  311.68  5253.2   314.5  5299.4  319.34
  5315.7  319.45    5328  320.79  5351.1  320.24  5375.2  321.89  5404.7  324.26
#Mann= 4 ,-1 , 0
  4349.8     .16       0  4873.4     .07       0  4879.4     .16       0
  5375.2     .16       0
Bank Sta=4873.4,4879.4
XS Rating Curve= 0 ,0
Exp/Cntr=0.3,0.1

Type RM Length L Ch R = 1 ,1395    ,341,341,341
BEGIN DESCRIPTION:
UNT247 IN CCTC 3.0
END DESCRIPTION:
XS GIS Cut Line= 3
      3621999.61     10649810.15      3622049.61     10649310.19
      3621799.59     10649010.16
#Sta/Elev= 30
  4527.5   320.1  4580.2  316.71  4587.8  316.99    4628   316.4    4638  316.88
  4648.1  316.65  4658.1  313.74  4668.2   313.1  4675.7  311.84  4688.3  311.42
  4695.3  303.61  4698.1  303.11  4701.3  303.61  5236.3  303.61  5250.6  311.88
  5263.1  312.71  5271.4  312.84  5277.9  313.95  5300.1     315  5306.6  315.95
  5328.7  316.98  5335.2  318.38  5363.8  319.74  5370.3   320.9  5384.7   322.6
  5392.5  322.69    5399  323.64  5413.3  324.53  5417.2   325.1  5420.5   325.1
#Mann= 4 ,-1 , 0
  4527.5     .05       0  4695.3    .033       0  4701.3     .05       0
  5263.1     .12       0
Bank Sta=4695.3,4701.3
XS Rating Curve= 0 ,0
Exp/Cntr=0.3,0.1

Type RM Length L Ch R = 1 ,1054    ,514,514,514
BEGIN DESCRIPTION:
Mapping XS 48a02898
END DESCRIPTION:
XS GIS Cut Line= 2
      3623158.97     10649390.26      3621826.53     10648982.28
#Sta/Elev= 30
    4042  332.87  4090.9  332.07  4096.2  331.31    4122  331.61  4145.9   330.5
  4156.4  330.65  4166.9  329.57    4240  327.41  4292.3  327.05  4303.2  326.16
    4336   325.6  4355.1  325.76  4522.4  318.55  4537.8  318.35  4636.1  312.63
  4668.8  312.14  4689.7  310.85  4697.2  303.61    4700  303.11  4703.2  303.61
  5296.3  303.61  5306.8     312  5315.8  312.34  5322.8  313.51  5338.2  314.43
  5348.6  316.29    5380  317.95  5388.3   319.6  5400.9  319.63  5435.5  322.21
#Mann= 5 ,-1 , 0
    4042     .05       0    4122     .16       0  4697.2    .033       0
  4703.2     .16       0  5315.8     .12       0
Bank Sta=4697.2,4703.2
XS Rating Curve= 0 ,0
Exp/Cntr=0.3,0.1

Type RM Length L Ch R = 1 ,540     ,513,513,513
BEGIN DESCRIPTION:
UNT247 IN CCTC 2.0
END DESCRIPTION:
XS GIS Cut Line= 3
      3623323.91     10648951.89      3622234.54     10648578.64
      3621814.08     10648934.08
#Sta/Elev= 30
  3907.3  333.31  3917.7  333.21  3964.7  332.02  3990.4  330.06  4020.9  329.61
  4038.7  329.68    4053  328.69  4084.2  328.22  4091.5  327.36  4124.1  327.19
  4141.5  325.74  4186.7  324.53  4323.9  316.69  4330.5  316.83  4423.1  312.37
  4440.4  311.27  4440.9   310.6  4446.1  303.61  4448.8  303.11  4452.1  303.61
  5344.3  303.61    5411  303.61  5418.8   311.1  5431.9  312.44    5489  314.76
  5496.8  316.09  5503.3  315.28  5517.6  317.75  5538.5  318.47  5609.4  324.22
#Mann= 9 ,-1 , 0
  3907.3     .07       0  3917.7     .16       0  4020.9     .07       0
  4124.1     .12       0  4330.5     .16       0  4440.9     .05       0
  4446.1    .033       0  4452.1     .05       0  5344.3     .12       0
Bank Sta=4446.1,4452.1
XS Rating Curve= 0 ,0
Exp/Cntr=0.3,0.1

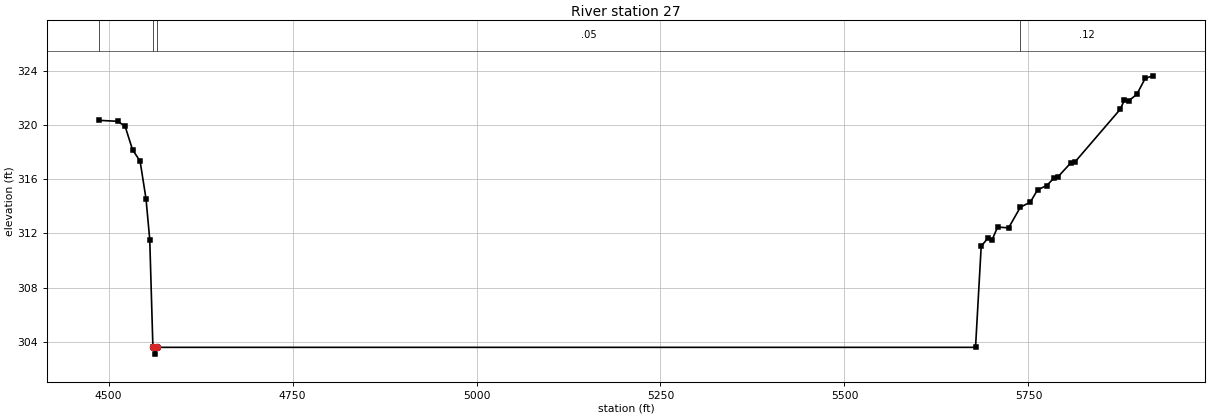
Type RM Length L Ch R = 1 ,27      ,0,0,0
BEGIN DESCRIPTION:
UNT247 IN CCTC 1.0
END DESCRIPTION:
XS GIS Cut Line= 4
       3622733.7     10647970.99      3622277.94     10648070.82
      3622152.07     10648127.25      3621787.49     10648869.44
#Sta/Elev= 30
  4487.5  320.33  4512.2  320.26  4522.4  319.91  4532.6  318.17  4542.9  317.32
  4550.9  314.56    4556  311.55  4560.3  303.61  4563.1  303.11  4566.3  303.61
  5678.1  303.61  5685.8  311.06    5695  311.66  5700.6  311.53  5708.1  312.47
    5723  312.41    5739  313.93  5752.6  314.31  5762.4  315.21  5774.9  315.53
  5784.9  316.09  5790.5  316.19  5807.4  317.19    5813  317.25  5874.8  321.15
  5880.4  321.83  5886.3  321.77  5897.3  322.25  5908.6  323.42  5918.9  323.61
#Mann= 4 ,-1 , 0
  4487.5     .05       0  4560.3    .033       0  4566.3     .05       0
    5739     .12       0
Bank Sta=4560.3,4566.3
XS Rating Curve= 0 ,0
Exp/Cntr=0.3,0.1

Chan Stop Cuts=-1
Use User Specified Reach Order=0
Composite Channel Slope=5