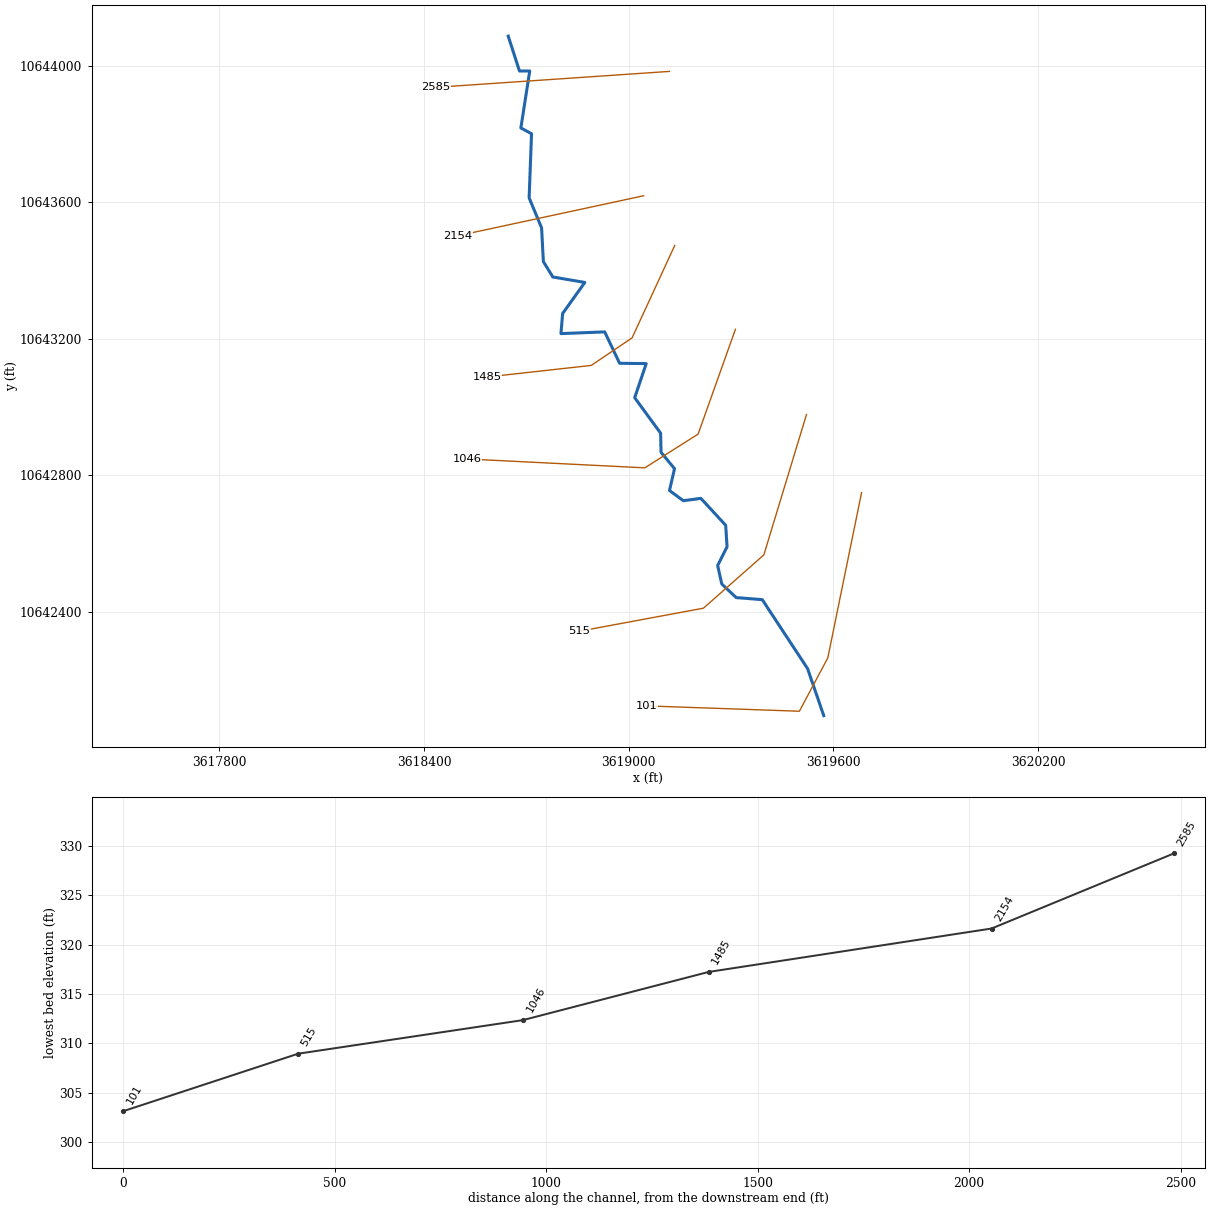
--- UNT248 IN CCTC.prj (project) ---

Proj Title=UNT248 IN CCTC Base Level Engineering
Current Plan=p01
Default Exp/Contr=0.3,0.1
English Units
Geom File=g01
Flow File=f01
Plan File=p01
BEGIN DESCRIPTION:
UNT248 IN CCTC
END DESCRIPTION:

--- UNT248 IN CCTC.p01 (plan) ---

Plan Title=Multiple Run
Short Identifier=Multiple
Geom File=g01
Flow File=f01
Subcritical Flow
K Sum by GR= 0
Std Step Tol= 0.01
Critical Tol= 0.01
Num of Std Step Trials= 20
Max Error Tol= 0.3
Flow Tol Ratio= 0.001
Split Flow NTrial= 30
Split Flow Tol= 0.02
Split Flow Ratio= 0.02
Log Output Level= 0
Friction Slope Method= 1
Unsteady Friction Slope Method= 2
Unsteady Bridges Friction Slope Method= 1
Parabolic Critical Depth
Global Vel Dist=  1 , 1 , 1
Global Log Level= 0
CheckData=True
Encroach Param= -1, 0, 0, 0
BEGIN DESCRIPTION:
Multiple Run
END DESCRIPTION:

--- UNT248 IN CCTC.f01 (steady flow) ---

Flow Title=Multiple
Number of Profiles=7
Profile Names=10-year,25-year,50-year,1pct_min,100-year,1pct_plu,500-year
River Rch & RM= UNT248 IN CCTC,Reach-1,2585
     446     574     673     579     783    1060    1054
Boundary for River Rch & Prof#=UNT248 IN CCTC,Reach-1,1
Up Type=0
Dn Type=3
Dn Slope=0.005
Boundary for River Rch & Prof#=UNT248 IN CCTC,Reach-1,2
Up Type=0
Dn Type=3
Dn Slope=0.005
Boundary for River Rch & Prof#=UNT248 IN CCTC,Reach-1,3
Up Type=0
Dn Type=3
Dn Slope=0.005
Boundary for River Rch & Prof#=UNT248 IN CCTC,Reach-1,4
Up Type=0
Dn Type=3
Dn Slope=0.005
Boundary for River Rch & Prof#=UNT248 IN CCTC,Reach-1,5
Up Type=0
Dn Type=3
Dn Slope=0.005
Boundary for River Rch & Prof#=UNT248 IN CCTC,Reach-1,6
Up Type=0
Dn Type=3
Dn Slope=0.005
Boundary for River Rch & Prof#=UNT248 IN CCTC,Reach-1,7
Up Type=0
Dn Type=3
Dn Slope=0.005

--- UNT248 IN CCTC.g01 (geometry) ---

Geom Title=Existing Conditions

River Reach=UNT248 IN CCTC,Reach-1
Reach XY= 30
      3618646.67     10644087.23      3618679.70     10643984.79
      3618709.75     10643985.00      3618683.75     10643818.00
      3618715.00     10643801.00      3618708.00     10643613.00
      3618744.50     10643525.00      3618749.75     10643426.00
      3618777.50     10643381.00      3618871.25     10643365.00
      3618806.25     10643274.00      3618801.25     10643215.00
      3618929.50     10643220.00      3618973.25     10643128.00
      3619051.25     10643127.00      3619017.50     10643027.00
      3619093.50     10642923.00      3619094.75     10642867.00
      3619134.25     10642819.00      3619119.50     10642755.00
      3619160.00     10642725.00      3619211.50     10642732.00
      3619284.25     10642653.00      3619288.25     10642590.00
      3619260.75     10642535.00      3619272.75     10642481.00
      3619315.00     10642441.00      3619391.50     10642435.00
      3619524.25     10642233.00      3619571.75     10642095.00

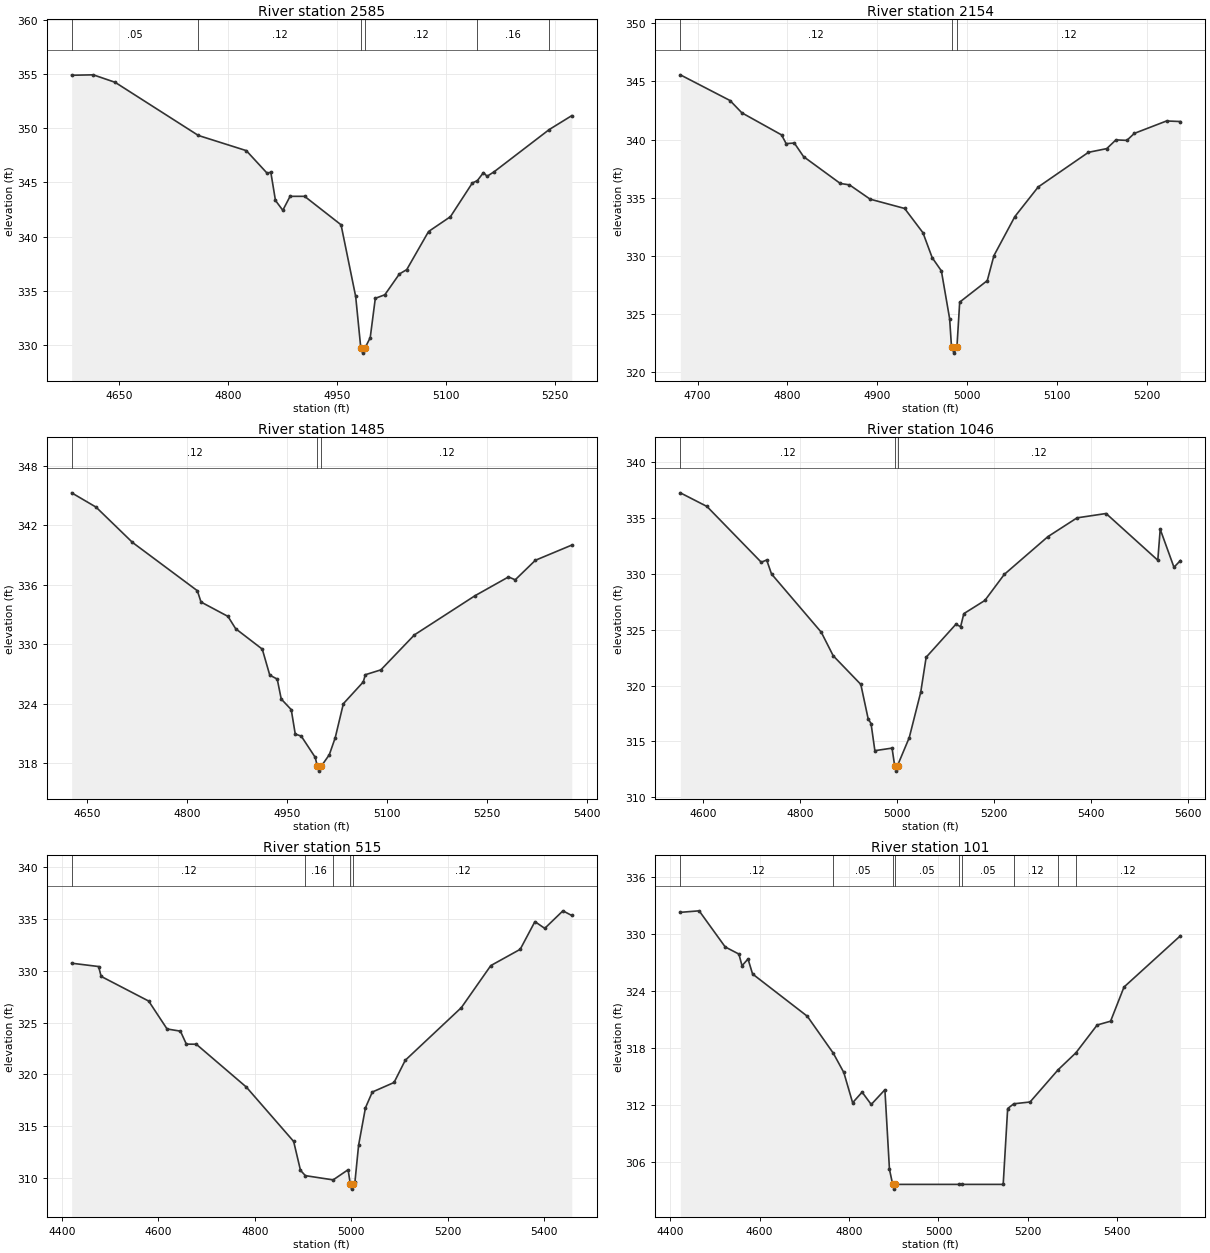
Type RM Length L Ch R = 1,2585,431,431,431
BEGIN DESCRIPTION:
UNT248 IN CCTC 5.0
END DESCRIPTION:
XS GIS Cut Line= 2
      3619119.19     10643983.72      3618433.19     10643936.95
#Sta/Elev= 30
  4585.0  354.89  4614.7  354.93  4644.7  354.24  4759.2  349.33  4825.1  347.93
  4853.8  345.84  4858.8  345.94  4865.2  343.33  4875.3  342.42  4885.3  343.71
  4905.3  343.71  4955.4  341.08  4975.5  334.46  4982.5  329.73  4985.3  329.23
  4988.5  329.73  4995.5  330.66  5002.5  334.29  5015.6  334.62  5035.6  336.54
  5045.7  336.94  5075.7  340.46  5105.8  341.83  5135.9  344.94  5142.8  345.16
  5151.2  345.90  5156.2  345.56  5165.9  345.98  5241.7  349.88  5272.6  351.16
#Mann=6,-1,0
  4585.0    0.05       0  4759.2    0.12       0  4982.5    0.07       0
  4988.5    0.12       0  5142.8    0.16       0  5241.7    0.05       0
Bank Sta=4982.5,4988.5
Exp/Cntr=0.3,0.1

Type RM Length L Ch R = 1,2154,669,669,669
BEGIN DESCRIPTION:
Mapping XS 9b2e1632
END DESCRIPTION:
XS GIS Cut Line= 2
      3619043.69     10643619.13      3618499.46     10643501.96
#Sta/Elev= 30
  4680.7  345.57  4736.0  343.36  4749.2  342.30  4793.4  340.40  4798.5  339.65
  4807.6  339.70  4817.9  338.53  4858.8  336.22  4869.0  336.10  4892.0  334.87
  4930.4  334.07  4950.8  331.98  4961.1  329.83  4971.3  328.70  4980.5  324.58
  4982.6  322.12  4985.3  321.62  4988.6  322.12  4991.7  326.01  5022.4  327.86
  5029.8  330.01  5053.1  333.37  5079.1  335.92  5135.0  338.90  5155.4  339.22
  5165.6  339.97  5177.8  339.93  5186.1  340.53  5222.0  341.60  5237.4  341.55
#Mann=3,-1,0
  4680.7    0.12       0  4982.6    0.07       0  4988.6    0.12       0
Bank Sta=4982.6,4988.6
Exp/Cntr=0.3,0.1

Type RM Length L Ch R = 1,1485,439,439,439
BEGIN DESCRIPTION:
UNT248 IN CCTC 4.0
END DESCRIPTION:
XS GIS Cut Line= 4
      3619134.86     10643473.31      3619009.86     10643202.47
      3618890.07     10643121.74      3618585.39     10643087.89
#Sta/Elev= 30
  4627.3  345.28  4663.8  343.84  4718.4  340.28  4815.6  335.41  4821.1  334.27
  4861.5  332.82  4873.0  331.58  4912.9  329.52  4924.1  326.90  4935.3  326.50
  4941.3  324.49  4956.3  323.42  4962.3  320.96  4971.3  320.75  4992.3  318.60
  4995.3  317.72  4998.0  317.22  5001.3  317.72  5013.3  318.87  5022.2  320.59
  5034.4  324.02  5064.2  326.21  5067.3  326.94  5090.6  327.43  5140.9  330.96
  5231.5  334.90  5281.8  336.80  5291.9  336.51  5322.1  338.48  5376.6  340.01
#Mann=3,-1,0
  4627.3    0.12       0  4995.3    0.07       0  5001.3    0.12       0
Bank Sta=4995.3,5001.3
Exp/Cntr=0.3,0.1

Type RM Length L Ch R = 1,1046,531,531,531
BEGIN DESCRIPTION:
UNT248 IN CCTC 3.0
END DESCRIPTION:
XS GIS Cut Line= 4
      3619312.80     10643227.63      3619203.43     10642920.35
      3619047.18     10642821.40      3618526.34     10642847.44
#Sta/Elev= 30
  4552.5  337.24  4607.5  336.02  4719.6  331.03  4730.8  331.23  4740.8  329.98
  4843.5  324.77  4868.2  322.66  4925.2  320.10  4940.4  317.01  4946.3  316.60
  4954.2  314.17  4989.7  314.40  4995.0  312.84  4997.8  312.34  5001.0  312.84
  5025.2  315.34  5048.9  319.40  5060.1  322.53  5121.3  325.47  5131.3  325.27
  5137.9  326.43  5181.3  327.61  5221.4  329.94  5311.5  333.32  5371.6  335.00
  5431.6  335.39  5538.4  331.21  5543.4  333.98  5571.8  330.58  5585.1  331.18
#Mann=3,-1,0
  4552.5    0.12       0  4995.0    0.07       0  5001.0    0.12       0
Bank Sta=4995,5001
Exp/Cntr=0.3,0.1

Type RM Length L Ch R = 1,515,414,414,414
BEGIN DESCRIPTION:
UNT248 IN CCTC 2.0
END DESCRIPTION:
XS GIS Cut Line= 4
      3619521.15     10642977.67      3619396.14     10642566.19
      3619219.06     10642409.94      3618854.51     10642342.24
#Sta/Elev= 30
  4420.2  330.72  4476.1  330.40  4481.3  329.45  4579.9  327.07  4618.0  324.38
  4645.7  324.17  4658.0  322.92  4678.6  322.91  4782.4  318.78  4880.5  313.54
  4894.7  310.75  4904.8  310.24  4962.4  309.83  4993.4  310.81  4998.0  309.44
  5000.7  308.94  5004.0  309.44  5007.6  309.63  5015.2  313.18  5029.4  316.78
  5043.6  318.30  5088.7  319.22  5111.9  321.36  5228.3  326.44  5289.3  330.49
  5350.3  332.06  5380.8  334.73  5401.2  334.08  5438.9  335.77  5457.2  335.32
#Mann=5,-1,0
  4420.2    0.12       0  4904.8    0.16       0  4962.4    0.12       0
  4998.0    0.07       0  5004.0    0.12       0
Bank Sta=4998,5004
Exp/Cntr=0.3,0.1

Type RM Length L Ch R = 1,101,0,0,0
BEGIN DESCRIPTION:
UNT248 IN CCTC 1.0
END DESCRIPTION:
XS GIS Cut Line= 4
      3619682.61     10642748.52      3619583.64     10642264.10
      3619500.31     10642107.85      3619053.49     10642123.44
#Sta/Elev= 30
  4422.6  332.30  4464.7  332.46  4523.0  328.65  4553.6  327.90  4560.6  326.67
  4574.0  327.38  4584.2  325.80  4706.7  321.34  4764.7  317.45  4788.3  315.41
  4808.0  312.22  4829.2  313.34  4849.6  312.04  4880.2  313.59  4890.4  305.19
  4897.6  303.61  4900.4  303.11  4903.6  303.61  5045.3  303.61  5052.8  303.61
  5144.8  303.61  5154.8  311.61  5168.5  312.11  5204.9  312.30  5267.7  315.70
  5307.5  317.49  5355.0  320.42  5385.0  320.82  5415.0  324.42  5541.2  329.83
#Mann=9,-1,0
  4422.6    0.12       0  4764.7    0.05       0  4897.6   0.033       0
  4903.6    0.05       0  5045.3    0.16       0  5052.8    0.05       0
  5168.5    0.12       0  5267.7    0.16       0  5307.5    0.12       0
Bank Sta=4897.6,4903.6
Exp/Cntr=0.3,0.1

Chan Stop Cuts=-1