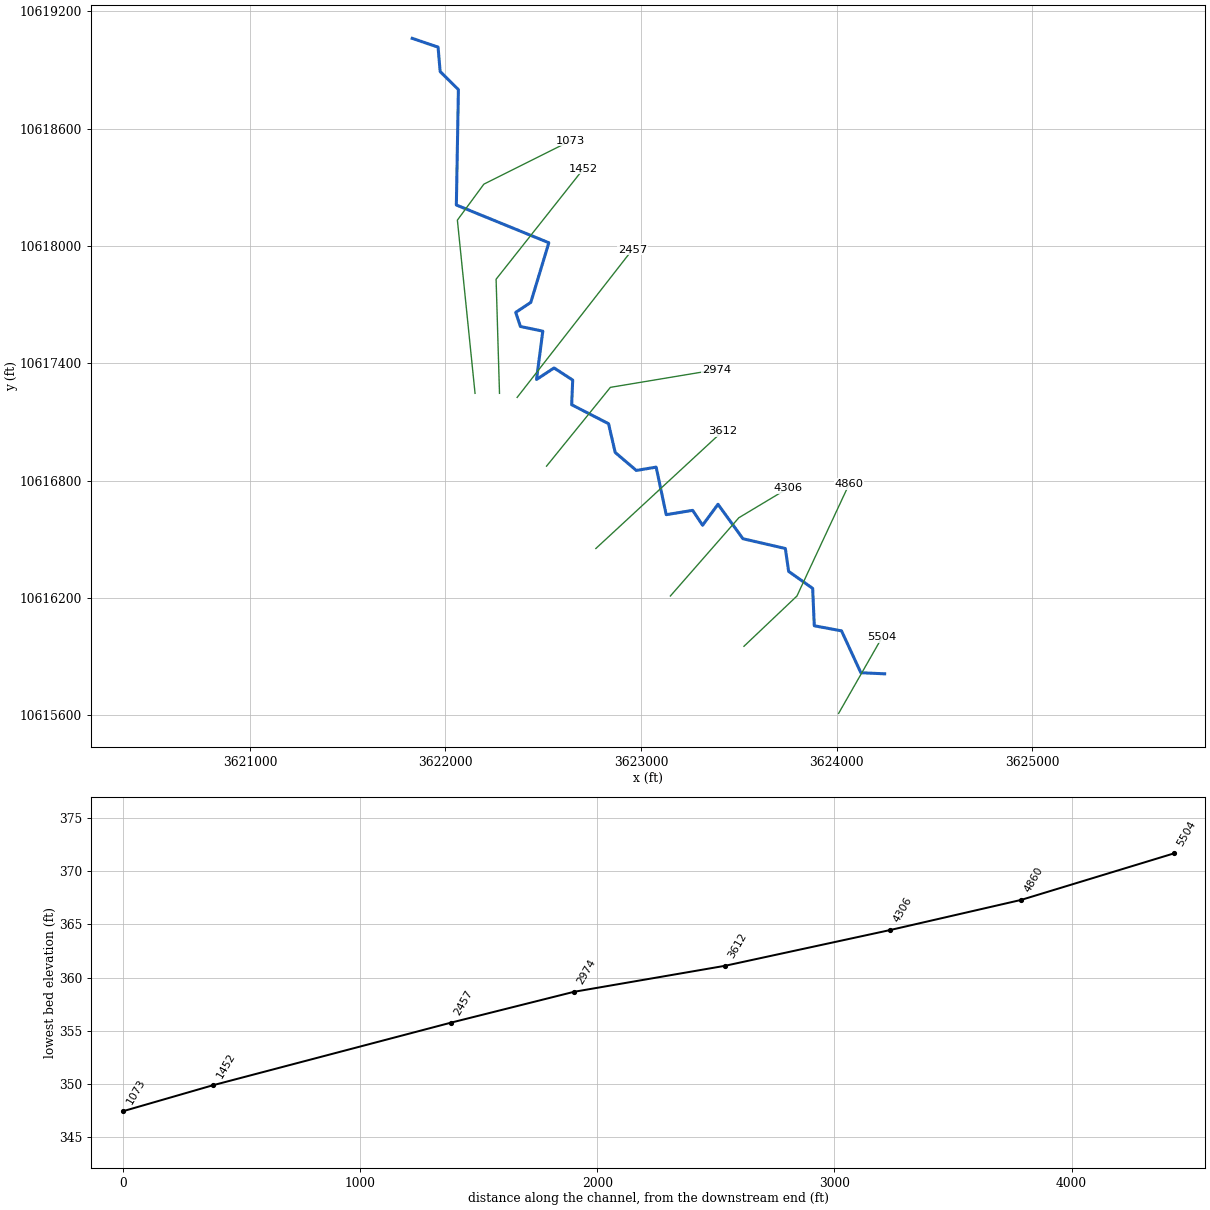
--- UNT250 IN CCTC.prj (project) ---

Proj Title=UNT250 IN CCTC Base Level Engineering
Current Plan=p01
Default Exp/Contr=0.3,0.1
English Units
Geom File=g01
Flow File=f01
Plan File=p01
BEGIN DESCRIPTION:
UNT250 IN CCTC
END DESCRIPTION:

--- UNT250 IN CCTC.p01 (plan) ---

Plan Title=Multiple Run
Short Identifier=Multiple
Geom File=g01
Flow File=f01
Subcritical Flow
K Sum by GR= 0
Std Step Tol= 0.01
Critical Tol= 0.01
Num of Std Step Trials= 20
Max Error Tol= 0.3
Flow Tol Ratio= 0.001
Split Flow NTrial= 30
Split Flow Tol= 0.02
Split Flow Ratio= 0.02
Log Output Level= 0
Friction Slope Method= 1
Unsteady Friction Slope Method= 2
Unsteady Bridges Friction Slope Method= 1
Parabolic Critical Depth
Global Vel Dist=  1 , 1 , 1
Global Log Level= 0
CheckData=True
Encroach Param= -1, 0, 0, 0
BEGIN DESCRIPTION:
Multiple Run
END DESCRIPTION:

--- UNT250 IN CCTC.f01 (steady flow) ---

Flow Title=Multiple
Number of Profiles=7
Profile Names=10-year,25-year,50-year,1pct_min,100-year,1pct_plu,500-year
River Rch & RM= UNT250 IN CCTC,Reach-1,5504
    1812    2568    3214    2939    3975    5376    6057
River Rch & RM= UNT250 IN CCTC,Reach-1,4860
    2165    3089    3884    3564    4819    6518    7396
Boundary for River Rch & Prof#=UNT250 IN CCTC,Reach-1,1
Up Type=0
Dn Type=3
Dn Slope=0.005
Boundary for River Rch & Prof#=UNT250 IN CCTC,Reach-1,2
Up Type=0
Dn Type=3
Dn Slope=0.005
Boundary for River Rch & Prof#=UNT250 IN CCTC,Reach-1,3
Up Type=0
Dn Type=3
Dn Slope=0.005
Boundary for River Rch & Prof#=UNT250 IN CCTC,Reach-1,4
Up Type=0
Dn Type=3
Dn Slope=0.005
Boundary for River Rch & Prof#=UNT250 IN CCTC,Reach-1,5
Up Type=0
Dn Type=3
Dn Slope=0.005
Boundary for River Rch & Prof#=UNT250 IN CCTC,Reach-1,6
Up Type=0
Dn Type=3
Dn Slope=0.005
Boundary for River Rch & Prof#=UNT250 IN CCTC,Reach-1,7
Up Type=0
Dn Type=3
Dn Slope=0.005

--- UNT250 IN CCTC.g01 (geometry) ---

Geom Title=Existing Conditions

River Reach=UNT250 IN CCTC,Reach-1
Reach XY= 30
      3624244.93     10615812.41      3624123.25     10615818.00
      3624024.50     10616032.00      3623885.25     10616058.00
      3623877.00     10616249.00      3623754.25     10616336.00
      3623737.25     10616453.00      3623520.50     10616503.00
      3623393.00     10616679.00      3623314.25     10616572.00
      3623263.50     10616648.00      3623128.25     10616626.00
      3623077.00     10616869.00      3622975.50     10616852.00
      3622867.50     10616944.00      3622833.50     10617091.00
      3622645.00     10617188.00      3622650.25     10617314.00
      3622555.00     10617376.00      3622465.25     10617317.00
      3622497.50     10617564.00      3622383.00     10617588.00
      3622359.00     10617660.00      3622436.00     10617711.00
      3622528.25     10618016.00      3622055.50     10618209.00
      3622066.00     10618799.00      3621972.75     10618891.00
      3621962.00     10619016.00      3621829.75     10619061.00

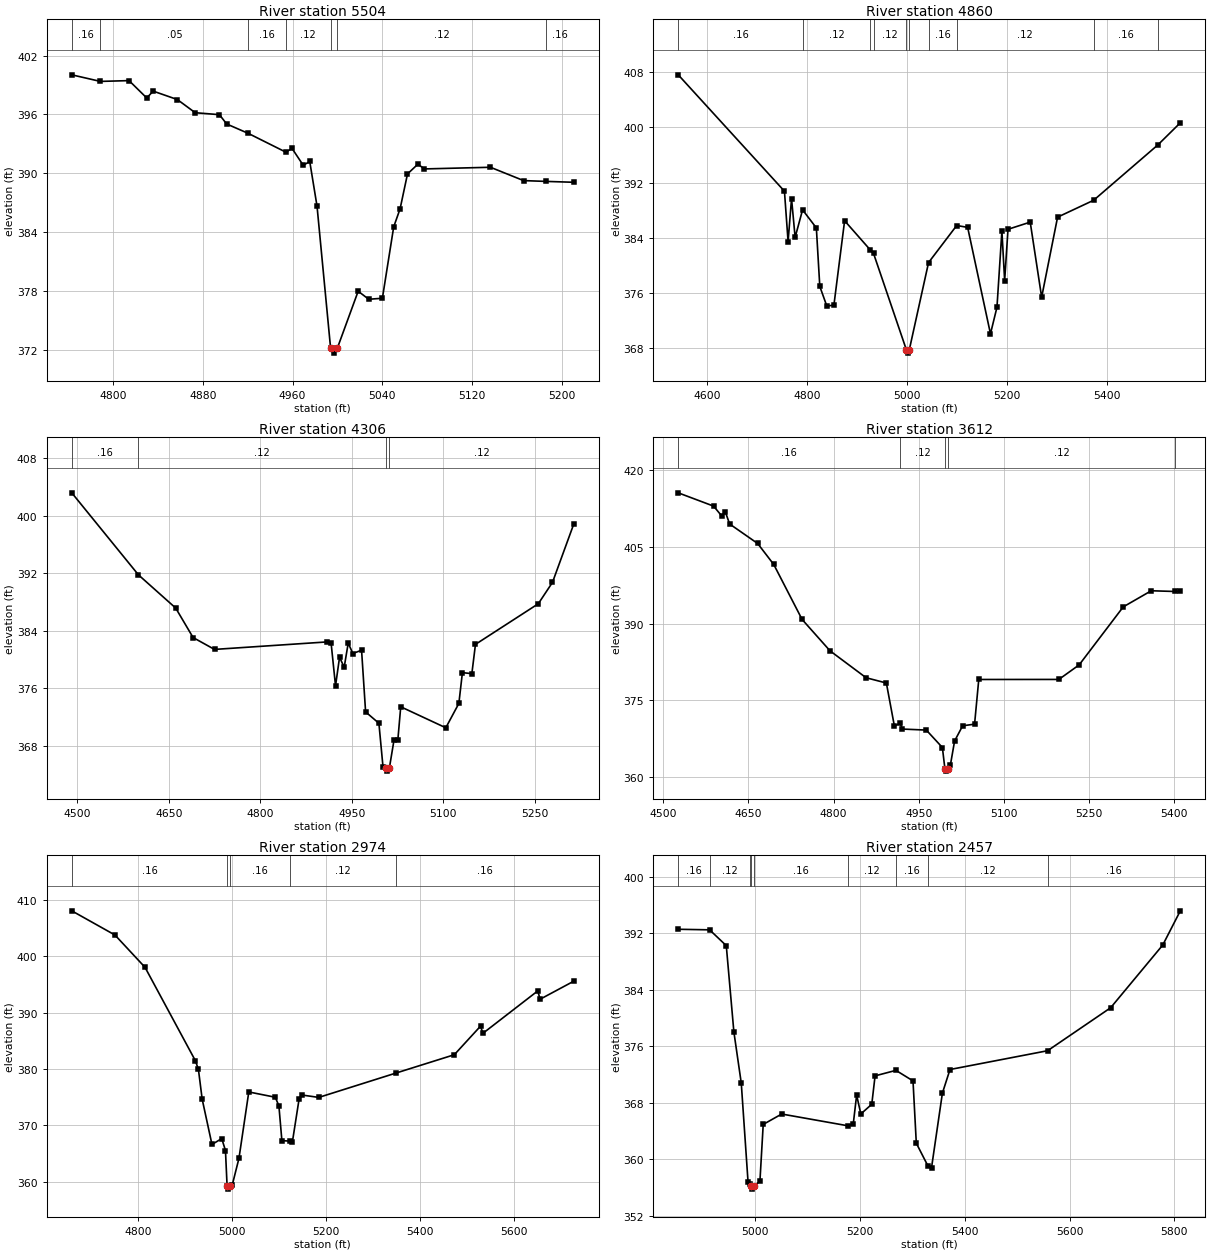
Type RM Length L Ch R = 1,5504,644,644,644
BEGIN DESCRIPTION:
UNT250 IN CCTC 9.0
END DESCRIPTION:
XS GIS Cut Line= 2
      3624009.67     10615610.18      3624231.89     10615999.07
#Sta/Elev= 30
  4763.0  400.04  4788.5  399.37  4814.1  399.45  4829.9  397.68  4835.6  398.38
  4857.2  397.52  4873.1  396.18  4894.7  395.98  4901.2  395.03  4920.5  394.07
  4954.0  392.16  4959.5  392.54  4969.5  390.82  4975.3  391.21  4981.8  386.65
  4993.9  372.18  4996.6  371.68  4999.9  372.18  5018.5  377.99  5027.9  377.17
  5040.1  377.27  5050.2  384.55  5055.9  386.39  5062.5  389.94  5071.8  390.94
  5077.5  390.45  5136.5  390.62  5166.1  389.26  5186.0  389.18  5210.9  389.09
#Mann=7,-1,0
  4763.0    0.16       0  4788.5    0.05       0  4920.5    0.16       0
  4954.0    0.12       0  4993.9    0.07       0  4999.9    0.12       0
  5186.0    0.16       0
Bank Sta=4993.9,4999.9
Exp/Cntr=0.3,0.1

Type RM Length L Ch R = 1,4860,554,554,554
BEGIN DESCRIPTION:
UNT250 IN CCTC 8.0
END DESCRIPTION:
XS GIS Cut Line= 3
      3623525.72     10615953.13      3623796.53     10616210.06
      3624063.88     10616782.95
#Sta/Elev= 30
  4541.6  407.63  4754.3  390.77  4761.6  383.47  4768.5  389.70  4775.7  384.08
  4790.6  388.07  4818.2  385.45  4825.1  376.98  4839.2  374.12  4853.4  374.28
  4874.8  386.49  4926.6  382.23  4932.7  381.76  4998.4  367.81  5001.1  367.31
  5004.4  367.81  5042.9  380.43  5099.3  385.80  5121.2  385.53  5166.9  370.11
  5179.9  373.95  5189.8  385.00  5195.3  377.81  5202.0  385.25  5246.5  386.29
  5269.4  375.41  5301.3  387.01  5373.6  389.46  5502.2  397.48  5547.1  400.68
#Mann=10,-1,0
  4541.6    0.16       0  4790.6    0.12       0  4926.6    0.16       0
  4932.7    0.12       0  4998.4    0.07       0  5004.4    0.12       0
  5042.9    0.16       0  5099.3    0.12       0  5373.6    0.16       0
  5502.2    0.12       0
Bank Sta=4998.4,5004.4
Exp/Cntr=0.3,0.1

Type RM Length L Ch R = 1,4306,694,694,694
BEGIN DESCRIPTION:
UNT250 IN CCTC 7.0
END DESCRIPTION:
XS GIS Cut Line= 3
      3623149.58     10616210.16      3623499.61     10616610.19
      3623749.62     10616760.19
#Sta/Elev= 30
  4490.8  403.18  4600.1  391.77  4661.2  387.15  4689.7  383.05  4724.8  381.40
  4908.9  382.44  4916.0  382.24  4923.2  376.33  4929.8  380.31  4937.4  378.92
  4944.0  382.28  4951.6  380.83  4965.9  381.29  4972.5  372.71  4994.3  371.13
  5001.0  365.09  5005.6  364.97  5008.3  364.47  5011.6  364.97  5019.0  368.75
  5025.3  368.75  5030.1  373.42  5104.0  370.50  5125.4  373.89  5131.2  378.17
  5146.7  378.03  5152.6  382.10  5255.6  387.75  5278.9  390.73  5313.9  398.87
#Mann=4,-1,0
  4490.8    0.16       0  4600.1    0.12       0  5005.6    0.07       0
  5011.6    0.12       0
Bank Sta=5005.6,5011.6
Exp/Cntr=0.3,0.1

Type RM Length L Ch R = 1,3612,638,638,638
BEGIN DESCRIPTION:
UNT250 IN CCTC 6.0
END DESCRIPTION:
XS GIS Cut Line= 2
      3622768.72     10616453.08      3623418.06     10617053.81
#Sta/Elev= 30
  4526.3  415.57  4588.6  412.97  4602.7  411.07  4609.5  411.76  4616.9  409.47
  4666.2  405.66  4694.6  401.55  4744.5  390.80  4793.8  384.65  4857.3  379.39
  4893.0  378.36  4907.2  369.90  4916.9  370.52  4921.4  369.35  4963.4  369.15
  4991.7  365.74  4996.1  361.62  4998.8  361.12  5002.1  361.62  5005.9  362.37
  5013.2  367.01  5027.4  369.99  5048.4  370.31  5055.8  379.05  5196.9  379.06
  5232.7  381.91  5310.3  393.25  5359.7  396.41  5400.7  396.27  5410.9  396.29
#Mann=5,-1,0
  4526.3    0.16       0  4916.9    0.12       0  4996.1    0.07       0
  5002.1    0.12       0  5400.7    0.16       0
Bank Sta=4996.1,5002.1
Exp/Cntr=0.3,0.1

Type RM Length L Ch R = 1,2974,517,517,517
BEGIN DESCRIPTION:
UNT250 IN CCTC 5.0
END DESCRIPTION:
XS GIS Cut Line= 3
      3622516.58     10616874.02      3622842.98     10617276.81
      3623384.68     10617367.09
#Sta/Elev= 30
  4659.0  408.10  4750.9  403.80  4814.8  398.06  4921.9  381.47  4928.3  379.93
  4936.3  374.64  4957.1  366.60  4977.9  367.65  4985.8  365.53  4989.3  359.17
  4992.0  358.67  4995.3  359.17  5000.2  359.39  5014.5  364.14  5035.4  375.93
  5091.7  374.99  5099.4  373.48  5105.8  367.28  5122.9  367.20  5128.1  367.04
  5142.5  374.74  5148.9  375.38  5184.2  374.96  5348.1  379.28  5472.4  382.54
  5528.2  387.62  5533.2  386.34  5649.8  393.87  5654.9  392.40  5726.6  395.61
#Mann=5,-1,0
  4659.0    0.16       0  4989.3    0.07       0  4995.3    0.16       0
  5122.9    0.12       0  5348.1    0.16       0
Bank Sta=4989.3,4995.3
Exp/Cntr=0.3,0.1

Type RM Length L Ch R = 1,2457,1005,1005,1005
BEGIN DESCRIPTION:
Mapping XS 06c32ee4
END DESCRIPTION:
XS GIS Cut Line= 2
      3622366.31     10617225.35      3622955.61     10617981.04
#Sta/Elev= 30
  4853.2  392.56  4913.1  392.48  4944.9  390.24  4959.4  378.03  4973.5  370.79
  4986.5  356.73  4989.3  356.48  4991.6  356.28  4994.4  355.78  4997.6  356.28
  5009.1  356.87  5015.4  364.94  5050.7  366.41  5176.6  364.75  5187.3  365.03
  5193.7  369.09  5201.7  366.42  5222.6  367.79  5228.9  371.81  5268.7  372.59
  5301.3  371.10  5307.6  362.28  5329.8  359.06  5336.6  358.78  5357.4  369.37
  5371.9  372.71  5558.2  375.37  5678.5  381.45  5778.0  390.33  5811.5  395.17
#Mann=9,-1,0
  4853.2    0.16       0  4913.1    0.12       0  4989.3    0.16       0
  4991.6    0.07       0  4997.6    0.16       0  5176.6    0.12       0
  5268.7    0.16       0  5329.8    0.12       0  5558.2    0.16       0
Bank Sta=4991.6,4997.6
Exp/Cntr=0.3,0.1

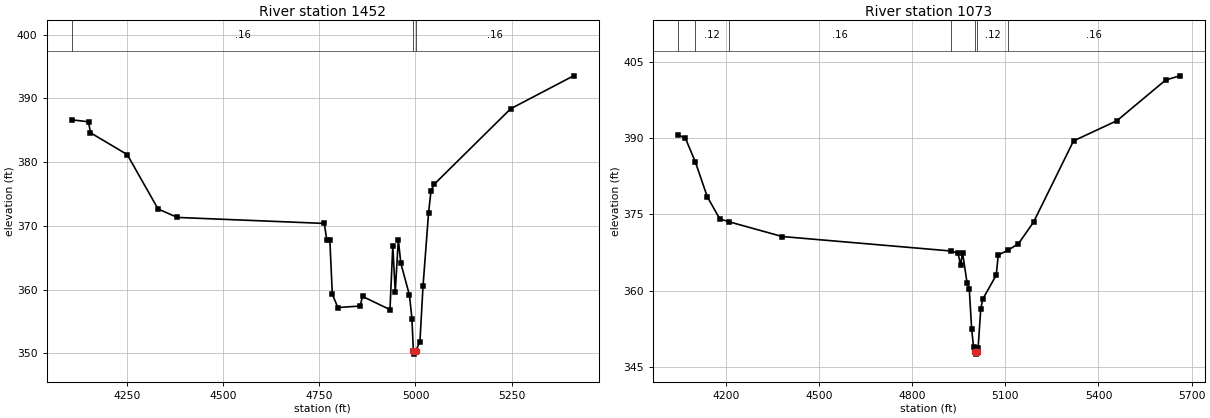
Type RM Length L Ch R = 1,1452,379,379,379
BEGIN DESCRIPTION:
UNT250 IN CCTC 3.0
END DESCRIPTION:
XS GIS Cut Line= 3
      3622276.04     10617246.20      3622258.68     10617829.53
      3622705.51     10618394.12
#Sta/Elev= 30
  4107.0  386.64  4150.6  386.33  4155.6  384.61  4251.1  381.19  4331.1  372.67
  4381.1  371.33  4763.1  370.39  4769.5  367.78  4777.5  367.76  4783.9  359.28
  4798.3  357.20  4856.1  357.43  4862.4  358.94  4933.7  356.87  4941.0  366.85
  4947.4  359.62  4955.4  367.84  4961.8  364.17  4984.3  359.14  4990.7  355.47
  4994.5  350.39  4997.2  349.89  5000.5  350.39  5011.5  351.83  5019.5  360.52
  5034.0  372.07  5040.3  375.51  5048.4  376.52  5247.1  388.37  5410.6  393.54
#Mann=3,-1,0
  4107.0    0.16       0  4994.5    0.07       0  5000.5    0.16       0
Bank Sta=4994.5,5000.5
Exp/Cntr=0.3,0.1

Type RM Length L Ch R = 1,1073,0,0,0
BEGIN DESCRIPTION:
UNT250 IN CCTC 4.0
END DESCRIPTION:
XS GIS Cut Line= 4
      3622151.04     10617246.21      3622060.77     10618131.62
      3622196.18     10618315.64      3622640.65     10618537.87
#Sta/Elev= 30
  4046.2  390.73  4070.3  390.04  4102.4  385.35  4140.7  378.51  4180.9  374.13
  4210.0  373.57  4381.9  370.65  4924.0  367.80  4947.9  367.37  4956.3  365.07
  4962.5  367.44  4977.2  361.46  4984.1  360.39  4991.8  352.46  4998.0  348.80
  5003.4  347.95  5006.2  347.45  5009.4  347.95  5012.6  348.63  5021.1  356.31
  5027.3  358.28  5071.0  363.03  5077.4  366.99  5108.8  367.96  5142.2  369.21
  5191.2  373.50  5319.8  389.51  5459.6  393.50  5616.1  401.51  5661.6  402.35
#Mann=7,-1,0
  4046.2    0.16       0  4102.4    0.12       0  4210.0    0.16       0
  4924.0    0.12       0  5003.4    0.07       0  5009.4    0.12       0
  5108.8    0.16       0
Bank Sta=5003.4,5009.4
Exp/Cntr=0.3,0.1

Chan Stop Cuts=-1