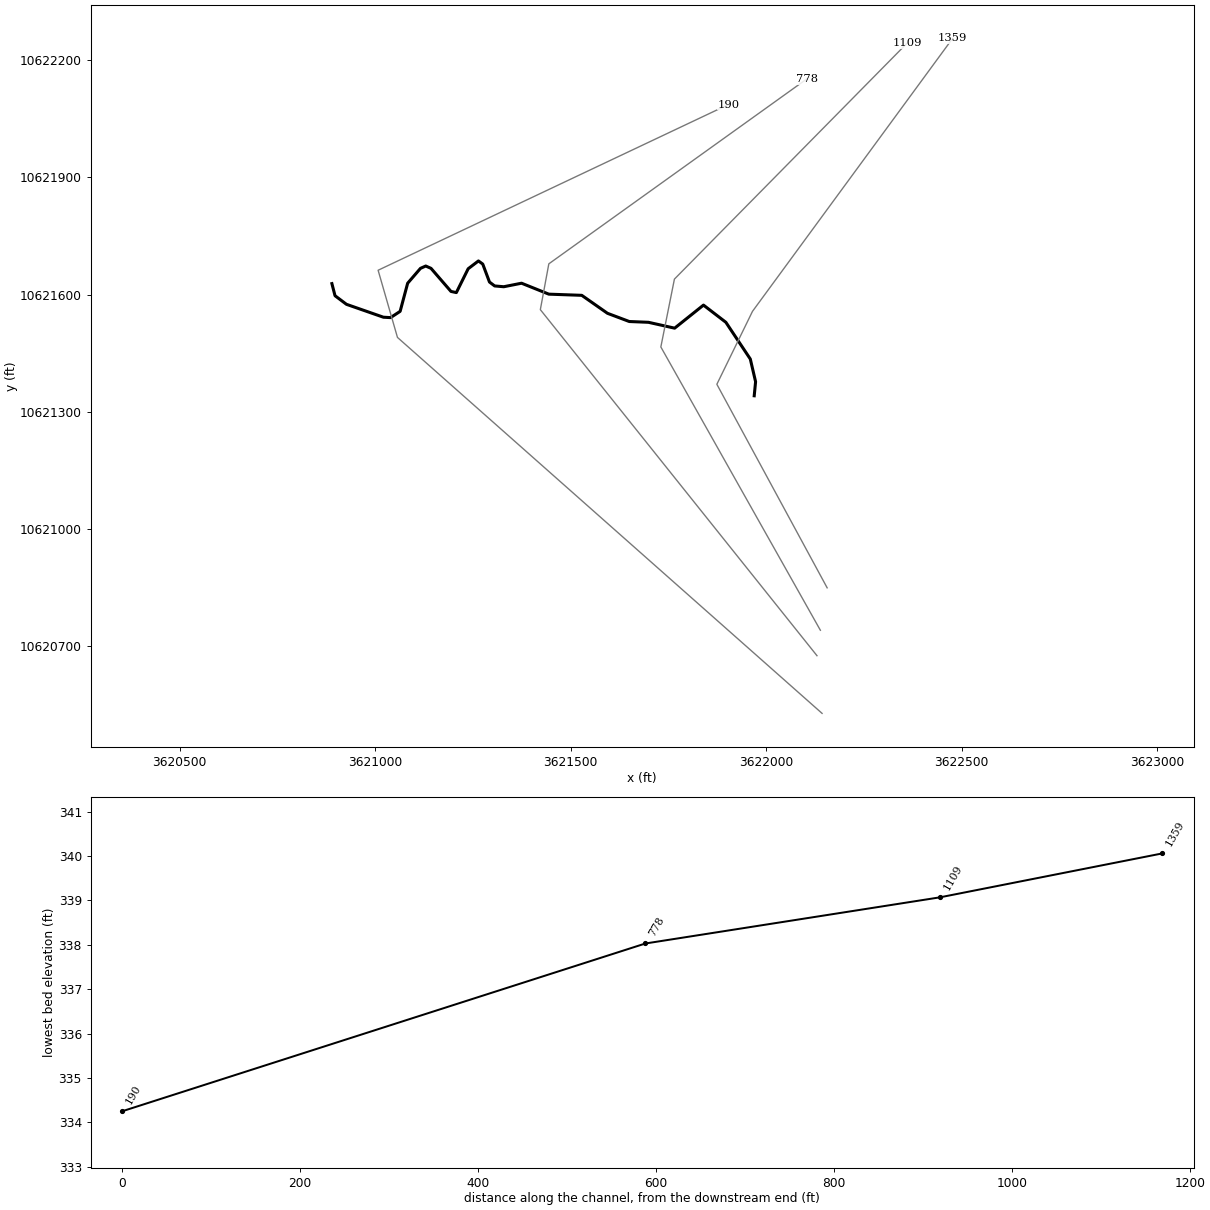
--- UNT251 IN CCTC.prj (project) ---

Proj Title=UNT251 IN CCTC Base Level Engineering
Current Plan=p01
Default Exp/Contr=0.3,0.1
English Units
Geom File=g01
Flow File=f01
Plan File=p01
BEGIN DESCRIPTION:
UNT251 IN CCTC
END DESCRIPTION:

--- UNT251 IN CCTC.p01 (plan) ---

Plan Title=Multiple Run
Short Identifier=Multiple
Geom File=g01
Flow File=f01
Subcritical Flow
K Sum by GR= 0
Std Step Tol= 0.01
Critical Tol= 0.01
Num of Std Step Trials= 20
Max Error Tol= 0.3
Flow Tol Ratio= 0.001
Split Flow NTrial= 30
Split Flow Tol= 0.02
Split Flow Ratio= 0.02
Log Output Level= 0
Friction Slope Method= 1
Unsteady Friction Slope Method= 2
Unsteady Bridges Friction Slope Method= 1
Parabolic Critical Depth
Global Vel Dist=  1 , 1 , 1
Global Log Level= 0
CheckData=True
Encroach Param= -1, 0, 0, 0
BEGIN DESCRIPTION:
Multiple Run
END DESCRIPTION:

--- UNT251 IN CCTC.f01 (steady flow) ---

Flow Title=Multiple
Number of Profiles=7
Profile Names=10-year,25-year,50-year,1pct_min,100-year,1pct_plu,500-year
River Rch & RM= UNT251 IN CCTC,Reach-1,1359
    1931    2728    3405    3102    4195    5673    6346
Boundary for River Rch & Prof#=UNT251 IN CCTC,Reach-1,1
Up Type=0
Dn Type=3
Dn Slope=0.005
Boundary for River Rch & Prof#=UNT251 IN CCTC,Reach-1,2
Up Type=0
Dn Type=3
Dn Slope=0.005
Boundary for River Rch & Prof#=UNT251 IN CCTC,Reach-1,3
Up Type=0
Dn Type=3
Dn Slope=0.005
Boundary for River Rch & Prof#=UNT251 IN CCTC,Reach-1,4
Up Type=0
Dn Type=3
Dn Slope=0.005
Boundary for River Rch & Prof#=UNT251 IN CCTC,Reach-1,5
Up Type=0
Dn Type=3
Dn Slope=0.005
Boundary for River Rch & Prof#=UNT251 IN CCTC,Reach-1,6
Up Type=0
Dn Type=3
Dn Slope=0.005
Boundary for River Rch & Prof#=UNT251 IN CCTC,Reach-1,7
Up Type=0
Dn Type=3
Dn Slope=0.005

--- UNT251 IN CCTC.g01 (geometry) ---

Geom Title=Existing Conditions

River Reach=UNT251 IN CCTC,Reach-1
Reach XY= 30
      3621969.50     10621341.00      3621973.00     10621377.00
      3621959.50     10621435.00      3621897.00     10621529.00
      3621839.75     10621573.00      3621766.00     10621514.00
      3621699.00     10621529.00      3621650.00     10621531.00
      3621594.25     10621552.00      3621528.50     10621598.00
      3621444.25     10621601.00      3621374.50     10621629.00
      3621329.00     10621620.00      3621305.75     10621622.00
      3621292.50     10621632.00      3621275.25     10621678.00
      3621264.25     10621686.00      3621238.00     10621666.00
      3621207.75     10621605.00      3621194.00     10621608.00
      3621143.00     10621667.00      3621129.50     10621673.00
      3621116.00     10621667.00      3621083.25     10621629.00
      3621064.00     10621557.00      3621039.50     10621541.00
      3621021.25     10621542.00      3620926.75     10621575.00
      3620897.50     10621597.00      3620889.50     10621628.00

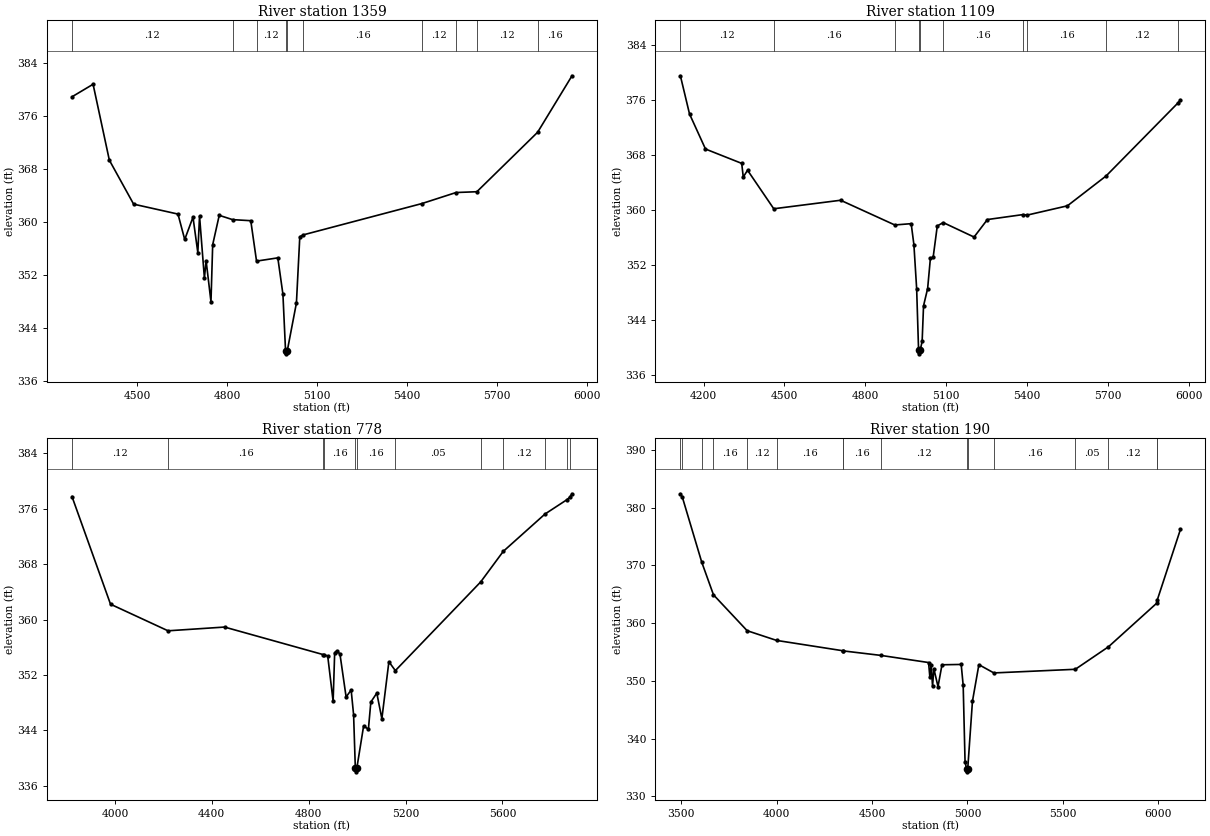
Type RM Length L Ch R = 1,1359,250,250,250
BEGIN DESCRIPTION:
UNT251 IN CCTC 2.0
END DESCRIPTION:
XS GIS Cut Line= 4
      3622156.04     10620849.61      3621873.94     10621370.41
      3621965.09     10621557.04      3622477.02     10622255.53
#Sta/Elev= 30
  4283.7  378.92  4354.0  380.82  4408.2  369.34  4489.1  362.69  4636.9  361.19
  4659.3  357.35  4686.9  360.72  4703.0  355.36  4708.7  360.89  4724.9  351.51
  4730.6  354.14  4746.8  347.94  4752.5  356.56  4774.3  361.00  4818.9  360.35
  4879.4  360.19  4898.6  354.08  4969.5  354.57  4986.5  349.08  4995.2  340.56
  4997.9  340.06  5001.2  340.56  5031.5  347.75  5042.7  357.75  5053.7  358.04
  5449.5  362.78  5563.5  364.45  5632.7  364.57  5835.1  373.56  5949.7  382.10
#Mann=10,-1,0
  4283.7    0.12       0  4818.9    0.16       0  4898.6    0.12       0
  4995.2    0.07       0  5001.2    0.12       0  5053.7    0.16       0
  5449.5    0.12       0  5563.5    0.16       0  5632.7    0.12       0
  5835.1    0.16       0
Bank Sta=4995.2,5001.2
Exp/Cntr=0.3,0.1

Type RM Length L Ch R = 1,1109,331,331,331
BEGIN DESCRIPTION:
Mapping XS f6307c49
END DESCRIPTION:
XS GIS Cut Line= 4
      3622138.68     10620741.09      3621730.71     10621465.89
      3621765.43     10621639.50      3622360.08     10622242.83
#Sta/Elev= 30
  4113.6  379.57  4147.5  374.01  4206.8  368.90  4341.2  366.81  4347.0  364.82
  4362.9  365.81  4460.2  360.20  4708.3  361.44  4909.4  357.84  4970.2  358.03
  4980.3  354.98  4990.5  348.58  4997.7  339.57  5000.5  339.07  5003.7  339.57
  5010.9  340.90  5016.1  346.07  5031.3  348.58  5041.5  352.97  5051.7  353.11
  5067.1  357.70  5089.1  358.19  5203.6  356.08  5253.1  358.63  5384.8  359.35
  5401.0  359.28  5550.1  360.63  5693.7  364.98  5961.6  375.66  5969.5  376.06
#Mann=10,-1,0
  4113.6    0.12       0  4460.2    0.16       0  4909.4    0.12       0
  4997.7    0.07       0  5003.7    0.12       0  5089.1    0.16       0
  5384.8    0.12       0  5401.0    0.16       0  5693.7    0.12       0
  5961.6    0.16       0
Bank Sta=4997.7,5003.7
Exp/Cntr=0.3,0.1

Type RM Length L Ch R = 1,778,588,588,588
BEGIN DESCRIPTION:
Mapping XS 4aae3e01
END DESCRIPTION:
XS GIS Cut Line= 4
      3622130.01     10620675.97      3621422.55     10621561.38
      3621444.25     10621678.57      3622103.95     10622151.64
#Sta/Elev= 30
  3822.9  377.77  3982.0  362.23  4219.4  358.39  4452.7  358.93  4859.4  354.96
  4861.8  354.91  4878.6  354.77  4901.0  348.21  4907.4  355.23  4915.4  355.48
  4929.1  355.06  4954.6  348.84  4975.4  349.84  4985.5  346.28  4992.7  338.53
  4995.5  338.03  4998.7  338.53  5026.9  344.66  5046.6  344.18  5056.7  348.10
  5081.3  349.40  5102.2  345.70  5131.2  353.93  5157.8  352.64  5510.3  365.45
  5603.2  369.85  5775.8  375.25  5865.5  377.30  5877.3  377.65  5887.2  378.17
#Mann=12,-1,0
  3822.9    0.12       0  4219.4    0.16       0  4859.4    0.12       0
  4861.8    0.16       0  4992.7    0.07       0  4998.7    0.16       0
  5157.8    0.05       0  5510.3    0.16       0  5603.2    0.12       0
  5775.8    0.16       0  5865.5    0.12       0  5877.3    0.16       0
Bank Sta=4992.7,4998.7
Exp/Cntr=0.3,0.1

Type RM Length L Ch R = 1,190,0,0,0
BEGIN DESCRIPTION:
UNT251 IN CCTC 1.0
END DESCRIPTION:
XS GIS Cut Line= 4
      3622143.01     10620528.42      3621057.17     10621490.32
      3621007.69     10621662.19      3621902.91     10622085.88
#Sta/Elev= 30
  3495.7  382.38  3506.2  381.77  3607.5  370.55  3669.1  364.89  3845.5  358.68
  3999.6  357.00  4349.0  355.20  4349.4  355.18  4545.0  354.41  4796.1  353.17
  4802.8  350.67  4809.5  352.76  4817.0  349.06  4823.7  352.11  4845.5  349.00
  4866.4  352.78  4967.0  352.84  4977.4  349.22  4987.2  336.02  4995.2  334.75
  4998.0  334.25  5001.2  334.75  5026.0  346.47  5059.7  352.80  5138.1  351.37
  5564.9  352.00  5738.8  355.90  5991.1  363.43  5994.1  363.97  6115.6  376.20
#Mann=16,-1,0
  3495.7    0.12       0  3506.2    0.16       0  3607.5    0.12       0
  3669.1    0.16       0  3845.5    0.12       0  3999.6    0.16       0
  4349.0    0.12       0  4349.4    0.16       0  4545.0    0.12       0
  4995.2    0.07       0  5001.2    0.12       0  5138.1    0.16       0
  5564.9    0.05       0  5738.8    0.12       0  5991.1    0.16       0
  5994.1    0.12       0
Bank Sta=4995.2,5001.2
Exp/Cntr=0.3,0.1

Chan Stop Cuts=-1