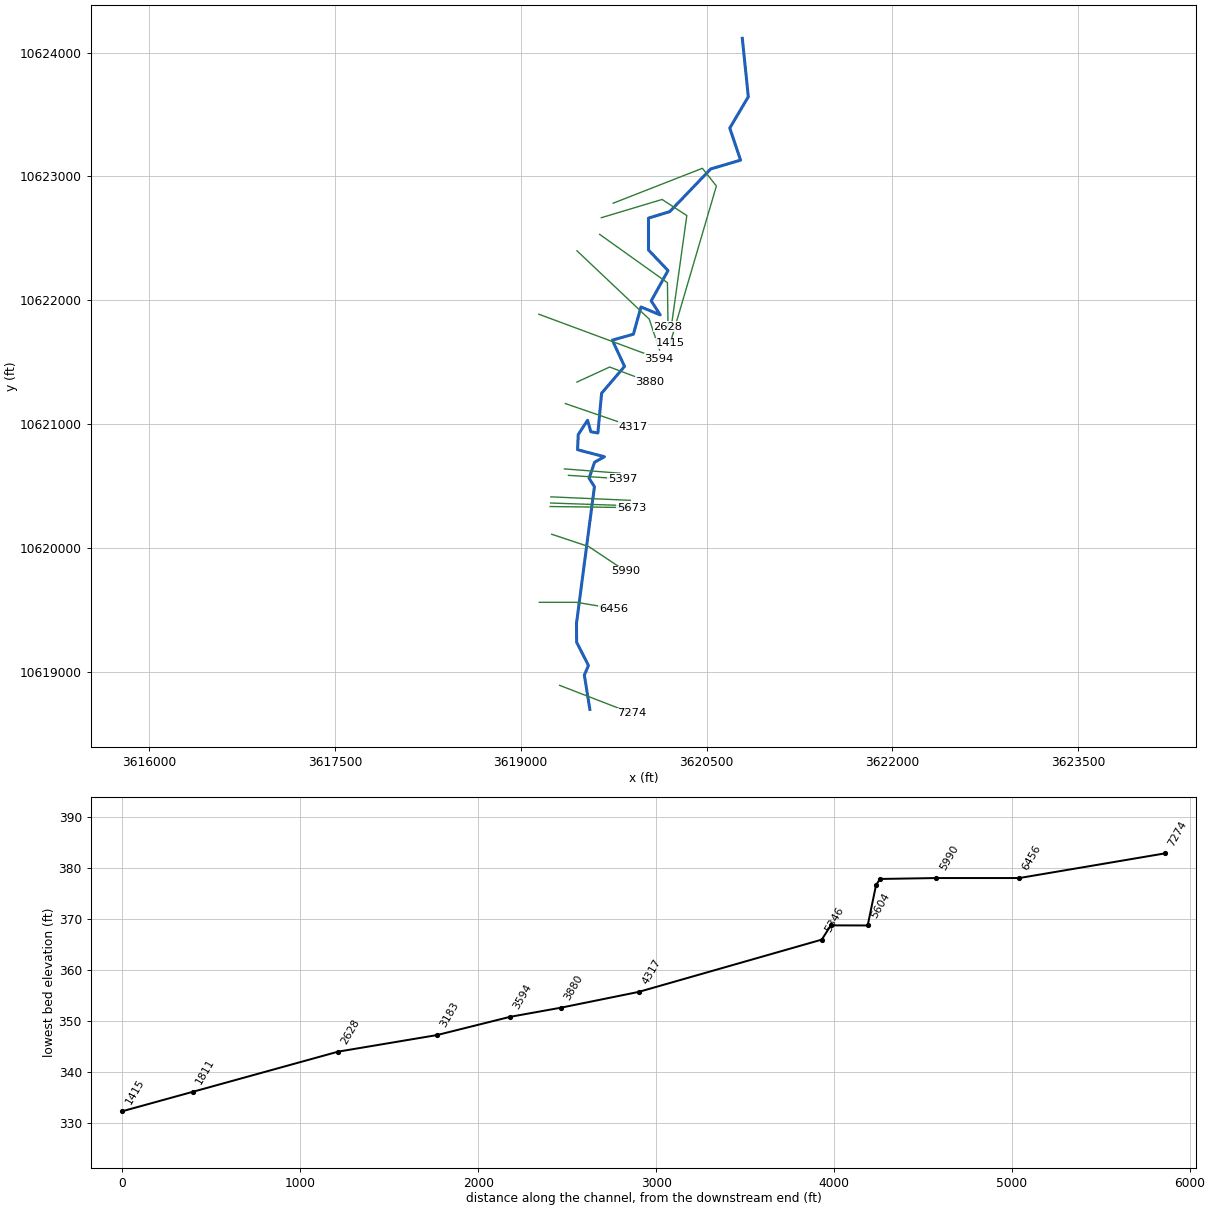
--- UNT252 IN CCTC.prj (project) ---

Proj Title=UNT252 IN CCTC Base Level Engineering
Current Plan=p01
Default Exp/Contr=0.3,0.1
English Units
Geom File=g01
Flow File=f01
Plan File=p01
Y Axis Title=Elevation
X Axis Title(PF)=Main Channel Distance
X Axis Title(XS)=Station
BEGIN DESCRIPTION:
UNT252 IN CCTC
END DESCRIPTION:
DSS Export Rating Curves= 0
DSS Export Rating Curve Sorted= 0
DSS Export Volume Flow Curves= 0
DXF OffsetX= 0
DXF OffsetY= 0
DXF ScaleX= 1
DXF ScaleY= 10

--- UNT252 IN CCTC.p01 (plan) ---

Plan Title=Multiple Run
Short Identifier=Multiple
Geom File=g01
Flow File=f01
Subcritical Flow
K Sum by GR= 0
Std Step Tol= 0.01
Critical Tol= 0.01
Num of Std Step Trials= 20
Max Error Tol= 0.3
Flow Tol Ratio= 0.001
Split Flow NTrial= 30
Split Flow Tol= 0.02
Split Flow Ratio= 0.02
Log Output Level= 0
Friction Slope Method= 1
Unsteady Friction Slope Method= 2
Unsteady Bridges Friction Slope Method= 1
Parabolic Critical Depth
Global Vel Dist=  1 , 1 , 1
Global Log Level= 0
CheckData=True
Encroach Param= -1, 0, 0, 0
BEGIN DESCRIPTION:
Multiple Run
END DESCRIPTION:

--- UNT252 IN CCTC.f01 (steady flow) ---

Flow Title=Multiple
Program Version=4.10
Number of Profiles= 7
Profile Names=10-year,25-year,50-year,1pct_min,100-year,1pct_plu,500-year
River Rch & RM=UNT252 IN CCTC,Reach-1         ,7274
  382.29  382.78  383.14  382.95  383.51  384.17  384.37
River Rch & RM=UNT252 IN CCTC,Reach-1         ,6456
    1434    1984    2441    2194    2967    4012    4365
River Rch & RM=UNT252 IN CCTC,Reach-1         ,3594
    1808    2531    3139    2840    3841    5195    5732
Boundary for River Rch & Prof#=UNT252 IN CCTC,Reach-1         , 1
Up Type= 0
Dn Type= 3
Dn Slope=0.005
Boundary for River Rch & Prof#=UNT252 IN CCTC,Reach-1         , 2
Up Type= 0
Dn Type= 3
Dn Slope=0.005
Boundary for River Rch & Prof#=UNT252 IN CCTC,Reach-1         , 3
Up Type= 0
Dn Type= 3
Dn Slope=0.005
Boundary for River Rch & Prof#=UNT252 IN CCTC,Reach-1         , 4
Up Type= 0
Dn Type= 3
Dn Slope=0.005
Boundary for River Rch & Prof#=UNT252 IN CCTC,Reach-1         , 5
Up Type= 0
Dn Type= 3
Dn Slope=0.005
Boundary for River Rch & Prof#=UNT252 IN CCTC,Reach-1         , 6
Up Type= 0
Dn Type= 3
Dn Slope=0.005
Boundary for River Rch & Prof#=UNT252 IN CCTC,Reach-1         , 7
Up Type= 0
Dn Type= 3
Dn Slope=0.005
DSS Import GetInterval= 0
DSS Import GetPeak= 0
DSS Import FillOption= 0

--- UNT252 IN CCTC.g01 (geometry) ---

Geom Title=Existing Conditions
Program Version=4.10

River Reach=UNT252 IN CCTC  ,Reach-1
Reach XY= 30
      3619557.95     10618695.43      3619513.68     10618972.12
      3619546.67     10619050.24      3619451.18     10619237.74
      3619450.25       10619391.        3619595.       10620494.
        3619552.       10620562.        3619596.       10620692.
       3619675.5       10620736.      3619458.75       10620793.
      3619464.25       10620915.       3619539.5       10621031.
        3619566.       10620938.      3619622.75       10620928.
        3619653.       10621249.      3619837.75       10621466.
       3619739.5       10621678.       3619909.5       10621726.
       3619970.5       10621946.      3620125.75       10621882.
      3620053.25       10621995.        3620189.       10622240.
       3620031.5       10622406.      3620031.25       10622664.
        3620203.       10622716.      3620533.75       10623061.
       3620774.5       10623132.      3620687.25       10623391.
        3620837.       10623644.       3620788.5       10624116.

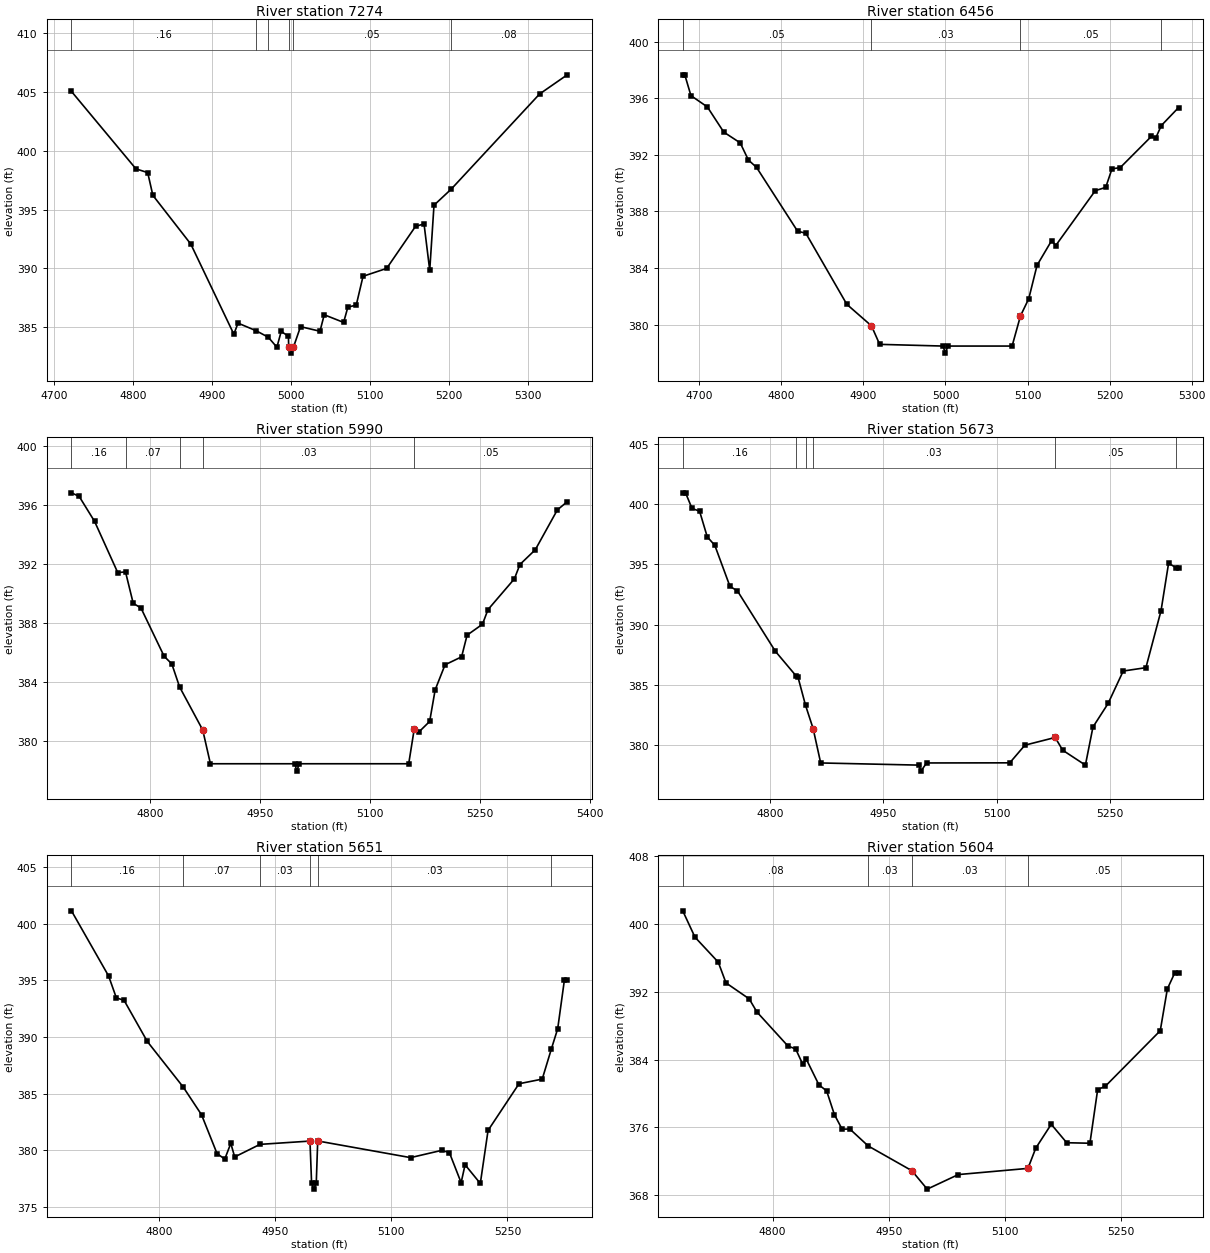
Type RM Length L Ch R = 1 ,7274    ,818,818,818
BEGIN DESCRIPTION:
Mapping XS 0c0688db
END DESCRIPTION:
XS GIS Cut Line= 2
      3619313.56     10618889.61      3619898.62     10618663.05
#Sta/Elev= 30
  4722.1  405.04  4803.7  398.46  4818.6  398.14  4825.1  396.21  4873.1  392.07
  4927.6  384.41  4932.9  385.35  4955.9   384.7  4971.2  384.15  4982.1   383.3
  4987.5  384.64  4996.7  384.24    4997   383.3  4999.8   382.8    5003   383.3
    5012  385.05  5036.6  384.66    5042  386.06  5066.5  385.41  5071.9  386.71
  5082.5  386.88  5091.1  389.33    5121     390  5157.5  393.57  5168.3  393.78
  5175.5  389.84  5180.9  395.37  5202.6  396.73  5314.5  404.82  5349.5  406.45
#Mann= 6 ,-1 , 0
  4722.1     .16       0  4955.9     .08       0  4971.2     .05       0
    4997     .04       0    5003     .05       0  5202.6     .08       0
Bank Sta=4997,5003
XS Rating Curve= 0 ,0
Exp/Cntr=0.3,0.1

Type RM Length L Ch R = 1 ,6456    ,466,466,466
BEGIN DESCRIPTION:
UNT252 IN CCTC 8.0
END DESCRIPTION:
XS GIS Cut Line= 3
      3619149.57     10619560.19      3619449.61     10619560.19
      3619749.64     10619510.18
#Sta/Elev= 30
  4679.8  397.66  4682.3  397.66  4689.8  396.19  4709.8  395.39  4729.8  393.61
  4749.8  392.85  4759.8  391.64  4769.8  391.11  4819.8   386.6  4829.8  386.46
  4879.8  381.43  4909.8  379.91  4919.8   378.6    4997  378.48  4999.8  377.98
    5003  378.48  5081.2  378.48  5091.4  380.61  5101.5  381.83  5111.6  384.19
  5129.4  385.94  5134.4  385.59  5182.6  389.47  5195.3   389.7  5202.9  391.01
    5213   391.1    5251  393.31  5256.1  393.17    5263  394.07    5284  395.34
#Mann= 4 ,-1 , 0
  4679.8     .05       0  4909.8     .03       0  5091.4     .05       0
    5263     .05       0
Bank Sta=4909.8,5091.4
XS Rating Curve= 0 ,0
Exp/Cntr=0.3,0.1

Type RM Length L Ch R = 1 ,5990    ,317,317,317
BEGIN DESCRIPTION:
UNT252 IN CCTC 7.0
END DESCRIPTION:
XS GIS Cut Line= 3
      3619249.62     10620110.19      3619549.61     10620010.19
      3619849.63     10619810.18
#Sta/Elev= 30
  4692.1  396.85  4702.6  396.61  4723.7  394.91  4755.3  391.44  4765.9  391.49
  4776.4  389.36    4787  389.04  4818.6  385.77  4829.1  385.25  4839.7  383.69
  4871.3  380.77  4881.8  378.48    4997  378.48  4999.8  377.98    5003  378.48
  5152.5  378.48  5160.1  380.85  5166.1  380.62  5181.1  381.35  5188.6  383.49
  5202.1  385.19  5224.7  385.73  5232.2   387.2  5253.2  387.94  5260.7  388.93
  5296.8  391.02  5304.3  391.99  5325.3  392.99  5355.4  395.69  5368.9  396.25
#Mann= 5 ,-1 , 0
  4692.1     .16       0  4765.9     .07       0  4839.7     .03       0
  4871.3     .03       0  5160.1     .05       0
Bank Sta=4871.3,5160.1
XS Rating Curve= 0 ,0
Exp/Cntr=0.3,0.1

Type RM Length L Ch R = 1 ,5673    ,22,22,22
BEGIN DESCRIPTION:
UNT252 IN CCTC 6.0
END DESCRIPTION:
XS GIS Cut Line= 2
      3619237.26     10620334.05       3619892.7     10620325.36
#Sta/Elev= 30
  4684.8  400.96  4688.5  400.96  4697.1  399.66  4707.1  399.43  4717.2   397.3
  4727.2  396.59  4747.2  393.18  4757.2  392.79  4807.2  387.78  4834.6  385.73
  4837.2  385.62  4847.2  383.27  4857.2  381.34  4867.2  378.48    4997   378.3
  4999.8   377.8  5007.2  378.48  5117.2  378.49  5137.2  379.96  5177.2   380.6
  5187.2  379.54  5217.2   378.3  5227.2  381.47  5247.2  383.43  5267.2  386.13
  5297.2  386.41  5317.2  391.15  5327.2  395.11  5337.6   394.7  5340.3   394.7
#Mann= 6 ,-1 , 0
  4684.8     .16       0  4834.6     .05       0  4847.2     .03       0
  4857.2     .03       0  5177.2     .05       0  5337.6      .1       0
Bank Sta=4857.2,5177.2
XS Rating Curve= 0 ,0
Exp/Cntr=0.3,0.1

Type RM Length L Ch R = 1 ,5651    ,47,47,47
BEGIN DESCRIPTION:
Mapping XS 05ad1c8a
END DESCRIPTION:
XS GIS Cut Line= 2
      3619241.62     10620362.26      3619881.85     10620340.55
#Sta/Elev= 30
  4686.7  401.14  4734.7  395.39  4744.7  393.46  4754.7  393.24  4784.7  389.61
  4831.2  385.58  4854.8  383.14  4874.8  379.72  4884.8  379.23  4892.6  380.62
  4897.6  379.42  4930.3  380.53  4994.9  380.82    4997  377.08  4999.8  376.58
    5003  377.08  5004.9  380.83  5124.9  379.36    5165     380    5175  379.81
  5190.2  377.15  5195.3  378.73    5215  377.08    5225  381.76    5265  385.88
    5295  386.29  5306.9  388.97    5315  390.74  5323.7  395.06  5327.3  395.06
#Mann= 6 ,-1 , 0
  4686.7     .16       0  4831.2     .07       0  4930.3     .03       0
  4994.9     .03       0  5004.9     .03       0  5306.9      .1       0
Bank Sta=4994.9,5004.9
XS Rating Curve= 0 ,0
Exp/Cntr=0.3,0.1

Type RM Length L Ch R = 1 ,5604    ,207,207,207
BEGIN DESCRIPTION:
Mapping XS e696c328
END DESCRIPTION:
XS GIS Cut Line= 2
      3619243.79     10620412.17      3619883.97     10620383.96
#Sta/Elev= 30
  4683.8  401.57  4699.6  398.46  4729.7  395.51  4739.7  393.06  4769.7  391.17
  4779.7  389.62  4819.7  385.61  4829.8  385.25  4838.6  383.51  4843.6  384.03
  4859.8  381.02  4869.8   380.3  4879.8  377.51  4889.8  375.78  4899.8   375.8
  4923.5   373.8  4979.9  370.88  4999.8   368.7    5040  370.42    5130  371.15
  5140.1  373.54  5160.1  376.36  5180.1  374.18  5210.1  374.12  5220.1  380.45
  5230.1  380.86    5301  387.41  5310.2  392.35  5319.9  394.27  5324.6  394.27
#Mann= 4 ,-1 , 0
  4683.8     .08       0  4923.5     .03       0  4979.9     .03       0
    5130     .05       0
Bank Sta=4979.9,5130
XS Rating Curve= 0 ,0
Exp/Cntr=0.3,0.1

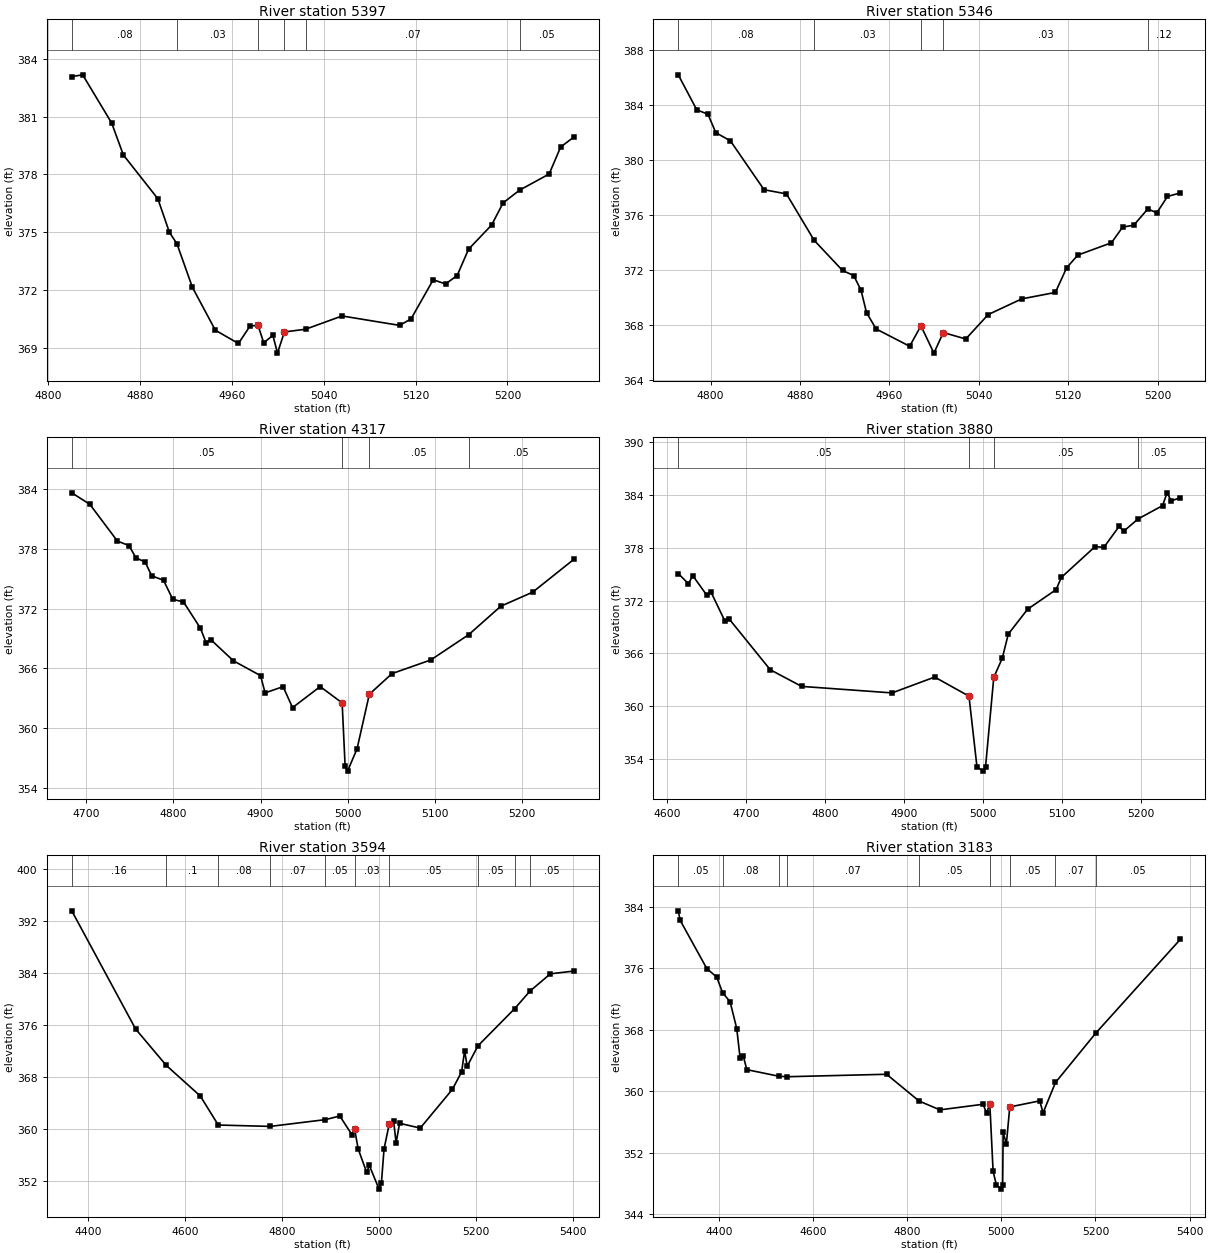
Type RM Length L Ch R = 1 ,5397    ,51,51,51
BEGIN DESCRIPTION:
Mapping XS a814e511
END DESCRIPTION:
XS GIS Cut Line= 2
      3619384.85     10620585.78      3619821.04     10620557.57
#Sta/Elev= 30
  4820.7  383.08  4830.2  383.17  4855.5  380.66  4865.6  379.01  4895.6  376.74
  4905.6  375.01  4912.3  374.39  4925.7  372.14  4945.7  369.91  4965.8  369.22
  4975.8  370.12  4982.8  370.17  4987.8  369.26  4995.8  369.64  4999.8  368.72
  5005.8  369.82  5024.2  369.96    5056  370.65  5106.1  370.16  5116.1   370.5
  5135.4  372.53  5146.1  372.31  5156.2  372.75  5166.2  374.12  5186.2  375.37
  5196.2  376.52  5210.5  377.18  5236.3  378.02  5246.3  379.42  5257.8  379.94
#Mann= 6 ,-1 , 0
  4820.7     .08       0  4912.3     .03       0  4982.8     .01       0
  5005.8     .03       0  5024.2     .07       0  5210.5     .05       0
Bank Sta=4982.8,5005.8
XS Rating Curve= 0 ,0
Exp/Cntr=0.3,0.1

Type RM Length L Ch R = 1 ,5346    ,1029,1029,1029
BEGIN DESCRIPTION:
UNT252 IN CCTC 5.0
END DESCRIPTION:
XS GIS Cut Line= 2
      3619353.08     10620637.94      3619801.04     10620603.21
#Sta/Elev= 30
    4771   386.2  4787.6  383.65  4797.6  383.33  4804.6  381.99  4817.7  381.39
  4847.8  377.83  4867.8  377.53  4892.6  374.15    4918  371.95    4928  371.58
  4934.5  370.53  4939.5  368.88  4948.1  367.69  4978.1  366.43  4988.2  367.92
  4999.8  365.93  5008.2  367.43  5028.3  366.96  5048.4  368.74  5078.4  369.88
  5108.5  370.35  5118.6  372.15  5128.6  373.07  5158.7  373.97  5168.7  375.11
  5178.7  375.25  5191.2  376.43  5199.3  376.15  5208.8  377.34  5220.3   377.6
#Mann= 5 ,-1 , 0
    4771     .08       0  4892.6     .03       0  4988.2     .01       0
  5008.2     .03       0  5191.2     .12       0
Bank Sta=4988.2,5008.2
XS Rating Curve= 0 ,0
Exp/Cntr=0.3,0.1

Type RM Length L Ch R = 1 ,4317    ,437,437,437
BEGIN DESCRIPTION:
UNT252 IN CCTC 4.0
END DESCRIPTION:
XS GIS Cut Line= 2
      3619360.02     10621165.72      3619904.89     10620978.31
#Sta/Elev= 30
  4683.3  383.61    4704  382.46  4735.7  378.77    4749  378.32  4756.9  377.09
  4767.5  376.67    4775  375.29  4788.6  374.84  4799.2  372.93  4811.5  372.67
  4830.9  370.04  4837.4  368.59  4842.7   368.9  4868.7  366.77  4899.9  365.28
  4905.2  363.55  4925.8  364.17  4936.7  362.07  4968.4  364.18  4993.6  362.54
    4997   356.2  4999.8   355.7  5010.7  357.94  5024.8  363.41  5050.8  365.48
  5095.3  366.85  5138.9  369.39  5175.7  372.24  5212.3  373.65  5259.5  376.94
#Mann= 4 ,-1 , 0
  4683.3     .05       0  4993.6     .03       0  5024.8     .05       0
  5138.9     .05       0
Bank Sta=4993.6,5024.8
XS Rating Curve= 0 ,0
Exp/Cntr=0.3,0.1

Type RM Length L Ch R = 1 ,3880    ,286,286,286
BEGIN DESCRIPTION:
UNT252 IN CCTC 3.0
END DESCRIPTION:
XS GIS Cut Line= 3
      3619453.79     10621339.34      3619717.66     10621460.86
      3620040.55     10621339.34
#Sta/Elev= 30
    4614  375.07  4626.9  373.91  4632.4  374.83  4649.9  372.63  4655.4  372.97
  4672.9   369.7  4678.4  369.91  4730.5  364.13  4770.2  362.24  4884.6   361.5
  4938.6   363.3    4982  361.13  4992.1  353.11  4999.8  352.61    5003  353.11
  5013.4  363.27  5024.1  365.43  5031.8  368.19  5056.2  371.01  5092.3  373.24
  5098.9  374.62  5141.6  378.13  5152.7  378.04  5172.2  380.44  5177.6  379.85
  5195.8  381.26  5227.1  382.79  5232.7  384.24    5238  383.33  5249.5  383.68
#Mann= 4 ,-1 , 0
    4614     .05       0    4982     .03       0  5013.4     .05       0
  5195.8     .05       0
Bank Sta=4982,5013.4
XS Rating Curve= 0 ,0
Exp/Cntr=0.3,0.1

Type RM Length L Ch R = 1 ,3594    ,411,411,411
BEGIN DESCRIPTION:
Mapping XS 90197d13
END DESCRIPTION:
XS GIS Cut Line= 2
      3619146.13     10621887.43      3620116.46     10621527.03
#Sta/Elev= 30
  4366.3  393.59    4498  375.42  4561.2  369.83  4631.3  365.13  4668.3  360.67
  4775.4  360.46  4889.2   361.5  4918.9  362.06  4943.9  359.18  4949.3  360.11
  4956.7  357.01  4974.3  353.39  4979.6  354.49  4999.8  350.82  5004.7  351.79
  5010.1     357  5020.7  360.78  5029.7  361.33    5035  357.93  5042.1  360.94
  5084.7   360.2  5151.1  366.16  5170.1  368.85  5176.2   372.1  5181.5   369.7
  5203.7  372.84  5279.3  378.55  5310.8  381.24    5353  383.91  5401.4  384.33
#Mann= 10 ,-1 , 0
  4366.3     .16       0  4561.2      .1       0  4668.3     .08       0
  4775.4     .07       0  4889.2     .05       0  4949.3     .03       0
  5020.7     .05       0  5203.7     .05       0  5279.3     .12       0
  5310.8     .05       0
Bank Sta=4949.3,5020.7
XS Rating Curve= 0 ,0
Exp/Cntr=0.3,0.1

Type RM Length L Ch R = 1 ,3183    ,555,555,555
BEGIN DESCRIPTION:
UNT252 IN CCTC 2.0
END DESCRIPTION:
XS GIS Cut Line= 3
       3619453.8     10622400.06       3620037.1     10621848.01
      3620120.42     10621598.05
#Sta/Elev= 30
  4313.8  383.45  4317.9  382.21  4374.5  375.94  4395.6  374.83    4408   372.8
  4423.9  371.63  4438.1  368.14  4445.3  364.25  4452.2  364.51  4459.5  362.79
  4527.1  361.94    4545  361.87  4756.4  362.19  4825.4  358.71  4869.7  357.56
  4961.5  358.29  4968.8  357.13  4975.7  358.35  4982.7  349.55  4989.8  347.77
  4999.8  347.25    5003  347.75    5004  354.62  5010.9  353.14  5018.1  357.94
  5081.7  358.73  5088.9  357.18  5115.2  361.12  5201.2  367.57  5380.4  379.74
#Mann= 9 ,-1 , 0
  4313.8     .05       0    4408     .08       0  4527.1      .1       0
    4545     .07       0  4825.4     .05       0  4975.7     .03       0
  5018.1     .05       0  5115.2     .07       0  5201.2     .05       0
Bank Sta=4975.7,5018.1
XS Rating Curve= 0 ,0
Exp/Cntr=0.3,0.1

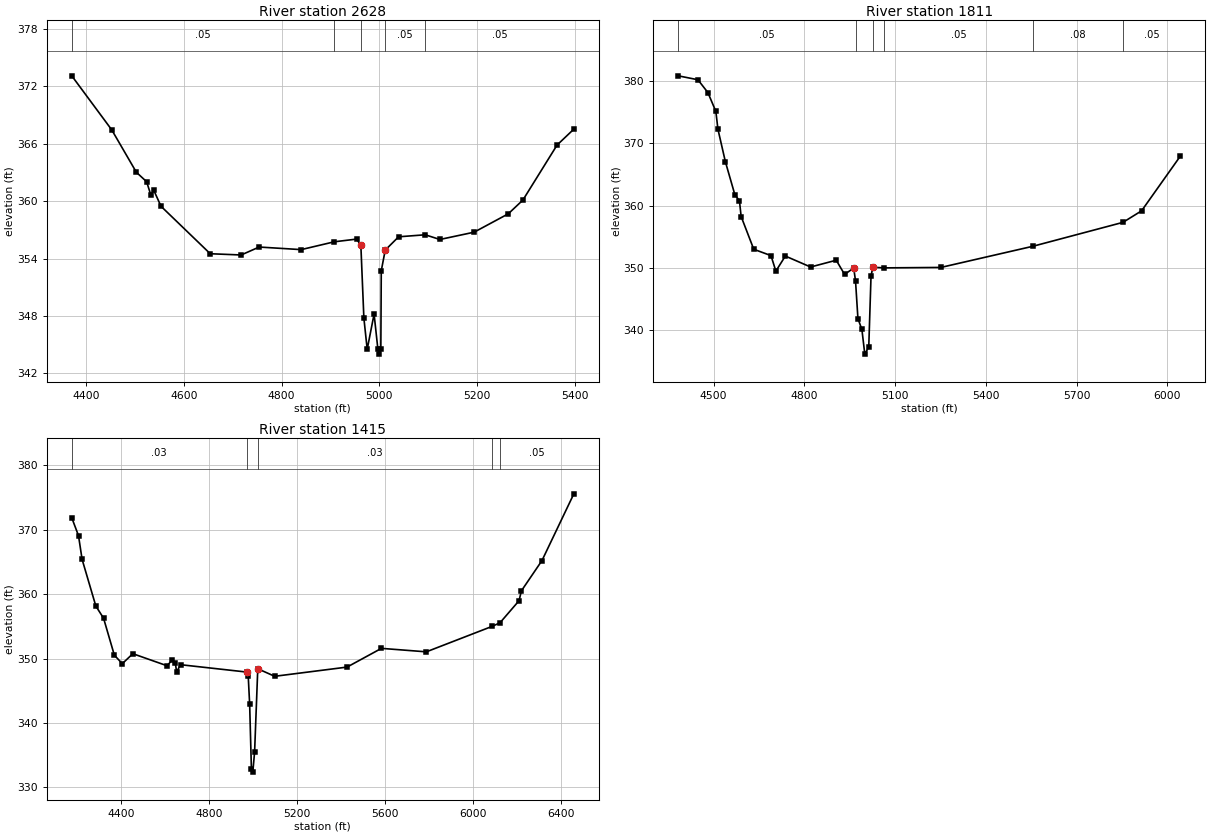
Type RM Length L Ch R = 1 ,2628    ,817,817,817
BEGIN DESCRIPTION:
Mapping XS 88318b0b
END DESCRIPTION:
XS GIS Cut Line= 3
      3619637.39     10622532.44      3620184.31     10622141.78
      3620188.65     10621785.91
#Sta/Elev= 30
  4370.2  373.09  4452.1  367.44  4502.5  363.01  4523.4  362.03    4532  360.66
  4538.2  361.12  4552.9  359.46  4653.7   354.5    4717  354.37  4753.9   355.2
  4839.9  354.93    4908  355.75  4953.5  356.03  4962.1  355.39  4968.3  347.77
  4975.1  344.51  4989.2   348.2    4997  344.51  4999.8  344.01    5003  344.51
  5003.9  352.72    5012  354.88  5039.4  356.27  5093.9  356.48  5123.9  355.99
  5193.9  356.75  5263.9  358.67  5293.9  360.11  5363.9  365.86  5398.2  367.52
#Mann= 5 ,-1 , 0
  4370.2     .05       0    4908     .05       0  4962.1     .03       0
    5012     .05       0  5093.9     .05       0
Bank Sta=4962.1,5012
XS Rating Curve= 0 ,0
Exp/Cntr=0.3,0.1

Type RM Length L Ch R = 1 ,1811    ,396,396,396
BEGIN DESCRIPTION:
Mapping XS aef17dff
END DESCRIPTION:
XS GIS Cut Line= 4
      3619650.47     10622666.96       3620140.9     10622814.52
      3620340.56     10622684.32      3620214.94     10621783.34
#Sta/Elev= 30
  4382.9  380.84    4448  380.21    4481  378.15  4507.3  375.12  4514.1  372.29
  4538.6  367.08    4570  361.77  4585.3  360.77  4590.9  358.25  4632.6  352.99
  4689.6  351.97  4705.7  349.48  4737.1   351.9  4820.6  350.14  4905.4  351.23
  4932.9  348.95  4963.1  349.97  4969.1  347.93  4977.1  341.85  4990.2  340.11
  4999.8  336.15  5012.9   337.3  5020.4   348.7  5026.4   350.1  5064.5     350
  5251.3  350.07  5554.8  353.46  5853.5  357.31    5915  359.16  6043.1  367.94
#Mann= 6 ,-1 , 0
  4382.9     .05       0  4969.1     .03       0  5026.4     .05       0
  5064.5     .05       0  5554.8     .08       0  5853.5     .05       0
Bank Sta=4963.1,5026.4
XS Rating Curve= 0 ,0
Exp/Cntr=0.3,0.1

Type RM Length L Ch R = 1 ,1415    ,0,0,0
BEGIN DESCRIPTION:
UNT252 IN CCTC 1.0
END DESCRIPTION:
XS GIS Cut Line= 4
       3619745.9     10622784.13      3620466.42     10623066.26
      3620579.27     10622923.03        3620206.     10621651.32
#Sta/Elev= 30
  4177.2  371.87  4207.8  369.09  4224.1  365.41  4286.5  358.16  4321.7  356.26
  4370.6  350.53  4406.7   349.2  4454.7  350.75  4610.8  348.87  4632.2  349.75
  4647.4  349.37  4653.7  347.94  4671.8  349.04  4971.5   347.9  4979.1  347.24
  4985.5   342.9  4993.5  332.85  4999.8  332.35    5008  335.47  5022.4  348.41
  5099.3  347.24  5428.1  348.67  5584.4  351.58  5788.3  351.04  6086.8  354.99
    6123  355.55  6209.8  358.99  6220.2  360.51    6314  365.23  6458.7  375.59
#Mann= 5 ,-1 , 0
  4177.2     .03       0  4971.5     .01       0  5022.4     .03       0
  6086.8     .08       0    6123     .05       0
Bank Sta=4971.5,5022.4
XS Rating Curve= 0 ,0
Exp/Cntr=0.3,0.1

Chan Stop Cuts=-1
Use User Specified Reach Order=0
Composite Channel Slope=5