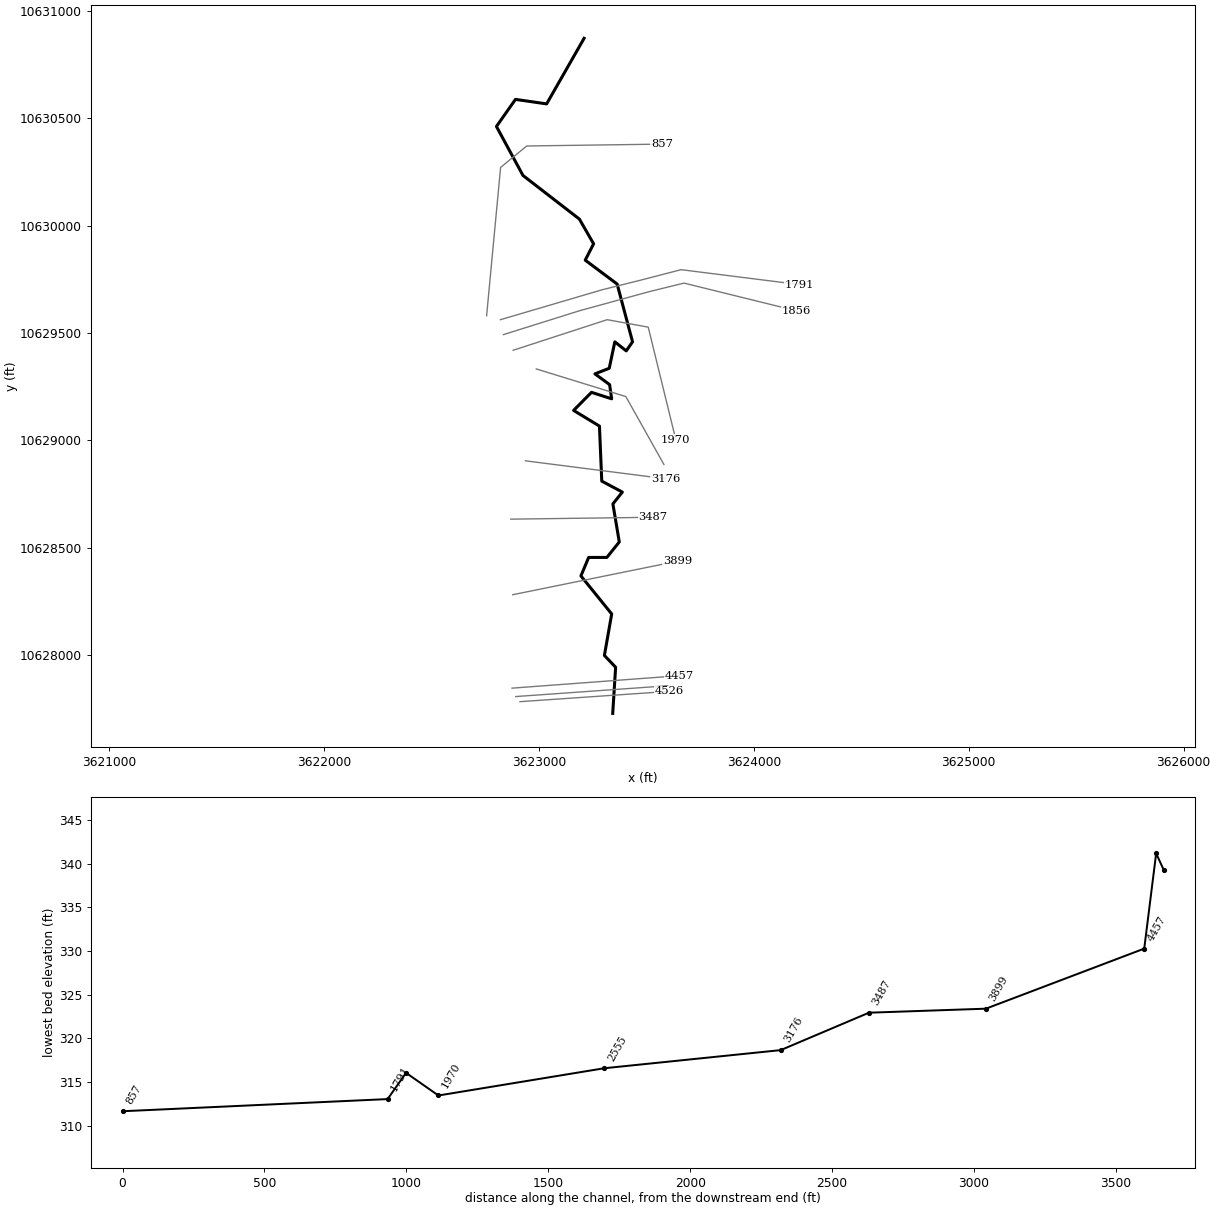
--- UNT253 IN CCTC.prj (project) ---

Proj Title=UNT253 IN CCTC Base Level Engineering
Current Plan=p01
Default Exp/Contr=0.3,0.1
English Units
Geom File=g01
Flow File=f01
Plan File=p01
Y Axis Title=Elevation
X Axis Title(PF)=Main Channel Distance
X Axis Title(XS)=Station
BEGIN DESCRIPTION:
UNT253 IN CCTC
END DESCRIPTION:
DSS Export Rating Curves= 0
DSS Export Rating Curve Sorted= 0
DSS Export Volume Flow Curves= 0
DXF OffsetX= 0
DXF OffsetY= 0
DXF ScaleX= 1
DXF ScaleY= 10

--- UNT253 IN CCTC.p01 (plan) ---

Plan Title=Multiple Run
Short Identifier=Multiple
Geom File=g01
Flow File=f01
Subcritical Flow
K Sum by GR= 0
Std Step Tol= 0.01
Critical Tol= 0.01
Num of Std Step Trials= 20
Max Error Tol= 0.3
Flow Tol Ratio= 0.001
Split Flow NTrial= 30
Split Flow Tol= 0.02
Split Flow Ratio= 0.02
Log Output Level= 0
Friction Slope Method= 1
Unsteady Friction Slope Method= 2
Unsteady Bridges Friction Slope Method= 1
Parabolic Critical Depth
Global Vel Dist=  1 , 1 , 1
Global Log Level= 0
CheckData=True
Encroach Param= -1, 0, 0, 0
BEGIN DESCRIPTION:
Multiple Run
END DESCRIPTION:

--- UNT253 IN CCTC.f01 (steady flow) ---

Flow Title=Multiple
Number of Profiles=7
Profile Names=10-year,25-year,50-year,1pct_min,100-year,1pct_plu,500-year
River Rch & RM= UNT253 IN CCTC,Reach-1,4526
    1450    2034    2529    2301    3112    4208    4689
River Rch & RM= UNT253 IN CCTC,Reach-1,1856
    2552    3698    4699    4358    5894    7970    9241
Boundary for River Rch & Prof#=UNT253 IN CCTC,Reach-1,1
Up Type=0
Dn Type=3
Dn Slope=0.005
Boundary for River Rch & Prof#=UNT253 IN CCTC,Reach-1,2
Up Type=0
Dn Type=3
Dn Slope=0.005
Boundary for River Rch & Prof#=UNT253 IN CCTC,Reach-1,3
Up Type=0
Dn Type=3
Dn Slope=0.005
Boundary for River Rch & Prof#=UNT253 IN CCTC,Reach-1,4
Up Type=0
Dn Type=3
Dn Slope=0.005
Boundary for River Rch & Prof#=UNT253 IN CCTC,Reach-1,5
Up Type=0
Dn Type=3
Dn Slope=0.005
Boundary for River Rch & Prof#=UNT253 IN CCTC,Reach-1,6
Up Type=0
Dn Type=3
Dn Slope=0.005
Boundary for River Rch & Prof#=UNT253 IN CCTC,Reach-1,7
Up Type=0
Dn Type=3
Dn Slope=0.005

--- UNT253 IN CCTC.g01 (geometry) ---

Geom Title=Existing Conditions

River Reach=UNT253 IN CCTC,Reach-1
Reach XY= 30
      3623343.74     10627730.48      3623357.25     10627945.00
      3623305.00     10628000.00      3623339.00     10628193.00
      3623195.75     10628370.00      3623231.75     10628456.00
      3623316.50     10628456.00      3623374.25     10628528.00
      3623344.50     10628705.00      3623388.50     10628760.00
      3623292.75     10628811.00      3623282.00     10629067.00
      3623161.75     10629140.00      3623245.00     10629224.00
      3623338.75     10629194.00      3623329.25     10629260.00
      3623261.00     10629310.00      3623327.50     10629336.00
      3623353.50     10629459.00      3623406.50     10629417.00
      3623436.00     10629459.00      3623364.25     10629728.00
      3623215.75     10629839.00      3623254.75     10629915.00
      3623188.75     10630030.00      3622926.25     10630233.00
      3622802.75     10630461.00      3622891.25     10630587.00
      3623036.25     10630566.00      3623210.50     10630871.00

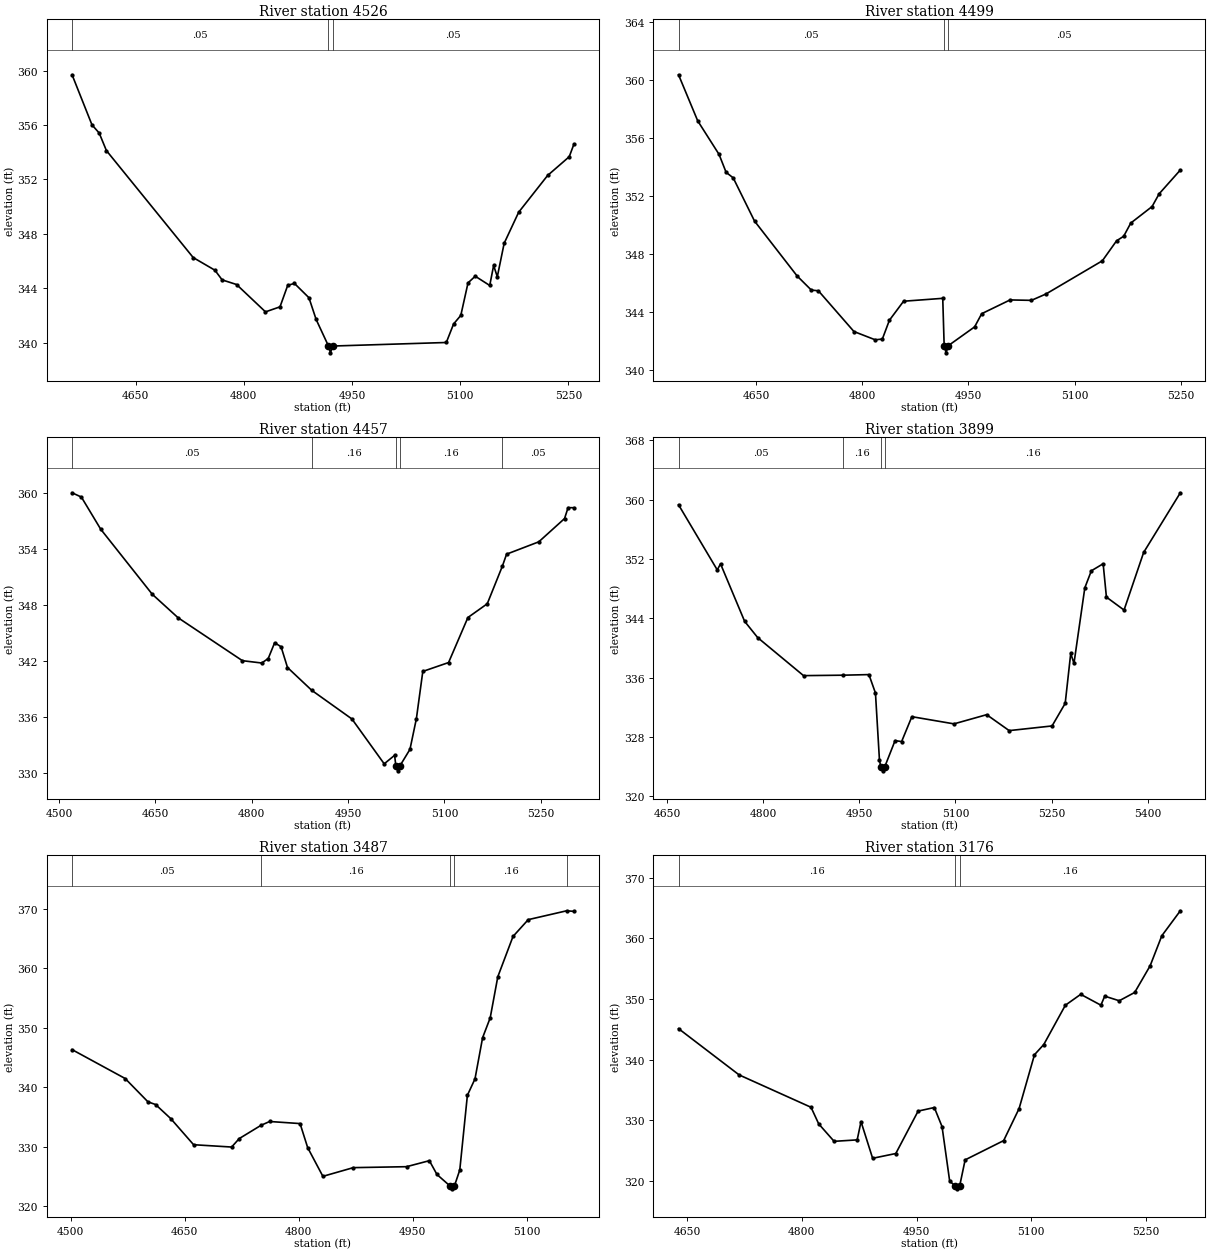
Type RM Length L Ch R = 1,4526,27,27,27
BEGIN DESCRIPTION:
UNT253 IN CCTC 7.0
END DESCRIPTION:
XS GIS Cut Line= 2
      3622912.11     10627784.88      3623605.96     10627832.82
#Sta/Elev= 30
  4562.0  359.69  4589.6  356.01  4599.6  355.41  4609.6  354.12  4729.9  346.26
  4760.0  345.33  4770.0  344.62  4790.0  344.28  4830.1  342.27  4850.2  342.64
  4860.9  344.22  4870.2  344.36  4890.3  343.31  4900.3  341.71  4917.4  339.76
  4920.1  339.26  4923.4  339.76  5080.7  340.02  5090.8  341.38  5100.8  342.01
  5110.8  344.40  5120.8  344.89  5140.9  344.21  5146.3  345.68  5151.4  344.85
  5160.9  347.31  5181.0  349.59  5221.1  352.29  5251.1  353.67  5257.5  354.58
#Mann=3,-1,0
  4562.0    0.05       0  4917.4   0.035       0  4923.4    0.05       0
Bank Sta=4917.4,4923.4
Exp/Cntr=0.3,0.1

Type RM Length L Ch R = 1,4499,42,42,42
BEGIN DESCRIPTION:
Mapping XS b2dfd5b1
END DESCRIPTION:
XS GIS Cut Line= 2
      3622892.57     10627808.75      3623599.39     10627858.95
#Sta/Elev= 30
  4540.7  360.35  4567.8  357.17  4597.9  354.86  4607.9  353.62  4617.9  353.24
  4648.0  350.26  4708.2  346.47  4728.2  345.50  4738.2  345.45  4788.4  342.64
  4818.4  342.07  4828.5  342.12  4838.5  343.42  4858.5  344.73  4913.8  344.93
  4915.8  341.67  4918.5  341.17  4921.8  341.67  4958.8  342.96  4968.8  343.87
  5008.9  344.82  5039.0  344.79  5059.6  345.23  5139.2  347.52  5159.3  348.90
  5169.3  349.21  5179.3  350.12  5209.4  351.26  5219.4  352.14  5249.3  353.78
#Mann=3,-1,0
  4540.7    0.05       0  4915.8   0.035       0  4921.8    0.05       0
Bank Sta=4915.8,4921.8
Exp/Cntr=0.3,0.1

Type RM Length L Ch R = 1,4457,558,558,558
BEGIN DESCRIPTION:
Mapping XS 800627bb
END DESCRIPTION:
XS GIS Cut Line= 2
      3622875.20     10627847.82      3623654.04     10627905.82
#Sta/Elev= 30
  4520.5  360.04  4535.0  359.58  4565.0  356.15  4645.3  349.18  4685.4  346.67
  4785.6  342.07  4815.7  341.82  4825.8  342.30  4835.8  343.99  4845.8  343.56
  4855.8  341.34  4893.5  338.90  4956.1  335.83  5006.3  331.03  5022.5  331.94
  5024.5  330.78  5027.3  330.28  5030.5  330.78  5046.4  332.58  5056.4  335.86
  5066.4  340.92  5106.5  341.87  5136.6  346.69  5166.7  348.16  5190.2  352.18
  5196.8  353.47  5246.9  354.79  5287.0  357.28  5292.5  358.45  5301.5  358.44
#Mann=5,-1,0
  4520.5    0.05       0  4893.5    0.16       0  5024.5    0.07       0
  5030.5    0.16       0  5190.2    0.05       0
Bank Sta=5024.5,5030.5
Exp/Cntr=0.3,0.1

Type RM Length L Ch R = 1,3899,412,412,412
BEGIN DESCRIPTION:
Mapping XS 34130178
END DESCRIPTION:
XS GIS Cut Line= 2
      3622878.55     10628282.53      3623645.65     10628438.55
#Sta/Elev= 30
  4668.1  359.32  4728.5  350.53  4733.6  351.35  4771.2  343.59  4791.6  341.39
  4863.1  336.26  4925.0  336.32  4965.1  336.40  4975.3  333.91  4981.5  324.92
  4983.6  323.91  4986.3  323.41  4989.6  323.91  5005.9  327.49  5016.1  327.36
  5032.1  330.72  5097.8  329.75  5148.8  330.99  5183.9  328.84  5250.8  329.47
  5271.3  332.52  5279.9  339.25  5285.0  337.92  5301.9  348.11  5312.1  350.41
  5330.5  351.36  5335.6  346.86  5363.1  345.11  5393.7  352.89  5450.9  360.94
#Mann=4,-1,0
  4668.1    0.05       0  4925.0    0.16       0  4983.6    0.07       0
  4989.6    0.16       0
Bank Sta=4983.6,4989.6
Exp/Cntr=0.3,0.1

Type RM Length L Ch R = 1,3487,311,311,311
BEGIN DESCRIPTION:
UNT253 IN CCTC 6.0
END DESCRIPTION:
XS GIS Cut Line= 2
      3622869.85     10628634.09      3623529.59     10628642.77
#Sta/Elev= 30
  4502.0  346.33  4571.8  341.48  4601.8  337.56  4611.8  337.11  4631.8  334.74
  4661.8  330.36  4711.8  329.97  4721.8  331.39  4750.6  333.63  4761.8  334.26
  4801.8  333.91  4811.8  329.87  4831.8  325.05  4871.8  326.51  4941.8  326.67
  4971.8  327.68  4981.8  325.36  4998.8  323.45  5001.6  322.95  5004.8  323.45
  5011.8  326.12  5021.8  338.66  5031.8  341.42  5041.8  348.33  5051.8  351.67
  5061.8  358.57  5081.8  365.34  5101.8  368.16  5152.4  369.65  5161.8  369.55
#Mann=5,-1,0
  4502.0    0.05       0  4750.6    0.16       0  4998.8    0.07       0
  5004.8    0.16       0  5152.4    0.05       0
Bank Sta=4998.8,5004.8
Exp/Cntr=0.3,0.1

Type RM Length L Ch R = 1,3176,621,621,621
BEGIN DESCRIPTION:
UNT253 IN CCTC 5.0
END DESCRIPTION:
XS GIS Cut Line= 2
      3622937.73     10628905.48      3623588.82     10628822.14
#Sta/Elev= 30
  4638.7  345.11  4718.0  337.47  4812.0  332.13  4822.1  329.38  4842.2  326.51
  4872.4  326.75  4877.4  329.76  4892.6  323.71  4922.9  324.50  4952.1  331.50
  4973.3  332.09  4983.4  328.94  4993.4  319.93  5000.5  319.17  5003.3  318.67
  5006.5  319.17  5013.6  323.45  5064.0  326.63  5084.2  331.92  5104.3  340.80
  5116.5  342.49  5144.7  348.97  5164.8  350.77  5191.2  348.98  5196.2  350.47
  5215.2  349.71  5235.4  351.08  5255.6  355.48  5270.9  360.44  5295.1  364.56
#Mann=3,-1,0
  4638.7    0.16       0  5000.5    0.07       0  5006.5    0.16       0
Bank Sta=5000.5,5006.5
Exp/Cntr=0.3,0.1

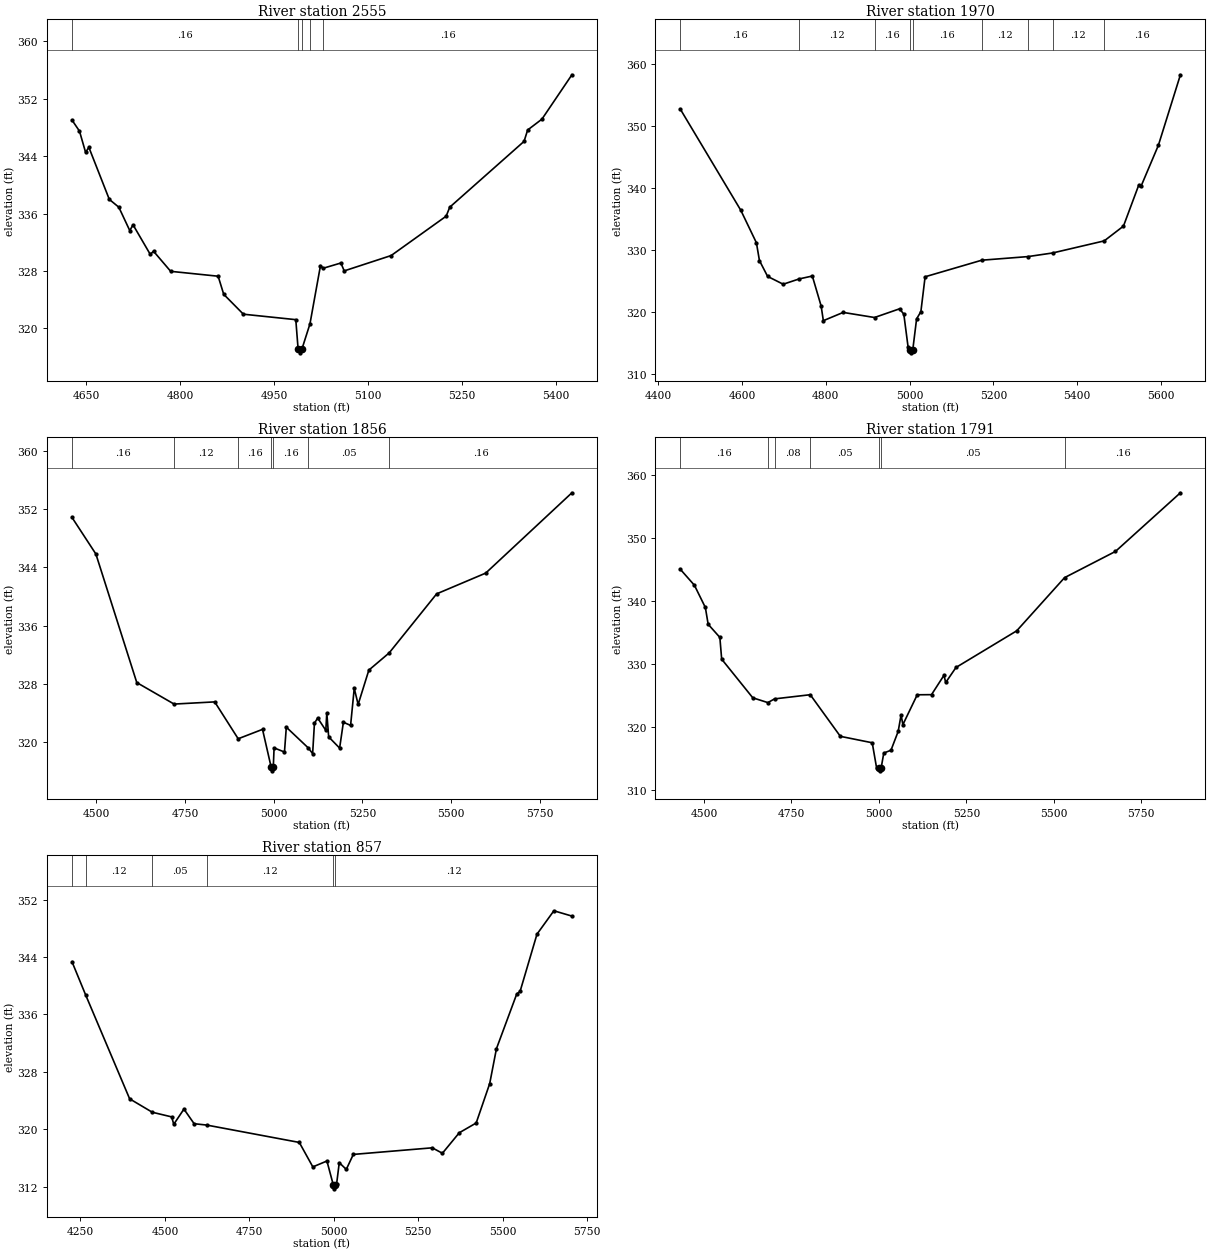
Type RM Length L Ch R = 1,2555,585,585,585
BEGIN DESCRIPTION:
Mapping XS 23879f72
END DESCRIPTION:
XS GIS Cut Line= 3
      3622988.09     10629332.91      3623404.78     10629204.43
      3623581.89     10628888.42
#Sta/Elev= 30
  4627.5  349.02  4639.5  347.47  4649.2  344.53  4654.5  345.21  4687.1  337.97
  4702.3  336.88  4719.8  333.62  4725.0  334.43  4752.5  330.31  4757.7  330.75
  4785.1  327.95  4860.9  327.27  4869.8  324.75  4901.2  321.98  4984.9  321.22
  4988.6  317.10  4991.4  316.60  4994.6  317.10  5007.5  320.63  5024.3  328.75
  5028.3  328.37  5056.9  329.11  5062.2  328.01  5137.2  330.15  5225.0  335.63
  5230.7  336.88  5349.4  346.05  5355.1  347.63  5377.9  349.14  5425.8  355.32
#Mann=5,-1,0
  4627.5    0.16       0  4988.6    0.07       0  4994.6    0.16       0
  5007.5    0.12       0  5028.3    0.16       0
Bank Sta=4988.6,4994.6
Exp/Cntr=0.3,0.1

Type RM Length L Ch R = 1,1970,114,114,114
BEGIN DESCRIPTION:
UNT253 IN CCTC 4.0
END DESCRIPTION:
XS GIS Cut Line= 4
      3622880.47     10629419.71      3623317.97     10629562.07
      3623508.95     10629527.35      3623637.16     10629004.12
#Sta/Elev= 30
  4453.2  352.68  4597.2  336.43  4634.4  331.20  4641.6  328.34  4661.1  325.79
  4698.3  324.53  4736.7  325.39  4767.8  325.85  4788.8  321.03  4794.1  318.66
  4841.4  319.99  4916.2  319.17  4975.9  320.57  4986.1  319.71  4996.3  314.41
  5001.5  313.98  5004.3  313.48  5007.5  313.98  5016.6  318.95  5026.8  320.11
  5036.9  325.73  5172.2  328.40  5282.3  328.98  5340.9  329.56  5464.3  331.51
  5510.2  333.89  5546.7  340.50  5551.9  340.27  5593.5  346.90  5646.1  358.26
#Mann=9,-1,0
  4453.2    0.16       0  4736.7    0.12       0  4916.2    0.16       0
  5001.5    0.07       0  5007.5    0.16       0  5172.2    0.12       0
  5282.3    0.16       0  5340.9    0.12       0  5464.3    0.16       0
Bank Sta=5001.5,5007.5
Exp/Cntr=0.3,0.1

Type RM Length L Ch R = 1,1856,65,65,65
BEGIN DESCRIPTION:
UNT253 IN CCTC 3.0
END DESCRIPTION:
XS GIS Cut Line= 5
      3622835.33     10629492.62      3623189.50     10629603.74
      3623519.36     10629694.02      3623675.61     10629732.21
      3624195.49     10629603.97
#Sta/Elev= 30
  4431.1  350.84  4498.5  345.82  4613.8  328.18  4719.0  325.23  4833.5  325.53
  4899.7  320.47  4968.3  321.76  4992.7  316.57  4995.5  316.07  4998.7  316.57
  5000.9  319.22  5030.2  318.65  5035.4  322.06  5097.8  319.19  5109.6  318.43
  5114.7  322.60  5123.8  323.32  5146.8  321.62  5149.5  324.04  5154.8  320.73
  5185.7  319.19  5196.3  322.74  5216.6  322.30  5226.9  327.39  5237.9  325.18
  5268.1  329.89  5325.4  332.25  5459.2  340.35  5597.6  343.20  5840.6  354.22
#Mann=7,-1,0
  4431.1    0.16       0  4719.0    0.12       0  4899.7    0.16       0
  4992.7    0.07       0  4998.7    0.16       0  5097.8    0.05       0
  5325.4    0.16       0
Bank Sta=4992.7,4998.7
Exp/Cntr=0.3,0.1

Type RM Length L Ch R = 1,1791,934,934,934
BEGIN DESCRIPTION:
UNT253 IN CCTC 2.0
END DESCRIPTION:
XS GIS Cut Line= 5
      3622821.40     10629562.06      3623293.67     10629700.96
      3623474.22     10629746.10      3623661.72     10629794.71
      3624213.79     10629725.27
#Sta/Elev= 30
  4433.1  345.00  4472.9  342.50  4504.2  338.97  4512.2  336.31  4545.6  334.23
  4550.8  330.78  4639.7  324.65  4682.8  323.89  4701.9  324.48  4803.9  325.14
  4889.9  318.54  4981.0  317.52  4993.3  313.59  5000.6  313.57  5003.4  313.07
  5006.6  313.57  5014.0  315.89  5034.6  316.34  5055.2  319.33  5063.4  321.93
  5068.6  320.40  5109.6  325.13  5150.4  325.15  5185.9  328.21  5191.0  327.08
  5220.3  329.46  5393.8  335.27  5530.5  343.70  5676.0  347.86  5861.6  357.16
#Mann=7,-1,0
  4433.1    0.16       0  4682.8    0.12       0  4701.9    0.08       0
  4803.9    0.05       0  5000.6    0.04       0  5006.6    0.05       0
  5530.5    0.16       0
Bank Sta=5000.6,5006.6
Exp/Cntr=0.3,0.1

Type RM Length L Ch R = 1,857,0,0,0
BEGIN DESCRIPTION:
UNT253 IN CCTC 1.0
END DESCRIPTION:
XS GIS Cut Line= 4
      3622757.00     10629580.22      3622822.11     10630270.37
      3622943.64     10630370.20      3623572.99     10630378.88
#Sta/Elev= 30
  4224.8  343.35  4265.5  338.69  4395.5  324.23  4462.5  322.36  4519.9  321.71
  4526.1  320.68  4556.2  322.80  4586.4  320.76  4623.8  320.57  4897.7  318.15
  4937.8  314.74  4979.5  315.56  4998.6  312.18  5001.4  311.68  5004.6  312.18
  5008.1  312.34  5016.0  315.33  5036.8  314.39  5057.6  316.48  5291.3  317.40
  5321.3  316.64  5371.3  319.50  5421.3  320.86  5461.3  326.35  5481.3  331.22
  5541.3  338.84  5551.3  339.21  5601.3  347.19  5651.3  350.45  5704.7  349.71
#Mann=6,-1,0
  4224.8    0.16       0  4265.5    0.12       0  4462.5    0.05       0
  4623.8    0.12       0  4998.6    0.07       0  5004.6    0.12       0
Bank Sta=4998.6,5004.6
Exp/Cntr=0.3,0.1

Chan Stop Cuts=-1