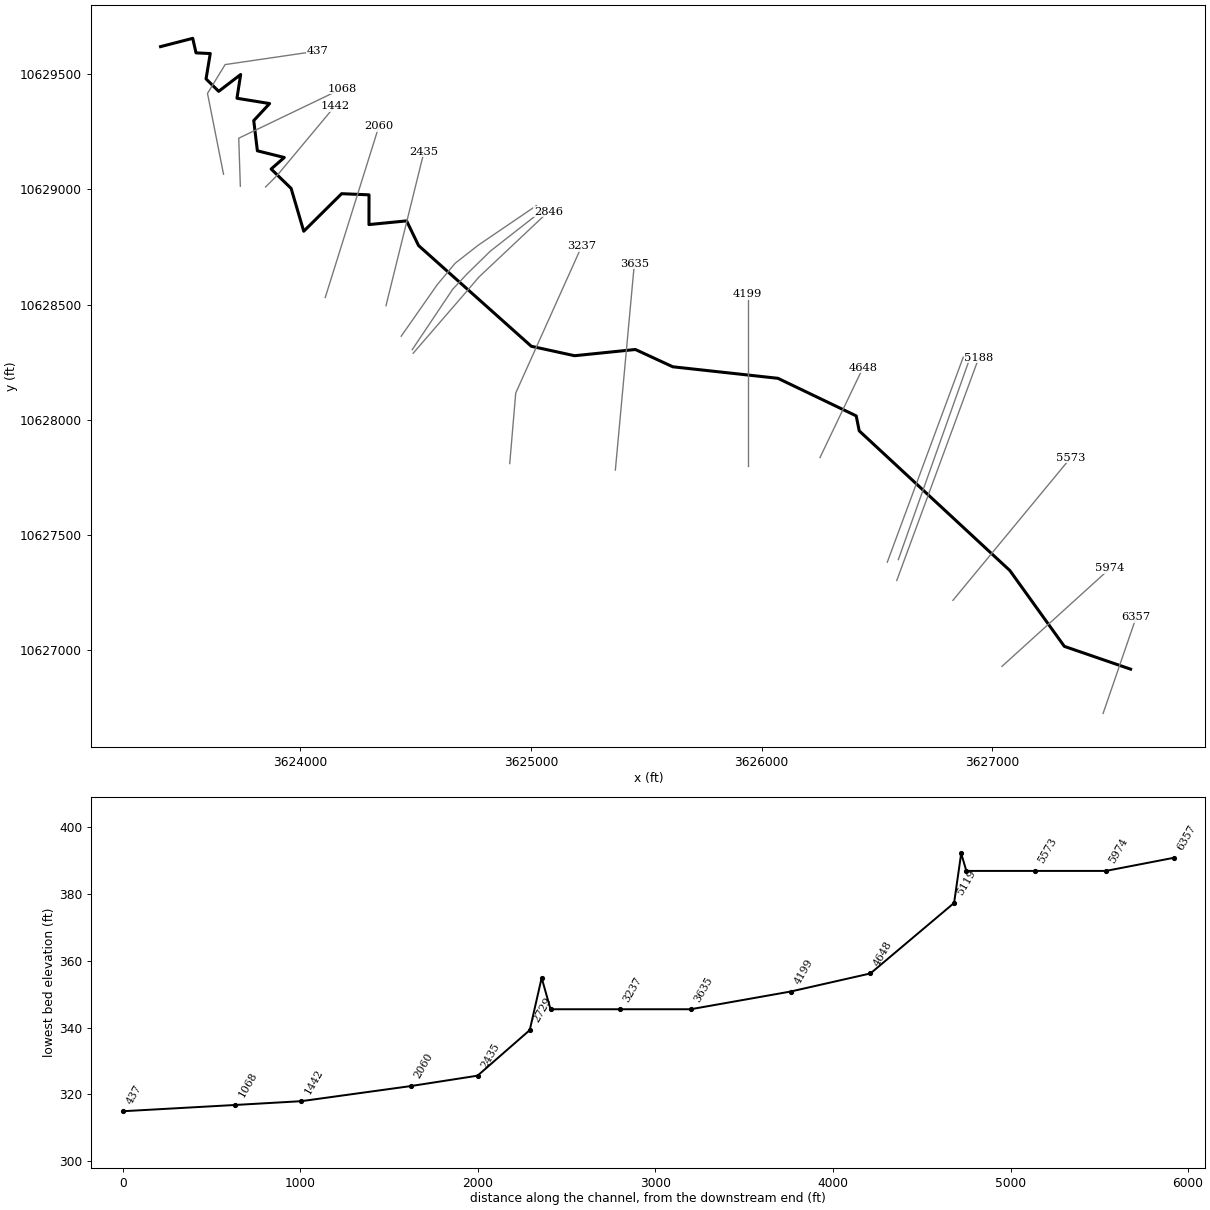
--- UNT254 IN CCTC.prj (project) ---

Proj Title=UNT254 IN CCTC Base Level Engineering
Current Plan=p01
Default Exp/Contr=0.3,0.1
English Units
Geom File=g01
Flow File=f01
Plan File=p01
Y Axis Title=Elevation
X Axis Title(PF)=Main Channel Distance
X Axis Title(XS)=Station
BEGIN DESCRIPTION:
UNT254 IN CCTC
END DESCRIPTION:
DSS Export Rating Curves= 0
DSS Export Rating Curve Sorted= 0
DSS Export Volume Flow Curves= 0
DXF OffsetX= 0
DXF OffsetY= 0
DXF ScaleX= 1
DXF ScaleY= 10

--- UNT254 IN CCTC.p01 (plan) ---

Plan Title=Multiple Run
Short Identifier=Multiple
Geom File=g01
Flow File=f01
Subcritical Flow
K Sum by GR= 0
Std Step Tol= 0.01
Critical Tol= 0.01
Num of Std Step Trials= 20
Max Error Tol= 0.3
Flow Tol Ratio= 0.001
Split Flow NTrial= 30
Split Flow Tol= 0.02
Split Flow Ratio= 0.02
Log Output Level= 0
Friction Slope Method= 1
Unsteady Friction Slope Method= 2
Unsteady Bridges Friction Slope Method= 1
Parabolic Critical Depth
Global Vel Dist=  1 , 1 , 1
Global Log Level= 0
CheckData=True
Encroach Param= -1, 0, 0, 0
BEGIN DESCRIPTION:
Multiple Run
END DESCRIPTION:

--- UNT254 IN CCTC.f01 (steady flow) ---

Flow Title=Multiple
Number of Profiles=7
Profile Names=10-year,25-year,50-year,1pct_min,100-year,1pct_plu,500-year
River Rch & RM= UNT254 IN CCTC,Reach-1,6357
    1427    2009    2505    2287    3093    4183    4692
Boundary for River Rch & Prof#=UNT254 IN CCTC,Reach-1,1
Up Type=0
Dn Type=3
Dn Slope=0.005
Boundary for River Rch & Prof#=UNT254 IN CCTC,Reach-1,2
Up Type=0
Dn Type=3
Dn Slope=0.005
Boundary for River Rch & Prof#=UNT254 IN CCTC,Reach-1,3
Up Type=0
Dn Type=3
Dn Slope=0.005
Boundary for River Rch & Prof#=UNT254 IN CCTC,Reach-1,4
Up Type=0
Dn Type=3
Dn Slope=0.005
Boundary for River Rch & Prof#=UNT254 IN CCTC,Reach-1,5
Up Type=0
Dn Type=3
Dn Slope=0.005
Boundary for River Rch & Prof#=UNT254 IN CCTC,Reach-1,6
Up Type=0
Dn Type=3
Dn Slope=0.005
Boundary for River Rch & Prof#=UNT254 IN CCTC,Reach-1,7
Up Type=0
Dn Type=3
Dn Slope=0.005

--- UNT254 IN CCTC.g01 (geometry) ---

Geom Title=Existing Conditions
Program Version=4.10

River Reach=UNT254 IN CCTC  ,Reach-1
Reach XY= 30
      3627599.41     10626918.14      3627312.25       10627017.
        3627076.       10627346.        3626423.       10627952.
        3626410.       10628017.       3626070.5       10628180.
      3625614.75       10628230.      3625452.75       10628305.
        3625189.       10628278.       3625001.5       10628319.
      3624512.75       10628756.        3624461.       10628863.
      3624297.75       10628847.        3624298.       10628976.
      3624179.25       10628981.        3624015.       10628818.
      3623960.25       10629004.      3623873.75       10629088.
      3623930.75       10629138.        3623814.       10629167.
      3623798.25       10629298.        3623867.       10629372.
       3623725.5       10629395.       3623741.5       10629498.
      3623646.25       10629425.       3623591.5       10629479.
      3623609.75       10629589.        3623548.       10629592.
      3623533.75       10629655.      3623394.25       10629619.

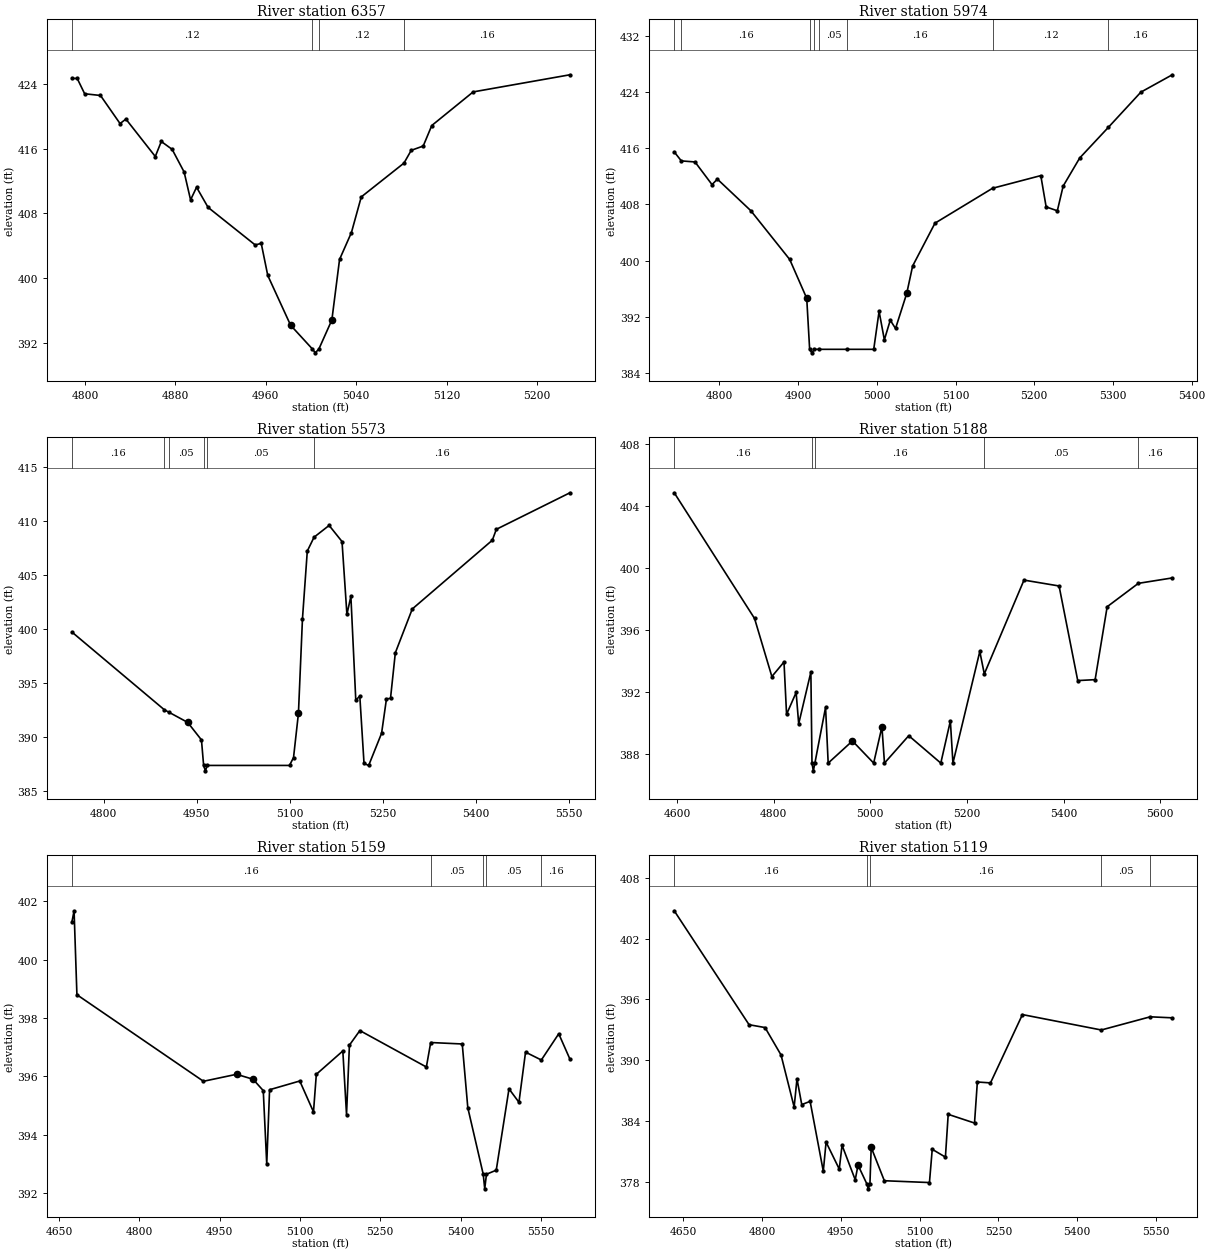
Type RM Length L Ch R = 1 ,6357    ,383,383,383
BEGIN DESCRIPTION:
UNT254 IN CCTC 12.0
END DESCRIPTION:
XS GIS Cut Line= 2
      3627480.32     10626726.28      3627623.55     10627142.95
#Sta/Elev= 30
  4788.4  424.64  4793.1  424.64  4799.7  422.75  4813.7  422.54    4831  419.08
  4836.2  419.63  4862.2  415.02  4867.5  416.87  4877.1   415.9  4887.7  413.11
  4893.4  409.68  4898.7  411.23  4908.9  408.75  4950.6  404.12  4955.9  404.32
  4961.7  400.36  4981.9  394.23    5001  391.33  5003.8  390.83    5007  391.33
  5018.4  394.88  5025.2  402.34  5035.7  405.65  5044.4  410.04  5082.2  414.21
  5088.6  415.78  5099.2  416.31  5106.8  418.84  5143.4  422.98    5229  425.09
#Mann= 4 ,-1 , 0
  4788.4     .12       0    5001     .07       0    5007     .12       0
  5082.2     .16       0
Bank Sta=4981.9,5018.4
XS Rating Curve= 0 ,0
Exp/Cntr=0.3,0.1

Type RM Length L Ch R = 1 ,5974    ,401,401,401
BEGIN DESCRIPTION:
UNT254 IN CCTC 11.0
END DESCRIPTION:
XS GIS Cut Line= 2
      3627041.98     10626930.29      3627510.46     10627355.39
#Sta/Elev= 30
  4742.7  415.46  4751.7  414.18  4769.1  414.03  4790.7  410.81  4797.5  411.59
    4840   407.1  4889.4  400.17    4911  394.65  4914.7   387.4  4917.5   386.9
  4920.7   387.4  4927.2   387.4  4962.5   387.4  4996.1   387.4  5002.9   392.8
  5009.6  388.75  5017.1  391.54  5023.8  390.36    5038  395.34  5045.5  399.24
  5073.9  405.33    5147  410.29  5208.3  412.09  5215.1  407.64  5229.3  407.09
  5236.7   410.6  5257.7  414.59  5294.2  418.96  5335.4  423.95  5375.3  426.42
#Mann= 8 ,-1 , 0
  4742.7     .12       0  4751.7     .16       0  4914.7     .07       0
  4920.7     .16       0  4927.2     .05       0  4962.5     .16       0
    5147     .12       0  5294.2     .16       0
Bank Sta=4911,5038
XS Rating Curve= 0 ,0
Exp/Cntr=0.3,0.1

Type RM Length L Ch R = 1 ,5573    ,385,385,385
BEGIN DESCRIPTION:
Mapping XS cee8cdda
END DESCRIPTION:
XS GIS Cut Line= 2
      3626829.28     10627216.72      3627340.55     10627836.31
#Sta/Elev= 30
  4748.9  399.74    4898  392.55  4904.8  392.34  4935.7  391.38  4957.9  389.76
  4961.4   387.4  4964.2   386.9  4967.4   387.4  5099.9   387.4  5106.4  388.13
  5114.3  392.21  5120.8  400.96  5128.6  407.23  5139.5  408.51  5163.8   409.6
  5184.6  408.11  5192.5  401.37  5198.9  403.04  5206.8  393.44  5213.3  393.81
  5220.1  387.58  5227.6   387.4  5248.4  390.37  5256.3  393.56  5262.8   393.6
  5270.6  397.82  5297.9  401.87    5427  408.23  5433.5  409.24  5552.2  412.62
#Mann= 6 ,-1 , 0
  4748.9     .16       0    4898      .1       0  4904.8     .05       0
  4961.4    .033       0  4967.4     .05       0  5139.5     .16       0
Bank Sta=4935.7,5114.3
XS Rating Curve= 0 ,0
Exp/Cntr=0.3,0.1

Type RM Length L Ch R = 1 ,5188    ,29,29,29
BEGIN DESCRIPTION:
Mapping XS 5ce1b3c0
END DESCRIPTION:
XS GIS Cut Line= 2
      3626585.85     10627302.95      3626941.75     10628269.94
#Sta/Elev= 30
  4594.5  404.86  4760.7  396.74  4796.5  392.99  4821.6  393.93  4826.9  390.55
  4846.7  391.96    4852  389.94  4877.2  393.28  4879.5   387.4  4882.3   386.9
  4885.5   387.4  4907.6     391    4913   387.4  4963.2  388.83  5007.1   387.4
  5024.2  389.74  5029.5   387.4  5079.7  389.17    5146   387.4  5165.8  390.12
  5171.1   387.4  5226.7  394.61    5236  393.16  5318.1  399.22  5390.7  398.84
  5429.3  392.73  5465.3  392.79  5490.2   397.5  5554.7  399.01  5624.9  399.36
#Mann= 5 ,-1 , 0
  4594.5     .16       0  4879.5     .07       0  4885.5     .16       0
    5236     .05       0  5554.7     .16       0
Bank Sta=4963.2,5024.2
XS Rating Curve= 0 ,0
Exp/Cntr=0.3,0.1

Type RM Length L Ch R = 1 ,5159    ,40,40,40
BEGIN DESCRIPTION:
Mapping XS 5c53f12b
END DESCRIPTION:
XS GIS Cut Line= 2
      3626592.53     10627393.34      3626903.54      10628269.9
#Sta/Elev= 30
  4674.2  401.29  4678.3  401.68  4683.6   398.8  4919.9  395.83  4981.7  396.07
  5012.5   395.9  5031.6  395.51  5038.1  392.99  5043.4  395.54  5099.8  395.84
  5125.4  394.78  5130.7  396.07  5180.2  396.87  5187.1  394.69  5192.5  397.07
    5212  397.57  5336.2  396.32  5344.3  397.16  5403.2  397.11  5413.6  394.92
  5442.4  392.64  5445.2  392.14  5448.4  392.64  5466.7  392.78  5490.5  395.57
  5509.1  395.11  5521.4  396.83  5550.9  396.56  5583.4  397.46  5604.3  396.59
#Mann= 5 ,-1 , 0
  4674.2     .16       0  5344.3     .05       0  5442.4     .07       0
  5448.4     .05       0  5550.9     .16       0
Bank Sta=4981.7,5012.5
XS Rating Curve= 0 ,0
Exp/Cntr=0.3,0.1

Type RM Length L Ch R = 1 ,5119    ,471,471,471
BEGIN DESCRIPTION:
UNT254 IN CCTC 10.0
END DESCRIPTION:
XS GIS Cut Line= 2
      3626544.79      10627382.5      3626874.05      10628271.7
#Sta/Elev= 30
  4632.9  404.74  4775.4   393.5  4805.8  393.22  4836.2  390.52  4861.2  385.38
  4866.6  388.16  4875.7  385.62  4891.6  385.94  4916.7  379.05    4922  381.92
  4947.1  379.26  4952.4  381.61  4977.5   378.2  4982.8  379.65  4999.5  377.81
  5002.3  377.31  5005.5  377.81  5007.9   381.4  5032.9  378.11  5118.8  377.93
  5124.1  381.21  5149.2  380.44  5154.5  384.66  5204.6   383.8    5210  387.85
    5235  387.76  5295.8   394.5    5446  392.98  5539.1  394.28  5581.1  394.18
#Mann= 5 ,-1 , 0
  4632.9     .16       0  4999.5     .07       0  5005.5     .16       0
    5446     .05       0  5539.1     .16       0
Bank Sta=4982.8,5007.9
XS Rating Curve= 0 ,0
Exp/Cntr=0.3,0.1

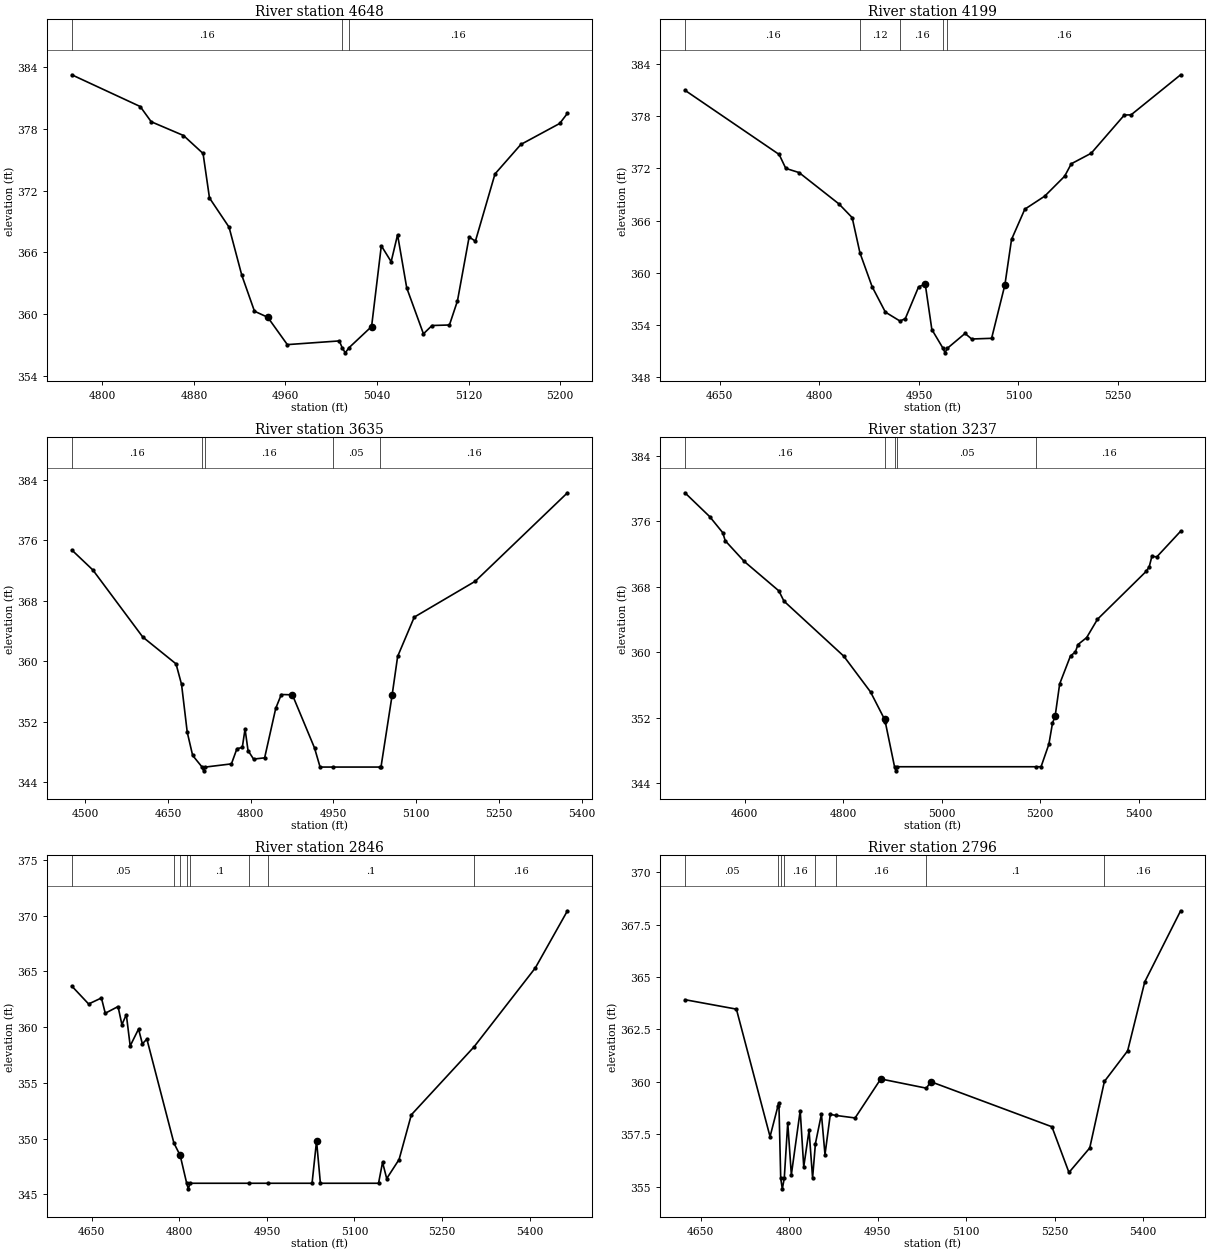
Type RM Length L Ch R = 1 ,4648    ,449,449,449
BEGIN DESCRIPTION:
UNT254 IN CCTC 9.0
END DESCRIPTION:
XS GIS Cut Line= 2
      3626252.99     10627836.21      3626439.69     10628226.89
#Sta/Elev= 30
  4773.3  383.28  4833.1  380.19  4842.7  378.71  4870.9  377.37    4888  375.62
  4893.6  371.29  4910.7  368.45  4921.8  363.78  4932.9  360.27  4944.5  359.68
  4961.6  357.02    5007  357.38  5009.5  356.72  5012.2  356.22  5015.5  356.72
  5035.2  358.78  5043.7  366.64  5052.3  365.09  5057.9  367.71  5065.9  362.54
  5080.5  358.07    5088  358.88  5103.2  358.93  5110.2  361.27  5120.4  367.49
  5125.9  367.09    5143  373.63  5165.6   376.5  5199.5  378.54  5206.3  379.53
#Mann= 3 ,-1 , 0
  4773.3     .16       0  5009.5     .07       0  5015.5     .16       0
Bank Sta=4944.5,5035.2
XS Rating Curve= 0 ,0
Exp/Cntr=0.3,0.1

Type RM Length L Ch R = 1 ,4199    ,564,564,564
BEGIN DESCRIPTION:
UNT254 IN CCTC 8.0
END DESCRIPTION:
XS GIS Cut Line= 2
      3625939.51     10627798.29      3625939.51     10628544.89
#Sta/Elev= 30
  4597.6  380.99  4739.5  373.61  4749.5  372.01  4769.5  371.53  4829.5  367.93
  4849.5  366.35  4861.2   362.3  4879.5  358.42  4899.5  355.49  4921.4  354.47
  4929.5  354.74  4949.5  358.39  4959.5  358.72  4969.5  353.49  4986.5  351.31
  4989.3  350.81  4992.5  351.31  5019.5  353.04  5029.5   352.4  5059.5  352.48
  5079.5  358.62  5089.5  363.84  5109.5  367.32  5139.5  368.82  5169.5  371.11
  5179.5  372.54  5209.5  373.75  5259.5  378.15  5269.5  378.16  5344.2  382.77
#Mann= 5 ,-1 , 0
  4597.6     .16       0  4861.2     .12       0  4921.4     .16       0
  4986.5     .07       0  4992.5     .16       0
Bank Sta=4959.5,5079.5
XS Rating Curve= 0 ,0
Exp/Cntr=0.3,0.1

Type RM Length L Ch R = 1 ,3635    ,398,398,398
BEGIN DESCRIPTION:
UNT254 IN CCTC 7.0
END DESCRIPTION:
XS GIS Cut Line= 2
      3625365.87     10627782.01      3625448.19     10628676.73
#Sta/Elev= 30
  4475.7   374.7    4514  372.05  4604.4  363.19  4664.7  359.64  4674.7  356.93
    4685  350.61  4694.8  347.54  4711.9     346  4714.6   345.5  4717.9     346
  4765.1  346.42  4775.1  348.43  4784.8  348.59  4789.8  351.03  4795.2  348.18
  4805.3  347.05  4825.3  347.22  4845.4  353.76  4855.5  355.59  4875.6  355.55
  4915.7  348.53  4925.8     346  4948.9     346  5033.6     346  5036.2     346
  5056.3  355.47  5066.4  360.63  5096.5  365.82    5207  370.56  5374.2  382.26
#Mann= 5 ,-1 , 0
  4475.7     .16       0  4711.9    .033       0  4717.9     .16       0
  4948.9     .05       0  5033.6     .16       0
Bank Sta=4875.6,5056.3
XS Rating Curve= 0 ,0
Exp/Cntr=0.3,0.1

Type RM Length L Ch R = 1 ,3237    ,391,391,391
BEGIN DESCRIPTION:
UNT254 IN CCTC 6.0
END DESCRIPTION:
XS GIS Cut Line= 3
      3624907.96     10627810.18      3624934.01     10628116.19
      3625220.47     10628754.22
#Sta/Elev= 30
  4478.6  379.49  4528.8  376.58  4555.4  374.61  4560.4  373.63    4599   371.1
  4669.3   367.5  4679.6  366.25  4801.1  359.52  4855.4  355.15  4884.1  351.78
  4885.4  351.48  4904.2     346    4907   345.5  4910.2     346  5192.2     346
  5201.7     346  5217.6  348.76  5224.9  351.33  5230.3  352.19  5239.5  356.13
  5261.5  359.56  5271.2  360.01  5276.7  360.94  5294.3  361.79  5316.3  364.03
  5414.9  369.87  5421.2  370.42  5426.7  371.71  5436.8  371.66  5485.1  374.79
#Mann= 5 ,-1 , 0
  4478.6     .16       0  4885.4     .05       0  4904.2    .033       0
  4910.2     .05       0  5192.2     .16       0
Bank Sta=4884.1,5230.3
XS Rating Curve= 0 ,0
Exp/Cntr=0.3,0.1

Type RM Length L Ch R = 1 ,2846    ,50,50,50
BEGIN DESCRIPTION:
UNT254 IN CCTC 5.0
END DESCRIPTION:
XS GIS Cut Line= 4
      3624489.56     10628288.93      3624723.91     10628560.16
      3624773.82     10628618.76      3625075.02     10628902.62
#Sta/Elev= 30
  4615.6  363.69  4644.5  362.08  4666.4  362.62    4673  361.25  4694.9  361.85
  4701.5  360.23  4709.1  361.12  4715.7  358.32    4730  359.83  4736.6  358.51
  4744.3  358.93  4790.6  349.61  4800.6  348.57  4801.3  348.51  4812.5     346
  4815.2   345.5  4818.5     346    4920     346  4952.4     346  5027.3     346
    5035  349.79  5041.6     346  5141.2     346  5148.1  347.88  5155.2  346.42
  5176.4  348.13  5197.4  352.14  5304.9  358.24  5409.9  365.32  5464.9  370.44
#Mann= 8 ,-1 , 0
  4615.6     .05       0  4790.6     .16       0  4800.6      .1       0
  4812.5     .07       0  4818.5      .1       0    4920     .16       0
  4952.4      .1       0  5304.9     .16       0
Bank Sta=4801.3,5035
XS Rating Curve= 0 ,0
Exp/Cntr=0.3,0.1

Type RM Length L Ch R = 1 ,2796    ,67,67,67
BEGIN DESCRIPTION:
Mapping XS 4c417bad
END DESCRIPTION:
XS GIS Cut Line= 5
       3624485.2      10628304.1      3624660.97     10628566.67
      3624723.91     10628633.95      3624823.73      10628731.6
      3625053.76     10628911.72
#Sta/Elev= 30
  4623.5  363.92  4710.7  363.47  4767.7  357.39  4781.3  358.87  4782.7     359
  4785.8   355.4  4788.5   354.9  4791.8   355.4  4797.7  358.05  4803.8  355.57
  4818.8  358.63  4824.8  355.95  4833.8  357.69  4839.8  355.42  4844.6  357.06
  4854.8  358.46  4860.8  356.53  4869.8  358.45  4879.6   358.4  4911.8  358.28
  4955.3  360.14  5032.6   359.7    5040  360.01  5245.3  357.86  5274.2  355.68
  5309.4  356.85  5334.2  360.02  5373.6  361.48  5402.6  364.77  5463.4  368.16
#Mann= 8 ,-1 , 0
  4623.5     .05       0  4781.3     .16       0  4785.8     .07       0
  4791.8     .16       0  4844.6      .1       0  4879.6     .16       0
  5032.6      .1       0  5334.2     .16       0
Bank Sta=4955.3,5040
XS Rating Curve= 0 ,0
Exp/Cntr=0.3,0.1

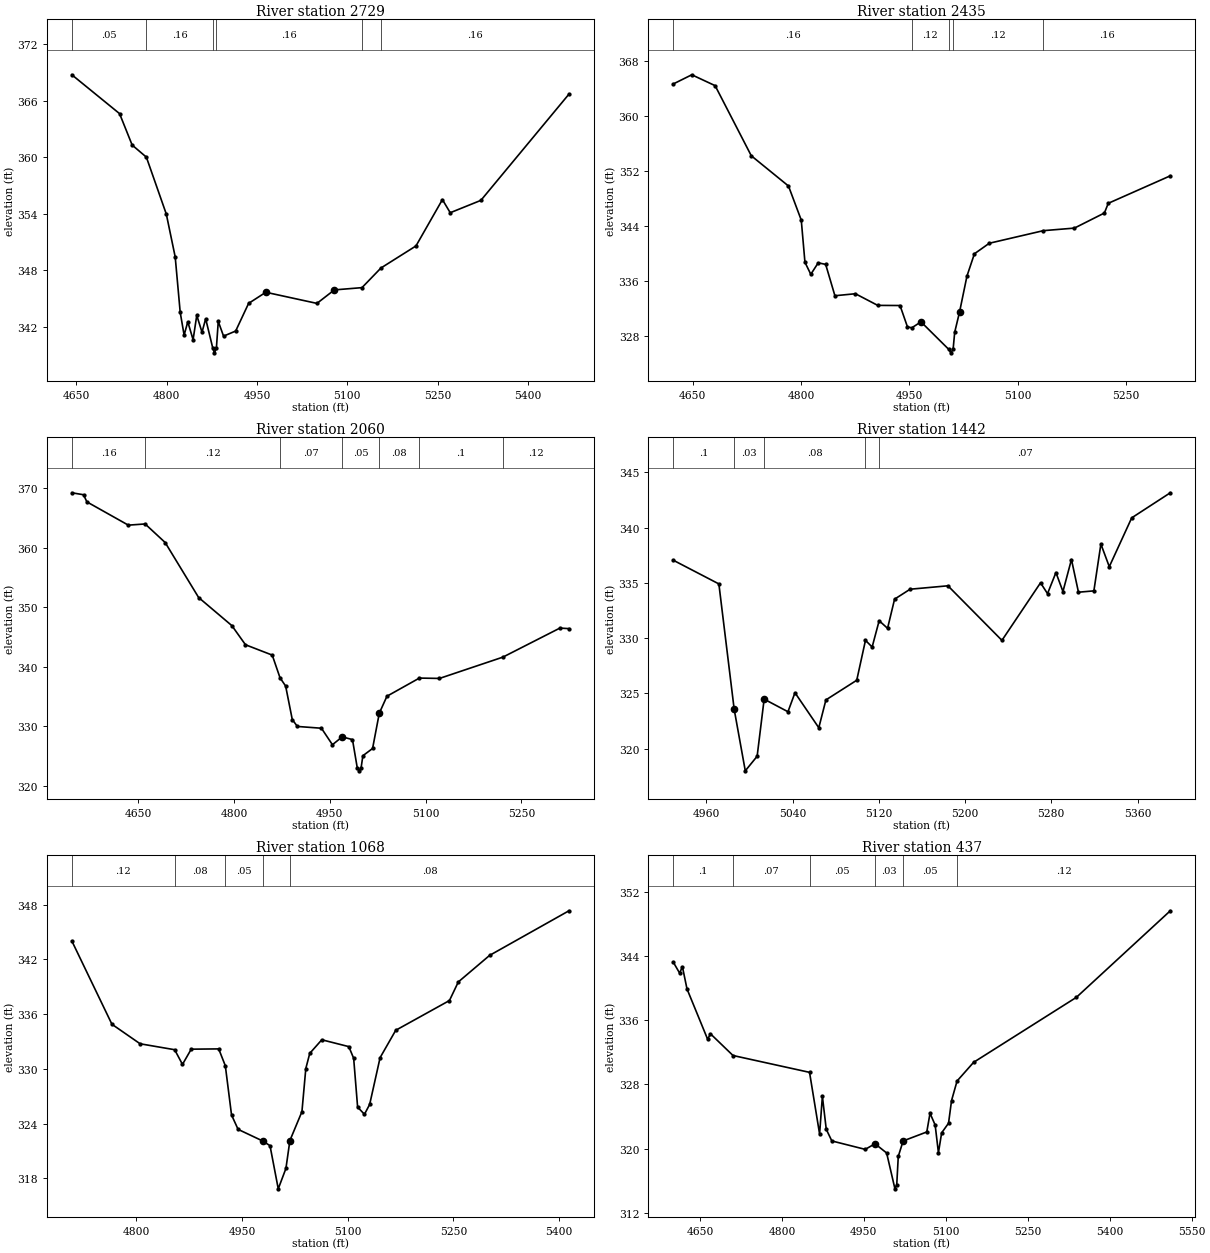
Type RM Length L Ch R = 1 ,2729    ,294,294,294
BEGIN DESCRIPTION:
Mapping XS a5f910bd
END DESCRIPTION:
XS GIS Cut Line= 5
      3624437.46     10628362.69       3624593.7      10628586.2
      3624671.82     10628679.52      3624771.65     10628757.64
      3625023.35     10628929.06
#Sta/Elev= 30
  4642.6  368.73  4721.9  364.61  4742.8  361.28  4766.4     360  4799.5  353.97
  4814.3  349.42  4822.6  343.55  4829.1  341.14  4835.2  342.55    4844  340.65
  4850.1  343.23  4858.8  341.45  4864.9  342.87  4876.7  339.76  4879.5  339.26
  4882.7  339.76  4885.8  342.59  4894.6  341.03  4914.7  341.57  4936.2   344.5
  4964.8  345.68  5049.7   344.5  5078.6  345.93  5124.5  346.17    5156  348.25
  5214.2  350.59  5258.1   355.5  5271.1  354.11    5322  355.42  5468.3  366.68
#Mann= 6 ,-1 , 0
  4642.6     .05       0  4766.4     .16       0  4876.7     .07       0
  4882.7     .16       0  5124.5      .1       0    5156     .16       0
Bank Sta=4964.8,5078.6
XS Rating Curve= 0 ,0
Exp/Cntr=0.3,0.1

Type RM Length L Ch R = 1 ,2435    ,375,375,375
BEGIN DESCRIPTION:
UNT254 IN CCTC 4.0
END DESCRIPTION:
XS GIS Cut Line= 2
      3624371.58     10628495.18      3624536.53     10629163.63
#Sta/Elev= 30
  4622.9  364.65  4648.7  365.99    4681  364.41  4731.1  354.23  4782.6  349.84
  4800.3  344.89  4805.4  338.77  4813.5  337.02  4823.8  338.69  4834.1  338.46
  4846.9  333.91  4875.3   334.2  4906.2  332.51  4937.1  332.49  4947.4  329.38
  4953.5  329.26  4966.1  330.12  5004.6  326.12  5007.4  325.62  5010.6  326.12
  5012.8  328.61  5019.5  331.54  5029.8  336.77  5040.1     340  5060.7  341.53
  5135.7  343.36  5178.6  343.73  5220.1  345.92  5225.5  347.33  5311.4  351.32
#Mann= 5 ,-1 , 0
  4622.9     .16       0  4953.5     .12       0  5004.6     .07       0
  5010.6     .12       0  5135.7     .16       0
Bank Sta=4966.1,5019.5
XS Rating Curve= 0 ,0
Exp/Cntr=0.3,0.1

Type RM Length L Ch R = 1 ,2060    ,618,618,618
BEGIN DESCRIPTION:
UNT254 IN CCTC 3.0
END DESCRIPTION:
XS GIS Cut Line= 2
      3624108.21     10628530.63      3624340.87     10629273.76
#Sta/Elev= 30
  4545.9  369.25  4564.2  368.92  4569.5  367.72  4634.4  363.81  4660.7  364.01
  4692.1  360.89  4744.5  351.65  4796.6  346.92  4817.9  343.71  4859.8  341.97
    4872  338.16  4880.8  336.77  4891.2  331.14  4899.2  329.98  4936.9  329.68
  4954.1  326.91  4969.4  328.23  4985.5  327.77    4993  323.02  4995.8  322.52
    4999  323.02  5001.8  325.06    5017  326.28  5027.5  332.21  5039.5  335.06
  5090.3  338.11  5121.8  338.05  5221.1  341.63  5310.4  346.51  5324.6  346.42
#Mann= 7 ,-1 , 0
  4545.9     .16       0  4660.7     .12       0    4872     .07       0
  4969.4     .05       0  5027.5     .08       0  5090.3      .1       0
  5221.1     .12       0
Bank Sta=4969.4,5027.5
XS Rating Curve= 0 ,0
Exp/Cntr=0.3,0.1

Type RM Length L Ch R = 1 ,1442    ,374,374,374
BEGIN DESCRIPTION:
UNT254 IN CCTC 2.0
END DESCRIPTION:
XS GIS Cut Line= 3
      3623849.61     10629010.19      3623899.61     10629060.19
      3624149.59     10629360.17
#Sta/Elev= 30
  4929.2  337.06  4971.6  334.91  4985.8  323.56  4996.1  317.99  5007.1  319.31
  5013.6  324.48  5035.7  323.34  5042.2  325.06  5064.3  321.89  5070.9  324.41
  5099.5  326.19  5107.6   329.8  5113.8   329.2  5120.3  331.58  5128.1  330.89
  5134.6  333.53    5149  334.43  5184.1  334.74  5234.2   329.8    5270  335.01
  5276.5  334.03  5284.3  335.94  5290.8  334.22  5298.7  337.12  5305.2  334.16
  5319.5  334.28    5326  338.52  5333.8  336.47  5354.6  340.89  5390.4  343.16
#Mann= 5 ,-1 , 0
  4929.2      .1       0  4985.8     .03       0  5013.6     .08       0
  5107.6     .07       0  5120.3     .07       0
Bank Sta=4985.8,5013.6
XS Rating Curve= 0 ,0
Exp/Cntr=0.3,0.1

Type RM Length L Ch R = 1 ,1068    ,631,631,631
BEGIN DESCRIPTION:
Mapping XS 7b65b568
END DESCRIPTION:
XS GIS Cut Line= 3
      3623740.17     10629013.33      3623733.22     10629221.65
      3624181.14     10629436.93
#Sta/Elev= 30
  4708.6  344.02  4765.5  334.89  4805.5  332.75  4854.5   332.1  4865.6  330.49
    4878  332.16    4917  332.19  4926.4  330.34  4935.2  324.95  4944.5  323.37
  4979.6  322.09  4989.8  321.58  5001.5  316.85  5012.4  319.09    5018  322.14
  5035.1  325.31  5040.6  330.04  5046.2   331.7  5063.3  333.19  5101.6  332.44
  5108.5  331.16  5114.1  325.81  5123.8  325.02  5131.2   326.1    5146  331.23
  5168.2  334.23  5244.4  337.49    5257  339.53  5301.4  342.44    5414  347.33
#Mann= 5 ,-1 , 0
  4708.6     .12       0  4854.5     .08       0  4926.4     .05       0
  4979.6     .03       0    5018     .08       0
Bank Sta=4979.6,5018
XS Rating Curve= 0 ,0
Exp/Cntr=0.3,0.1

Type RM Length L Ch R = 1 ,437     ,0,0,0
BEGIN DESCRIPTION:
UNT254 IN CCTC 1.0
END DESCRIPTION:
XS GIS Cut Line= 4
      3623667.26     10629065.35      3623597.81     10629416.09
       3623674.2     10629541.09      3624075.76     10629599.94
#Sta/Elev= 30
    4601  343.26  4612.8  341.87  4617.9  342.67  4626.3   339.9  4664.1  333.62
  4669.2  334.31  4710.5   331.6  4850.6   329.5    4869  321.82  4874.1  326.51
  4881.2   322.4  4891.4  320.95  4952.5   319.9  4970.4   320.6  4991.7  319.45
  5006.9  314.98  5010.2  315.48    5013  319.02  5021.9  320.95  5065.2  322.07
  5071.1   324.4  5080.5  322.94  5086.5  319.48  5092.4  321.96    5105  323.16
  5110.5  325.98  5120.6  328.42  5150.9  330.75    5339  338.85  5510.9  349.64
#Mann= 6 ,-1 , 0
    4601      .1       0  4710.5     .07       0  4850.6     .05       0
  4970.4     .03       0  5021.9     .05       0  5120.6     .12       0
Bank Sta=4970.4,5021.9
XS Rating Curve= 0 ,0
Exp/Cntr=0.3,0.1

Chan Stop Cuts=-1
Use User Specified Reach Order=0
Composite Channel Slope=5