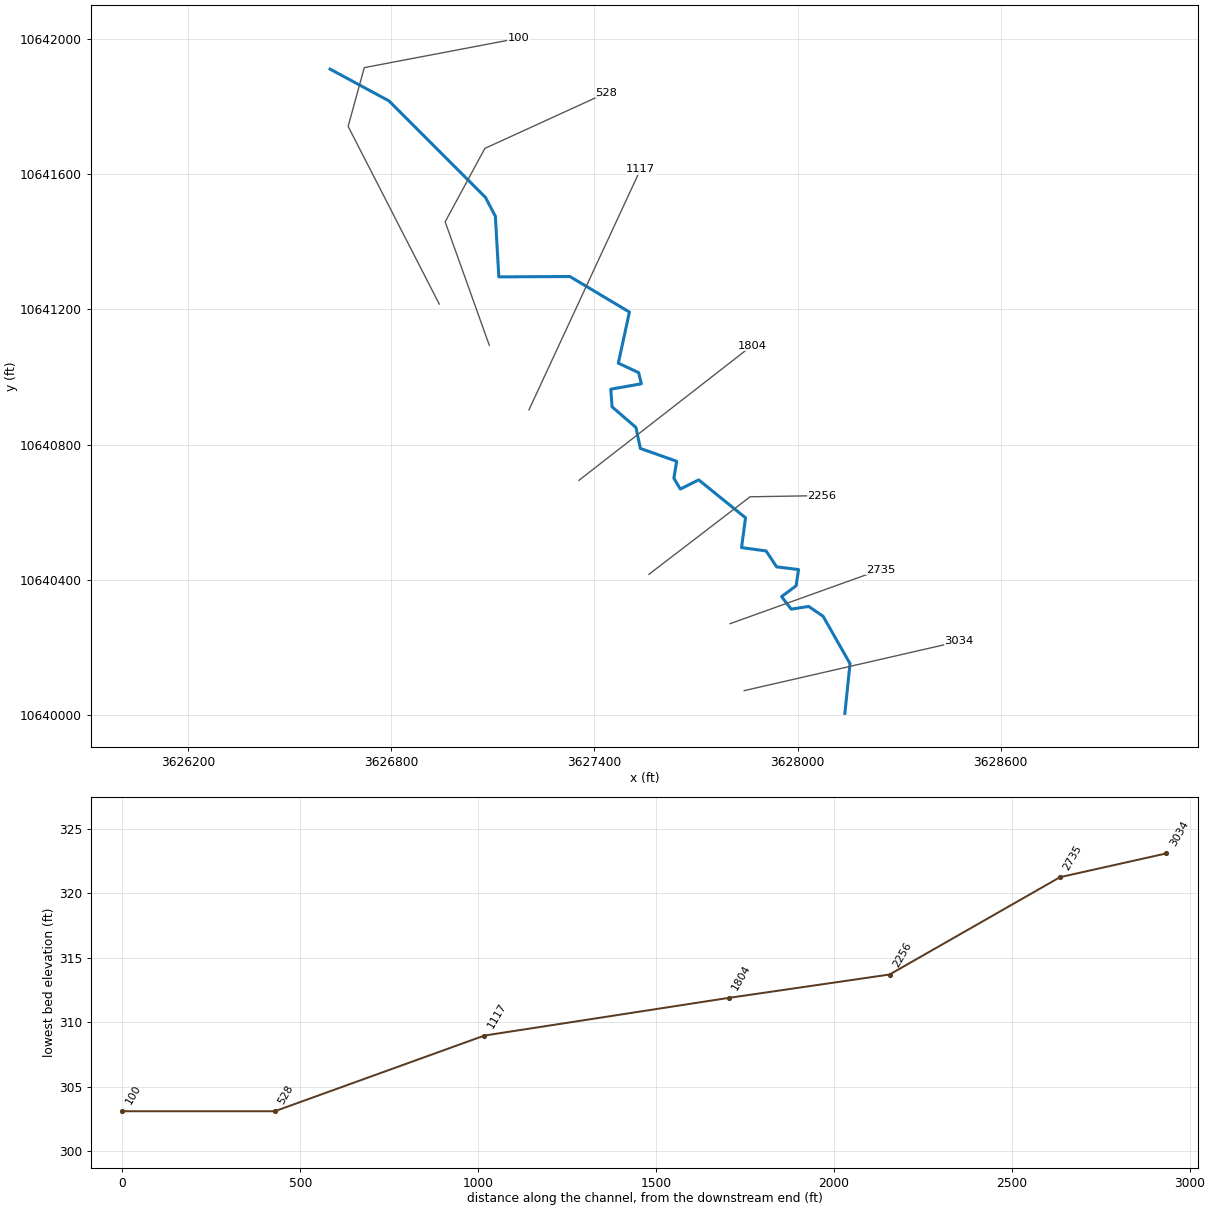
--- UNT257 IN CCTC.prj (project) ---

Proj Title=UNT257 IN CCTC Base Level Engineering
Current Plan=p01
Default Exp/Contr=0.3,0.1
English Units
Geom File=g01
Flow File=f01
Plan File=p01
BEGIN DESCRIPTION:
UNT257 IN CCTC
END DESCRIPTION:

--- UNT257 IN CCTC.p01 (plan) ---

Plan Title=Multiple Run
Short Identifier=Multiple
Geom File=g01
Flow File=f01
Subcritical Flow
K Sum by GR= 0
Std Step Tol= 0.01
Critical Tol= 0.01
Num of Std Step Trials= 20
Max Error Tol= 0.3
Flow Tol Ratio= 0.001
Split Flow NTrial= 30
Split Flow Tol= 0.02
Split Flow Ratio= 0.02
Log Output Level= 0
Friction Slope Method= 1
Unsteady Friction Slope Method= 2
Unsteady Bridges Friction Slope Method= 1
Parabolic Critical Depth
Global Vel Dist=  1 , 1 , 1
Global Log Level= 0
CheckData=True
Encroach Param= -1, 0, 0, 0
BEGIN DESCRIPTION:
Multiple Run
END DESCRIPTION:

--- UNT257 IN CCTC.f01 (steady flow) ---

Flow Title=Multiple
Number of Profiles=7
Profile Names=10-year,25-year,50-year,1pct_min,100-year,1pct_plu,500-year
River Rch & RM= UNT257 IN CCTC,Reach-1,3034
     615     810     966     844    1141    1544    1584
Boundary for River Rch & Prof#=UNT257 IN CCTC,Reach-1,1
Up Type=0
Dn Type=3
Dn Slope=0.005
Boundary for River Rch & Prof#=UNT257 IN CCTC,Reach-1,2
Up Type=0
Dn Type=3
Dn Slope=0.005
Boundary for River Rch & Prof#=UNT257 IN CCTC,Reach-1,3
Up Type=0
Dn Type=3
Dn Slope=0.005
Boundary for River Rch & Prof#=UNT257 IN CCTC,Reach-1,4
Up Type=0
Dn Type=3
Dn Slope=0.005
Boundary for River Rch & Prof#=UNT257 IN CCTC,Reach-1,5
Up Type=0
Dn Type=3
Dn Slope=0.005
Boundary for River Rch & Prof#=UNT257 IN CCTC,Reach-1,6
Up Type=0
Dn Type=3
Dn Slope=0.005
Boundary for River Rch & Prof#=UNT257 IN CCTC,Reach-1,7
Up Type=0
Dn Type=3
Dn Slope=0.005

--- UNT257 IN CCTC.g01 (geometry) ---

Geom Title=Existing Conditions

River Reach=UNT257 IN CCTC,Reach-1
Reach XY= 30
      3628139.75     10640006.00      3628155.00     10640153.00
      3628075.50     10640293.00      3628033.00     10640322.00
      3627981.25     10640314.00      3627953.00     10640351.00
      3627995.75     10640383.00      3628003.00     10640431.00
      3627938.25     10640439.00      3627907.25     10640486.00
      3627834.75     10640496.00      3627846.50     10640584.00
      3627708.25     10640696.00      3627654.00     10640669.00
      3627635.00     10640701.00      3627643.25     10640751.00
      3627536.00     10640789.00      3627523.00     10640851.00
      3627452.50     10640912.00      3627448.75     10640964.00
      3627539.00     10640980.00      3627531.00     10641013.00
      3627471.00     10641041.00      3627503.75     10641192.00
      3627328.00     10641297.00      3627118.25     10641296.00
      3627108.00     10641475.00      3627078.75     10641531.00
      3626794.00     10641816.00      3626620.00     10641910.00

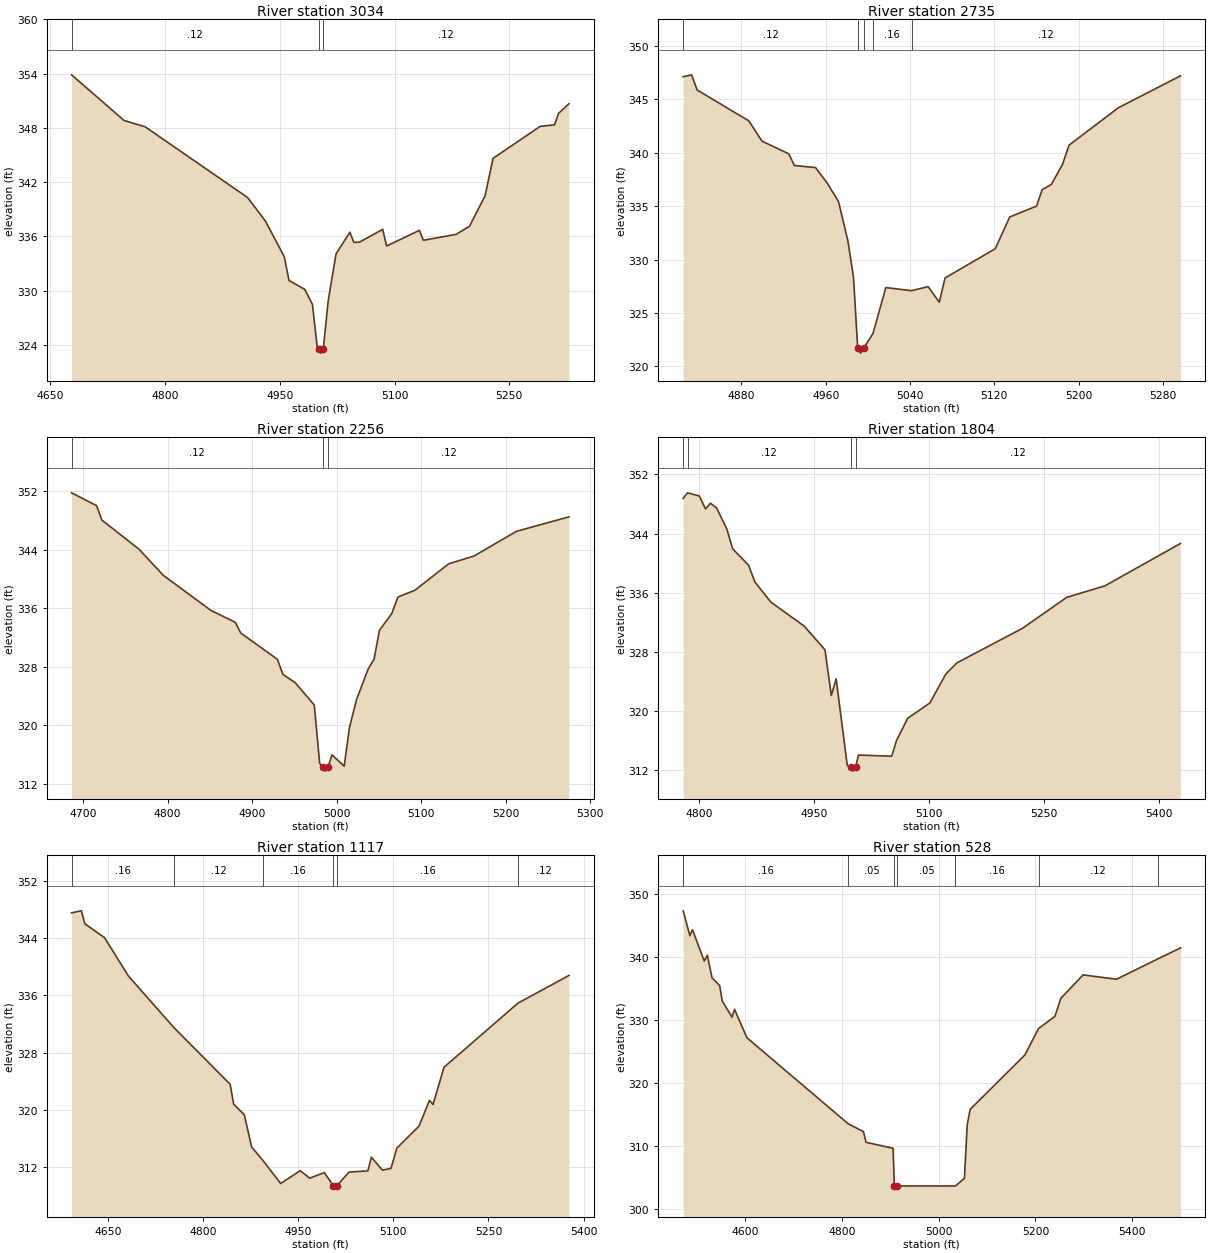
Type RM Length L Ch R = 1,3034,299,299,299
BEGIN DESCRIPTION:
UNT257 IN CCTC 5.0
END DESCRIPTION:
XS GIS Cut Line= 2
      3627842.65     10640073.19      3628476.27     10640218.61
#Sta/Elev= 30
  4677.8  353.86  4746.5  348.81  4774.1  348.11  4907.9  340.29  4931.2  337.69
  4955.9  333.73  4962.0  331.12  4982.5  330.14  4992.7  328.47  4998.8  323.80
  5000.9  323.58  5003.6  323.08  5006.9  323.58  5013.3  328.89  5023.5  334.05
  5041.6  336.45  5046.8  335.32  5054.3  335.36  5084.5  336.77  5089.6  334.93
  5132.5  336.66  5137.6  335.56  5180.5  336.22  5197.9  337.11  5218.3  340.48
  5228.7  344.62  5290.3  348.16  5309.1  348.33  5314.3  349.59  5327.9  350.66
#Mann=3,-1,0
  4677.8    0.12       0  5000.9    0.07       0  5006.9    0.12       0
Bank Sta=5000.9,5006.9
Exp/Cntr=0.3,0.1

Type RM Length L Ch R = 1,2735,479,479,479
BEGIN DESCRIPTION:
Mapping XS d4a38e23
END DESCRIPTION:
XS GIS Cut Line= 2
      3627800.94     10640271.10      3628245.03     10640430.69
#Sta/Elev= 30
  4824.8  347.13  4832.8  347.31  4838.1  345.89  4887.1  343.00  4899.6  341.10
  4925.0  339.91  4930.3  338.82  4950.4  338.62  4961.5  337.17  4972.2  335.44
  4981.1  331.76  4986.4  328.38  4990.4  321.74  4993.2  321.24  4996.4  321.74
  5004.9  323.08  5017.1  327.38  5041.5  327.09  5057.2  327.47  5067.8  326.01
  5073.3  328.28  5120.9  331.02  5134.7  334.00  5160.1  335.01  5165.4  336.55
  5174.1  337.04  5184.7  338.91  5190.9  340.72  5237.8  344.23  5296.7  347.22
#Mann=5,-1,0
  4824.8    0.12       0  4990.4    0.07       0  4996.4    0.12       0
  5004.9    0.16       0  5041.5    0.12       0
Bank Sta=4990.4,4996.4
Exp/Cntr=0.3,0.1

Type RM Length L Ch R = 1,2256,452,452,452
BEGIN DESCRIPTION:
Mapping XS f392b7ad
END DESCRIPTION:
XS GIS Cut Line= 3
      3627561.37     10640416.94      3627859.96     10640646.10
      3628071.74     10640649.57
#Sta/Elev= 30
  4686.5  351.80  4716.1  350.05  4722.4  348.07  4766.0  344.11  4795.0  340.51
  4851.2  335.71  4880.2  334.07  4886.5  332.62  4930.0  329.00  4936.4  326.95
  4950.9  325.82  4973.6  322.74  4979.9  314.78  4983.8  314.20  4986.6  313.70
  4989.8  314.20  4994.4  315.93  5008.9  314.39  5015.2  319.69  5023.4  323.45
  5037.2  327.66  5044.3  329.04  5050.6  332.97  5065.2  335.27  5072.5  337.54
  5092.5  338.46  5132.5  342.08  5162.5  343.15  5212.6  346.53  5274.7  348.51
#Mann=3,-1,0
  4686.5    0.12       0  4983.8    0.07       0  4989.8    0.12       0
Bank Sta=4983.8,4989.8
Exp/Cntr=0.3,0.1

Type RM Length L Ch R = 1,1804,687,687,687
BEGIN DESCRIPTION:
UNT257 IN CCTC 4.0
END DESCRIPTION:
XS GIS Cut Line= 2
      3627354.77     10640694.72      3627865.72     10641093.09
#Sta/Elev= 30
  4779.7  348.75  4785.4  349.50  4800.8  349.07  4808.9  347.32  4815.3  348.09
  4823.4  347.44  4836.6  344.61  4844.2  341.93  4865.0  339.70  4873.2  337.44
  4894.0  334.73  4937.4  331.49  4964.5  328.28  4972.7  322.11  4979.0  324.36
  4993.5  312.66  4998.4  312.39  5001.2  311.89  5004.4  312.39  5008.0  314.06
  5051.4  313.91  5057.7  316.04  5072.2  319.03  5101.1  321.10  5121.9  325.02
  5136.4  326.53  5221.4  331.17  5279.3  335.37  5329.1  336.93  5427.6  342.66
#Mann=4,-1,0
  4779.7    0.16       0  4785.4    0.12       0  4998.4    0.07       0
  5004.4    0.12       0
Bank Sta=4998.4,5004.4
Exp/Cntr=0.3,0.1

Type RM Length L Ch R = 1,1117,589,589,589
BEGIN DESCRIPTION:
UNT257 IN CCTC 3.0
END DESCRIPTION:
XS GIS Cut Line= 2
      3627207.19     10640903.05      3627537.04     10641614.84
#Sta/Elev= 30
  4592.5  347.53  4608.0  347.81  4613.5  346.00  4644.5  344.07  4682.3  338.70
  4753.8  331.53  4842.7  323.60  4848.2  320.83  4864.9  319.36  4876.6  314.85
  4894.4  312.97  4922.4  309.75  4953.1  311.55  4968.2  310.50  4991.2  311.28
  5005.2  309.47  5007.9  308.97  5011.2  309.47  5030.2  311.35  5059.9  311.52
  5065.4  313.43  5082.8  311.62  5096.3  311.86  5105.7  314.71  5140.4  317.75
  5157.1  321.36  5162.6  320.78  5180.0  325.98  5296.7  334.93  5377.0  338.79
#Mann=6,-1,0
  4592.5    0.16       0  4753.8    0.12       0  4894.4    0.16       0
  5005.2    0.07       0  5011.2    0.16       0  5296.7    0.12       0
Bank Sta=5005.2,5011.2
Exp/Cntr=0.3,0.1

Type RM Length L Ch R = 1,528,428,428,428
BEGIN DESCRIPTION:
UNT257 IN CCTC 2.0
END DESCRIPTION:
XS GIS Cut Line= 4
      3627090.00     10641094.01      3626959.79     10641458.60
      3627076.98     10641675.61      3627435.87     10641839.92
#Sta/Elev= 30
  4471.6  347.28  4485.6  343.33  4490.9  344.28  4515.3  339.30  4521.7  340.25
  4531.3  336.64  4547.1  335.42  4552.5  332.97  4572.6  330.41  4577.9  331.65
  4603.4  327.14  4813.1  313.47  4844.5  312.24  4849.8  310.54  4905.7  309.59
  4908.3  303.61  4911.1  303.11  4914.3  303.61  5034.6  303.61  5053.2  304.82
  5058.9  313.27  5065.1  315.77  5178.1  324.39  5206.5  328.60  5240.3  330.53
  5252.6  333.39  5298.6  337.11  5367.7  336.42  5452.7  339.63  5500.1  341.40
#Mann=7,-1,0
  4471.6    0.16       0  4813.1    0.05       0  4908.3   0.033       0
  4914.3    0.05       0  5034.6    0.16       0  5206.5    0.12       0
  5452.7    0.16       0
Bank Sta=4908.3,4914.3
Exp/Cntr=0.3,0.1

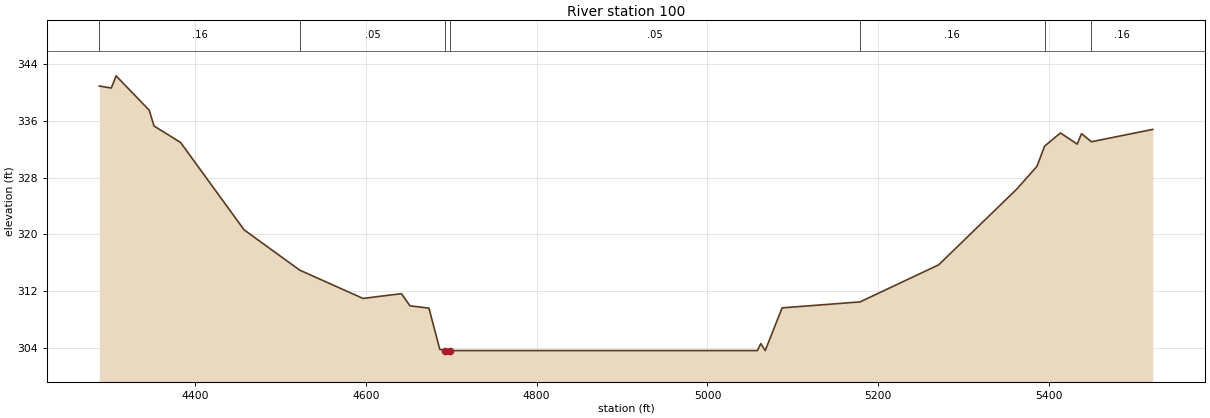
Type RM Length L Ch R = 1,100,0,0,0
BEGIN DESCRIPTION:
UNT257 IN CCTC 1.0
END DESCRIPTION:
XS GIS Cut Line= 4
      3626942.43     10641215.53      3626673.33     10641740.71
      3626721.07     10641914.33      3627175.74     10642000.93
#Sta/Elev= 30
  4288.2  340.89  4302.2  340.61  4307.8  342.33  4346.6  337.48  4352.2  335.26
  4383.3  332.94  4457.6  320.63  4522.7  314.95  4596.8  310.96  4641.8  311.63
  4651.8  309.92  4674.0  309.59  4686.7  303.78  4693.2  303.61  4695.9  303.11
  4699.2  303.61  5058.4  303.61  5062.5  304.59  5067.6  303.61  5087.4  309.63
  5178.6  310.47  5270.6  315.69  5362.3  326.40  5385.7  329.58  5394.6  332.42
  5413.2  334.28  5432.8  332.71  5437.8  334.18  5449.4  333.04  5521.2  334.78
#Mann=7,-1,0
  4288.2    0.16       0  4522.7    0.05       0  4693.2   0.033       0
  4699.2    0.05       0  5178.6    0.16       0  5394.6    0.12       0
  5449.4    0.16       0
Bank Sta=4693.2,4699.2
Exp/Cntr=0.3,0.1

Chan Stop Cuts=-1