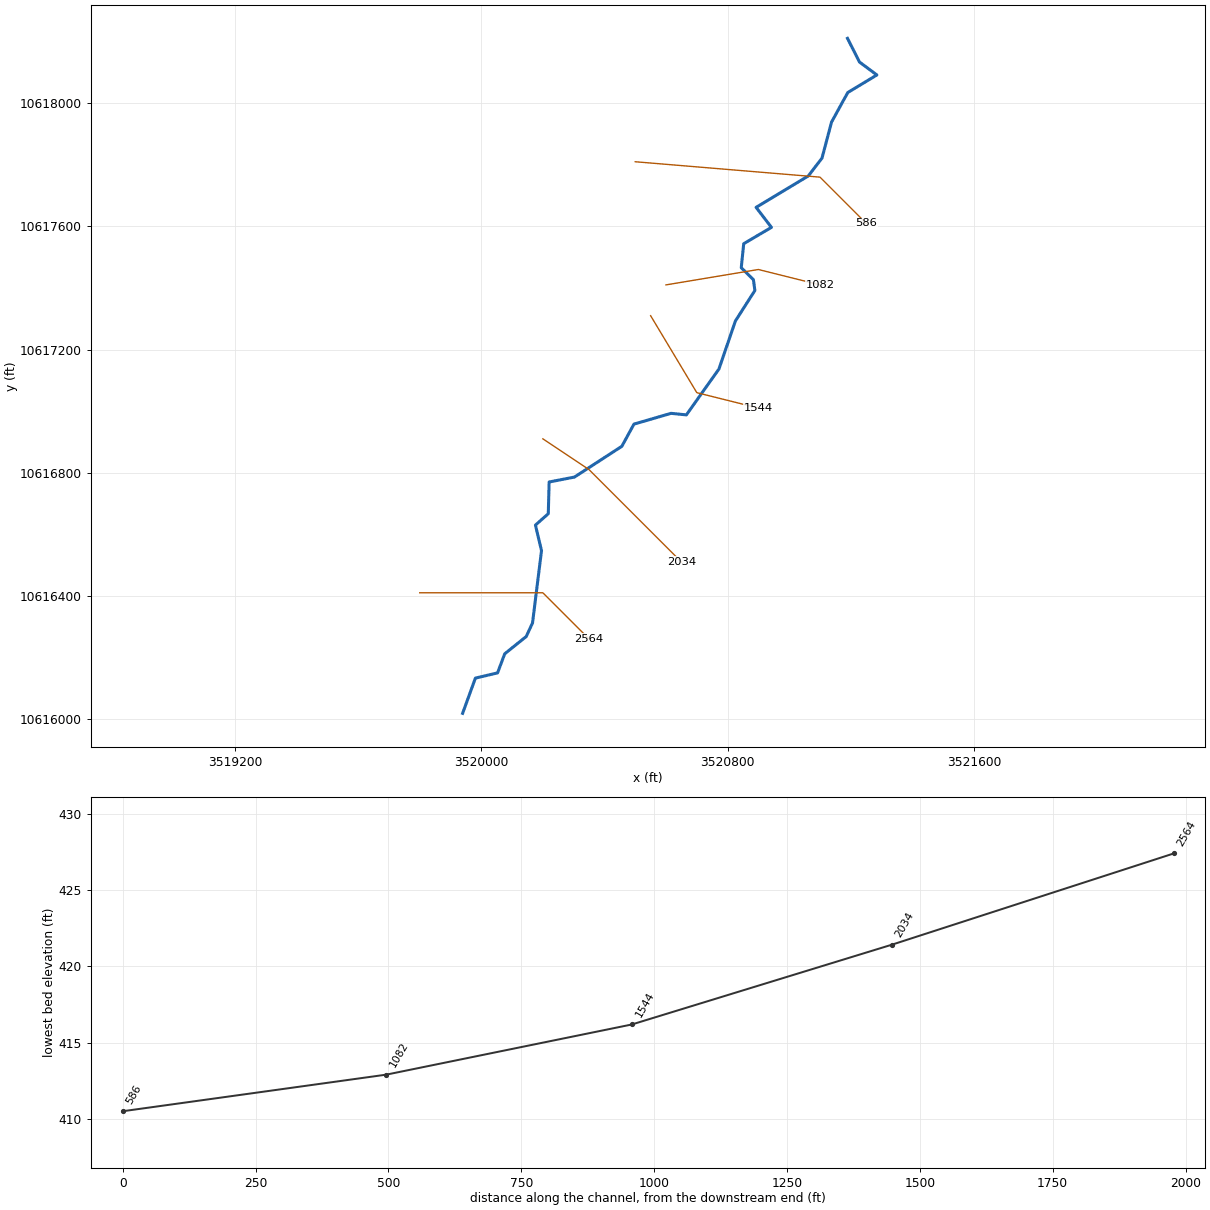
--- UNT260 IN CCTC.prj (project) ---

Proj Title=UNT260 IN CCTC Base Level Engineering
Current Plan=p01
Default Exp/Contr=0.3,0.1
English Units
Geom File=g01
Flow File=f01
Plan File=p01
BEGIN DESCRIPTION:
UNT260 IN CCTC
END DESCRIPTION:

--- UNT260 IN CCTC.p01 (plan) ---

Plan Title=Multiple Run
Short Identifier=Multiple
Geom File=g01
Flow File=f01
Subcritical Flow
K Sum by GR= 0
Std Step Tol= 0.01
Critical Tol= 0.01
Num of Std Step Trials= 20
Max Error Tol= 0.3
Flow Tol Ratio= 0.001
Split Flow NTrial= 30
Split Flow Tol= 0.02
Split Flow Ratio= 0.02
Log Output Level= 0
Friction Slope Method= 1
Unsteady Friction Slope Method= 2
Unsteady Bridges Friction Slope Method= 1
Parabolic Critical Depth
Global Vel Dist=  1 , 1 , 1
Global Log Level= 0
CheckData=True
Encroach Param= -1, 0, 0, 0
BEGIN DESCRIPTION:
Multiple Run
END DESCRIPTION:

--- UNT260 IN CCTC.f01 (steady flow) ---

Flow Title=Multiple
Number of Profiles=7
Profile Names=10-year,25-year,50-year,1pct_min,100-year,1pct_plu,500-year
River Rch & RM= UNT260 IN CCTC,Reach-1,2564
     621     821     980     857    1159    1568    1615
Boundary for River Rch & Prof#=UNT260 IN CCTC,Reach-1,1
Up Type=0
Dn Type=3
Dn Slope=0.005
Boundary for River Rch & Prof#=UNT260 IN CCTC,Reach-1,2
Up Type=0
Dn Type=3
Dn Slope=0.005
Boundary for River Rch & Prof#=UNT260 IN CCTC,Reach-1,3
Up Type=0
Dn Type=3
Dn Slope=0.005
Boundary for River Rch & Prof#=UNT260 IN CCTC,Reach-1,4
Up Type=0
Dn Type=3
Dn Slope=0.005
Boundary for River Rch & Prof#=UNT260 IN CCTC,Reach-1,5
Up Type=0
Dn Type=3
Dn Slope=0.005
Boundary for River Rch & Prof#=UNT260 IN CCTC,Reach-1,6
Up Type=0
Dn Type=3
Dn Slope=0.005
Boundary for River Rch & Prof#=UNT260 IN CCTC,Reach-1,7
Up Type=0
Dn Type=3
Dn Slope=0.005

--- UNT260 IN CCTC.g01 (geometry) ---

Geom Title=Existing Conditions

River Reach=UNT260 IN CCTC,Reach-1
Reach XY= 30
      3519938.95     10616018.49      3519980.50     10616133.00
      3520052.50     10616150.00      3520075.75     10616212.00
      3520145.50     10616268.00      3520166.00     10616312.00
      3520195.25     10616547.00      3520175.50     10616630.00
      3520217.25     10616667.00      3520220.00     10616770.00
      3520302.25     10616786.00      3520456.25     10616886.00
      3520495.50     10616958.00      3520616.00     10616993.00
      3520665.75     10616988.00      3520771.50     10617137.00
      3520825.00     10617293.00      3520888.25     10617392.00
      3520883.50     10617427.00      3520844.00     10617466.00
      3520852.00     10617544.00      3520942.00     10617597.00
      3520892.25     10617662.00      3521061.75     10617764.00
      3521106.25     10617822.00      3521137.25     10617939.00
      3521190.00     10618035.00      3521284.50     10618092.00
      3521228.00     10618134.00      3521189.00     10618211.00

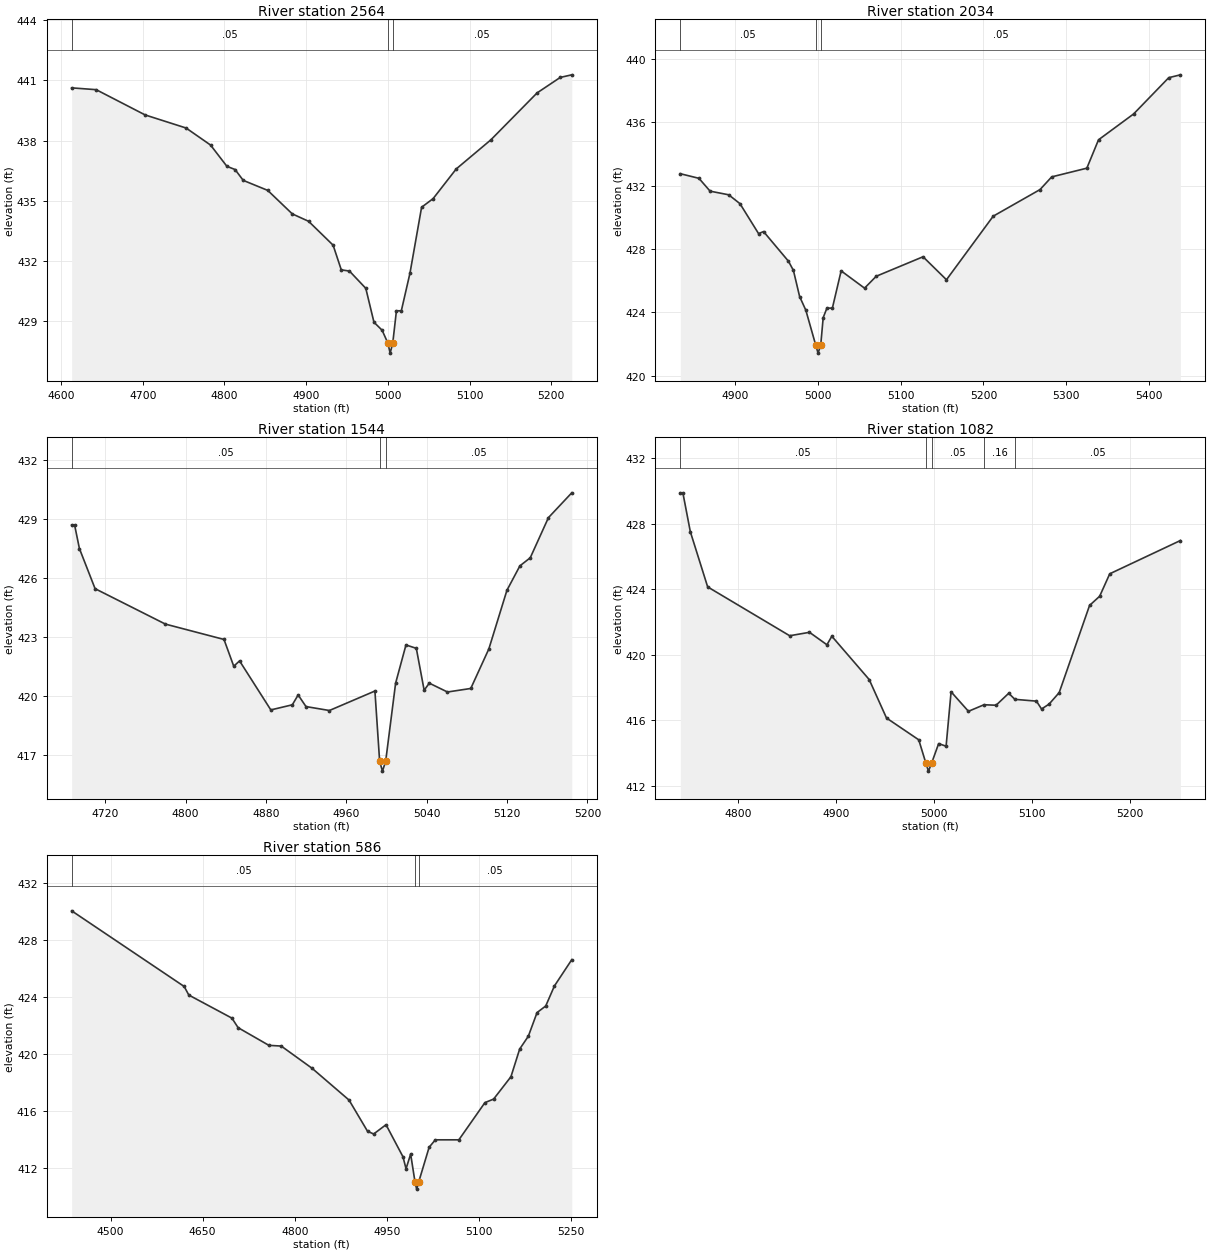
Type RM Length L Ch R = 1,2564,530,530,530
BEGIN DESCRIPTION:
UNT260 IN CCTC 5.0
END DESCRIPTION:
XS GIS Cut Line= 3
      3519799.60     10616410.19      3520199.61     10616410.19
      3520349.58     10616260.22
#Sta/Elev= 30
  4613.0  440.63  4643.0  440.54  4703.0  439.28  4753.0  438.63  4783.0  437.78
  4803.0  436.72  4813.0  436.56  4823.0  436.02  4853.0  435.52  4883.0  434.35
  4903.0  433.98  4933.0  432.79  4943.0  431.56  4953.0  431.50  4973.0  430.64
  4983.0  428.95  4993.0  428.55  5000.0  427.91  5002.8  427.41  5006.0  427.91
  5010.5  429.52  5016.5  429.52  5027.1  431.40  5041.3  434.68  5055.4  435.11
  5083.7  436.59  5126.1  438.04  5182.7  440.38  5211.0  441.15  5225.1  441.28
#Mann=3,-1,0
  4613.0    0.05       0  5000.0    0.03       0  5006.0    0.05       0
Bank Sta=5000,5006
Exp/Cntr=0.3,0.1

Type RM Length L Ch R = 1,2034,490,490,490
BEGIN DESCRIPTION:
UNT260 IN CCTC 4.0
END DESCRIPTION:
XS GIS Cut Line= 3
      3520199.64     10616910.17      3520349.61     10616810.19
      3520649.61     10616510.19
#Sta/Elev= 30
  4833.6  432.75  4856.1  432.46  4869.6  431.65  4892.1  431.42  4905.7  430.86
  4928.2  428.97  4934.2  429.10  4964.3  427.23  4970.3  426.65  4977.8  425.00
  4985.3  424.14  4997.3  421.93  5000.1  421.43  5003.3  421.93  5006.3  423.67
  5010.8  424.27  5017.4  424.27  5028.0  426.62  5056.3  425.53  5070.4  426.28
  5127.0  427.51  5155.3  426.06  5211.8  430.07  5268.4  431.75  5282.5  432.55
  5325.0  433.10  5339.1  434.89  5381.5  436.52  5424.0  438.81  5438.1  438.99
#Mann=3,-1,0
  4833.6    0.05       0  4997.3    0.03       0  5003.3    0.05       0
Bank Sta=4997.3,5003.3
Exp/Cntr=0.3,0.1

Type RM Length L Ch R = 1,1544,462,462,462
BEGIN DESCRIPTION:
UNT260 IN CCTC 3.0
END DESCRIPTION:
XS GIS Cut Line= 3
      3520549.63     10617310.15      3520699.61     10617060.19
      3520899.65     10617010.18
#Sta/Elev= 30
  4686.7  428.70  4689.6  428.70  4694.4  427.50  4710.0  425.46  4780.0  423.66
  4838.3  422.88  4848.0  421.52  4853.8  421.79  4884.9  419.30  4906.3  419.56
  4912.1  420.06  4919.9  419.47  4943.2  419.27  4988.5  420.26  4993.2  416.69
  4996.0  416.19  4999.2  416.69  5009.1  420.66  5019.4  422.60  5029.7  422.43
  5037.5  420.30  5042.6  420.66  5060.7  420.21  5083.9  420.39  5101.9  422.40
  5119.9  425.38  5132.8  426.62  5143.1  427.03  5161.2  429.07  5184.4  430.33
#Mann=3,-1,0
  4686.7    0.05       0  4993.2    0.03       0  4999.2    0.05       0
Bank Sta=4993.2,4999.2
Exp/Cntr=0.3,0.1

Type RM Length L Ch R = 1,1082,496,496,496
BEGIN DESCRIPTION:
UNT260 IN CCTC 2.0
END DESCRIPTION:
XS GIS Cut Line= 3
      3520599.58     10617410.18      3520899.61     10617460.19
      3521099.58     10617410.20
#Sta/Elev= 30
  4741.0  429.88  4743.6  429.88  4751.2  427.51  4768.9  424.14  4852.6  421.16
  4872.8  421.37  4890.6  420.61  4895.6  421.13  4933.7  418.49  4951.4  416.14
  4984.3  414.81  4991.5  413.40  4994.2  412.90  4997.5  413.40  5004.6  414.58
  5012.2  414.42  5017.3  417.74  5035.0  416.55  5050.9  416.95  5063.2  416.92
  5076.1  417.65  5082.4  417.28  5104.4  417.17  5109.6  416.69  5117.3  416.99
  5127.6  417.69  5158.6  423.01  5168.9  423.57  5179.2  424.94  5251.3  426.97
#Mann=5,-1,0
  4741.0    0.05       0  4991.5    0.03       0  4997.5    0.05       0
  5050.9    0.16       0  5082.4    0.05       0
Bank Sta=4991.5,4997.5
Exp/Cntr=0.3,0.1

Type RM Length L Ch R = 1,586,0,0,0
BEGIN DESCRIPTION:
UNT260 IN CCTC 1.0
END DESCRIPTION:
XS GIS Cut Line= 3
      3520499.59     10617810.19      3521099.61     10617760.19
      3521249.58     10617610.21
#Sta/Elev= 30
  4436.7  430.03  4619.9  424.72  4627.4  424.12  4697.6  422.50  4707.7  421.83
  4757.8  420.59  4777.9  420.54  4828.1  418.98  4888.3  416.75  4918.4  414.56
  4928.4  414.37  4948.5  415.02  4976.1  412.77  4981.1  411.93  4988.6  412.96
  4995.7  411.00  4998.4  410.50  5001.7  411.00  5018.7  413.44  5028.8  413.96
  5067.1  413.96  5109.5  416.57  5123.7  416.82  5151.9  418.39  5166.1  420.33
  5180.2  421.23  5194.4  422.89  5208.5  423.35  5222.7  424.76  5250.9  426.60
#Mann=3,-1,0
  4436.7    0.05       0  4995.7    0.03       0  5001.7    0.05       0
Bank Sta=4995.7,5001.7
Exp/Cntr=0.3,0.1

Chan Stop Cuts=-1