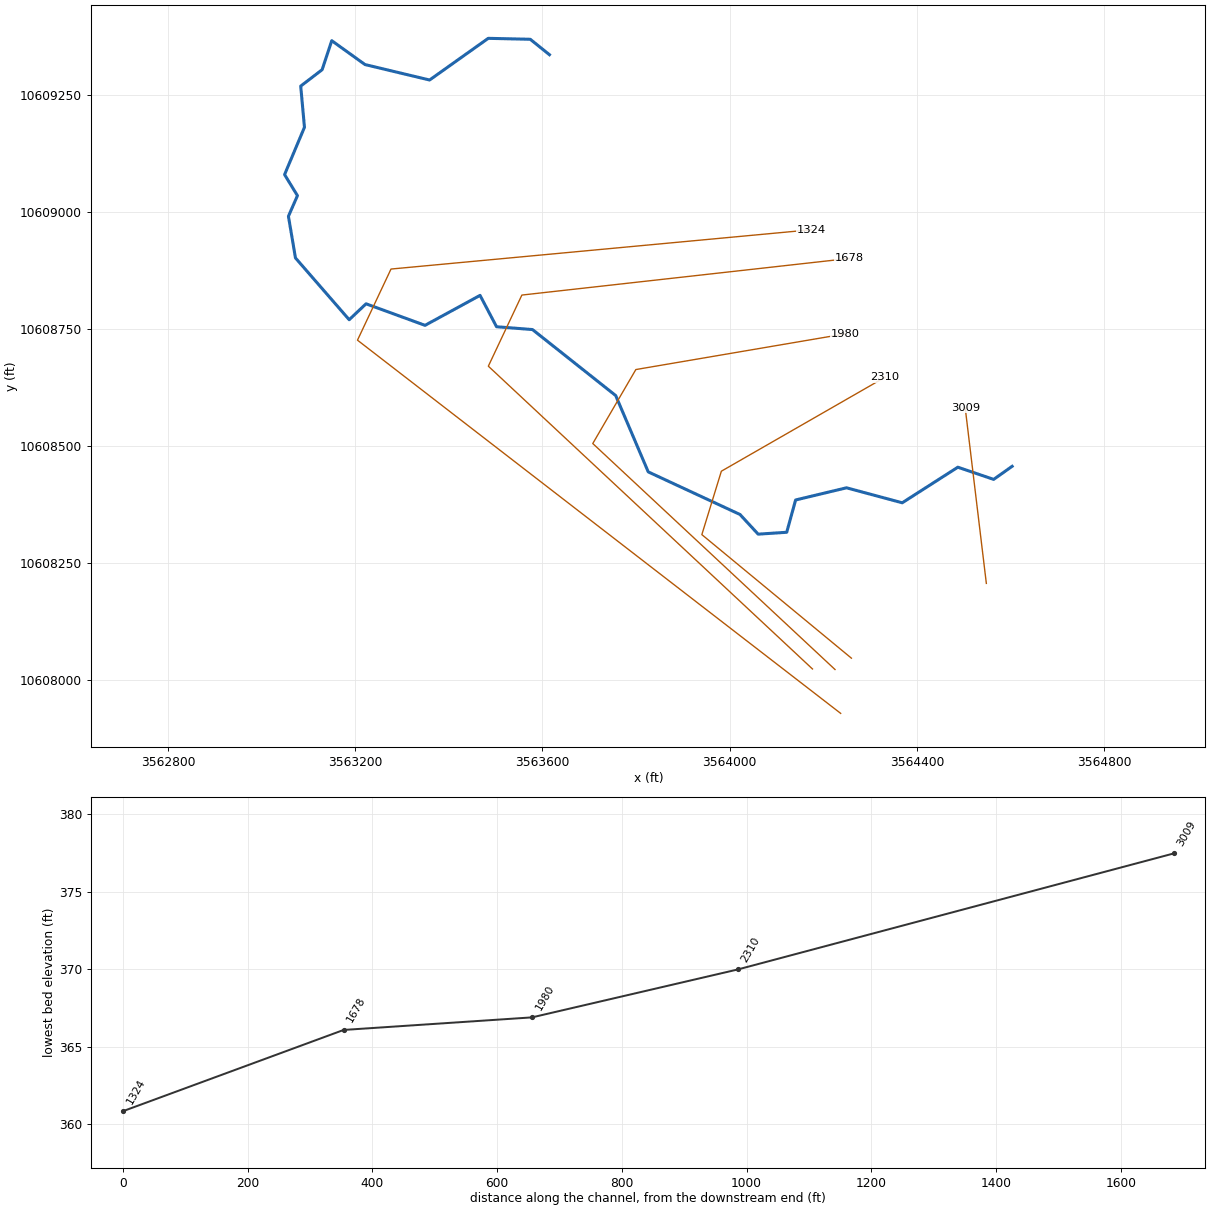
--- UNT261 IN CCTC.prj (project) ---

Proj Title=UNT261 IN CCTC Base Level Engineering
Current Plan=p02
Default Exp/Contr=0.3,0.1
English Units
Geom File=g01
Flow File=f01
Plan File=p01
Plan File=p02
Y Axis Title=Elevation
X Axis Title(PF)=Main Channel Distance
X Axis Title(XS)=Station
BEGIN DESCRIPTION:
UNT261 IN CCTC
END DESCRIPTION:
DSS Export Rating Curves= 0
DSS Export Rating Curve Sorted= 0
DSS Export Volume Flow Curves= 0
DXF OffsetX= 0
DXF OffsetY= 0
DXF ScaleX= 1
DXF ScaleY= 10

--- UNT261 IN CCTC.p01 (plan) ---

Plan Title=Multiple Run
Short Identifier=Multiple
Geom File=g01
Flow File=f01
Subcritical Flow
K Sum by GR= 0
Std Step Tol= 0.01
Critical Tol= 0.01
Num of Std Step Trials= 20
Max Error Tol= 0.3
Flow Tol Ratio= 0.001
Split Flow NTrial= 30
Split Flow Tol= 0.02
Split Flow Ratio= 0.02
Log Output Level= 0
Friction Slope Method= 1
Unsteady Friction Slope Method= 2
Unsteady Bridges Friction Slope Method= 1
Parabolic Critical Depth
Global Vel Dist=  1 , 1 , 1
Global Log Level= 0
CheckData=True
Encroach Param= -1, 0, 0, 0
BEGIN DESCRIPTION:
Multiple Run
END DESCRIPTION:

--- UNT261 IN CCTC.f01 (steady flow) ---

Flow Title=Multiple
Program Version=4.10
Number of Profiles= 7
Profile Names=10-year,25-year,50-year,1pct_min,100-year,1pct_plu,500-year
River Rch & RM=UNT261 IN CCTC,Reach-1         ,3009
     401     508     590     503     680     920     898
Boundary for River Rch & Prof#=UNT261 IN CCTC,Reach-1         , 1
Up Type= 0
Dn Type= 3
Dn Slope=0.00125
Boundary for River Rch & Prof#=UNT261 IN CCTC,Reach-1         , 2
Up Type= 0
Dn Type= 3
Dn Slope=0.00125
Boundary for River Rch & Prof#=UNT261 IN CCTC,Reach-1         , 3
Up Type= 0
Dn Type= 3
Dn Slope=0.00125
Boundary for River Rch & Prof#=UNT261 IN CCTC,Reach-1         , 4
Up Type= 0
Dn Type= 3
Dn Slope=0.00125
Boundary for River Rch & Prof#=UNT261 IN CCTC,Reach-1         , 5
Up Type= 0
Dn Type= 3
Dn Slope=0.00125
Boundary for River Rch & Prof#=UNT261 IN CCTC,Reach-1         , 6
Up Type= 0
Dn Type= 3
Dn Slope=0.00125
Boundary for River Rch & Prof#=UNT261 IN CCTC,Reach-1         , 7
Up Type= 0
Dn Type= 3
Dn Slope=0.00125
DSS Import GetInterval= 0
DSS Import GetPeak= 0
DSS Import FillOption= 0

--- UNT261 IN CCTC.g01 (geometry) ---

Geom Title=Existing Conditions
Program Version=4.10

River Reach=UNT261 IN CCTC  ,Reach-1
Reach XY= 30
      3564603.21     10608455.87      3564563.75       10608428.
      3564487.25       10608454.       3564368.5       10608378.
       3564249.5       10608410.      3564140.75       10608384.
      3564121.75       10608315.      3564060.75       10608311.
        3564022.       10608353.        3563826.       10608444.
       3563756.5       10608607.      3563578.75       10608748.
        3563502.       10608754.      3563466.75       10608821.
      3563349.25       10608757.      3563223.25       10608803.
      3563187.25       10608769.       3563072.5       10608901.
       3563057.5       10608990.      3563076.75       10609034.
      3563049.25       10609079.      3563091.75       10609180.
      3563083.75       10609268.       3563129.5       10609303.
        3563150.       10609365.        3563221.       10609314.
        3563359.       10609281.      3563484.25       10609370.
        3563574.       10609368.        3563615.       10609335.

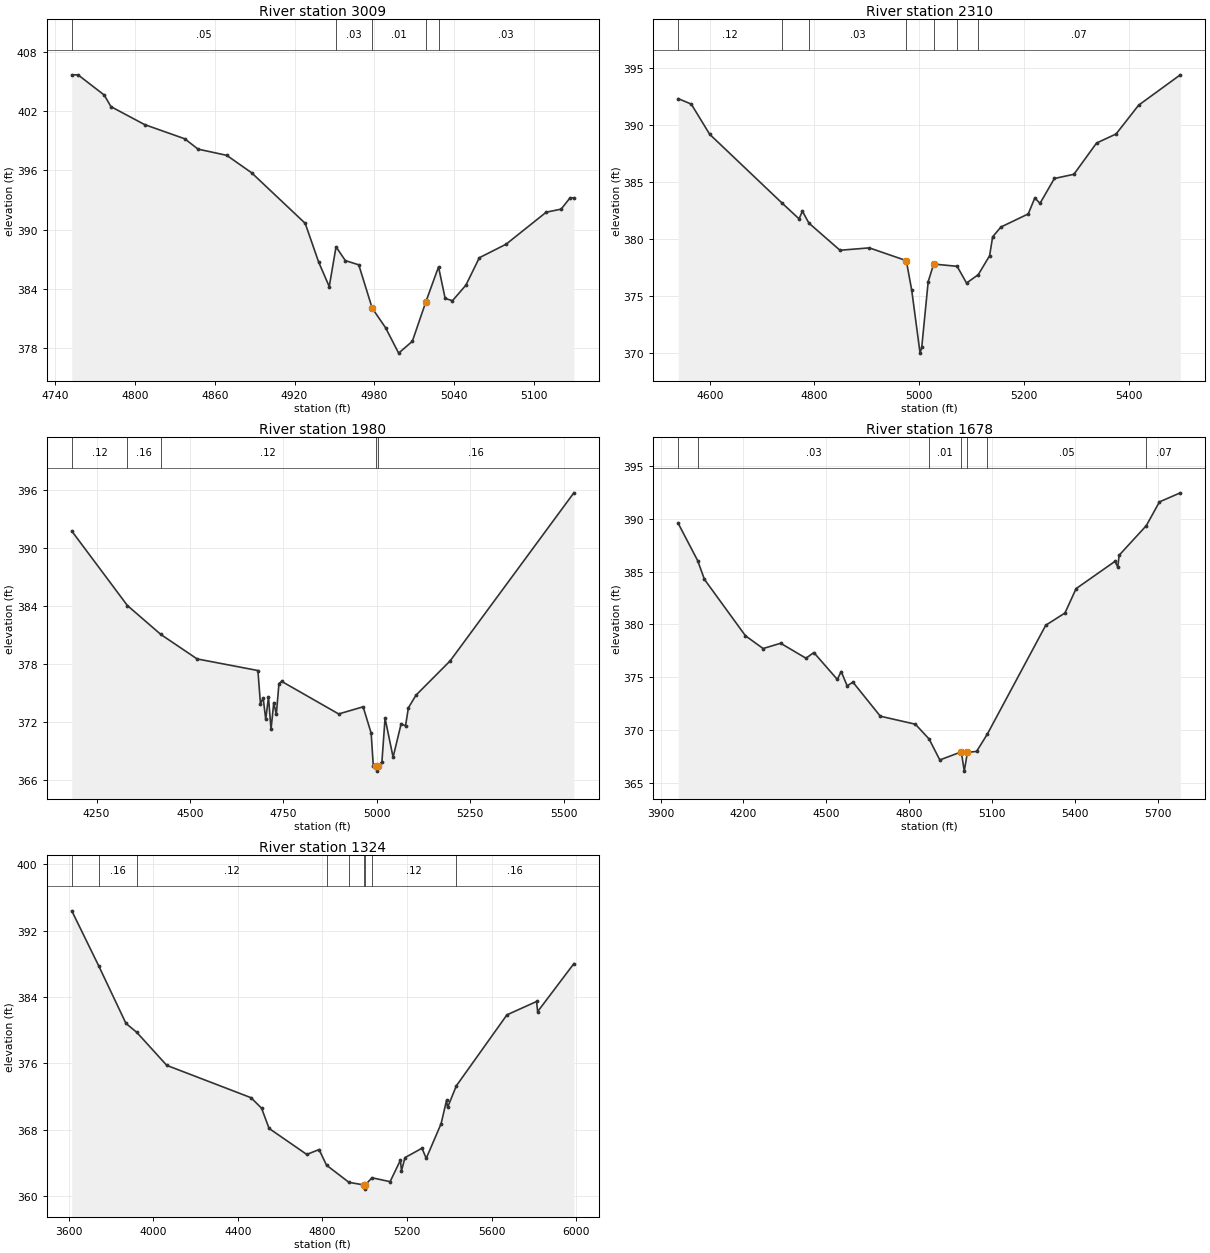
Type RM Length L Ch R = 1 ,3009    ,699,699,699
BEGIN DESCRIPTION:
UNT261 IN CCTC 1.0
END DESCRIPTION:
XS GIS Cut Line= 2
      3564548.12     10608205.82      3564502.98     10608580.81
#Sta/Elev= 30
  4752.4   405.7  4757.1   405.7  4776.8  403.65  4781.9  402.47  4807.2  400.65
  4837.4  399.21  4847.4  398.16    4869  397.53  4887.7  395.76    4928  390.63
  4938.1  386.71  4946.1  384.21  4951.2  388.25  4958.2  386.85  4968.3  386.42
  4978.4  382.02  4988.5  380.03  4998.3  377.46  5008.6  378.66  5018.7  382.64
  5028.3  386.21  5033.3  383.01  5038.8  382.78  5048.9  384.36    5059  387.14
  5079.1  388.51  5109.3  391.76  5120.5  392.07  5127.3  393.22  5130.1  393.22
#Mann= 5 ,-1 , 0
  4752.4     .05       0  4951.2     .03       0  4978.4     .01       0
  5018.7     .03       0  5028.3     .03       0
Bank Sta=4978.4,5018.7
XS Rating Curve= 0 ,0
Exp/Cntr=0.3,0.1

Type RM Length L Ch R = 1 ,2310    ,330,330,330
BEGIN DESCRIPTION:
UNT261 IN CCTC 3.0
END DESCRIPTION:
XS GIS Cut Line= 4
      3564259.93     10608046.12      3563940.48     10608310.02
      3563982.14     10608445.43      3564331.41       10608646.
#Sta/Elev= 30
  4539.8  392.32  4564.7  391.84  4599.9  389.19  4737.4  383.18  4770.5  381.77
    4777  382.44  4789.2   381.4  4848.7  379.01  4904.7  379.22  4975.3   378.1
  4985.7   375.5  5001.6  369.98  5004.8  370.48  5017.1  376.25  5027.6   377.8
  5072.4   377.6  5090.4  376.13  5112.8  376.87  5134.4  378.53  5140.2  380.19
    5156  381.05  5208.2   382.2  5220.7   383.6  5230.7  383.13  5258.1  385.31
  5295.4  385.68  5338.6  388.42    5376  389.22  5419.1  391.75  5498.6  394.41
#Mann= 7 ,-1 , 0
  4539.8     .12       0  4737.4     .05       0  4789.2     .03       0
  4975.3     .01       0  5027.6     .01       0  5072.4     .03       0
  5112.8     .07       0
Bank Sta=4975.3,5027.6
XS Rating Curve= 0 ,0
Exp/Cntr=0.3,0.1

Type RM Length L Ch R = 1 ,1980    ,302,302,302
BEGIN DESCRIPTION:
Mapping XS eed9d4e9
END DESCRIPTION:
XS GIS Cut Line= 4
      3564224.89     10608021.92      3563707.51     10608504.58
      3563799.52     10608662.57      3564245.98     10608738.71
#Sta/Elev= 30
  4183.6  391.71  4332.4  384.01  4421.9  381.02  4518.9  378.49  4681.6  377.29
  4688.4  373.87  4695.7  374.44  4702.6  372.24  4709.9  374.56  4716.7   371.2
  4724.1  373.98  4730.9  372.75  4737.9  375.94  4745.1  376.17  4897.7   372.8
  4963.1  373.54  4984.6  370.82  4990.4  367.39    4997  367.39  4999.8  366.89
    5003  367.39  5013.4  367.85  5021.8  372.36  5043.3  368.33  5064.8  371.78
  5076.6  371.57  5084.2  373.43  5104.5  374.74  5195.8  378.28  5526.9  395.66
#Mann= 5 ,-1 , 0
  4183.6     .12       0  4332.4     .16       0  4421.9     .12       0
    4997     .07       0    5003     .16       0
Bank Sta=4997,5003
XS Rating Curve= 0 ,0
Exp/Cntr=0.3,0.1

Type RM Length L Ch R = 1 ,1678    ,354,354,354
BEGIN DESCRIPTION:
UNT261 IN CCTC 2.0
END DESCRIPTION:
XS GIS Cut Line= 4
      3564176.77     10608023.06      3563484.48     10608669.77
       3563556.1     10608821.68      3564254.73     10608899.79
#Sta/Elev= 30
  3963.9  389.58  4034.4  386.04  4058.8  384.27  4207.3  378.92  4271.3  377.71
  4334.8  378.21  4426.6  376.79    4455  377.33    4540  374.78  4554.1  375.53
  4575.6  374.17  4596.6  374.52  4695.8  371.29  4822.8  370.53  4872.6  369.12
  4911.2  367.14  4989.1  367.91  4999.8  366.08  5011.2  367.86  5044.4  367.95
  5083.5   369.6  5294.9  379.92  5364.5  381.08  5404.7  383.39  5545.6  385.98
  5555.7  385.44  5560.7  386.56  5659.1  389.37  5706.6  391.62  5782.2  392.48
#Mann= 7 ,-1 , 0
  3963.9     .07       0  4034.4     .03       0  4872.6     .01       0
  4989.1     .01       0  5011.2     .03       0  5083.5     .05       0
  5659.1     .07       0
Bank Sta=4989.1,5011.2
XS Rating Curve= 0 ,0
Exp/Cntr=0.3,0.1

Type RM Length L Ch R = 1 ,1324    ,0,0,0
BEGIN DESCRIPTION:
UNT261 IN CCTC 4.0
END DESCRIPTION:
XS GIS Cut Line= 4
      3564236.98     10607928.22      3563204.97     10608725.33
      3563276.58     10608877.24      3564174.52     10608961.18
#Sta/Elev= 30
  3615.3  394.39    3742  387.79  3871.5  380.82  3922.7  379.74  4064.5  375.76
    4463  371.86  4512.8  370.59  4548.1  368.16  4726.5  365.02  4784.5  365.61
  4819.7  363.73  4925.7  361.66    4997  361.34  4999.8  360.84    5003  361.34
  5034.5  362.21  5120.4  361.74  5169.1  364.33  5174.2  363.05  5190.7  364.64
  5271.1  365.77  5291.2  364.55  5361.5  368.73  5387.1  371.53  5392.1  370.69
  5433.7   373.3  5672.8  381.85  5812.9  383.46  5817.9  382.24  5989.1  388.02
#Mann= 9 ,-1 , 0
  3615.3     .12       0    3742     .16       0  3922.7     .12       0
  4819.7     .07       0  4925.7     .05       0    4997    .035       0
    5003     .05       0  5034.5     .12       0  5433.7     .16       0
Bank Sta=4997,5003
XS Rating Curve= 0 ,0
Exp/Cntr=0.3,0.1

Chan Stop Cuts=-1
Use User Specified Reach Order=0
Composite Channel Slope=5