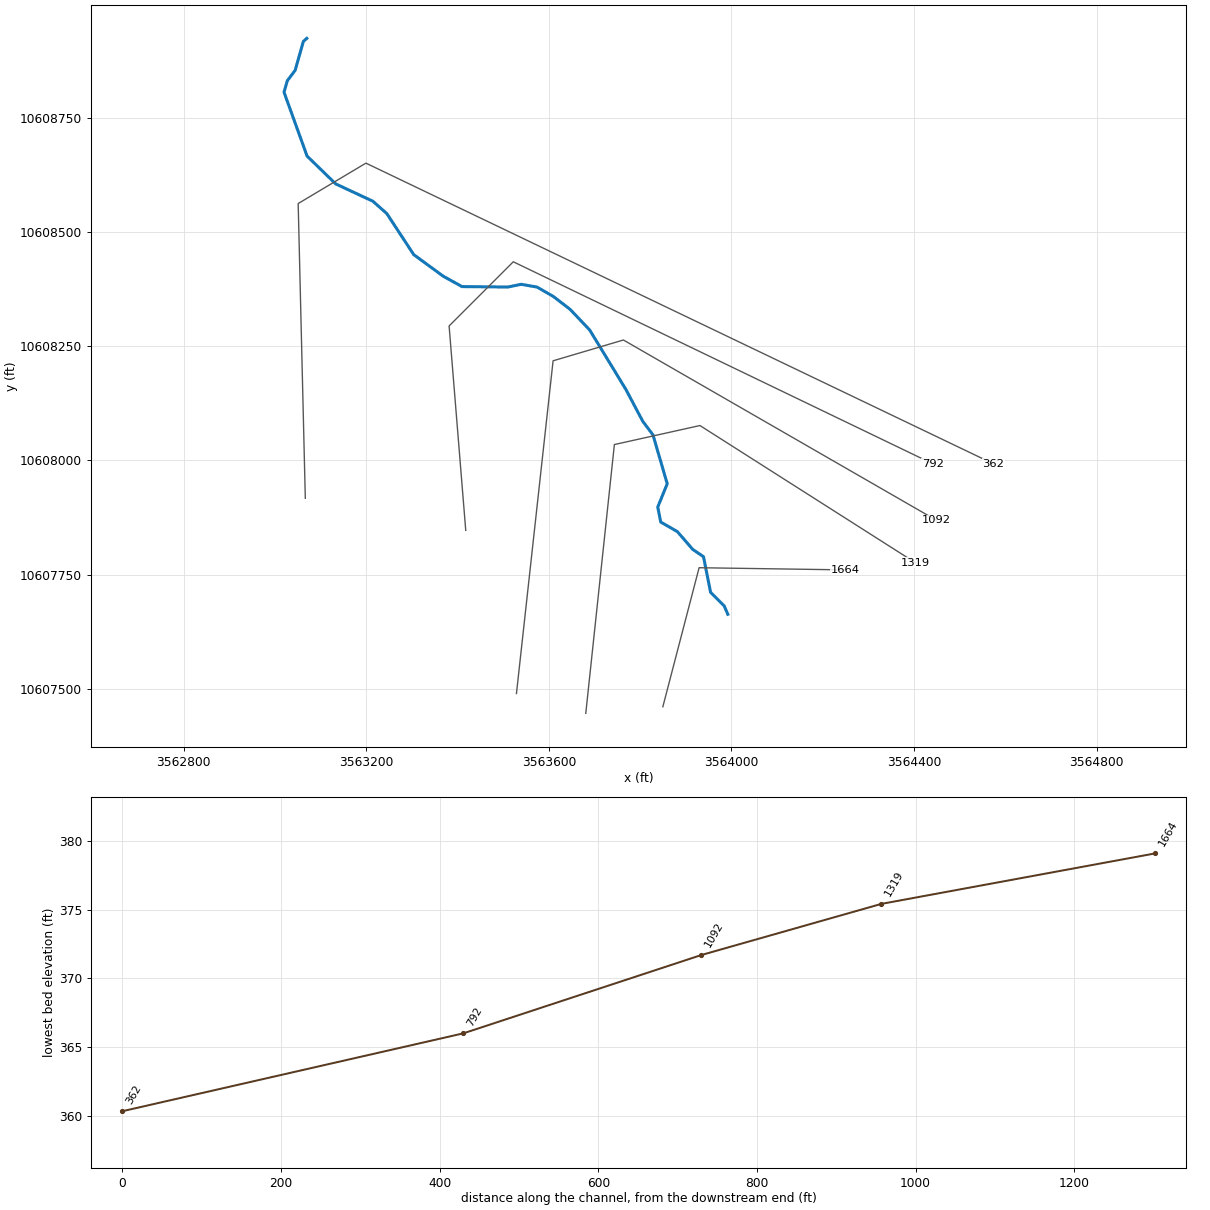
--- UNT262 IN CCTC.prj (project) ---

Proj Title=UNT262 IN CCTC Base Level Engineering
Current Plan=p01
Default Exp/Contr=0.3,0.1
English Units
Geom File=g01
Flow File=f01
Plan File=p01
BEGIN DESCRIPTION:
UNT262 IN CCTC
END DESCRIPTION:

--- UNT262 IN CCTC.p01 (plan) ---

Plan Title=Multiple Run
Short Identifier=Multiple
Geom File=g01
Flow File=f01
Subcritical Flow
K Sum by GR= 0
Std Step Tol= 0.01
Critical Tol= 0.01
Num of Std Step Trials= 20
Max Error Tol= 0.3
Flow Tol Ratio= 0.001
Split Flow NTrial= 30
Split Flow Tol= 0.02
Split Flow Ratio= 0.02
Log Output Level= 0
Friction Slope Method= 1
Unsteady Friction Slope Method= 2
Unsteady Bridges Friction Slope Method= 1
Parabolic Critical Depth
Global Vel Dist=  1 , 1 , 1
Global Log Level= 0
CheckData=True
Encroach Param= -1, 0, 0, 0
BEGIN DESCRIPTION:
Multiple Run
END DESCRIPTION:

--- UNT262 IN CCTC.f01 (steady flow) ---

Flow Title=Multiple
Number of Profiles=7
Profile Names=10-year,25-year,50-year,1pct_min,100-year,1pct_plu,500-year
River Rch & RM= UNT262 IN CCTC,Reach-1,1664
     411     525     614     528     714     966     957
Boundary for River Rch & Prof#=UNT262 IN CCTC,Reach-1,1
Up Type=0
Dn Type=3
Dn Slope=0.005
Boundary for River Rch & Prof#=UNT262 IN CCTC,Reach-1,2
Up Type=0
Dn Type=3
Dn Slope=0.005
Boundary for River Rch & Prof#=UNT262 IN CCTC,Reach-1,3
Up Type=0
Dn Type=3
Dn Slope=0.005
Boundary for River Rch & Prof#=UNT262 IN CCTC,Reach-1,4
Up Type=0
Dn Type=3
Dn Slope=0.005
Boundary for River Rch & Prof#=UNT262 IN CCTC,Reach-1,5
Up Type=0
Dn Type=3
Dn Slope=0.005
Boundary for River Rch & Prof#=UNT262 IN CCTC,Reach-1,6
Up Type=0
Dn Type=3
Dn Slope=0.005
Boundary for River Rch & Prof#=UNT262 IN CCTC,Reach-1,7
Up Type=0
Dn Type=3
Dn Slope=0.005

--- UNT262 IN CCTC.g01 (geometry) ---

Geom Title=Existing Conditions

River Reach=UNT262 IN CCTC,Reach-1
Reach XY= 30
      3563992.00     10607663.00      3563984.25     10607681.00
      3563954.25     10607711.00      3563938.75     10607789.00
      3563915.25     10607805.00      3563881.50     10607844.00
      3563845.00     10607865.00      3563838.50     10607898.00
      3563859.25     10607949.00      3563828.00     10608056.00
      3563805.50     10608086.00      3563769.00     10608155.00
      3563689.25     10608286.00      3563646.50     10608331.00
      3563610.25     10608359.00      3563573.75     10608380.00
      3563539.00     10608386.00      3563510.25     10608380.00
      3563409.50     10608381.00      3563368.00     10608404.00
      3563303.75     10608451.00      3563244.75     10608541.00
      3563214.25     10608568.00      3563132.75     10608606.00
      3563070.00     10608667.00      3563019.50     10608807.00
      3563026.75     10608832.00      3563044.00     10608855.00
      3563061.75     10608918.00      3563069.50     10608925.00

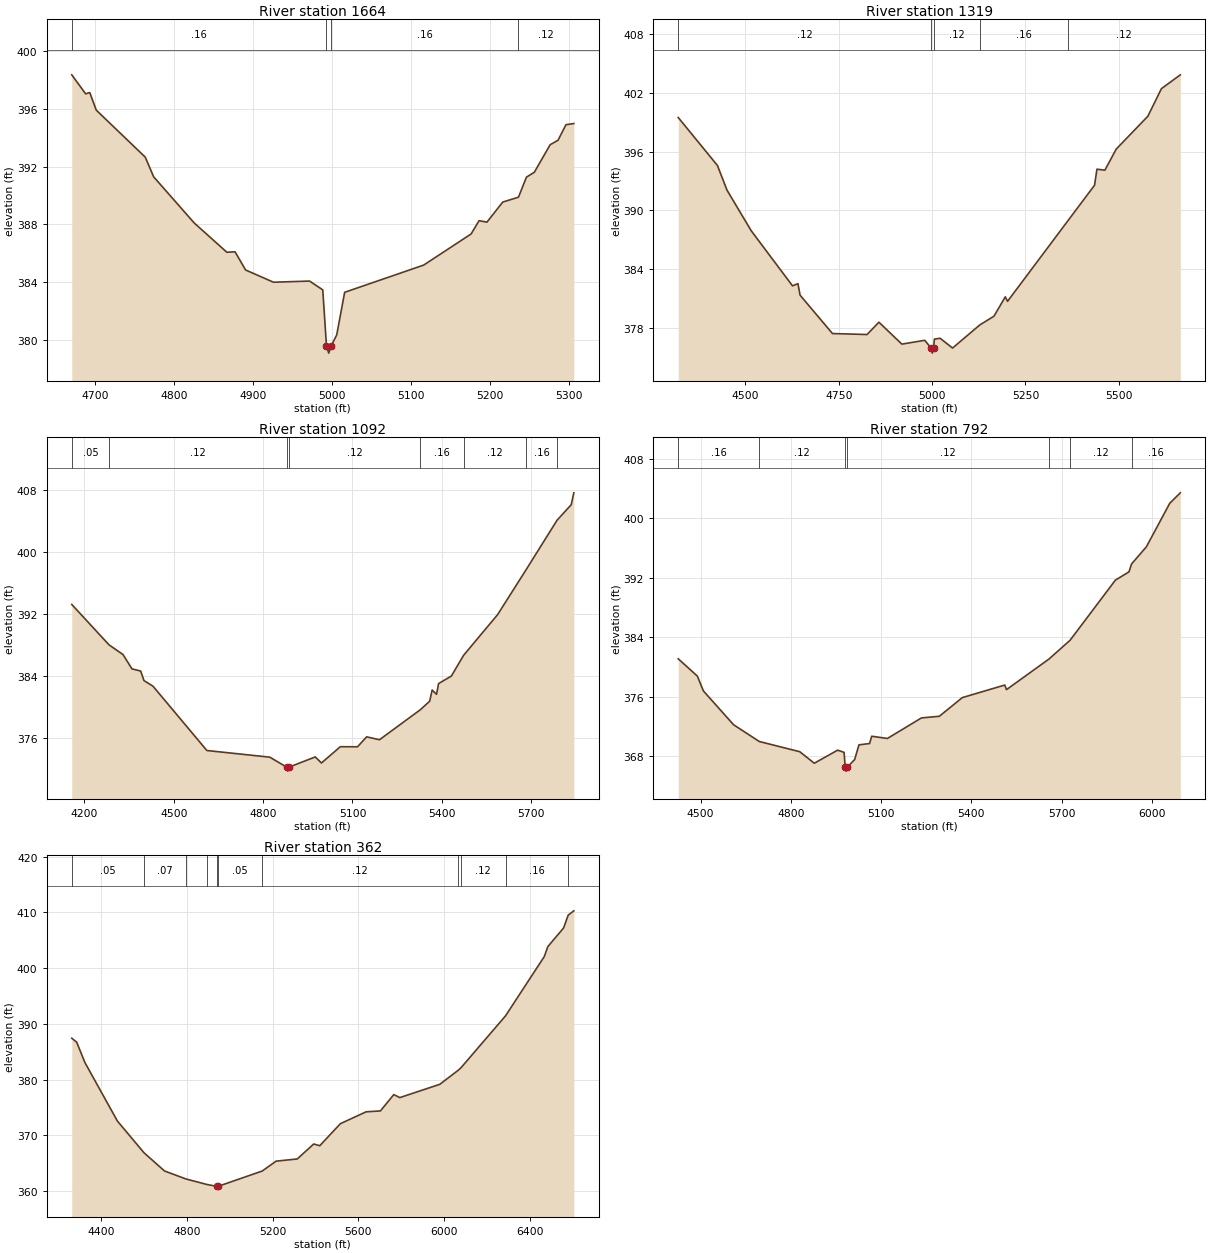
Type RM Length L Ch R = 1,1664,345,345,345
BEGIN DESCRIPTION:
UNT262 IN CCTC 2.0
END DESCRIPTION:
XS GIS Cut Line= 3
      3563849.62     10607460.22      3563929.09     10607764.95
      3564249.64     10607760.19
#Sta/Elev= 30
  4670.6  398.38  4688.2  397.06  4693.4  397.15  4701.6  395.93  4763.6  392.67
  4774.3  391.30  4825.6  388.10  4866.9  386.07  4877.3  386.10  4890.6  384.84
  4925.9  383.99  4971.6  384.07  4988.3  383.46  4993.0  379.57  4995.8  379.07
  4999.0  379.57  5006.0  380.34  5016.0  383.29  5116.1  385.18  5176.1  387.34
  5186.1  388.26  5196.1  388.16  5216.1  389.55  5236.0  389.89  5246.1  391.28
  5256.1  391.62  5276.1  393.53  5286.1  393.84  5296.1  394.92  5306.1  395.00
#Mann=4,-1,0
  4670.6    0.16       0  4993.0    0.07       0  4999.0    0.16       0
  5236.0    0.12       0
Bank Sta=4993,4999
Exp/Cntr=0.3,0.1

Type RM Length L Ch R = 1,1319,227,227,227
BEGIN DESCRIPTION:
Mapping XS 9dc0669c
END DESCRIPTION:
XS GIS Cut Line= 4
      3563680.74     10607445.77      3563743.43     10608034.84
      3563930.93     10608076.51      3564403.41     10607775.67
#Sta/Elev= 30
  4320.3  399.48  4425.3  394.58  4450.9  392.06  4515.8  387.91  4626.4  382.28
  4640.9  382.51  4646.6  381.33  4733.4  377.41  4826.0  377.31  4857.7  378.57
  4919.2  376.33  4980.5  376.72  4998.0  375.91  5000.7  375.41  5004.0  375.91
  5006.3  376.84  5021.5  376.93  5055.0  375.93  5127.9  378.29  5165.8  379.18
  5196.2  381.16  5202.2  380.70  5362.8  388.88  5435.2  392.56  5441.7  394.20
  5462.9  394.10  5493.4  396.26  5578.0  399.61  5614.4  402.43  5664.9  403.84
#Mann=5,-1,0
  4320.3    0.12       0  4998.0    0.07       0  5004.0    0.12       0
  5127.9    0.16       0  5362.8    0.12       0
Bank Sta=4998,5004
Exp/Cntr=0.3,0.1

Type RM Length L Ch R = 1,1092,300,300,300
BEGIN DESCRIPTION:
Mapping XS 609adb7f
END DESCRIPTION:
XS GIS Cut Line= 4
      3563528.84     10607489.27      3563609.13     10608218.38
      3563763.21     10608263.96      3564448.99     10607868.98
#Sta/Elev= 30
  4157.7  393.20  4282.8  387.99  4329.7  386.74  4359.8  384.89  4389.1  384.61
  4400.1  383.38  4430.3  382.66  4611.3  374.36  4822.6  373.50  4880.0  372.20
  4882.7  371.70  4886.0  372.20  4975.2  373.53  4996.0  372.75  5059.3  374.85
  5117.0  374.84  5147.7  376.12  5190.8  375.75  5327.7  379.61  5359.3  380.72
  5367.6  382.16  5382.4  381.61  5389.1  382.99  5432.2  383.97  5473.2  386.64
  5587.4  391.89  5682.7  397.66  5786.9  404.06  5834.5  406.07  5843.3  407.60
#Mann=8,-1,0
  4157.7    0.05       0  4282.8    0.12       0  4880.0    0.07       0
  4886.0    0.12       0  5327.7    0.16       0  5473.2    0.12       0
  5682.7    0.16       0  5786.9    0.12       0
Bank Sta=4880,4886
Exp/Cntr=0.3,0.1

Type RM Length L Ch R = 1,792,430,430,430
BEGIN DESCRIPTION:
Mapping XS 6e361422
END DESCRIPTION:
XS GIS Cut Line= 4
      3563417.72     10607846.83      3563381.26     10608294.75
      3563521.89     10608435.37      3564441.17     10607992.66
#Sta/Elev= 30
  4425.8  381.12  4489.4  378.79  4509.4  376.80  4609.8  372.25  4695.3  370.00
  4829.7  368.63  4877.9  367.08  4955.7  368.84  4976.9  368.54  4980.9  366.52
  4983.7  366.02  4986.9  366.52  5012.2  367.58  5026.4  369.55  5061.7  369.73
  5068.8  370.71  5121.0  370.41  5234.1  373.17  5293.5  373.39  5369.9  375.90
  5511.2  377.59  5516.7  376.97  5658.5  381.10  5728.1  383.61  5878.7  391.69
  5923.9  392.80  5932.2  393.85  5981.7  396.17  6059.4  402.02  6094.4  403.42
#Mann=7,-1,0
  4425.8    0.16       0  4695.3    0.12       0  4980.9    0.07       0
  4986.9    0.12       0  5658.5    0.16       0  5728.1    0.12       0
  5932.2    0.16       0
Bank Sta=4980.9,4986.9
Exp/Cntr=0.3,0.1

Type RM Length L Ch R = 1,362,0,0,0
BEGIN DESCRIPTION:
UNT262 IN CCTC 1.0
END DESCRIPTION:
XS GIS Cut Line= 4
      3563066.16     10607917.13      3563050.53     10608562.98
      3563198.97     10608651.52      3564573.99     10607992.65
#Sta/Elev= 30
  4262.7  387.45  4285.8  386.72  4323.8  383.10  4475.8  372.58  4600.0  366.89
  4695.9  363.62  4796.0  362.19  4894.0  361.20  4939.6  360.87  4942.3  360.37
  4945.6  360.87  5151.8  363.62  5216.4  365.39  5315.1  365.78  5392.1  368.47
  5420.3  368.16  5516.5  372.11  5636.7  374.24  5703.4  374.40  5765.8  377.33
  5794.0  376.79  5980.8  379.18  6064.8  381.64  6079.8  382.16  6287.3  391.45
  6468.4  402.10  6484.9  403.88  6558.4  407.22  6579.9  409.52  6606.3  410.30
#Mann=11,-1,0
  4262.7    0.05       0  4600.0    0.07       0  4796.0    0.12       0
  4894.0    0.05       0  4939.6   0.035       0  4945.6    0.05       0
  5151.8    0.12       0  6064.8    0.16       0  6079.8    0.12       0
  6287.3    0.16       0  6579.9    0.12       0
Bank Sta=4939.6,4945.6
Exp/Cntr=0.3,0.1

Chan Stop Cuts=-1