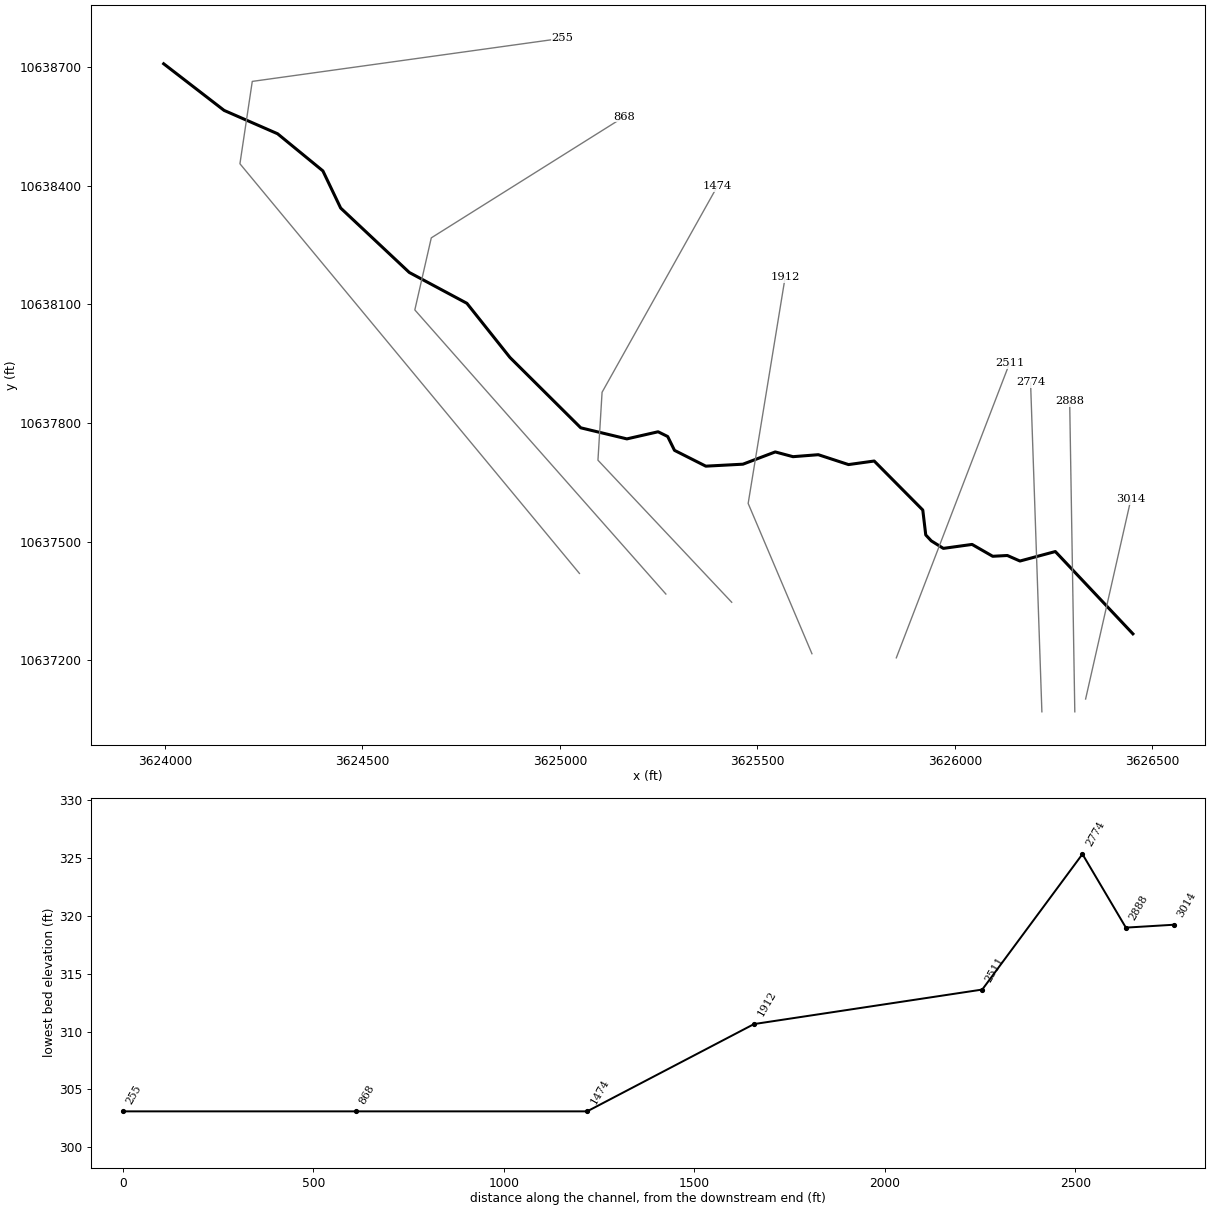
--- UNT266 IN CCTC.prj (project) ---

Proj Title=UNT266 IN CCTC Base Level Engineering
Current Plan=p01
Default Exp/Contr=0.3,0.1
English Units
Geom File=g01
Flow File=f01
Plan File=p01
BEGIN DESCRIPTION:
UNT266 IN CCTC
END DESCRIPTION:

--- UNT266 IN CCTC.p01 (plan) ---

Plan Title=Multiple Run
Short Identifier=Multiple
Geom File=g01
Flow File=f01
Subcritical Flow
K Sum by GR= 0
Std Step Tol= 0.01
Critical Tol= 0.01
Num of Std Step Trials= 20
Max Error Tol= 0.3
Flow Tol Ratio= 0.001
Split Flow NTrial= 30
Split Flow Tol= 0.02
Split Flow Ratio= 0.02
Log Output Level= 0
Friction Slope Method= 1
Unsteady Friction Slope Method= 2
Unsteady Bridges Friction Slope Method= 1
Parabolic Critical Depth
Global Vel Dist=  1 , 1 , 1
Global Log Level= 0
CheckData=True
Encroach Param= -1, 0, 0, 0
BEGIN DESCRIPTION:
Multiple Run
END DESCRIPTION:

--- UNT266 IN CCTC.f01 (steady flow) ---

Flow Title=Multiple
Number of Profiles=7
Profile Names=10-year,25-year,50-year,1pct_min,100-year,1pct_plu,500-year
River Rch & RM= UNT266 IN CCTC,Reach-1,3014
     457     586     685     588     795    1075    1062
Boundary for River Rch & Prof#=UNT266 IN CCTC,Reach-1,1
Up Type=0
Dn Type=3
Dn Slope=0.005
Boundary for River Rch & Prof#=UNT266 IN CCTC,Reach-1,2
Up Type=0
Dn Type=3
Dn Slope=0.005
Boundary for River Rch & Prof#=UNT266 IN CCTC,Reach-1,3
Up Type=0
Dn Type=3
Dn Slope=0.005
Boundary for River Rch & Prof#=UNT266 IN CCTC,Reach-1,4
Up Type=0
Dn Type=3
Dn Slope=0.005
Boundary for River Rch & Prof#=UNT266 IN CCTC,Reach-1,5
Up Type=0
Dn Type=3
Dn Slope=0.005
Boundary for River Rch & Prof#=UNT266 IN CCTC,Reach-1,6
Up Type=0
Dn Type=3
Dn Slope=0.005
Boundary for River Rch & Prof#=UNT266 IN CCTC,Reach-1,7
Up Type=0
Dn Type=3
Dn Slope=0.005

--- UNT266 IN CCTC.g01 (geometry) ---

Geom Title=Existing Conditions

River Reach=UNT266 IN CCTC,Reach-1
Reach XY= 30
      3626450.62     10637266.80      3626254.25     10637475.00
      3626164.75     10637451.00      3626132.75     10637465.00
      3626095.75     10637463.00      3626043.50     10637493.00
      3625970.75     10637483.00      3625940.25     10637502.00
      3625926.25     10637517.00      3625918.75     10637580.00
      3625795.75     10637704.00      3625730.75     10637695.00
      3625654.25     10637720.00      3625590.25     10637715.00
      3625545.25     10637727.00      3625463.50     10637696.00
      3625369.50     10637691.00      3625290.25     10637731.00
      3625273.00     10637766.00      3625248.75     10637778.00
      3625169.75     10637760.00      3625053.00     10637788.00
      3624873.75     10637966.00      3624764.75     10638103.00
      3624619.00     10638181.00      3624445.25     10638344.00
      3624400.25     10638438.00      3624285.50     10638532.00
      3624150.25     10638591.00      3623997.25     10638709.00

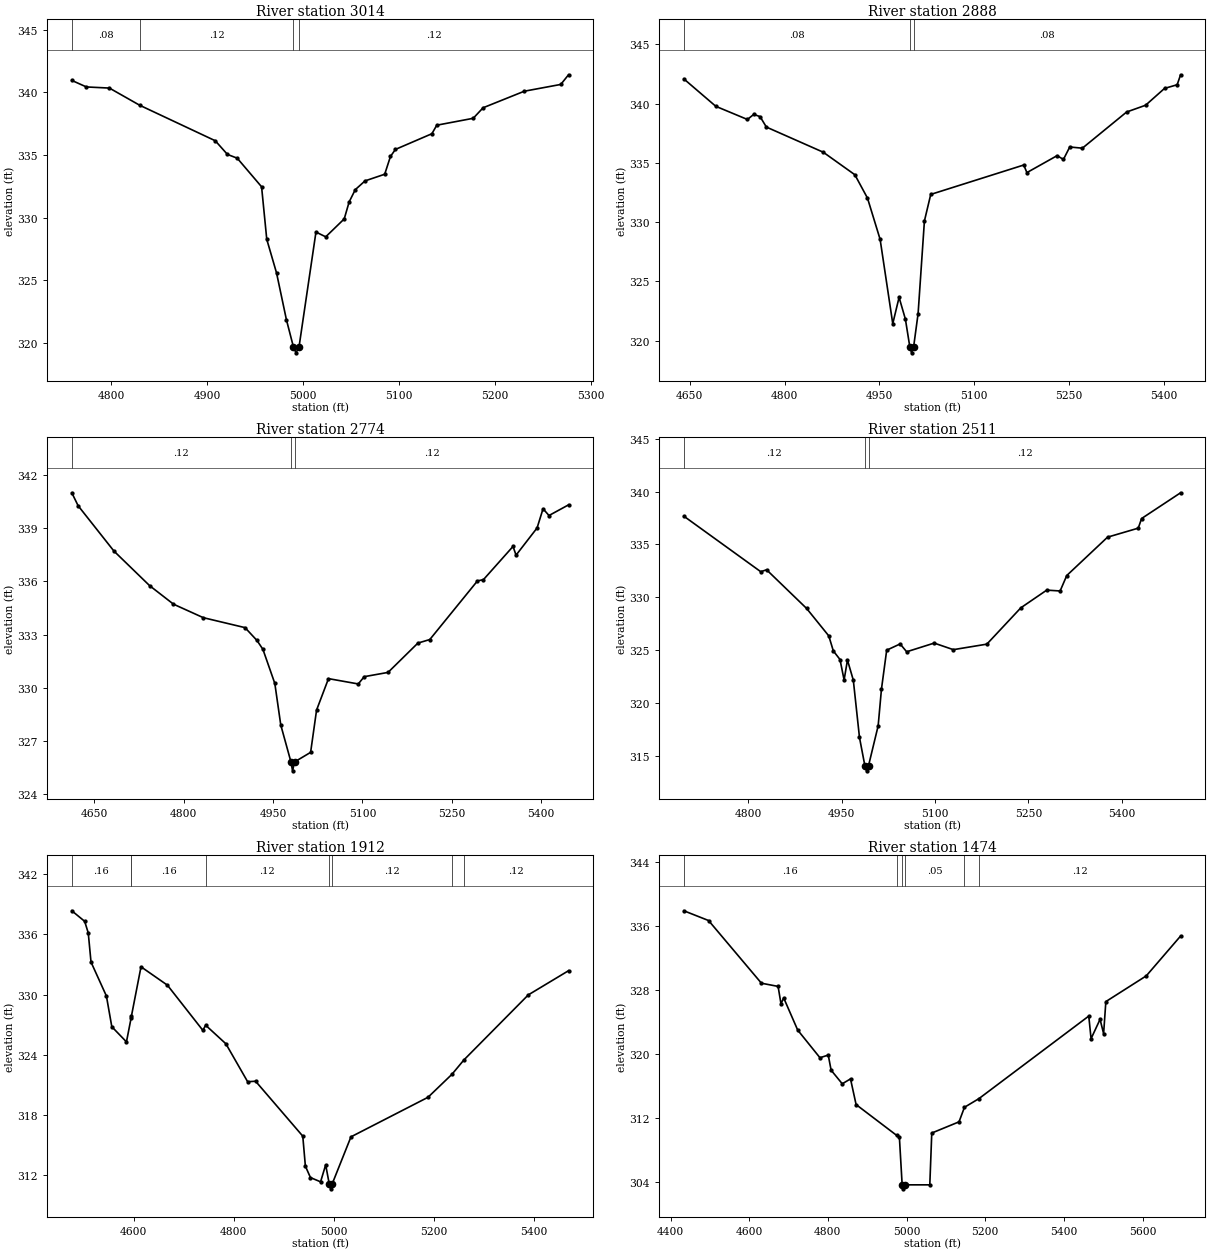
Type RM Length L Ch R = 1,3014,126,126,126
BEGIN DESCRIPTION:
UNT266 IN CCTC 4.0
END DESCRIPTION:
XS GIS Cut Line= 2
      3626330.90     10637101.94      3626445.48     10637607.11
#Sta/Elev= 30
  4758.8  340.95  4774.0  340.43  4798.0  340.34  4829.6  338.97  4908.4  336.14
  4921.1  335.05  4931.3  334.75  4956.7  332.47  4962.1  328.28  4972.3  325.60
  4982.6  321.87  4989.8  319.73  4992.6  319.23  4995.8  319.73  5013.4  328.86
  5023.6  328.48  5042.9  329.91  5048.0  331.26  5054.4  332.24  5064.6  332.94
  5085.1  333.47  5091.1  334.89  5096.3  335.45  5134.3  336.70  5139.4  337.38
  5177.4  337.93  5187.7  338.77  5230.7  340.09  5268.7  340.63  5276.8  341.40
#Mann=4,-1,0
  4758.8    0.08       0  4829.6    0.12       0  4989.8    0.07       0
  4995.8    0.12       0
Bank Sta=4989.8,4995.8
Exp/Cntr=0.3,0.1

Type RM Length L Ch R = 1,2888,114,114,114
BEGIN DESCRIPTION:
Mapping XS 29d244a6
END DESCRIPTION:
XS GIS Cut Line= 2
      3626303.55     10637069.59      3626290.54     10637855.58
#Sta/Elev= 30
  4640.5  342.08  4691.1  339.77  4741.1  338.66  4751.1  339.09  4761.1  338.90
  4771.1  338.02  4861.1  335.90  4911.1  334.00  4931.1  332.03  4951.1  328.55
  4971.1  321.44  4981.1  323.66  4991.1  321.82  4998.1  319.48  5000.9  318.98
  5004.1  319.48  5011.2  322.29  5021.2  330.10  5031.2  332.34  5178.4  334.82
  5183.4  334.18  5231.2  335.61  5241.2  335.29  5251.2  336.34  5271.2  336.24
  5341.2  339.29  5371.2  339.86  5401.2  341.28  5421.2  341.59  5426.6  342.43
#Mann=3,-1,0
  4640.5    0.08       0  4998.1    0.07       0  5004.1    0.08       0
Bank Sta=4998.1,5004.1
Exp/Cntr=0.3,0.1

Type RM Length L Ch R = 1,2774,263,263,263
BEGIN DESCRIPTION:
Mapping XS 39db04da
END DESCRIPTION:
XS GIS Cut Line= 2
      3626220.22     10637069.56      3626191.57     10637902.96
#Sta/Elev= 30
  4612.1  340.98  4622.7  340.25  4682.8  337.70  4742.8  335.75  4782.8  334.71
  4832.9  333.95  4902.9  333.39  4922.9  332.67  4932.9  332.17  4952.9  330.25
  4962.9  327.91  4980.0  325.83  4982.7  325.33  4986.0  325.83  5013.0  326.37
  5023.0  328.75  5043.0  330.52  5093.0  330.22  5103.0  330.63  5143.0  330.87
  5193.1  332.52  5213.1  332.72  5293.1  336.02  5303.1  336.09  5352.8  337.96
  5357.9  337.47  5393.2  339.00  5403.2  340.08  5413.2  339.70  5446.0  340.30
#Mann=3,-1,0
  4612.1    0.12       0  4980.0    0.07       0  4986.0    0.12       0
Bank Sta=4980,4986
Exp/Cntr=0.3,0.1

Type RM Length L Ch R = 1,2511,599,599,599
BEGIN DESCRIPTION:
Mapping XS 48962be7
END DESCRIPTION:
XS GIS Cut Line= 2
      3625851.74     10637206.11      3626138.17     10637950.83
#Sta/Elev= 30
  4696.6  337.67  4820.1  332.43  4829.5  332.61  4893.8  328.96  4929.4  326.37
  4936.7  324.95  4947.4  324.14  4954.0  322.21  4959.4  324.09  4968.8  322.19
  4978.7  316.78  4987.3  314.13  4990.0  313.63  4993.3  314.13  5008.7  317.88
  5014.0  321.34  5022.4  325.02  5044.0  325.61  5054.5  324.87  5098.7  325.69
  5129.5  325.07  5183.3  325.59  5237.9  329.02  5279.5  330.69  5301.0  330.61
  5311.7  332.07  5377.2  335.69  5426.5  336.54  5431.9  337.45  5494.5  339.88
#Mann=3,-1,0
  4696.6    0.12       0  4987.3    0.07       0  4993.3    0.12       0
Bank Sta=4987.3,4993.3
Exp/Cntr=0.3,0.1

Type RM Length L Ch R = 1,1912,438,438,438
BEGIN DESCRIPTION:
Mapping XS cc77fb1b
END DESCRIPTION:
XS GIS Cut Line= 3
      3625638.17     10637216.51      3625476.73     10637596.69
      3625570.48     10638169.63
#Sta/Elev= 30
  4476.3  338.35  4502.0  337.30  4509.2  336.14  4514.7  333.24  4545.5  329.86
  4556.3  326.80  4585.6  325.29  4594.8  327.64  4595.4  327.82  4614.7  332.77
  4667.5  330.94  4738.4  326.44  4744.0  326.95  4784.5  325.10  4828.0  321.32
  4843.9  321.37  4938.3  315.90  4943.5  312.91  4953.7  311.77  4973.9  311.35
  4984.1  313.04  4991.2  311.15  4994.0  310.65  4997.2  311.15  5034.7  315.83
  5188.8  319.77  5236.7  322.06  5260.6  323.49  5389.4  329.97  5469.9  332.38
#Mann=8,-1,0
  4476.3    0.16       0  4594.8    0.05       0  4595.4    0.16       0
  4744.0    0.12       0  4991.2    0.07       0  4997.2    0.12       0
  5236.7    0.16       0  5260.6    0.12       0
Bank Sta=4991.2,4997.2
Exp/Cntr=0.3,0.1

Type RM Length L Ch R = 1,1474,606,606,606
BEGIN DESCRIPTION:
UNT266 IN CCTC 3.0
END DESCRIPTION:
XS GIS Cut Line= 4
      3625435.07     10637346.68      3625096.52     10637706.07
      3625106.94     10637877.94      3625398.62     10638398.81
#Sta/Elev= 30
  4433.9  337.89  4496.7  336.67  4631.1  328.83  4673.5  328.43  4680.8  326.26
  4687.7  326.99  4723.3  322.97  4779.9  319.51  4801.0  319.84  4808.3  317.95
  4836.6  316.25  4857.6  316.86  4871.8  313.65  4975.1  309.79  4981.9  309.55
  4988.9  303.61  4991.6  303.11  4994.9  303.61  5059.2  303.61  5064.2  310.09
  5133.5  311.49  5147.3  313.31  5184.0  314.39  5463.4  324.72  5469.2  321.89
  5492.1  324.31  5501.1  322.52  5506.8  326.53  5609.6  329.75  5696.8  334.73
#Mann=6,-1,0
  4433.9    0.16       0  4975.1    0.05       0  4988.9   0.035       0
  4994.9    0.05       0  5147.3    0.16       0  5184.0    0.12       0
Bank Sta=4988.9,4994.9
Exp/Cntr=0.3,0.1

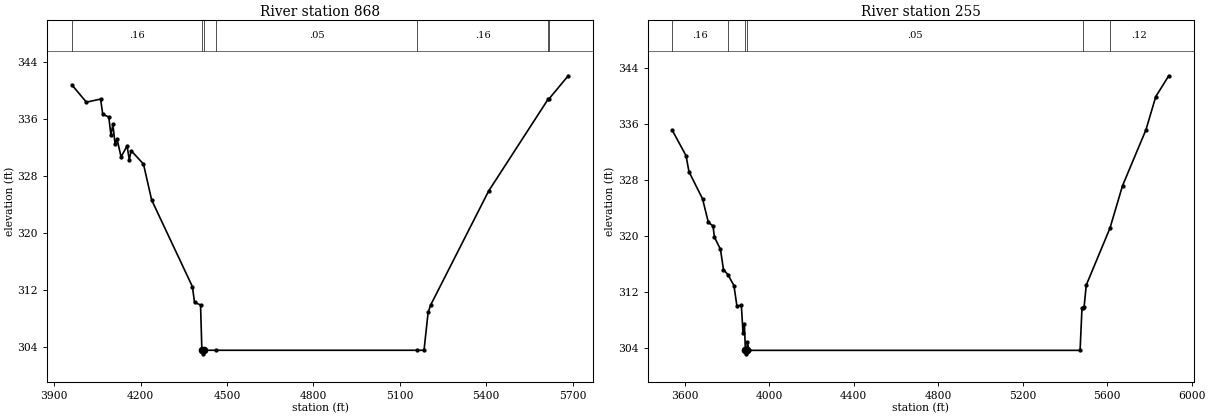
Type RM Length L Ch R = 1,868,613,613,613
BEGIN DESCRIPTION:
UNT266 IN CCTC 2.0
END DESCRIPTION:
XS GIS Cut Line= 4
      3625268.40     10637367.52      3624632.98     10638086.28
      3624674.64     10638268.57      3625163.73     10638575.55
#Sta/Elev= 30
  3960.9  340.75  4011.5  338.32  4060.9  338.75  4068.4  336.62  4089.3  336.25
  4096.9  333.69  4103.6  335.25  4111.1  332.45  4117.8  333.20  4132.0  330.66
  4152.9  332.20  4160.4  330.26  4167.1  331.53  4209.8  329.66  4238.2  324.63
  4379.6  312.52  4387.1  310.31  4408.0  309.95  4412.6  303.61  4415.3  303.11
  4418.6  303.61  4461.4  303.61  5160.4  303.61  5184.0  303.61  5198.3  308.92
  5207.6  309.98  5408.3  325.88  5615.2  338.75  5616.8  338.72  5684.7  342.01
#Mann=7,-1,0
  3960.9    0.16       0  4412.6   0.033       0  4418.6    0.16       0
  4461.4    0.05       0  5160.4    0.16       0  5615.2    0.12       0
  5616.8    0.16       0
Bank Sta=4412.6,4418.6
Exp/Cntr=0.3,0.1

Type RM Length L Ch R = 1,255,0,0,0
BEGIN DESCRIPTION:
UNT266 IN CCTC 1.0
END DESCRIPTION:
XS GIS Cut Line= 4
      3625049.65     10637419.60      3624190.27     10638456.07
      3624221.52     10638664.40      3625006.30     10638773.54
#Sta/Elev= 30
  3542.1  335.09  3607.0  331.47  3620.8  329.18  3685.1  325.29  3712.5  321.93
  3734.6  321.42  3741.1  319.83  3769.8  318.07  3784.1  315.17  3805.0  314.45
  3833.6  312.89  3847.9  309.92  3868.7  310.09  3876.6  306.06  3883.1  307.37
  3887.9  303.61  3890.6  303.11  3893.9  303.61  3897.4  304.74  3905.2  303.61
  5471.9  303.61  5480.9  309.64  5485.6  309.74  5491.0  309.85  5501.1  312.95
  5613.2  321.09  5672.7  327.17  5783.8  335.19  5830.0  339.92  5891.5  342.91
#Mann=6,-1,0
  3542.1    0.16       0  3805.0    0.05       0  3887.9   0.033       0
  3893.9    0.05       0  5485.6    0.16       0  5613.2    0.12       0
Bank Sta=3887.9,3893.9
Exp/Cntr=0.3,0.1

Chan Stop Cuts=-1