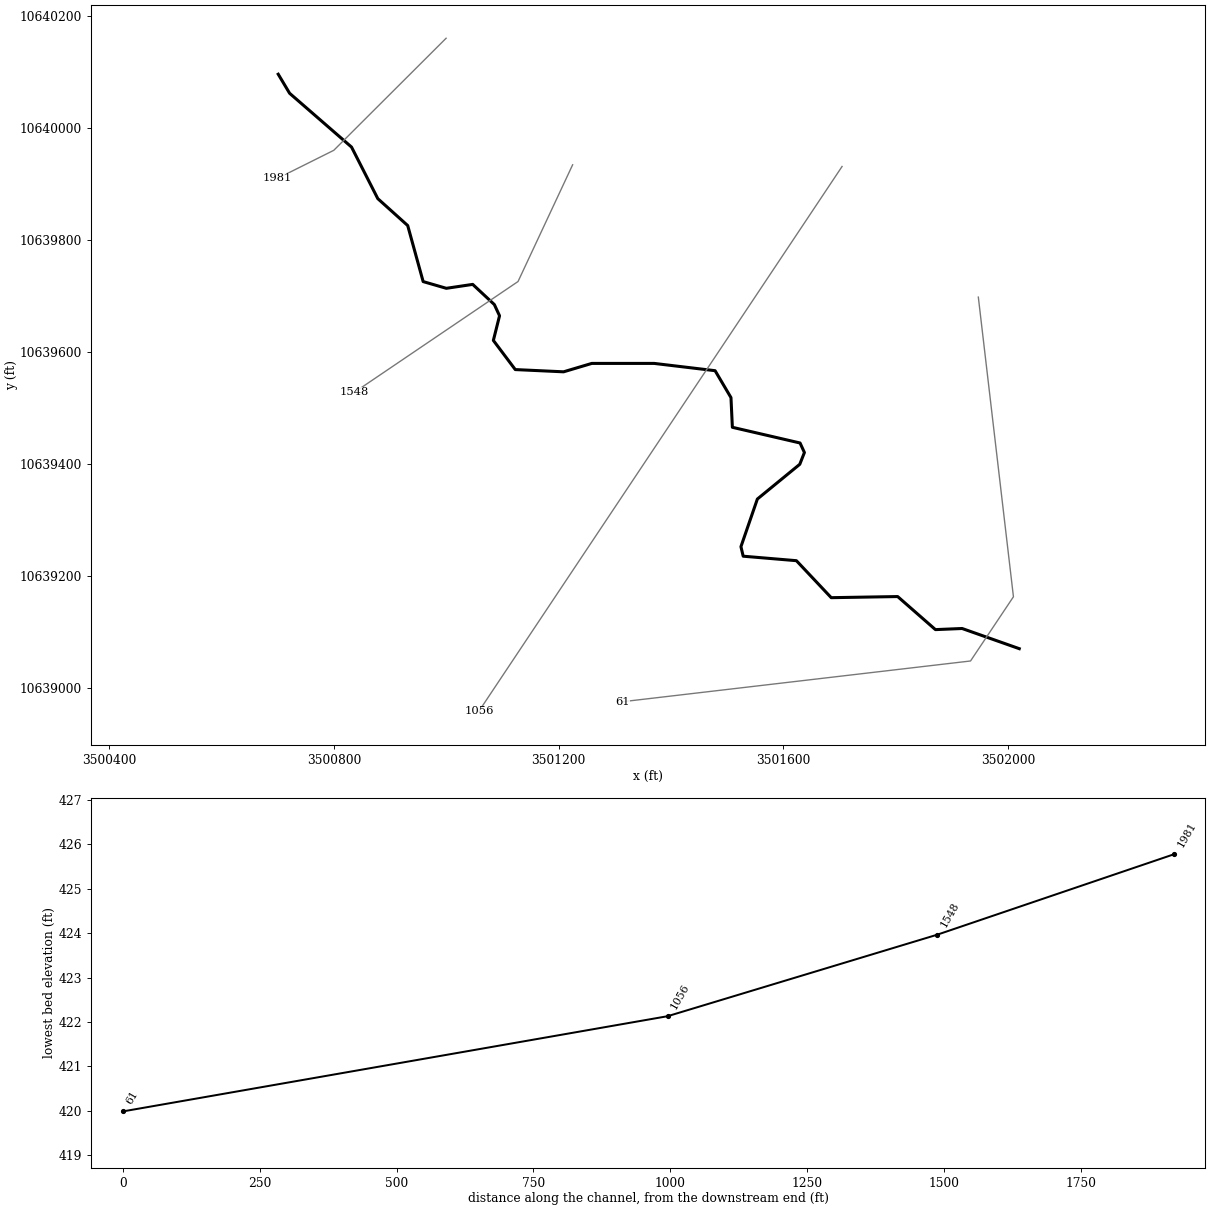
--- UNT300 IN CCTC.prj (project) ---

Proj Title=UNT300 IN CCTC Base Level Engineering
Current Plan=p01
Default Exp/Contr=0.3,0.1
English Units
Geom File=g01
Flow File=f01
Plan File=p01
Y Axis Title=Elevation
X Axis Title(PF)=Main Channel Distance
X Axis Title(XS)=Station
BEGIN DESCRIPTION:
UNT300 IN CCTC
END DESCRIPTION:
DSS Export Rating Curves= 0
DSS Export Rating Curve Sorted= 0
DSS Export Volume Flow Curves= 0
DXF OffsetX= 0
DXF OffsetY= 0
DXF ScaleX= 1
DXF ScaleY= 10

--- UNT300 IN CCTC.p01 (plan) ---

Plan Title=Multiple Run
Short Identifier=Multiple
Geom File=g01
Flow File=f01
Subcritical Flow
K Sum by GR= 0
Std Step Tol= 0.01
Critical Tol= 0.01
Num of Std Step Trials= 20
Max Error Tol= 0.3
Flow Tol Ratio= 0.001
Split Flow NTrial= 30
Split Flow Tol= 0.02
Split Flow Ratio= 0.02
Log Output Level= 0
Friction Slope Method= 1
Unsteady Friction Slope Method= 2
Unsteady Bridges Friction Slope Method= 1
Parabolic Critical Depth
Global Vel Dist=  1 , 1 , 1
Global Log Level= 0
CheckData=True
Encroach Param= -1, 0, 0, 0
BEGIN DESCRIPTION:
Multiple Run
END DESCRIPTION:

--- UNT300 IN CCTC.f01 (steady flow) ---

Flow Title=Multiple
Number of Profiles=7
Profile Names=10-year,25-year,50-year,1pct_min,100-year,1pct_plu,500-year
River Rch & RM= UNT300 IN CCTC,Reach-1,1981
    1020    1383    1678    1487    2011    2720    2880
Boundary for River Rch & Prof#=UNT300 IN CCTC,Reach-1,1
Up Type=0
Dn Type=3
Dn Slope=0.005
Boundary for River Rch & Prof#=UNT300 IN CCTC,Reach-1,2
Up Type=0
Dn Type=3
Dn Slope=0.005
Boundary for River Rch & Prof#=UNT300 IN CCTC,Reach-1,3
Up Type=0
Dn Type=3
Dn Slope=0.005
Boundary for River Rch & Prof#=UNT300 IN CCTC,Reach-1,4
Up Type=0
Dn Type=3
Dn Slope=0.005
Boundary for River Rch & Prof#=UNT300 IN CCTC,Reach-1,5
Up Type=0
Dn Type=3
Dn Slope=0.005
Boundary for River Rch & Prof#=UNT300 IN CCTC,Reach-1,6
Up Type=0
Dn Type=3
Dn Slope=0.005
Boundary for River Rch & Prof#=UNT300 IN CCTC,Reach-1,7
Up Type=0
Dn Type=3
Dn Slope=0.005

--- UNT300 IN CCTC.g01 (geometry) ---

Geom Title=Existing Conditions
Program Version=4.10

River Reach=UNT300 IN CCTC  ,Reach-1
Reach XY= 30
      3500700.75       10640096.        3500721.       10640062.
      3500831.25       10639966.        3500878.       10639874.
      3500931.25       10639826.      3500958.75       10639726.
        3501000.       10639714.        3501047.       10639721.
       3501085.5       10639685.      3501094.75       10639665.
      3501083.75       10639621.      3501122.75       10639569.
      3501208.75       10639565.        3501259.       10639580.
        3501370.       10639580.       3501478.5       10639567.
      3501506.75       10639519.      3501509.25       10639466.
      3501629.75       10639438.       3501637.5       10639421.
      3501629.25       10639400.      3501553.75       10639338.
       3501524.5       10639253.       3501528.5       10639236.
      3501623.25       10639228.      3501685.25       10639162.
       3501803.5       10639164.      3501870.75       10639105.
      3501918.25       10639107.        3502020.       10639071.

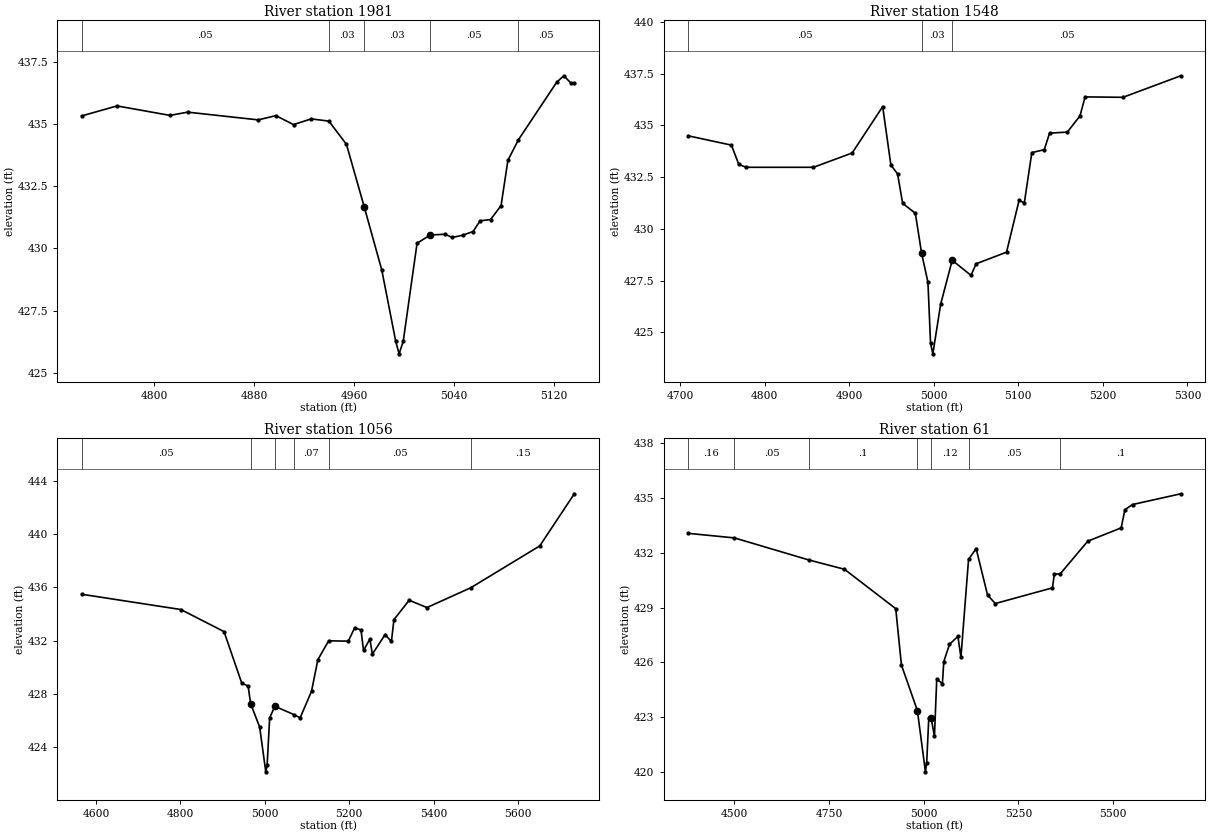
Type RM Length L Ch R = 1 ,1981    ,433,433,433
BEGIN DESCRIPTION:
UNT300 IN CCTC 4.0
END DESCRIPTION:
XS GIS Cut Line= 3
      3500999.62      10640160.2      3500799.61     10639960.19
      3500699.57     10639910.17
#Sta/Elev= 30
  4741.7  435.32    4770  435.72  4812.4  435.34  4826.6  435.47  4883.1  435.16
  4897.3  435.33  4911.4  434.97  4925.6   435.2  4939.7  435.11  4953.8  434.18
    4968  431.68  4982.1  429.14  4993.3  426.27    4996  425.77  4999.3  426.27
  5010.4  430.21    5021  430.54  5032.9  430.57  5038.5  430.44  5046.9  430.53
  5055.3  430.68  5060.9  431.11  5069.3  431.16  5077.7  431.72  5083.2  433.54
  5091.6  434.36  5122.4  436.68    5128  436.93  5133.6  436.64  5136.4  436.64
#Mann= 5 ,-1 , 0
  4741.7     .05       0  4939.7     .03       0    4968     .03       0
    5021     .05       0  5091.6     .05       0
Bank Sta=4968,5021
XS Rating Curve= 0 ,0
Exp/Cntr=0.3,0.1

Type RM Length L Ch R = 1 ,1548    ,492,492,492
BEGIN DESCRIPTION:
UNT300 IN CCTC 3.0
END DESCRIPTION:
XS GIS Cut Line= 3
      3501224.88     10639934.42      3501127.68     10639726.12
      3500836.05     10639528.23
#Sta/Elev= 30
  4709.8  434.49  4760.9  434.04  4769.6  433.11  4778.3  432.97  4857.9  432.97
  4903.6  433.66  4939.7   435.9  4949.4  433.08  4957.3  432.65  4963.3  431.23
  4978.3  430.75  4985.7  428.82  4993.2  427.42  4996.3  424.46    4999  423.96
  5008.2  426.35  5021.9  428.48  5044.1  427.75  5050.2  428.31  5086.1  428.87
    5101  431.38  5107.1  431.24    5116  433.68  5130.7  433.82    5137  434.62
    5158  434.67  5172.9  435.45    5179  436.37  5223.8  436.35  5292.1  437.39
#Mann= 3 , 0 , 0
  4709.8     .05       0  4985.7     .03       0  5021.9     .05       0
Bank Sta=4985.7,5021.9
XS Rating Curve= 0 ,0
Exp/Cntr=0.3,0.1

Type RM Length L Ch R = 1 ,1056    ,995,995,995
BEGIN DESCRIPTION:
UNT300 IN CCTC 2.0
END DESCRIPTION:
XS GIS Cut Line= 2
      3501704.54     10639931.38      3501057.82     10638959.13
#Sta/Elev= 30
    4566  435.49  4801.1  434.34  4903.3  432.68  4945.4   428.8  4960.4  428.59
  4966.4  427.25  4987.8   425.5  5002.3  422.13  5005.5  422.63  5011.5  426.19
  5023.8  427.06  5069.6  426.43  5083.7  426.19  5110.7  428.19  5125.8  430.57
  5151.3  431.99  5197.9  431.96  5212.9  432.96    5228  432.81    5234  431.26
    5249  432.12    5255  430.99  5285.1  432.45  5300.1  431.94  5306.1  433.58
  5342.2  435.04  5384.3  434.49  5488.3  435.98  5651.8  439.13  5733.7  443.05
#Mann= 6 ,-1 , 0
    4566     .05       0  4966.4    .035       0  5023.8     .05       0
  5069.6     .07       0  5151.3     .05       0  5488.3     .15       0
Bank Sta=4966.4,5023.8
XS Rating Curve= 0 ,0
Exp/Cntr=0.3,0.1

Type RM Length L Ch R = 1 ,61      ,0,0,0
BEGIN DESCRIPTION:
UNT300 IN CCTC 1.0
END DESCRIPTION:
XS GIS Cut Line= 4
      3501947.12     10639698.31      3502009.62     10639163.62
      3501933.23     10639049.04      3501313.13     10638976.29
#Sta/Elev= 30
  4378.1  433.07    4500  432.82  4696.6  431.61  4790.6   431.1    4926  428.94
    4941  425.85  4983.1  423.35  5004.4  419.99  5007.7  420.49  5013.2  422.94
  5019.2  422.97  5028.2  421.94  5034.2  425.07  5049.2  424.83  5052.9  426.04
  5067.9  426.98  5090.1  427.42  5098.1  426.27  5118.2  431.64  5138.3  432.23
  5168.3  429.69  5188.7  429.22  5339.7  430.08  5344.7  430.84  5359.9  430.84
  5432.9  432.64  5521.1  433.37    5531  434.37  5551.2  434.65  5678.5  435.24
#Mann= 7 ,-1 , 0
  4378.1     .16       0    4500     .05       0  4696.6      .1       0
  4983.1     .07       0  5019.2     .12       0  5118.2     .05       0
  5359.9      .1       0
Bank Sta=4983.1,5019.2
XS Rating Curve= 0 ,0
Exp/Cntr=0.3,0.1

Chan Stop Cuts=-1
Use User Specified Reach Order=0
Composite Channel Slope=5