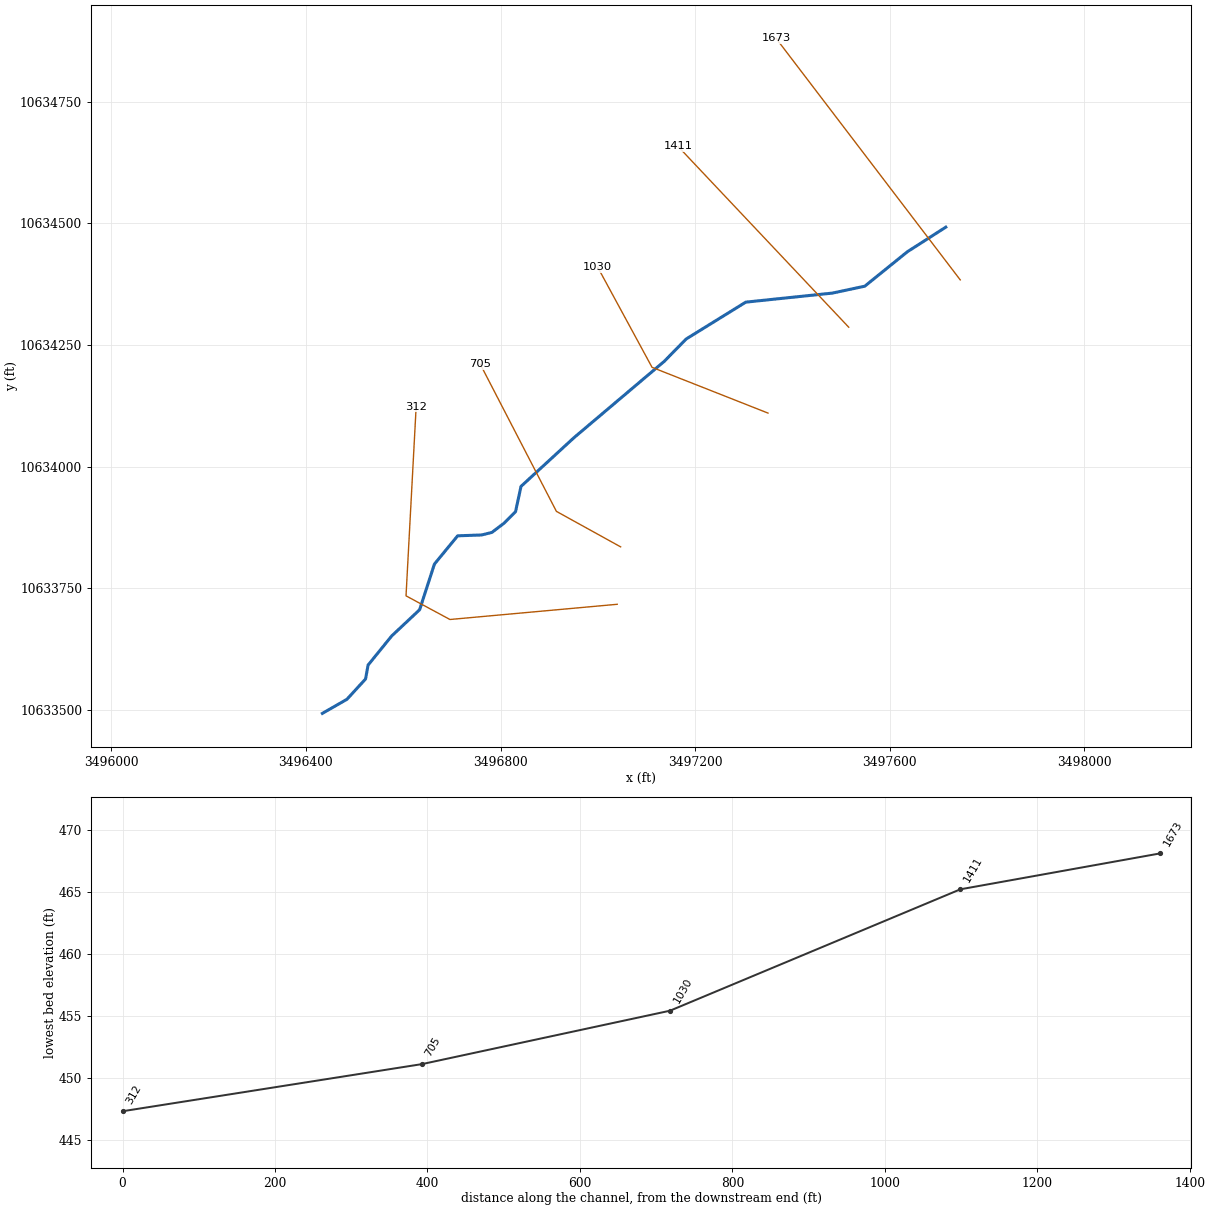
--- UNT400 IN CCTC.prj (project) ---

Proj Title=UNT400 IN CCTC Base Level Engineering
Current Plan=p01
Default Exp/Contr=0.3,0.1
English Units
Geom File=g01
Flow File=f01
Plan File=p01
Y Axis Title=Elevation
X Axis Title(PF)=Main Channel Distance
X Axis Title(XS)=Station
BEGIN DESCRIPTION:
UNT400 IN CCTC
END DESCRIPTION:
DSS Export Rating Curves= 0
DSS Export Rating Curve Sorted= 0
DSS Export Volume Flow Curves= 0
DXF OffsetX= 0
DXF OffsetY= 0
DXF ScaleX= 1
DXF ScaleY= 10

--- UNT400 IN CCTC.p01 (plan) ---

Plan Title=Multiple Run
Short Identifier=Multiple
Geom File=g01
Flow File=f01
Subcritical Flow
K Sum by GR= 0
Std Step Tol= 0.01
Critical Tol= 0.01
Num of Std Step Trials= 20
Max Error Tol= 0.3
Flow Tol Ratio= 0.001
Split Flow NTrial= 30
Split Flow Tol= 0.02
Split Flow Ratio= 0.02
Log Output Level= 0
Friction Slope Method= 1
Unsteady Friction Slope Method= 2
Unsteady Bridges Friction Slope Method= 1
Parabolic Critical Depth
Global Vel Dist=  1 , 1 , 1
Global Log Level= 0
CheckData=True
Encroach Param= -1, 0, 0, 0
BEGIN DESCRIPTION:
Multiple Run
END DESCRIPTION:

--- UNT400 IN CCTC.f01 (steady flow) ---

Flow Title=Multiple
Program Version=4.10
Number of Profiles= 7
Profile Names=10-year,25-year,50-year,1pct_min,100-year,1pct_plu,500-year
River Rch & RM=UNT400 IN CCTC,Reach-1         ,1673
     192     231     260     215     290     393     359
Boundary for River Rch & Prof#=UNT400 IN CCTC,Reach-1         , 1
Up Type= 0
Dn Type= 3
Dn Slope=0.01
Boundary for River Rch & Prof#=UNT400 IN CCTC,Reach-1         , 2
Up Type= 0
Dn Type= 3
Dn Slope=0.01
Boundary for River Rch & Prof#=UNT400 IN CCTC,Reach-1         , 3
Up Type= 0
Dn Type= 3
Dn Slope=0.01
Boundary for River Rch & Prof#=UNT400 IN CCTC,Reach-1         , 4
Up Type= 0
Dn Type= 3
Dn Slope=0.01
Boundary for River Rch & Prof#=UNT400 IN CCTC,Reach-1         , 5
Up Type= 0
Dn Type= 3
Dn Slope=0.01
Boundary for River Rch & Prof#=UNT400 IN CCTC,Reach-1         , 6
Up Type= 0
Dn Type= 3
Dn Slope=0.01
Boundary for River Rch & Prof#=UNT400 IN CCTC,Reach-1         , 7
Up Type= 0
Dn Type= 3
Dn Slope=0.01
DSS Import GetInterval= 0
DSS Import GetPeak= 0
DSS Import FillOption= 0

--- UNT400 IN CCTC.g01 (geometry) ---

Geom Title=Existing Conditions
Program Version=4.10

River Reach=UNT400 IN CCTC  ,Reach-1
Reach XY= 21
      3497715.01     10634492.34      3497636.16     10634441.84
      3497548.45     10634370.96        3497482.     10634356.79
      3497303.92     10634338.18      3497181.51     10634262.45
      3497136.37     10634216.45      3496950.61     10634059.33
       3496842.1      10633959.5      3496830.82     10633907.42
      3496807.38     10633883.98      3496782.21     10633864.88
      3496761.37     10633859.68      3496711.89     10633857.94
      3496664.15     10633799.78      3496633.77     10633706.03
      3496576.48     10633652.21      3496527.86     10633592.31
      3496522.66     10633563.67      3496484.46       10633522.
        3496434.       10633493.

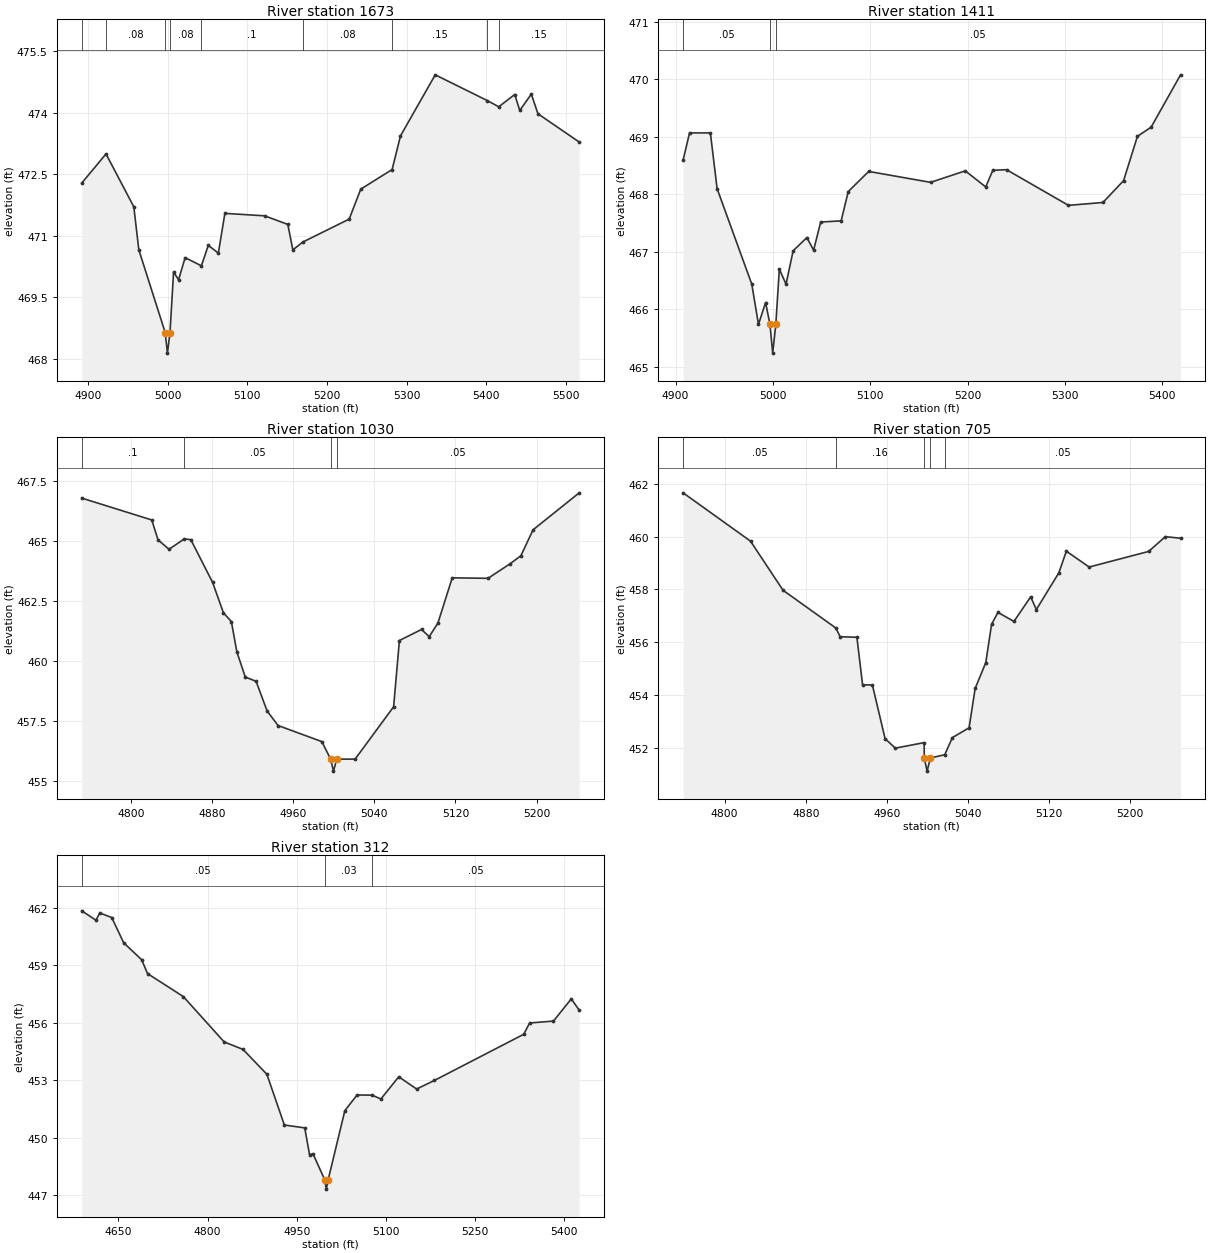
Type RM Length L Ch R = 1 ,1673    ,262,262,262
BEGIN DESCRIPTION:
UNT400 IN CCTC 3.0
END DESCRIPTION:
XS GIS Cut Line= 2
       3497744.7     10634383.88      3497366.24     10634880.39
#Sta/Elev= 30
  4892.3  472.29  4922.7     473  4957.6  471.71  4963.9  470.66    4997  468.64
  4999.8  468.14    5003  468.64  5007.5  470.12  5013.8  469.93    5022  470.47
  5042.4  470.27  5051.1  470.77  5063.7  470.58  5071.9  471.55  5121.8  471.49
  5150.9  471.28  5157.2  470.66  5169.7  470.85  5227.9  471.41  5242.4  472.14
  5281.8  472.62  5292.3  473.44  5335.9  474.93  5401.5   474.3  5415.6  474.15
  5435.7  474.45    5442  474.06  5456.5  474.46  5464.8  473.98  5516.6  473.29
#Mann= 9 ,-1 , 0
  4892.3     .05       0  4922.7     .08       0    4997     .07       0
    5003     .08       0  5042.4      .1       0  5169.7     .08       0
  5281.8     .15       0  5401.5      .1       0  5415.6     .15       0
Bank Sta=4997,5003
XS Rating Curve= 0 ,0
Exp/Cntr=0.3,0.1

Type RM Length L Ch R = 1 ,1411    ,381,381,381
BEGIN DESCRIPTION:
Mapping XS f9398e3e
END DESCRIPTION:
XS GIS Cut Line= 2
      3497515.55     10634286.63      3497164.86     10634658.16
#Sta/Elev= 30
  4907.8   468.6  4914.4  469.07  4935.8  469.07  4942.7   468.1  4978.3  466.44
  4985.2  465.74  4992.5  466.12    4997  465.74  4999.8  465.24    5003  465.74
  5006.6   466.7  5013.5  466.44  5020.8  467.02  5034.9  467.25  5041.8  467.03
  5049.1  467.52  5070.1  467.54  5077.4  468.05  5098.4   468.4    5162  468.21
  5197.6  468.41  5218.6  468.13  5225.9  468.42    5240  468.43  5303.6  467.81
    5339  467.86  5360.2  468.24  5374.4  469.01  5388.5  469.17  5418.7  470.08
#Mann= 3 ,-1 , 0
  4907.8     .05       0    4997     .04       0    5003     .05       0
Bank Sta=4997,5003
XS Rating Curve= 0 ,0
Exp/Cntr=0.3,0.1

Type RM Length L Ch R = 1 ,1030    ,325,325,325
BEGIN DESCRIPTION:
UNT400 IN CCTC 2.0
END DESCRIPTION:
XS GIS Cut Line= 3
       3497349.6     10634110.19      3497111.38     10634204.18
      3496999.59     10634410.22
#Sta/Elev= 30
  4751.6   466.8  4820.6  465.89  4826.8  465.06  4837.6  464.67  4852.7   465.1
  4859.1  465.07  4880.6  463.29  4891.3  462.02  4899.1  461.66  4904.5   460.4
  4912.8  459.35  4923.5  459.17  4934.3  457.94  4945.1  457.33  4988.3  456.66
    4997  455.93  4999.8  455.43    5003  455.93  5021.1  455.93  5059.1  458.11
  5064.8  460.87  5086.6  461.33  5094.2  461.03  5102.8   461.6  5116.9  463.48
  5152.2  463.46  5174.1  464.07  5184.6   464.4  5196.6  465.48  5242.1  467.02
#Mann= 4 ,-1 , 0
  4751.6      .1       0  4852.7     .05       0    4997    .035       0
    5003     .05       0
Bank Sta=4997,5003
XS Rating Curve= 0 ,0
Exp/Cntr=0.3,0.1

Type RM Length L Ch R = 1 ,705     ,393,393,393
BEGIN DESCRIPTION:
Mapping XS 03ff022a
END DESCRIPTION:
XS GIS Cut Line= 3
      3497046.82     10633835.24      3496914.85     10633908.17
      3496758.59     10634210.26
#Sta/Elev= 30
    4759  461.66  4825.5  459.83  4857.6  457.97  4909.7  456.54    4914  456.21
  4930.5  456.19  4936.1  454.39  4945.8  454.38  4958.3  452.35  4968.4  451.99
  4996.9   452.2    4997  451.62  4999.8  451.12    5003  451.62  5017.2  451.74
  5024.7  452.39  5041.2  452.76  5047.2  454.25  5057.7  455.23  5063.4  456.68
  5069.7  457.13  5085.5  456.79    5102  457.72  5107.6  457.24  5129.8  458.63
  5137.2  459.45  5159.7  458.85  5218.4  459.44  5234.9     460  5249.9  459.94
#Mann= 5 ,-1 , 0
    4759     .05       0  4909.7     .16       0    4997     .07       0
    5003     .16       0  5017.2     .05       0
Bank Sta=4997,5003
XS Rating Curve= 0 ,0
Exp/Cntr=0.3,0.1

Type RM Length L Ch R = 1 ,312     ,0,0,0
BEGIN DESCRIPTION:
UNT400 IN CCTC 1.0
END DESCRIPTION:
XS GIS Cut Line= 4
      3497039.81      10633717.2       3496696.1     10633685.95
      3496605.82     10633734.56      3496626.65     10634123.44
#Sta/Elev= 30
  4588.3  461.85  4612.1  461.36  4618.6  461.74  4638.7   461.5  4658.8  460.18
  4688.9   459.3    4699  458.57  4759.2  457.37  4827.9     455  4859.6  454.61
  4899.8  453.31  4929.2  450.66  4963.5  450.51  4971.6  449.11  4977.3  449.16
    4997  447.81  4999.8  447.31    5003  447.81    5031  451.41  5051.6  452.23
  5076.8  452.22  5091.7  452.02  5121.7  453.18  5151.8  452.54  5181.8  452.99
    5332   455.4    5342  455.99  5382.1  456.09  5412.1  457.25  5425.4  456.66
#Mann= 3 ,-1 , 0
  4588.3     .05       0    4997     .03       0  5076.8     .05       0
Bank Sta=4997,5003
XS Rating Curve= 0 ,0
Exp/Cntr=0.3,0.1

Chan Stop Cuts=-1
Use User Specified Reach Order=0
Composite Channel Slope=5