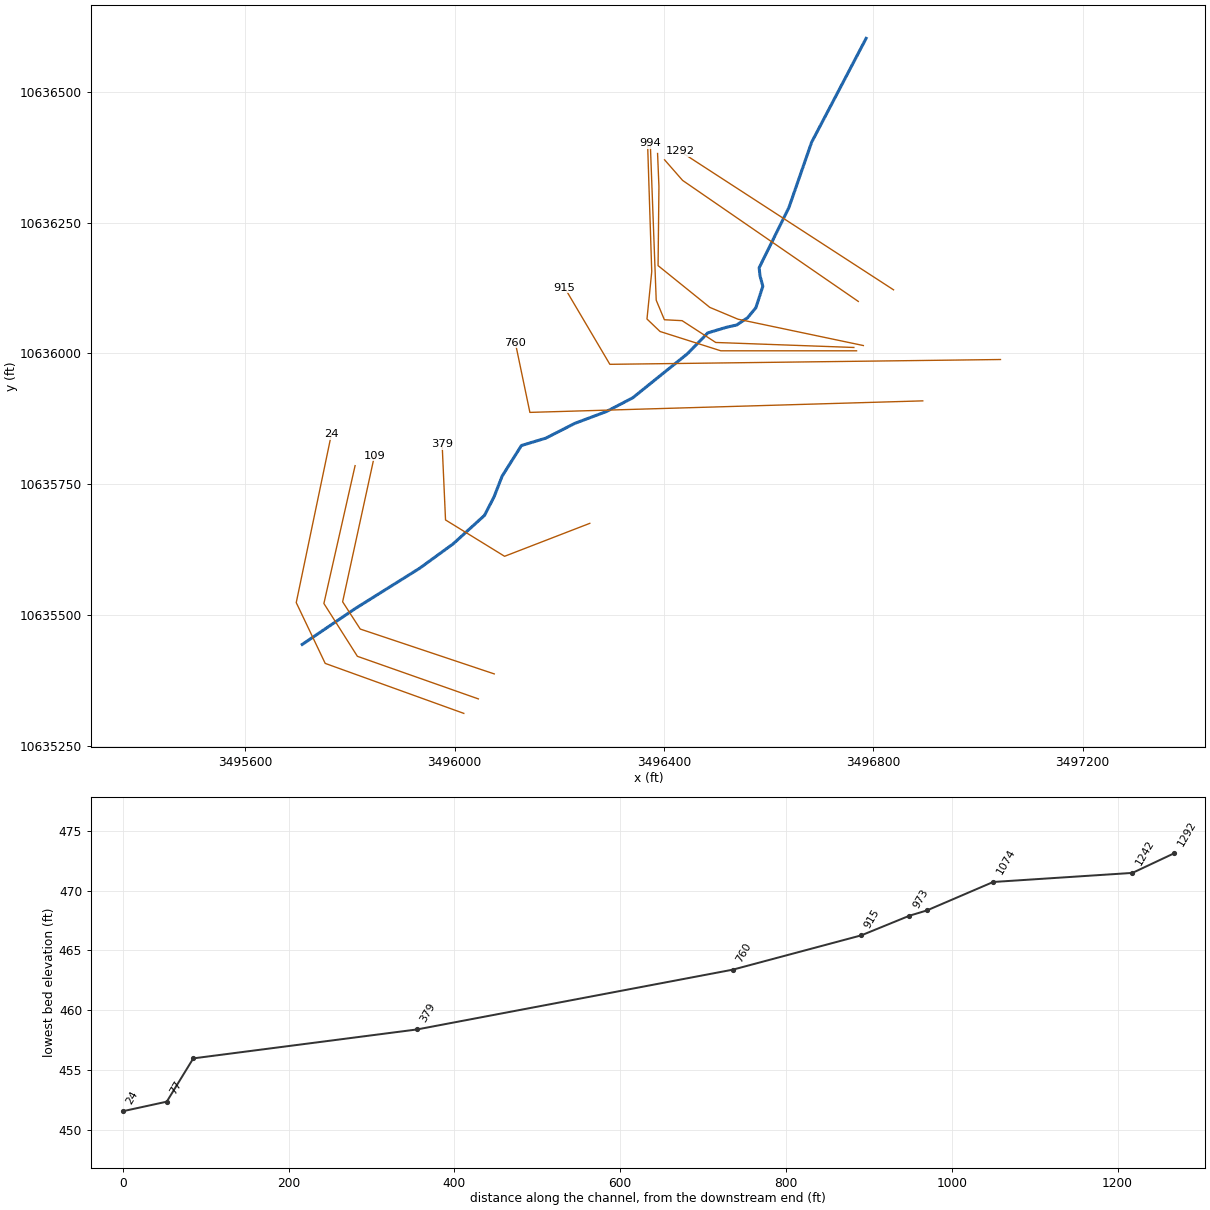
--- UNT401 IN CCTC.prj (project) ---

Proj Title=UNT401 IN CCTC Base Level Engineering
Current Plan=p01
Default Exp/Contr=0.3,0.1
English Units
Geom File=g01
Flow File=f01
Plan File=p01
Y Axis Title=Elevation
X Axis Title(PF)=Main Channel Distance
X Axis Title(XS)=Station
BEGIN DESCRIPTION:
UNT401 IN CCTC
END DESCRIPTION:
DSS File=dss
DSS Export Rating Curves= 0
DSS Export Rating Curve Sorted= 0
DSS Export Volume Flow Curves= 0
DXF OffsetX= 0
DXF OffsetY= 0
DXF ScaleX= 1
DXF ScaleY= 10

--- UNT401 IN CCTC.p01 (plan) ---

Plan Title=Multiple Run
Program Version=4.10
Short Identifier=Multiple Run
Geom File=g01
Flow File=f01
Subcritical Flow
K Sum by GR= 0
Std Step Tol= 0.01
Critical Tol= 0.01
Num of Std Step Trials= 20
Max Error Tol= 0.3
Flow Tol Ratio= 0.001
Split Flow NTrial= 30
Split Flow Tol= 0.02
Split Flow Ratio= 0.02
Log Output Level= 0
Friction Slope Method= 1
Unsteady Friction Slope Method= 2
Unsteady Bridges Friction Slope Method= 1
Parabolic Critical Depth
Global Vel Dist= 1 , 1 , 1
Global Log Level= 0
CheckData=True
Encroach Param=-1 ,0,0, 0
BEGIN DESCRIPTION:
Multiple Run
END DESCRIPTION:
Computation Interval=1HOUR
Output Interval=1HOUR
Run HTab= 0
Run UNet= 0
Run PostProcess= 0
Run WQNet= 0
UNET Theta= 1
UNET Theta Warmup= 1
UNET ZTol= 0.02
UNET ZSATol= 0.05
UNET MxIter= 20
UNET MaxInSteps= 0
UNET DtIC= 0
UNET DtMin= 0
UNET MaxCRTS= 20
UNET WFStab= 2
UNET SFStab= 1
UNET WFX= 1
UNET SFX= 1
UNET DSS MLevel= 4
UNET DZMax Abort= 100
UNET Convert EG Bridges= 0
UNET Use Existing IB Tables=-1
UNET Froude Reduction=False
UNET Froude Limit= 1
UNET Froude Power= 10
UNET Time Slicing=0,0, 5
UNET Junction Losses=0
Instantaneous Interval=1HOUR
DSS File=dss
Write IC File= 0
Write IC File at Sim End=0
Echo Input=False
Echo Parameters=False
Echo Output=False
Write Detailed= 0
WQ AD Non Conservative
WQ ULTIMATE=-1
WQ Max Comp Step=1HOUR
WQ Output Interval=15MIN
WQ Output Selected Increments= 0
WQ Output face flow=0
WQ Output face velocity=0
WQ Output face area=0
WQ Output face dispersion=0
WQ Output cell volume=0
WQ Output cell surface area=0
WQ Output cell continuity=0
WQ Output cumulative cell continuity=0
WQ Output face conc=0
WQ Output face dconc_dx=0
WQ Output face courant=0
WQ Output face peclet=0
WQ Output face adv mass=0
WQ Output face disp mass=0
WQ Output cell mass=0
WQ Output cell source sink temp=0
WQ Output cell source sink nsm=0
WQ Output MaxMinRange=-1
WQ Daily Max Min Mean=-1
WQ Daily Range=0
WQ Daily Time=0
WQ Create Restart=0
WQ Fixed Restart=0
WQ System Summary=0
WQ Use Fixed Temperature=0
Sorting and Armoring Iterations= 10
XS Update Threshold= 0.02
Hydraulics Update Threshold= 0.02
Energy Slope Method= 1
Volume Change Method= 0
XS Weighting Method= 0
Number of US Weighted Cross Sections= 1
Number of DS Weighted Cross Sections= 1
Upstream XS Weight=0.25
Main XS Weight=0.5
Downstream XS Weight=0.25
Number of DS XS's Weighted with US Boundary= 1
Upstream Boundary Weight= 1
Weight of XSs Associated with US Boundary= 0
Number of US XS's Weighted with DS Boundary= 1
Downstream Boundary Weight= 0.5
Weight of XSs Associated with DS Boundary= 0.5
Sediment Output Level= 4
Mass or Volume Output= 0
Output Increment Type= 1
Profile and TS Output Increment= 10
XS Output Flag= 0
XS Output Increment= 10
Disregard all LS=0
Disregard all Conn=0
Disregard all Breaches=0
Disregard all Pumps=0

--- UNT401 IN CCTC.f01 (steady flow) ---

Flow Title=Multiple
Program Version=4.10
Number of Profiles= 7
Profile Names=10-year,25-year,50-year,1pct_min,100-year,1pct_plu,500-year
River Rch & RM=UNT401 IN CCTC,Reach-1         ,1292
     155     184     204     166     225     304     271
River Rch & RM=UNT401 IN CCTC,Reach-1         ,77
     372     471     546     464     628     849     825
River Rch & RM=UNT401 IN CCTC,Reach-1         ,24
     470     605     710     610     825    1116    1108
Boundary for River Rch & Prof#=UNT401 IN CCTC,Reach-1         , 1
Up Type= 0
Dn Type= 3
Dn Slope=0.01376
Boundary for River Rch & Prof#=UNT401 IN CCTC,Reach-1         , 2
Up Type= 0
Dn Type= 3
Dn Slope=0.01376
Boundary for River Rch & Prof#=UNT401 IN CCTC,Reach-1         , 3
Up Type= 0
Dn Type= 3
Dn Slope=0.01376
Boundary for River Rch & Prof#=UNT401 IN CCTC,Reach-1         , 4
Up Type= 0
Dn Type= 3
Dn Slope=0.01376
Boundary for River Rch & Prof#=UNT401 IN CCTC,Reach-1         , 5
Up Type= 0
Dn Type= 3
Dn Slope=0.01376
Boundary for River Rch & Prof#=UNT401 IN CCTC,Reach-1         , 6
Up Type= 0
Dn Type= 3
Dn Slope=0.01376
Boundary for River Rch & Prof#=UNT401 IN CCTC,Reach-1         , 7
Up Type= 0
Dn Type= 3
Dn Slope=0.01376
DSS Import GetInterval= 0
DSS Import GetPeak= 0
DSS Import FillOption= 0

--- UNT401 IN CCTC.g01 (geometry) ---

Geom Title=Existing Conditions
Program Version=4.10

River Reach=UNT401 IN CCTC  ,Reach-1
Reach XY= 24
      3496786.29     10636601.94      3496682.12     10636403.37
      3496638.72     10636278.58       3496581.9     10636163.62
      3496583.47     10636148.51      3496588.94      10636128.2
      3496575.65     10636087.32       3496559.9      10636068.2
      3496538.94     10636054.24      3496520.19     10636050.08
      3496483.73     10636039.14      3496445.19     10635999.56
      3496340.32     10635915.09      3496290.41     10635889.05
      3496229.64     10635866.26      3496174.31     10635838.05
      3496127.65     10635823.94      3496090.76     10635765.35
      3496075.56     10635726.28      3496057.12     10635690.48
      3495997.44     10635636.22      3495933.42     10635589.57
      3495809.29     10635511.87      3495708.95     10635443.96

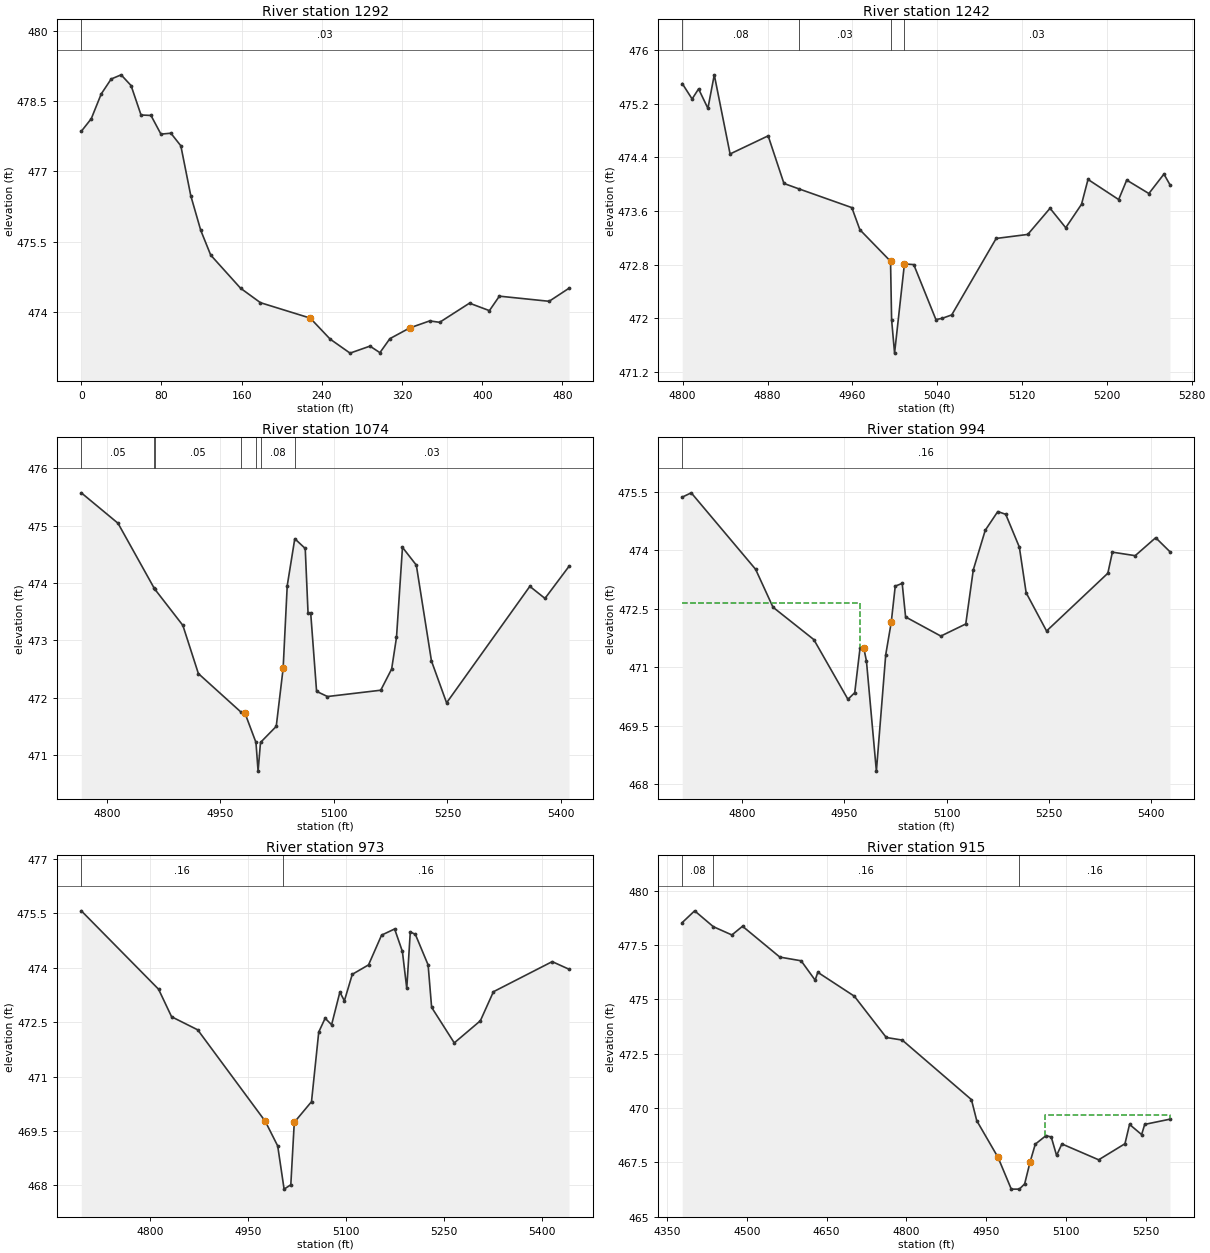
Type RM Length L Ch R = 1 ,1292    ,50,50,50
BEGIN DESCRIPTION:
Mapping XS 7cf6e285
END DESCRIPTION:
XS GIS Cut Line= 2
     3496838.677    10636121.429      3496430.96     10636386.01
#Sta/Elev= 30
       0  477.86    9.93  478.13   19.86  478.66   29.79  478.98   39.72  479.07
   49.65  478.84   59.58  478.21   69.51   478.2   79.44   477.8   89.37  477.82
    99.3  477.55  109.23  476.48  119.16  475.74  129.09  475.21  158.88   474.5
  178.75  474.19   228.4  473.86  248.26  473.41  268.12  473.11  287.98  473.26
  297.91  473.12  307.84  473.42   327.7  473.65  347.56   473.8  357.49  473.77
  387.28  474.18  407.14  474.02  417.07  474.33  466.72  474.22  486.58   474.5
#Mann= 1 ,-1 , 0
       0     .03       0
Bank Sta=228.4,327.7
XS Rating Curve= 0 ,0
Exp/Cntr=0.3,0.1

Type RM Length L Ch R = 1 ,1242    ,168,168,168
BEGIN DESCRIPTION:
Mapping XS 96833870
END DESCRIPTION:
XS GIS Cut Line= 3
      3496771.32     10636099.28      3496435.64     10636330.49
      3496401.18     10636369.82
#Sta/Elev= 30
  4799.6   475.5  4808.9  475.27    4815  475.42  4823.8  475.13  4829.8  475.63
  4844.7  474.45  4880.6  474.72  4895.5  474.01  4909.5  473.93  4959.5  473.65
  4967.1  473.32    4996  472.85    4997  471.98  4999.8  471.48  5009.1  472.81
  5017.9   472.8  5038.8  471.98  5044.9     472  5053.7  472.05  5095.6  473.19
  5125.4  473.25  5146.4  473.64  5161.2  473.35  5176.1   473.7  5182.2  474.07
  5211.1  473.77  5218.7  474.06  5239.6  473.86  5253.8  474.15  5259.5  473.99
#Mann= 4 ,-1 , 0
  4799.6     .08       0  4909.5     .03       0    4996     .03       0
  5009.1     .03       0
Bank Sta=4996,5009.1
XS Rating Curve= 0 ,0
Exp/Cntr=0.3,0.1

Type RM Length L Ch R = 1 ,1074    ,80,80,80
BEGIN DESCRIPTION:
Mapping XS b26b849d
END DESCRIPTION:
XS GIS Cut Line= 6
      3496780.99     10636014.98      3496541.44     10636065.32
      3496487.62     10636087.89      3496388.76     10636167.65
      3496390.42      10636318.6      3496387.82     10636381.92
#Sta/Elev= 30
  4766.2  475.57  4814.7  475.04    4862  473.92  4863.4  473.89  4900.4  473.26
  4920.9  472.42  4977.1  471.75  4982.2  471.74    4997  471.22  4999.8  470.72
    5003  471.22  5023.8   471.5  5032.9  472.51  5038.3  473.95  5048.3  474.77
  5062.1   474.6  5065.8  473.48  5069.3  473.48  5077.1  472.11  5091.5  472.02
  5161.9  472.13  5176.3   472.5  5182.7  473.05  5190.6  474.62  5208.9  474.31
  5228.9  472.64  5248.9  471.91  5358.9  473.94  5378.9  473.73  5410.7  474.29
#Mann= 7 ,-1 , 0
  4766.2     .05       0    4862     .08       0  4863.4     .05       0
  4977.1     .08       0    4997     .07       0    5003     .08       0
  5048.3     .03       0
Bank Sta=4982.2,5032.9
XS Rating Curve= 0 ,0
Exp/Cntr=0.3,0.1

Type RM Length L Ch R = 1 ,994     ,21,21,21
XS GIS Cut Line= 6
      3496762.82     10636011.31      3496498.93     10636020.86
      3496434.69     10636062.52      3496400.84     10636064.26
      3496385.21     10636101.59      3496373.93     10636401.05
#Sta/Elev= 30
  4711.8  475.36    4725  475.47  4819.6  473.51  4845.1  472.54  4905.1  471.71
  4955.2  470.18  4965.2  470.35    4973   471.5  4978.4   471.5  4982.4  471.16
    4997  468.34  5010.7  471.32  5018.8  472.15  5024.7  473.08  5034.9  473.15
  5039.9  472.29  5091.7   471.8  5128.3  472.11  5139.4   473.5  5156.9  474.51
  5175.3  474.99    5187  474.92    5207  474.08    5217  472.91    5247  471.93
    5337  473.41  5343.7  473.95  5377.2  473.86  5407.3  474.32  5428.3  473.96
#Mann= 1 ,-1 , 0
  4711.8     .16       0
#XS Ineff= 2 , 0
         4973.64  472.66
Permanent Ineff=
       F       F
Bank Sta=4978.4,5018.8
XS Rating Curve= 0 ,0
Exp/Cntr=0.3,0.1

Type RM Length L Ch R = 1 ,973     ,58,58,58
BEGIN DESCRIPTION:
Mapping XS 74e32b2d
END DESCRIPTION:
XS GIS Cut Line= 6
      3496767.99     10636004.93      3496508.63     10636004.93
      3496392.52     10636041.83      3496367.57      10636065.7
      3496376.67     10636156.17      3496368.89       10636396.
#Sta/Elev= 30
    4694  475.57  4812.4  473.41  4832.4  472.65  4872.4  472.29 4975.91  469.77
    4995  469.09  5004.8   467.9  5015.1  468.02  5020.4  469.74  5046.8  470.31
  5057.9  472.23  5067.7  472.61  5077.6  472.43  5090.3  473.33  5097.2  473.09
  5109.3  473.82  5134.2  474.08  5154.2   474.9  5174.2  475.07  5186.1  474.45
  5192.8  473.43  5198.2  474.99    5206  474.92  5225.5  474.08  5230.9  472.91
  5265.6  471.93  5305.6  472.54  5325.6  473.34  5415.7  474.17  5441.5  473.96
#Mann= 2 ,-1 , 0
    4694     .16       0    5003     .16       0
#XS Ineff= 2 , 0
         4648.42  469.77
Permanent Ineff=
       F       F
Bank Sta=4975.91,5020.4
XS Rating Curve= 0 ,0
Exp/Cntr=0.3,0.1

Type RM Length L Ch R = 1 ,915     ,155,155,155
BEGIN DESCRIPTION:
Mapping XS bef44ed1
END DESCRIPTION:
XS GIS Cut Line= 3
      3497042.95     10635988.28      3496296.65      10635979.1
      3496210.13      10636125.6
#Sta/Elev= 30
  4378.7  478.53    4402  479.07  4437.1  478.34    4472  477.96    4492  478.36
  4562.1  476.94  4602.1  476.77  4628.4  475.88  4633.4  476.24  4702.1  475.14
  4762.1  473.24  4792.1  473.12  4922.1  470.38  4932.1  469.41  4972.1  467.72
    4997  466.26  5012.1  466.26  5022.1   466.5  5032.1  467.49  5042.1  468.33
  5062.1  468.72  5072.1  468.66  5082.1  467.81  5092.1  468.34  5161.2  467.61
  5210.6  468.35  5219.2  469.24  5241.9  468.77  5247.7  469.24  5295.2  469.48
#Mann= 3 ,-1 , 0
  4378.7     .08       0  4437.1     .16       0  5012.1     .16       0
#XS Ineff= 2 , 0
                         5060.45          469.67
Permanent Ineff=
       F       F
Bank Sta=4972.1,5032.1
XS Rating Curve= 0 ,0
Exp/Cntr=0.3,0.1

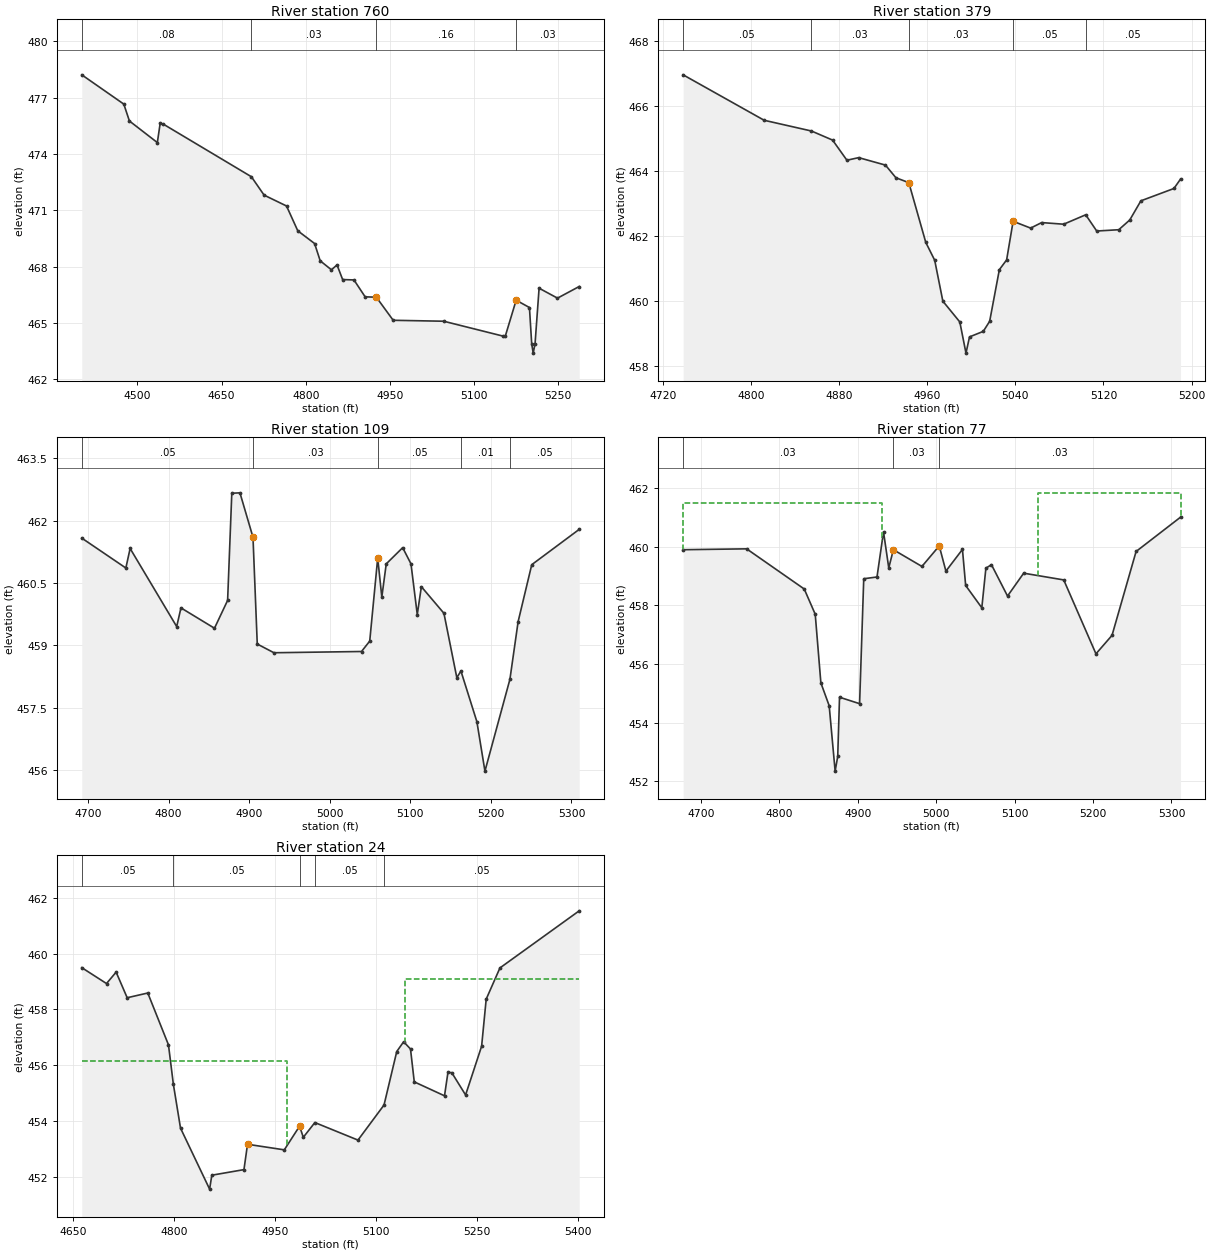
Type RM Length L Ch R = 1 ,760     ,381,381,381
BEGIN DESCRIPTION:
Mapping XS b9582945
END DESCRIPTION:
XS GIS Cut Line= 3
      3496894.45     10635909.28      3496143.85     10635887.26
       3496116.1     10636020.17
#Sta/Elev= 30
  4400.8  478.22  4475.7  476.66  4485.7  475.76  4535.5  474.61  4540.5  475.63
  4545.7   475.6  4703.1  472.79  4725.8  471.81  4765.8  471.23  4785.8  469.91
  4815.8  469.23  4825.8  468.31  4845.8  467.83  4855.8  468.09  4865.8  467.31
    4886  467.29  4905.9  466.39  4925.9  466.37  4955.9  465.14  5045.9  465.09
  5151.3   464.3  5155.8   464.3  5175.1  466.21  5198.8  465.82  5202.8  463.89
  5205.5  463.39  5208.8  463.89    5216  466.85  5248.8  466.32  5287.5  466.94
#Mann= 4 ,-1 , 0
  4400.8     .08       0  4703.1     .03       0  4925.9     .16       0
  5175.1     .03       0
Bank Sta=4925.9,5175.1
XS Rating Curve= 0 ,0
Exp/Cntr=0.3,0.1

Type RM Length L Ch R = 1 ,379     ,270,270,270
BEGIN DESCRIPTION:
Mapping XS e2ef55f8
END DESCRIPTION:
XS GIS Cut Line= 4
      3496258.29     10635675.26      3496095.51     10635612.32
      3495982.67     10635681.76       3495976.2      10635826.2
#Sta/Elev= 30
  4738.4  466.96    4812  465.56  4854.9  465.23  4874.1  464.95  4887.1  464.33
  4897.8  464.41  4922.1  464.18  4931.6  463.79  4943.3  463.64  4958.7   461.8
  4966.8  461.25  4974.2  459.99  4989.6  459.35  4995.2  458.39  4998.4  458.89
  5010.9  459.06  5016.7  459.37  5025.5  460.96  5032.1  461.26    5038  462.45
  5053.9  462.24  5063.9  462.41  5083.9  462.36  5103.9  462.65  5113.9  462.15
  5133.9  462.19  5143.9  462.49    5154  463.08    5184  463.46    5190  463.75
#Mann= 5 ,-1 , 0
  4738.4     .05       0  4854.9     .03       0  4943.3     .03       0
    5038     .05       0  5103.9     .05       0
Bank Sta=4943.3,5038
XS Rating Curve= 0 ,0
Exp/Cntr=0.3,0.1

Type RM Length L Ch R = 1 ,109     ,32,32,32
BEGIN DESCRIPTION:
Mapping XS 430a4e94
END DESCRIPTION:
XS GIS Cut Line= 4
      3496075.76      10635387.6      3495819.71     10635473.31
      3495786.07     10635525.39      3495846.83     10635804.24
#Sta/Elev= 30
  4692.2  461.58  4746.9  460.86  4752.2  461.33    4810  459.45  4815.3   459.9
  4856.9  459.41  4873.2  460.08  4878.4  462.66  4888.5  462.67  4904.7   461.6
    4910  459.03  4930.7  458.82  5039.4  458.85  5049.6   459.1  5059.5   461.1
  5064.6  460.16  5070.1  460.96  5090.5  461.35  5100.8  460.96  5108.6  459.74
  5113.7  460.41  5141.7  459.77  5157.7  458.22  5162.8  458.38  5182.6  457.16
  5192.6  455.97  5223.6  458.18  5233.8  459.57  5250.7  460.94  5309.6  461.79
#Mann= 5 ,-1 , 0
  4692.2     .05       0  4904.7     .03       0  5059.5     .05       0
  5162.8     .01       0  5223.6     .05       0
Bank Sta=4904.7,5059.5
XS Rating Curve= 0 ,0
Exp/Cntr=0.3,0.1

Type RM Length L Ch R = 1 ,77      ,53,53,53
BEGIN DESCRIPTION:
Mapping XS f419fd96
END DESCRIPTION:
XS GIS Cut Line= 4
      3496045.37     10635339.86      3495814.28     10635421.22
      3495750.27     10635522.14      3495809.87     10635785.47
#Sta/Elev= 30
  4677.1   459.9  4758.1  459.93  4831.6  458.56  4845.6   457.7  4852.8  455.36
  4863.4  454.58    4871  452.35  4874.3  452.85  4876.6  454.87  4902.2  454.65
  4907.5  458.91  4924.4  458.97  4932.7  460.51  4939.4  459.28  4945.3   459.9
  4981.7  459.33  5003.8  460.03  5012.3  459.17  5033.4  459.91  5037.5  458.68
  5058.1  457.92  5063.3  459.27  5070.4  459.39  5090.9  458.32  5111.5   459.1
  5162.6  458.87  5203.7  456.35  5224.2  456.98  5254.9  459.84  5311.6  461.01
#Mann= 3 , 0 , 0
  4677.1     .03       0  4945.3     .03       0  5003.8     .03       0
#XS Ineff= 2 , 0
         4931.07  461.48 5129.17          461.84
Permanent Ineff=
       F       F
Bank Sta=4945.3,5003.8
XS Rating Curve= 0 ,0
Exp/Cntr=0.3,0.1

Type RM Length L Ch R = 1 ,24      ,0,0,0
BEGIN DESCRIPTION:
UNT401 IN CCTC 2.0
END DESCRIPTION:
XS GIS Cut Line= 4
      3496017.56     10635312.19      3495752.78     10635407.68
      3495697.44     10635523.79      3495764.58     10635845.37
#Sta/Elev= 30
  4663.3   459.5    4700  458.93  4714.3  459.34  4730.7  458.42  4761.3  458.59
    4792  456.73  4799.3  455.31  4809.9  453.74  4853.1  451.55  4856.4  452.05
  4904.1  452.25  4909.4  453.16    4964  452.96  4986.7  453.81  4992.2  453.41
  5009.4  453.94  5073.4  453.31  5112.1  454.57    5131  456.49  5141.2  456.84
  5151.4  456.58    5157   455.4  5201.9   454.9    5207  455.74  5212.7  455.73
  5233.2  454.93    5257  456.68  5263.8  458.37  5284.2  459.49  5401.9  461.54
#Mann= 5 ,-1 , 0
  4663.3     .05       0  4799.3     .05       0  4986.7     .03       0
  5009.4     .05       0  5112.1     .05       0
#XS Ineff= 2 , 0
         4968.08  456.16 5143.46          459.11
Permanent Ineff=
       F       F
Bank Sta=4909.4,4986.7
XS Rating Curve= 0 ,0
Exp/Cntr=0.3,0.1

Chan Stop Cuts=-1
Use User Specified Reach Order=0
Composite Channel Slope=5