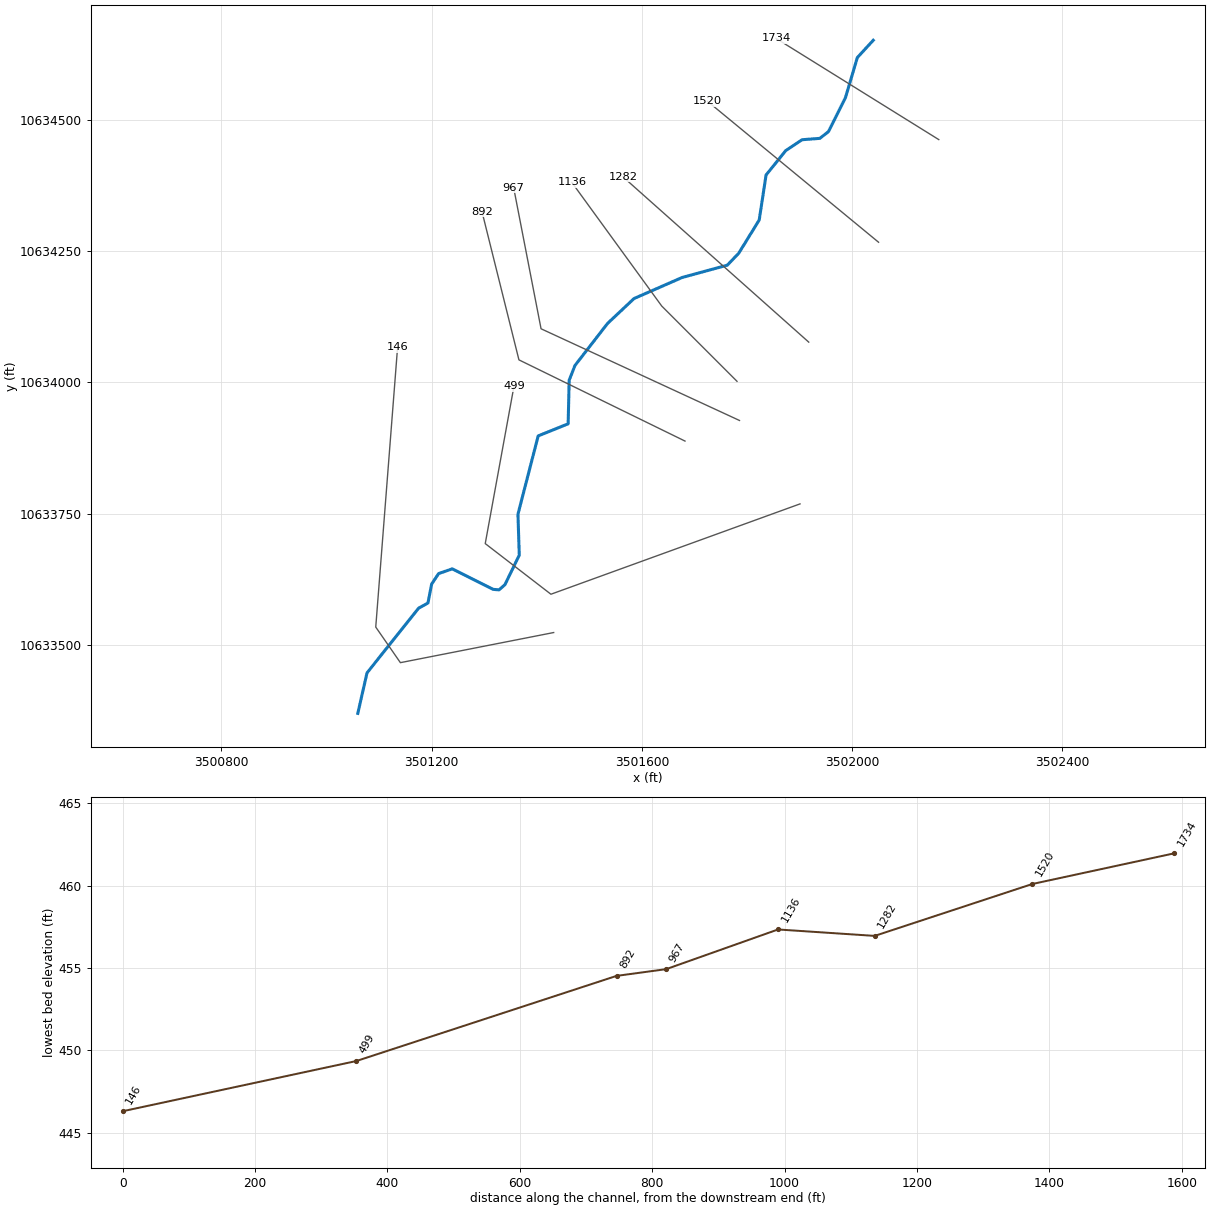
--- UNT402 IN CCTC.prj (project) ---

Proj Title=UNT402 IN CCTC Base Level Engineering
Current Plan=p01
Default Exp/Contr=0.3,0.1
English Units
Geom File=g01
Flow File=f01
Plan File=p01
Y Axis Title=Elevation
X Axis Title(PF)=Main Channel Distance
X Axis Title(XS)=Station
BEGIN DESCRIPTION:
UNT402 IN CCTC
END DESCRIPTION:
DSS Export Rating Curves= 0
DSS Export Rating Curve Sorted= 0
DSS Export Volume Flow Curves= 0
DXF OffsetX= 0
DXF OffsetY= 0
DXF ScaleX= 1
DXF ScaleY= 10

--- UNT402 IN CCTC.p01 (plan) ---

Plan Title=Multiple Run
Short Identifier=Multiple
Geom File=g01
Flow File=f01
Subcritical Flow
K Sum by GR= 0
Std Step Tol= 0.01
Critical Tol= 0.01
Num of Std Step Trials= 20
Max Error Tol= 0.3
Flow Tol Ratio= 0.001
Split Flow NTrial= 30
Split Flow Tol= 0.02
Split Flow Ratio= 0.02
Log Output Level= 0
Friction Slope Method= 1
Unsteady Friction Slope Method= 2
Unsteady Bridges Friction Slope Method= 1
Parabolic Critical Depth
Global Vel Dist=  1 , 1 , 1
Global Log Level= 0
CheckData=True
Encroach Param= -1, 0, 0, 0
BEGIN DESCRIPTION:
Multiple Run
END DESCRIPTION:

--- UNT402 IN CCTC.f01 (steady flow) ---

Flow Title=Multiple
Number of Profiles=7
Profile Names=10-year,25-year,50-year,1pct_min,100-year,1pct_plu,500-year
River Rch & RM= UNT402 IN CCTC,Reach-1,1734
     211     255     287     238     321     434     398
Boundary for River Rch & Prof#=UNT402 IN CCTC,Reach-1,1
Up Type=0
Dn Type=3
Dn Slope=0.005
Boundary for River Rch & Prof#=UNT402 IN CCTC,Reach-1,2
Up Type=0
Dn Type=3
Dn Slope=0.005
Boundary for River Rch & Prof#=UNT402 IN CCTC,Reach-1,3
Up Type=0
Dn Type=3
Dn Slope=0.005
Boundary for River Rch & Prof#=UNT402 IN CCTC,Reach-1,4
Up Type=0
Dn Type=3
Dn Slope=0.005
Boundary for River Rch & Prof#=UNT402 IN CCTC,Reach-1,5
Up Type=0
Dn Type=3
Dn Slope=0.005
Boundary for River Rch & Prof#=UNT402 IN CCTC,Reach-1,6
Up Type=0
Dn Type=3
Dn Slope=0.005
Boundary for River Rch & Prof#=UNT402 IN CCTC,Reach-1,7
Up Type=0
Dn Type=3
Dn Slope=0.005

--- UNT402 IN CCTC.g01 (geometry) ---

Geom Title=Existing Conditions
Program Version=4.10

River Reach=UNT402 IN CCTC  ,Reach-1
Reach XY= 30
      3502040.34     10634650.82      3502010.01      10634617.9
      3501987.39     10634541.44      3501955.27     10634477.21
      3501938.78     10634464.19      3501904.93     10634461.58
      3501873.68     10634440.75      3501836.37     10634394.43
      3501823.33      10634308.8      3501784.27     10634245.44
      3501762.57     10634222.87      3501676.63     10634199.43
      3501585.18      10634159.4      3501534.75       10634112.
      3501472.75       10634032.      3501461.75       10634004.
      3501459.75       10633921.      3501402.75       10633898.
      3501364.25       10633749.      3501366.75       10633671.
       3501339.5       10633615.      3501328.25       10633605.
        3501317.       10633606.      3501239.25       10633645.
      3501213.25       10633636.        3501200.       10633616.
        3501193.       10633580.        3501175.       10633570.
        3501077.       10633447.       3501059.5       10633370.

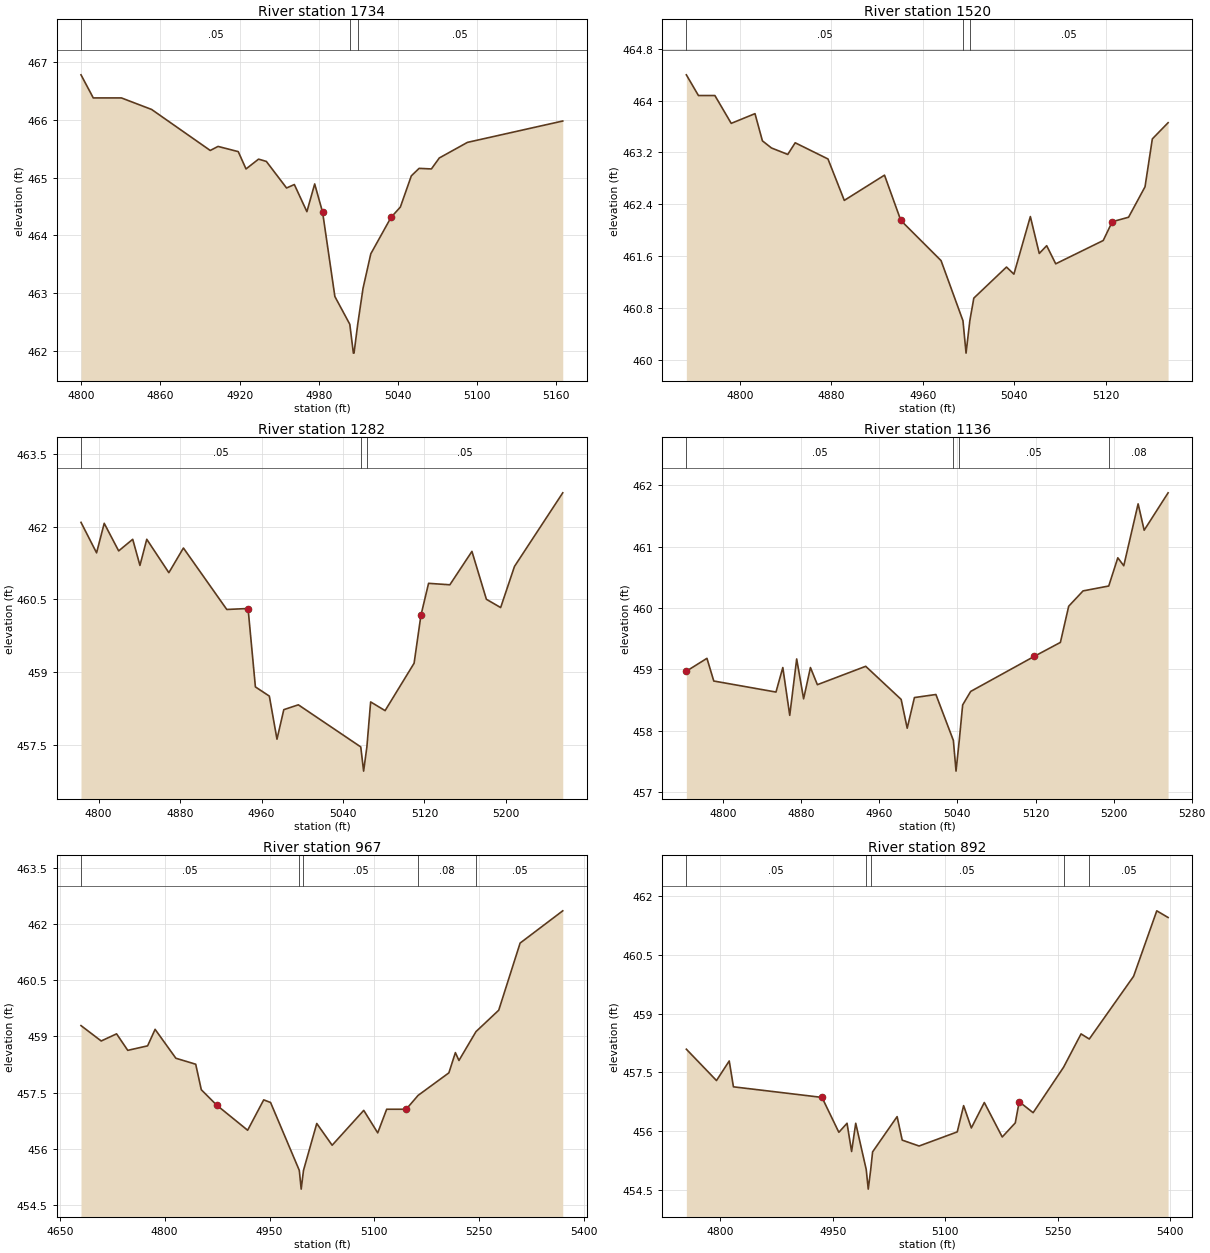
Type RM Length L Ch R = 1 ,1734    ,214,214,214
BEGIN DESCRIPTION:
UNT402 IN CCTC 2.0
END DESCRIPTION:
XS GIS Cut Line= 2
      3502165.02     10634461.82      3501855.15     10634654.51
#Sta/Elev= 30
  4799.9  466.78  4809.2  466.38  4830.5  466.38  4853.4  466.18  4897.8  465.47
  4903.7  465.54    4919  465.45  4924.9  465.15  4934.4  465.32  4940.3  465.28
  4955.6  464.82  4961.5  464.88    4971  464.41  4976.9  464.89  4982.9   464.4
  4992.2  462.94  5003.5  462.46  5006.2  461.96  5006.7  461.96  5009.5  462.46
  5013.5  463.08  5019.4  463.68  5034.7  464.31  5041.8  464.49  5050.1  465.03
    5056  465.16  5065.3  465.15  5071.3  465.34  5092.6  465.61  5164.8  465.98
#Mann= 3 ,-1 , 0
  4799.9     .05       0  5003.5     .03       0  5009.5     .05       0
Bank Sta=4982.9,5034.7
XS Rating Curve= 0 ,0
Exp/Cntr=0.3,0.1

Type RM Length L Ch R = 1 ,1520    ,238,238,238
BEGIN DESCRIPTION:
Mapping XS b29417f9
END DESCRIPTION:
XS GIS Cut Line= 2
      3502050.45     10634266.49      3501724.93     10634534.72
#Sta/Elev= 30
    4753   464.4  4763.6  464.08    4778  464.08  4792.3  463.65  4813.1   463.8
  4819.6  463.38  4827.5  463.27  4841.8  463.17  4848.3  463.35    4877   463.1
  4891.3  462.46  4926.5  462.85  4940.8  462.15    4976  461.53  4995.2   460.6
  4997.9   460.1  5001.2   460.6  5004.7  460.95  5033.3  461.43  5039.8  461.32
  5054.2  462.21    5062  461.64  5068.5  461.76  5076.4  461.48    5118  461.84
  5125.9  462.13  5140.2   462.2  5154.6  462.67    5161  463.41  5174.8  463.66
#Mann= 3 ,-1 , 0
    4753     .05       0  4995.2     .03       0  5001.2     .05       0
Bank Sta=4940.8,5125.9
XS Rating Curve= 0 ,0
Exp/Cntr=0.3,0.1

Type RM Length L Ch R = 1 ,1282    ,146,146,146
BEGIN DESCRIPTION:
Mapping XS efda7b8d
END DESCRIPTION:
XS GIS Cut Line= 2
      3501917.59     10634076.43      3501564.06     10634390.97
#Sta/Elev= 30
  4782.7  462.09    4798  461.46  4805.5  462.07  4819.7   461.5  4833.5  461.74
  4840.6   461.2  4847.3  461.74    4869  461.05  4883.3  461.56  4925.9  460.29
  4946.8  460.31    4954  458.69  4967.7   458.5  4975.2  457.61  4981.9  458.22
  4996.2  458.32  5057.5  457.45  5060.3  456.95  5063.5  457.45  5067.2  458.38
  5081.4   458.2  5109.9  459.18  5116.6  460.17  5124.1  460.83    5145   460.8
  5166.7  461.49  5180.9   460.5  5194.9  460.33  5208.5  461.18  5255.9   462.7
#Mann= 3 ,-1 , 0
  4782.7     .05       0  5057.5     .03       0  5063.5     .05       0
Bank Sta=4946.8,5116.6
XS Rating Curve= 0 ,0
Exp/Cntr=0.3,0.1

Type RM Length L Ch R = 1 ,1136    ,169,169,169
BEGIN DESCRIPTION:
Mapping XS 21e0b350
END DESCRIPTION:
XS GIS Cut Line= 3
      3501781.07     10634001.86      3501637.81     10634145.12
      3501466.82     10634380.33
#Sta/Elev= 30
  4762.4  458.97  4783.5  459.18  4790.5  458.81  4854.2  458.63  4861.2  459.03
  4868.3  458.25  4875.4  459.17  4882.5  458.52  4889.5  459.03  4896.6  458.75
  4946.1  459.05  4982.4  458.51  4988.6  458.04    4996  458.54    5018  458.59
  5035.9  457.84  5038.6  457.34  5041.9  457.84  5045.4  458.42  5053.6  458.64
  5118.5  459.21  5145.5  459.44    5154  460.03  5168.7  460.28    5195  460.36
  5204.3  460.82  5210.4  460.69  5225.1   461.7  5231.3  461.27  5255.8  461.88
#Mann= 4 ,-1 , 0
  4762.4     .05       0  5035.9     .03       0  5041.9     .05       0
    5195     .08       0
Bank Sta=4762.4,5118.5
XS Rating Curve= 0 ,0
Exp/Cntr=0.3,0.1

Type RM Length L Ch R = 1 ,967     ,75,75,75
BEGIN DESCRIPTION:
Mapping XS 288b0aab
END DESCRIPTION:
XS GIS Cut Line= 3
       3501785.8     10633927.36       3501408.2     10634101.84
      3501356.11     10634370.07
#Sta/Elev= 30
  4680.3  459.29  4709.2  458.88  4731.2  459.07  4747.2  458.63  4775.6  458.75
  4786.3  459.19    4816  458.42  4844.4  458.26  4852.4  457.58  4874.4  457.17
  4918.7   456.5  4941.7  457.31  4951.5  457.24  4992.6  455.43  4995.3  454.93
  4998.6  455.43  5017.6  456.68  5039.6   456.1  5084.8  457.03  5104.8  456.43
  5117.6  457.06  5145.5  457.06  5162.6  457.43  5206.6  458.03  5215.9  458.57
    5221  458.36  5245.4  459.13  5277.9   459.7  5308.5  461.49  5369.5  462.35
#Mann= 5 ,-1 , 0
  4680.3     .05       0  4992.6    .035       0  4998.6     .05       0
  5162.6     .08       0  5245.4     .05       0
Bank Sta=4874.4,5145.5
XS Rating Curve= 0 ,0
Exp/Cntr=0.3,0.1

Type RM Length L Ch R = 1 ,892     ,393,393,393
BEGIN DESCRIPTION:
Mapping XS 1a96829c
END DESCRIPTION:
XS GIS Cut Line= 3
       3501682.1     10633888.16       3501366.1     10634042.69
      3501295.79      10634324.8
#Sta/Elev= 30
  4754.5  458.09  4794.7  457.29  4811.7  457.79  4817.3  457.13  4935.4  456.86
  4957.9  455.97  4968.8   456.2  4974.9  455.48  4980.4   456.2  4994.4  455.02
  4997.1  454.52  5000.4  455.02  5002.9  455.47  5035.6  456.37  5042.4  455.77
  5064.9  455.62  5115.8  455.98  5124.3  456.65  5134.6  456.08  5151.9  456.73
  5175.8  455.85  5193.2  456.21  5198.4  456.75    5217  456.47  5257.6  457.63
  5280.9  458.48  5291.9  458.35    5351  459.95  5381.9  461.62    5397  461.45
#Mann= 5 ,-1 , 0
  4754.5     .05       0  4994.4    .035       0  5000.4     .05       0
  5257.6     .08       0  5291.9     .05       0
Bank Sta=4935.4,5198.4
XS Rating Curve= 0 ,0
Exp/Cntr=0.3,0.1

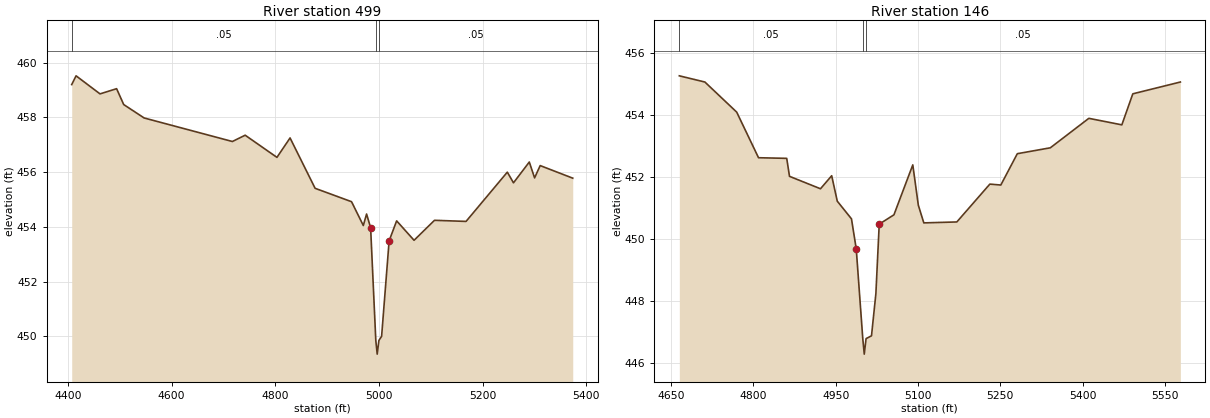
Type RM Length L Ch R = 1 ,499     ,353,353,353
BEGIN DESCRIPTION:
Mapping XS cae24ec7
END DESCRIPTION:
XS GIS Cut Line= 4
      3501900.98     10633768.61      3501426.99     10633596.72
      3501301.99     10633693.08      3501356.68     10633992.59
#Sta/Elev= 30
  4407.3   459.2  4415.7  459.52  4461.9  458.86  4493.9  459.05  4507.6  458.47
    4547  457.98  4717.2  457.12  4741.9  457.35  4803.2  456.54  4828.5  457.25
  4876.8  455.41  4947.1  454.92  4969.8  454.05  4976.1  454.47  4983.9  453.97
  4993.9  449.85  4996.6  449.35  4999.9  449.85  5005.1     450  5019.6  453.49
  5034.1  454.22  5067.7  453.51  5107.1  454.24    5168   454.2  5247.6     456
  5259.5  455.61    5290  456.37  5300.2  455.79    5311  456.24  5373.8  455.78
#Mann= 3 ,-1 , 0
  4407.3     .05       0  4993.9    .035       0  4999.9     .05       0
Bank Sta=4983.9,5019.6
XS Rating Curve= 0 ,0
Exp/Cntr=0.3,0.1

Type RM Length L Ch R = 1 ,146     ,0,0,0
BEGIN DESCRIPTION:
UNT402 IN CCTC 1.0
END DESCRIPTION:
XS GIS Cut Line= 4
      3501432.22     10633523.81      3501140.53     10633466.51
      3501093.65     10633534.22       3501135.2     10634066.59
#Sta/Elev= 30
  4664.8  455.27  4711.4  455.07  4769.4   454.1  4809.2  452.63  4860.6  452.61
  4865.7  452.03  4922.2  451.63  4942.6  452.05  4952.8  451.23  4978.7  450.66
  4987.4  449.69  4999.3   446.8    5002   446.3  5005.3   446.8  5015.2  446.89
  5023.2  448.25  5029.3  450.49  5056.1  450.79  5090.5   452.4  5100.6   451.1
  5110.6  450.53  5170.8  450.56    5231  451.78    5251  451.75  5281.1  452.76
  5341.3  452.95  5411.5   453.9  5471.7  453.69  5491.7  454.69  5578.4  455.07
#Mann= 3 ,-1 , 0
  4664.8     .05       0  4999.3    .035       0  5005.3     .05       0
Bank Sta=4987.4,5029.3
XS Rating Curve= 0 ,0
Exp/Cntr=0.3,0.1

Chan Stop Cuts=-1
Use User Specified Reach Order=0
Composite Channel Slope=5