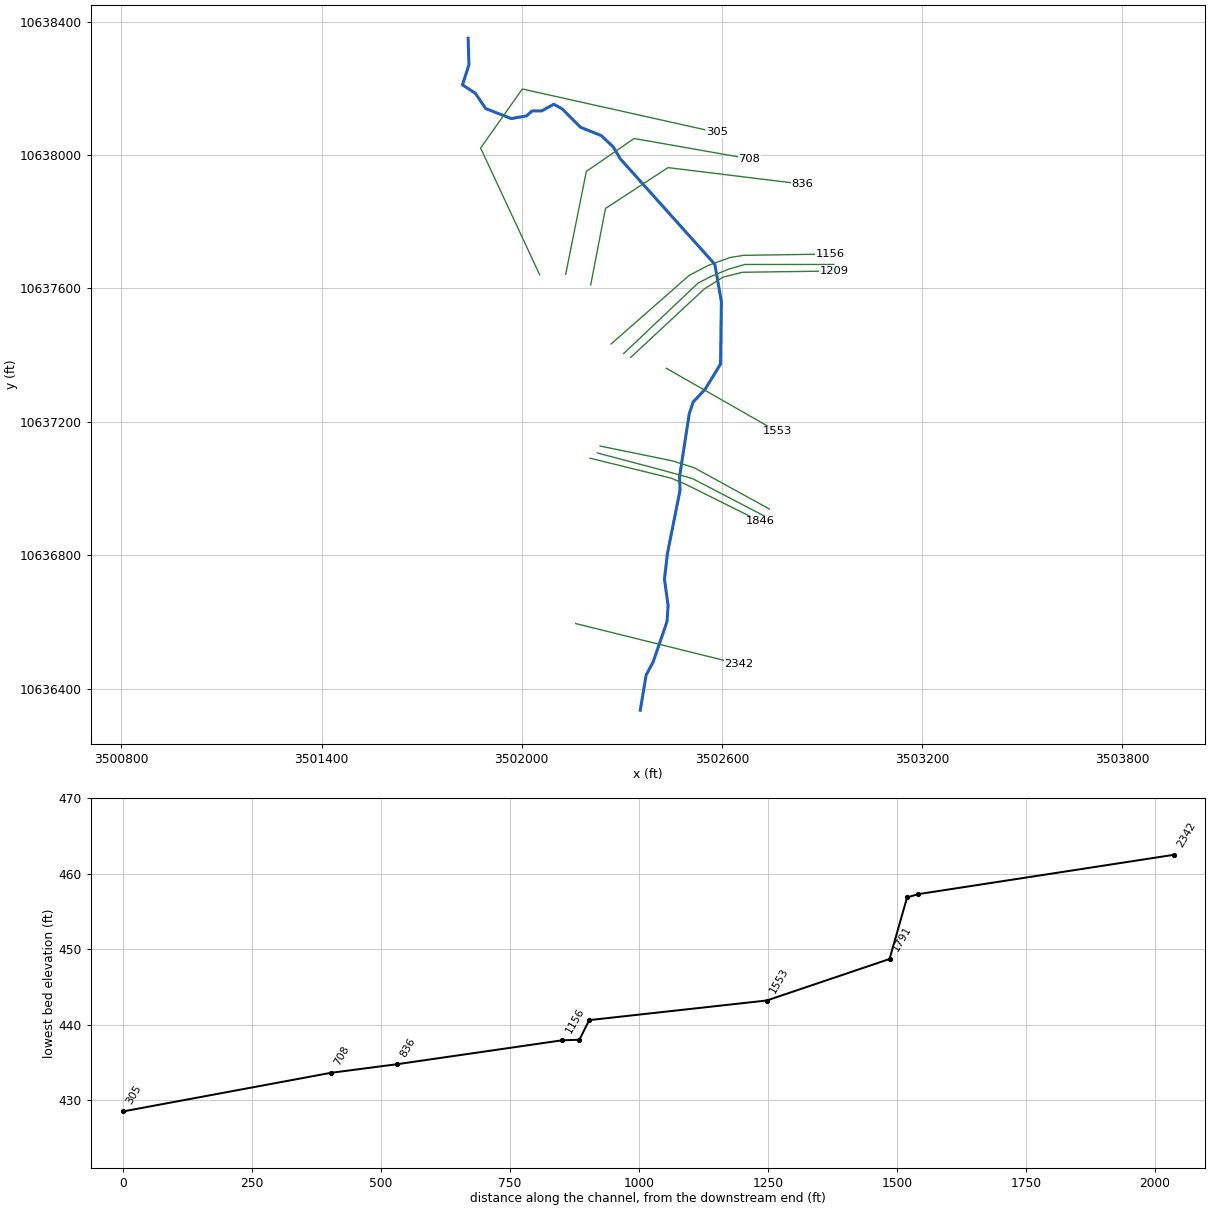
--- UNT403 IN CCTC.prj (project) ---

Proj Title=UNT403 IN CCTC Base Level Engineering
Current Plan=p01
Default Exp/Contr=0.3,0.1
English Units
Geom File=g01
Flow File=f01
Plan File=p01
Y Axis Title=Elevation
X Axis Title(PF)=Main Channel Distance
X Axis Title(XS)=Station
BEGIN DESCRIPTION:
UNT403 IN CCTC
END DESCRIPTION:
DSS Export Rating Curves= 0
DSS Export Rating Curve Sorted= 0
DSS Export Volume Flow Curves= 0
DXF OffsetX= 0
DXF OffsetY= 0
DXF ScaleX= 1
DXF ScaleY= 10

--- UNT403 IN CCTC.p01 (plan) ---

Plan Title=Multiple Run
Short Identifier=Multiple
Geom File=g01
Flow File=f01
Subcritical Flow
K Sum by GR= 0
Std Step Tol= 0.01
Critical Tol= 0.01
Num of Std Step Trials= 20
Max Error Tol= 0.3
Flow Tol Ratio= 0.001
Split Flow NTrial= 30
Split Flow Tol= 0.02
Split Flow Ratio= 0.02
Log Output Level= 0
Friction Slope Method= 1
Unsteady Friction Slope Method= 2
Unsteady Bridges Friction Slope Method= 1
Parabolic Critical Depth
Global Vel Dist=  1 , 1 , 1
Global Log Level= 0
CheckData=True
Encroach Param= -1, 0, 0, 0
BEGIN DESCRIPTION:
Multiple Run
END DESCRIPTION:

--- UNT403 IN CCTC.f01 (steady flow) ---

Flow Title=Multiple
Program Version=4.10
Number of Profiles= 7
Profile Names=10-year,25-year,50-year,1pct_min,100-year,1pct_plu,500-year
River Rch & RM=UNT403 IN CCTC,Reach-1         ,2342
     221     270     306     255     345     467     436
Boundary for River Rch & Prof#=UNT403 IN CCTC,Reach-1         , 1
Up Type= 0
Dn Type= 3
Dn Slope=0.0019
Boundary for River Rch & Prof#=UNT403 IN CCTC,Reach-1         , 2
Up Type= 0
Dn Type= 3
Dn Slope=0.0019
Boundary for River Rch & Prof#=UNT403 IN CCTC,Reach-1         , 3
Up Type= 0
Dn Type= 3
Dn Slope=0.0019
Boundary for River Rch & Prof#=UNT403 IN CCTC,Reach-1         , 4
Up Type= 0
Dn Type= 3
Dn Slope=0.0019
Boundary for River Rch & Prof#=UNT403 IN CCTC,Reach-1         , 5
Up Type= 0
Dn Type= 3
Dn Slope=0.0019
Boundary for River Rch & Prof#=UNT403 IN CCTC,Reach-1         , 6
Up Type= 0
Dn Type= 3
Dn Slope=0.0019
Boundary for River Rch & Prof#=UNT403 IN CCTC,Reach-1         , 7
Up Type= 0
Dn Type= 3
Dn Slope=0.0019
DSS Import GetInterval= 0
DSS Import GetPeak= 0
DSS Import FillOption= 0

--- UNT403 IN CCTC.g01 (geometry) ---

Geom Title=Existing Conditions
Program Version=4.10

River Reach=UNT403 IN CCTC  ,Reach-1
Reach XY= 30
      3502355.27     10636335.15      3502373.01     10636440.49
      3502394.33     10636480.55      3502435.56       10636601.
      3502438.82     10636648.74      3502427.97     10636727.95
      3502436.65      10636803.9      3502474.62     10636994.88
      3502473.08      10637034.7      3502502.25       10637224.
      3502513.75       10637259.      3502550.25       10637298.
        3502596.       10637373.       3502598.5       10637560.
        3502579.       10637672.      3502295.75       10637988.
      3502274.25       10638024.       3502238.5       10638058.
        3502176.       10638083.      3502121.25       10638138.
      3502096.25       10638152.      3502059.75       10638132.
        3502031.       10638132.       3502014.5       10638117.
       3501968.5       10638109.        3501892.       10638139.
      3501860.75       10638185.      3501822.25       10638210.
      3501841.75       10638270.      3501839.25       10638350.

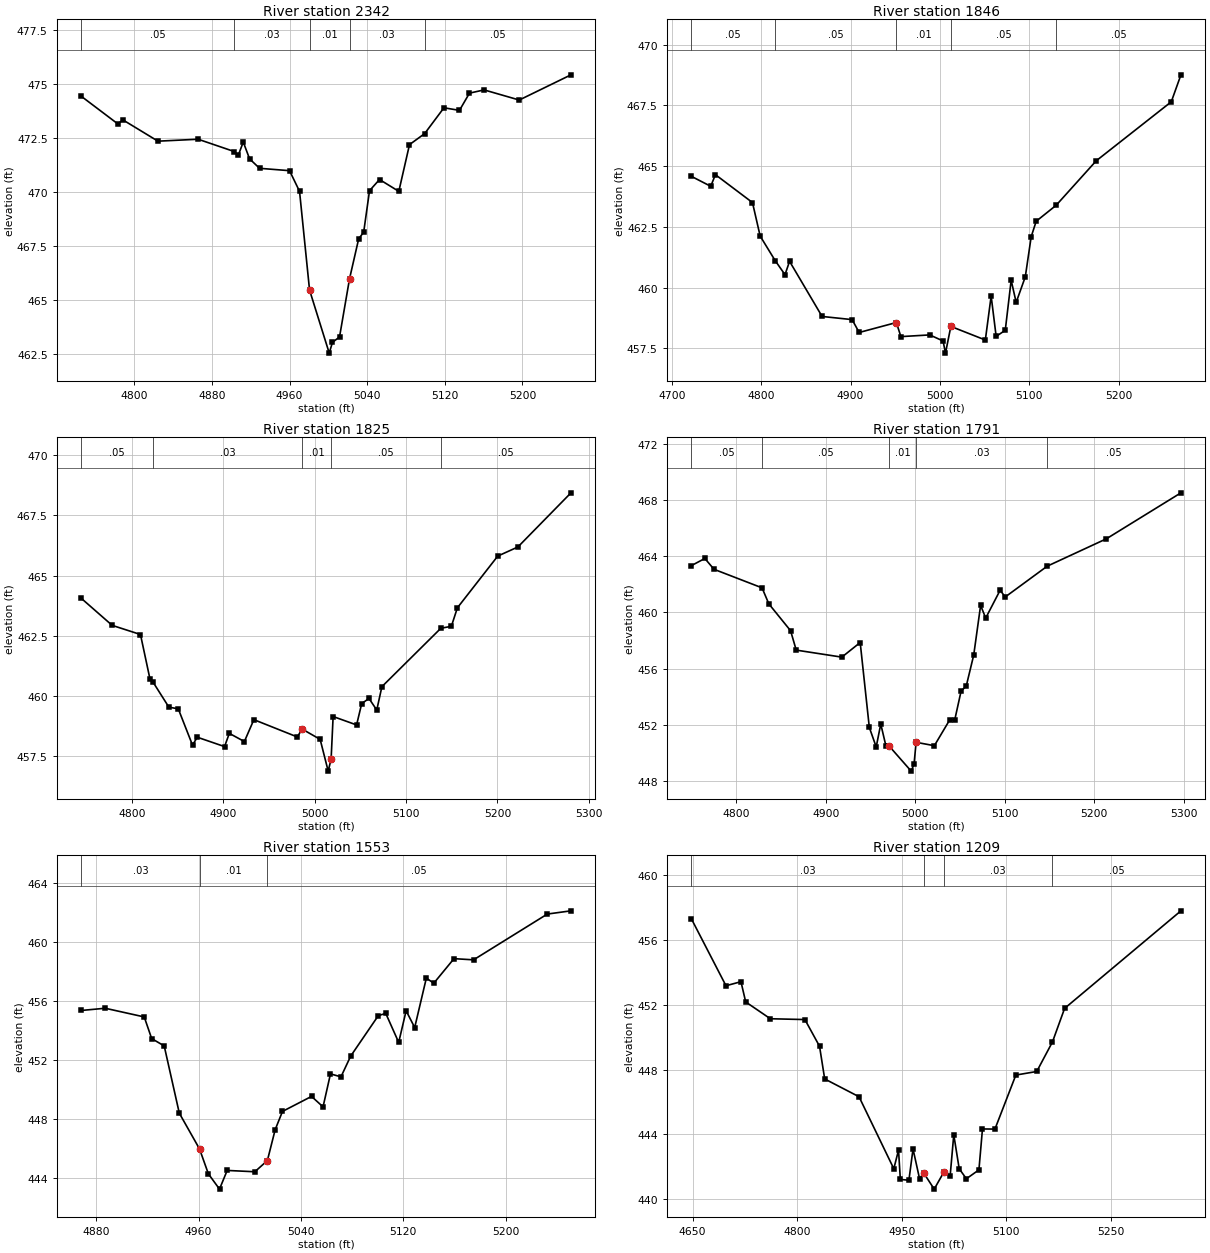
Type RM Length L Ch R = 1 ,2342    ,496,496,496
BEGIN DESCRIPTION:
UNT403 IN CCTC 4.0
END DESCRIPTION:
XS GIS Cut Line= 2
      3502161.44     10636595.06      3502651.08     10636473.52
#Sta/Elev= 30
  4745.5  474.44  4783.1  473.16  4788.2  473.35  4824.4  472.36  4865.8  472.45
  4902.9  471.88  4907.2  471.71  4912.3  472.32  4918.8  471.54  4929.1   471.1
    4960  470.99  4970.3  470.03  4980.6  465.45  5000.9  462.52  5004.2  463.02
  5011.5  463.27  5021.8  465.97  5031.2  467.82  5036.4  468.14  5042.4  470.06
  5052.7  470.58  5072.6  470.03  5083.6   472.2  5099.2  472.71  5119.1  473.91
  5135.1  473.79  5145.4  474.59  5160.5  474.74  5196.7  474.27    5250  475.44
#Mann= 5 ,-1 , 0
  4745.5     .05       0  4902.9     .03       0  4980.6     .01       0
  5021.8     .03       0  5099.2     .05       0
Bank Sta=4980.6,5021.8
XS Rating Curve= 0 ,0
Exp/Cntr=0.3,0.1

Type RM Length L Ch R = 1 ,1846    ,21,21,21
BEGIN DESCRIPTION:
Mapping XS bbbc0c63
END DESCRIPTION:
XS GIS Cut Line= 4
      3502204.89     10637090.71      3502448.35     10637030.82
      3502491.32     10637012.59      3502715.63     10636901.08
#Sta/Elev= 30
  4721.8  464.58  4743.5  464.17  4748.7  464.65  4790.2   463.5  4798.8  462.12
  4815.6  461.11  4826.6  460.53  4831.7  461.08  4868.1  458.81  4901.7  458.68
  4909.6  458.15  4951.2  458.56  4956.3  457.98  4988.6  458.05  5003.5   457.8
  5006.2   457.3  5012.2   458.4  5050.8  457.84  5057.3  459.65  5062.9  457.99
  5073.1  458.24  5079.7   460.3  5085.3  459.39  5095.5  460.44  5102.1  462.09
  5107.7  462.73  5130.1  463.39  5174.9  465.22  5258.9  467.65  5269.7  468.76
#Mann= 5 ,-1 , 0
  4721.8     .05       0  4815.6     .05       0  4951.2     .01       0
  5012.2     .05       0  5130.1     .05       0
Bank Sta=4951.2,5012.2
XS Rating Curve= 0 ,0
Exp/Cntr=0.3,0.1

Type RM Length L Ch R = 1 ,1825    ,34,34,34
BEGIN DESCRIPTION:
Mapping XS b0923646
END DESCRIPTION:
XS GIS Cut Line= 4
      3502227.03     10637106.33      3502428.82     10637052.96
      3502512.15     10637029.52      3502725.78     10636918.18
#Sta/Elev= 30
  4744.4  464.05  4778.1  462.93  4809.1  462.55  4819.5   460.7  4822.7  460.58
  4840.2  459.53  4850.5  459.46  4866.1  457.95  4871.3  458.28  4901.2  457.89
  4906.4  458.44  4922.9   458.1  4933.3  459.01  4980.9  458.29  4986.1  458.62
  5005.9  458.19  5014.7  456.87  5017.9  457.37  5020.1  459.14  5045.8  458.79
  5051.4  459.68  5059.4  459.89  5067.9  459.41  5073.5  460.38  5138.1  462.81
  5149.6  462.89  5156.2  463.66  5200.4  465.81  5222.5  466.19  5280.6  468.44
#Mann= 5 ,-1 , 0
  4744.4     .05       0  4822.7     .03       0  4986.1     .01       0
  5017.9     .05       0  5138.1     .05       0
Bank Sta=4986.1,5017.9
XS Rating Curve= 0 ,0
Exp/Cntr=0.3,0.1

Type RM Length L Ch R = 1 ,1791    ,238,238,238
BEGIN DESCRIPTION:
Mapping XS 89a4c63b
END DESCRIPTION:
XS GIS Cut Line= 4
      3502234.79     10637127.18      3502450.95     10637082.91
      3502517.36     10637062.07      3502742.58     10636938.39
#Sta/Elev= 30
  4749.8  463.33  4764.9  463.84  4775.1  463.07  4828.8  461.75  4836.4  460.61
  4860.7   458.7    4867  457.32    4918  456.82  4938.5  457.86  4948.7  451.82
  4956.4  450.43  4961.5  452.06  4967.2  450.52  4970.5  450.52  4995.5  448.71
  4998.7  449.21    5001  450.76  5021.4  450.52  5038.6  452.36  5044.2  452.36
  5051.3  454.41    5057  454.75  5065.4  456.97  5073.1   460.5  5078.8   459.6
  5094.9  461.58  5100.6   461.1  5147.5  463.29  5213.7  465.24    5297  468.51
#Mann= 5 ,-1 , 0
  4749.8     .05       0  4828.8     .05       0  4970.5     .01       0
    5001     .03       0  5147.5     .05       0
Bank Sta=4970.5,5001
XS Rating Curve= 0 ,0
Exp/Cntr=0.3,0.1

Type RM Length L Ch R = 1 ,1553    ,344,344,344
BEGIN DESCRIPTION:
UNT403 IN CCTC 3.0
END DESCRIPTION:
XS GIS Cut Line= 2
      3502433.41     10637360.36      3502765.67     10637170.86
#Sta/Elev= 30
  4868.5  455.35  4887.1   455.5  4917.6  454.91  4923.4  453.44  4933.2  452.94
    4945  448.37  4960.8  445.94  4967.7  444.25  4976.4  443.21  4982.4  444.48
    5004  444.39  5013.8  445.15  5019.9  447.25  5025.6  448.49  5048.3  449.51
  5057.3   448.8  5063.1  451.04  5071.3  450.84  5078.9  452.25  5100.5     455
  5106.3  455.15  5116.4  453.18  5122.2  455.33  5128.9  454.19    5138  457.55
  5143.8   457.2  5159.6  458.87  5174.9  458.79  5232.5   461.9    5251  462.12
#Mann= 3 , 0 , 0
  4868.5     .03       0  4960.8     .01       0  5013.8     .05       0
Bank Sta=4960.8,5013.8
XS Rating Curve= 0 ,0
Exp/Cntr=0.3,0.1

Type RM Length L Ch R = 1 ,1209    ,19,19,19
BEGIN DESCRIPTION:
UNT403 IN CCTC 2.0
END DESCRIPTION:
XS GIS Cut Line= 5
      3502326.57      10637392.9      3502547.96     10637598.66
      3502603.95     10637633.82      3502661.24     10637648.14
       3502936.6     10637652.02
#Sta/Elev= 30
  4648.1  457.32  4697.8  453.18  4719.3  453.43  4726.1  452.18  4761.5  451.14
  4811.1  451.09  4832.1  449.44  4839.5  447.42  4888.8  446.32  4938.7  441.87
  4945.5  443.02  4948.1  441.21  4960.4  441.16  4966.3  443.09  4975.7  441.25
  4981.6  441.61  4996.7  440.61  5010.9  441.69  5019.6  441.43  5024.8  443.97
  5032.6  441.87  5042.9  441.25  5060.9   441.8    5066  444.33  5083.9  444.32
  5113.9  447.66  5143.9  447.88  5166.5  449.71  5183.9  451.78  5350.9  457.81
#Mann= 4 ,-1 , 0
  4648.1     .03       0  4981.6     .01       0  5010.9     .03       0
  5166.5     .05       0
Bank Sta=4981.6,5010.9
XS Rating Curve= 0 ,0
Exp/Cntr=0.3,0.1

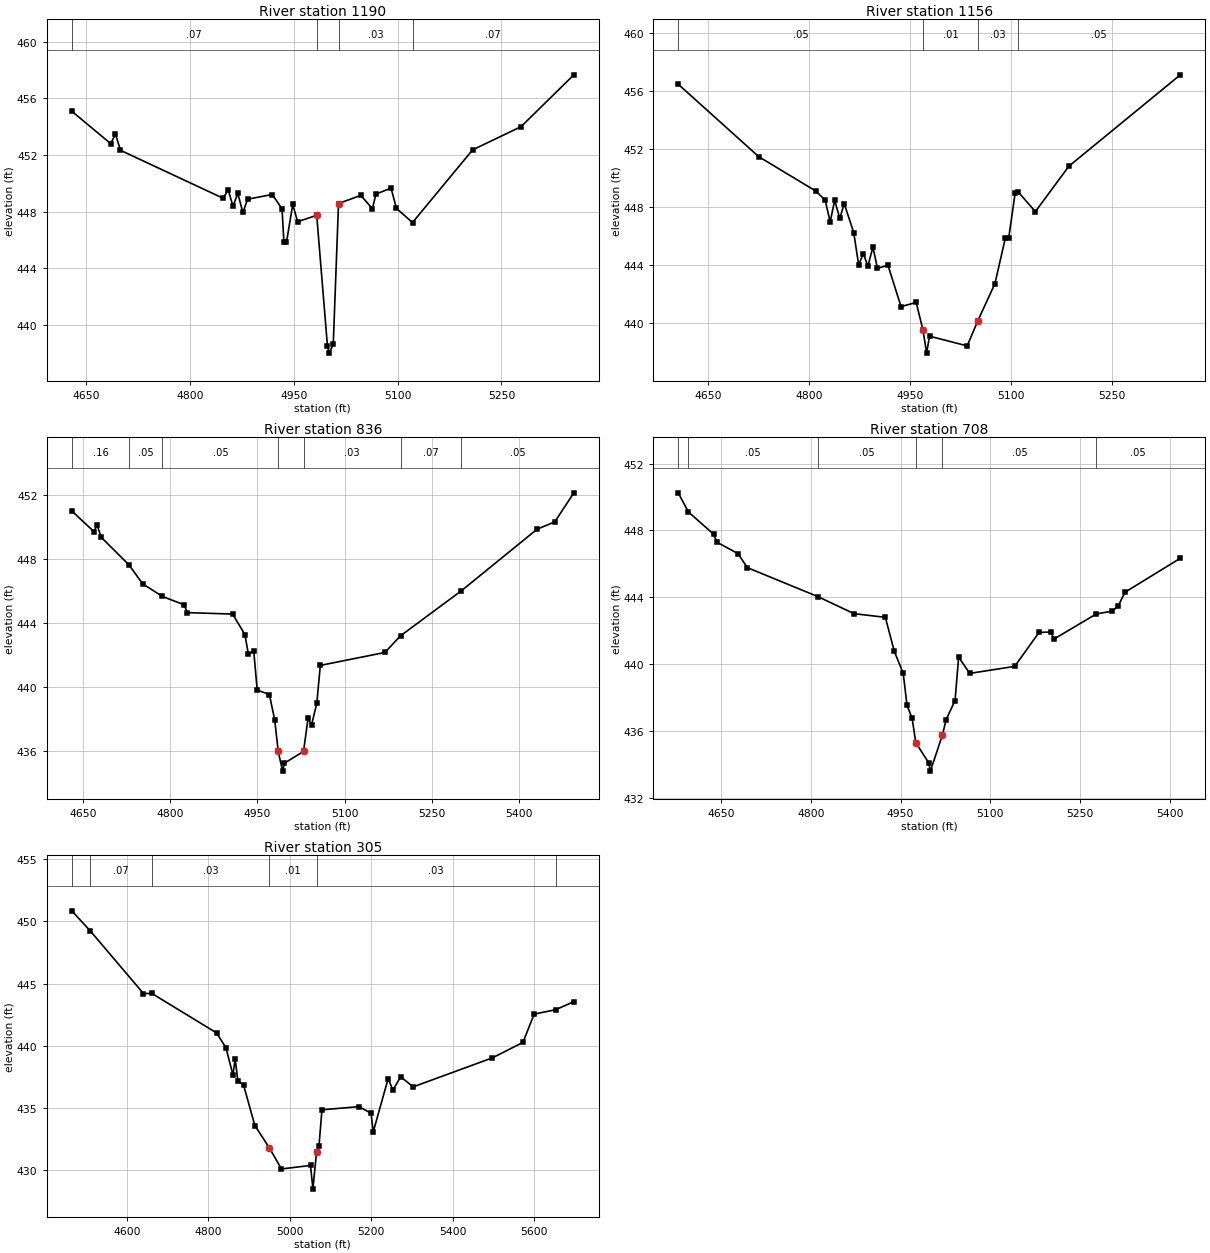
Type RM Length L Ch R = 1 ,1190    ,34,34,34
BEGIN DESCRIPTION:
Mapping XS 51f99a89
END DESCRIPTION:
XS GIS Cut Line= 6
      3502305.75     10637404.63      3502528.43     10637615.59
      3502566.19     10637635.12      3502619.57     10637657.25
      3502669.05     10637671.58       3502935.9     10637671.58
#Sta/Elev= 30
  4629.3  455.09  4685.6   452.8  4692.4  453.48  4699.7  452.33  4848.2  448.94
  4855.1  449.55  4862.3  448.39  4869.2  449.29  4876.5  447.94  4883.4  448.88
    4919  449.21  4933.1   448.2  4935.8  445.84  4939.5  445.84  4948.6  448.51
  4955.6  447.29  4983.2  447.74  4998.7  438.51  5001.4  438.01  5007.1  438.64
  5014.7  448.57  5046.8  449.15  5063.6  448.21  5068.8  449.24  5090.6  449.66
  5098.4  448.23  5121.6  447.23  5208.4  452.36  5278.4     454  5354.7  457.66
#Mann= 4 ,-1 , 0
  4629.3     .07       0  4983.2     .01       0  5014.7     .03       0
  5121.6     .07       0
Bank Sta=4983.2,5014.7
XS Rating Curve= 0 ,0
Exp/Cntr=0.3,0.1

Type RM Length L Ch R = 1 ,1156    ,320,320,320
BEGIN DESCRIPTION:
Mapping XS 34124c22
END DESCRIPTION:
XS GIS Cut Line= 6
      3502268.04     10637433.32      3502502.39     10637639.02
      3502559.68     10637668.97      3502624.78     10637692.41
      3502665.15     10637698.92      3502925.06     10637702.82
#Sta/Elev= 30
  4605.7  456.49  4725.4  451.49  4809.8  449.13  4824.1   448.5  4831.6  446.99
  4838.3  448.48  4845.9  447.23  4852.5  448.25  4866.7  446.24  4873.9  444.03
    4881   444.8  4887.6  443.93  4895.2  445.25  4901.9  443.78  4917.5     444
    4937  441.14  4959.5  441.43  4969.6  439.52    4975  437.93  4979.3   439.1
  5035.3  438.43  5051.3  440.18  5076.5  442.72    5092  445.86    5097  445.86
  5106.7     449  5110.9  449.07  5136.7   447.7  5186.7  450.84  5352.2  457.14
#Mann= 4 ,-1 , 0
  4605.7     .05       0  4969.6     .01       0  5051.3     .03       0
  5110.9     .05       0
Bank Sta=4969.6,5051.3
XS Rating Curve= 0 ,0
Exp/Cntr=0.3,0.1

Type RM Length L Ch R = 1 ,836     ,128,128,128
BEGIN DESCRIPTION:
Mapping XS 933c9a03
END DESCRIPTION:
XS GIS Cut Line= 4
      3502206.81     10637610.38      3502251.08     10637839.55
      3502438.58     10637961.94      3502842.25     10637912.46
#Sta/Elev= 30
  4630.6  451.03  4668.9  449.73    4674  450.16  4681.3  449.38  4729.2  447.65
  4752.6  446.47  4786.7  445.68  4823.9  445.16  4829.4  444.67  4907.5  444.58
  4928.6  443.29  4934.5  442.07  4943.7  442.28  4949.7  439.83  4970.7  439.55
  4979.9  437.94  4985.9  435.99  4993.4  434.76  4996.6  435.26  5029.4  435.99
  5037.2  438.06  5043.2  437.65  5052.3  439.01  5058.3  441.37  5169.5  442.18
  5196.3  443.22  5300.5  446.02  5431.5  449.89  5461.7  450.34  5494.6  452.16
#Mann= 7 ,-1 , 0
  4630.6     .16       0  4729.2     .05       0  4786.7     .05       0
  4985.9     .01       0  5029.4     .03       0  5196.3     .07       0
  5300.5     .05       0
Bank Sta=4985.9,5029.4
XS Rating Curve= 0 ,0
Exp/Cntr=0.3,0.1

Type RM Length L Ch R = 1 ,708     ,403,403,403
BEGIN DESCRIPTION:
Mapping XS 8e682ec9
END DESCRIPTION:
XS GIS Cut Line= 4
      3502131.84     10637642.33       3502193.7     10637950.51
      3502336.92     10638049.26      3502682.01     10637988.48
#Sta/Elev= 30
  4578.6  450.25  4595.5  449.11  4637.6  447.78  4643.1   447.3  4678.4  446.62
    4694  445.78  4812.4  444.04  4872.2  443.03  4924.6  442.81  4939.5  440.78
  4954.4  439.47  4960.8  437.55  4969.3  436.78  4975.4  435.32    4997  434.12
  4999.8  433.62    5020  435.79  5026.1   436.7    5041  437.84    5047  440.43
  5065.5  439.46  5140.7  439.88  5181.3  441.91  5201.1  441.93  5206.2  441.51
  5276.8  443.01  5303.2  443.18  5313.3  443.47  5324.8  444.31  5417.3  446.34
#Mann= 6 ,-1 , 0
  4578.6     .16       0  4595.5     .05       0  4812.4     .05       0
  4975.4     .03       0    5020     .05       0  5276.8     .05       0
Bank Sta=4975.4,5020
XS Rating Curve= 0 ,0
Exp/Cntr=0.3,0.1

Type RM Length L Ch R = 1 ,305     ,0,0,0
BEGIN DESCRIPTION:
UNT403 IN CCTC 1.0
END DESCRIPTION:
XS GIS Cut Line= 4
       3502053.8     10637640.46      3501876.74     10638020.64
      3502001.74     10638197.72      3502584.84     10638067.56
#Sta/Elev= 30
  4464.1  450.84  4509.6  449.23  4640.3   444.2  4660.9  444.21  4819.9  441.04
  4842.8  439.85  4860.1  437.68  4865.6  438.96    4872  437.21  4886.3  436.84
    4914   433.6  4949.7  431.81  4979.3  430.12  5050.7   430.4  5056.6   428.5
  5065.5  431.49  5071.6  431.99  5078.8  434.87  5169.8  435.12  5199.5  434.59
  5204.7  433.09  5241.5  437.37  5253.2  436.45  5272.2  437.52    5303  436.71
  5497.7  439.04  5572.7  440.28  5600.1  442.55  5652.8   442.9  5697.7  443.55
#Mann= 6 ,-1 , 0
  4464.1     .16       0  4509.6     .07       0  4660.9     .03       0
  4949.7     .01       0  5065.5     .03       0  5652.8     .05       0
Bank Sta=4949.7,5065.5
XS Rating Curve= 0 ,0
Exp/Cntr=0.3,0.1

Chan Stop Cuts=-1
Use User Specified Reach Order=0
Composite Channel Slope=5