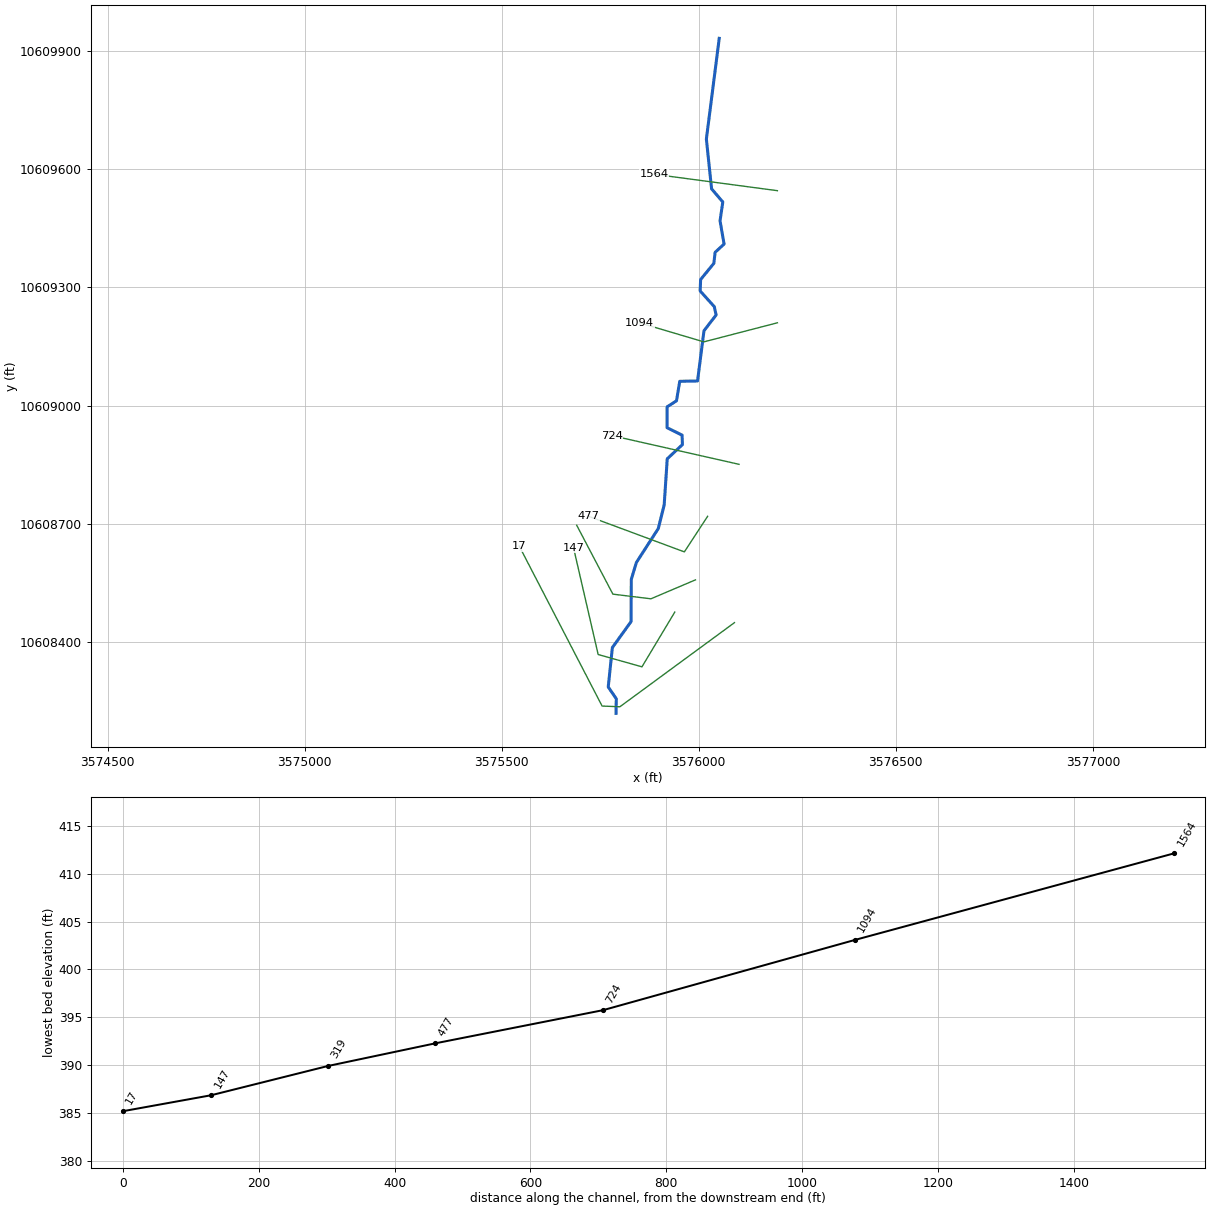
--- UNT450 IN CCTC.prj (project) ---

Proj Title=UNT450 IN CCTC Base Level Engineering
Current Plan=p01
Default Exp/Contr=0.3,0.1
English Units
Geom File=g01
Flow File=f01
Plan File=p01
Y Axis Title=Elevation
X Axis Title(PF)=Main Channel Distance
X Axis Title(XS)=Station
BEGIN DESCRIPTION:
UNT450 IN CCTC
END DESCRIPTION:
DSS Export Rating Curves= 0
DSS Export Rating Curve Sorted= 0
DSS Export Volume Flow Curves= 0
DXF OffsetX= 0
DXF OffsetY= 0
DXF ScaleX= 1
DXF ScaleY= 10

--- UNT450 IN CCTC.p01 (plan) ---

Plan Title=Multiple Run
Short Identifier=Multiple
Geom File=g01
Flow File=f01
Subcritical Flow
K Sum by GR= 0
Std Step Tol= 0.01
Critical Tol= 0.01
Num of Std Step Trials= 20
Max Error Tol= 0.3
Flow Tol Ratio= 0.001
Split Flow NTrial= 30
Split Flow Tol= 0.02
Split Flow Ratio= 0.02
Log Output Level= 0
Friction Slope Method= 1
Unsteady Friction Slope Method= 2
Unsteady Bridges Friction Slope Method= 1
Parabolic Critical Depth
Global Vel Dist=  1 , 1 , 1
Global Log Level= 0
CheckData=True
Encroach Param= -1, 0, 0, 0
BEGIN DESCRIPTION:
Multiple Run
END DESCRIPTION:

--- UNT450 IN CCTC.f01 (steady flow) ---

Flow Title=Multiple
Program Version=4.10
Number of Profiles= 7
Profile Names=10-year,25-year,50-year,1pct_min,100-year,1pct_plu,500-year
River Rch & RM=UNT450 IN CCTC,Reach-1         ,1564
     151     177     196     160     216     292     259
Boundary for River Rch & Prof#=UNT450 IN CCTC,Reach-1         , 1
Up Type= 0
Dn Type= 3
Dn Slope=0.005
Boundary for River Rch & Prof#=UNT450 IN CCTC,Reach-1         , 2
Up Type= 0
Dn Type= 3
Dn Slope=0.005
Boundary for River Rch & Prof#=UNT450 IN CCTC,Reach-1         , 3
Up Type= 0
Dn Type= 3
Dn Slope=0.005
Boundary for River Rch & Prof#=UNT450 IN CCTC,Reach-1         , 4
Up Type= 0
Dn Type= 3
Dn Slope=0.005
Boundary for River Rch & Prof#=UNT450 IN CCTC,Reach-1         , 5
Up Type= 0
Dn Type= 3
Dn Slope=0.005
Boundary for River Rch & Prof#=UNT450 IN CCTC,Reach-1         , 6
Up Type= 0
Dn Type= 3
Dn Slope=0.005
Boundary for River Rch & Prof#=UNT450 IN CCTC,Reach-1         , 7
Up Type= 0
Dn Type= 3
Dn Slope=0.005
DSS Import GetInterval= 0
DSS Import GetPeak= 0
DSS Import FillOption= 0

--- UNT450 IN CCTC.g01 (geometry) ---

Geom Title=Existing Conditions
Program Version=4.10

River Reach=UNT450 IN CCTC  ,Reach-1
Reach XY= 30
      3576051.96     10609932.09      3576019.32     10609676.53
      3576032.52     10609550.15      3576060.99     10609516.81
      3576054.04      10609468.9      3576064.25       10609410.
       3576041.5       10609389.      3576038.25       10609361.
      3576004.75       10609320.       3576003.5       10609291.
       3576039.5       10609251.        3576044.       10609230.
      3576013.25       10609190.       3575996.9     10609062.56
      3575951.76     10609061.69      3575943.52     10609012.21
      3575919.75       10608997.       3575919.5       10608944.
      3575957.75       10608925.       3575958.5       10608901.
        3575920.       10608865.      3575912.25       10608748.
      3575897.25       10608688.      3575841.75       10608602.
      3575828.75       10608559.      3575828.25       10608452.
      3575780.75       10608386.      3575770.25       10608286.
      3575790.75       10608256.        3575790.       10608219.

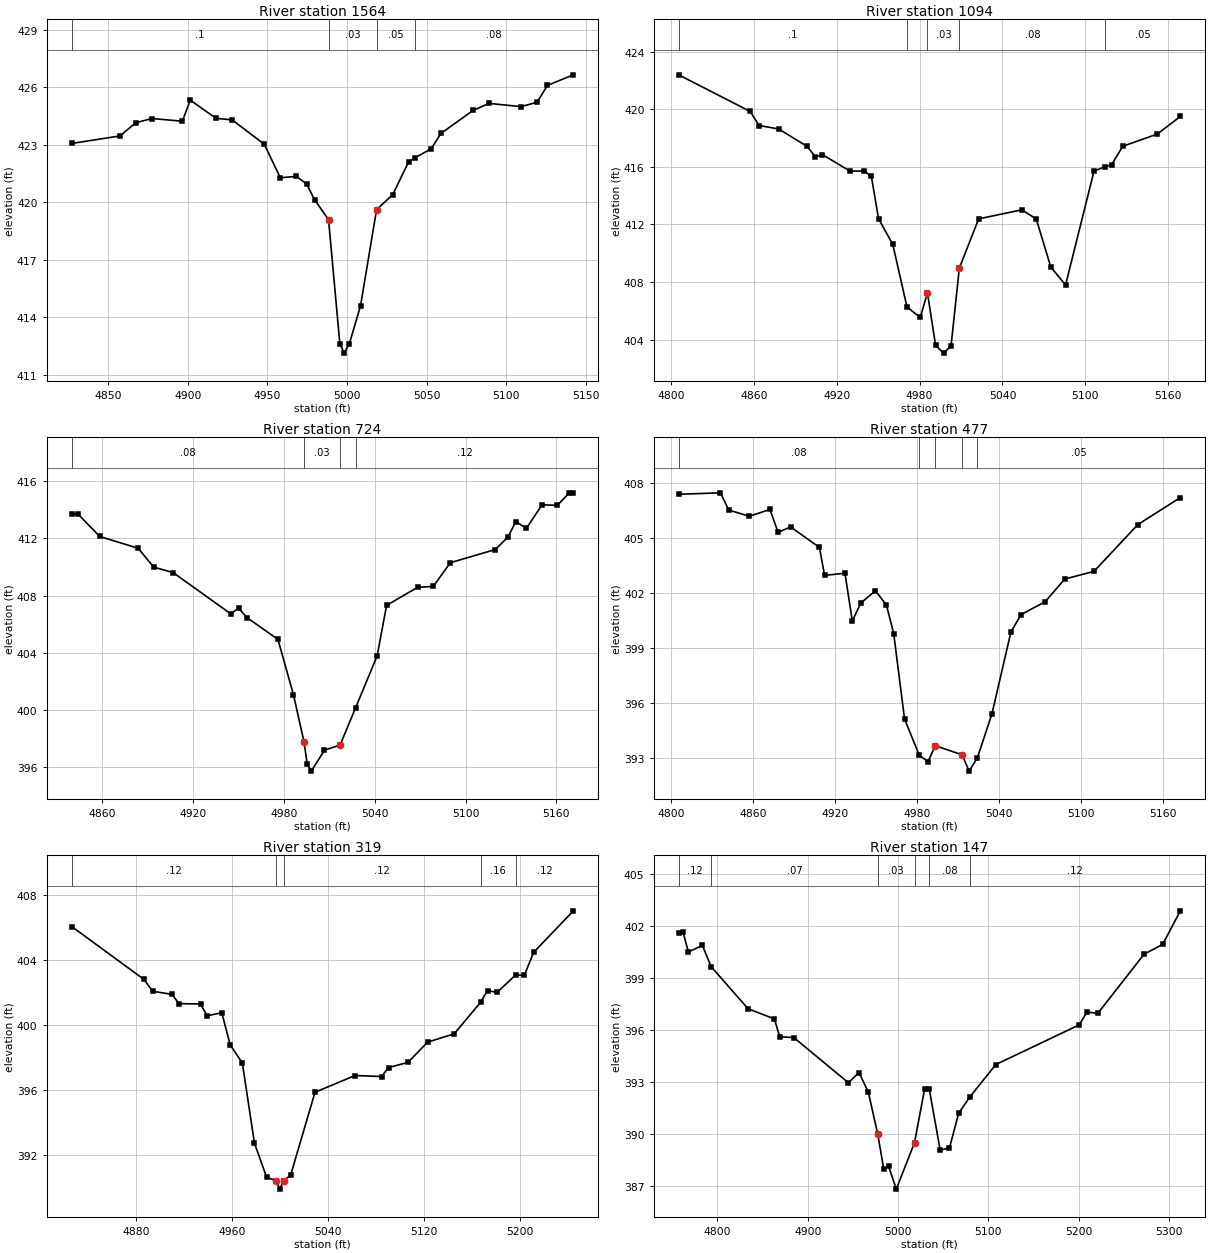
Type RM Length L Ch R = 1 ,1564    ,470,470,470
BEGIN DESCRIPTION:
Mapping XS 22e74771
END DESCRIPTION:
XS GIS Cut Line= 2
      3576199.56     10609545.48      3575887.03     10609587.15
#Sta/Elev= 30
    4827  423.07  4857.2  423.46  4867.3  424.15  4877.4  424.37  4896.5  424.23
  4901.5  425.33  4917.7  424.38  4927.8   424.3    4948  423.03  4958.1  421.28
  4968.2  421.35  4974.7  420.95  4979.7  420.12  4988.4   419.1  4995.5  412.63
  4998.2  412.13  5001.5  412.63  5008.5  414.59  5018.6  419.62  5028.7  420.39
  5038.8  422.12  5042.7  422.32  5052.9  422.79    5059  423.59  5079.2  424.79
  5089.3  425.16  5109.4  424.99  5119.5  425.22    5126   426.1  5142.3  426.65
#Mann= 4 ,-1 , 0
    4827      .1       0  4988.4     .03       0  5018.6     .05       0
  5042.7     .08       0
Bank Sta=4988.4,5018.6
XS Rating Curve= 0 ,0
Exp/Cntr=0.3,0.1

Type RM Length L Ch R = 1 ,1094    ,370,370,370
BEGIN DESCRIPTION:
UNT450 IN CCTC 2.0
END DESCRIPTION:
XS GIS Cut Line= 3
      3576199.65      10609210.2      3576012.97     10609161.79
      3575849.64     10609210.18
#Sta/Elev= 30
  4805.6  422.39  4857.3  419.85  4863.9  418.87    4878  418.63  4898.6  417.42
  4904.5   416.7  4909.7  416.85  4929.6  415.71  4939.9  415.71  4945.1  415.34
  4950.3   412.4  4960.6  410.62  4970.9  406.27  4980.5  405.55  4985.7  407.26
  4991.6  403.61  4997.4  403.07  5002.8  403.57  5008.8  408.98  5022.8  412.39
  5054.1  413.02  5064.5  412.38    5075  409.05  5085.7   407.8  5106.3  415.71
  5114.5  416.02    5119  416.14  5127.1  417.43  5152.2  418.28  5168.8   419.5
#Mann= 5 ,-1 , 0
  4805.6      .1       0  4970.9     .07       0  4985.7     .03       0
  5008.8     .08       0  5114.5     .05       0
Bank Sta=4985.7,5008.8
XS Rating Curve= 0 ,0
Exp/Cntr=0.3,0.1

Type RM Length L Ch R = 1 ,724     ,247,247,247
BEGIN DESCRIPTION:
Mapping XS 70e1109e
END DESCRIPTION:
XS GIS Cut Line= 2
      3576102.35     10608851.03      3575779.38     10608923.96
#Sta/Elev= 30
  4840.1  413.71  4844.1  413.71  4858.6  412.13  4883.9  411.31  4894.2  409.99
    4907  409.61    4945  406.73  4950.2  407.13  4955.7  406.47  4976.2  404.94
  4986.4  401.09  4993.4  397.79  4995.5  396.24  4998.2  395.74  5006.9   397.2
  5017.2  397.56  5027.4  400.15  5041.7   403.8  5047.9  407.32  5068.4  408.58
  5078.7  408.64    5090   410.3  5119.7  411.22  5128.1  412.11  5133.2  413.17
  5140.2   412.7  5150.5  414.34  5160.7  414.31  5168.5  415.18  5171.2  415.18
#Mann= 4 ,-1 , 0
  4840.1     .08       0  4993.4     .03       0  5017.2     .05       0
  5027.4     .12       0
Bank Sta=4993.4,5017.2
XS Rating Curve= 0 ,0
Exp/Cntr=0.3,0.1

Type RM Length L Ch R = 1 ,477     ,158,158,158
BEGIN DESCRIPTION:
Mapping XS a4579078
END DESCRIPTION:
XS GIS Cut Line= 3
      3576022.48      10608719.1      3575963.45     10608628.81
      3575720.35     10608719.11
#Sta/Elev= 30
  4805.7  407.39  4836.3  407.47  4842.3  406.53  4857.4  406.19  4872.5  406.56
  4878.5  405.31  4887.6  405.61  4908.7  404.49  4912.5  402.96  4927.4  403.08
  4932.8  400.47    4939  401.45  4949.7  402.12  4957.8  401.34  4963.1  399.78
    4971  395.13  4981.7  393.15  4988.2  392.78  4993.5  393.66  5013.2  393.16
  5018.3  392.27  5024.3  392.99    5035   395.4  5048.9  399.87  5056.3  400.82
  5073.9  401.52  5088.3  402.76  5109.7  403.18  5141.7  405.73  5172.9  407.21
#Mann= 5 ,-1 , 0
  4805.7     .08       0  4981.7     .05       0  4993.5     .03       0
  5013.2     .07       0  5024.3     .05       0
Bank Sta=4993.5,5013.2
XS Rating Curve= 0 ,0
Exp/Cntr=0.3,0.1

Type RM Length L Ch R = 1 ,319     ,172,172,172
BEGIN DESCRIPTION:
Mapping XS 01484018
END DESCRIPTION:
XS GIS Cut Line= 4
      3575991.68     10608557.84       3575878.6     10608509.76
      3575782.08     10608521.57      3575690.26     10608696.41
#Sta/Elev= 30
  4826.7  406.08  4886.7  402.83  4894.1  402.09  4910.3   401.9  4915.9  401.33
  4933.9  401.31  4939.4  400.58  4951.6  400.77  4958.6  398.79  4968.7  397.68
  4978.8  392.73  4988.9  390.64    4997   390.4  4999.8   389.9    5003   390.4
    5009  390.78  5029.2  395.87  5062.5   396.9  5084.6  396.84  5090.4  397.39
  5106.6  397.71    5123  398.96  5145.1  399.47  5167.1  401.42  5172.8  402.14
  5180.8  402.02  5196.2   403.1  5203.4  403.07  5211.2  404.49  5244.3  407.05
#Mann= 5 ,-1 , 0
  4826.7     .12       0    4997     .07       0    5003     .12       0
  5167.1     .16       0  5196.2     .12       0
Bank Sta=4997,5003
XS Rating Curve= 0 ,0
Exp/Cntr=0.3,0.1

Type RM Length L Ch R = 1 ,147     ,130,130,130
BEGIN DESCRIPTION:
UNT450 IN CCTC 1.0
END DESCRIPTION:
XS GIS Cut Line= 4
      3575939.15     10608476.05      3575855.81     10608337.15
       3575744.7      10608368.4      3575682.19     10608639.27
#Sta/Elev= 30
  4757.1  401.61    4762  401.66  4767.8  400.53  4783.4   400.9    4793  399.68
  4833.9  397.25  4863.1  396.66  4868.9  395.63  4884.5  395.59    4945  392.98
  4956.7  393.57  4967.1  392.43  4977.5  390.01  4984.2  387.98  4989.4  388.18
    4998  386.84  5018.2  389.52  5029.4  392.62  5034.5  392.62  5046.6  389.09
  5056.9  389.22  5067.1  391.22  5079.2  392.14  5108.2  394.03  5200.6  396.32
  5209.2  397.06  5221.1  396.98  5272.4   400.4  5292.9  400.96  5312.5   402.9
#Mann= 6 ,-1 , 0
  4757.1     .12       0    4793     .07       0  4977.5     .03       0
  5018.2     .05       0  5034.5     .08       0  5079.2     .12       0
Bank Sta=4977.5,5018.2
XS Rating Curve= 0 ,0
Exp/Cntr=0.3,0.1

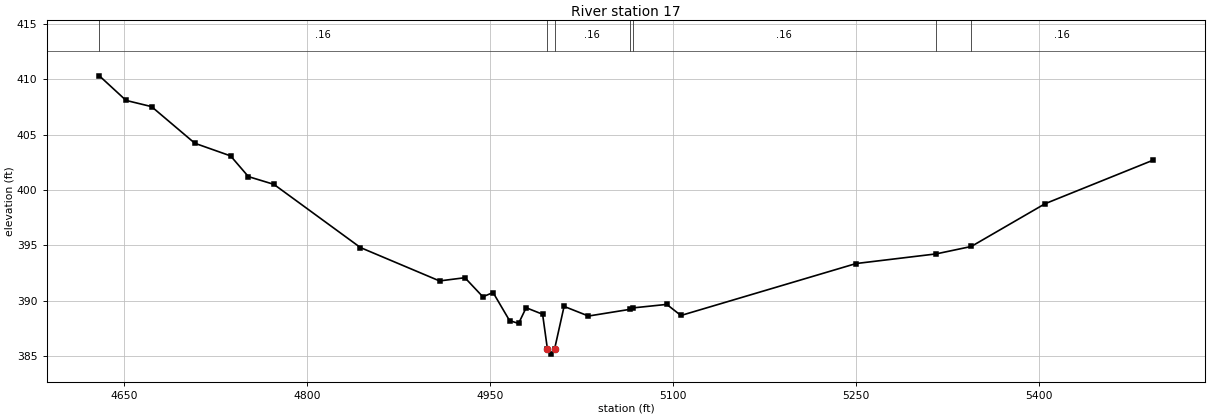
Type RM Length L Ch R = 1 ,17      ,0,0,0
BEGIN DESCRIPTION:
Mapping XS 621e1786
END DESCRIPTION:
XS GIS Cut Line= 4
      3576090.66     10608449.34      3575799.87     10608235.81
      3575754.73     10608237.54      3575544.19      10608643.9
#Sta/Elev= 30
  4629.7   410.3  4651.6  408.08  4672.5  407.52    4708  404.21  4737.3  403.07
  4751.9   401.2  4772.8   400.5  4843.8  394.79  4908.6  391.78  4929.4  392.07
  4944.1  390.35  4952.5  390.73    4966   388.2  4973.4  387.94  4979.6  389.36
  4993.1  388.77    4997  385.67  4999.8  385.17    5003  385.67  5010.7  389.48
  5030.7  388.61  5064.5  389.21  5066.8  389.34  5094.9  389.66  5106.5  388.66
  5250.1  393.35  5315.7  394.22  5344.5  394.89    5405  398.75  5493.3  402.67
#Mann= 7 ,-1 , 0
  4629.7     .16       0    4997     .07       0    5003     .16       0
  5064.5     .12       0  5066.8     .16       0  5315.7     .05       0
  5344.5     .16       0
Bank Sta=4997,5003
XS Rating Curve= 0 ,0
Exp/Cntr=0.3,0.1

Chan Stop Cuts=-1
Use User Specified Reach Order=0
Composite Channel Slope=5