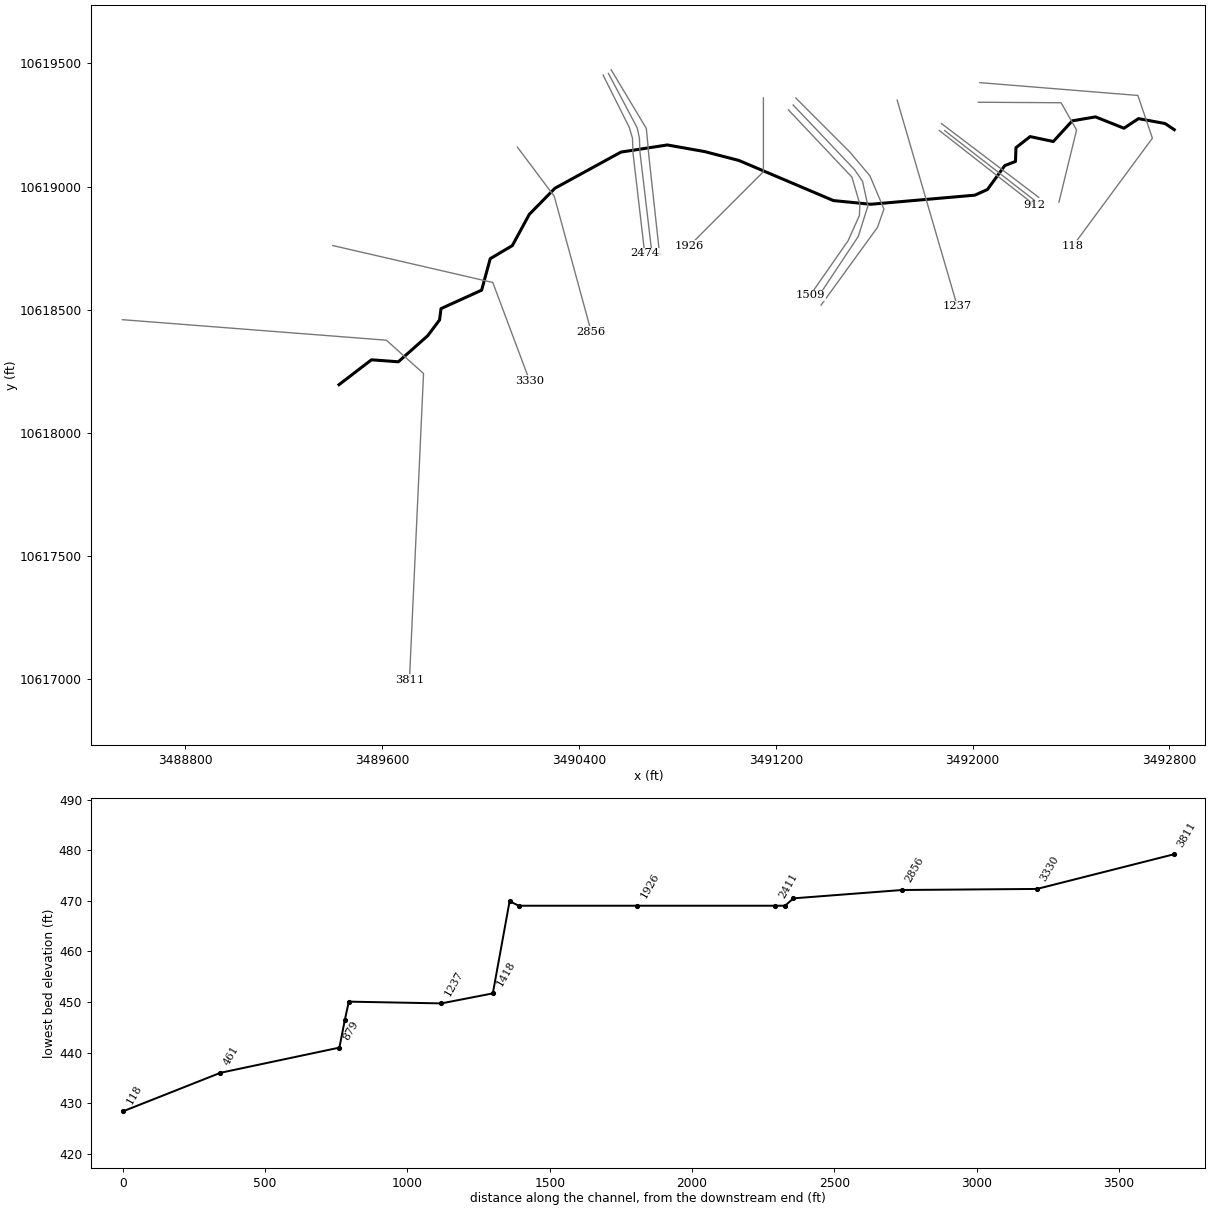
--- UNT500 IN CCTC.prj (project) ---

Proj Title=UNT500 IN CCTC Base Level Engineering
Current Plan=p01
Default Exp/Contr=0.3,0.1
English Units
Geom File=g01
Flow File=f01
Plan File=p01
BEGIN DESCRIPTION:
UNT500 IN CCTC
END DESCRIPTION:

--- UNT500 IN CCTC.p01 (plan) ---

Plan Title=Multiple Run
Short Identifier=Multiple
Geom File=g01
Flow File=f01
Subcritical Flow
K Sum by GR= 0
Std Step Tol= 0.01
Critical Tol= 0.01
Num of Std Step Trials= 20
Max Error Tol= 0.3
Flow Tol Ratio= 0.001
Split Flow NTrial= 30
Split Flow Tol= 0.02
Split Flow Ratio= 0.02
Log Output Level= 0
Friction Slope Method= 1
Unsteady Friction Slope Method= 2
Unsteady Bridges Friction Slope Method= 1
Parabolic Critical Depth
Global Vel Dist=  1 , 1 , 1
Global Log Level= 0
CheckData=True
Encroach Param= -1, 0, 0, 0
BEGIN DESCRIPTION:
Multiple Run
END DESCRIPTION:

--- UNT500 IN CCTC.f01 (steady flow) ---

Flow Title=Multiple
Number of Profiles=7
Profile Names=10-year,25-year,50-year,1pct_min,100-year,1pct_plu,500-year
River Rch & RM= UNT500 IN CCTC,Reach-1,3811
     557     727     861     746    1008    1364    1377
Boundary for River Rch & Prof#=UNT500 IN CCTC,Reach-1,1
Up Type=0
Dn Type=3
Dn Slope=0.005
Boundary for River Rch & Prof#=UNT500 IN CCTC,Reach-1,2
Up Type=0
Dn Type=3
Dn Slope=0.005
Boundary for River Rch & Prof#=UNT500 IN CCTC,Reach-1,3
Up Type=0
Dn Type=3
Dn Slope=0.005
Boundary for River Rch & Prof#=UNT500 IN CCTC,Reach-1,4
Up Type=0
Dn Type=3
Dn Slope=0.005
Boundary for River Rch & Prof#=UNT500 IN CCTC,Reach-1,5
Up Type=0
Dn Type=3
Dn Slope=0.005
Boundary for River Rch & Prof#=UNT500 IN CCTC,Reach-1,6
Up Type=0
Dn Type=3
Dn Slope=0.005
Boundary for River Rch & Prof#=UNT500 IN CCTC,Reach-1,7
Up Type=0
Dn Type=3
Dn Slope=0.005

--- UNT500 IN CCTC.g01 (geometry) ---

Geom Title=Existing Conditions

River Reach=UNT500 IN CCTC,Reach-1
Reach XY= 30
      3489424.50     10618195.00      3489556.50     10618296.00
      3489665.75     10618288.00      3489785.25     10618394.00
      3489833.25     10618458.00      3489839.25     10618504.00
      3490004.25     10618579.00      3490039.25     10618707.00
      3490129.00     10618760.00      3490198.00     10618887.00
      3490302.00     10618993.00      3490570.50     10619140.00
      3490759.25     10619169.00      3490911.00     10619142.00
      3491050.00     10619106.00      3491434.25     10618943.00
      3491586.00     10618928.00      3492009.25     10618965.00
      3492060.25     10618988.00      3492130.75     10619085.00
      3492174.25     10619102.00      3492176.25     10619158.00
      3492233.75     10619203.00      3492328.00     10619183.00
      3492405.00     10619267.00      3492499.50     10619283.00
      3492615.25     10619237.00      3492674.25     10619276.00
      3492782.50     10619256.00      3492819.75     10619231.00

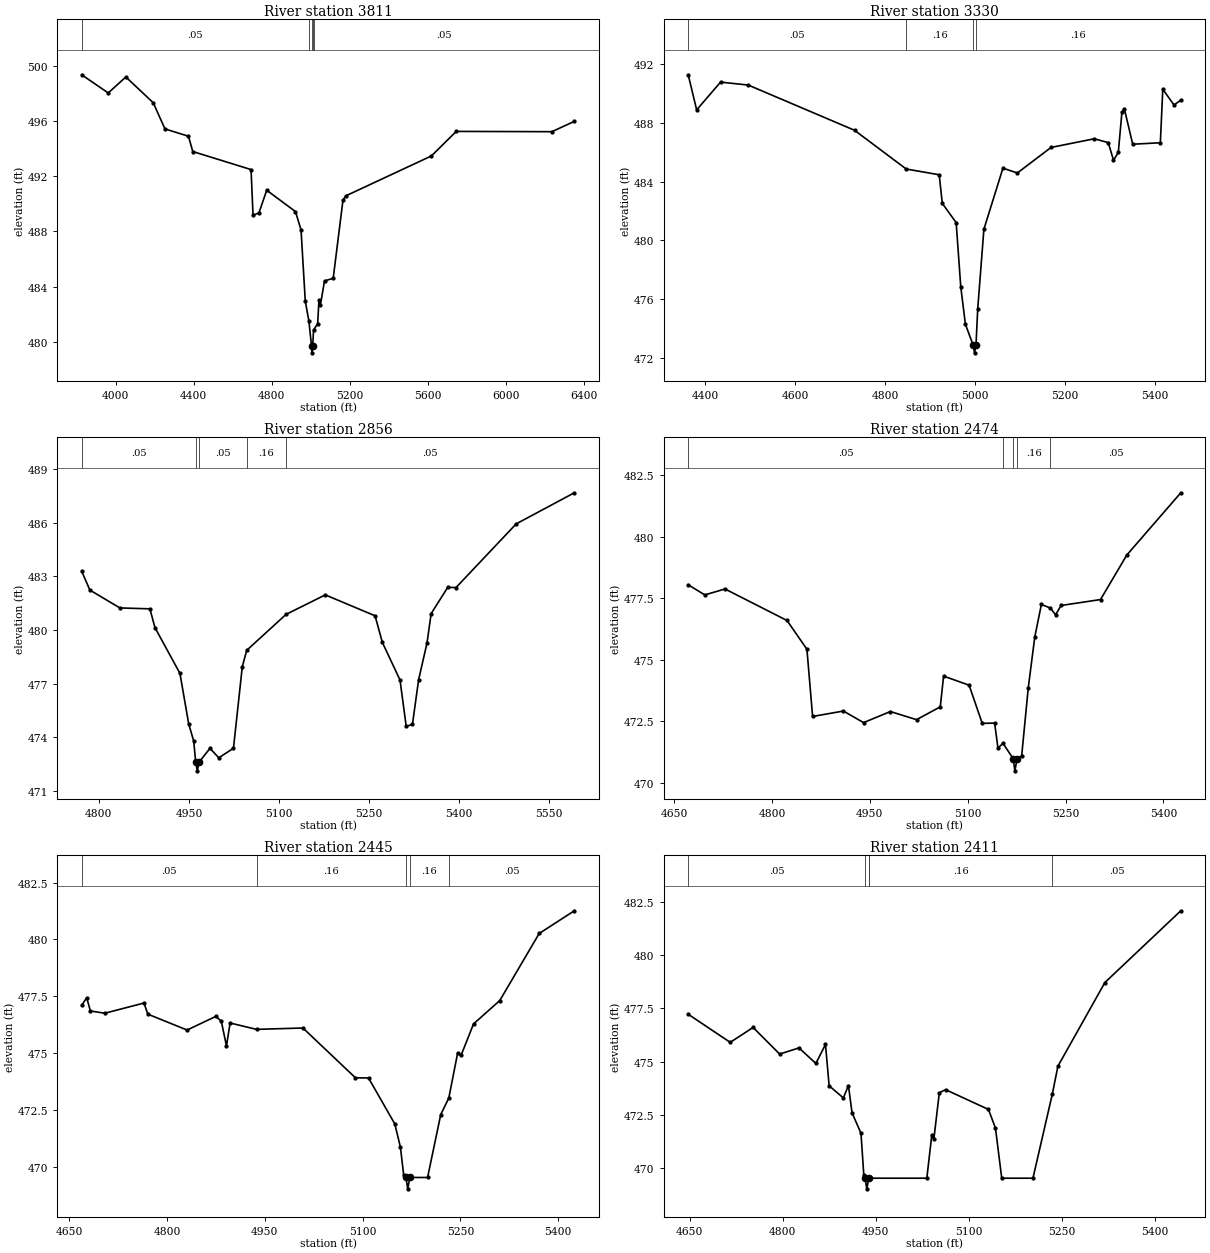
Type RM Length L Ch R = 1,3811,481,481,481
BEGIN DESCRIPTION:
UNT500 IN CCTC 8.0
END DESCRIPTION:
XS GIS Cut Line= 4
      3488544.17     10618459.03      3489617.08     10618375.70
      3489768.12     10618240.28      3489710.83     10616995.50
#Sta/Elev= 30
  3825.6  499.37  3961.4  498.05  4051.7  499.21  4192.1  497.34  4252.3  495.44
  4372.7  494.91  4394.8  493.80  4693.6  492.49  4703.7  489.18  4733.8  489.34
  4773.9  490.99  4921.4  489.44  4949.8  488.11  4971.5  482.95  4990.0  481.50
  5003.6  479.69  5006.4  479.19  5009.6  479.69  5013.9  480.84  5035.0  481.31
  5041.7  483.03  5049.2  482.68  5070.2  484.41  5114.7  484.60  5164.8  490.28
  5180.4  490.59  5618.1  493.48  5745.4  495.26  6235.9  495.24  6350.7  495.99
#Mann=5,-1,0
  3825.6    0.05       0  4990.0    0.16       0  5003.6    0.07       0
  5009.6    0.16       0  5013.9    0.05       0
Bank Sta=5003.6,5009.6
Exp/Cntr=0.3,0.1

Type RM Length L Ch R = 1,3330,474,474,474
BEGIN DESCRIPTION:
UNT500 IN CCTC 7.0
END DESCRIPTION:
XS GIS Cut Line= 3
      3489399.58     10618760.20      3490049.61     10618610.19
      3490199.60     10618210.20
#Sta/Elev= 30
  4362.8  491.28  4381.6  488.89  4434.7  490.78  4496.2  490.58  4732.3  487.50
  4847.2  484.86  4920.4  484.47  4927.3  482.52  4958.1  481.21  4968.3  476.84
  4978.6  474.29  4996.1  472.84  4998.9  472.34  5002.1  472.84  5006.0  475.34
  5019.7  480.76  5062.0  484.92  5094.0  484.59  5168.8  486.33  5264.9  486.92
  5296.0  486.66  5307.6  485.46  5318.3  485.99  5326.3  488.72  5331.6  488.98
  5350.3  486.55  5411.7  486.65  5417.1  490.30  5442.0  489.22  5457.1  489.55
#Mann=4,-1,0
  4362.8    0.05       0  4847.2    0.16       0  4996.1    0.07       0
  5002.1    0.16       0
Bank Sta=4996.1,5002.1
Exp/Cntr=0.3,0.1

Type RM Length L Ch R = 1,2856,382,382,382
BEGIN DESCRIPTION:
UNT500 IN CCTC 6.0
END DESCRIPTION:
XS GIS Cut Line= 3
      3490149.61     10619160.18      3490299.61     10618960.19
      3490449.61     10618410.17
#Sta/Elev= 30
  4771.6  483.29  4785.1  482.24  4835.1  481.24  4885.1  481.19  4893.5  480.14
  4935.1  477.58  4949.7  474.75  4958.0  473.80  4961.3  472.63  4964.0  472.13
  4967.3  472.63  4985.1  473.39  4999.7  472.86  5024.2  473.39  5038.9  477.95
  5046.3  478.87  5111.8  480.88  5177.1  481.97  5260.0  480.80  5272.1  479.31
  5301.5  477.21  5311.8  474.62  5322.2  474.73  5332.5  477.23  5346.4  479.27
  5353.3  480.92  5380.9  482.39  5394.7  482.38  5494.9  485.94  5591.7  487.68
#Mann=5,-1,0
  4771.6    0.05       0  4961.3   0.035       0  4967.3    0.05       0
  5046.3    0.16       0  5111.8    0.05       0
Bank Sta=4961.3,4967.3
Exp/Cntr=0.3,0.1

Type RM Length L Ch R = 1,2474,29,29,29
BEGIN DESCRIPTION:
Mapping XS 029942ab
END DESCRIPTION:
XS GIS Cut Line= 5
      3490498.01     10619452.91      3490604.37     10619240.20
      3490617.39     10619196.80      3490619.56     10619136.04
      3490667.30     10618728.05
#Sta/Elev= 30
  4671.8  478.04  4697.2  477.63  4728.2  477.87  4823.2  476.59  4853.7  475.42
  4862.4  472.69  4909.6  472.91  4940.5  472.44  4981.6  472.89  5021.6  472.56
  5058.0  473.08  5063.1  474.33  5102.2  473.96  5122.3  472.41  5141.3  472.42
  5146.4  471.40  5154.0  471.60  5169.6  470.98  5172.4  470.48  5175.6  470.98
  5182.7  471.08  5192.8  473.85  5202.8  475.92  5212.9  477.24  5226.5  477.10
  5234.7  476.82  5243.1  477.20  5303.5  477.44  5343.8  479.25  5426.5  481.78
#Mann=5,-1,0
  4671.8    0.05       0  5154.0    0.16       0  5169.6   0.033       0
  5175.6    0.16       0  5226.5    0.05       0
Bank Sta=5169.6,5175.6
Exp/Cntr=0.3,0.1

Type RM Length L Ch R = 1,2445,34,34,34
BEGIN DESCRIPTION:
Mapping XS d7cd00dd
END DESCRIPTION:
XS GIS Cut Line= 5
      3490519.71     10619459.42      3490636.92     10619238.03
      3490645.60     10619196.80      3490647.77     10619140.38
      3490695.52     10618736.69
#Sta/Elev= 30
  4669.1  477.10  4676.7  477.43  4682.4  476.85  4704.4  476.75  4764.7  477.20
  4770.4  476.71  4830.7  476.01  4874.7  476.61  4883.2  476.40  4891.1  475.31
  4896.7  476.32  4937.2  476.04  5008.4  476.10  5088.9  473.91  5109.0  473.90
  5149.3  471.88  5157.9  470.86  5163.0  469.62  5166.4  469.52  5169.2  469.02
  5172.4  469.52  5199.6  469.52  5219.8  472.29  5232.2  473.02  5245.8  475.01
  5250.9  474.89  5270.1  476.28  5310.4  477.31  5370.8  480.26  5424.7  481.26
#Mann=5,-1,0
  4669.1    0.05       0  4937.2    0.16       0  5166.4    0.07       0
  5172.4    0.16       0  5232.2    0.05       0
Bank Sta=5166.4,5172.4
Exp/Cntr=0.3,0.1

Type RM Length L Ch R = 1,2411,485,485,485
BEGIN DESCRIPTION:
UNT500 IN CCTC 5.0
END DESCRIPTION:
XS GIS Cut Line= 4
      3490530.59     10619474.56      3490673.81     10619235.86
      3490684.66     10619118.68      3490727.86     10618723.38
#Sta/Elev= 30
  4647.8  477.22  4715.5  475.90  4752.4  476.60  4795.2  475.35  4826.3  475.64
  4853.5  474.91  4869.0  475.80  4874.9  473.86  4897.8  473.29  4906.0  473.87
  4911.8  472.59  4926.2  471.63  4930.8  469.65  4932.8  469.52  4935.6  469.02
  4938.8  469.52  4939.9  469.52  5032.3  469.52  5040.3  471.55  5043.6  471.35
  5052.4  473.53  5062.4  473.68  5131.6  472.75  5142.9  471.87  5153.0  469.52
  5203.3  469.52  5234.5  473.47  5243.5  474.78  5319.2  478.71  5441.5  482.08
#Mann=5,-1,0
  4647.8    0.05       0  4932.8    0.07       0  4938.8    0.05       0
  4939.9    0.16       0  5234.5    0.05       0
Bank Sta=4932.8,4938.8
Exp/Cntr=0.3,0.1

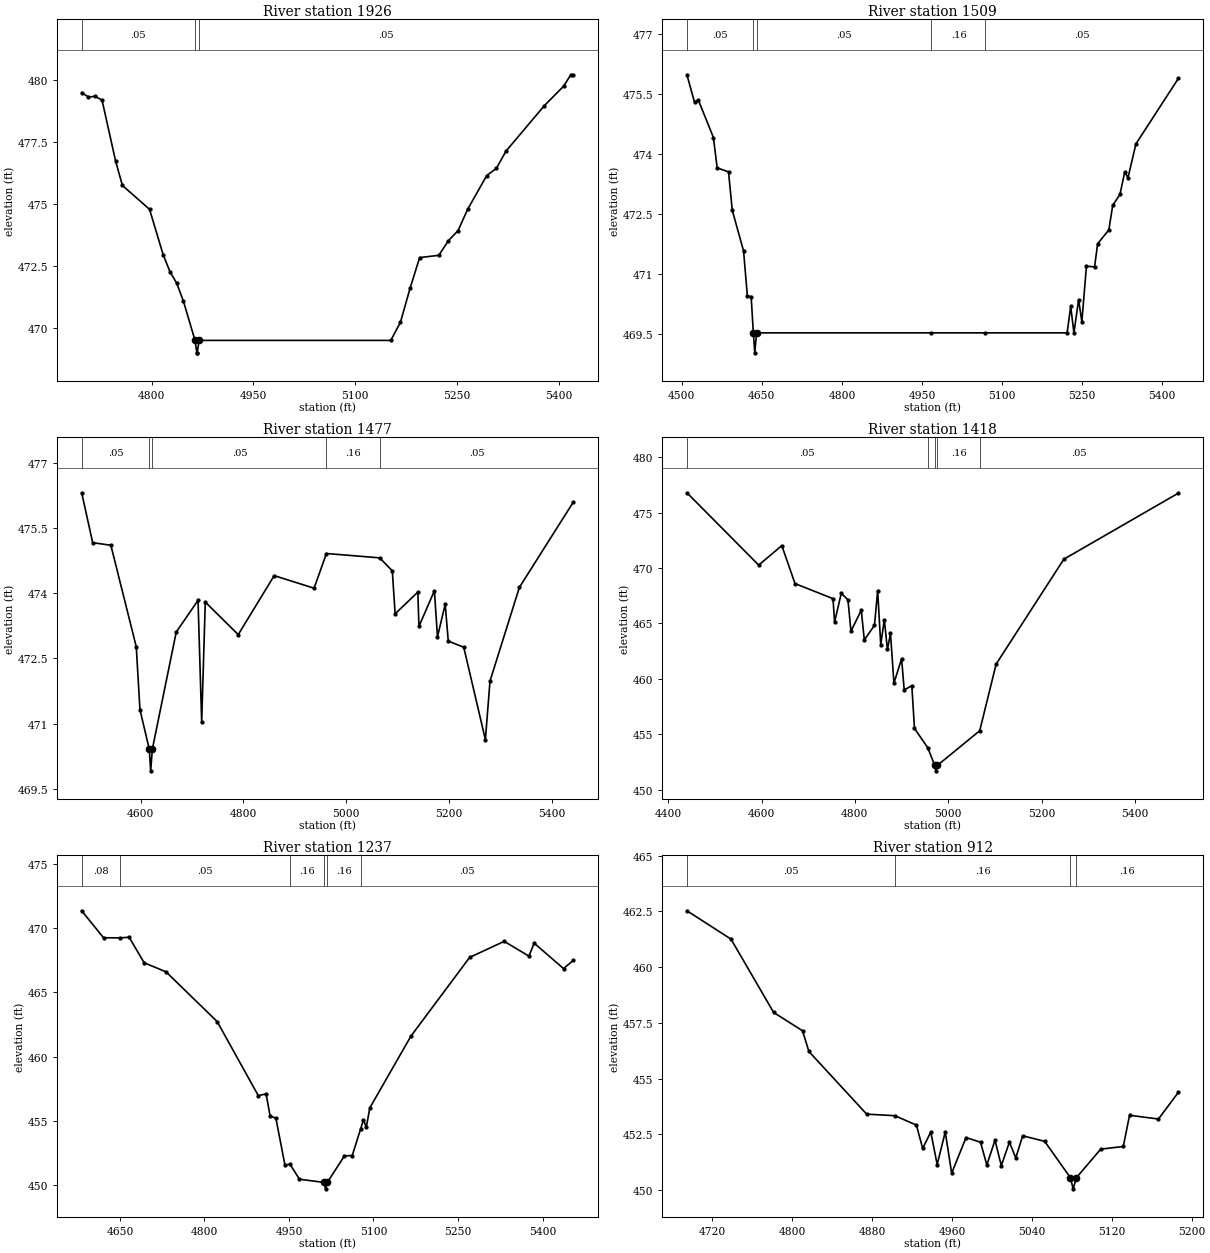
Type RM Length L Ch R = 1,1926,417,417,417
BEGIN DESCRIPTION:
UNT500 IN CCTC 4.0
END DESCRIPTION:
XS GIS Cut Line= 3
      3491149.61     10619360.15      3491149.61     10619060.19
      3490849.63     10618760.21
#Sta/Elev= 30
  4696.9  479.48  4706.9  479.31  4716.9  479.33  4726.9  479.18  4746.9  476.73
  4756.9  475.75  4796.9  474.79  4816.9  472.97  4826.9  472.29  4836.9  471.82
  4846.9  471.09  4863.9  469.52  4866.6  469.02  4867.1  469.02  4869.9  469.52
  5152.4  469.52  5166.6  470.25  5180.7  471.61  5194.9  472.85  5223.1  472.94
  5237.3  473.53  5251.4  473.93  5265.6  474.79  5293.8  476.15  5308.0  476.44
  5322.1  477.13  5378.7  478.96  5407.0  479.74  5417.6  480.20  5421.1  480.20
#Mann=3,-1,0
  4696.9    0.05       0  4863.9   0.033       0  4869.9    0.05       0
Bank Sta=4863.9,4869.9
Exp/Cntr=0.3,0.1

Type RM Length L Ch R = 1,1509,32,32,32
BEGIN DESCRIPTION:
Mapping XS db8bb8bf
END DESCRIPTION:
XS GIS Cut Line= 6
      3491251.10     10619311.79      3491509.31     10619038.38
      3491541.87     10618927.70      3491539.70     10618882.13
      3491494.12     10618780.13      3491340.05     10618558.80
#Sta/Elev= 30
  4509.7  475.98  4523.9  475.29  4531.0  475.35  4559.3  474.41  4566.3  473.65
  4587.6  473.55  4594.6  472.59  4615.8  471.57  4622.9  470.44  4630.0  470.43
  4634.1  469.52  4636.8  469.02  4640.1  469.52  4967.7  469.52  5069.0  469.52
  5221.9  469.52  5228.6  470.18  5234.7  469.52  5243.4  470.35  5249.5  469.80
  5258.1  471.19  5273.3  471.17  5279.1  471.75  5300.1  472.10  5307.3  472.71
  5321.0  472.99  5329.9  473.55  5335.9  473.40  5350.8  474.25  5430.4  475.89
#Mann=5,-1,0
  4509.7    0.05       0  4634.1    0.07       0  4640.1    0.05       0
  4967.7    0.16       0  5069.0    0.05       0
Bank Sta=4634.1,4640.1
Exp/Cntr=0.3,0.1

Type RM Length L Ch R = 1,1477,59,59,59
BEGIN DESCRIPTION:
Mapping XS b51ebb9f
END DESCRIPTION:
XS GIS Cut Line= 6
      3491270.57     10619331.38      3491520.16     10619068.76
      3491552.72     10619021.02      3491574.42     10618921.19
      3491535.36     10618797.50      3491368.24     10618545.74
#Sta/Elev= 30
  4485.3  476.32  4506.7  475.17  4542.1  475.11  4591.5  472.77  4598.7  471.32
  4616.8  470.41  4619.6  469.91  4622.8  470.41  4669.3  473.11  4711.7  473.84
  4718.8  471.03  4725.8  473.80  4789.9  473.05  4859.9  474.41  4937.5  474.12
  4961.5  474.92  5065.2  474.82  5089.7  474.52  5095.2  473.53  5139.4  474.03
  5141.5  473.24  5171.6  474.06  5177.6  473.00  5192.6  473.75  5198.6  472.90
  5228.7  472.76  5270.8  470.63  5279.8  471.98  5337.0  474.14  5441.6  476.10
#Mann=5,-1,0
  4485.3    0.05       0  4616.8    0.07       0  4622.8    0.05       0
  4961.5    0.16       0  5065.2    0.05       0
Bank Sta=4616.8,4622.8
Exp/Cntr=0.3,0.1

Type RM Length L Ch R = 1,1418,181,181,181
BEGIN DESCRIPTION:
UNT500 IN CCTC 3.0
END DESCRIPTION:
XS GIS Cut Line= 6
      3491281.47     10619359.54      3491502.80     10619138.21
      3491583.10     10619042.72      3491639.52     10618908.17
      3491613.48     10618834.39      3491384.06     10618518.37
#Sta/Elev= 30
  4440.2  476.80  4594.0  470.27  4643.5  472.03  4671.8  468.60  4753.2  467.24
  4756.6  465.12  4770.9  467.72  4785.2  467.14  4791.7  464.30  4813.8  466.20
  4820.3  463.51  4842.1  464.83  4848.9  467.97  4855.5  463.09  4863.2  465.34
  4869.8  462.65  4876.4  464.10  4883.8  459.61  4900.2  461.81  4905.8  459.00
  4922.1  459.38  4927.8  455.52  4956.2  453.78  4971.1  452.19  4973.8  451.69
  4977.1  452.19  5067.6  455.31  5102.8  461.33  5247.8  470.80  5493.4  476.77
#Mann=5,-1,0
  4440.2    0.05       0  4956.2    0.16       0  4971.1    0.07       0
  4977.1    0.16       0  5067.6    0.05       0
Bank Sta=4971.1,4977.1
Exp/Cntr=0.3,0.1

Type RM Length L Ch R = 1,1237,325,325,325
BEGIN DESCRIPTION:
Mapping XS 2321bfc9
END DESCRIPTION:
XS GIS Cut Line= 2
      3491693.36     10619351.06      3491937.78     10618513.81
#Sta/Elev= 30
  4582.2  471.36  4621.0  469.26  4650.3  469.25  4666.4  469.30  4693.1  467.31
  4731.8  466.61  4822.7  462.73  4895.6  456.97  4909.5  457.10  4916.5  455.40
  4926.9  455.20  4943.0  451.54  4951.7  451.64  4968.6  450.46  5012.1  450.21
  5014.9  449.71  5018.1  450.21  5048.6  452.28  5062.3  452.30  5077.3  454.38
  5082.1  455.08  5087.3  454.51  5093.6  456.02  5166.5  461.60  5270.7  467.73
  5332.0  468.98  5375.9  467.83  5385.2  468.84  5437.3  466.86  5454.4  467.49
#Mann=6,-1,0
  4582.2    0.08       0  4650.3    0.05       0  4951.7    0.16       0
  5012.1    0.07       0  5018.1    0.16       0  5077.3    0.05       0
Bank Sta=5012.1,5018.1
Exp/Cntr=0.3,0.1

Type RM Length L Ch R = 1,912,14,14,14
BEGIN DESCRIPTION:
Mapping XS cd9caece
END DESCRIPTION:
XS GIS Cut Line= 2
      3491864.87     10619227.62      3492252.42     10618924.51
#Sta/Elev= 30
  4694.7  462.53  4738.8  461.26  4781.5  457.97  4810.4  457.15  4816.8  456.22
  4874.6  453.41  4902.8  453.34  4924.4  452.92  4930.7  451.87  4938.8  452.61
  4945.2  451.15  4953.3  452.61  4959.7  450.76  4974.1  452.36  4988.6  452.15
  4994.9  451.13  5003.1  452.24  5009.4  451.10  5017.5  452.15  5023.9  451.45
  5030.8  452.44  5052.8  452.19  5078.6  450.56  5081.3  450.06  5084.6  450.56
  5108.9  451.84  5131.5  451.96  5137.8  453.36  5166.7  453.19  5186.7  454.39
#Mann=4,-1,0
  4694.7    0.05       0  4902.8    0.16       0  5078.6    0.07       0
  5084.6    0.16       0
Bank Sta=5078.6,5084.6
Exp/Cntr=0.3,0.1

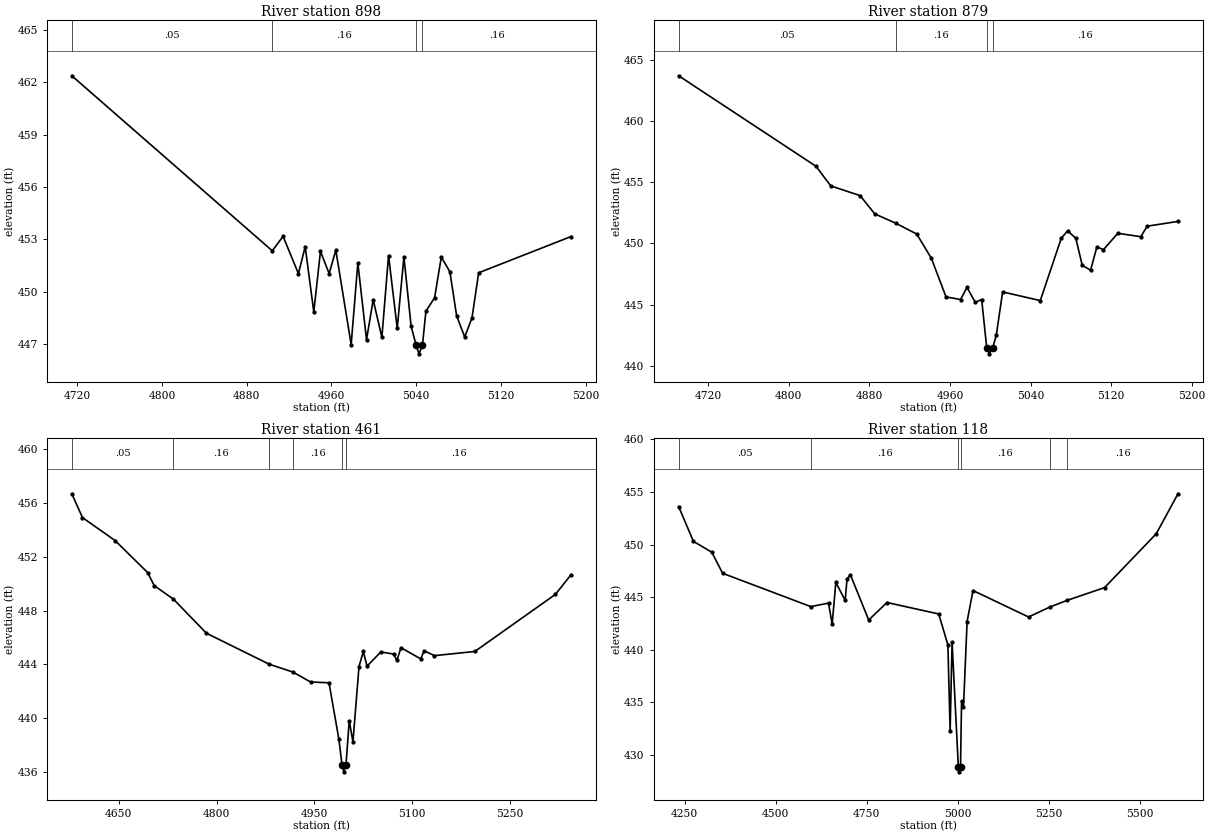
Type RM Length L Ch R = 1,898,19,19,19
BEGIN DESCRIPTION:
Mapping XS c1760cae
END DESCRIPTION:
XS GIS Cut Line= 2
      3491886.54     10619227.21      3492259.00     10618938.10
#Sta/Elev= 30
  4714.8  462.38  4904.1  452.34  4914.3  453.17  4928.8  451.03  4935.2  452.58
  4943.3  448.83  4949.6  452.31  4957.8  451.03  4964.1  452.38  4978.6  446.96
  4984.9  451.64  4993.1  447.24  4999.4  449.53  5007.6  447.37  5013.9  452.07
  5022.1  447.89  5028.4  451.99  5035.2  448.02  5039.9  446.93  5042.6  446.43
  5045.9  446.93  5049.2  448.88  5057.4  449.65  5063.7  451.98  5071.8  451.14
  5078.2  448.61  5085.8  447.40  5092.7  448.49  5099.0  451.08  5186.3  453.16
#Mann=4,-1,0
  4714.8    0.05       0  4904.1    0.16       0  5039.9    0.07       0
  5045.9    0.16       0
Bank Sta=5039.9,5045.9
Exp/Cntr=0.3,0.1

Type RM Length L Ch R = 1,879,418,418,418
BEGIN DESCRIPTION:
Mapping XS 80e6fb64
END DESCRIPTION:
XS GIS Cut Line= 2
      3491873.55     10619255.83      3492268.54     10618956.33
#Sta/Elev= 30
  4690.7  463.69  4827.1  456.29  4841.7  454.69  4870.8  453.90  4885.3  452.41
  4906.0  451.65  4927.0  450.76  4941.5  448.79  4956.1  445.62  4970.6  445.41
  4976.9  446.40  4985.2  445.18  4991.5  445.41  4996.5  441.47  4999.2  440.97
  5002.5  441.47  5006.0  442.49  5012.3  446.03  5049.7  445.32  5070.5  450.41
  5076.8  451.02  5085.0  450.41  5091.3  448.21  5099.6  447.80  5105.9  449.71
  5112.4  449.48  5126.7  450.82  5149.5  450.54  5155.8  451.40  5186.4  451.79
#Mann=4,-1,0
  4690.7    0.05       0  4906.0    0.16       0  4996.5    0.07       0
  5002.5    0.16       0
Bank Sta=4996.5,5002.5
Exp/Cntr=0.3,0.1

Type RM Length L Ch R = 1,461,343,343,343
BEGIN DESCRIPTION:
UNT500 IN CCTC 2.0
END DESCRIPTION:
XS GIS Cut Line= 4
      3492023.28     10619342.63      3492359.66     10619340.46
      3492422.60     10619229.79      3492350.98     10618936.82
#Sta/Elev= 30
  4578.2  456.69  4594.5  454.92  4644.5  453.21  4694.5  450.82  4704.5  449.85
  4733.9  448.85  4784.5  446.31  4880.8  444.00  4917.0  443.42  4944.2  442.68
  4972.4  442.62  4987.5  438.43  4992.4  436.49  4995.2  435.99  4998.4  436.49
  5003.4  439.79  5009.1  438.22  5018.4  443.83  5025.0  444.95  5030.7  443.86
  5051.8  444.91  5071.4  444.76  5076.5  444.29  5082.7  445.23  5113.0  444.40
  5118.2  445.00  5134.1  444.64  5195.9  444.95  5319.4  449.20  5343.5  450.67
#Mann=6,-1,0
  4578.2    0.05       0  4733.9    0.16       0  4880.8    0.05       0
  4917.0    0.16       0  4992.4    0.07       0  4998.4    0.16       0
Bank Sta=4992.4,4998.4
Exp/Cntr=0.3,0.1

Type RM Length L Ch R = 1,118,0,0,0
BEGIN DESCRIPTION:
UNT500 IN CCTC 1.0
END DESCRIPTION:
XS GIS Cut Line= 4
      3492029.34     10619422.21      3492671.73     10619370.12
      3492730.76     10619196.51      3492407.86     10618759.04
#Sta/Elev= 30
  4234.0  453.61  4274.4  450.30  4325.2  449.26  4354.7  447.26  4596.9  444.09
  4645.6  444.42  4655.6  442.42  4665.7  446.39  4691.4  444.68  4696.4  446.72
  4705.8  447.11  4756.0  442.81  4806.1  444.48  4948.3  443.39  4973.5  440.45
  4979.7  432.26  4985.0  440.72  5002.2  428.86  5004.9  428.36  5008.2  428.86
  5011.1  435.12  5016.4  434.54  5026.3  442.67  5042.5  445.62  5195.2  443.10
  5254.3  444.06  5300.8  444.68  5404.0  445.90  5546.0  451.03  5605.6  454.83
#Mann=6,-1,0
  4234.0    0.05       0  4596.9    0.16       0  5002.2    0.07       0
  5008.2    0.16       0  5254.3    0.05       0  5300.8    0.16       0
Bank Sta=5002.2,5008.2
Exp/Cntr=0.3,0.1

Chan Stop Cuts=-1