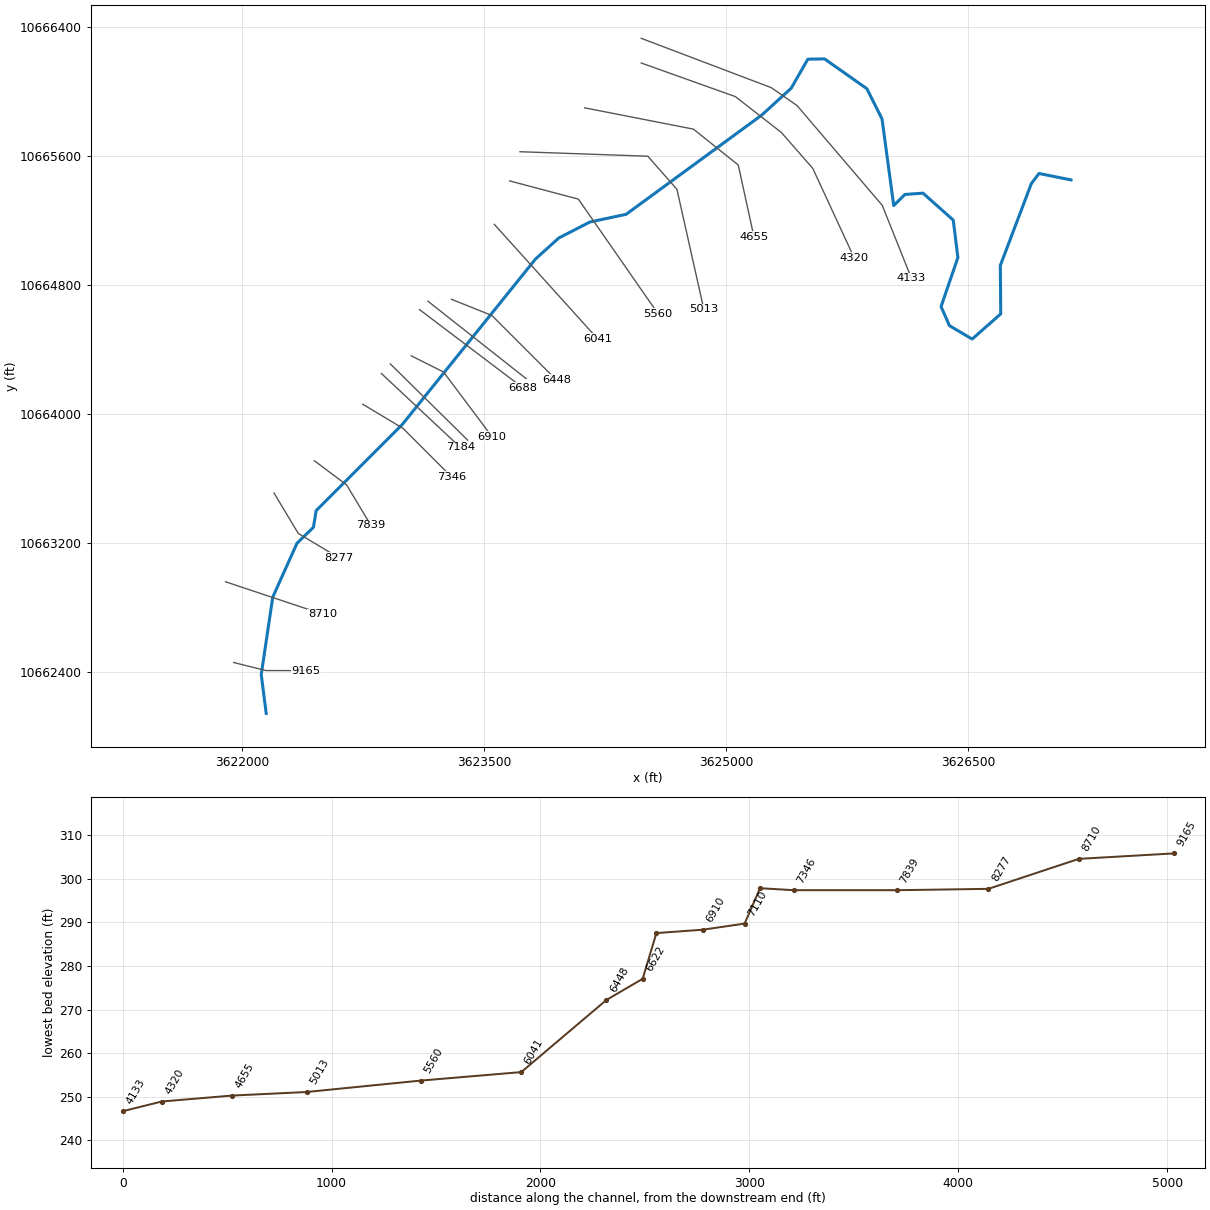
--- UNT502 IN CCTC.prj (project) ---

Proj Title=UNT502 IN CCTC Base Level Engineering
Current Plan=p01
Default Exp/Contr=0.3,0.1
English Units
Geom File=g01
Flow File=f01
Plan File=p01
BEGIN DESCRIPTION:
UNT502 IN CCTC
END DESCRIPTION:

--- UNT502 IN CCTC.p01 (plan) ---

Plan Title=Multiple Run
Short Identifier=Multiple
Geom File=g01
Flow File=f01
Subcritical Flow
K Sum by GR= 0
Std Step Tol= 0.01
Critical Tol= 0.01
Num of Std Step Trials= 20
Max Error Tol= 0.3
Flow Tol Ratio= 0.001
Split Flow NTrial= 30
Split Flow Tol= 0.02
Split Flow Ratio= 0.02
Log Output Level= 0
Friction Slope Method= 1
Unsteady Friction Slope Method= 2
Unsteady Bridges Friction Slope Method= 1
Parabolic Critical Depth
Global Vel Dist=  1 , 1 , 1
Global Log Level= 0
CheckData=True
Encroach Param= -1, 0, 0, 0
BEGIN DESCRIPTION:
Multiple Run
END DESCRIPTION:

--- UNT502 IN CCTC.f01 (steady flow) ---

Flow Title=Multiple
Number of Profiles=7
Profile Names=10-year,25-year,50-year,1pct_min,100-year,1pct_plu,500-year
River Rch & RM= UNT502 IN CCTC,Reach-1,9165
    1227    1668    2028    1800    2435    3293    3495
River Rch & RM= UNT502 IN CCTC,Reach-1,6688
    1744    2420    2982    2680    3625    4902    5337
Boundary for River Rch & Prof#=UNT502 IN CCTC,Reach-1,1
Up Type=0
Dn Type=3
Dn Slope=0.005
Boundary for River Rch & Prof#=UNT502 IN CCTC,Reach-1,2
Up Type=0
Dn Type=3
Dn Slope=0.005
Boundary for River Rch & Prof#=UNT502 IN CCTC,Reach-1,3
Up Type=0
Dn Type=3
Dn Slope=0.005
Boundary for River Rch & Prof#=UNT502 IN CCTC,Reach-1,4
Up Type=0
Dn Type=3
Dn Slope=0.005
Boundary for River Rch & Prof#=UNT502 IN CCTC,Reach-1,5
Up Type=0
Dn Type=3
Dn Slope=0.005
Boundary for River Rch & Prof#=UNT502 IN CCTC,Reach-1,6
Up Type=0
Dn Type=3
Dn Slope=0.005
Boundary for River Rch & Prof#=UNT502 IN CCTC,Reach-1,7
Up Type=0
Dn Type=3
Dn Slope=0.005

--- UNT502 IN CCTC.g01 (geometry) ---

Geom Title=Existing Conditions

River Reach=UNT502 IN CCTC,Reach-1
Reach XY= 30
      3622151.25     10662145.00      3622120.50     10662385.00
      3622191.75     10662865.00      3622342.00     10663199.00
      3622444.00     10663298.00      3622460.75     10663401.00
      3622995.25     10663936.00      3623819.75     10664960.00
      3623963.50     10665090.00      3624156.25     10665189.00
      3624381.25     10665237.00      3625221.75     10665852.00
      3625403.99     10666018.34      3625506.85     10666198.02
      3625610.58     10666199.76      3625872.75     10666015.00
      3625966.50     10665828.00      3626039.00     10665291.00
      3626108.25     10665360.00      3626220.25     10665368.00
      3626407.75     10665201.00      3626436.50     10664969.00
      3626332.25     10664665.00      3626384.25     10664547.00
      3626525.00     10664464.00      3626702.00     10664620.00
      3626699.50     10664920.00      3626892.00     10665428.00
      3626939.00     10665490.00      3627137.25     10665450.00

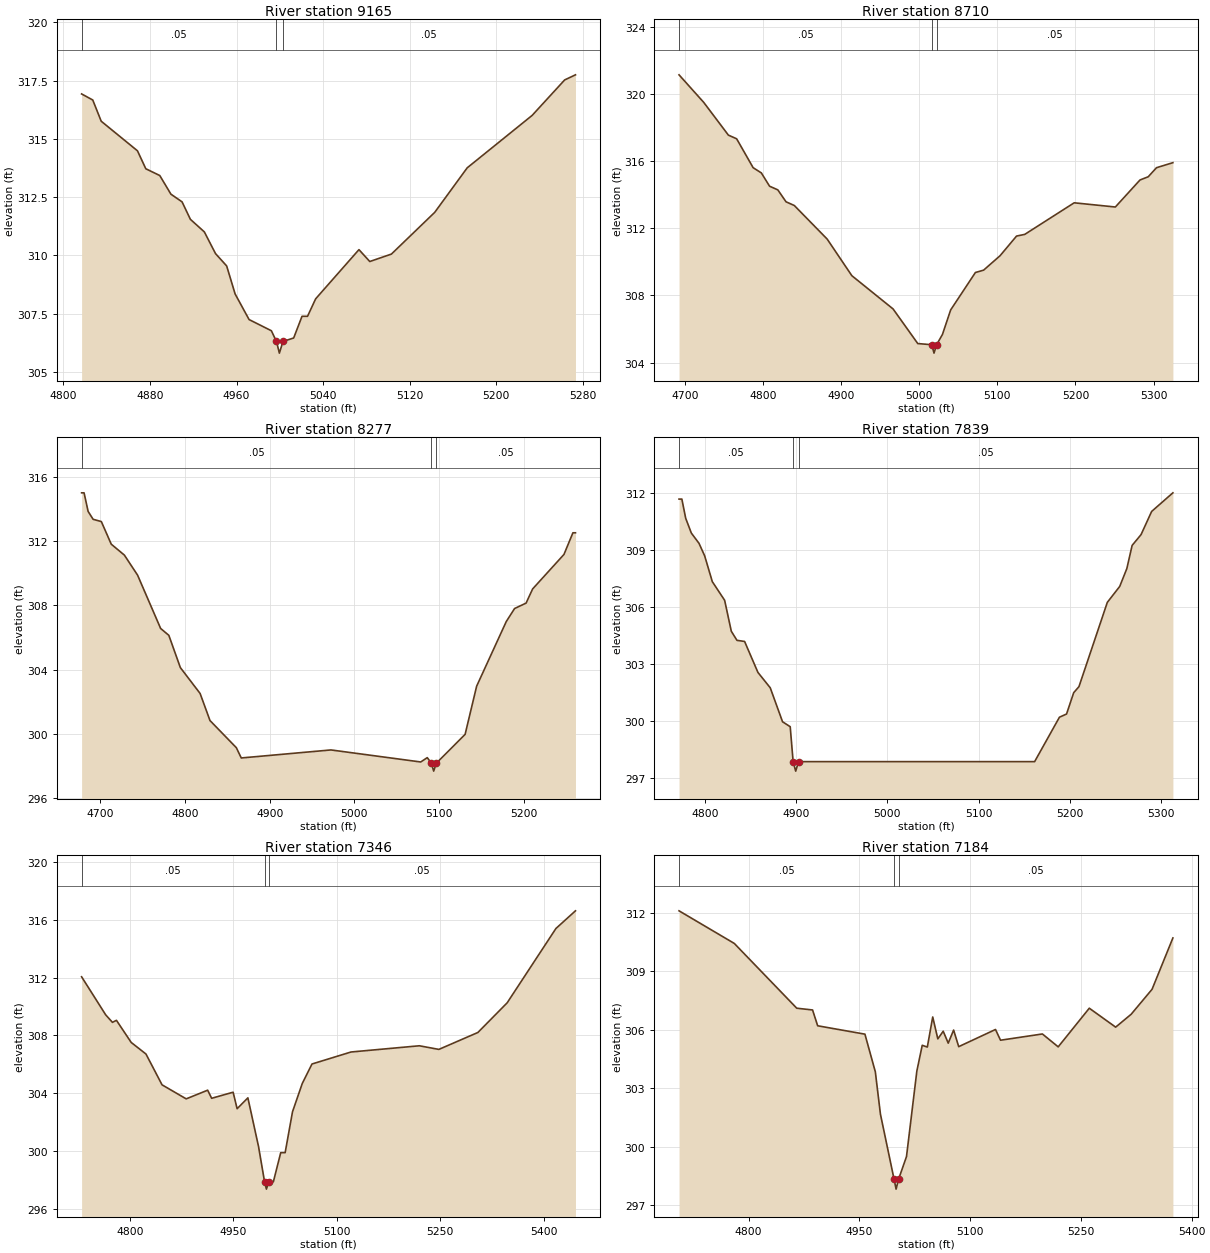
Type RM Length L Ch R = 1,9165,455,455,455
BEGIN DESCRIPTION:
UNT502 IN CCTC 12.0
END DESCRIPTION:
XS GIS Cut Line= 3
      3621949.57     10662460.20      3622149.61     10662410.19
      3622399.62     10662410.19
#Sta/Elev= 30
  4816.9  316.93  4827.2  316.67  4835.0  315.76  4868.5  314.49  4876.2  313.72
  4889.1  313.43  4899.4  312.63  4909.7  312.30  4917.4  311.55  4930.3  311.01
  4940.6  310.08  4950.9  309.55  4958.7  308.35  4971.6  307.25  4992.2  306.77
  4996.9  306.31  4999.6  305.81  5002.9  306.31  5012.8  306.46  5020.5  307.39
  5025.6  307.39  5033.1  308.14  5073.1  310.25  5083.1  309.74  5103.1  310.06
  5143.1  311.85  5173.1  313.76  5233.1  316.01  5263.1  317.53  5273.1  317.75
#Mann=3,-1,0
  4816.9    0.05       0  4996.9    0.03       0  5002.9    0.05       0
Bank Sta=4996.9,5002.9
Exp/Cntr=0.3,0.1

Type RM Length L Ch R = 1,8710,433,433,433
BEGIN DESCRIPTION:
UNT502 IN CCTC 11.0
END DESCRIPTION:
XS GIS Cut Line= 3
      3621899.62     10662960.18      3622199.61     10662860.19
      3622499.57     10662760.20
#Sta/Elev= 30
  4692.4  321.13  4724.0  319.49  4755.6  317.54  4766.2  317.32  4787.3  315.60
  4797.8  315.29  4808.3  314.50  4818.9  314.28  4829.4  313.57  4840.0  313.35
  4882.1  311.35  4913.7  309.17  4966.5  307.19  4998.1  305.13  5016.2  305.06
  5018.9  304.56  5022.2  305.06  5029.7  305.67  5040.2  307.13  5071.9  309.36
  5082.4  309.50  5103.5  310.36  5124.6  311.53  5135.1  311.63  5198.4  313.51
  5251.1  313.26  5282.7  314.87  5293.2  315.06  5303.8  315.60  5324.8  315.90
#Mann=3,-1,0
  4692.4    0.05       0  5016.2    0.03       0  5022.2    0.05       0
Bank Sta=5016.2,5022.2
Exp/Cntr=0.3,0.1

Type RM Length L Ch R = 1,8277,438,438,438
BEGIN DESCRIPTION:
UNT502 IN CCTC 10.0
END DESCRIPTION:
XS GIS Cut Line= 3
      3622199.62     10663510.16      3622349.61     10663260.19
      3622599.64     10663110.17
#Sta/Elev= 30
  4677.9  315.02  4680.8  315.02  4685.6  313.86  4691.5  313.37  4701.2  313.23
  4712.9  311.82  4728.4  311.14  4744.0  309.89  4771.2  306.57  4780.9  306.14
  4794.5  304.13  4817.8  302.52  4829.5  300.83  4860.6  299.14  4866.4  298.50
  4972.3  299.00  5078.3  298.25  5086.0  298.52  5090.8  298.18  5093.6  297.68
  5096.8  298.18  5130.7  299.97  5144.3  302.97  5179.3  307.00  5189.1  307.81
  5202.7  308.15  5210.4  309.03  5247.4  311.18  5258.0  312.53  5261.0  312.53
#Mann=3,-1,0
  4677.9    0.05       0  5090.8    0.03       0  5096.8    0.05       0
Bank Sta=5090.8,5096.8
Exp/Cntr=0.3,0.1

Type RM Length L Ch R = 1,7839,493,493,493
BEGIN DESCRIPTION:
UNT502 IN CCTC 9.0
END DESCRIPTION:
XS GIS Cut Line= 3
      3622449.61     10663710.19      3622649.61     10663560.19
      3622799.59     10663310.22
#Sta/Elev= 30
  4771.6  311.70  4774.7  311.70  4778.9  310.69  4785.1  309.91  4793.5  309.37
  4799.7  308.71  4808.1  307.35  4821.6  306.37  4828.9  304.74  4835.1  304.26
  4843.5  304.20  4858.1  302.57  4871.6  301.76  4885.1  299.97  4893.5  299.71
  4896.7  297.87  4899.5  297.37  4902.7  297.87  5161.5  297.87  5188.7  300.21
  5196.5  300.38  5204.3  301.50  5210.1  301.82  5241.2  306.26  5254.8  307.10
  5262.6  308.04  5268.4  309.26  5278.2  309.83  5289.8  311.05  5313.1  312.03
#Mann=3,-1,0
  4771.6    0.05       0  4896.7   0.033       0  4902.7    0.05       0
Bank Sta=4896.7,4902.7
Exp/Cntr=0.3,0.1

Type RM Length L Ch R = 1,7346,162,162,162
BEGIN DESCRIPTION:
UNT502 IN CCTC 8.0
END DESCRIPTION:
XS GIS Cut Line= 3
      3622749.64     10664060.17      3622999.61     10663910.19
      3623299.63     10663610.17
#Sta/Elev= 30
  4730.3  312.05  4765.2  309.42  4775.0  308.90  4780.8  309.04  4802.2  307.51
  4823.6  306.71  4846.9  304.58  4881.9  303.61  4913.0  304.21  4918.8  303.65
  4949.9  304.07  4955.7  302.93  4971.3  303.68  4986.8  300.30  4995.5  297.87
  4998.2  297.37  5001.5  297.87  5008.2  297.87  5018.9  299.89  5025.3  299.89
  5036.0  302.72  5050.1  304.67  5064.2  306.02  5120.8  306.85  5219.8  307.28
  5248.1  307.03  5304.7  308.20  5347.1  310.25  5417.8  315.39  5446.1  316.61
#Mann=3,-1,0
  4730.3    0.05       0  4995.5    0.03       0  5001.5    0.05       0
Bank Sta=4995.5,5001.5
Exp/Cntr=0.3,0.1

Type RM Length L Ch R = 1,7184,74,74,74
BEGIN DESCRIPTION:
Mapping XS bddc8e7e
END DESCRIPTION:
XS GIS Cut Line= 2
      3622864.79     10664250.84      3623352.96     10663793.83
#Sta/Elev= 30
  4705.9  312.09  4780.7  310.42  4865.3  307.10  4886.7  307.01  4893.6  306.20
  4957.6  305.77  4971.7  303.84  4978.6  301.67  4997.1  298.33  4999.8  297.83
  5003.1  298.33  5013.9  299.50  5027.9  303.88  5035.2  305.20  5042.1  305.11
  5049.4  306.65  5056.3  305.53  5063.6  305.92  5070.4  305.31  5077.7  305.98
  5084.6  305.13  5134.4  306.01  5141.2  305.46  5197.9  305.78  5219.3  305.12
  5261.4  307.10  5297.1  306.13  5318.1  306.79  5346.4  308.07  5374.6  310.70
#Mann=3,-1,0
  4705.9    0.05       0  4997.1    0.03       0  5003.1    0.05       0
Bank Sta=4997.1,5003.1
Exp/Cntr=0.3,0.1

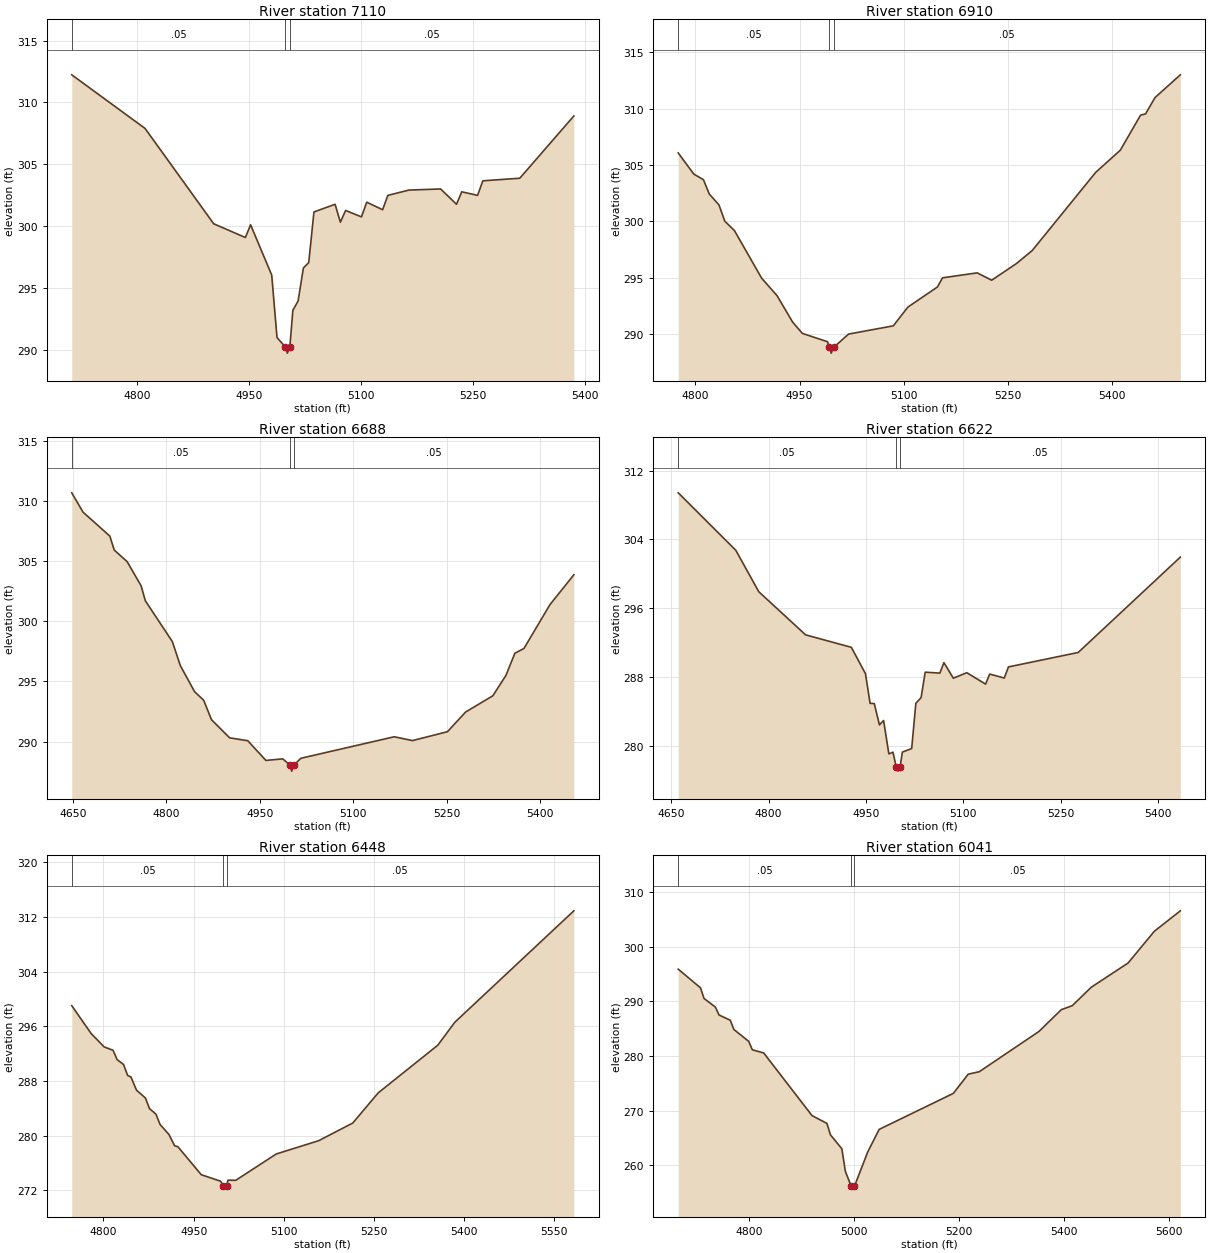
Type RM Length L Ch R = 1,7110,200,200,200
BEGIN DESCRIPTION:
Mapping XS 17a8db91
END DESCRIPTION:
XS GIS Cut Line= 2
      3622920.36     10664309.85      3623399.49     10663837.66
#Sta/Elev= 30
  4712.6  312.24  4810.8  307.90  4902.8  300.18  4945.2  299.07  4952.2  300.10
  4980.5  296.03  4987.6  290.97  4998.8  290.21  5001.5  289.71  5004.8  290.21
  5008.8  293.17  5015.9  293.94  5022.9  296.60  5030.1  297.04  5037.1  301.14
  5065.4  301.76  5072.5  300.31  5079.5  301.26  5100.8  300.74  5107.8  301.93
  5129.1  301.32  5136.1  302.48  5164.4  302.91  5206.8  303.00  5228.1  301.76
  5235.1  302.77  5256.3  302.48  5263.4  303.66  5312.9  303.87  5385.3  308.91
#Mann=3,-1,0
  4712.6    0.05       0  4998.8    0.03       0  5004.8    0.05       0
Bank Sta=4998.8,5004.8
Exp/Cntr=0.3,0.1

Type RM Length L Ch R = 1,6910,222,222,222
BEGIN DESCRIPTION:
UNT502 IN CCTC 7.0
END DESCRIPTION:
XS GIS Cut Line= 3
      3623049.63     10664360.18      3623249.61     10664260.19
      3623549.62     10663860.17
#Sta/Elev= 30
  4775.2  306.07  4797.5  304.20  4811.5  303.70  4819.9  302.43  4833.9  301.46
  4842.3  300.02  4856.2  299.18  4895.4  294.96  4917.7  293.40  4940.1  291.06
  4954.1  290.06  4990.4  289.32  4993.0  288.81  4995.7  288.31  4999.0  288.81
  5020.7  290.00  5085.2  290.73  5106.1  292.39  5148.8  294.18  5156.1  294.99
  5206.1  295.43  5226.9  294.78  5262.3  296.24  5285.2  297.40  5376.9  304.35
  5412.3  306.31  5441.5  309.42  5448.8  309.54  5462.3  310.98  5498.8  313.00
#Mann=3,-1,0
  4775.2    0.05       0  4993.0    0.03       0  4999.0    0.05       0
Bank Sta=4993,4999
Exp/Cntr=0.3,0.1

Type RM Length L Ch R = 1,6688,66,66,66
BEGIN DESCRIPTION:
Mapping XS 118da30b
END DESCRIPTION:
XS GIS Cut Line= 2
      3623100.88     10664646.69      3623743.27     10664160.55
#Sta/Elev= 30
  4648.5  310.70  4666.6  309.09  4709.6  307.10  4716.6  305.94  4737.4  304.97
  4759.8  302.96  4766.5  301.72  4809.9  298.32  4822.7  296.32  4845.6  294.15
  4860.1  293.44  4872.7  291.82  4901.8  290.31  4930.9  290.07  4960.0  288.43
  4987.1  288.56  4998.7  288.04  5001.4  287.54  5004.7  288.04  5016.2  288.61
  5166.0  290.40  5195.1  290.08  5251.3  290.82  5280.5  292.46  5324.1  293.81
  5345.0  295.49  5359.5  297.35  5374.1  297.75  5415.7  301.39  5454.1  303.88
#Mann=3,-1,0
  4648.5    0.05       0  4998.7    0.03       0  5004.7    0.05       0
Bank Sta=4998.7,5004.7
Exp/Cntr=0.3,0.1

Type RM Length L Ch R = 1,6622,174,174,174
BEGIN DESCRIPTION:
Mapping XS 5e4d121f
END DESCRIPTION:
XS GIS Cut Line= 2
      3623153.01     10664698.74      3623760.62     10664219.59
#Sta/Elev= 30
  4660.8  309.42  4749.6  302.73  4784.9  297.92  4857.1  292.90  4927.6  291.45
  4949.4  288.38  4956.5  284.93  4962.9  284.91  4970.9  282.43  4977.3  282.94
  4985.4  279.06  4991.7  279.25  4996.8  277.55  4999.6  277.05  5002.8  277.55
  5006.2  279.26  5020.6  279.68  5027.0  284.94  5035.1  285.60  5041.4  288.56
  5064.0  288.45  5070.3  289.67  5084.8  287.86  5105.6  288.50  5134.5  287.17
  5140.8  288.34  5163.3  287.88  5169.7  289.17  5277.2  290.85  5434.6  301.94
#Mann=3,-1,0
  4660.8    0.05       0  4996.8    0.03       0  5002.8    0.05       0
Bank Sta=4996.8,5002.8
Exp/Cntr=0.3,0.1

Type RM Length L Ch R = 1,6448,407,407,407
BEGIN DESCRIPTION:
UNT502 IN CCTC 6.0
END DESCRIPTION:
XS GIS Cut Line= 3
      3623299.60     10664710.19      3623549.61     10664610.19
      3623949.64     10664210.15
#Sta/Elev= 30
  4747.3  299.02  4779.6  294.93  4801.2  292.98  4816.0  292.49  4822.7  291.13
  4833.5  290.40  4840.2  288.80  4845.6  288.60  4855.0  286.65  4869.8  285.51
  4876.6  283.95  4887.3  283.14  4894.1  281.64  4908.9  280.17  4918.3  278.52
  4923.7  278.38  4962.7  274.28  4995.0  273.32  4998.8  272.67  5001.5  272.17
  5004.8  272.67  5007.1  273.48  5020.1  273.46  5087.3  277.31  5158.0  279.26
  5214.6  281.84  5257.0  286.26  5356.0  293.23  5384.3  296.59  5582.3  312.90
#Mann=3,-1,0
  4747.3    0.05       0  4998.8    0.03       0  5004.8    0.05       0
Bank Sta=4998.8,5004.8
Exp/Cntr=0.3,0.1

Type RM Length L Ch R = 1,6041,481,481,481
BEGIN DESCRIPTION:
UNT502 IN CCTC 5.0
END DESCRIPTION:
XS GIS Cut Line= 2
      3623564.48     10665174.67      3624204.70     10664465.23
#Sta/Elev= 30
  4665.5  295.90  4707.8  292.50  4714.6  290.54  4736.2  288.97  4743.0  287.53
  4764.6  286.55  4771.4  284.87  4799.8  282.68  4806.5  281.15  4828.2  280.57
  4920.1  269.11  4948.5  267.68  4955.2  265.59  4976.9  263.03  4983.6  258.91
  4994.8  256.15  4997.6  255.65  5000.8  256.15  5026.2  262.46  5047.9  266.58
  5189.1  273.17  5217.5  276.69  5238.4  277.13  5352.0  284.50  5394.6  288.49
  5415.6  289.23  5451.4  292.58  5521.7  297.03  5571.7  302.84  5621.1  306.58
#Mann=3,-1,0
  4665.5    0.05       0  4994.8    0.03       0  5000.8    0.05       0
Bank Sta=4994.8,5000.8
Exp/Cntr=0.3,0.1

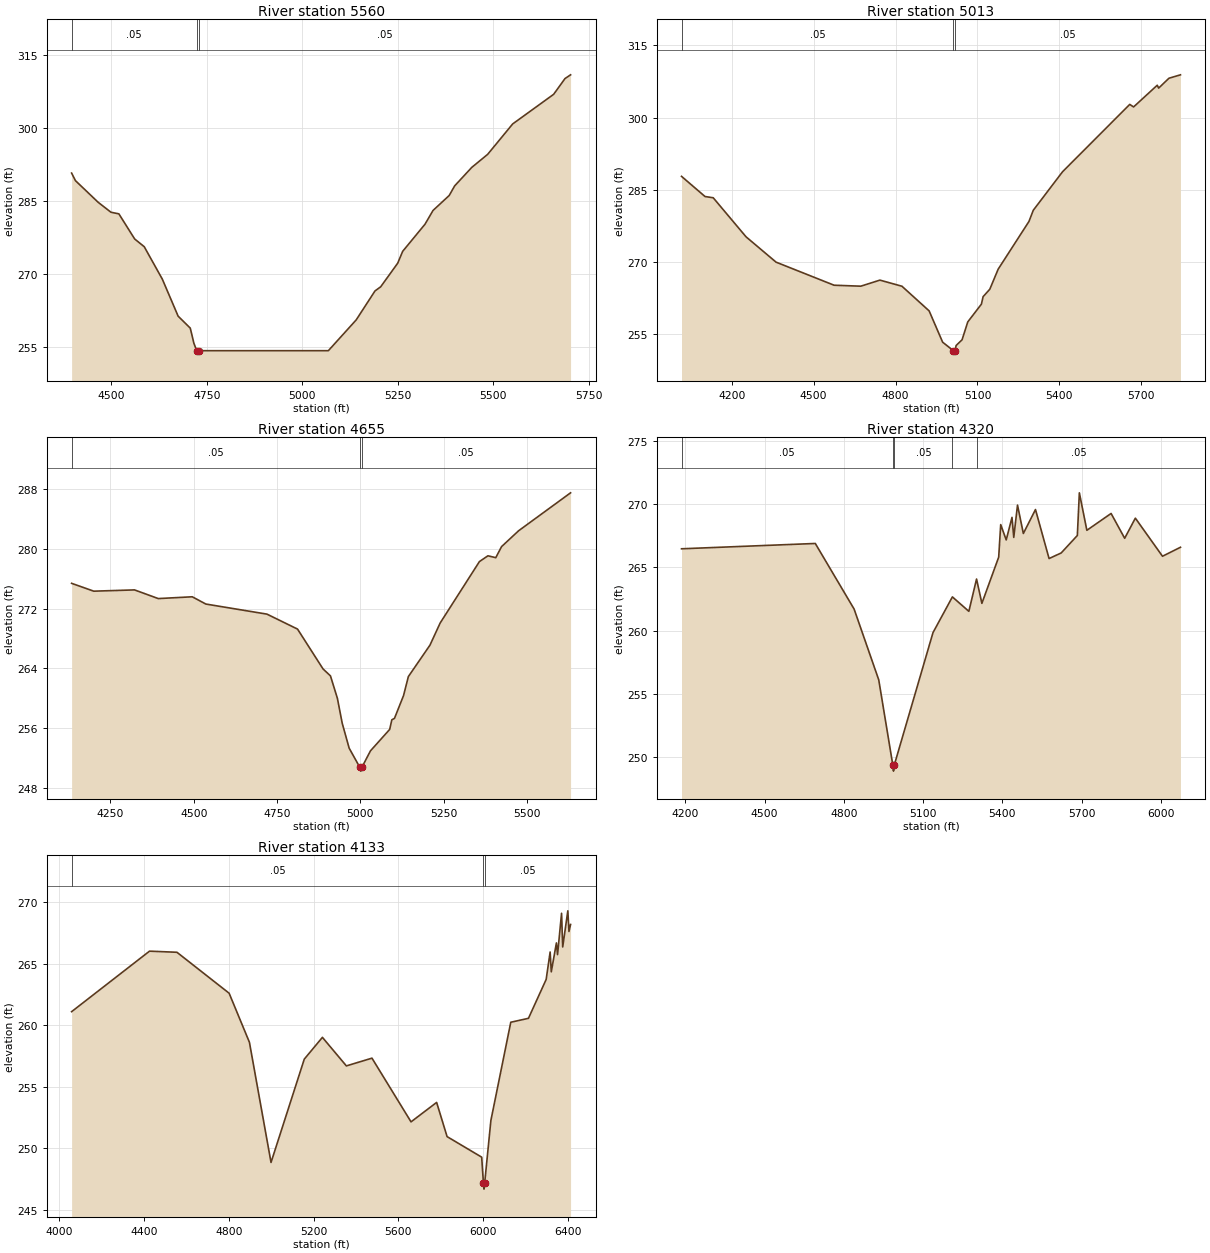
Type RM Length L Ch R = 1,5560,547,547,547
BEGIN DESCRIPTION:
UNT502 IN CCTC 4.0
END DESCRIPTION:
XS GIS Cut Line= 3
      3623659.98     10665443.75      3624085.33     10665330.90
      3624580.09     10664619.13
#Sta/Elev= 30
  4395.8  290.66  4405.8  289.11  4465.4  284.66  4498.9  282.62  4519.6  282.29
  4561.0  277.13  4586.0  275.55  4633.4  268.89  4674.8  261.29  4706.6  258.83
  4716.1  255.73  4723.5  254.20  4726.2  253.70  4729.5  254.20  5068.3  254.20
  5141.2  260.52  5190.5  266.47  5205.4  267.32  5249.9  272.16  5263.0  274.60
  5321.5  280.17  5342.4  282.98  5384.8  286.06  5399.1  288.03  5443.7  291.81
  5485.6  294.51  5551.1  300.75  5658.4  306.83  5688.1  310.06  5702.7  310.83
#Mann=3,-1,0
  4395.8    0.05       0  4723.5   0.033       0  4729.5    0.05       0
Bank Sta=4723.5,4729.5
Exp/Cntr=0.3,0.1

Type RM Length L Ch R = 1,5013,358,358,358
BEGIN DESCRIPTION:
Mapping XS 6e7f114f
END DESCRIPTION:
XS GIS Cut Line= 4
      3623723.61     10665624.68      3624515.25     10665596.91
      3624695.81     10665392.04      3624862.47     10664649.01
#Sta/Elev= 30
  4016.5  287.79  4102.6  283.60  4132.6  283.34  4252.6  275.24  4362.7  269.97
  4575.1  265.18  4672.9  264.98  4742.9  266.24  4823.5  264.97  4923.1  259.85
  4972.5  253.35  5012.1  251.58  5014.9  251.08  5018.1  251.58  5021.8  252.66
  5043.6  253.85  5064.5  257.56  5114.4  261.25  5120.7  262.81  5145.1  264.34
  5175.8  268.51  5288.6  278.43  5304.3  280.74  5411.6  288.75  5657.5  302.73
  5671.6  302.20  5758.2  306.71  5763.4  306.11  5801.0  308.16  5843.2  308.87
#Mann=3,-1,0
  4016.5    0.05       0  5012.1    0.03       0  5018.1    0.05       0
Bank Sta=5012.1,5018.1
Exp/Cntr=0.3,0.1

Type RM Length L Ch R = 1,4655,335,335,335
BEGIN DESCRIPTION:
UNT502 IN CCTC 3.0
END DESCRIPTION:
XS GIS Cut Line= 4
      3624124.38     10665896.62      3624798.00     10665764.67
      3625075.78     10665542.45      3625173.00     10665098.01
#Sta/Elev= 30
  4133.6  275.37  4200.1  274.32  4322.4  274.49  4393.7  273.33  4495.6  273.57
  4536.3  272.60  4719.8  271.25  4811.5  269.25  4887.9  263.93  4910.3  262.99
  4931.1  259.99  4945.5  256.67  4966.3  253.34  4998.5  250.76  5001.3  250.26
  5004.5  250.76  5030.3  252.97  5088.0  255.84  5094.4  257.12  5102.4  257.32
  5129.6  260.37  5144.0  262.90  5208.8  267.10  5239.5  270.07  5357.3  278.28
  5382.8  279.05  5406.3  278.80  5423.7  280.28  5474.9  282.40  5630.7  287.47
#Mann=3,-1,0
  4133.6    0.05       0  4998.5    0.03       0  5004.5    0.05       0
Bank Sta=4998.5,5004.5
Exp/Cntr=0.3,0.1

Type RM Length L Ch R = 1,4320,187,187,187
BEGIN DESCRIPTION:
UNT502 IN CCTC 2.0
END DESCRIPTION:
XS GIS Cut Line= 5
      3624474.87     10666174.37      3625058.24     10665966.03
      3625342.96     10665743.81      3625537.41     10665521.58
      3625794.35     10664966.04
#Sta/Elev= 30
  4185.7  266.46  4691.9  266.88  4838.8  261.70  4932.0  256.11  4985.1  249.40
  4987.8  248.90  4991.1  249.40  5137.3  259.84  5210.7  262.66  5273.0  261.52
  5302.1  264.07  5322.3  262.15  5385.9  265.80  5393.5  268.37  5414.4  267.16
  5436.2  268.94  5442.9  267.36  5457.1  269.91  5479.2  267.67  5525.1  269.56
  5576.5  265.69  5622.3  266.13  5683.5  267.51  5691.1  270.88  5719.5  267.92
  5811.2  269.25  5862.6  267.29  5903.0  268.88  6005.7  265.87  6073.7  266.58
#Mann=5,-1,0
  4185.7    0.05       0  4985.1    0.03       0  4991.1    0.05       0
  5210.7    0.08       0  5302.1    0.05       0
Bank Sta=4985.1,4991.1
Exp/Cntr=0.3,0.1

Type RM Length L Ch R = 1,4133,0,0,0
BEGIN DESCRIPTION:
UNT502 IN CCTC 1.0
END DESCRIPTION:
XS GIS Cut Line= 5
      3624474.86     10666327.16      3625280.46     10666021.58
      3625440.19     10665910.47      3625967.96     10665292.42
      3626148.53     10664841.00
#Sta/Elev= 30
  4057.5  261.10  4425.2  266.02  4554.6  265.93  4801.0  262.60  4896.8  258.61
  4998.8  248.84  5155.7  257.24  5241.3  259.01  5354.4  256.69  5475.2  257.32
  5659.6  252.14  5780.4  253.72  5829.8  250.94  5993.1  249.27  6001.2  247.17
  6004.0  246.67  6007.2  247.17  6036.5  252.25  6130.4  260.24  6213.9  260.56
  6297.4  263.72  6316.2  265.95  6321.6  264.34  6345.8  266.69  6351.2  265.74
  6370.1  269.10  6375.5  266.36  6399.7  269.30  6405.1  267.62  6412.6  268.19
#Mann=3,-1,0
  4057.5    0.05       0  6001.2    0.03       0  6007.2    0.05       0
Bank Sta=6001.2,6007.2
Exp/Cntr=0.3,0.1

Chan Stop Cuts=-1