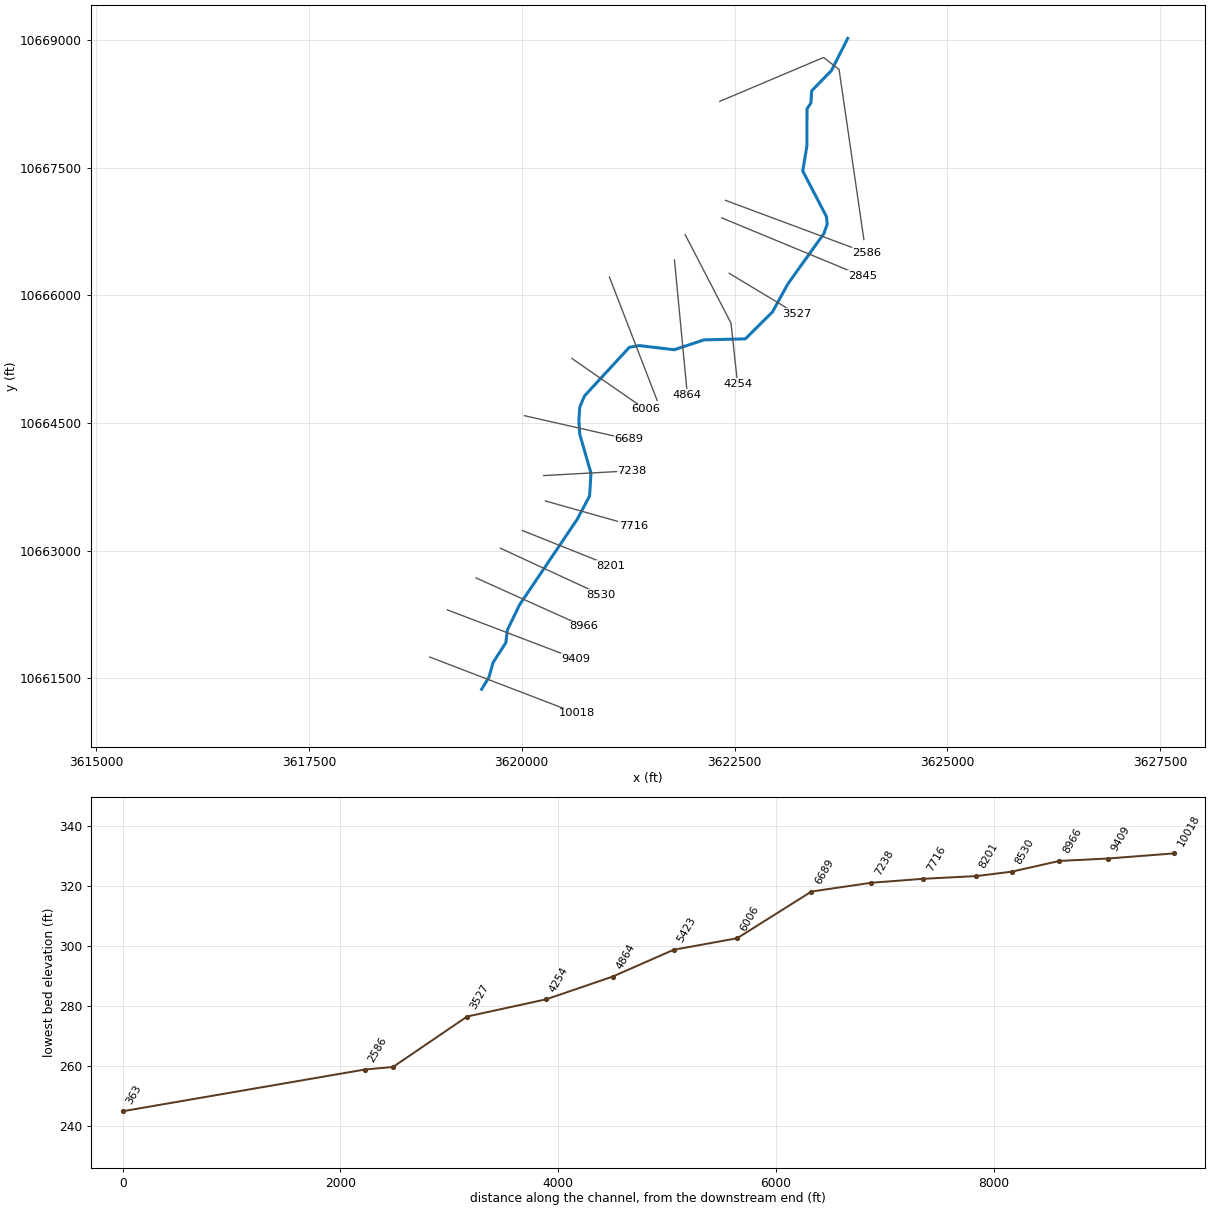
--- UNT503 IN CCTC.prj (project) ---

Proj Title=UNT503 IN CCTC Base Level Engineering
Current Plan=p01
Default Exp/Contr=0.3,0.1
English Units
Geom File=g01
Flow File=f01
Plan File=p01
Y Axis Title=Elevation
X Axis Title(PF)=Main Channel Distance
X Axis Title(XS)=Station
BEGIN DESCRIPTION:
UNT503 IN CCTC
END DESCRIPTION:
DSS Export Rating Curves= 0
DSS Export Rating Curve Sorted= 0
DSS Export Volume Flow Curves= 0
DXF OffsetX= 0
DXF OffsetY= 0
DXF ScaleX= 1
DXF ScaleY= 10

--- UNT503 IN CCTC.p01 (plan) ---

Plan Title=Multiple Run
Short Identifier=Multiple
Geom File=g01
Flow File=f01
Subcritical Flow
K Sum by GR= 0
Std Step Tol= 0.01
Critical Tol= 0.01
Num of Std Step Trials= 20
Max Error Tol= 0.3
Flow Tol Ratio= 0.001
Split Flow NTrial= 30
Split Flow Tol= 0.02
Split Flow Ratio= 0.02
Log Output Level= 0
Friction Slope Method= 1
Unsteady Friction Slope Method= 2
Unsteady Bridges Friction Slope Method= 1
Parabolic Critical Depth
Global Vel Dist=  1 , 1 , 1
Global Log Level= 0
CheckData=True
Encroach Param= -1, 0, 0, 0
BEGIN DESCRIPTION:
Multiple Run
END DESCRIPTION:

--- UNT503 IN CCTC.f01 (steady flow) ---

Flow Title=Multiple
Number of Profiles=7
Profile Names=10-year,25-year,50-year,1pct_min,100-year,1pct_plu,500-year
River Rch & RM= UNT503 IN CCTC,Reach-1,10018
    1956    2739    3397    3072    4155    5619    6195
Boundary for River Rch & Prof#=UNT503 IN CCTC,Reach-1,1
Up Type=0
Dn Type=3
Dn Slope=0.005
Boundary for River Rch & Prof#=UNT503 IN CCTC,Reach-1,2
Up Type=0
Dn Type=3
Dn Slope=0.005
Boundary for River Rch & Prof#=UNT503 IN CCTC,Reach-1,3
Up Type=0
Dn Type=3
Dn Slope=0.005
Boundary for River Rch & Prof#=UNT503 IN CCTC,Reach-1,4
Up Type=0
Dn Type=3
Dn Slope=0.005
Boundary for River Rch & Prof#=UNT503 IN CCTC,Reach-1,5
Up Type=0
Dn Type=3
Dn Slope=0.005
Boundary for River Rch & Prof#=UNT503 IN CCTC,Reach-1,6
Up Type=0
Dn Type=3
Dn Slope=0.005
Boundary for River Rch & Prof#=UNT503 IN CCTC,Reach-1,7
Up Type=0
Dn Type=3
Dn Slope=0.005

--- UNT503 IN CCTC.g01 (geometry) ---

Geom Title=Existing Conditions
Program Version=4.10

River Reach=UNT503 IN CCTC  ,Reach-1
Reach XY= 30
       3619529.5       10661370.        3619616.       10661512.
      3619663.25       10661683.      3619814.25       10661918.
        3619831.       10662065.      3619975.25       10662363.
        3620653.       10663369.        3620797.       10663641.
       3620813.5       10663910.        3620682.       10664366.
      3620671.25       10664530.       3620681.5       10664685.
      3620737.25       10664817.      3621264.25       10665389.
      3621379.25       10665409.      3621790.75       10665360.
       3622140.5       10665476.      3622626.25       10665488.
        3622945.       10665804.       3623125.5       10666133.
      3623548.75       10666725.        3623588.       10666836.
      3623578.75       10666925.       3623300.5       10667461.
        3623349.       10667755.      3623350.75       10668190.
      3623396.75       10668261.      3623405.25       10668403.
       3623637.5       10668641.      3623828.75       10669020.

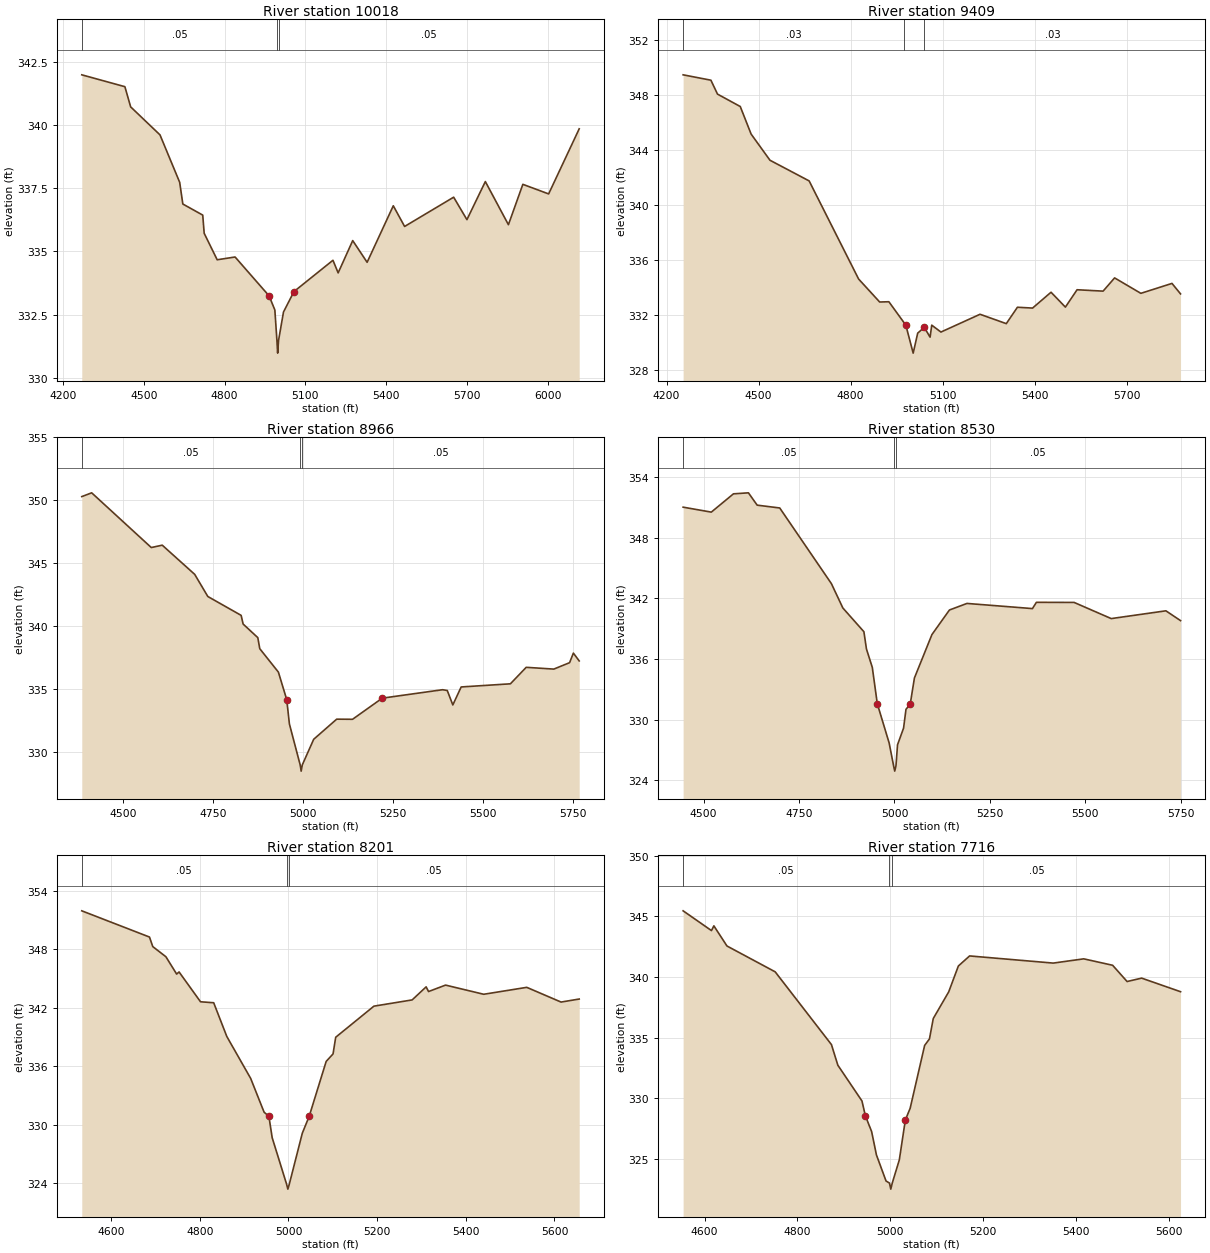
Type RM Length L Ch R = 1 ,10018   ,609,609,609
BEGIN DESCRIPTION:
UNT503 IN CCTC 15.0
END DESCRIPTION:
XS GIS Cut Line= 2
      3618920.12     10661748.01      3620645.04     10661086.25
#Sta/Elev= 30
  4269.4     342  4429.5  341.53  4450.9  340.73  4559.9  339.62    4633  337.74
  4644.7  336.88  4718.7  336.44    4724  335.72  4772.3  334.67  4838.8  334.78
    4965  333.24  4986.5  332.68  4994.2  331.47  4996.9  330.97  5000.2  331.47
  5018.6   332.6  5057.5  333.41  5202.3  334.65  5221.6  334.15  5275.7  335.43
  5329.2  334.57  5426.4  336.81  5468.4  335.99  5650.6  337.15  5699.9  336.26
  5768.3  337.77    5854  336.06  5907.6  337.66  6003.4  337.28  6116.9  339.86
#Mann= 3 ,-1 , 0
  4269.4     .05       0  4994.2     .03       0  5000.2     .05       0
Bank Sta=4965,5057.5
XS Rating Curve= 0 ,0
Exp/Cntr=0.3,0.1

Type RM Length L Ch R = 1 ,9409    ,443,443,443
BEGIN DESCRIPTION:
UNT503 IN CCTC 14.0
END DESCRIPTION:
XS GIS Cut Line= 2
      3619124.98     10662303.26      3620640.47     10661725.18
#Sta/Elev= 30
  4253.9  349.46  4344.5  349.07    4366  348.06  4440.2  347.16  4475.6  345.16
  4537.1  343.26  4664.8  341.76  4826.1  334.64  4894.8  332.97  4924.8  332.99
  4974.3  331.47  4979.7  331.32  5004.1  329.26  5018.8  330.71  5040.2  331.13
  5059.2  330.42  5064.6  331.29  5094.6  330.79  5222.1  332.08  5307.7   331.4
    5344  332.59  5393.4  332.53  5453.6  333.68  5500.4   332.6  5538.5  333.86
  5623.4  333.76  5660.9  334.72  5746.5   333.6    5848  334.32  5875.9  333.56
#Mann= 3 ,-1 , 0
  4253.9     .03       0  4974.3     .01       0  5040.2     .03       0
Bank Sta=4979.7,5040.2
XS Rating Curve= 0 ,0
Exp/Cntr=0.3,0.1

Type RM Length L Ch R = 1 ,8966    ,436,436,436
BEGIN DESCRIPTION:
UNT503 IN CCTC 13.0
END DESCRIPTION:
XS GIS Cut Line= 2
      3619463.47     10662678.28      3620723.92     10662110.56
#Sta/Elev= 30
  4384.7  350.28  4412.2  350.58  4577.9  346.23  4608.3  346.42  4698.5   344.1
    4735  342.34  4827.6  340.84  4833.1  340.15  4873.9  339.07  4879.4  338.19
  4931.1  336.33  4954.3  334.14  4961.7  332.21  4991.6  328.96  4994.4  328.46
  4997.6  328.96  5029.2  330.99  5093.1  332.59  5137.2  332.58  5219.8  334.26
  5387.3  334.93  5400.4  334.87  5415.9  333.72  5439.1  335.15  5575.9   335.4
  5619.8  336.71  5696.6  336.57  5740.4  337.08  5750.9  337.84  5767.1  337.22
#Mann= 3 ,-1 , 0
  4384.7     .05       0  4991.6     .03       0  4997.6     .05       0
Bank Sta=4954.3,5219.8
XS Rating Curve= 0 ,0
Exp/Cntr=0.3,0.1

Type RM Length L Ch R = 1 ,8530    ,329,329,329
BEGIN DESCRIPTION:
UNT503 IN CCTC 12.0
END DESCRIPTION:
XS GIS Cut Line= 2
      3619749.97     10663027.22      3620932.22     10662480.36
#Sta/Elev= 30
  4446.5  351.02  4520.3  350.53  4578.3  352.34  4617.5  352.44  4640.4  351.22
  4699.5  350.94  4834.8  343.45  4864.8  341.04  4919.9  338.69  4926.6  336.98
  4941.9  335.16    4955  331.56    4986  327.68  4997.8  325.39  5000.6  324.89
  5003.8  325.39    5008   327.5  5023.8  329.15  5030.1  331.01  5041.1   331.5
  5052.2  334.11  5098.1  338.41  5143.9  340.84  5189.8  341.49  5361.3  340.98
  5371.6   341.6  5470.4  341.59  5567.6  339.99  5710.7  340.76  5749.1  339.79
#Mann= 3 ,-1 , 0
  4446.5     .05       0  4997.8     .03       0  5003.8     .05       0
Bank Sta=4955,5041.1
XS Rating Curve= 0 ,0
Exp/Cntr=0.3,0.1

Type RM Length L Ch R = 1 ,8201    ,485,485,485
BEGIN DESCRIPTION:
UNT503 IN CCTC 11.0
END DESCRIPTION:
XS GIS Cut Line= 2
      3620007.83     10663235.42      3621049.48     10662818.75
#Sta/Elev= 30
  4533.9  351.96  4686.6  349.27    4694  348.29  4723.6  347.25  4747.9  345.47
  4753.3  345.69  4801.7  342.63  4831.4  342.53    4861  339.07  4914.8  334.77
  4945.1   331.3  4955.9  330.89  4963.3  328.69  4995.9  323.91  4998.7  323.41
  5001.9  323.91  5031.3  329.15  5046.8  330.88  5085.1  336.51  5100.6  337.28
  5106.6  338.99  5192.8  342.18    5279  342.82  5310.6  344.16    5316  343.68
  5354.4  344.34  5440.5   343.4  5537.5  344.11  5614.9   342.6  5655.8  342.91
#Mann= 3 ,-1 , 0
  4533.9     .05       0  4995.9     .03       0  5001.9     .05       0
Bank Sta=4955.9,5046.8
XS Rating Curve= 0 ,0
Exp/Cntr=0.3,0.1

Type RM Length L Ch R = 1 ,7716    ,478,478,478
BEGIN DESCRIPTION:
UNT503 IN CCTC 10.0
END DESCRIPTION:
XS GIS Cut Line= 2
      3620278.66     10663582.64      3621310.45     10663291.04
#Sta/Elev= 30
  4553.7  345.46  4614.8  343.83    4620  344.22  4648.2  342.56  4752.1  340.43
  4873.4  334.43  4887.2  332.73  4939.2  329.78  4946.6  328.55    4960  327.26
  4970.4  325.33  4991.1  323.18  4998.5  323.01  5001.3  322.51  5004.5  323.01
  5019.7  324.92  5032.7  328.21  5043.1  329.18  5074.3  334.36  5084.7   334.9
  5092.9  336.58  5126.2  338.78    5147  340.91  5171.2  341.74  5351.5  341.15
  5417.2   341.5  5479.5  340.97  5510.7  339.63  5542.1  339.91  5625.9  338.79
#Mann= 3 ,-1 , 0
  4553.7     .05       0  4998.5     .03       0  5004.5     .05       0
Bank Sta=4946.6,5032.7
XS Rating Curve= 0 ,0
Exp/Cntr=0.3,0.1

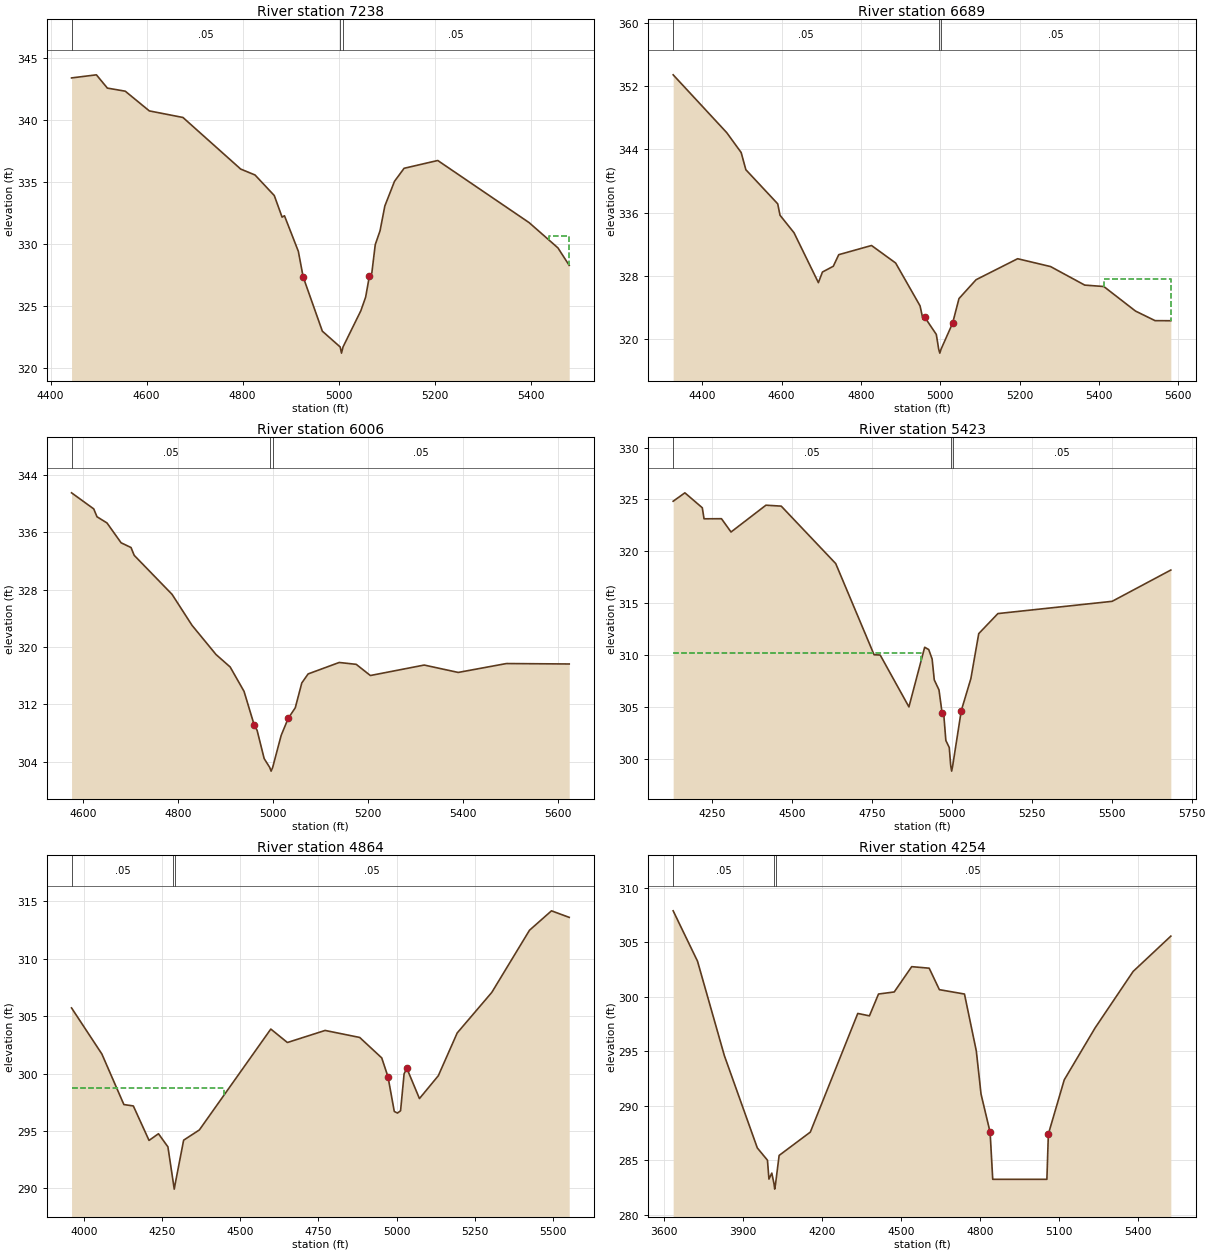
Type RM Length L Ch R = 1 ,7238    ,549,549,549
BEGIN DESCRIPTION:
UNT503 IN CCTC 9.0
END DESCRIPTION:
XS GIS Cut Line= 3
      3620257.84     10663881.25      3620975.98      10663920.4
       3621293.1     10663937.75
#Sta/Elev= 30
  4443.8  343.39  4495.6  343.64  4518.4  342.57  4555.7  342.32  4605.8  340.73
  4675.9   340.2  4796.1  336.04  4826.1  335.56  4866.2   333.9  4882.4  332.16
  4887.4  332.27  4916.3   329.4  4926.3  327.34  4966.3  322.96  5003.4  321.69
  5006.2  321.19  5009.4  321.69  5046.5  324.61  5056.5  325.71  5064.3   327.4
  5069.4  327.66  5076.5  329.94  5086.5  331.06  5096.5  333.06  5116.6  335.05
  5136.6   336.1  5206.7  336.73    5397  331.72  5457.1  329.68  5480.6  328.27
#Mann= 3 ,-1 , 0
  4443.8     .05       0  5003.4     .03       0  5009.4     .05       0
#XS Ineff= 2 , 0
                         5437.73          330.64
Permanent Ineff=
       F       F
Bank Sta=4926.3,5064.3
XS Rating Curve= 0 ,0
Exp/Cntr=0.3,0.1

Type RM Length L Ch R = 1 ,6689    ,683,683,683
BEGIN DESCRIPTION:
UNT503 IN CCTC 8.0
END DESCRIPTION:
XS GIS Cut Line= 2
      3620032.41     10664584.99      3621256.46      10664307.1
#Sta/Elev= 30
  4326.3   353.4  4461.4   346.1  4497.8  343.59  4509.6  341.42    4590  337.11
  4595.8  335.67  4631.1  333.46  4692.6  327.16  4702.8   328.5  4730.2  329.23
  4743.9  330.69  4826.6  331.85  4887.4  329.64    4949  324.23  4955.9  322.63
    4961  322.78    4990  320.62    4996  318.76  4998.8  318.26    5002  318.76
    5031  322.03  5047.2  325.15  5090.3  327.53  5195.1  330.18  5278.1  329.19
  5364.3  326.85  5412.5  326.67  5492.4  323.57  5541.8  322.36  5581.5  322.35
#Mann= 3 ,-1 , 0
  4326.3     .05       0    4996     .03       0    5002     .05       0
#XS Ineff= 2 , 0
                         5412.27          327.57
Permanent Ineff=
       F       F
Bank Sta=4961,5031
XS Rating Curve= 0 ,0
Exp/Cntr=0.3,0.1

Type RM Length L Ch R = 1 ,6006    ,583,583,583
BEGIN DESCRIPTION:
UNT503 IN CCTC 7.0
END DESCRIPTION:
XS GIS Cut Line= 2
       3620591.2     10665256.22      3621452.28     10664659.02
#Sta/Elev= 30
  4576.1  341.52  4622.8  339.28  4629.7  338.18  4650.7  337.32  4680.4  334.55
  4701.3  333.89    4708   332.8  4787.8  327.35  4829.7  323.04  4880.3  318.96
  4910.1  317.22  4939.3  313.82  4960.7  309.12  4966.8  308.38  4981.7  304.44
  4993.5  303.19  4996.3  302.69  4999.5  303.19  5017.5  307.68  5032.3  310.05
  5047.2  311.53  5060.9  314.99  5074.2  316.25  5139.7  317.85  5175.5  317.59
  5205.3  316.03  5318.7  317.49  5390.3  316.46  5491.7   317.7    5624  317.64
#Mann= 3 ,-1 , 0
  4576.1     .05       0  4993.5     .03       0  4999.5     .05       0
Bank Sta=4960.7,5032.3
XS Rating Curve= 0 ,0
Exp/Cntr=0.3,0.1

Type RM Length L Ch R = 1 ,5423    ,559,559,559
BEGIN DESCRIPTION:
UNT503 IN CCTC 6.0
END DESCRIPTION:
XS GIS Cut Line= 2
      3621029.86     10666215.25      3621590.78     10664764.19
#Sta/Elev= 30
  4129.2  324.83  4165.8  325.64  4220.3   324.2  4225.7  323.14  4280.2  323.15
  4310.1  321.87  4419.2  324.45    4467  324.36  4637.4  318.83  4757.2  310.06
  4776.4  310.03  4866.2  305.04  4915.4  310.78    4928  310.56  4938.7  309.65
  4945.4  307.64  4960.1  306.68    4970  304.43  4975.3  304.23  4981.6  301.81
  4992.3  301.13  4996.9  299.36  4999.7  298.86  5002.9  299.36  5029.9  304.69
  5059.8  307.76  5084.4  312.09  5144.3  314.02  5501.5   315.2  5684.9  318.21
#Mann= 3 ,-1 , 0
  4129.2     .05       0  4996.9    .035       0  5002.9     .05       0
#XS Ineff= 2 , 0
         4903.07   310.2
Permanent Ineff=
       F       F
Bank Sta=4970,5029.9
XS Rating Curve= 0 ,0
Exp/Cntr=0.3,0.1

Type RM Length L Ch R = 1 ,4864    ,610,610,610
BEGIN DESCRIPTION:
UNT503 IN CCTC 5.0
END DESCRIPTION:
XS GIS Cut Line= 2
      3621793.76     10666416.64      3621945.21     10664833.87
#Sta/Elev= 30
  3961.2  305.71  4058.1   301.7  4128.4   297.3  4158.6  297.18  4208.8  294.18
  4238.9  294.76  4269.1  293.62  4286.6  290.44  4289.3  289.94  4292.6  290.44
  4319.3   294.2  4369.5  295.09  4597.8  303.87  4650.8   302.7  4771.3  303.75
  4881.8  303.14  4952.2  301.36  4972.2  299.72  4992.3   296.7  5002.4  296.56
  5012.4  296.76  5023.7  299.98  5032.5  300.45  5072.7  297.82    5133  299.81
  5193.3  303.53  5303.8  307.06  5424.3  312.47  5494.6  314.16  5551.2  313.59
#Mann= 3 ,-1 , 0
  3961.2     .05       0  4286.6     .03       0  4292.6     .05       0
#XS Ineff= 2 , 0
         4447.39   298.7
Permanent Ineff=
       F       F
Bank Sta=4972.2,5032.5
XS Rating Curve= 0 ,0
Exp/Cntr=0.3,0.1

Type RM Length L Ch R = 1 ,4254    ,727,727,727
BEGIN DESCRIPTION:
UNT503 IN CCTC 4.0
END DESCRIPTION:
XS GIS Cut Line= 3
      3621919.79     10666712.94      3622457.72     10665673.25
       3622535.6     10664957.68
#Sta/Elev= 30
    3635  307.89  3727.5  303.27  3829.5  294.61  3954.6  286.15  3993.2  285.02
  3998.8  283.29  4009.7  283.84    4018  282.87  4020.7  282.37    4024  282.87
  4037.5  285.46    4156   287.6  4336.2  298.48  4380.5  298.26    4415  300.26
  4474.7  300.45  4541.1  302.77  4607.5  302.63  4646.2  300.66  4741.5  300.26
  4786.5  295.04  4804.5  291.08  4838.9  287.59  4848.9  283.27  5054.6  283.27
  5060.2  287.42  5120.5  292.39  5237.6  297.15  5382.1  302.33  5525.4  305.57
#Mann= 3 ,-1 , 0
    3635     .05       0    4018     .03       0    4024     .05       0
#XS Ineff= 2 , 0
         4223.01  291.56
Permanent Ineff=
       F       F
Bank Sta=4838.9,5060.2
XS Rating Curve= 0 ,0
Exp/Cntr=0.3,0.1

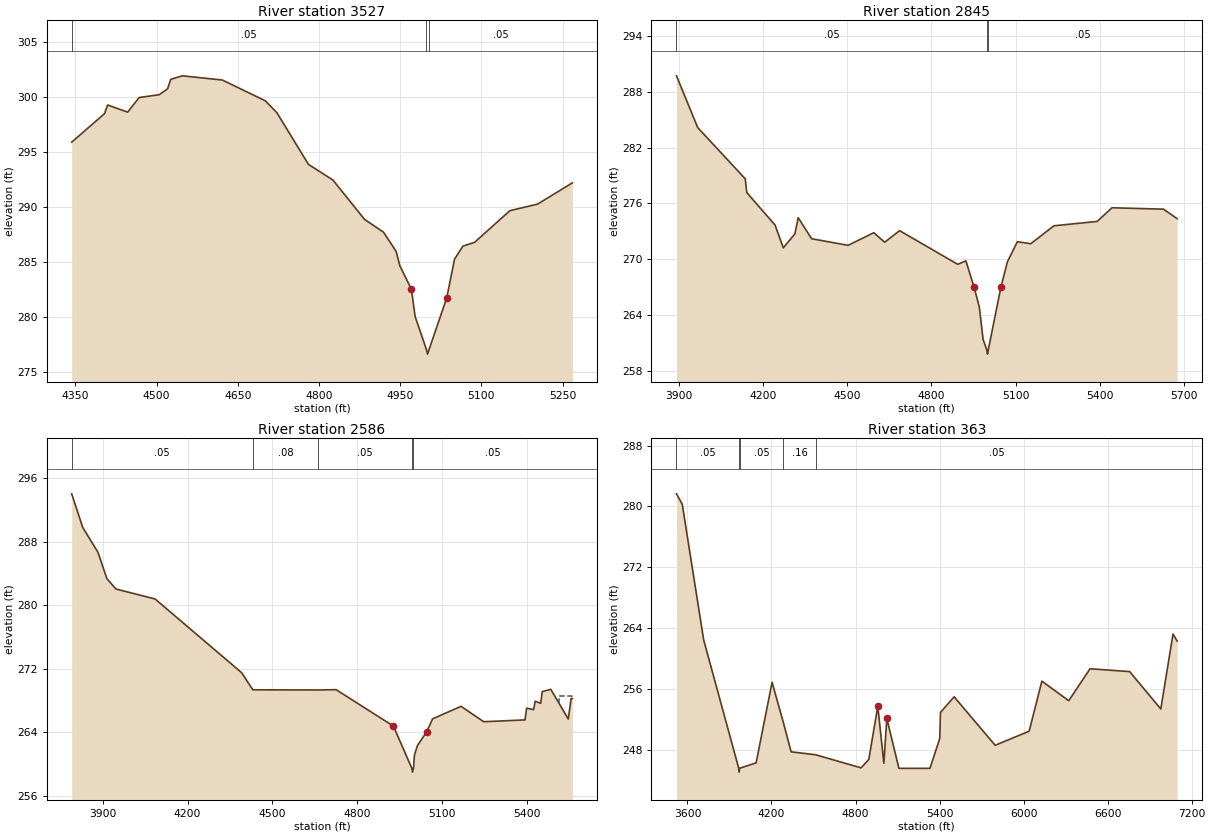
Type RM Length L Ch R = 1 ,3527    ,682,682,682
BEGIN DESCRIPTION:
Mapping XS b5296ef8
END DESCRIPTION:
XS GIS Cut Line= 2
      3622436.36     10666258.68      3623228.41     10665781.28
#Sta/Elev= 30
  4343.2   295.9  4403.8  298.49  4409.6  299.28  4446.5  298.63  4467.9  299.96
  4504.8  300.21  4520.3  300.75  4526.1  301.61  4547.5  301.93  4621.3  301.55
  4700.9  299.66  4722.2  298.58  4780.5  293.88  4825.7  292.46  4884.1  288.88
  4919.1  287.72  4942.5  285.97  4949.4  284.65  4970.8  282.52  4977.5  280.06
  4997.9  277.13  5000.6  276.63  5003.9  277.13  5035.9  281.73  5050.4  285.27
  5065.9  286.45  5087.3  286.79  5152.6  289.67  5203.8  290.27    5268   292.2
#Mann= 3 ,-1 , 0
  4343.2     .05       0  4997.9     .03       0  5003.9     .05       0
Bank Sta=4970.8,5035.9
XS Rating Curve= 0 ,0
Exp/Cntr=0.3,0.1

Type RM Length L Ch R = 1 ,2845    ,259,259,259
BEGIN DESCRIPTION:
UNT503 IN CCTC 3.0
END DESCRIPTION:
XS GIS Cut Line= 2
      3622349.55     10666909.73       3623998.8     10666226.16
#Sta/Elev= 30
  3890.7  289.73  3966.5  284.16    4136  278.65  4141.4  277.17  4242.3  273.68
  4271.6  271.23  4312.9  272.73  4324.8  274.47  4372.6  272.21  4502.8   271.5
  4594.4  272.86  4633.1  271.83  4686.2  273.08  4893.5  269.46  4922.8  269.83
  4952.1  266.98  4970.6  264.87  4984.1  261.37  4996.9   260.3  4999.7   259.8
  5002.9   260.3  5047.7  267.02  5070.7  269.72  5106.3  271.89    5154  271.67
  5236.5   273.6  5390.6  274.07  5443.8  275.54  5627.2  275.39    5676  274.37
#Mann= 3 ,-1 , 0
  3890.7     .05       0  4996.9     .03       0  5002.9     .05       0
Bank Sta=4952.1,5047.7
XS Rating Curve= 0 ,0
Exp/Cntr=0.3,0.1

Type RM Length L Ch R = 1 ,2586    ,2223,2223,2223
BEGIN DESCRIPTION:
UNT503 IN CCTC 2.0
END DESCRIPTION:
XS GIS Cut Line= 2
      3622392.95      10667115.9      3624053.08     10666497.41
#Sta/Elev= 30
  3790.1  294.02  3829.2  289.78    3883  286.66  3914.6  283.34  3946.6  282.03
  4085.3  280.77  4391.6  271.48    4431  269.33  4661.8  269.31  4725.6  269.35
  4928.4  264.76  4993.5  259.46  4996.2  258.96  4999.5  259.46  5003.1  261.14
  5013.8  262.33  5045.8  264.01  5067.1  265.67  5167.8  267.25  5248.1  265.31
  5394.4  265.54  5399.7  267.01  5424.7  266.84  5430.1  267.89  5449.7  267.63
  5455.1   269.1  5485.4  269.39  5547.3  265.65  5557.2  268.22  5561.7  268.22
#Mann= 5 ,-1 , 0
  3790.1     .05       0    4431     .08       0  4661.8     .05       0
  4993.5     .03       0  4999.5     .05       0
#XS Ineff= 2 , 0
                         5515.62          268.57
Permanent Ineff=
       F       F
Bank Sta=4928.4,5045.8
XS Rating Curve= 0 ,0
Exp/Cntr=0.3,0.1

Type RM Length L Ch R = 1 ,363     ,0,0,0
BEGIN DESCRIPTION:
UNT503 IN CCTC 1.0
END DESCRIPTION:
XS GIS Cut Line= 4
      3622325.99     10668279.31      3623544.74     10668794.94
      3623727.03     10668654.31      3624018.64     10666654.73
#Sta/Elev= 30
  3521.7  281.66    3563  280.28    3716  262.44  3966.2  245.57    3969  245.07
  3972.2  245.57  4090.3  246.29  4204.2  256.89  4284.9  251.59    4340  247.74
  4516.1  247.35  4839.5  245.63  4894.6  246.74  4958.9  253.71  5002.4  246.23
  5023.2  252.13  5109.7  245.57  5331.4  245.57  5401.4  249.51  5406.4  252.92
  5503.9  254.97  5796.9   248.6  6039.5  250.45  6130.4  257.03  6322.4  254.46
    6474  258.66    6757  258.29  6979.3  253.37  7066.7  263.23    7096   262.3
#Mann= 5 ,-1 , 0
  3521.7     .05       0  3966.2     .03       0  3972.2     .05       0
  4284.9     .16       0  4516.1     .05       0
Bank Sta=4958.9,5023.2
XS Rating Curve= 0 ,0
Exp/Cntr=0.3,0.1

Chan Stop Cuts=-1
Use User Specified Reach Order=0
Composite Channel Slope=5