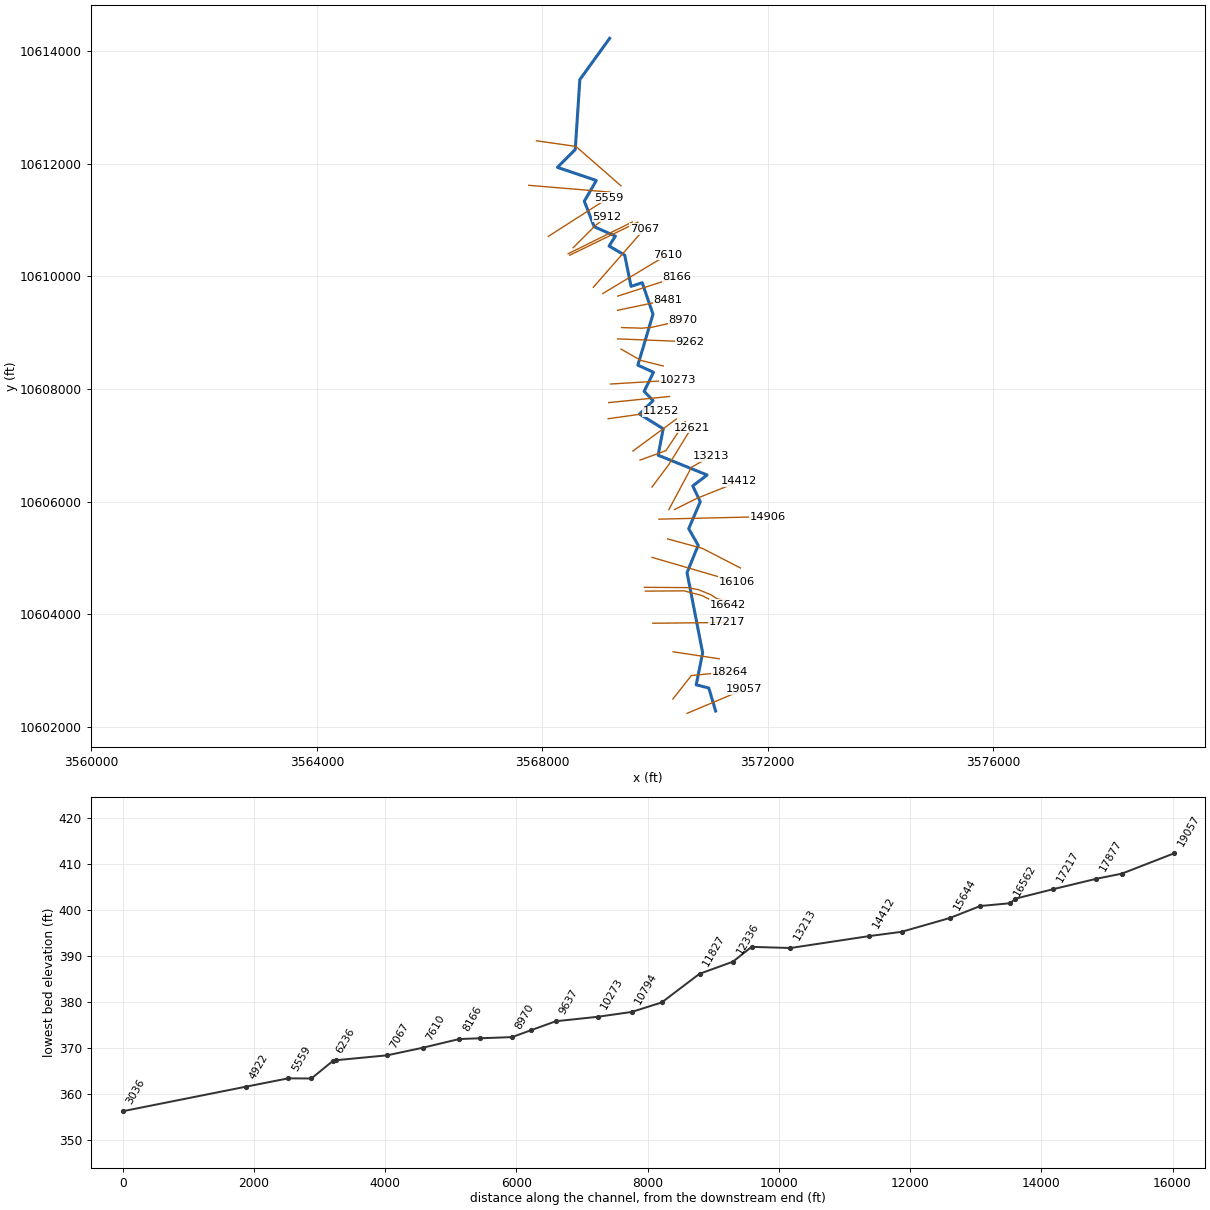
--- WALTHALL CREEK.prj (project) ---

Proj Title=WALTHALL CREEK Base Level Engineering
Current Plan=p01
Default Exp/Contr=0.3,0.1
English Units
Geom File=g01
Flow File=f01
Plan File=p01
Y Axis Title=Elevation
X Axis Title(PF)=Main Channel Distance
X Axis Title(XS)=Station
BEGIN DESCRIPTION:
WALTHALL CREEK
END DESCRIPTION:
DSS Export Rating Curves= 0
DSS Export Rating Curve Sorted= 0
DSS Export Volume Flow Curves= 0
DXF OffsetX= 0
DXF OffsetY= 0
DXF ScaleX= 1
DXF ScaleY= 10

--- WALTHALL CREEK.p01 (plan) ---

Plan Title=Multiple Run
Short Identifier=Multiple
Geom File=g01
Flow File=f01
Subcritical Flow
K Sum by GR= 0
Std Step Tol= 0.01
Critical Tol= 0.01
Num of Std Step Trials= 20
Max Error Tol= 0.3
Flow Tol Ratio= 0.001
Split Flow NTrial= 30
Split Flow Tol= 0.02
Split Flow Ratio= 0.02
Log Output Level= 0
Friction Slope Method= 1
Unsteady Friction Slope Method= 2
Unsteady Bridges Friction Slope Method= 1
Parabolic Critical Depth
Global Vel Dist=  1 , 1 , 1
Global Log Level= 0
CheckData=True
Encroach Param= -1, 0, 0, 0
BEGIN DESCRIPTION:
Multiple Run
END DESCRIPTION:

--- WALTHALL CREEK.f01 (steady flow) ---

Flow Title=Multiple
Program Version=4.10
Number of Profiles= 7
Profile Names=10-year,25-year,50-year,1pct_min,100-year,1pct_plu,500-year
River Rch & RM=WALTHALL CREEK,Reach-1         ,19057
    2105    2946    3652    3300    4463    6035    6641
River Rch & RM=WALTHALL CREEK,Reach-1         ,11252
    2663    3757    4682    4247    5744    7768    8620
Boundary for River Rch & Prof#=WALTHALL CREEK,Reach-1         , 1
Up Type= 0
Dn Type= 3
Dn Slope=0.00292
Boundary for River Rch & Prof#=WALTHALL CREEK,Reach-1         , 2
Up Type= 0
Dn Type= 3
Dn Slope=0.00292
Boundary for River Rch & Prof#=WALTHALL CREEK,Reach-1         , 3
Up Type= 0
Dn Type= 3
Dn Slope=0.00292
Boundary for River Rch & Prof#=WALTHALL CREEK,Reach-1         , 4
Up Type= 0
Dn Type= 3
Dn Slope=0.00292
Boundary for River Rch & Prof#=WALTHALL CREEK,Reach-1         , 5
Up Type= 0
Dn Type= 3
Dn Slope=0.00292
Boundary for River Rch & Prof#=WALTHALL CREEK,Reach-1         , 6
Up Type= 0
Dn Type= 3
Dn Slope=0.00292
Boundary for River Rch & Prof#=WALTHALL CREEK,Reach-1         , 7
Up Type= 0
Dn Type= 3
Dn Slope=0.00292
DSS Import GetInterval= 0
DSS Import GetPeak= 0
DSS Import FillOption= 0

--- WALTHALL CREEK.g01 (geometry) ---

Geom Title=Existing Conditions
Program Version=4.10

River Reach=WALTHALL CREEK  ,Reach-1
Reach XY= 30
       3571079.5       10602281.      3570957.75       10602690.
       3570734.5       10602747.        3570849.       10603315.
      3570571.75       10604740.      3570769.75       10605225.
       3570601.5       10605520.        3570807.       10605999.
        3570673.       10606279.      3570927.75       10606474.
        3570059.       10606825.       3570148.5       10607295.
       3569729.5       10607556.       3569969.5       10607795.
       3569810.5       10607959.       3569976.5       10608299.
      3569698.75       10608425.       3569967.5       10609329.
       3569776.5       10609889.      3569577.75       10609824.
      3569465.75       10610378.       3569188.5       10610541.
        3569300.       10610717.      3568923.75       10610884.
      3568748.75       10611337.       3568961.5       10611705.
        3568271.       10611939.       3568587.5       10612255.
        3568669.       10613497.        3569198.       10614230.

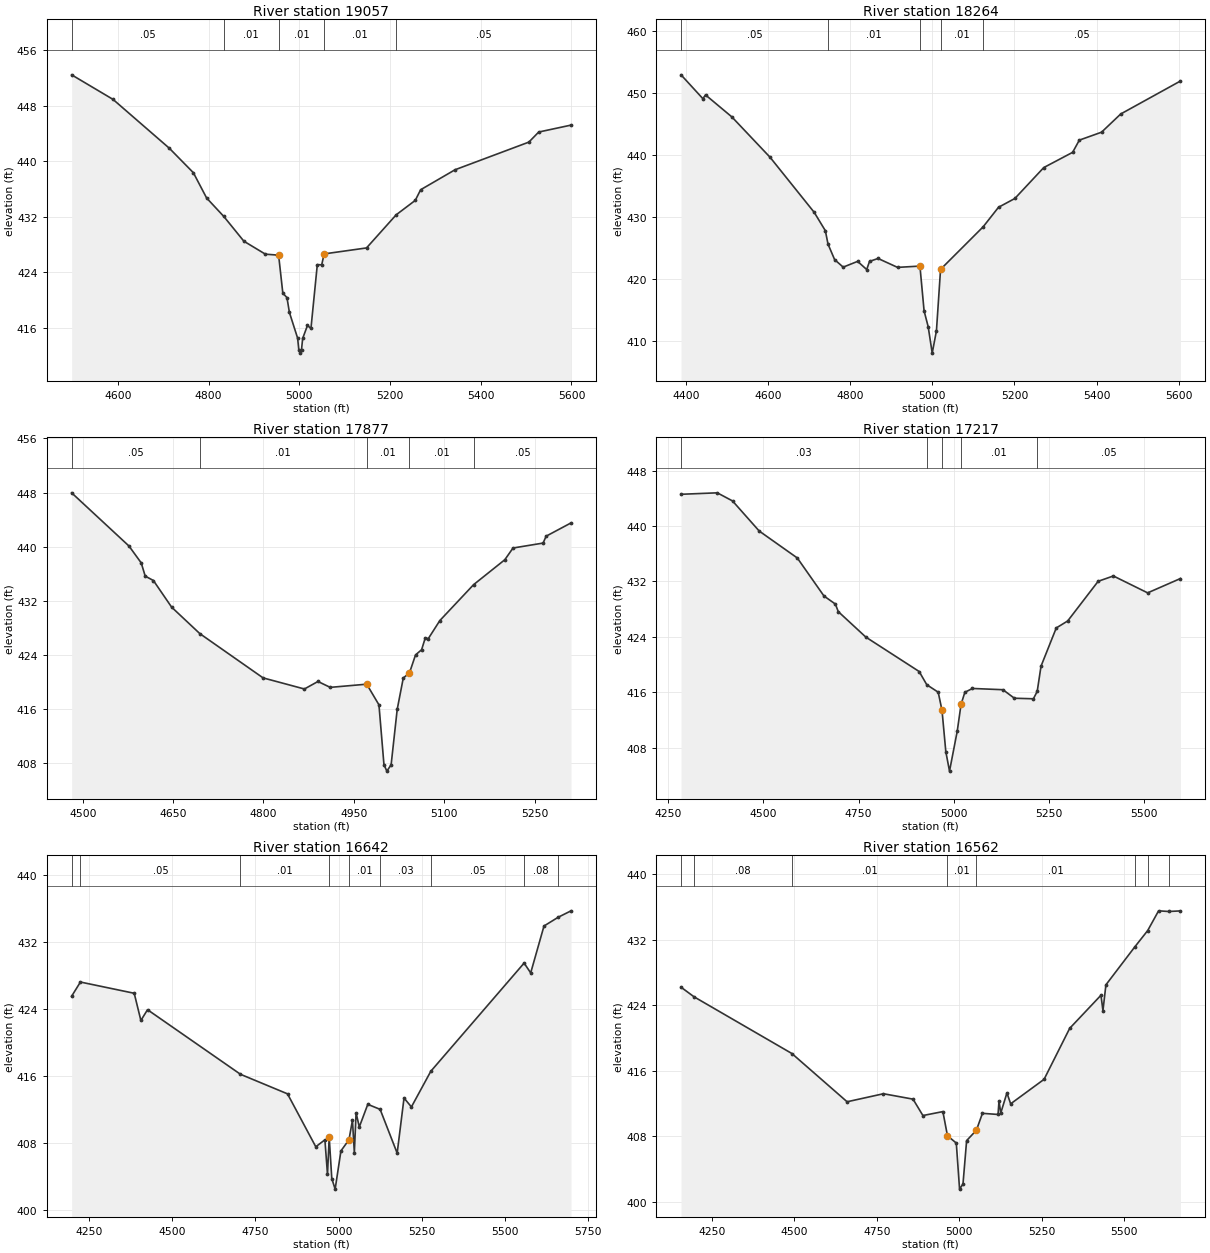
Type RM Length L Ch R = 1 ,19057   ,793,793,793
BEGIN DESCRIPTION:
WALTHALL CREEK 30.0
END DESCRIPTION:
XS GIS Cut Line= 2
      3570570.38      10602239.8      3571585.29     10602666.59
#Sta/Elev= 30
  4498.1  452.46  4589.4  448.92  4713.6  441.88  4766.5  438.36  4795.7  434.72
  4833.6  432.06  4877.8   428.5  4925.3  426.63  4954.4  426.49  4963.7  421.01
  4972.8  420.38  4978.2  418.24  4996.3  414.54  4998.9  412.88  5001.7  412.38
  5004.9  412.88  5007.4  414.49    5018  416.36  5025.7  415.94  5039.7  425.12
  5049.4   425.1  5054.8  426.67  5148.2  427.53  5213.6   432.3  5255.7  434.38
  5267.5  435.91  5343.4  438.79  5506.1  442.77  5527.8  444.22  5599.1  445.22
#Mann= 5 ,-1 , 0
  4498.1     .05       0  4833.6     .01       0  4954.4     .01       0
  5054.8     .01       0  5213.6     .05       0
Bank Sta=4954.4,5054.8
XS Rating Curve= 0 ,0
Exp/Cntr=0.3,0.1

Type RM Length L Ch R = 1 ,18264   ,387,387,387
BEGIN DESCRIPTION:
WALTHALL CREEK 29.0
END DESCRIPTION:
XS GIS Cut Line= 3
      3570320.39     10602495.01      3570648.52     10602911.68
      3571330.81     10602979.39
#Sta/Elev= 30
  4388.3   452.9  4441.5  449.05  4447.9  449.66    4512  446.11  4605.1  439.59
  4712.6   430.7  4739.7  427.74  4746.2  425.57  4762.3  423.07  4783.1  421.86
  4818.3  422.79  4840.4  421.47  4847.2  422.78    4868  423.26  4915.5  421.82
    4970  422.03  4980.1   414.8  4990.1  412.24  4999.9  407.98  5010.2  411.59
  5020.2   421.5  5123.8  428.36  5161.3  431.52  5201.1  432.94  5271.5  437.93
  5341.8  440.39  5358.1  442.36  5412.2  443.64  5458.9  446.58  5604.3   451.9
#Mann= 5 ,-1 , 0
  4388.3     .05       0  4746.2     .01       0    4970     .01       0
  5020.2     .01       0  5123.8     .05       0
Bank Sta=4970,5020.2
XS Rating Curve= 0 ,0
Exp/Cntr=0.3,0.1

Type RM Length L Ch R = 1 ,17877   ,660,660,660
BEGIN DESCRIPTION:
WALTHALL CREEK 28.0
END DESCRIPTION:
XS GIS Cut Line= 2
      3570325.46     10603333.84      3571144.78     10603208.86
#Sta/Elev= 30
  4481.6  447.97  4576.8  440.11  4597.1  437.62  4603.7  435.67  4617.3  435.02
  4647.6  431.08  4694.3  427.18  4799.3  420.64  4867.9     419  4890.4  420.11
  4910.7  419.24  4971.3  419.71  4991.6  416.66  4999.9  407.84  5004.7  406.87
  5011.8   407.8  5021.9  415.99    5032  420.63  5042.2  421.36  5052.3  424.03
  5062.4   424.8  5068.5  426.55  5073.5  426.44  5092.7  429.11  5148.7  434.41
  5200.5  438.09  5214.1  439.82    5264  440.55  5269.1  441.57  5310.4  443.53
#Mann= 5 ,-1 , 0
  4481.6     .05       0  4694.3     .01       0  4971.3     .01       0
  5042.2     .01       0  5148.7     .05       0
Bank Sta=4971.3,5042.2
XS Rating Curve= 0 ,0
Exp/Cntr=0.3,0.1

Type RM Length L Ch R = 1 ,17217   ,575,575,575
BEGIN DESCRIPTION:
WALTHALL CREEK 27.0
END DESCRIPTION:
XS GIS Cut Line= 2
      3569964.37     10603840.79      3571275.69     10603854.67
#Sta/Elev= 30
  4283.8  444.59    4379   444.8    4419  443.63  4489.1  439.28  4589.1  435.39
  4659.1   429.9  4689.1  428.73  4696.7  427.64  4769.1  423.96  4909.1  418.99
  4929.1  417.08  4959.1     416  4969.1  413.38  4979.1  407.41  4988.8   404.6
  5009.1  410.38  5019.1  414.24  5029.1  415.99  5049.1  416.54  5129.1  416.36
  5159.1  415.13  5209.1  415.05  5219.1  416.12  5229.1  419.76  5269.1  425.28
  5299.1  426.29  5379.1  432.02  5419.1  432.79  5509.1  430.35  5595.2  432.42
#Mann= 5 ,-1 , 0
  4283.8     .03       0  4929.1       0       0  4969.1     .01       0
  5019.1     .01       0  5219.1     .05       0
Bank Sta=4969.1,5019.1
XS Rating Curve= 0 ,0
Exp/Cntr=0.3,0.1

Type RM Length L Ch R = 1 ,16642   ,80,80,80
BEGIN DESCRIPTION:
WALTHALL CREEK 26.0
END DESCRIPTION:
XS GIS Cut Line= 6
      3569831.53     10604411.11      3570519.01     10604416.31
      3570836.72     10604332.98      3570977.34     10604260.06
      3571190.88     10604187.15      3571289.89     10604171.51
#Sta/Elev= 30
  4197.7  425.54  4224.1  427.23  4385.8  425.89  4405.8  422.65  4425.8  423.93
  4705.2  416.23  4846.5   413.9  4931.5  407.59  4958.9  408.42  4966.7  404.29
  4971.8  408.75  4979.6   403.8  4989.7  402.54  5007.1   407.1  5031.3  408.43
  5041.7  410.76  5047.4  406.89  5052.6  411.64  5062.3  409.95  5087.8  412.65
  5124.9  412.05  5176.1  406.83  5196.7   413.4  5218.9  412.34  5277.2  416.59
  5557.6  429.49  5577.4  428.32  5617.4  433.91  5660.3  434.96  5698.7  435.72
#Mann= 9 ,-1 , 0
  4197.7     .05       0  4224.1     .05       0  4705.2     .01       0
  4971.8     .01       0  5031.3     .01       0  5124.9     .03       0
  5277.2     .05       0  5557.6     .08       0  5660.3     .05       0
Bank Sta=4971.8,5031.3
XS Rating Curve= 0 ,0
Exp/Cntr=0.3,0.1

Type RM Length L Ch R = 1 ,16562   ,456,456,456
BEGIN DESCRIPTION:
WALTHALL CREEK 25.0
END DESCRIPTION:
XS GIS Cut Line= 6
      3569815.85     10604478.81       3570576.3      10604473.6
      3570774.22     10604437.15      3570992.97      10604348.6
      3571102.34     10604275.69       3571284.6     10604239.24
#Sta/Elev= 30
  4156.4  426.19  4195.8  425.02  4492.6   418.1  4660.2  412.21  4770.5  413.19
  4860.2  412.53  4890.2  410.53  4950.8  411.01  4964.7  408.06  4991.5  407.17
  5001.4  401.55  5011.8  402.18  5022.8  407.47  5052.5  408.74  5070.8   410.8
  5118.2  410.66    5121  412.31  5126.4  410.84  5145.1  413.29  5156.4  411.96
  5257.8  414.95  5335.5  421.17  5430.4  425.21  5436.4  423.33  5445.4  426.48
  5533.8  431.15  5572.1   433.1  5605.2  435.51  5635.5  435.43  5671.5   435.5
#Mann= 8 ,-1 , 0
  4156.4     .05       0  4195.8     .08       0  4492.6     .01       0
  4964.7     .01       0  5052.5     .01       0  5533.8     .07       0
  5572.1     .08       0  5635.5     .05       0
Bank Sta=4964.7,5052.5
XS Rating Curve= 0 ,0
Exp/Cntr=0.3,0.1

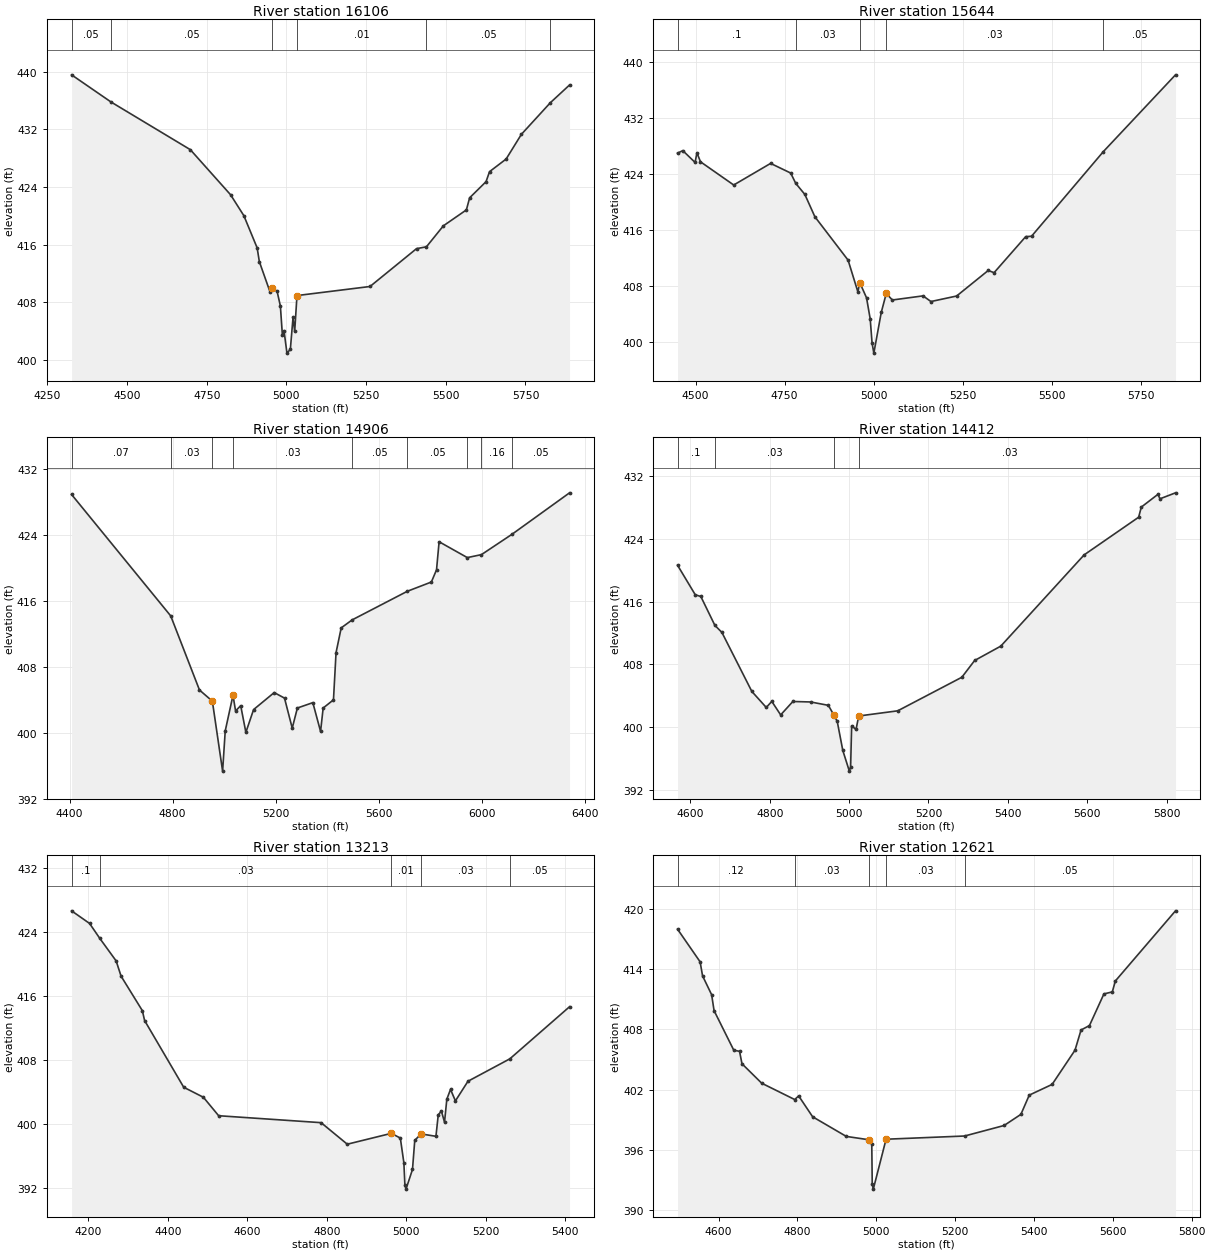
Type RM Length L Ch R = 1 ,16106   ,462,462,462
BEGIN DESCRIPTION:
WALTHALL CREEK 24.0
END DESCRIPTION:
XS GIS Cut Line= 2
       3569950.6     10605010.64       3571450.6     10604573.14
#Sta/Elev= 30
  4325.8  439.57  4449.6   435.8  4698.5  429.18  4824.8  422.92  4866.4  420.02
  4908.1  415.55    4915  413.64  4948.5  409.44  4953.7  409.94  4970.6  409.54
    4981  407.48  4987.2   403.5  4992.4  404.06  5001.6  400.94  5012.3  401.47
  5020.7  405.91  5025.9  403.95  5033.1  408.93  5262.3  410.19  5408.1  415.44
  5439.3   415.7  5492.4  418.61  5564.6  420.82  5574.8   422.5  5626.3  424.74
  5637.3  426.13  5689.3  427.88  5737.2  431.31  5828.1   435.7  5888.3  438.16
#Mann= 6 ,-1 , 0
  4325.8     .05       0  4449.6     .05       0  4953.7     .01       0
  5033.1     .01       0  5439.3     .05       0  5828.1     .05       0
Bank Sta=4953.7,5033.1
XS Rating Curve= 0 ,0
Exp/Cntr=0.3,0.1

Type RM Length L Ch R = 1 ,15644   ,738,738,738
BEGIN DESCRIPTION:
WALTHALL CREEK 23.0
END DESCRIPTION:
XS GIS Cut Line= 3
      3570227.33     10605338.19      3570841.93     10605171.52
        3571519.     10604822.57
#Sta/Elev= 30
  4449.5  426.94  4464.2  427.31  4498.8  425.62    4504     427    4514  425.71
  4607.3  422.39  4710.9  425.48  4767.3   424.1  4781.4  422.63  4807.1  421.04
  4835.2  417.85  4928.5  411.64    4956   407.1  4961.2  408.44  4980.3  406.25
  4990.6  403.23  4995.8  399.81  5000.8  398.34  5021.7  404.18  5035.7  406.87
  5052.8  405.94    5139  406.53  5161.2  405.72  5233.3  406.51    5322  410.16
  5338.5  409.85  5427.2     415  5443.7  415.06  5645.4  427.17    5848  438.15
#Mann= 5 ,-1 , 0
  4449.5      .1       0  4781.4     .03       0  4961.2     .01       0
  5035.7     .03       0  5645.4     .05       0
Bank Sta=4961.2,5035.7
XS Rating Curve= 0 ,0
Exp/Cntr=0.3,0.1

Type RM Length L Ch R = 1 ,14906   ,494,494,494
BEGIN DESCRIPTION:
WALTHALL CREEK 22.0
END DESCRIPTION:
XS GIS Cut Line= 2
      3570073.12     10605689.75       3572005.9     10605734.86
#Sta/Elev= 30
    4408  428.86    4793  414.14  4904.6  405.16  4954.6  403.81  4994.4  395.33
  5004.6  400.21  5034.7  404.52  5044.7  402.63  5064.7  403.26  5084.7  400.03
  5114.7  402.79  5194.7  404.85  5234.7  404.18  5264.7  400.54  5284.7  402.98
  5344.7  403.63  5374.7  400.14  5384.8  402.98  5424.8  403.97  5434.8  409.69
  5454.8  412.69  5497.3  413.66  5711.7  417.13  5804.9  418.25  5824.9  419.73
  5834.9  423.13  5944.4  421.21  5999.3  421.57  6118.1  424.04  6341.3  429.06
#Mann= 9 ,-1 , 0
    4408     .07       0    4793     .03       0  4954.6     .01       0
  5034.7     .03       0  5497.3     .05       0  5711.7     .05       0
  5944.4     .05       0  5999.3     .16       0  6118.1     .05       0
Bank Sta=4954.6,5034.7
XS Rating Curve= 0 ,0
Exp/Cntr=0.3,0.1

Type RM Length L Ch R = 1 ,14412   ,1199,1199,1199
BEGIN DESCRIPTION:
WALTHALL CREEK 21.0
END DESCRIPTION:
XS GIS Cut Line= 3
      3570349.62      10605860.2      3570749.61     10606060.19
      3571499.63      10606360.2
#Sta/Elev= 30
  4567.6  420.66  4612.3  416.89  4626.3  416.67  4661.7  412.99  4679.4  412.09
  4754.9  404.56  4791.2  402.52  4805.2  403.29  4827.5  401.57  4858.3  403.28
    4903  403.22  4947.7  402.79  4961.7  401.54  4970.1  400.74  4984.1  397.04
  5000.6   394.4  5003.8   394.9  5006.4  400.18  5017.5  399.71  5024.2  401.43
  5122.5  402.09  5284.1  406.37  5316.4  408.51  5382.3  410.34  5592.4  421.98
  5729.7  426.78  5736.4  428.07  5778.1  429.69  5783.6  429.13  5822.6  429.89
#Mann= 5 ,-1 , 0
  4567.6      .1       0  4661.7     .03       0  4961.7     .01       0
  5024.2     .03       0  5783.6     .05       0
Bank Sta=4961.7,5024.2
XS Rating Curve= 0 ,0
Exp/Cntr=0.3,0.1

Type RM Length L Ch R = 1 ,13213   ,592,592,592
BEGIN DESCRIPTION:
WALTHALL CREEK 20.0
END DESCRIPTION:
XS GIS Cut Line= 3
      3570249.63     10605860.22      3570649.61     10606610.19
      3570999.63      10606810.2
#Sta/Elev= 30
  4157.5  426.69  4202.8  425.11  4228.5  423.24  4269.7  420.41  4282.1   418.5
  4335.6  414.18  4341.3  412.94  4439.7  404.58  4489.3  403.32  4527.6  401.01
  4785.4  400.14  4851.3  397.44  4962.1   398.8  4984.8  398.21  4993.7  395.12
  4996.3  392.31  4999.1  391.81  5015.4  394.28  5021.1  397.92    5037  398.73
  5074.4  398.43  5080.2  401.11  5088.1   401.6    5096   400.2  5101.8  403.08
  5111.1  404.31  5123.4  402.87    5155  405.33  5260.4  408.14  5410.6  414.67
#Mann= 5 ,-1 , 0
  4157.5      .1       0  4228.5     .03       0  4962.1     .01       0
    5037     .03       0  5260.4     .05       0
Bank Sta=4962.1,5037
XS Rating Curve= 0 ,0
Exp/Cntr=0.3,0.1

Type RM Length L Ch R = 1 ,12621   ,285,285,285
BEGIN DESCRIPTION:
WALTHALL CREEK 19.0
END DESCRIPTION:
XS GIS Cut Line= 3
      3569949.61     10606260.19      3570249.61     10606660.19
       3570649.6     10607310.18
#Sta/Elev= 30
  4495.9     418  4553.2  414.74  4559.4  413.34  4582.4  411.46  4588.6  409.87
  4638.6  405.92  4653.2  405.81  4659.4  404.57  4709.4  402.63  4793.1     401
  4803.2  401.36  4838.6  399.28    4924  397.32  4982.4  396.98  4988.6  396.61
  4989.8  392.56  4992.5  392.06  5024.9  397.04  5224.1  397.36  5324.3  398.41
  5366.9  399.52  5388.1  401.44  5446.1  402.51  5504.1  405.92  5519.5  407.94
  5540.8  408.38  5577.5  411.54  5598.8  411.74  5606.5  412.83  5759.1  419.83
#Mann= 5 ,-1 , 0
  4495.9     .12       0  4793.1     .03       0  4982.4     .01       0
  5024.9     .03       0  5224.1     .05       0
Bank Sta=4982.4,5024.9
XS Rating Curve= 0 ,0
Exp/Cntr=0.3,0.1

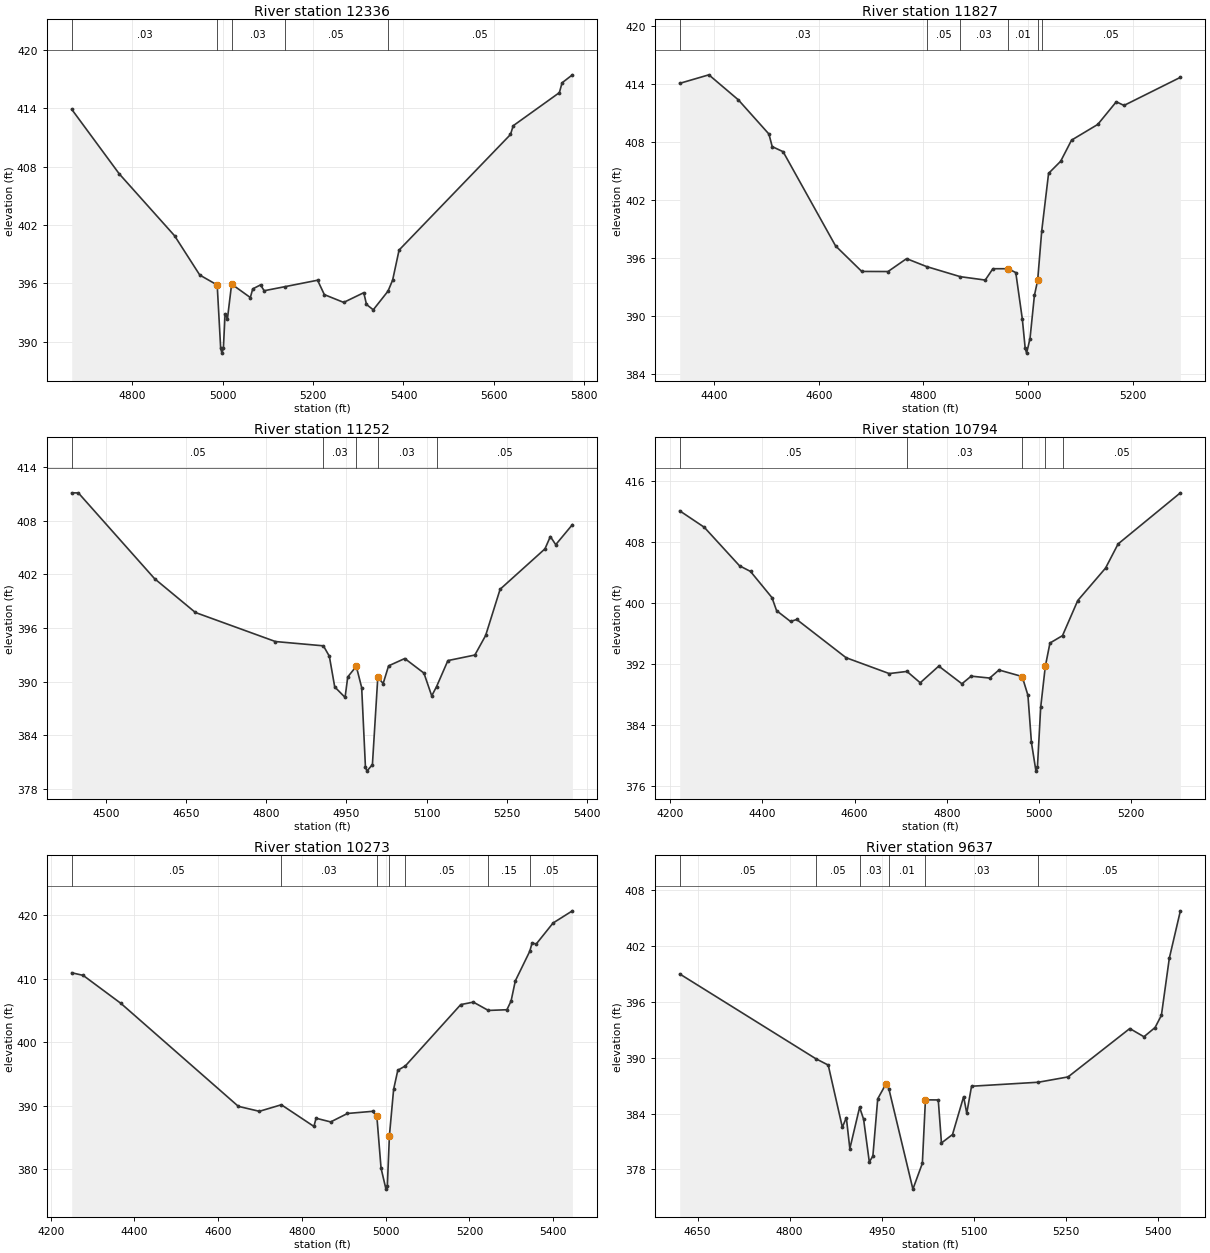
Type RM Length L Ch R = 1 ,12336   ,509,509,509
BEGIN DESCRIPTION:
WALTHALL CREEK 18.0
END DESCRIPTION:
XS GIS Cut Line= 3
      3569737.17     10606738.78      3570195.55     10606905.46
      3570539.27     10607421.05
#Sta/Elev= 30
  4666.2  413.88  4771.3  407.25  4893.7  400.89  4949.5  396.85    4988  395.83
  4995.7  389.33  4998.4  388.83  5001.7  389.33  5005.4  392.83  5010.7  392.38
  5019.9  395.92  5061.3  394.54  5066.6  395.43  5083.8  395.84  5091.9  395.24
    5137  395.65    5210  396.32    5225  394.84  5267.8  394.04  5312.2  395.04
  5318.2  393.83  5333.2  393.28  5365.8   395.2    5376  396.33  5390.3  399.42
  5636.7  411.29  5642.7  412.19  5744.8  415.59  5750.8   416.6  5773.6  417.42
#Mann= 5 ,-1 , 0
  4666.2     .03       0    4988     .01       0  5019.9     .03       0
    5137     .05       0  5365.8     .05       0
Bank Sta=4988,5019.9
XS Rating Curve= 0 ,0
Exp/Cntr=0.3,0.1

Type RM Length L Ch R = 1 ,11827   ,575,575,575
BEGIN DESCRIPTION:
WALTHALL CREEK 17.0
END DESCRIPTION:
XS GIS Cut Line= 2
      3569612.23     10606900.26      3570383.04     10607467.95
#Sta/Elev= 30
  4334.1  414.04  4389.9  414.92  4446.2  412.34  4504.7  408.81    4511  407.51
  4531.8  406.99  4632.1  397.27  4682.2  394.63  4732.4  394.62  4767.9  395.95
  4806.3  395.13  4870.6  394.09  4918.3  393.74  4932.9  394.91  4962.2  394.91
  4976.7  394.51  4989.2  389.72  4994.7   386.7  4997.4   386.2  5003.9   387.7
  5012.3  392.15  5018.5   393.7  5026.3  398.81  5039.4  404.75  5062.5     406
  5083.3  408.18  5133.4   409.8  5168.9  412.14  5183.6  411.76  5291.4  414.66
#Mann= 6 ,-1 , 0
  4334.1     .03       0  4806.3     .05       0  4870.6     .03       0
  4962.2     .01       0  5018.5     .03       0  5026.3     .05       0
Bank Sta=4962.2,5018.5
XS Rating Curve= 0 ,0
Exp/Cntr=0.3,0.1

Type RM Length L Ch R = 1 ,11252   ,458,458,458
BEGIN DESCRIPTION:
WALTHALL CREEK 16.0
END DESCRIPTION:
XS GIS Cut Line= 2
      3569171.72     10607473.51      3570100.54     10607603.72
#Sta/Elev= 30
  4435.3  411.12  4447.8  411.11  4590.6  401.51    4667  397.73  4816.9  394.48
  4906.8     394  4917.9  392.84    4928   389.4  4947.4  388.23  4952.4  390.52
  4968.4  391.71  4978.5  389.32  4985.5  380.48  4988.3  379.98  4998.6  380.71
  5008.7  390.49  5018.7  389.78  5028.9  391.76  5059.2  392.58  5095.1  390.95
  5109.7   388.4  5118.7  389.43    5140  392.35  5190.5  392.97  5210.7  395.16
  5237.8  400.33  5321.8  404.85  5331.9  406.23    5342  405.32  5373.2  407.56
#Mann= 5 ,-1 , 0
  4435.3     .05       0  4906.8     .03       0  4968.4     .01       0
  5008.7     .03       0  5118.7     .05       0
Bank Sta=4968.4,5008.7
XS Rating Curve= 0 ,0
Exp/Cntr=0.3,0.1

Type RM Length L Ch R = 1 ,10794   ,521,521,521
BEGIN DESCRIPTION:
WALTHALL CREEK 15.0
END DESCRIPTION:
XS GIS Cut Line= 2
      3569180.46     10607759.98      3570261.13     10607868.48
#Sta/Elev= 30
  4220.7  412.09    4274  409.93  4350.5  404.87  4374.3  404.13  4420.9  400.69
  4430.9  398.98  4461.1  397.56  4474.6  397.82  4581.7   392.8  4675.2  390.72
  4713.7     391  4742.5  389.51  4782.7   391.7  4832.9  389.38    4853  390.38
  4893.2  390.13  4913.3  391.19  4963.6  390.33  4976.1  387.87  4983.7  381.67
  4993.5  377.91  4996.7  378.41  5003.8   386.3  5013.8  391.66  5023.9  394.73
  5051.1   395.7  5084.2  400.31  5144.5  404.57  5171.7  407.74  5306.8  414.45
#Mann= 5 ,-1 , 0
  4220.7     .05       0  4713.7     .03       0  4963.6     .01       0
  5013.8     .03       0  5051.1     .05       0
Bank Sta=4963.6,5013.8
XS Rating Curve= 0 ,0
Exp/Cntr=0.3,0.1

Type RM Length L Ch R = 1 ,10273   ,636,636,636
BEGIN DESCRIPTION:
WALTHALL CREEK 14.0
END DESCRIPTION:
XS GIS Cut Line= 2
      3569212.31     10608089.63      3570405.69     10608162.48
#Sta/Elev= 30
  4250.2  410.91  4277.5   410.5  4367.7  406.09  4648.2  389.88  4698.3   389.1
  4750.8  390.13  4828.6  386.72  4833.7  388.01  4868.6  387.43  4908.7  388.76
  4968.8   389.1  4978.9  388.29  4988.9  380.15  5000.6  376.85  5003.9  377.35
  5008.9  385.29  5018.9  392.55  5028.9  395.56    5047  396.25  5179.2   405.9
  5209.3  406.29  5245.1  404.98  5289.4  405.09  5299.4  406.46  5309.5  409.63
    5344  414.29  5349.5  415.58  5359.6  415.45  5399.6  418.74  5445.8  420.66
#Mann= 7 ,-1 , 0
  4250.2     .05       0  4750.8     .03       0  4978.9     .01       0
  5008.9     .03       0    5047     .05       0  5245.1     .15       0
    5344     .05       0
Bank Sta=4978.9,5008.9
XS Rating Curve= 0 ,0
Exp/Cntr=0.3,0.1

Type RM Length L Ch R = 1 ,9637    ,375,375,375
BEGIN DESCRIPTION:
WALTHALL CREEK 13.0
END DESCRIPTION:
XS GIS Cut Line= 3
      3569399.61     10608710.19      3569749.61     10608510.19
      3570149.59     10608410.19
#Sta/Elev= 30
  4620.9  398.98  4842.4  389.89  4862.8   389.2  4885.8  382.53  4892.3  383.56
    4898  380.23  4913.9  384.67  4920.4  383.39  4929.7  378.81  4935.5  379.43
  4943.4  385.58  4957.1  387.21  4961.5  386.67  5000.7  375.89  5016.1  378.66
  5021.1  385.47    5042  385.46  5047.2  380.84  5065.2  381.75  5083.3  385.81
  5088.4  384.03  5096.2  386.93  5205.1  387.36  5253.4  387.93  5353.9  393.12
    5377  392.24  5395.1  393.23  5405.4  394.54  5418.3  400.67  5436.3  405.75
#Mann= 6 ,-1 , 0
  4620.9     .05       0  4842.4     .05       0  4913.9     .03       0
  4961.5     .01       0  5021.1     .03       0  5205.1     .05       0
Bank Sta=4957.1,5021.1
XS Rating Curve= 0 ,0
Exp/Cntr=0.3,0.1

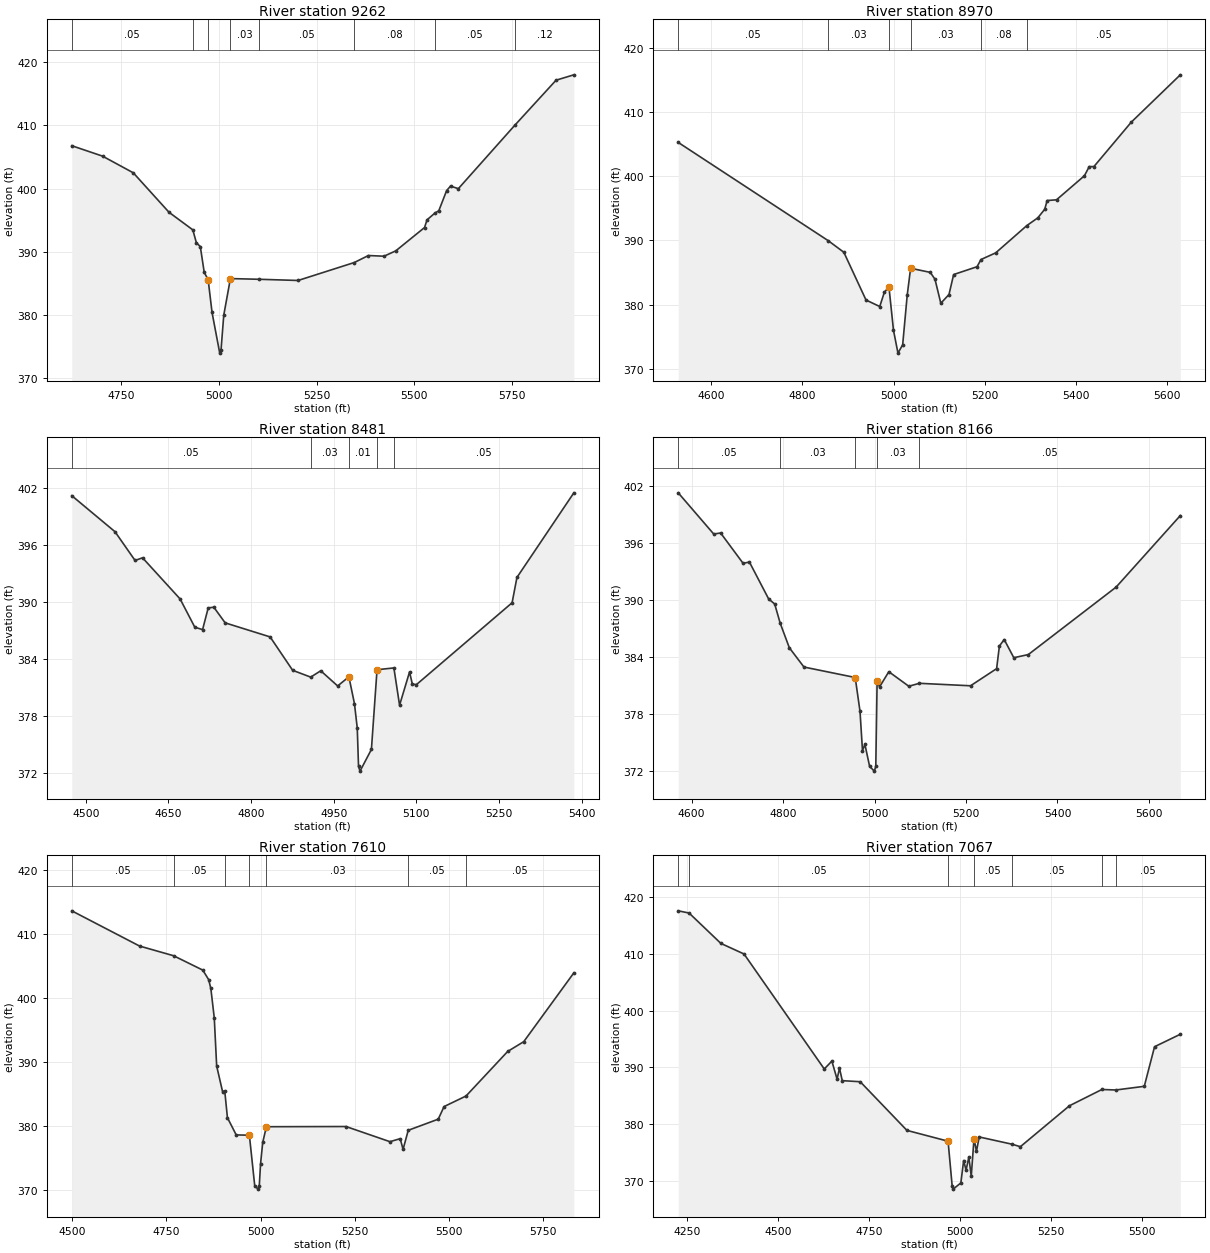
Type RM Length L Ch R = 1 ,9262    ,292,292,292
BEGIN DESCRIPTION:
WALTHALL CREEK 12.0
END DESCRIPTION:
XS GIS Cut Line= 2
      3569340.83     10608891.72      3570625.07     10608839.65
#Sta/Elev= 30
  4623.3  406.78  4702.1  405.13  4780.8  402.49  4872.3  396.24  4933.2  393.46
  4942.3  391.42  4952.4  390.81  4962.4  386.72  4972.4  385.58  4982.4  380.39
  5002.1  373.95  5005.4  374.45  5012.4  379.96  5029.4  385.75  5102.2  385.64
  5202.6  385.45  5346.5  388.29  5382.7   389.4  5422.7  389.29  5452.8  390.14
  5526.4  393.83  5532.8  395.05    5553  396.12  5562.9  396.49  5582.9  399.67
  5592.9  400.39  5612.9  399.98  5758.1  410.06  5863.1  417.15  5908.6     418
#Mann= 8 ,-1 , 0
  4623.3     .05       0  4933.2     .03       0  4972.4     .01       0
  5029.4     .03       0  5102.2     .05       0  5346.5     .08       0
    5553     .05       0  5758.1     .12       0
Bank Sta=4972.4,5029.4
XS Rating Curve= 0 ,0
Exp/Cntr=0.3,0.1

Type RM Length L Ch R = 1 ,8970    ,489,489,489
BEGIN DESCRIPTION:
WALTHALL CREEK 11.0
END DESCRIPTION:
XS GIS Cut Line= 4
       3569408.5     10609092.24      3569767.87     10609081.82
      3569944.96     10609097.45      3570494.39     10609219.83
#Sta/Elev= 30
  4528.2  405.26    4857  389.95  4891.1  388.15  4939.7  380.71  4969.8   379.7
  4979.8  381.91  4989.9  382.77  4999.9     376  5009.7  372.44    5020  373.74
    5030  381.49  5037.4  385.66  5080.5  385.02  5090.8  383.95  5103.6  380.21
  5121.5  381.57  5131.7  384.68    5183   385.9  5191.6  387.02  5223.9  388.06
  5292.1  392.31  5316.1  393.51  5331.3  394.85  5336.6  396.21  5357.1  396.32
  5418.3  400.07  5428.8  401.49  5439.1   401.5    5521  408.42  5628.4  415.79
#Mann= 6 ,-1 , 0
  4528.2     .05       0    4857     .03       0  4989.9     .01       0
  5037.4     .03       0  5191.6     .08       0  5292.1     .05       0
Bank Sta=4989.9,5037.4
XS Rating Curve= 0 ,0
Exp/Cntr=0.3,0.1

Type RM Length L Ch R = 1 ,8481    ,315,315,315
BEGIN DESCRIPTION:
WALTHALL CREEK 10.0
END DESCRIPTION:
XS GIS Cut Line= 2
       3569337.1     10609399.31      3570229.37     10609585.56
#Sta/Elev= 30
  4474.6  401.22  4553.1  397.42  4589.5  394.39  4603.1  394.67  4671.3  390.33
    4698  387.35  4712.1   387.1  4722.3  389.39  4732.5  389.46  4753.1  387.81
  4834.7  386.33  4875.6  382.81  4908.4  382.09  4926.6  382.76  4957.3  381.16
  4977.7  382.12  4987.8   379.3  4992.9  376.72  4995.2  372.68  4997.9  372.18
  5018.6  374.47  5028.8  382.87  5059.4  383.06  5069.7  379.13  5087.8  382.63
  5092.9  381.36  5100.3   381.3    5274  389.93  5282.8   392.6  5386.1  401.52
#Mann= 5 ,-1 , 0
  4474.6     .05       0  4908.4     .03       0  4977.7     .01       0
  5028.8     .03       0  5059.4     .05       0
Bank Sta=4977.7,5028.8
XS Rating Curve= 0 ,0
Exp/Cntr=0.3,0.1

Type RM Length L Ch R = 1 ,8166    ,556,556,556
BEGIN DESCRIPTION:
WALTHALL CREEK 9.0
END DESCRIPTION:
XS GIS Cut Line= 2
      3569341.45     10609651.05        3570386.     10609989.12
#Sta/Elev= 30
  4570.7  401.27  4648.3  396.94  4663.4  397.05  4712.4  393.87  4726.4  393.99
  4768.5  390.11  4781.6  389.59  4793.7  387.56  4813.6  384.99  4845.6  382.96
  4957.7  381.86  4968.2   378.3  4973.6  374.18  4978.9  374.83  4989.2  372.52
  4999.5  372.02  5002.7  372.52  5005.6  381.49  5010.9  380.87  5031.2  382.47
  5074.9  380.94    5098  381.25  5209.9  380.99  5266.9  382.79    5273  385.17
  5283.5  385.85  5304.5  383.94  5336.2  384.27  5528.2  391.36  5668.6  398.88
#Mann= 5 ,-1 , 0
  4570.7     .05       0  4793.7     .03       0  4957.7     .01       0
  5005.6     .03       0    5098     .05       0
Bank Sta=4957.7,5005.6
XS Rating Curve= 0 ,0
Exp/Cntr=0.3,0.1

Type RM Length L Ch R = 1 ,7610    ,543,543,543
BEGIN DESCRIPTION:
WALTHALL CREEK 8.0
END DESCRIPTION:
XS GIS Cut Line= 2
       3569075.2     10609696.42       3570218.4     10610383.91
#Sta/Elev= 30
  4498.4  413.65  4678.6  408.14  4768.8  406.63  4846.5  404.38  4862.1  402.89
  4867.9  401.51    4877  396.92  4883.4  389.38    4899  385.39  4904.8   385.5
    4912   381.3  4935.3  378.61  4970.3  378.56  4984.5  370.67  4993.4  370.13
  4996.6  370.63    5000  374.09  5005.8  377.44  5015.5  379.89    5227  379.92
  5343.7  377.55    5371  378.02  5378.7  376.35  5392.4  379.33  5472.1  381.07
  5487.6  383.04  5545.9  384.69  5656.6  391.66  5699.3  393.19  5832.4  403.95
#Mann= 7 ,-1 , 0
  4498.4     .05       0  4768.8     .05       0  4904.8     .03       0
  4970.3     .01       0  5015.5     .03       0  5392.4     .05       0
  5545.9     .05       0
Bank Sta=4970.3,5015.5
XS Rating Curve= 0 ,0
Exp/Cntr=0.3,0.1

Type RM Length L Ch R = 1 ,7067    ,782,782,782
BEGIN DESCRIPTION:
WALTHALL CREEK 7.0
END DESCRIPTION:
XS GIS Cut Line= 2
       3568907.4      10609807.3      3569814.51     10610844.62
#Sta/Elev= 30
  4226.3  417.61  4256.1  417.22  4343.3  411.86  4406.9  409.99  4627.1  389.69
    4648  391.08  4662.2   387.9  4668.9  389.83  4676.5  387.63  4725.8  387.44
    4854  378.85  4966.9  376.94  4978.2  368.98  4980.9  368.48    5002  369.58
  5009.6  373.53  5016.3  371.83  5023.9  374.14  5030.5  370.76  5038.1  377.41
  5044.8  375.15  5052.3  377.69  5142.4  376.41  5165.3  375.97  5300.1   383.2
  5389.1  386.07  5427.1  385.98  5505.4  386.63  5533.6  393.62  5604.3  395.82
#Mann= 7 ,-1 , 0
  4226.3     .05       0  4256.1     .05       0  4966.9     .03       0
  5038.1     .05       0  5142.4     .05       0  5389.1     .07       0
  5427.1     .05       0
Bank Sta=4966.9,5038.1
XS Rating Curve= 0 ,0
Exp/Cntr=0.3,0.1

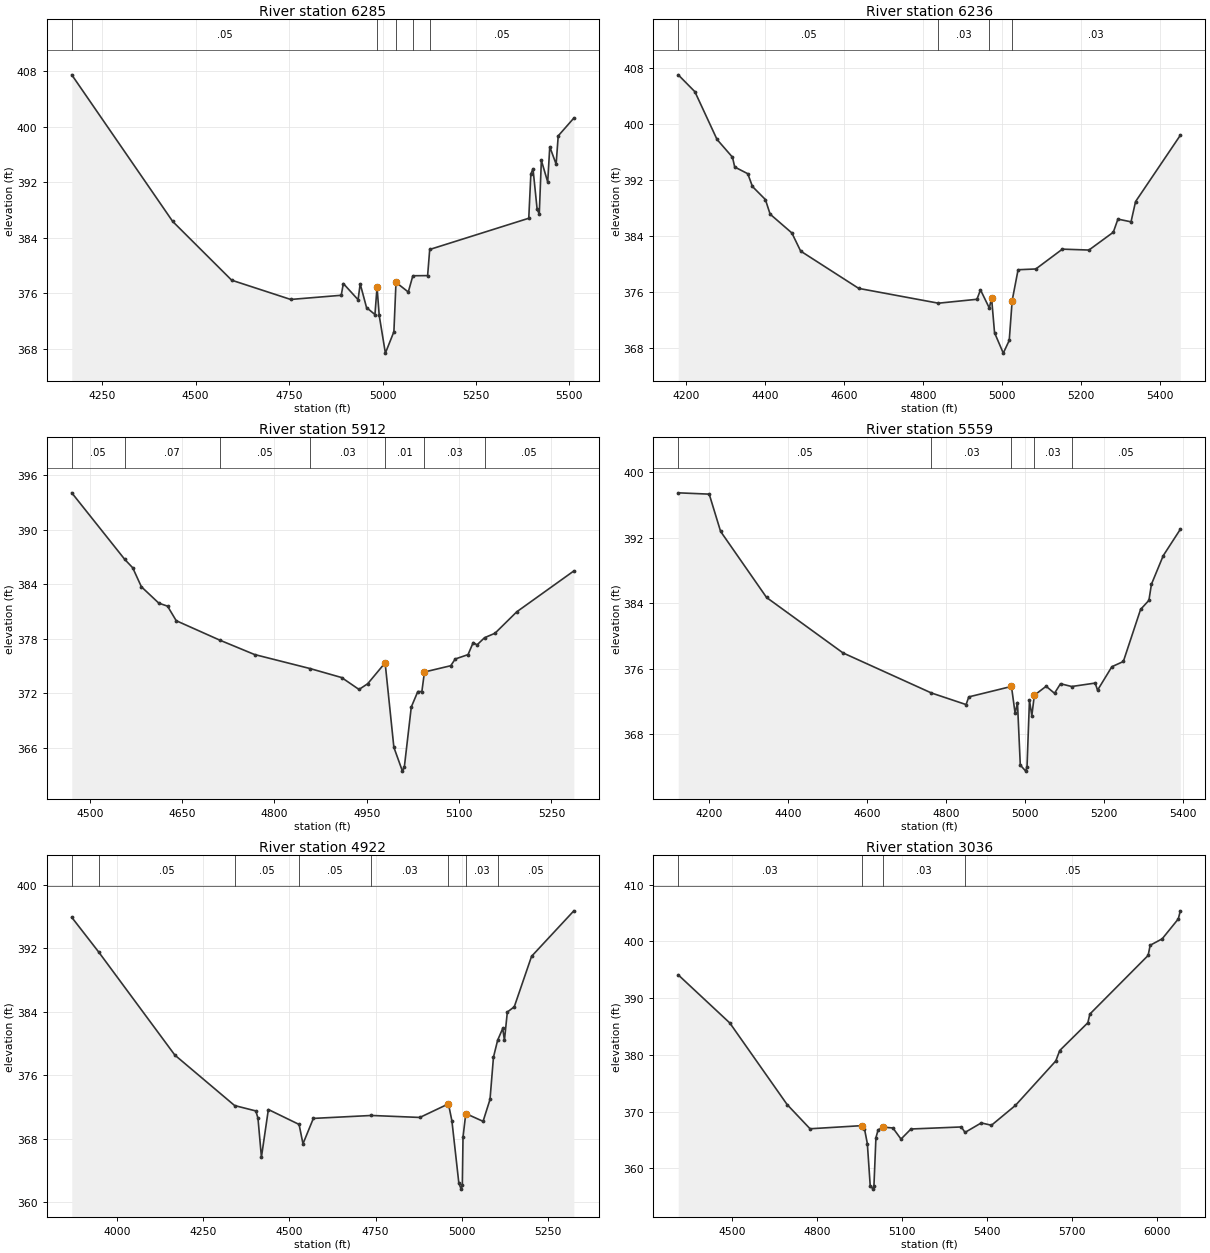
Type RM Length L Ch R = 1 ,6285    ,49,49,49
BEGIN DESCRIPTION:
Mapping XS b13d5266
END DESCRIPTION:
XS GIS Cut Line= 2
      3568490.04     10610377.96      3569697.87     10610965.62
#Sta/Elev= 30
  4168.6  407.44  4438.6  386.35  4596.4   377.9  4754.3  375.13  4889.5  375.73
  4895.1  377.42  4934.6  375.09  4940.2  377.38  4957.2  373.96  4979.7  372.96
  4985.3  376.89  4991.1  372.84  5007.6  367.41  5030.4  370.49    5036  377.59
  5068.9   376.2  5081.1  378.54  5120.6  378.56  5126.2  382.32  5391.2  386.81
  5396.8  393.16  5402.5  393.94  5413.6  388.09  5419.3  387.42  5424.9  395.13
  5441.9  392.02  5447.4  397.09  5464.4  394.59    5470  398.66  5511.8  401.22
#Mann= 5 ,-1 , 0
  4168.6     .05       0  4985.3     .01       0    5036     .03       0
  5081.1     .05       0  5126.2     .05       0
Bank Sta=4985.3,5036
XS Rating Curve= 0 ,0
Exp/Cntr=0.3,0.1

Type RM Length L Ch R = 1 ,6236    ,324,324,324
BEGIN DESCRIPTION:
WALTHALL CREEK 6.0
END DESCRIPTION:
XS GIS Cut Line= 2
      3568461.82       10610404.      3569601.16     10610968.24
#Sta/Elev= 30
    4180  407.07  4222.2  404.65  4278.2  397.82  4317.4  395.27    4323  393.87
  4356.1  392.91  4367.9  391.08  4400.7  389.21  4412.7  387.12  4467.7  384.43
    4490  381.83    4637  376.49  4838.8  374.37  4936.4  374.93  4945.4  376.28
  4967.8  373.67  4973.4  375.15    4981  370.14  5003.1  367.22  5018.2  369.04
  5025.6  374.74  5040.6  379.16  5085.5  379.27  5152.8  382.11    5220  381.98
  5281.7  384.53  5293.4  386.41  5326.6  386.02  5338.1  388.92  5451.4  398.41
#Mann= 4 ,-1 , 0
    4180     .05       0  4838.8     .03       0  4967.8     .01       0
  5025.6     .03       0
Bank Sta=4973.4,5025.6
XS Rating Curve= 0 ,0
Exp/Cntr=0.3,0.1

Type RM Length L Ch R = 1 ,5912    ,353,353,353
BEGIN DESCRIPTION:
WALTHALL CREEK 5.0
END DESCRIPTION:
XS GIS Cut Line= 3
       3568549.6     10610510.18      3568949.61     10610910.19
      3569149.61     10611060.19
#Sta/Elev= 30
  4470.8  394.04    4557  386.71  4569.8   385.8  4583.9  383.71  4612.2  381.91
  4626.4  381.58  4640.5  379.98    4711  377.85  4767.8  376.26  4858.4  374.71
  4909.2  373.73  4937.5  372.42  4951.6  373.05  4979.9  375.35  4994.1  366.06
    5008  363.44  5011.2  363.94  5022.4  370.49    5033  372.19  5039.6  372.19
  5043.8  374.34  5086.5  375.03  5093.8  375.77  5114.6  376.25    5123  377.58
  5129.2  377.32  5141.4  378.11  5158.4   378.6  5193.8  380.96  5286.5  385.45
#Mann= 7 ,-1 , 0
  4470.8     .05       0    4557     .07       0    4711     .05       0
  4858.4     .03       0  4979.9     .01       0  5043.8     .03       0
  5141.4     .05       0
Bank Sta=4979.9,5043.8
XS Rating Curve= 0 ,0
Exp/Cntr=0.3,0.1

Type RM Length L Ch R = 1 ,5559    ,637,637,637
BEGIN DESCRIPTION:
WALTHALL CREEK 4.0
END DESCRIPTION:
XS GIS Cut Line= 2
      3568109.17      10610712.5      3569181.28      10611398.3
#Sta/Elev= 30
  4121.4  397.51  4199.9  397.35  4228.8  392.79  4345.3  384.71    4539  377.93
  4763.1  373.03  4851.1  371.61  4857.9  372.55  4966.1  373.83  4975.4  370.52
  4981.3  371.86  4988.5  364.21  5002.2  363.47  5005.5  363.97  5011.7  372.13
  5017.7  370.25  5024.1  372.75    5054  373.85  5075.2  372.99  5090.4  374.16
  5118.7  373.82  5178.3  374.24  5184.3  373.37  5220.6  376.24  5249.7  376.88
  5293.4  383.25  5314.5  384.36  5320.9  386.33  5350.9  389.83  5394.1  393.05
#Mann= 5 ,-1 , 0
  4121.4     .05       0  4763.1     .03       0  4966.1     .01       0
  5024.1     .03       0  5118.7     .05       0
Bank Sta=4966.1,5024.1
XS Rating Curve= 0 ,0
Exp/Cntr=0.3,0.1

Type RM Length L Ch R = 1 ,4922    ,1886,1886,1886
BEGIN DESCRIPTION:
WALTHALL CREEK 3.0
END DESCRIPTION:
XS GIS Cut Line= 2
      3567762.03     10611619.64      3569211.65     10611498.11
#Sta/Elev= 30
  3869.5  395.92  3947.7  391.54  4168.1  378.57  4341.3  372.21  4402.8  371.53
    4409  370.61    4419  365.71  4439.1  371.71  4528.1  369.83  4539.4  367.39
  4569.5  370.59  4737.9  370.96    4878  370.71  4960.9  372.42  4970.9  370.28
    4991  362.43  4997.8  361.68  5001.1  362.18  5003.1  368.24  5011.1   371.2
  5061.2  370.22  5081.3  372.98  5091.3   378.3  5103.4  380.44  5118.1  381.92
  5123.1  380.44  5131.5  383.99  5151.6  384.65  5201.7  391.01  5324.2  396.74
#Mann= 8 ,-1 , 0
  3869.5     .12       0  3947.7     .05       0  4341.3     .05       0
  4528.1     .05       0  4737.9     .03       0  4960.9     .01       0
  5011.1     .03       0  5103.4     .05       0
Bank Sta=4960.9,5011.1
XS Rating Curve= 0 ,0
Exp/Cntr=0.3,0.1

Type RM Length L Ch R = 1 ,3036    ,620,620,620
BEGIN DESCRIPTION:
WALTHALL CREEK 2.0
END DESCRIPTION:
XS GIS Cut Line= 3
       3567899.6     10612410.19      3568599.61     10612310.19
      3569399.58     10611610.21
#Sta/Elev= 30
  4311.2  394.09    4493  385.61  4695.1  371.23  4775.9  366.96  4957.7  367.51
  4967.8  366.96  4977.9  364.35    4988  356.95  4997.9  356.32  5001.1  356.82
  5008.2  365.39  5015.8  366.75  5032.1  367.25  5068.1   367.1  5096.6  365.14
  5131.7  366.92  5309.2  367.28  5322.3  366.32  5379.5  367.99  5415.5  367.58
    5500  371.08  5642.4  378.92  5656.1  380.75  5755.3  385.65  5762.4  387.18
  5967.9  397.52    5975  399.31  6017.3  400.44  6074.2  403.95  6081.3  405.38
#Mann= 4 ,-1 , 0
  4311.2     .03       0  4957.7     .01       0  5032.1     .03       0
  5322.3     .05       0
Bank Sta=4957.7,5032.1
XS Rating Curve= 0 ,0
Exp/Cntr=0.3,0.1