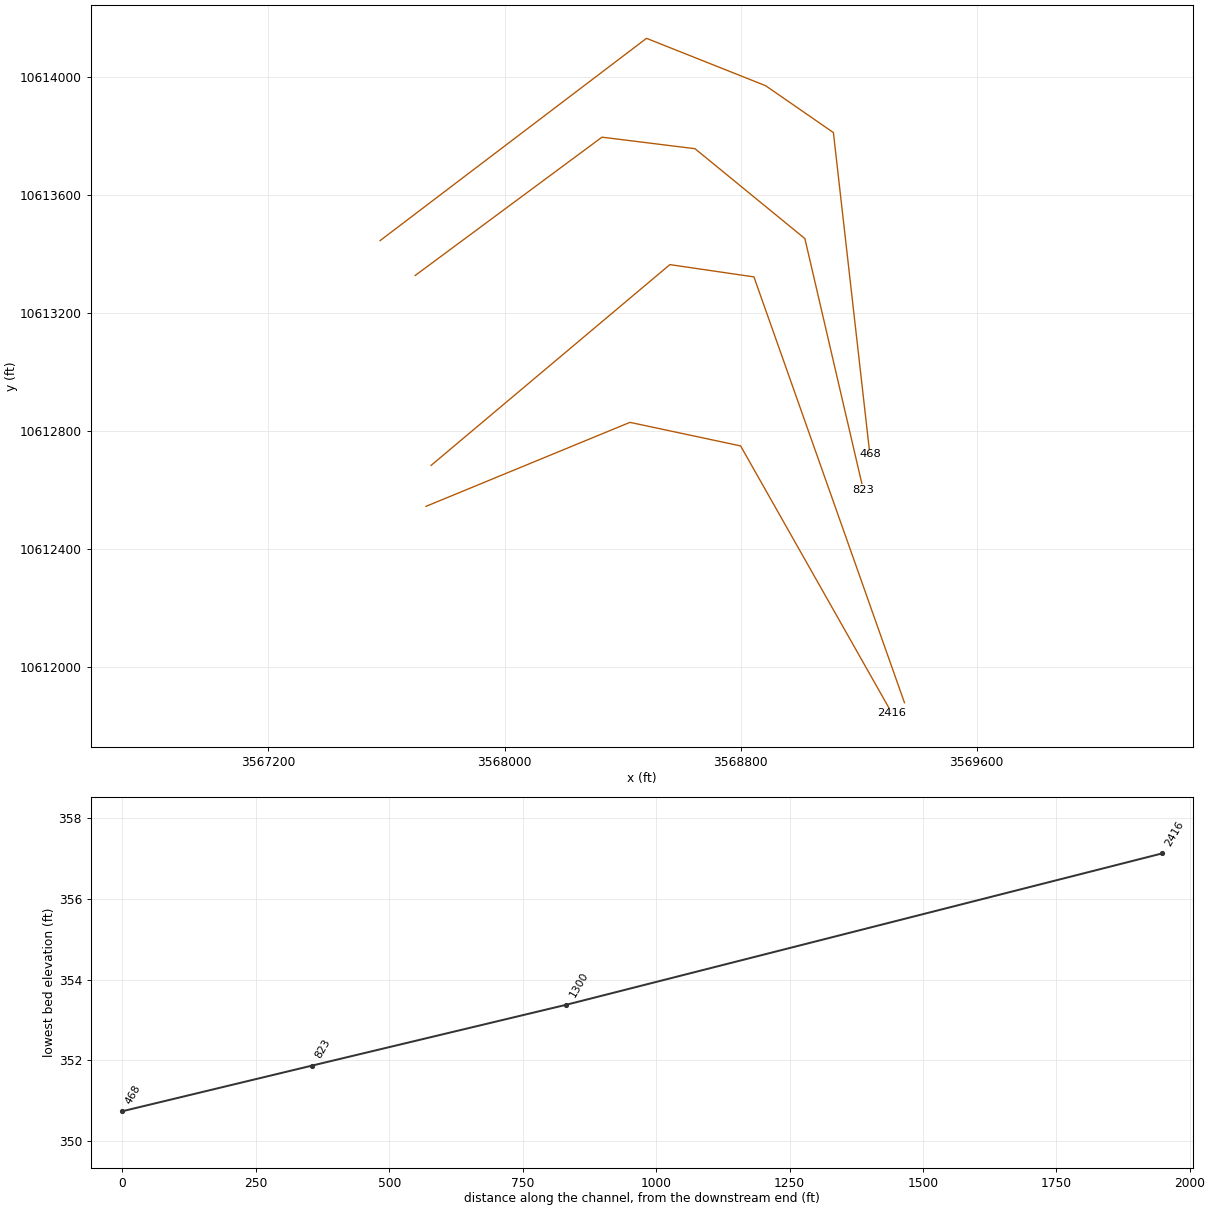
HEC-RAS study WALTHALL CREEK.prj: WALTHALL CREEK Base Level Engineering

--- WALTHALL CREEK.g01 (geometry) --- (continued)

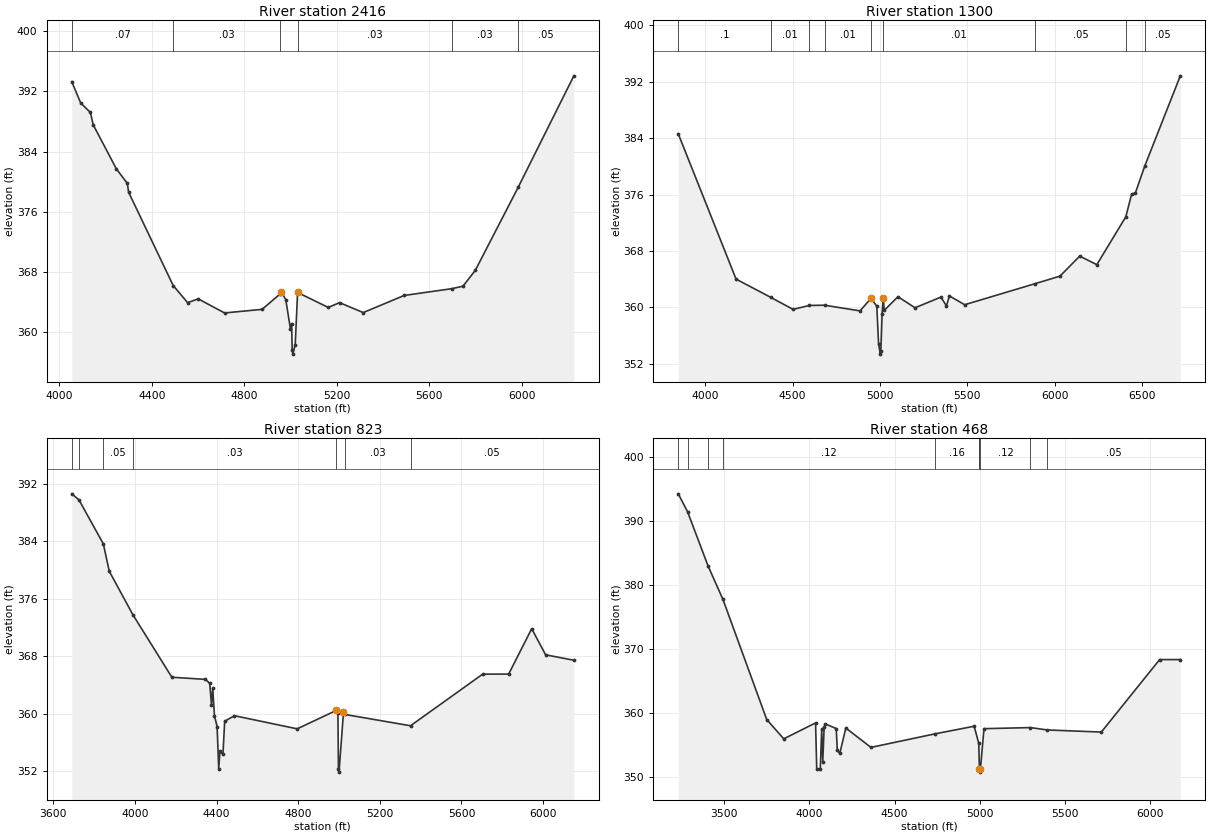
Type RM Length L Ch R = 1 ,2416    ,1116,1116,1116
BEGIN DESCRIPTION:
Mapping XS d8c508cb
END DESCRIPTION:
XS GIS Cut Line= 4
      3567733.89     10612542.92      3568424.86     10612827.64
      3568799.86     10612747.78      3569312.93     10611841.13
#Sta/Elev= 30
  4053.5  393.27  4092.1  390.44  4134.1  389.18  4146.2  387.55  4246.1  381.72
    4294  379.77  4299.4  378.61  4492.3  366.23    4555  363.95  4600.5  364.46
  4714.8  362.59  4877.3  363.07  4955.3  365.12  4960.4  365.42  4979.5  364.34
  4999.8  360.48  5004.9  361.18  5007.2  357.63  5009.9  357.13  5020.4  358.39
  5030.6  365.31  5163.5  363.32  5212.2  363.96  5314.7  362.64  5491.7  364.91
  5697.7  365.81  5746.2  366.14  5799.6  368.24  5984.7  379.23    6226  394.04
#Mann= 6 ,-1 , 0
  4053.5     .07       0  4492.3     .03       0  4955.3     .01       0
  5030.6     .03       0  5697.7     .03       0  5984.7     .05       0
Bank Sta=4960.4,5030.6
XS Rating Curve= 0 ,0
Exp/Cntr=0.3,0.1

Type RM Length L Ch R = 1 ,1300    ,477,477,477
BEGIN DESCRIPTION:
WALTHALL CREEK 1.0
END DESCRIPTION:
XS GIS Cut Line= 4
      3567751.22     10612681.79      3568560.28     10613362.37
        3568845.      10613320.7      3569355.03     10611877.36
#Sta/Elev= 30
  3844.5  384.61  4175.8  364.01  4374.8  361.42  4502.3  359.72  4595.9  360.28
  4682.4  360.31  4885.9  359.51  4948.9   361.3  4981.9  360.16    4992  354.85
  5001.9  353.38  5005.1  353.88  5012.2  359.09  5018.8   361.4  5023.9  359.57
  5103.2  361.52  5200.6  359.95  5349.1  361.46  5380.9  360.21  5397.6  361.63
  5485.1  360.38  5887.7  363.36    6031  364.43    6144  367.27  6242.1  366.06
  6408.1  372.84  6441.5  376.06  6462.8  376.21  6517.5  380.09  6720.3  392.82
#Mann= 9 ,-1 , 0
  3844.5      .1       0  4374.8     .01       0  4595.9     .01       0
  4682.4     .01       0  4948.9     .01       0  5018.8     .01       0
  5887.7     .05       0  6408.1     .16       0  6517.5     .05       0
Bank Sta=4948.9,5018.8
XS Rating Curve= 0 ,0
Exp/Cntr=0.3,0.1

Type RM Length L Ch R = 1 ,823     ,355,355,355
BEGIN DESCRIPTION:
Mapping XS cd6a8d08
END DESCRIPTION:
XS GIS Cut Line= 5
      3567697.32     10613325.61      3568330.12     10613794.36
      3568645.23     10613755.29      3569017.62     10613450.61
      3569215.53     10612599.08
#Sta/Elev= 30
  3690.2  390.64  3725.4   389.8    3845  383.66  3873.9  379.86  3989.4  373.81
  4180.7  365.09  4345.5  364.79  4366.4  364.23  4374.8  361.27    4381  363.59
  4389.4  359.71  4402.4  358.22  4410.3  352.37  4416.5  354.82  4431.1  354.34
  4439.5  358.96  4487.3  359.73  4794.9   357.9  4986.6  360.47  4994.5  360.09
    4997  352.37  4999.8  351.87  5021.7  360.18  5029.6   359.9  5350.2  358.33
  5703.8  365.52  5831.2  365.53  5944.1  371.85  6012.4  368.21  6150.6  367.46
#Mann= 7 ,-1 , 0
  3690.2     .12       0  3725.4     .08       0    3845     .05       0
  3989.4     .03       0  4986.6     .01       0  5029.6     .03       0
  5350.2     .05       0
Bank Sta=4986.6,5021.7
XS Rating Curve= 0 ,0
Exp/Cntr=0.3,0.1

Type RM Length L Ch R = 1 ,468     ,0,0,0
BEGIN DESCRIPTION:
Mapping XS 746de1fe
END DESCRIPTION:
XS GIS Cut Line= 5
      3567578.23     10613443.65      3568481.02     10614129.42
      3568884.67     10613968.83      3569114.27     10613809.98
      3569237.75     10612719.89
#Sta/Elev= 30
  3230.7  394.29  3285.1  391.51  3405.7     383    3493  377.76  3749.7  358.97
  3849.5  355.95  4036.1  358.44  4042.9  351.24  4063.7  351.25    4072  357.47
  4078.2  352.35  4086.4  357.76  4092.8  358.29  4157.2  357.56  4163.5  354.22
  4178.1  353.66  4213.4  357.64  4360.9  354.61  4738.2  356.74  4966.2  357.92
    4993  355.25    4997  351.24  4999.8  350.74    5003  351.24  5023.7  357.54
  5296.1  357.71  5394.4  357.34  5711.9  357.01  6053.7  368.35  6175.1  368.35
#Mann= 10 ,-1 , 0
  3230.7     .12       0  3285.1      .1       0  3405.7     .05       0
    3493     .12       0  4738.2     .16       0    4993     .12       0
    4997     .07       0    5003     .12       0  5296.1     .16       0
  5394.4     .05       0
Bank Sta=4997,5003
XS Rating Curve= 0 ,0
Exp/Cntr=0.3,0.1

Chan Stop Cuts=-1
Use User Specified Reach Order=0
Composite Channel Slope=5