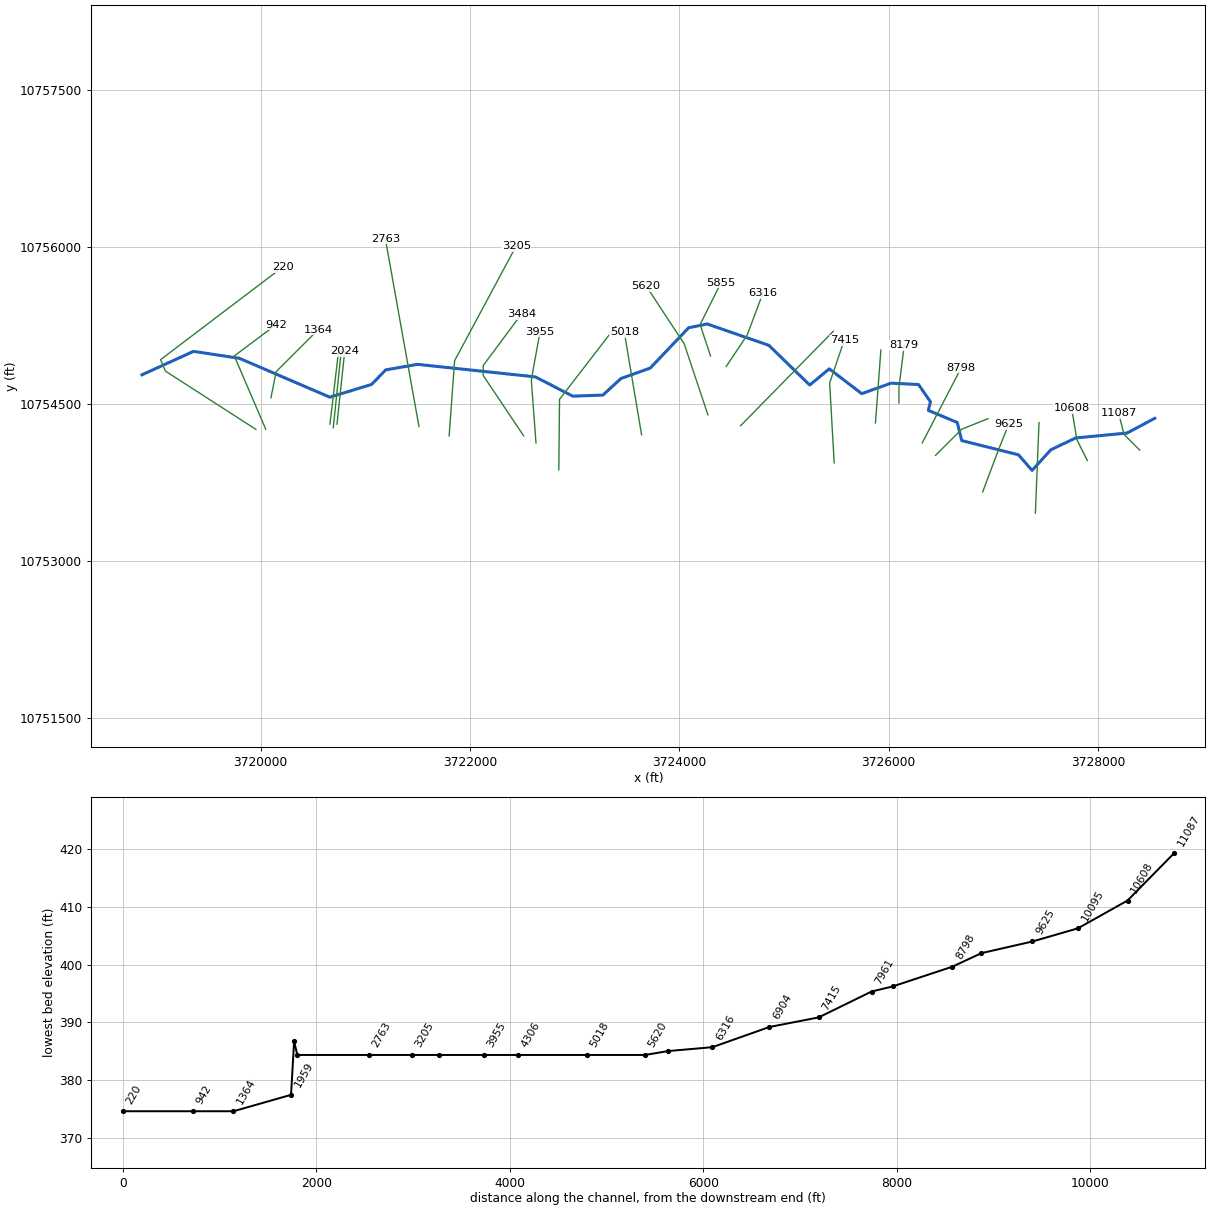
--- ALDER CREEK.prj (project) ---

Proj Title=ALDER CREEK Base Level Engineering
Current Plan=p01
Default Exp/Contr=0.3,0.1
English Units
Geom File=g01
Flow File=f01
Plan File=p01
Y Axis Title=Elevation
X Axis Title(PF)=Main Channel Distance
X Axis Title(XS)=Station
BEGIN DESCRIPTION:
ALDER CREEK
END DESCRIPTION:
DSS Export Rating Curves= 0
DSS Export Rating Curve Sorted= 0
DSS Export Volume Flow Curves= 0
DXF OffsetX= 0
DXF OffsetY= 0
DXF ScaleX= 1
DXF ScaleY= 10

--- ALDER CREEK.p01 (plan) ---

Plan Title=Multiple Run
Short Identifier=Multiple
Geom File=g01
Flow File=f01
Subcritical Flow
K Sum by GR= 0
Std Step Tol= 0.01
Critical Tol= 0.01
Num of Std Step Trials= 20
Max Error Tol= 0.3
Flow Tol Ratio= 0.001
Split Flow NTrial= 30
Split Flow Tol= 0.02
Split Flow Ratio= 0.02
Log Output Level= 0
Friction Slope Method= 1
Unsteady Friction Slope Method= 2
Unsteady Bridges Friction Slope Method= 1
Parabolic Critical Depth
Global Vel Dist=  1 , 1 , 1
Global Log Level= 0
CheckData=True
Encroach Param= -1, 0, 0, 0
BEGIN DESCRIPTION:
Multiple Run
END DESCRIPTION:

--- ALDER CREEK.f01 (steady flow) ---

Flow Title=Multiple
Number of Profiles=7
Profile Names=10-year,25-year,50-year,1pct_min,100-year,1pct_plu,500-year
River Rch & RM= ALDER CREEK,Reach-1,11087
    1059    1481    1839    1673    2263    3060    3434
River Rch & RM= ALDER CREEK,Reach-1,6904
    1212    1706    2128    1944    2629    3555    4021
River Rch & RM= ALDER CREEK,Reach-1,6316
    1295    1828    2285    2091    2827    3823    4340
River Rch & RM= ALDER CREEK,Reach-1,5620
    1462    2073    2598    2382    3221    4357    4967
River Rch & RM= ALDER CREEK,Reach-1,3955
    1509    2141    2685    2462    3330    4504    5139
River Rch & RM= ALDER CREEK,Reach-1,3205
    1716    2451    3087    2842    3844    5199    5980
Boundary for River Rch & Prof#=ALDER CREEK,Reach-1,1
Up Type=0
Dn Type=3
Dn Slope=0.005
Boundary for River Rch & Prof#=ALDER CREEK,Reach-1,2
Up Type=0
Dn Type=3
Dn Slope=0.005
Boundary for River Rch & Prof#=ALDER CREEK,Reach-1,3
Up Type=0
Dn Type=3
Dn Slope=0.005
Boundary for River Rch & Prof#=ALDER CREEK,Reach-1,4
Up Type=0
Dn Type=3
Dn Slope=0.005
Boundary for River Rch & Prof#=ALDER CREEK,Reach-1,5
Up Type=0
Dn Type=3
Dn Slope=0.005
Boundary for River Rch & Prof#=ALDER CREEK,Reach-1,6
Up Type=0
Dn Type=3
Dn Slope=0.005
Boundary for River Rch & Prof#=ALDER CREEK,Reach-1,7
Up Type=0
Dn Type=3
Dn Slope=0.005

--- ALDER CREEK.g01 (geometry) ---

Geom Title=Existing Conditions
Program Version=4.10

River Reach=ALDER CREEK     ,Reach-1
Reach XY= 30
      3728543.77     10754364.04       3728278.5       10754223.
      3727786.75       10754176.        3727551.       10754063.
      3727371.25       10753866.        3727242.       10754015.
      3726699.25       10754151.      3726656.75       10754324.
      3726380.25       10754440.        3726401.       10754522.
      3726286.25       10754687.        3726025.       10754700.
      3725743.75       10754600.        3725434.       10754837.
      3725247.25       10754682.      3724856.25       10755062.
       3724267.5       10755266.       3724090.5       10755230.
        3723723.       10754844.       3723444.5       10754745.
      3723271.25       10754586.        3722983.       10754576.
       3722625.5       10754760.      3721500.25       10754880.
        3721196.       10754827.       3721061.5       10754688.
        3720662.       10754566.       3719797.5       10754938.
        3719360.       10755004.        3718867.       10754780.

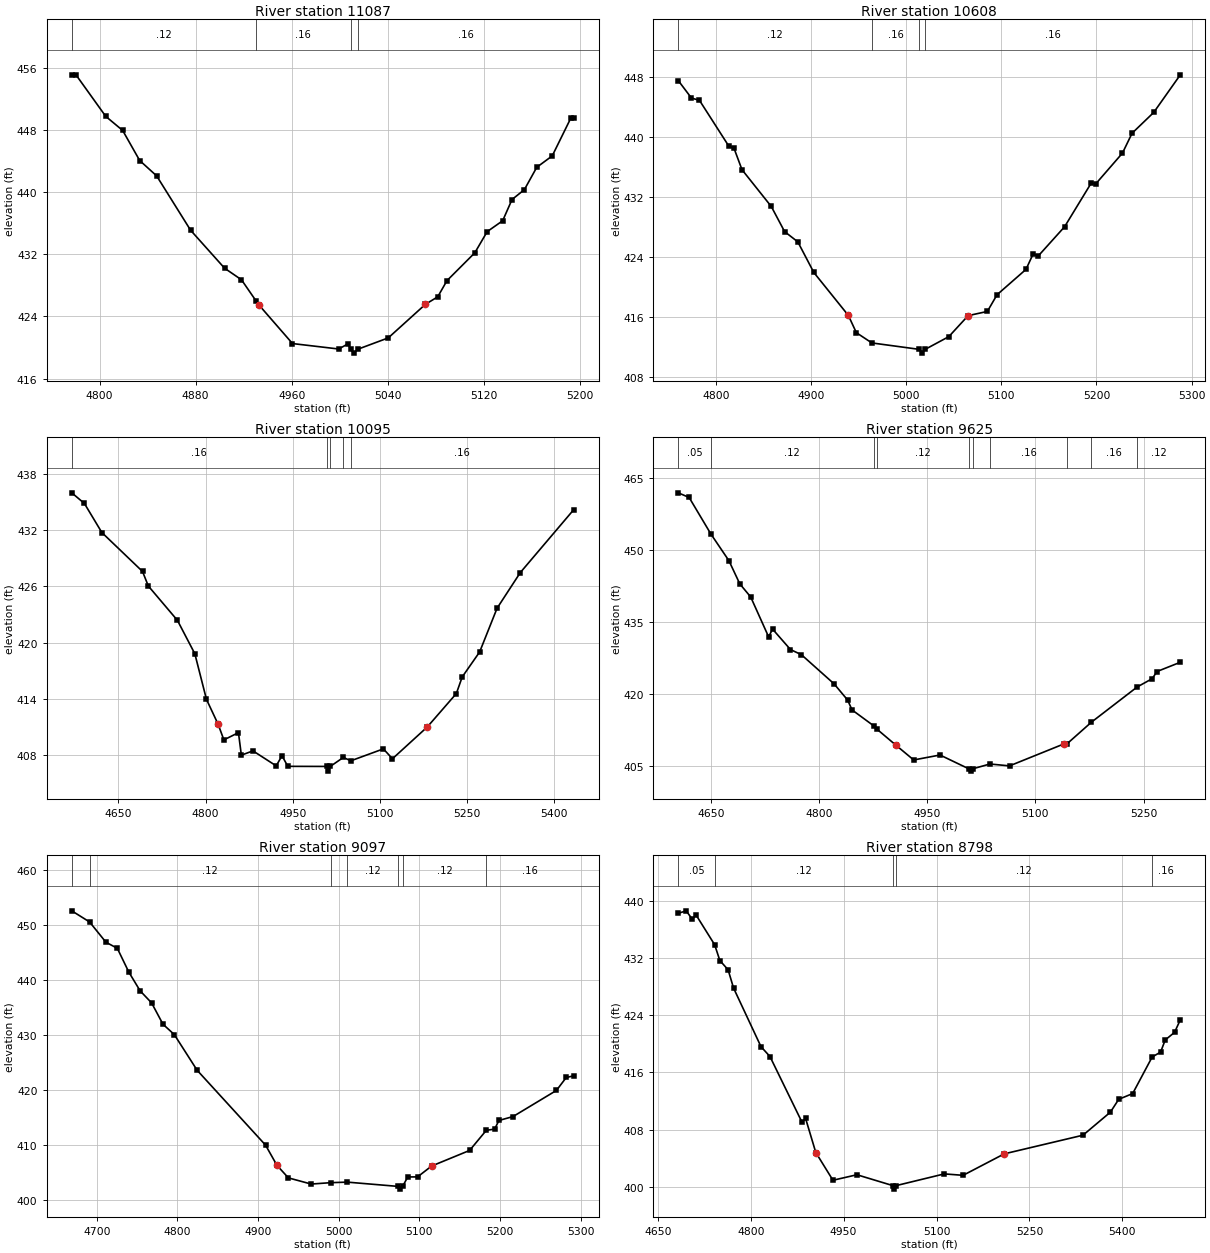
Type RM Length L Ch R = 1 ,11087   ,479,479,479
BEGIN DESCRIPTION:
ALDER CREEK 15.0
END DESCRIPTION:
XS GIS Cut Line= 3
      3728399.61     10754060.18      3728249.61     10754210.19
      3728199.61     10754410.19
#Sta/Elev= 30
  4776.8  455.07  4780.3  455.07  4805.1  449.73  4819.2  447.92  4833.4  444.05
  4847.5  442.08  4875.8  435.09  4904.1  430.21  4918.2  428.72  4930.4  425.99
  4932.4  425.54  4960.7  420.52  4999.2  419.82    5007  420.49  5009.1  419.79
  5011.9  419.29  5015.1  419.79  5040.5  421.25  5071.4  425.56  5081.7  426.53
  5089.4  428.61  5112.6  432.19  5122.9  434.91  5135.8  436.31  5143.6  439.04
  5153.9  440.31  5164.2  443.18  5177.1  444.65  5192.5  449.48  5195.1  449.48
#Mann= 4 ,-1 , 0
  4776.8     .12       0  4930.4     .16       0  5009.1     .07       0
  5015.1     .16       0
Bank Sta=4932.4,5071.4
XS Rating Curve= 0 ,0
Exp/Cntr=0.3,0.1

Type RM Length L Ch R = 1 ,10608   ,513,513,513
BEGIN DESCRIPTION:
ALDER CREEK 14.0
END DESCRIPTION:
XS GIS Cut Line= 3
      3727899.59     10753960.22      3727799.61     10754160.19
      3727749.61     10754460.18
#Sta/Elev= 30
  4760.4  447.49  4774.3  445.15  4782.7  444.85  4813.5  438.75  4819.1  438.43
  4827.4   435.6  4858.2  430.69  4872.2  427.34  4886.1  425.97  4902.9  421.89
  4939.2  416.16  4947.6  413.86  4963.9  412.49  5013.9  411.63  5016.7  411.13
  5019.9  411.63  5044.8  413.33  5065.1  416.13  5085.3  416.69  5095.5  418.92
  5125.9   422.3  5133.5  424.38  5138.6  424.06  5166.5  427.99  5194.3  433.78
  5199.4  433.73  5227.3  437.81  5237.4  440.46  5260.2  443.24  5288.1  448.25
#Mann= 4 ,-1 , 0
  4760.4     .12       0  4963.9     .16       0  5013.9     .07       0
  5019.9     .16       0
Bank Sta=4939.2,5065.1
XS Rating Curve= 0 ,0
Exp/Cntr=0.3,0.1

Type RM Length L Ch R = 1 ,10095   ,470,470,470
BEGIN DESCRIPTION:
ALDER CREEK 13.0
END DESCRIPTION:
XS GIS Cut Line= 2
      3727403.08     10753458.47      3727437.81     10754322.28
#Sta/Elev= 30
  4569.6  435.97  4591.3  434.84  4621.4  431.74  4691.4  427.59  4701.4  426.04
  4751.5  422.38  4781.5  418.82  4801.5  413.96  4821.5  411.32  4831.5  409.64
  4856.6  410.41  4861.6  408.01  4881.6  408.47  4921.6  406.87  4931.6  407.95
  4941.6  406.82  5008.7  406.81  5011.4  406.31  5014.7  406.81  5037.2  407.77
  5050.1  407.41  5106.1  408.68  5121.8  407.63  5181.8  411.02  5231.8  414.58
  5241.9  416.35  5271.9  419.01  5301.9  423.67  5341.9  427.47  5434.1  434.19
#Mann= 5 ,-1 , 0
  4569.6     .16       0  5008.7     .07       0  5014.7     .16       0
  5037.2     .12       0  5050.1     .16       0
Bank Sta=4821.5,5181.8
XS Rating Curve= 0 ,0
Exp/Cntr=0.3,0.1

Type RM Length L Ch R = 1 ,9625    ,528,528,528
BEGIN DESCRIPTION:
ALDER CREEK 12.0
END DESCRIPTION:
XS GIS Cut Line= 3
      3726899.63     10753660.23      3727049.61     10754060.19
      3727149.61     10754310.18
#Sta/Elev= 30
  4604.6  461.86  4619.7   460.9  4649.9   453.3  4674.9  447.76    4690  442.94
  4705.1  440.22    4730  431.92  4735.4  433.55  4760.3  429.29  4775.4  428.23
  4820.8  422.16  4839.5  418.81  4845.7  416.75  4875.5  413.47    4880  412.78
  4906.3  409.45  4931.2  406.35  4967.7  407.38  5007.4  404.53  5010.1  404.03
  5013.4  404.53    5037  405.51  5064.1  405.12  5139.5  409.68  5144.2  409.75
  5177.8  414.21  5241.2  421.52    5262  423.24  5268.7  424.73    5301  426.65
#Mann= 10 ,-1 , 0
  4604.6     .05       0  4649.9     .12       0  4875.5     .16       0
    4880     .12       0  5007.4     .07       0  5013.4     .12       0
    5037     .16       0  5144.2     .12       0  5177.8     .16       0
  5241.2     .12       0
Bank Sta=4906.3,5139.5
XS Rating Curve= 0 ,0
Exp/Cntr=0.3,0.1

Type RM Length L Ch R = 1 ,9097    ,299,299,299
BEGIN DESCRIPTION:
ALDER CREEK 11.0
END DESCRIPTION:
XS GIS Cut Line= 3
      3726449.63     10754010.21      3726699.61     10754260.19
      3726949.63      10754360.2
#Sta/Elev= 30
  4668.9  452.51    4691  450.49  4711.3  446.81  4725.4  445.71  4739.6  441.41
  4753.7  437.99  4767.9  435.81    4782  431.94  4796.1  430.05  4824.4  423.58
  4909.3  409.99  4923.4  406.33  4937.6  404.05  4965.9  402.93  4989.9  403.18
  5010.7  403.28  5073.3  402.51    5076  402.01  5079.3  402.51  5085.7  404.22
  5097.8  404.23  5115.3   406.2  5162.4  409.03  5183.1  412.68  5193.4   412.9
  5198.8  414.47  5216.3  415.18  5270.1  419.92  5282.3  422.27  5291.7  422.57
#Mann= 7 ,-1 , 0
  4668.9     .05       0    4691     .12       0  4989.9     .16       0
  5010.7     .12       0  5073.3     .07       0  5079.3     .12       0
  5183.1     .16       0
Bank Sta=4923.4,5115.3
XS Rating Curve= 0 ,0
Exp/Cntr=0.3,0.1

Type RM Length L Ch R = 1 ,8798    ,619,619,619
BEGIN DESCRIPTION:
ALDER CREEK 10.0
END DESCRIPTION:
XS GIS Cut Line= 2
      3726322.09      10754128.7      3726694.97     10754848.45
#Sta/Elev= 30
    4683  438.23  4695.9  438.58  4705.9  437.37  4711.5  438.04  4741.8  433.84
  4750.2  431.63  4763.5  430.34  4772.3  427.79  4816.6  419.59  4831.1  418.21
  4882.9  409.01  4888.6  409.56  4905.1  404.79  4932.8  400.91  4971.5  401.68
  5029.2  400.17    5032  399.67  5035.2  400.17  5112.6   401.8  5142.9   401.6
  5209.3   404.6  5336.5  407.21  5380.7  410.43  5394.2  412.23  5416.7  413.03
  5448.2  418.15  5461.8  418.83  5469.2  420.52  5484.3  421.59  5493.6  423.34
#Mann= 5 ,-1 , 0
    4683     .05       0  4741.8     .12       0  5029.2     .07       0
  5035.2     .12       0  5448.2     .16       0
Bank Sta=4905.1,5209.3
XS Rating Curve= 0 ,0
Exp/Cntr=0.3,0.1

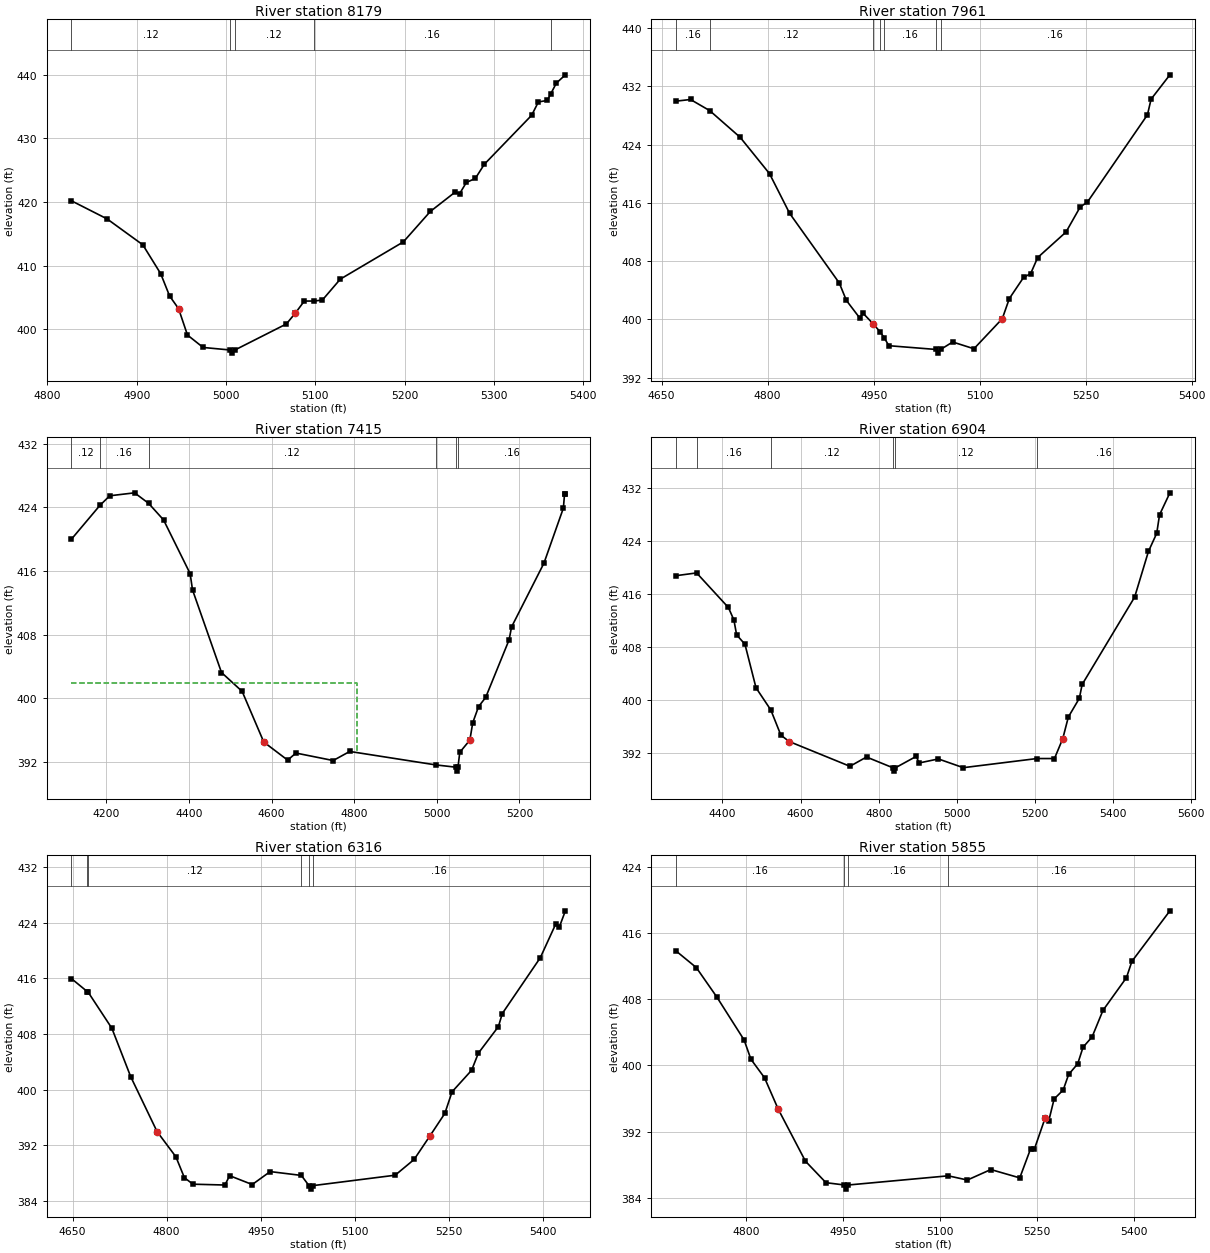
Type RM Length L Ch R = 1 ,8179    ,218,218,218
BEGIN DESCRIPTION:
ALDER CREEK 9.0
END DESCRIPTION:
XS GIS Cut Line= 3
      3726099.61     10754510.22      3726099.61     10754660.19
      3726149.61      10755060.2
#Sta/Elev= 30
  4826.9  420.17  4866.9  417.32  4906.9  413.25  4926.9  408.72  4936.9  405.21
  4946.9  403.23  4956.9  399.08  4974.4  397.13  5004.1  396.74  5006.9  396.24
  5010.1  396.74  5067.6  400.82  5077.6  402.51  5087.7  404.42  5098.2  404.42
  5107.9  404.57    5128  407.86  5198.6  413.71  5228.8  418.49  5256.5  421.52
  5261.6  421.28  5269.1  423.04  5279.2  423.68  5289.3  425.91  5342.2  433.59
  5349.8  435.69  5359.8  435.93  5363.5  436.93  5369.9  438.65    5380  439.95
#Mann= 5 ,-1 , 0
  4826.9     .12       0  5004.1     .07       0  5010.1     .12       0
  5098.2     .16       0  5363.5     .12       0
Bank Sta=4946.9,5077.6
XS Rating Curve= 0 ,0
Exp/Cntr=0.3,0.1

Type RM Length L Ch R = 1 ,7961    ,546,546,546
BEGIN DESCRIPTION:
ALDER CREEK 8.0
END DESCRIPTION:
XS GIS Cut Line= 2
      3725875.01     10754319.59      3725926.98     10755016.75
#Sta/Elev= 30
  4670.1  429.98  4690.8  430.21    4718  428.68    4761  425.02  4802.6  420.02
  4831.1  414.56  4901.3     405  4911.4   402.6  4930.1  400.21  4935.1  400.83
  4948.9  399.42  4959.3  398.27  4964.7   397.5  4971.5  396.38  5038.7  395.86
  5041.5  395.36  5044.7  395.86  5061.8  396.89  5091.9  395.96    5132  400.09
    5142  402.86  5162.1  405.76  5172.1  406.28  5182.1  408.49  5222.2     412
  5242.3  415.45  5252.3  416.09  5337.4   428.1  5342.6  430.26  5369.2   433.6
#Mann= 7 ,-1 , 0
  4670.1     .16       0    4718     .12       0  4948.9     .16       0
  4959.3     .12       0  4964.7     .16       0  5038.7     .07       0
  5044.7     .16       0
Bank Sta=4948.9,5132
XS Rating Curve= 0 ,0
Exp/Cntr=0.3,0.1

Type RM Length L Ch R = 1 ,7415    ,511,511,511
BEGIN DESCRIPTION:
ALDER CREEK 7.0
END DESCRIPTION:
XS GIS Cut Line= 3
      3725480.88     10753937.32      3725437.48     10754701.24
      3725576.35      10755109.2
#Sta/Elev= 30
    4115  419.99  4184.4  424.26    4208  425.45  4268.1  425.82    4302   424.5
  4338.2  422.42  4402.6  415.67  4408.3  413.64  4478.5  403.26  4528.5  400.89
  4580.9  394.53  4638.7  392.26  4658.7  393.15  4748.9  392.21    4789  393.35
  4997.4  391.66  5045.1  391.38  5047.8  390.88  5051.1  391.38  5055.4  393.24
  5079.8  394.77  5086.8  396.95  5100.9  398.98  5118.1  400.13  5174.8  407.36
  5180.8  408.98  5259.3     417  5306.3  423.91    5309  425.62  5311.1  425.62
#Mann= 6 ,-1 , 0
    4115     .12       0  4184.4     .16       0    4302     .12       0
  4997.4     .16       0  5045.1     .07       0  5051.1     .16       0
#XS Ineff= 2 , 0
         4807.39  401.96
Permanent Ineff=
       F       F
Bank Sta=4580.9,5079.8
XS Rating Curve= 0 ,0
Exp/Cntr=0.3,0.1

Type RM Length L Ch R = 1 ,6904    ,588,588,588
BEGIN DESCRIPTION:
ALDER CREEK 6.0
END DESCRIPTION:
XS GIS Cut Line= 2
      3724586.76     10754293.24      3725471.76     10755195.58
#Sta/Elev= 30
  4281.1  418.71  4334.1  419.13  4415.4  413.91  4429.5  412.03  4436.5  409.78
  4457.8  408.36  4486.1  401.79    4524  398.44  4549.7  394.64    4571  393.68
  4726.4  389.94  4768.8  391.34  4836.6  389.71  4839.3  389.21  4842.6  389.71
  4896.1  391.44  4903.3  390.44  4952.7  391.05  5016.4  389.73  5204.9  391.11
  5249.7  391.11    5271  394.13  5285.2  397.38  5313.3   400.2  5320.5  402.29
  5454.8  415.48  5490.2  422.39  5511.3  425.11  5518.5   427.9    5545  431.22
#Mann= 6 ,-1 , 0
  4281.1      .1       0  4334.1     .16       0    4524     .12       0
  4836.6     .07       0  4842.6     .12       0  5204.9     .16       0
Bank Sta=4571,5271
XS Rating Curve= 0 ,0
Exp/Cntr=0.3,0.1

Type RM Length L Ch R = 1 ,6316    ,461,461,461
BEGIN DESCRIPTION:
ALDER CREEK 5.0
END DESCRIPTION:
XS GIS Cut Line= 3
      3724449.63     10754860.22      3724649.61     10755160.19
       3724799.6     10755560.17
#Sta/Elev= 30
  4648.1  415.98  4673.8  414.08  4674.8  414.03  4712.7  408.83  4742.7  401.88
  4784.8  393.98  4814.8  390.36  4828.3  387.37  4841.9  386.43  4892.9  386.31
  4900.5  387.65  4936.5  386.38  4965.1  388.24  5014.8  387.69    5027  386.22
  5029.7  385.72    5033  386.22  5164.4  387.72  5194.6  389.98  5219.5  393.32
  5243.6   396.6  5255.1   399.7  5286.3   402.8    5297  405.25    5329  409.07
  5335.2  410.95  5395.8  418.97  5420.7  423.87    5426  423.34  5435.8  425.71
#Mann= 6 ,-1 , 0
  4648.1     .12       0  4673.8     .07       0  4674.8     .12       0
  5014.8     .16       0    5027     .07       0    5033     .16       0
Bank Sta=4784.8,5219.5
XS Rating Curve= 0 ,0
Exp/Cntr=0.3,0.1

Type RM Length L Ch R = 1 ,5855    ,235,235,235
BEGIN DESCRIPTION:
ALDER CREEK 4.0
END DESCRIPTION:
XS GIS Cut Line= 3
       3724299.6     10754960.22      3724199.61     10755260.19
      3724399.61     10755660.18
#Sta/Elev= 30
  4691.7  413.87  4723.3  411.84  4754.9  408.29  4797.1  403.09  4807.6  400.76
  4828.7  398.51  4849.8  394.72  4891.9  388.42  4923.6  385.82  4952.2  385.54
  4954.9  385.04  4958.2  385.54  5112.6  386.65  5142.1  386.14  5178.4  387.41
  5223.1   386.4  5239.9  389.93  5245.5  389.84  5262.2  393.62  5267.8  393.27
  5276.2  395.95  5290.2  397.03  5298.6  398.91  5312.6   400.2  5320.9  402.21
  5334.9  403.46  5351.7  406.67    5388  410.63  5396.4   412.6  5455.1  418.71
#Mann= 4 ,-1 , 0
  4691.7     .16       0  4952.2     .07       0  4958.2     .16       0
  5112.6     .16       0
Bank Sta=4849.8,5262.2
XS Rating Curve= 0 ,0
Exp/Cntr=0.3,0.1

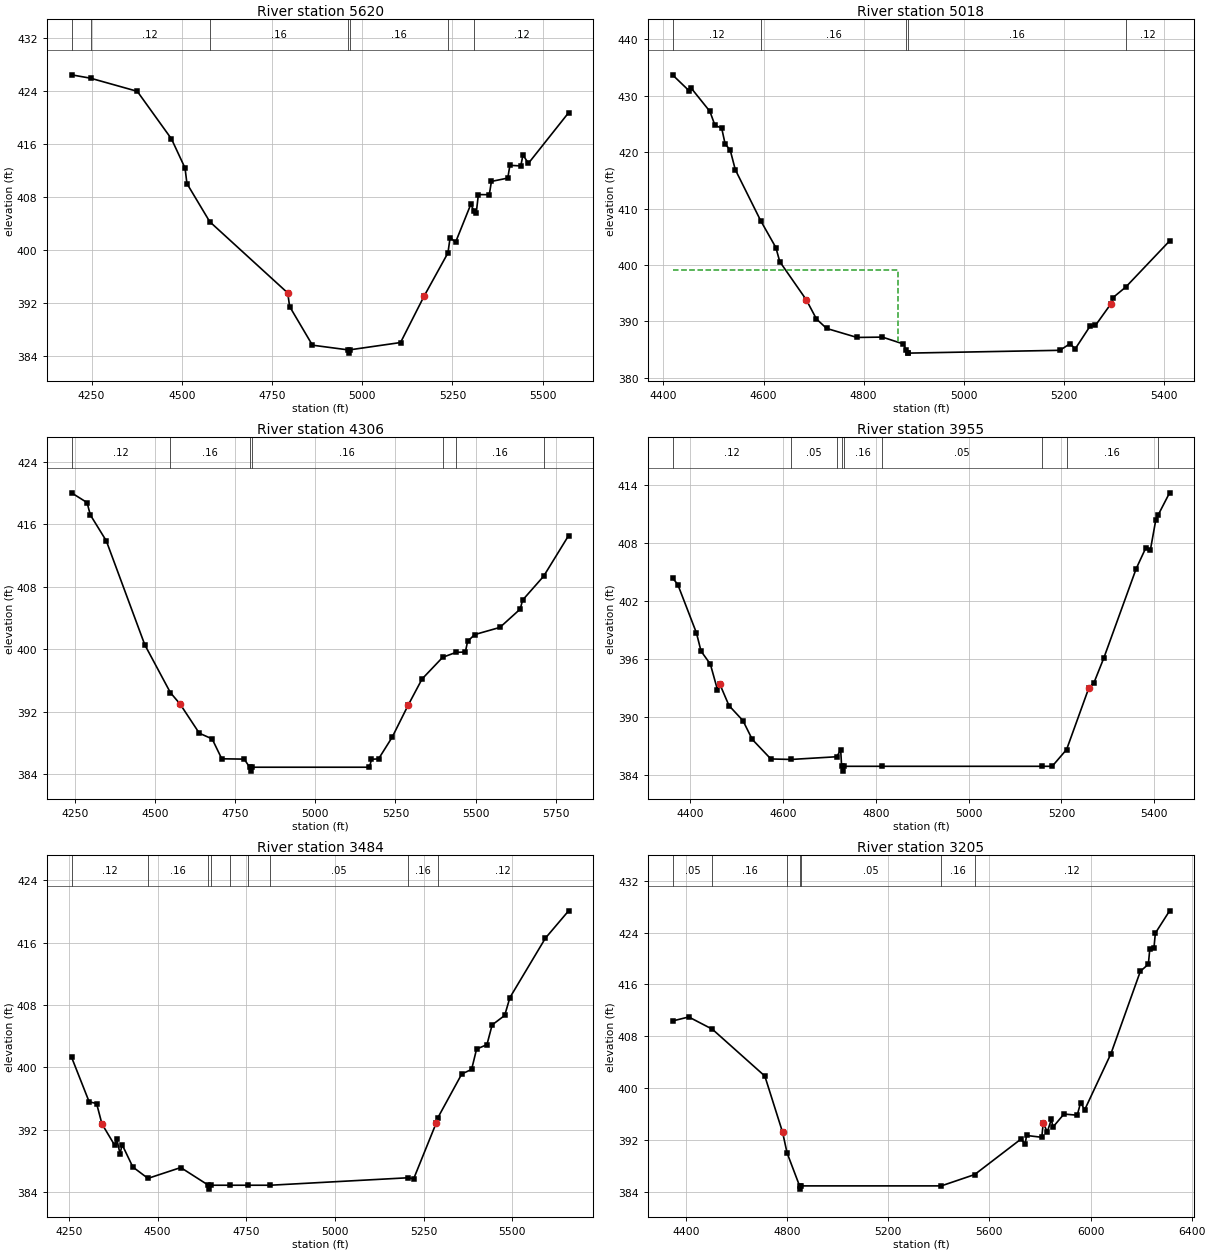
Type RM Length L Ch R = 1 ,5620    ,602,602,602
BEGIN DESCRIPTION:
ALDER CREEK 3.0
END DESCRIPTION:
XS GIS Cut Line= 3
       3724274.3     10754397.37      3724048.59      10755074.5
      3723684.31     10755629.59
#Sta/Elev= 30
  4194.4  426.41  4247.1   425.9  4376.6  423.92  4471.4  416.73    4509  412.33
  4514.3  409.98  4577.5  404.22  4793.6  393.46  4798.9  391.41  4862.1  385.57
  4959.8  384.87  4962.6  384.37  4965.8  384.87  5106.3  385.97  5171.3  392.95
  5237.7  399.51  5243.7  401.83  5258.8  401.12  5300.9  406.83  5310.7  405.79
    5316  405.49    5322  408.32  5352.2   408.3  5358.2  410.31  5403.5  410.81
  5409.4  412.74  5439.6  412.65  5445.6  414.31  5460.7  413.04  5572.1  420.69
#Mann= 7 ,-1 , 0
  4194.4      .1       0  4247.1     .12       0  4577.5     .16       0
  4959.8     .07       0  4965.8     .16       0  5237.7     .16       0
  5310.7     .12       0
Bank Sta=4793.6,5171.3
XS Rating Curve= 0 ,0
Exp/Cntr=0.3,0.1

Type RM Length L Ch R = 1 ,5018    ,712,712,712
BEGIN DESCRIPTION:
ALDER CREEK 2.0
END DESCRIPTION:
XS GIS Cut Line= 2
       3723640.6     10754206.46      3723475.85     10755186.31
#Sta/Elev= 30
    4418  433.71  4450.6  430.93  4455.7  431.32  4492.8  427.22  4502.9  424.74
  4516.3  424.27  4523.2  421.45  4533.3  420.38  4543.5   416.9  4594.2  407.86
  4624.6  403.09  4632.4  400.59  4685.4  393.83  4705.7  390.43    4726  388.75
  4786.8  387.15  4837.5  387.21  4879.7  385.99  4885.2  384.87    4888  384.37
  4888.5  384.37  5192.4  384.87  5212.7  386.05  5222.9  385.12  5253.3  389.24
  5263.4  389.28  5293.6  393.02  5298.7  394.23  5324.3  396.11  5411.6  404.26
#Mann= 5 ,-1 , 0
    4418     .12       0  4594.2     .16       0  4885.2     .07       0
  4888.5     .16       0  5324.3     .12       0
#XS Ineff= 2 , 0
         4868.41  399.15
Permanent Ineff=
       F       F
Bank Sta=4685.4,5293.6
XS Rating Curve= 0 ,0
Exp/Cntr=0.3,0.1

Type RM Length L Ch R = 1 ,4306    ,351,351,351
BEGIN DESCRIPTION:
ALDER CREEK 1.0
END DESCRIPTION:
XS GIS Cut Line= 3
      3722849.84      10753871.7      3722856.79     10754545.32
       3723391.5     10755239.76
#Sta/Elev= 30
  4239.9  420.04  4288.4  418.79  4298.4  417.22  4348.4  413.88  4468.4  400.56
  4548.4  394.42  4578.4  392.97  4638.4  389.23  4678.4   388.5  4708.4  385.95
  4778.4  385.91  4795.4  384.87  4798.2  384.37  4801.4  384.87    5169  384.87
  5175.3  385.89  5197.4  385.94  5239.7  388.71  5289.5  392.81    5333  396.18
  5397.3  398.96  5438.9  399.59    5468  399.64    5475     401    5497  401.87
  5575.8  402.79  5639.1  405.14  5646.5  406.29  5712.1  409.35    5790  414.56
#Mann= 7 ,-1 , 0
  4239.9     .12       0  4548.4     .16       0  4795.4     .07       0
  4801.4     .16       0  5397.3     .12       0  5438.9     .16       0
  5712.1     .12       0
Bank Sta=4578.4,5289.5
XS Rating Curve= 0 ,0
Exp/Cntr=0.3,0.1

Type RM Length L Ch R = 1 ,3955    ,471,471,471
BEGIN DESCRIPTION:
Mapping XS as3986fg
END DESCRIPTION:
XS GIS Cut Line= 4
      3722631.81     10754128.82      3722587.87     10754720.68
      3722600.79     10754808.55      3722670.57     10755191.04
#Sta/Elev= 30
    4362  404.39  4373.4   403.7  4413.5   398.7  4423.5   396.8  4443.6  395.45
  4458.9   392.8    4464  393.38  4483.7  391.16  4513.8   389.6  4533.8  387.66
  4573.9  385.63  4617.8  385.58  4715.8  385.86  4724.4  386.56  4726.4  384.87
  4729.1  384.37  4732.4  384.87  4813.8  384.87  5158.7  384.87  5180.1  384.87
  5211.2  386.61  5259.4  393.03  5269.6  393.46  5291.7  396.13  5361.1  405.34
  5381.4  407.45  5391.6  407.25  5403.4   410.4  5408.1  410.87  5433.1   413.2
#Mann= 9 ,-1 , 0
    4362     .12       0  4617.8     .05       0  4715.8     .16       0
  4726.4    .033       0  4732.4     .16       0  4813.8     .05       0
  5158.7     .12       0  5211.2     .16       0  5408.1     .12       0
Bank Sta=4464,5259.4
XS Rating Curve= 0 ,0
Exp/Cntr=0.3,0.1

Type RM Length L Ch R = 1 ,3484    ,279,279,279
BEGIN DESCRIPTION:
Mapping XS 605903ce
END DESCRIPTION:
XS GIS Cut Line= 4
      3722513.89     10754196.38      3722127.62     10754773.62
      3722127.62     10754869.11      3722492.23     10755359.59
#Sta/Elev= 30
  4257.5  401.32  4307.2  395.58  4328.2  395.36  4343.2  392.75  4379.2     390
  4385.3  390.77  4394.2  388.92  4400.3  390.07  4430.3  387.21    4473  385.75
  4565.4  387.14  4643.4  384.87  4646.2  384.37  4649.4  384.87    4703  384.87
  4754.7  384.87  4817.9  384.87  5206.5  385.83    5222   385.7  5285.6  392.87
  5289.7   393.5  5357.6  399.16  5385.3  399.74  5399.3  402.35  5428.5  402.92
  5443.1  405.45  5478.5  406.67  5493.2  408.96  5593.3  416.59  5658.7   420.1
#Mann= 9 ,-1 , 0
  4257.5     .12       0    4473     .16       0  4643.4    .035       0
  4649.4     .16       0    4703     .05       0  4754.7     .16       0
  4817.9     .05       0  5206.5     .16       0  5289.7     .12       0
Bank Sta=4343.2,5285.6
XS Rating Curve= 0 ,0
Exp/Cntr=0.3,0.1

Type RM Length L Ch R = 1 ,3205    ,442,442,442
BEGIN DESCRIPTION:
Mapping XS ec5962gh
END DESCRIPTION:
XS GIS Cut Line= 3
      3721802.15     10754196.05      3721854.23     10754914.79
       3722442.7     10756012.02
#Sta/Elev= 30
    4347  410.35  4411.3  410.97  4504.5  409.08  4712.1  401.84  4782.3  393.16
  4800.1  389.96  4849.5  384.87  4852.2  384.37  4855.5  384.87  5409.9  384.87
  5541.8  386.62  5725.3  392.11  5741.5  391.35  5747.2  392.66  5807.3  392.38
    5813  394.56  5829.2  393.21  5845.4   395.2  5851.2  393.94    5895  395.97
  5947.5  395.79  5960.8  397.74    5977  396.63    6081  405.32  6197.1  418.03
  6228.8  419.12  6234.5  421.51  6250.7  421.57  6256.4  423.92  6312.7  427.37
#Mann= 7 ,-1 , 0
    4347     .05       0  4504.5     .16       0  4800.1     .05       0
  4849.5    .033       0  4855.5     .05       0  5409.9     .16       0
  5541.8     .12       0
Bank Sta=4782.3,5813
XS Rating Curve= 0 ,0
Exp/Cntr=0.3,0.1

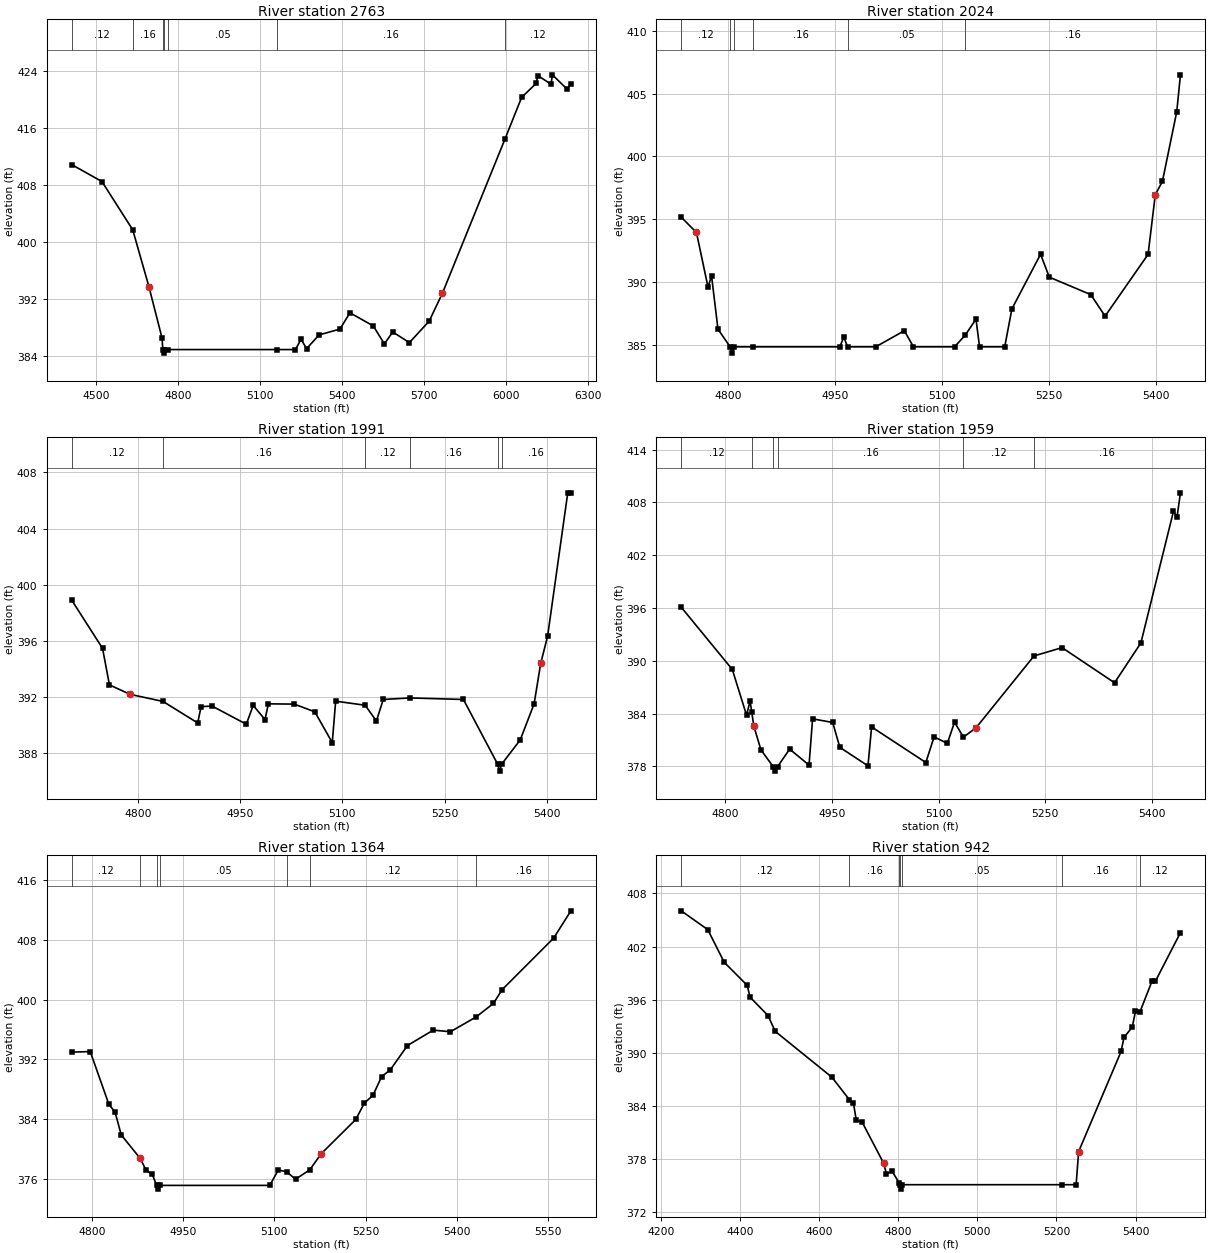
Type RM Length L Ch R = 1 ,2763    ,739,739,739
BEGIN DESCRIPTION:
Mapping XS bt6738ye
END DESCRIPTION:
XS GIS Cut Line= 2
      3721513.86     10754284.61      3721192.69     10756081.43
#Sta/Elev= 30
  4411.1  410.87    4522  408.48  4634.5   401.7  4693.6  393.72  4741.8  386.46
  4744.4  384.87  4747.1  384.37  4750.4  384.87  4765.2  384.87  5160.8  384.87
  5229.4  384.87  5249.8  386.32  5270.1     385    5316  386.93    5392  387.75
  5428.7  390.04  5513.9  388.19  5554.5  385.67    5585  387.34  5645.9  385.85
  5718.1  388.85  5766.8   392.8  5996.2  414.53  6056.2   420.3    6110   422.3
  6115.1  423.38  6163.8  422.17  6168.9  423.48  6222.7  421.46  6236.4  422.22
#Mann= 7 ,-1 , 0
  4411.1     .12       0  4634.5     .16       0  4744.4    .033       0
  4750.4     .16       0  4765.2     .05       0  5160.8     .16       0
  5996.2     .12       0
Bank Sta=4693.6,5766.8
XS Rating Curve= 0 ,0
Exp/Cntr=0.3,0.1

Type RM Length L Ch R = 1 ,2024    ,33,33,33
BEGIN DESCRIPTION:
Mapping XS ct0257gs
END DESCRIPTION:
XS GIS Cut Line= 2
      3720730.54     10754308.91       3720804.3     10755005.31
#Sta/Elev= 30
  4733.8  395.18  4755.2  393.96  4771.4  389.62  4776.4   390.5  4785.4  386.27
  4802.5  384.87  4805.2  384.37  4808.5  384.87  4835.2  384.87  4956.3  384.87
  4961.8  385.63  4967.3  384.87  5006.6  384.87  5046.8  386.15  5059.6  384.87
  5117.2  384.87  5132.1  385.79  5147.3  387.07  5152.3  384.87  5187.6  384.87
  5197.7  387.89  5237.9  392.23  5250.1  390.41  5308.3  389.02  5328.4  387.31
  5388.7  392.22  5398.8  396.96  5408.8  398.02  5428.9  403.56  5434.1  406.49
#Mann= 6 ,-1 , 0
  4733.8     .12       0  4802.5    .033       0  4808.5     .12       0
  4835.2     .16       0  4967.3     .05       0  5132.1     .16       0
Bank Sta=4755.2,5398.8
XS Rating Curve= 0 ,0
Exp/Cntr=0.3,0.1

Type RM Length L Ch R = 1 ,1991    ,32,32,32
BEGIN DESCRIPTION:
Mapping XS 572dabcd
END DESCRIPTION:
XS GIS Cut Line= 2
      3720695.13     10754275.02      3720770.65     10755004.22
#Sta/Elev= 30
  4702.4  398.91  4747.8  395.47  4757.9  392.87    4788   392.2  4836.6  391.69
  4887.5  390.16  4892.5  391.32  4908.7  391.36  4958.9  390.07    4969  391.41
  4986.3   390.4  4991.3  391.52  5029.3   391.5  5059.5  390.95  5085.1  388.76
  5090.1  391.71  5133.4  391.42  5149.9   390.3    5160  391.83  5199.5  391.94
  5277.7  391.83  5327.9  387.23  5330.7  386.73  5333.9  387.23  5361.1  388.95
  5381.5  391.52  5391.2  394.41  5401.3  396.33  5430.9  406.54  5435.5  406.54
#Mann= 6 ,-1 , 0
  4702.4     .12       0  4836.6     .16       0  5133.4     .12       0
  5199.5     .16       0  5327.9     .07       0  5333.9     .16       0
Bank Sta=4788,5391.2
XS Rating Curve= 0 ,0
Exp/Cntr=0.3,0.1

Type RM Length L Ch R = 1 ,1959    ,595,595,595
BEGIN DESCRIPTION:
Mapping XS bd6931tx
END DESCRIPTION:
XS GIS Cut Line= 2
      3720663.26     10754308.84      3720745.71     10755005.38
#Sta/Elev= 30
  4738.5  396.09  4810.3  389.01  4830.3  383.82  4835.3  385.43  4837.5  384.23
  4840.6  382.54  4850.6  379.87  4867.8  377.96  4870.5  377.46  4873.8  377.96
  4890.9  379.96  4918.1  378.14  4923.1   383.4  4951.3  382.99  4961.4  380.16
  5000.9  378.06    5006  382.48  5082.2  378.44  5093.8  381.35  5112.4  380.61
  5122.5  383.02    5135  381.32  5152.7  382.38  5234.2  390.55  5273.6  391.49
  5347.3   387.5  5384.3  392.02  5430.1  406.98  5435.1  406.34  5439.9  409.08
#Mann= 6 ,-1 , 0
  4738.5     .12       0  4837.5     .16       0  4867.8     .07       0
  4873.8     .16       0    5135     .12       0  5234.2     .16       0
Bank Sta=4840.6,5152.7
XS Rating Curve= 0 ,0
Exp/Cntr=0.3,0.1

Type RM Length L Ch R = 1 ,1364    ,422,422,422
BEGIN DESCRIPTION:
Mapping XS ac29583s
END DESCRIPTION:
XS GIS Cut Line= 3
       3720099.6     10754560.15      3720149.61     10754810.19
      3720549.62      10755210.2
#Sta/Elev= 30
  4766.9  392.97  4797.5  393.04  4828.1  385.98  4838.3  384.93  4848.5  381.87
  4879.5  378.75  4889.3  377.15  4899.5  376.58  4906.7  375.12  4909.5  374.62
  4912.7  375.12  5092.6  375.12  5106.7  377.19  5120.2  376.94    5135  375.95
  5158.3   377.2  5177.5  379.39    5234  383.95  5248.2  386.15  5262.3  387.19
  5276.5  389.69  5290.6  390.58  5318.9  393.85  5361.3  395.91  5389.6   395.7
  5431.7  397.67  5460.3  399.49  5474.4  401.32  5559.3  408.24  5587.6  411.89
#Mann= 7 ,-1 , 0
  4766.9     .12       0  4879.5     .05       0  4906.7    .033       0
  4912.7     .05       0  5120.2     .16       0  5158.3     .12       0
  5431.7     .16       0
Bank Sta=4879.5,5177.5
XS Rating Curve= 0 ,0
Exp/Cntr=0.3,0.1

Type RM Length L Ch R = 1 ,942     ,722,722,722
BEGIN DESCRIPTION:
Mapping XS sd4593re
END DESCRIPTION:
XS GIS Cut Line= 3
      3720049.61     10754260.18      3719749.61     10754960.19
      3720149.62      10755260.2
#Sta/Elev= 30
  4251.7  406.03  4318.8  403.91  4360.5  400.22  4418.5  397.62  4425.8  396.28
  4471.1  394.21  4489.2  392.43  4632.5  387.25    4677   384.7  4686.9  384.33
  4694.1  382.41  4708.7   382.2    4763  377.57  4770.3  376.37  4784.8  376.63
  4802.8   375.3  4803.6  375.12  4806.3  374.62  4809.6  375.12  5213.1  375.12
  5249.7  375.12    5256  378.86  5363.3  390.16  5370.6  391.74  5391.4   392.9
  5399.7   394.7  5410.6  394.58  5441.4  398.09  5449.7  398.06  5513.3  403.57
#Mann= 7 ,-1 , 0
  4251.7     .12       0    4677     .16       0  4802.8     .05       0
  4803.6    .033       0  4809.6     .05       0  5213.1     .16       0
  5410.6     .12       0
Bank Sta=4763,5256
XS Rating Curve= 0 ,0
Exp/Cntr=0.3,0.1

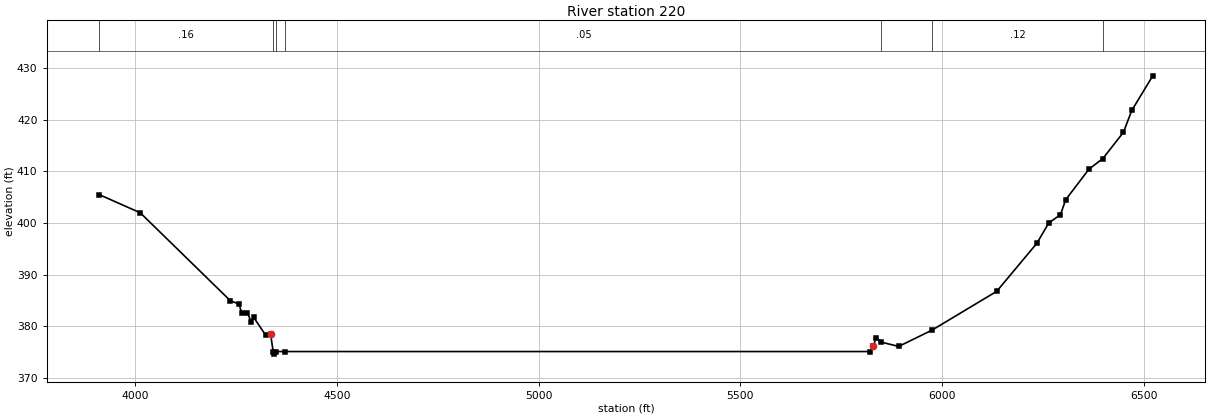
Type RM Length L Ch R = 1 ,220     ,0,0,0
BEGIN DESCRIPTION:
Mapping XS we3503eg
END DESCRIPTION:
XS GIS Cut Line= 4
      3719956.25     10754257.95      3719091.65     10754815.25
      3719044.77     10754924.63      3720211.47     10755810.07
#Sta/Elev= 30
  3910.5  405.47  4011.9  401.97  4235.7  384.93  4256.8  384.33  4263.4  382.59
  4277.9  382.57  4287.1  380.85  4293.1  381.76  4322.9  378.29  4335.3  378.43
  4341.6  375.12  4344.3  374.62  4347.6  375.12  4371.8  375.12  5821.9  375.12
    5830  376.14  5836.4  377.75  5849.8  376.93  5892.8  376.11  5975.2  379.25
  6135.9  386.77  6235.8   396.1  6264.9     400  6293.9  401.59    6307   404.5
  6364.7  410.41  6399.1  412.46    6450  417.52  6470.8  421.76  6522.8  428.46
#Mann= 7 ,-1 , 0
  3910.5     .16       0  4341.6    .033       0  4347.6     .16       0
  4371.8     .05       0  5849.8     .16       0  5975.2     .12       0
  6399.1     .16       0
Bank Sta=4335.3,5830
XS Rating Curve= 0 ,0
Exp/Cntr=0.3,0.1

Chan Stop Cuts=-1
Use User Specified Reach Order=0
Composite Channel Slope=5