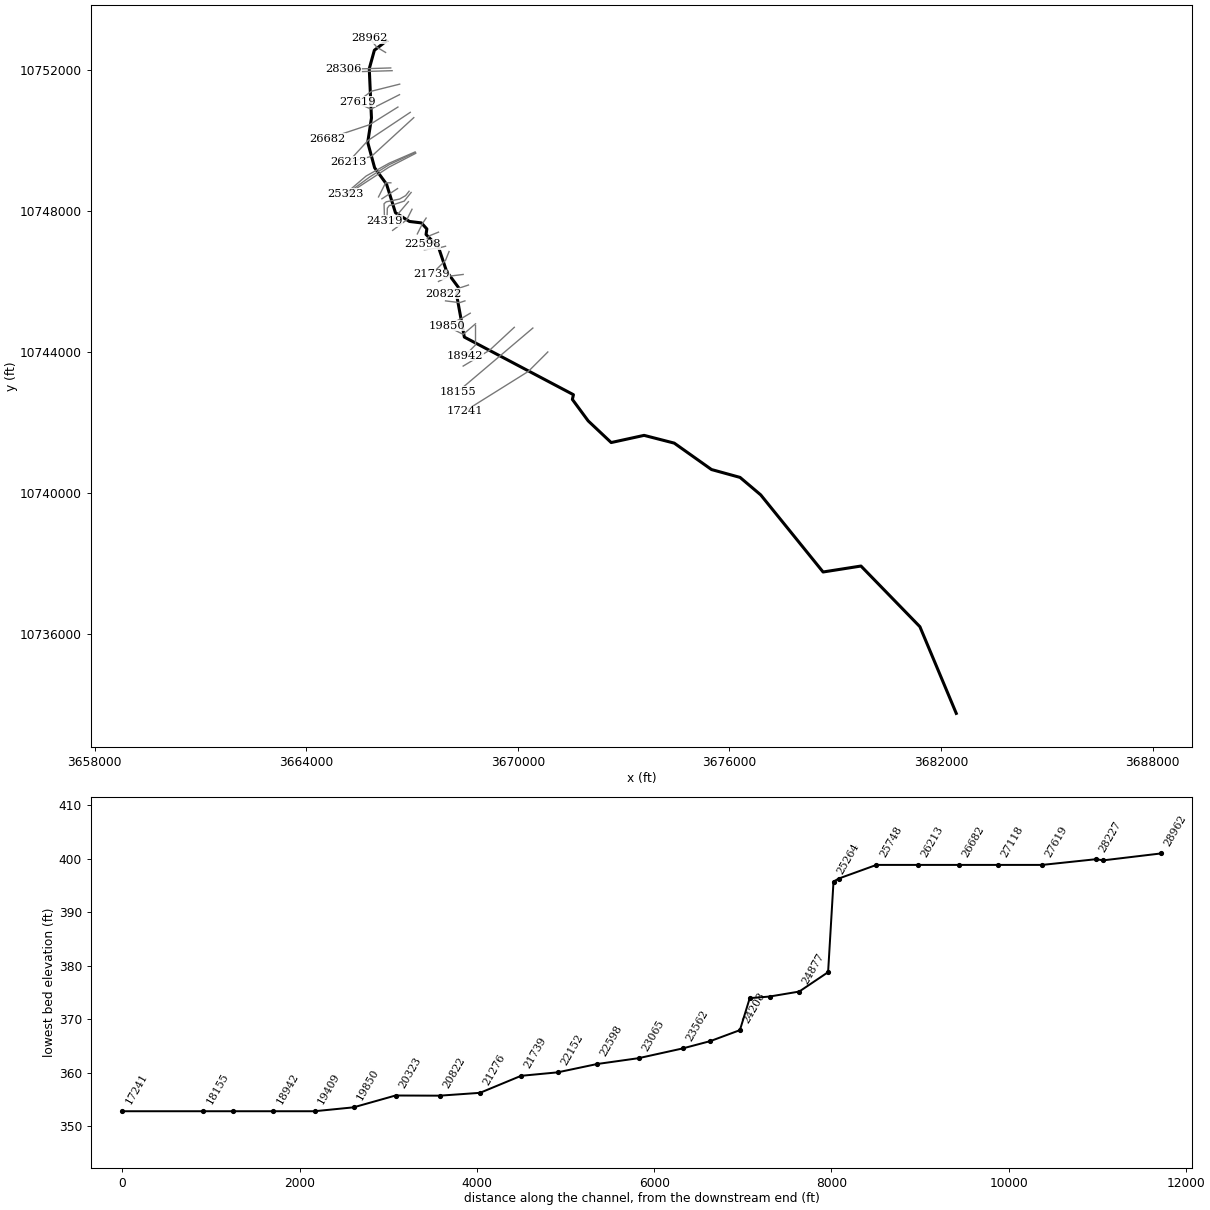
--- ANDING BRANCH.prj (project) ---

Proj Title=ANDING BRANCH Base Level Engineering
Current Plan=p01
Default Exp/Contr=0.3,0.1
English Units
Geom File=g01
Flow File=f01
Plan File=p01
Y Axis Title=Elevation
X Axis Title(PF)=Main Channel Distance
X Axis Title(XS)=Station
BEGIN DESCRIPTION:
ANDING BRANCH
END DESCRIPTION:
DSS Export Rating Curves= 0
DSS Export Rating Curve Sorted= 0
DSS Export Volume Flow Curves= 0
DXF OffsetX= 0
DXF OffsetY= 0
DXF ScaleX= 1
DXF ScaleY= 10

--- ANDING BRANCH.p01 (plan) ---

Plan Title=Multiple Run
Short Identifier=Multiple
Geom File=g01
Flow File=f01
Subcritical Flow
K Sum by GR= 0
Std Step Tol= 0.01
Critical Tol= 0.01
Num of Std Step Trials= 20
Max Error Tol= 0.3
Flow Tol Ratio= 0.001
Split Flow NTrial= 30
Split Flow Tol= 0.02
Split Flow Ratio= 0.02
Log Output Level= 0
Friction Slope Method= 1
Unsteady Friction Slope Method= 2
Unsteady Bridges Friction Slope Method= 1
Parabolic Critical Depth
Global Vel Dist=  1 , 1 , 1
Global Log Level= 0
CheckData=True
Encroach Param= -1, 0, 0, 0
BEGIN DESCRIPTION:
Multiple Run
END DESCRIPTION:

--- ANDING BRANCH.f01 (steady flow) ---

Flow Title=Multiple
Program Version=4.10
Number of Profiles= 7
Profile Names=10-year,25-year,50-year,1pct_min,100-year,1pct_plu,500-year
River Rch & RM=ANDING BRANCH,Reach-1         ,28962
     752    1039    1279    1156    1563    2113    2338
River Rch & RM=ANDING BRANCH,Reach-1         ,28306
    1015    1419    1762    1602    2167    2930    3286
River Rch & RM=ANDING BRANCH,Reach-1         ,26682
    1272    1803    2259    2073    2804    3792    4330
River Rch & RM=ANDING BRANCH,Reach-1         ,25323
    1272    1803    2259    2073    2804    3792    4330
River Rch & RM=ANDING BRANCH,Reach-1         ,24208
    1379    1955    2448    2244    3034    4104    4676
River Rch & RM=ANDING BRANCH,Reach-1         ,18942
    1623    2318    2917    2685    3631    4911    5644
River Rch & RM=ANDING BRANCH,Reach-1         ,18494
    2231    3230    4103    3809    5151    6966    8143
River Rch & RM=ANDING BRANCH,Reach-1         ,18155
    2231    3230    4103    3809    5151    6966    8143
River Rch & RM=ANDING BRANCH,Reach-1         ,14595
    2320    3358    4264    3955    5349    7234    8447
River Rch & RM=ANDING BRANCH,Reach-1         ,11964
    2424    3505    4447    4121    5573    7537    8782
River Rch & RM=ANDING BRANCH,Reach-1         ,8853
    2587    3744    4755    4407    5960    8061    9399
River Rch & RM=ANDING BRANCH,Reach-1         ,7041
    2683    3884    4932    4571    6181    8360    9743
River Rch & RM=ANDING BRANCH,Reach-1         ,2854
    3370    4917    6278    5847    7908   10694   12586
River Rch & RM=ANDING BRANCH,Reach-1         ,695
    3370    4917    6278    5847    7908   10694   12586
Boundary for River Rch & Prof#=ANDING BRANCH,Reach-1         , 1
Up Type= 0
Dn Type= 3
Dn Slope=0.00294
Boundary for River Rch & Prof#=ANDING BRANCH,Reach-1         , 2
Up Type= 0
Dn Type= 3
Dn Slope=0.00294
Boundary for River Rch & Prof#=ANDING BRANCH,Reach-1         , 3
Up Type= 0
Dn Type= 3
Dn Slope=0.00294
Boundary for River Rch & Prof#=ANDING BRANCH,Reach-1         , 4
Up Type= 0
Dn Type= 3
Dn Slope=0.00294
Boundary for River Rch & Prof#=ANDING BRANCH,Reach-1         , 5
Up Type= 0
Dn Type= 3
Dn Slope=0.00294
Boundary for River Rch & Prof#=ANDING BRANCH,Reach-1         , 6
Up Type= 0
Dn Type= 3
Dn Slope=0.00294
Boundary for River Rch & Prof#=ANDING BRANCH,Reach-1         , 7
Up Type= 0
Dn Type= 3
Dn Slope=0.00294
DSS Import GetInterval= 0
DSS Import GetPeak= 0
DSS Import FillOption= 0

--- ANDING BRANCH.g01 (geometry) ---

Geom Title=Existing Conditions
Program Version=4.10

River Reach=ANDING BRANCH   ,Reach-1
Reach XY= 30
       3666271.5     10752834.75      3665931.75       10752572.
      3665787.25       10752048.       3665849.5       10750650.
       3665743.5       10749957.      3665938.75       10749238.
        3666278.       10748770.      3666530.25       10747960.
       3666926.5       10747714.        3667266.       10747673.
        3667420.       10747501.      3667397.25       10747344.
      3667749.25       10746985.      3667982.25       10746291.
        3668339.       10745810.      3668262.75       10745634.
      3668482.75       10744433.        3671576.       10742798.
       3671545.5       10742664.      3671993.75       10742055.
        3672646.       10741440.        3673579.       10741644.
        3674434.       10741424.      3675490.75       10740674.
      3676299.75       10740451.       3676885.5       10739955.
      3678653.75       10737767.        3679728.       10737936.
       3681398.5       10736215.      3682429.75       10733755.

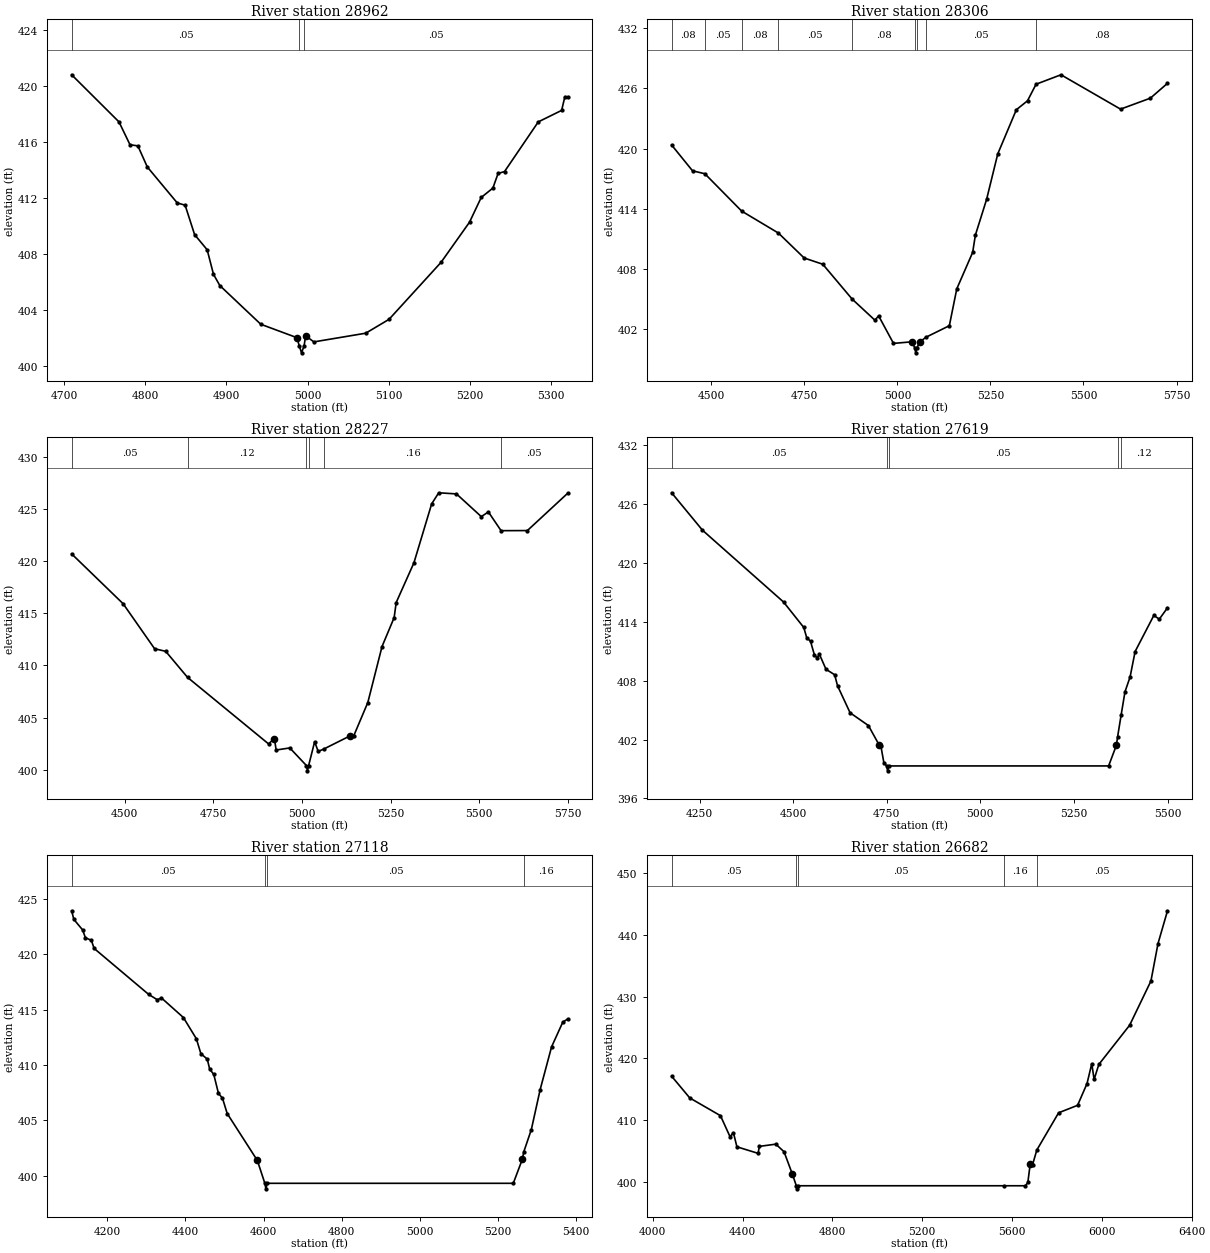
Type RM Length L Ch R = 1 ,28962   ,656,656,656
BEGIN DESCRIPTION:
ANDING BRANCH 60.0
END DESCRIPTION:
XS GIS Cut Line= 3
      3666249.65     10752510.16      3665999.61     10752660.19
      3665799.58     10752910.23
#Sta/Elev= 30
    4709  420.79  4767.4  417.43    4781   415.8  4790.7  415.72  4802.3  414.22
  4839.3  411.65    4849  411.49  4860.7  409.39  4876.2  408.31    4884  406.56
  4891.8  405.76  4942.3     403    4987  402.04  4989.8  401.46  4992.6  400.96
  4995.8  401.46  4997.7  402.18  5007.8  401.74  5071.8  402.36  5100.6  403.35
  5164.7  407.41  5199.9  410.28  5214.3  412.04  5228.7  412.71  5235.1  413.75
  5243.1  413.89  5284.7  417.43  5313.5  418.25  5317.5  419.22  5320.8  419.22
#Mann= 3 ,-1 , 0
    4709     .05       0  4989.8     .03       0  4995.8     .05       0
Bank Sta=4987,4997.7
XS Rating Curve= 0 ,0
Exp/Cntr=0.3,0.1

Type RM Length L Ch R = 1 ,28306   ,79,79,79
BEGIN DESCRIPTION:
ANDING BRANCH 59.0
END DESCRIPTION:
XS GIS Cut Line= 2
      3666395.75     10752070.39       3665063.5     10752028.76
#Sta/Elev= 30
  4392.9  420.35  4449.1  417.78  4482.2  417.49  4581.2  413.77  4680.1  411.58
  4749.2   409.1  4799.2  408.48  4877.9  405.02  4939.3  402.91  4949.3  403.34
  4989.3   400.6  5039.4  400.76  5046.4  400.16  5049.1  399.66  5052.4  400.16
  5059.4  400.71  5075.8   401.2  5139.4  402.36  5159.4  406.03  5202.1  409.66
  5209.4  411.38  5239.5  414.93  5269.5  419.46  5319.5  423.86  5349.5  424.75
  5372.5   426.4  5439.5  427.34  5599.6  423.92  5679.7  425.01  5725.8  426.49
#Mann= 9 ,-1 , 0
  4392.9     .08       0  4482.2     .05       0  4581.2     .08       0
  4680.1     .05       0  4877.9     .08       0  5046.4     .07       0
  5052.4     .08       0  5075.8     .05       0  5372.5     .08       0
Bank Sta=5039.4,5059.4
XS Rating Curve= 0 ,0
Exp/Cntr=0.3,0.1

Type RM Length L Ch R = 1 ,28227   ,608,608,608
BEGIN DESCRIPTION:
ANDING BRANCH 58.0
END DESCRIPTION:
XS GIS Cut Line= 2
      3666434.89     10751992.27      3665036.41      10751950.6
#Sta/Elev= 30
  4350.2  420.72  4495.5  415.93  4584.2  411.61  4615.6  411.36  4677.1  408.86
  4905.7  402.47  4922.2  402.98  4927.2  401.88  4965.7  402.08  5012.8  400.38
  5015.5  399.88  5018.8  400.38  5035.8  402.68  5045.8  401.74  5061.9  401.98
  5135.8  403.24  5145.8  403.22  5185.8  406.44  5225.9  411.82  5260.1   414.6
  5265.9  416.05  5315.9  419.86  5365.9  425.52  5385.9  426.59    5436  426.48
    5506   424.3    5526  424.75  5561.8  422.95    5636  422.96  5749.3  426.53
#Mann= 6 ,-1 , 0
  4350.2     .05       0  4677.1     .12       0  5012.8     .07       0
  5018.8     .12       0  5061.9     .16       0  5561.8     .05       0
Bank Sta=4922.2,5135.8
XS Rating Curve= 0 ,0
Exp/Cntr=0.3,0.1

Type RM Length L Ch R = 1 ,27619   ,501,501,501
BEGIN DESCRIPTION:
Mapping XS 20cbf83c
END DESCRIPTION:
XS GIS Cut Line= 3
      3666649.65      10751610.2      3665849.61     10751410.19
      3665449.58     10751110.17
#Sta/Elev= 30
  4175.2  427.17  4257.7  423.35  4474.2  416.03  4528.3  413.43    4536   412.4
  4546.3  412.02  4556.6  410.64  4564.4  410.31  4569.5  410.75  4587.6  409.17
  4610.7  408.61  4618.5  407.48    4652  404.73  4700.9  403.43  4729.3  401.47
  4734.4  401.31  4742.2  399.64  4749.5  399.31  4752.2  398.81  4755.5  399.31
  5342.6  399.31  5363.4  401.42  5366.7   402.3  5375.9  404.47  5386.3  406.87
  5399.9  408.38  5413.4  410.98  5463.4  414.66    5478  414.28  5499.9  415.44
#Mann= 5 ,-1 , 0
  4175.2     .05       0  4749.5    .033       0  4755.5     .05       0
  5366.7     .16       0  5375.9     .12       0
Bank Sta=4729.3,5363.4
XS Rating Curve= 0 ,0
Exp/Cntr=0.3,0.1

Type RM Length L Ch R = 1 ,27118   ,436,436,436
BEGIN DESCRIPTION:
Mapping XS ff586ceb
END DESCRIPTION:
XS GIS Cut Line= 3
      3666644.64     10751311.75      3665835.64     10750902.04
      3665505.79     10751051.33
#Sta/Elev= 30
  4108.7  423.95  4114.3  423.17  4136.8  422.22  4143.9  421.51  4159.2  421.28
  4166.1  420.55  4305.4   416.4  4327.7  415.91  4338.5  416.07  4394.6   414.3
  4427.8  412.38  4439.4  411.03  4455.7  410.54  4461.8  409.65  4472.4  409.15
  4484.3  407.45  4494.7     407  4506.7  405.62  4583.8  401.38  4603.1  399.31
  4605.8  398.81  4609.1  399.31  5238.8  399.31  5261.9  401.48  5265.7  402.16
    5285  404.17  5307.6  407.79  5336.7  411.64  5365.3  413.87  5377.6  414.16
#Mann= 4 ,-1 , 0
  4108.7     .05       0  4603.1    .033       0  4609.1     .05       0
  5265.7     .16       0
Bank Sta=4583.8,5261.9
XS Rating Curve= 0 ,0
Exp/Cntr=0.3,0.1

Type RM Length L Ch R = 1 ,26682   ,469,469,469
BEGIN DESCRIPTION:
ANDING BRANCH 55.0
END DESCRIPTION:
XS GIS Cut Line= 3
      3666599.61     10750960.19      3665799.61     10750460.19
      3664599.62     10750060.19
#Sta/Elev= 30
  4083.8  417.09  4164.6  413.56  4301.4  410.68  4343.8  407.28  4359.2  407.91
  4374.5  405.63  4468.8  404.57  4474.7   405.7  4547.8  406.06  4584.4  404.83
  4620.9  401.26  4639.2  399.31  4641.9  398.81  4645.2  399.31  5562.1  399.31
  5659.7  399.31  5670.2  399.85  5680.7  402.84  5691.3  402.74  5710.2  405.11
  5807.2  411.15  5891.6  412.36  5933.7  415.89  5954.8  419.11  5965.3  416.57
  5986.4     419  6123.5  425.36  6218.3  432.53  6249.9  438.62  6292.1  443.93
#Mann= 5 ,-1 , 0
  4083.8     .05       0  4639.2    .033       0  4645.2     .05       0
  5562.1     .16       0  5710.2     .05       0
Bank Sta=4620.9,5680.7
XS Rating Curve= 0 ,0
Exp/Cntr=0.3,0.1

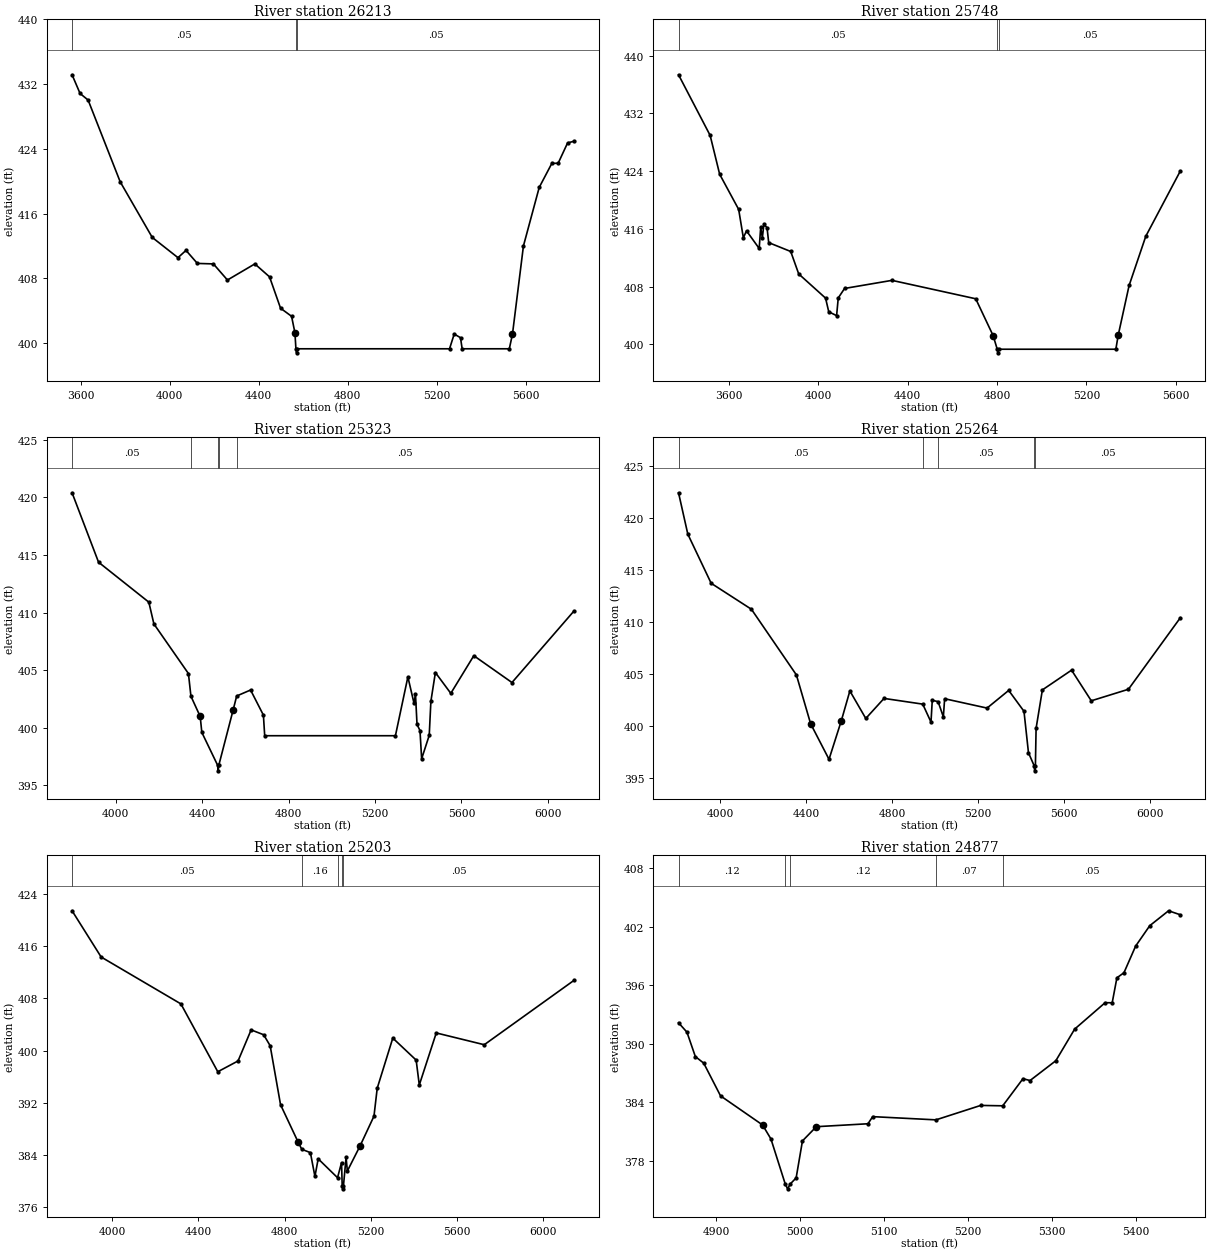
Type RM Length L Ch R = 1 ,26213   ,465,465,465
BEGIN DESCRIPTION:
ANDING BRANCH 54.0
END DESCRIPTION:
XS GIS Cut Line= 3
       3666949.6     10750810.18      3665749.61     10750010.19
      3665199.58     10749410.15
#Sta/Elev= 30
  3560.5  433.14  3596.5  430.83  3632.6  430.02  3776.8  419.93    3921  413.06
  4036.7  410.56  4072.8  411.46  4123.9  409.85    4196  409.79  4259.1   407.8
  4382.3  409.79  4448.4  408.19  4497.9  404.32  4547.5  403.32  4562.5  401.29
    4567  399.31  4569.8  398.81    4573  399.31  5257.7  399.31  5278.7  401.13
    5307  400.68  5314.4  399.31  5526.5  399.31  5540.7  401.12    5590  412.01
    5661  419.24  5717.7   422.2  5746.1  422.22  5788.6  424.73  5816.7  424.93
#Mann= 3 ,-1 , 0
  3560.5     .05       0    4567    .033       0    4573     .05       0
Bank Sta=4562.5,5540.7
XS Rating Curve= 0 ,0
Exp/Cntr=0.3,0.1

Type RM Length L Ch R = 1 ,25748   ,425,425,425
BEGIN DESCRIPTION:
ANDING BRANCH 53.0
END DESCRIPTION:
XS GIS Cut Line= 3
      3667049.61     10750660.19      3665849.61     10749560.19
      3665249.66      10749410.2
#Sta/Elev= 30
  3373.8  437.33  3515.3  428.93  3557.9  423.55    3643  418.68  3663.9  414.75
  3678.1  415.71  3734.8  413.27  3741.6  416.18    3749  414.74  3755.8  416.59
    3770  416.16  3777.4  414.08    3876  412.85  3911.8  409.74    4032  406.39
  4046.2   404.5  4081.4  403.96  4088.8  406.42  4117.1  407.73  4329.3  408.85
  4704.2   406.3  4782.5  401.17  4800.4  399.31  4803.2  398.81  4806.4  399.31
  5331.5  399.31  5341.8  401.22  5390.8  408.14  5465.5  414.96  5620.1     424
#Mann= 3 ,-1 , 0
  3373.8     .05       0  4800.4    .033       0  4806.4     .05       0
Bank Sta=4782.5,5341.8
XS Rating Curve= 0 ,0
Exp/Cntr=0.3,0.1

Type RM Length L Ch R = 1 ,25323   ,59,59,59
BEGIN DESCRIPTION:
Mapping XS 852b2ab3
END DESCRIPTION:
XS GIS Cut Line= 4
      3667083.59     10749685.56      3666346.34     10749364.97
      3665697.47     10749002.55      3665107.92     10748498.07
#Sta/Elev= 30
  3797.4  420.41    3920  414.38  4152.8  410.91  4176.2  409.02  4336.1  404.71
  4347.7  402.74  4390.6  400.98  4398.1   399.6  4470.9  396.76  4473.6  396.26
  4476.9  396.76  4543.3  401.56  4559.5  402.76  4623.8  403.28  4683.2   401.1
  4689.2  399.31  5294.4  399.31  5352.1  404.42  5380.7  402.11  5387.2  402.94
  5394.4  400.29  5408.1  399.76  5415.8  397.31  5450.9  399.34  5458.6   402.3
  5479.4   404.8  5550.8  402.99  5657.3  406.26    5834  403.93  6120.5  410.13
#Mann= 5 ,-1 , 0
  3797.4     .05       0  4347.7     .16       0  4470.9    .033       0
  4476.9     .16       0  4559.5     .05       0
Bank Sta=4390.6,4543.3
XS Rating Curve= 0 ,0
Exp/Cntr=0.3,0.1

Type RM Length L Ch R = 1 ,25264   ,61,61,61
BEGIN DESCRIPTION:
Mapping XS 1812457b
END DESCRIPTION:
XS GIS Cut Line= 4
      3667097.51     10749671.69      3666352.85      10749325.9
       3665803.8     10748978.68      3665104.54     10748466.89
#Sta/Elev= 30
  3804.9  422.45  3848.1  418.47  3956.9  413.74  4144.4  411.24  4353.9  404.92
    4420  400.23  4505.8   396.8  4563.4  400.53  4602.9  403.38  4677.1  400.73
    4762  402.66  4942.3  402.11  4980.8  400.38  4986.7  402.48  5013.9  402.35
  5038.4  400.88  5044.3  402.63  5241.9  401.73  5342.7  403.43  5413.9  401.42
  5434.8  397.43  5461.1  396.19  5463.8  395.69  5467.1  396.19  5470.3  399.78
  5499.6  403.48  5635.5  405.38  5727.4  402.43  5900.4  403.54  6142.1  410.42
#Mann= 5 ,-1 , 0
  3804.9     .05       0  4942.3     .16       0  5013.9     .05       0
  5461.1     .07       0  5467.1     .05       0
Bank Sta=4420,4563.4
XS Rating Curve= 0 ,0
Exp/Cntr=0.3,0.1

Type RM Length L Ch R = 1 ,25203   ,326,326,326
BEGIN DESCRIPTION:
ANDING BRANCH 52.0
END DESCRIPTION:
XS GIS Cut Line= 3
       3667104.5     10749647.41      3666348.51     10749256.46
      3665107.97     10748446.02
#Sta/Elev= 30
  3812.3  421.46  3947.5  414.36  4318.3  407.16  4489.8  396.74    4584   398.4
  4644.8  403.17  4703.1  402.42  4733.3  400.73  4781.5  391.68    4863  385.96
    4880  384.84  4920.3  384.32  4941.4  380.66  4956.5  383.37  5046.5  380.47
  5065.1  382.79  5068.1  379.26  5070.8  378.76  5074.1  379.26  5086.2  383.58
  5092.2   381.5  5151.8  385.39  5215.9  389.92    5231  394.21  5303.4  401.91
    5412  398.53  5426.6  394.71  5505.5   402.7  5728.7  400.89  6145.2  410.76
#Mann= 5 ,-1 , 0
  3812.3     .05       0    4880     .16       0  5046.5     .05       0
  5068.1     .07       0  5074.1     .05       0
Bank Sta=4863,5151.8
XS Rating Curve= 0 ,0
Exp/Cntr=0.3,0.1

Type RM Length L Ch R = 1 ,24877   ,335,335,335
BEGIN DESCRIPTION:
Mapping XS 70157ca1
END DESCRIPTION:
XS GIS Cut Line= 3
      3666399.65     10748810.19      3666249.61     10748810.19
      3666049.59     10748410.15
#Sta/Elev= 30
  4855.3  392.15  4865.3  391.19  4875.3  388.69  4885.3  388.01  4905.3  384.66
  4955.3  381.68  4965.3  380.24  4982.3  375.63  4985.1  375.13  4988.3  375.63
  4995.3  376.25  5002.8  380.04  5019.3   381.5  5080.8   381.8  5086.4  382.53
  5161.7   382.2    5215  383.68  5241.2  383.64  5265.3  386.42  5273.7  386.23
  5304.4  388.26  5326.8   391.5  5363.1  394.21  5371.5   394.2  5377.1  396.76
  5385.5  397.28  5399.4  400.01  5416.2   402.1  5438.6  403.63  5452.6  403.22
#Mann= 5 ,-1 , 0
  4855.3     .12       0  4982.3     .07       0  4988.3     .12       0
  5161.7     .07       0  5241.2     .05       0
Bank Sta=4955.3,5019.3
XS Rating Curve= 0 ,0
Exp/Cntr=0.3,0.1

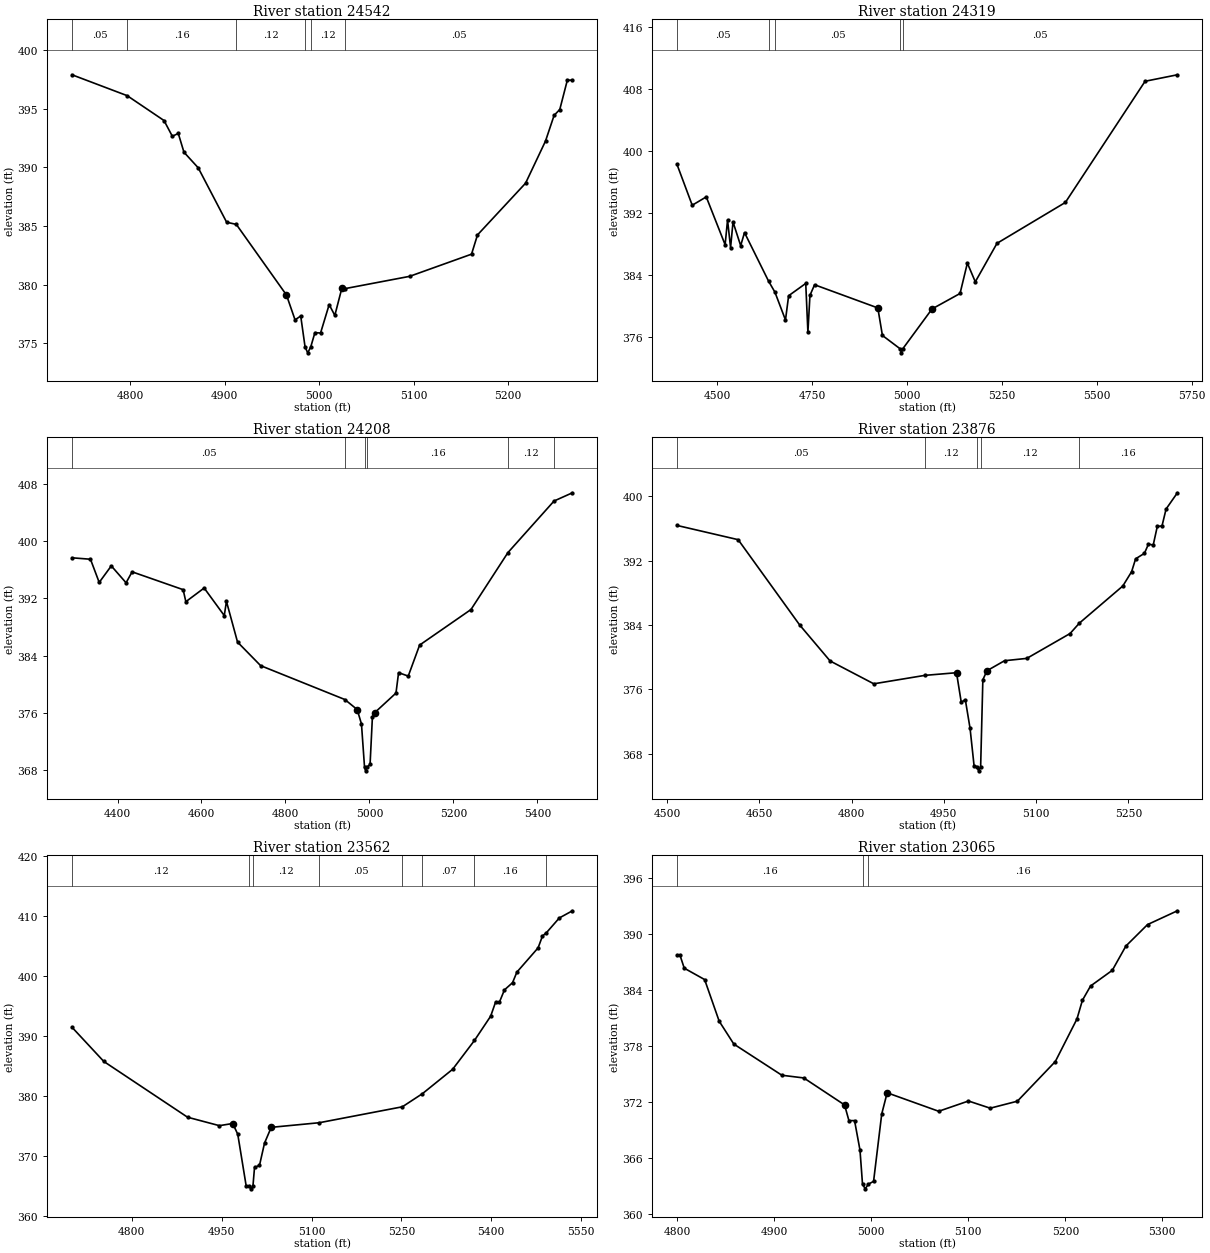
Type RM Length L Ch R = 1 ,24542   ,223,223,223
BEGIN DESCRIPTION:
Mapping XS 2253d5e9
END DESCRIPTION:
XS GIS Cut Line= 2
      3666588.34     10748647.15      3666145.61     10748356.34
#Sta/Elev= 30
  4738.3   397.9  4796.7  396.12  4835.7     394  4844.5  392.66  4850.8   392.9
  4856.8   391.3  4871.9  389.97    4902  385.33  4912.2  385.15  4965.3  379.13
  4974.4  377.01  4980.4  377.34    4985   374.7  4987.8   374.2    4991   374.7
  4995.4  375.92  5001.4  375.89  5010.5  378.31  5016.5  377.39  5023.9   379.7
  5027.7  379.68  5095.7  380.72  5161.2  382.61  5167.5  384.25  5218.4  388.66
  5239.5  392.25  5248.6  394.44  5254.6  394.94  5262.6  397.44    5268  397.44
#Mann= 6 ,-1 , 0
  4738.3     .05       0  4796.7     .16       0  4912.2     .12       0
    4985     .07       0    4991     .12       0  5027.7     .05       0
Bank Sta=4965.3,5023.9
XS Rating Curve= 0 ,0
Exp/Cntr=0.3,0.1

Type RM Length L Ch R = 1 ,24319   ,111,111,111
BEGIN DESCRIPTION:
ANDING BRANCH 50.0
END DESCRIPTION:
XS GIS Cut Line= 6
      3666916.05     10748571.21      3666818.38      10748447.5
      3666646.94     10748349.85      3666269.34     10748271.72
       3666206.4     10748217.47      3666221.59       10747725.
#Sta/Elev= 30
  4393.5  398.29  4433.7     393  4470.7  394.08  4520.4  387.89  4526.8  391.08
  4534.8  387.52  4541.2  390.83  4561.4  387.77  4571.5  389.46  4634.9  383.18
  4651.7  381.75  4679.5  378.15  4687.8  381.29  4732.9  382.88  4738.6  376.57
    4744  381.34  4756.2  382.71  4922.9  379.71    4935  376.15  4982.3   374.4
  4985.1   373.9  4988.3   374.4  5065.8  379.58  5139.6  381.58  5158.9  385.51
  5179.8  383.09    5237  388.07  5417.2  393.36  5627.3  409.04  5712.5  409.88
#Mann= 5 ,-1 , 0
  4393.5     .05       0  4634.9     .16       0  4651.7     .05       0
  4982.3     .04       0  4988.3     .05       0
Bank Sta=4922.9,5065.8
XS Rating Curve= 0 ,0
Exp/Cntr=0.3,0.1

Type RM Length L Ch R = 1 ,24208   ,332,332,332
BEGIN DESCRIPTION:
ANDING BRANCH 49.0
END DESCRIPTION:
XS GIS Cut Line= 6
      3666974.62     10748536.46      3666777.15     10748291.25
      3666484.18      10748193.6      3666356.14     10748167.55
      3666299.72      10748091.6      3666288.87     10747748.71
#Sta/Elev= 30
  4291.6  397.67  4335.6  397.47  4356.4  394.23  4385.2  396.54  4420.4  394.18
  4434.8  395.71  4556.3  393.22  4562.8  391.54  4606.4  393.45  4654.3   389.6
  4659.5  391.58  4685.9   385.9  4740.9  382.61  4941.5  377.88  4970.9  376.48
  4981.1  374.46  4988.4  368.42  4991.1  367.92  4994.4  368.42  5001.6  368.83
  5007.1  375.38  5012.2  376.02  5063.3  378.78  5069.5  381.63  5092.5  381.15
  5119.6  385.48    5242  390.45    5330   398.4  5439.8   405.6  5483.6  406.75
#Mann= 6 ,-1 , 0
  4291.6     .05       0  4941.5     .16       0  4988.4     .07       0
  4994.4     .16       0    5330     .12       0  5439.8     .07       0
Bank Sta=4970.9,5012.2
XS Rating Curve= 0 ,0
Exp/Cntr=0.3,0.1

Type RM Length L Ch R = 1 ,23876   ,314,314,314
BEGIN DESCRIPTION:
Mapping XS 4eedf76b
END DESCRIPTION:
XS GIS Cut Line= 2
       3666896.5     10748273.88      3666370.02     10747654.24
#Sta/Elev= 30
  4516.4  396.39  4615.8  394.62  4715.8  384.01  4765.2  379.54  4836.2   376.7
  4919.2  377.75  4970.6  378.08  4978.3   374.4  4984.9  374.73  4992.6  371.17
  4999.1  366.54  5003.8  366.38  5006.5  365.88  5009.8  366.38  5013.4   377.2
    5020  378.32  5048.6  379.57  5084.8  379.86  5155.1  382.95  5170.3  384.25
  5240.8  388.86  5255.1  390.64  5261.6  392.24  5275.9  392.92  5282.5  394.07
  5290.2  393.95  5296.8  396.26  5304.5  396.33  5311.1  398.43  5329.5  400.45
#Mann= 5 ,-1 , 0
  4516.4     .05       0  4919.2     .12       0  5003.8     .07       0
  5009.8     .12       0  5170.3     .16       0
Bank Sta=4970.6,5020
XS Rating Curve= 0 ,0
Exp/Cntr=0.3,0.1

Type RM Length L Ch R = 1 ,23562   ,497,497,497
BEGIN DESCRIPTION:
ANDING BRANCH 48.0
END DESCRIPTION:
XS GIS Cut Line= 3
      3666999.61     10748060.19      3666849.61     10747760.19
      3666449.61     10747460.19
#Sta/Elev= 30
  4700.1  391.48  4753.2  385.77    4893  376.46  4946.1  375.05  4968.4  375.41
  4976.8  373.62  4990.8  365.02  4996.2     365  4998.9   364.5  5002.2     365
  5004.8  368.07  5013.1  368.42  5021.5  372.14  5032.7  374.77  5112.9  375.54
  5251.6   378.2  5285.2   380.4  5335.5  384.46  5371.9  389.27    5399  393.33
  5407.4  395.74  5413.6  395.67    5422  397.72  5435.5  398.92  5442.8  400.69
  5478.2  404.74  5485.5  406.72  5492.1  407.27  5513.6  409.73  5535.5  410.93
#Mann= 8 ,-1 , 0
  4700.1     .12       0  4996.2     .07       0  5002.2     .12       0
  5112.9     .05       0  5251.6     .12       0  5285.2     .07       0
  5371.9     .16       0  5492.1     .12       0
Bank Sta=4968.4,5032.7
XS Rating Curve= 0 ,0
Exp/Cntr=0.3,0.1

Type RM Length L Ch R = 1 ,23065   ,467,467,467
BEGIN DESCRIPTION:
ANDING BRANCH 47.0
END DESCRIPTION:
XS GIS Cut Line= 3
       3667399.6     10747810.17      3667299.61     10747660.19
      3667149.59     10747360.16
#Sta/Elev= 30
  4799.8  387.74  4802.8  387.74  4807.3  386.32  4828.3   385.1  4843.3  380.64
  4858.4  378.19  4907.9  374.85  4930.5  374.56  4972.5  371.67    4977  369.99
  4982.8  369.99  4988.4  366.83    4991  363.18  4993.8  362.68    4997  363.18
  5002.4  363.48  5010.8   370.7  5016.4  372.97  5069.5  370.99  5100.2  372.09
  5122.6  371.32  5150.6  372.07  5189.7  376.32    5212  380.88  5217.6  382.88
    5226  384.41  5248.4  386.09  5262.4  388.69  5284.7  390.99  5315.5  392.47
#Mann= 3 ,-1 , 0
  4799.8     .16       0    4991     .07       0    4997     .16       0
Bank Sta=4972.5,5016.4
XS Rating Curve= 0 ,0
Exp/Cntr=0.3,0.1

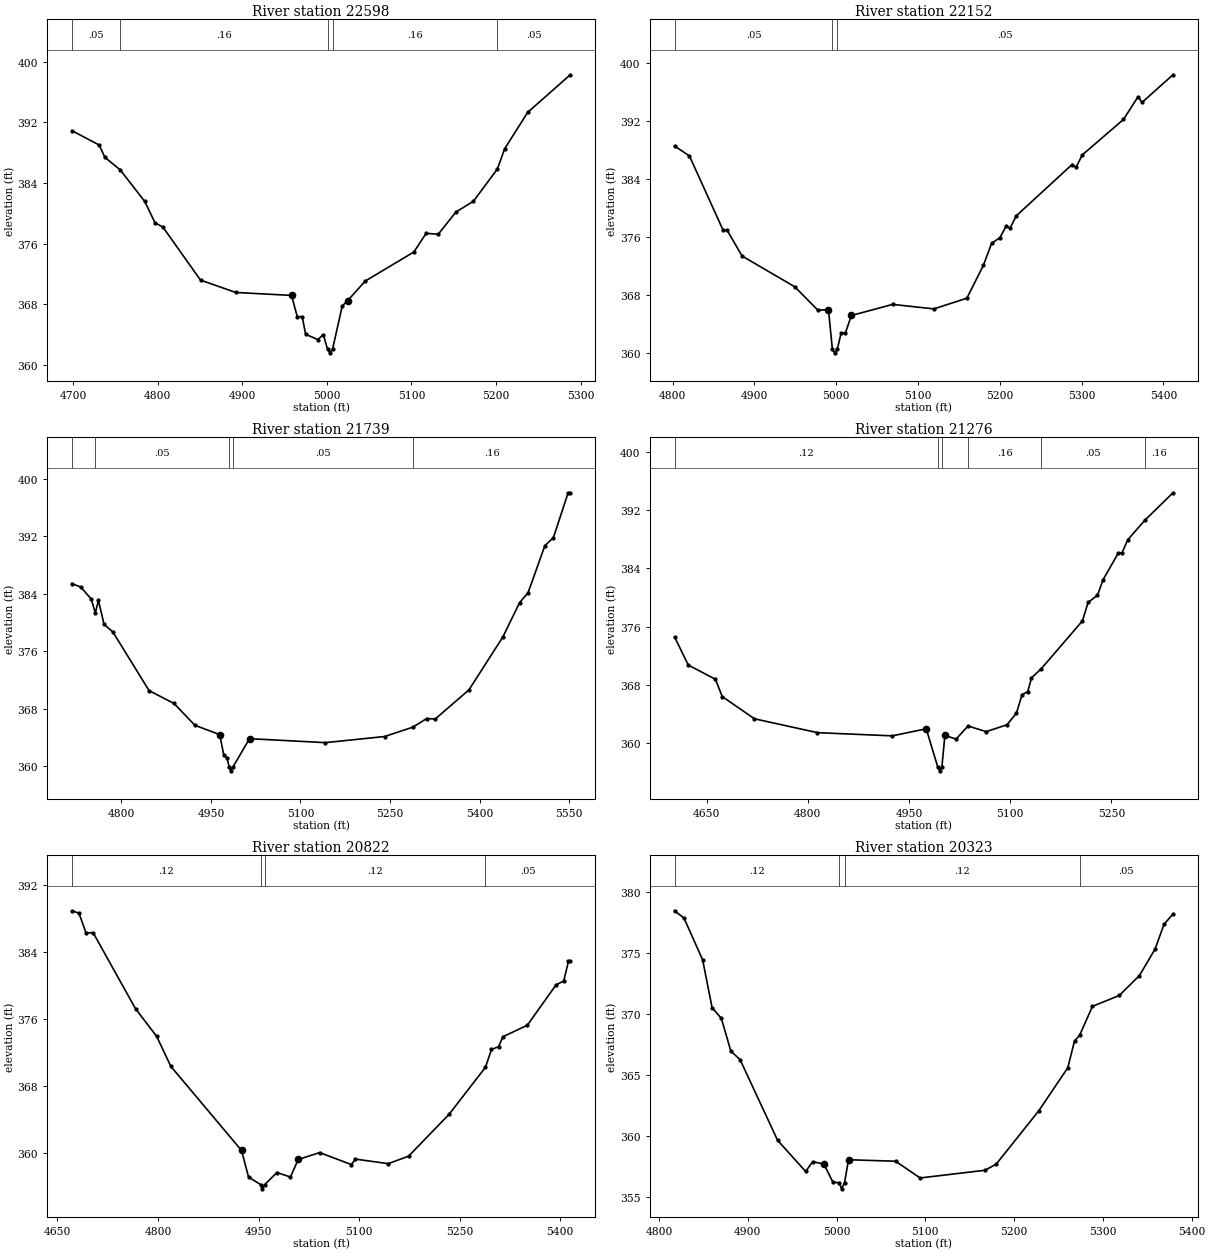
Type RM Length L Ch R = 1 ,22598   ,446,446,446
BEGIN DESCRIPTION:
ANDING BRANCH 46.0
END DESCRIPTION:
XS GIS Cut Line= 3
      3667749.59     10747410.18      3667499.61     10747310.19
      3667299.61     10747060.19
#Sta/Elev= 30
  4698.4  390.88  4730.7  388.99  4737.4  387.36  4755.4  385.73  4784.5  381.56
  4796.7  378.74  4806.1  378.16  4850.5  371.18  4892.2  369.55  4958.2  369.16
  4964.9  366.36  4970.8  366.36  4974.8  364.04  4989.3  363.34  4995.7  363.99
  5000.7  362.09  5003.4  361.59  5006.7  362.09  5018.1  367.76  5024.5  368.47
  5045.3  371.05  5102.9  374.89  5117.3  377.34  5131.7  377.23  5152.5  380.15
  5173.3  381.58  5201.6  385.83  5210.2  388.49  5237.4  393.29  5287.8  398.25
#Mann= 5 ,-1 , 0
  4698.4     .05       0  4755.4     .16       0  5000.7     .07       0
  5006.7     .16       0  5201.6     .05       0
Bank Sta=4958.2,5024.5
XS Rating Curve= 0 ,0
Exp/Cntr=0.3,0.1

Type RM Length L Ch R = 1 ,22152   ,413,413,413
BEGIN DESCRIPTION:
ANDING BRANCH 45.0
END DESCRIPTION:
XS GIS Cut Line= 3
      3667949.62     10747010.19      3667749.61     10746960.19
      3667349.59     10746910.19
#Sta/Elev= 30
  4802.4  388.54  4820.5  387.19  4861.7  376.94  4866.8   376.9  4884.9  373.38
  4949.3  369.14  4977.6  365.91  4990.5  365.99  4995.3  360.53    4998  360.03
  5001.3  360.53    5006  362.75  5011.1  362.75  5018.6  365.18    5069  366.71
  5119.4  366.09  5159.7  367.56  5179.9  372.09    5190  375.13    5200   375.9
  5207.6  377.46  5212.6  377.25  5220.2  378.93  5288.2  385.98  5293.3  385.63
  5300.8  387.32  5351.2  392.21  5368.9  395.33  5373.9  394.56  5411.7  398.37
#Mann= 3 ,-1 , 0
  4802.4     .05       0  4995.3     .03       0  5001.3     .05       0
Bank Sta=4990.5,5018.6
XS Rating Curve= 0 ,0
Exp/Cntr=0.3,0.1

Type RM Length L Ch R = 1 ,21739   ,463,463,463
BEGIN DESCRIPTION:
ANDING BRANCH 44.0
END DESCRIPTION:
XS GIS Cut Line= 3
      3668049.62     10746860.21      3667949.61     10746610.19
      3667549.58     10746210.16
#Sta/Elev= 30
    4717   385.4  4731.8  384.93  4749.3  383.27  4756.3  381.33  4761.4  383.07
  4770.9  379.74  4785.7  378.68  4846.3  370.53    4888  368.75    4923  365.72
  4964.7  364.41  4971.5  361.56  4976.9  361.18  4980.6  359.88  4983.3  359.38
  4986.6  359.88  5014.6  363.85  5141.8   363.3  5240.8  364.15    5288  365.44
  5311.5  366.65  5325.7  366.58  5382.3  370.64  5438.8  377.95  5467.1  382.76
  5481.3  384.14  5509.5  390.69  5523.7  391.78  5548.4  398.03    5552  398.03
#Mann= 5 ,-1 , 0
    4717     .16       0  4756.3     .05       0  4980.6     .03       0
  4986.6     .05       0    5288     .16       0
Bank Sta=4964.7,5014.6
XS Rating Curve= 0 ,0
Exp/Cntr=0.3,0.1

Type RM Length L Ch R = 1 ,21276   ,454,454,454
BEGIN DESCRIPTION:
ANDING BRANCH 43.0
END DESCRIPTION:
XS GIS Cut Line= 3
      3668449.64     10746210.19      3668049.61     10746160.19
      3667749.57     10746010.17
#Sta/Elev= 30
  4602.6  374.57  4622.8  370.72  4663.1  368.76  4673.2  366.39    4721  363.34
  4814.3  361.44  4925.1     361  4975.5  361.97  4992.7   356.7  4995.4   356.2
  4998.7   356.7  5003.2  361.07  5019.7  360.55  5037.5  362.35  5064.4  361.58
  5095.2  362.52  5109.2  364.11  5117.5  366.65  5125.9  367.05  5131.5  368.95
  5146.1  370.22    5207  376.77  5215.4   379.3  5229.3  380.29  5237.7  382.44
  5260.1  386.06  5265.7  386.11  5274.1  387.89  5299.2  390.55  5341.2  394.35
#Mann= 6 ,-1 , 0
  4602.6     .12       0  4992.7     .07       0  4998.7     .12       0
  5037.5     .16       0  5146.1     .05       0  5299.2     .16       0
Bank Sta=4975.5,5003.2
XS Rating Curve= 0 ,0
Exp/Cntr=0.3,0.1

Type RM Length L Ch R = 1 ,20822   ,499,499,499
BEGIN DESCRIPTION:
ANDING BRANCH 42.0
END DESCRIPTION:
XS GIS Cut Line= 3
       3668599.6     10745910.18      3668299.61     10745810.19
      3667899.62     10745660.19
#Sta/Elev= 30
  4671.6  388.89  4682.1  388.61  4692.7  386.23  4703.2  386.28  4766.5  377.19
  4798.1  373.88  4819.2   370.3  4924.6  360.26  4935.1  357.08  4953.2  356.17
  4955.9  355.67  4959.2  356.17  4977.3  357.62  4997.6  357.08  5009.2  359.18
  5041.2     360  5088.4  358.57  5094.6  359.22  5143.6  358.68  5173.8  359.57
  5234.3  364.58  5288.5  370.19  5297.5  372.32  5308.2  372.66  5314.4  373.84
  5350.9  375.21  5393.7  380.03  5405.2   380.5  5412.3  382.84    5415  382.84
#Mann= 4 ,-1 , 0
  4671.6     .12       0  4953.2     .07       0  4959.2     .12       0
  5288.5     .05       0
Bank Sta=4924.6,5009.2
XS Rating Curve= 0 ,0
Exp/Cntr=0.3,0.1

Type RM Length L Ch R = 1 ,20323   ,473,473,473
BEGIN DESCRIPTION:
Mapping XS 9d0d9dad
END DESCRIPTION:
XS GIS Cut Line= 3
      3668499.63      10745460.2      3668349.61     10745410.19
      3667949.56     10745460.19
#Sta/Elev= 30
  4817.6  378.45  4828.2  377.85  4849.2  374.43  4859.8  370.53  4870.3  369.64
  4880.9  366.98  4891.4  366.26  4933.6  359.67  4965.2  357.12  4973.1  357.92
  4985.8  357.73  4995.9  356.24    5003   356.2  5005.7   355.7    5009   356.2
  5013.5  358.08  5066.4  357.96  5094.2  356.59  5167.2  357.22  5179.8  357.72
  5227.7  362.08  5260.4   365.6    5268   367.8  5273.8  368.27  5288.2  370.63
  5318.4  371.52  5341.1  373.15  5358.7  375.31  5368.8  377.34  5378.9  378.19
#Mann= 4 ,-1 , 0
  4817.6     .12       0    5003     .07       0    5009     .12       0
  5273.8     .05       0
Bank Sta=4985.8,5013.5
XS Rating Curve= 0 ,0
Exp/Cntr=0.3,0.1

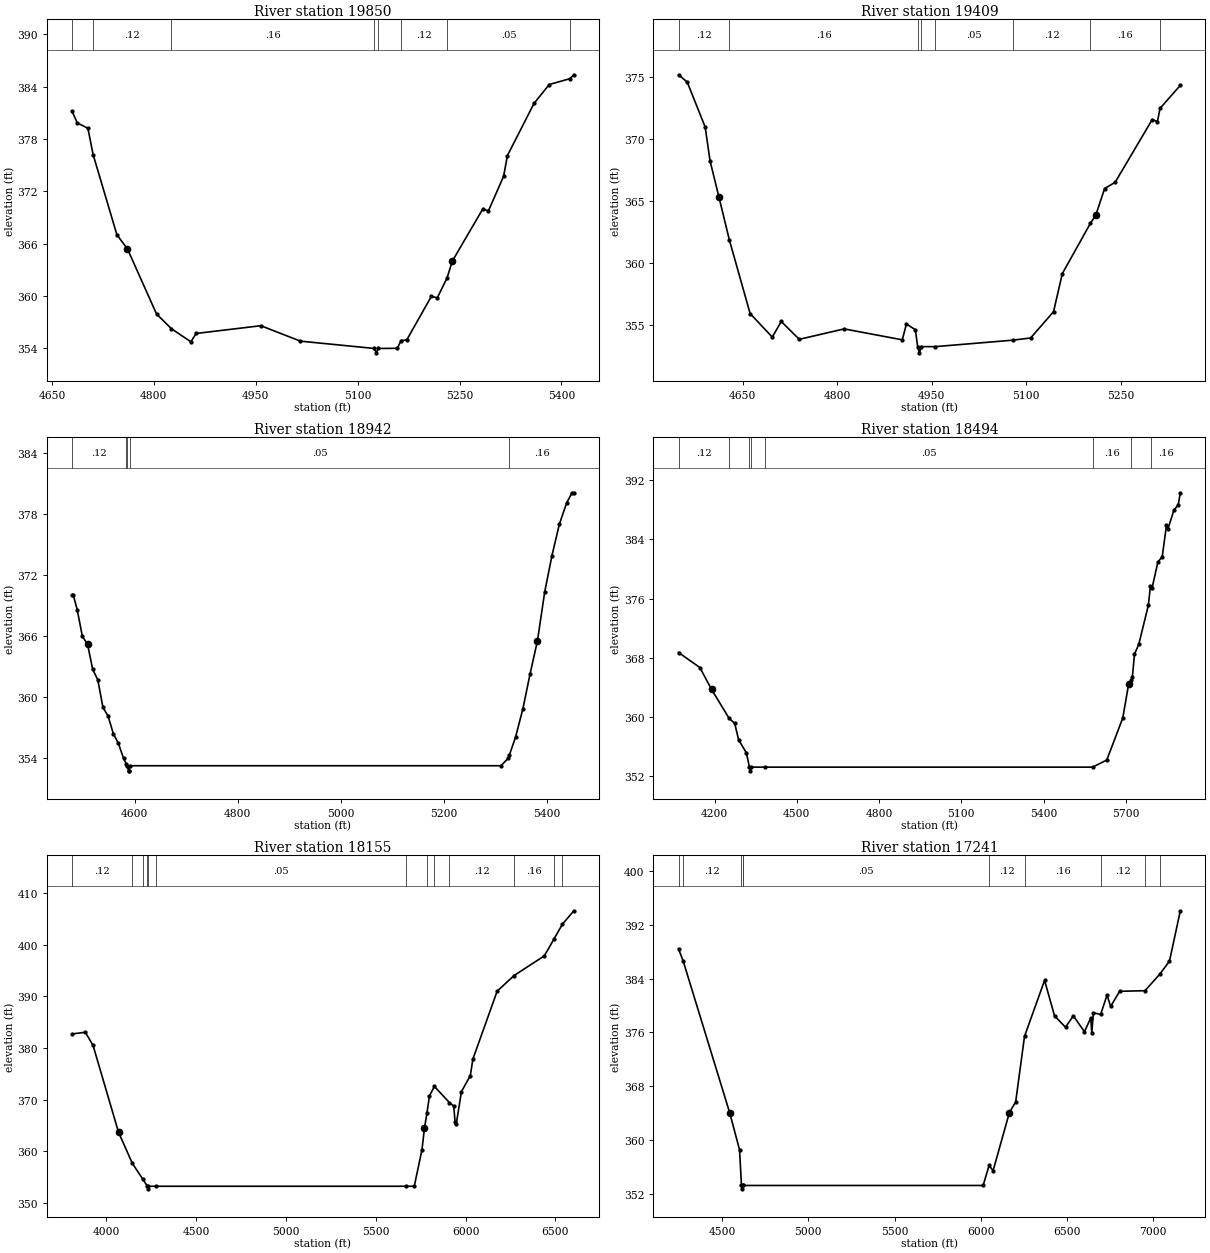
Type RM Length L Ch R = 1 ,19850   ,441,441,441
BEGIN DESCRIPTION:
ANDING BRANCH 40.0
END DESCRIPTION:
XS GIS Cut Line= 3
      3668649.57     10745110.17      3668399.61     10744960.19
      3667999.62      10744760.2
#Sta/Elev= 30
  4679.6  381.18  4687.3  379.84  4702.9  379.23  4710.6  376.21  4745.6  367.02
  4761.2  365.39  4803.9  357.95  4825.9  356.25  4854.5  354.76  4862.3  355.71
  4957.5   356.6  5015.8  354.83  5124.6  353.99  5127.4  353.49  5130.6  353.99
  5158.4  354.01  5163.9  354.89  5172.3  354.97  5208.7  359.99  5217.1  359.77
  5231.7  362.09  5239.4  364.01  5284.2  369.98  5292.5  369.76  5314.9  373.73
  5320.5   376.1  5359.6  382.07    5382  384.24  5412.4  384.91  5418.3  385.36
#Mann= 8 ,-1 , 0
  4679.6     .16       0  4710.6     .12       0  4825.9     .16       0
  5124.6     .07       0  5130.6     .16       0  5163.9     .12       0
  5231.7     .05       0  5412.4     .16       0
Bank Sta=4761.2,5239.4
XS Rating Curve= 0 ,0
Exp/Cntr=0.3,0.1

Type RM Length L Ch R = 1 ,19409   ,467,467,467
BEGIN DESCRIPTION:
Mapping XS 73e62138
END DESCRIPTION:
XS GIS Cut Line= 3
      3668799.63     10744810.21      3668449.61     10744510.19
      3668149.63     10744660.18
#Sta/Elev= 30
  4548.4  375.19  4562.2   374.6  4590.7  370.97  4598.4  368.25  4612.6  365.31
    4629  361.88    4662  355.93  4697.2  354.03  4711.4  355.29    4740  353.85
  4811.3  354.69  4903.5  353.81  4910.1  355.09  4924.3  354.62  4927.9  353.26
  4930.7  352.76  4933.9  353.26  4955.7  353.26  5078.6  353.78  5107.2  353.96
  5143.6  356.08  5157.5  359.15  5202.1  363.21  5210.7  363.88  5224.6  366.01
  5241.4  366.52  5300.1  371.57  5308.5  371.42  5312.6  372.48  5344.8  374.34
#Mann= 8 ,-1 , 0
  4548.4     .12       0    4629     .16       0  4927.9    .033       0
  4933.9     .16       0  4955.7     .05       0  5078.6     .12       0
  5202.1     .16       0  5312.6     .05       0
Bank Sta=4612.6,5210.7
XS Rating Curve= 0 ,0
Exp/Cntr=0.3,0.1

Type RM Length L Ch R = 1 ,18942   ,448,448,448
BEGIN DESCRIPTION:
Mapping XS 17ef570e
END DESCRIPTION:
XS GIS Cut Line= 3
      3668799.61     10744760.19      3668799.61     10744210.19
      3668499.58     10743910.16
#Sta/Elev= 30
  4478.7  369.99  4481.2  369.99  4488.7  368.57  4498.7  365.96  4508.7  365.19
  4518.7  362.73  4528.7  361.68  4538.7  358.98  4548.7  358.13  4558.7  356.42
  4568.7  355.45  4578.7  353.98  4583.7  353.47  4585.7  353.26  4588.4  352.76
  4588.9  352.76  4591.7  353.26  5311.5  353.26  5325.7     354  5327.6  354.28
  5339.8  356.07    5354  358.84  5368.1   362.3  5382.3  365.52  5396.4  370.32
  5410.5  373.89  5424.7  376.94  5438.8  379.03  5449.4  380.05    5453  380.05
#Mann= 5 ,-1 , 0
  4478.7     .12       0  4583.7     .05       0  4585.7    .033       0
  4591.7     .05       0  5327.6     .16       0
Bank Sta=4508.7,5382.3
XS Rating Curve= 0 ,0
Exp/Cntr=0.3,0.1

Type RM Length L Ch R = 1 ,18494   ,339,339,339
BEGIN DESCRIPTION:
ANDING BRANCH 37.0
END DESCRIPTION:
XS GIS Cut Line= 3
       3669899.6     10744710.18      3669199.61     10744060.19
      3668449.59     10743610.18
#Sta/Elev= 30
  4068.7  368.73  4146.6   366.7  4189.1  363.75  4252.9  359.86  4273.6  359.16
  4287.8  356.95  4316.2  355.18  4327.3  353.26  4330.1  352.76  4333.3  353.26
  4383.3  353.26  5578.7  353.26  5630.4  354.22  5688.7  359.89    5710  364.43
    5720  364.99  5723.6  365.36  5731.4  368.51    5747  369.83    5782   375.1
  5789.7  377.74  5791.8  377.63  5795.6  377.44  5816.9  380.97  5832.5  381.63
    5848  385.89  5853.9  385.46  5875.3  387.96  5890.8  388.64  5898.6  390.29
#Mann= 8 ,-1 , 0
  4068.7     .12       0  4252.9     .16       0  4327.3    .033       0
  4333.3     .16       0  4383.3     .05       0  5578.7     .16       0
    5720     .12       0  5791.8     .16       0
Bank Sta=4189.1,5710
XS Rating Curve= 0 ,0
Exp/Cntr=0.3,0.1

Type RM Length L Ch R = 1 ,18155   ,914,914,914
BEGIN DESCRIPTION:
Mapping XS d7eda9ae
END DESCRIPTION:
XS GIS Cut Line= 2
      3670425.57     10744689.19      3668295.35     10742881.89
#Sta/Elev= 30
  3808.7  382.71  3882.7  383.03  3925.5  380.49  4067.2  363.72  4144.2  357.69
  4200.9  354.72  4227.9  353.26  4230.7  352.76  4233.9  353.26    4276  353.26
    5667  353.26  5713.8  353.26  5756.7  360.32  5770.5  364.47  5784.1  367.34
  5798.4  370.72  5825.8  372.57  5909.8  369.42  5933.5  368.77    5941  365.68
  5947.8  365.34  5976.4  371.56  6025.8  374.64  6040.1  377.84  6175.2  390.97
  6269.6     394  6437.7   397.8  6490.8     401  6538.1   403.9  6602.3  406.52
#Mann= 13 ,-1 , 0
  3808.7     .12       0  4144.2     .16       0  4200.9     .12       0
  4227.9    .033       0  4233.9     .12       0    4276     .05       0
    5667     .16       0  5784.1     .12       0  5825.8     .16       0
  5909.8     .12       0  6269.6     .16       0  6490.8     .05       0
  6538.1     .12       0
Bank Sta=4067.2,5770.5
XS Rating Curve= 0 ,0
Exp/Cntr=0.3,0.1

Type RM Length L Ch R = 1 ,17241   ,438,438,438
BEGIN DESCRIPTION:
ANDING BRANCH 34.0
END DESCRIPTION:
XS GIS Cut Line= 3
      3670849.58     10744010.16      3670299.61     10743460.19
      3668493.91     10742330.21
#Sta/Elev= 30
  4248.3  388.39  4275.3  386.59  4545.2  364.02  4601.8  358.56    4613  353.26
  4615.7  352.76    4619  353.26  4624.4  353.26  6013.4  353.26    6048  356.23
  6071.2  355.46  6165.5  364.07  6202.1  365.68  6253.3  375.41  6369.5  383.72
  6427.2  378.46  6490.9  376.76  6536.1  378.46  6600.5   376.1  6637.1  378.14
    6643   375.9  6652.4  378.91  6694.5  378.66  6731.4  381.54  6752.6  379.86
  6804.5   382.1  6951.5  382.19  7038.6  384.69  7093.3  386.58  7156.2  394.06
#Mann= 10 ,-1 , 0
  4248.3     .16       0  4275.3     .12       0    4613    .033       0
    4619     .12       0  4624.4     .05       0    6048     .12       0
  6253.3     .16       0  6694.5     .12       0  6951.5     .16       0
  7038.6      .1       0
Bank Sta=4545.2,6165.5
XS Rating Curve= 0 ,0
Exp/Cntr=0.3,0.1