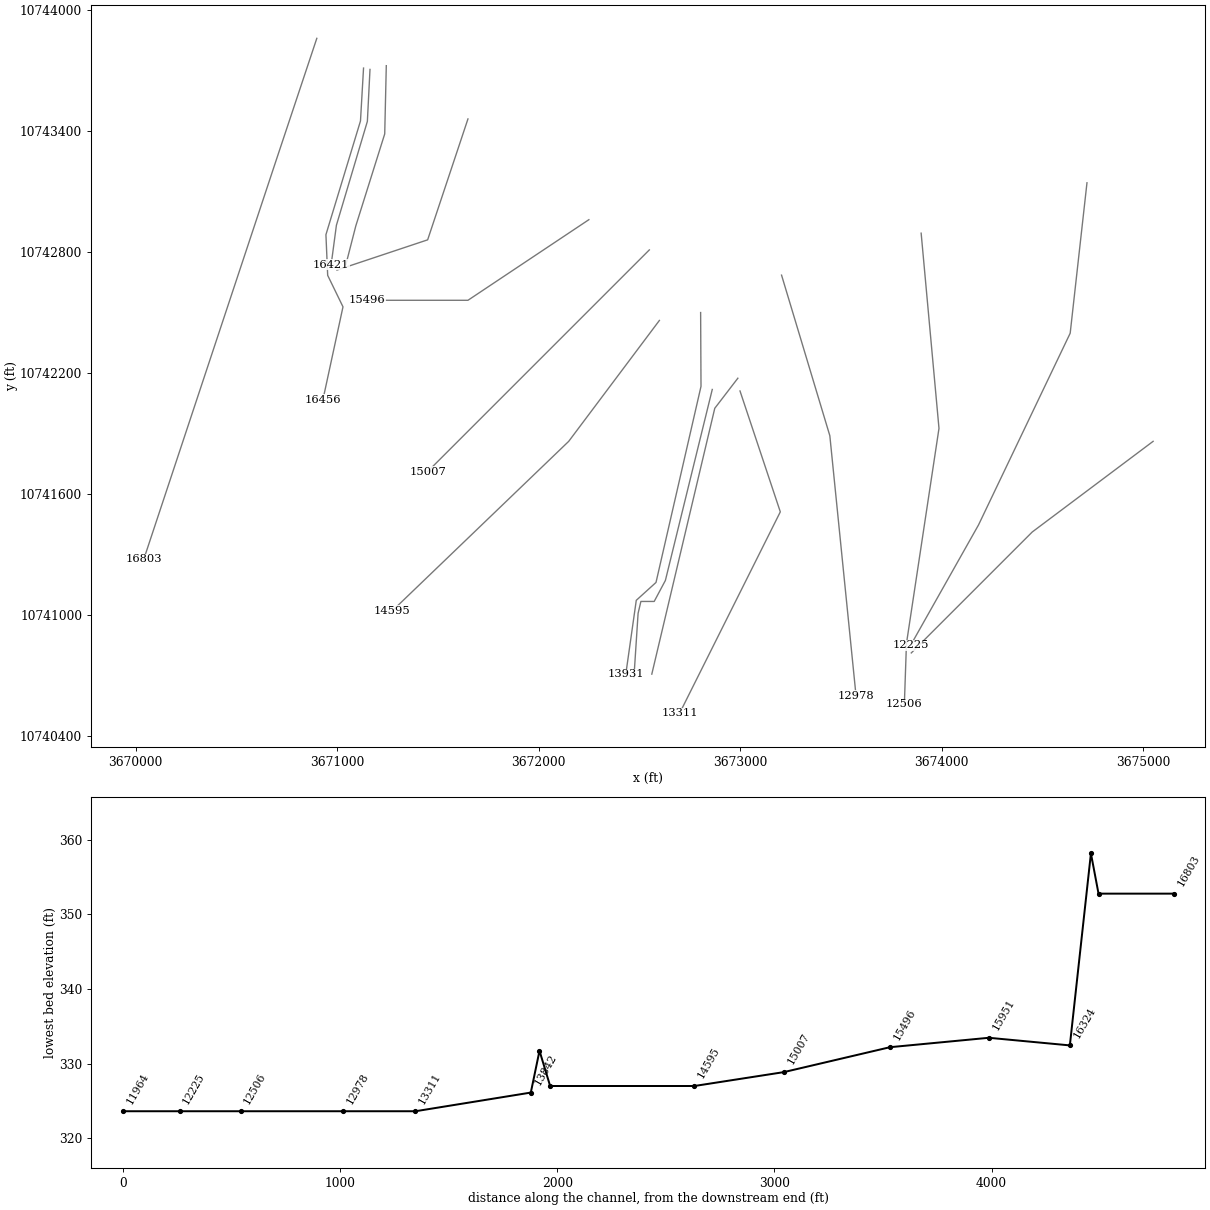
HEC-RAS study ANDING BRANCH.prj: ANDING BRANCH Base Level Engineering

--- ANDING BRANCH.g01 (geometry) --- (continued)

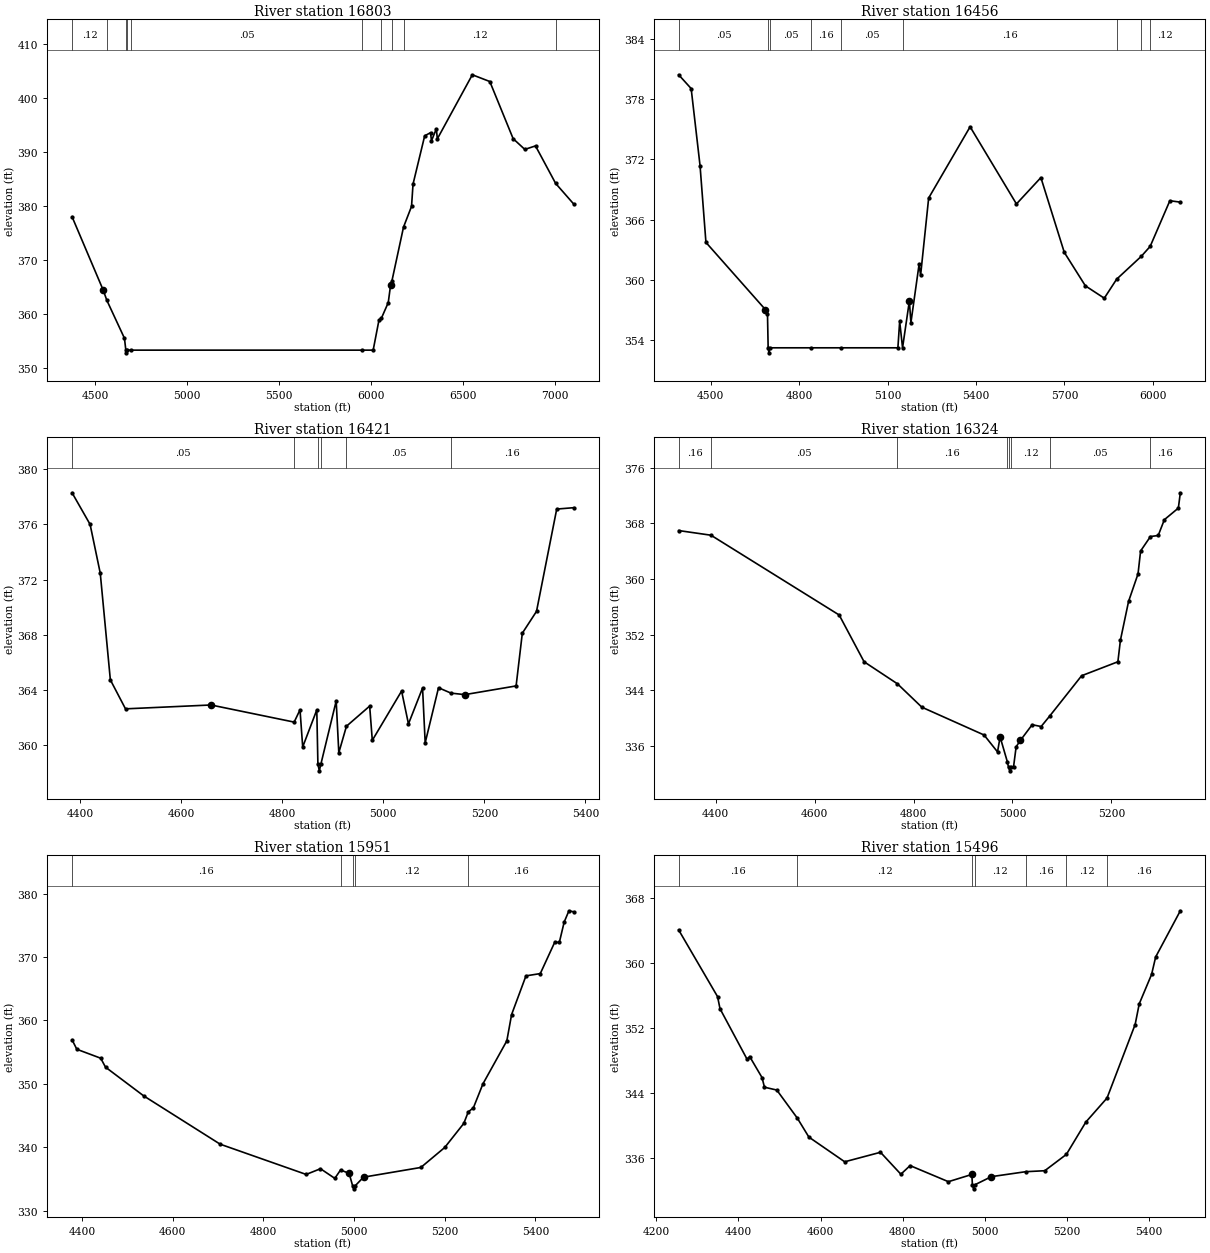
Type RM Length L Ch R = 1 ,16803   ,347,347,347
BEGIN DESCRIPTION:
ANDING BRANCH 33.0
END DESCRIPTION:
XS GIS Cut Line= 3
       3670899.6     10743860.15      3670699.61     10743260.19
      3670040.58     10741273.88
#Sta/Elev= 30
  4375.5  377.96  4544.1  364.42  4564.5  362.48  4660.1  355.46  4667.6  353.26
  4670.4  352.76  4673.6  353.26  4697.4  353.26  5951.3  353.26  6011.2  353.26
  6042.8  358.85  6055.9  359.17  6093.1  362.06  6106.2  365.41  6112.9  366.05
    6176  376.04  6219.6  379.88  6227.7     384    6291  392.94  6322.7  393.53
    6328  392.03  6354.4  394.25  6359.7  392.38  6549.8  404.25  6644.8     403
  6771.5  392.42  6834.9  390.43    6893  391.08  7002.5  384.13  7100.7  380.31
#Mann= 10 ,-1 , 0
  4375.5     .12       0  4564.5     .16       0  4667.6    .033       0
  4673.6     .16       0  4697.4     .05       0  5951.3     .16       0
  6055.9     .12       0  6112.9     .16       0    6176     .12       0
  7002.5     .16       0
Bank Sta=4544.1,6106.2
XS Rating Curve= 0 ,0
Exp/Cntr=0.3,0.1

Type RM Length L Ch R = 1 ,16456   ,35,35,35
BEGIN DESCRIPTION:
Mapping XS c4b8192c
END DESCRIPTION:
XS GIS Cut Line= 6
      3671131.46     10743712.54      3671116.27     10743449.99
      3670944.83     10742885.76      3670953.51     10742683.94
      3671029.47     10742527.69      3670929.65     10742065.47
#Sta/Elev= 30
  4391.6   380.4    4434  379.03  4464.1  371.38  4484.1  363.74  4685.7  357.06
  4692.8  356.67  4695.1  353.26  4697.8  352.76  4701.1  353.26  4839.9  353.26
  4943.6  353.26  5135.1  353.26  5141.1  355.89  5150.9  353.26    5174  357.92
  5179.2  355.75  5206.9  361.55  5212.1  360.47  5239.4  368.15    5380  375.23
  5537.1  367.56    5620  370.18  5699.3  362.75  5770.9  359.42    5835  358.19
  5876.9  360.08  5960.7  362.36  5990.6  363.34  6057.4  367.88  6092.9  367.74
#Mann= 9 ,-1 , 0
  4391.6     .05       0  4695.1     .03       0  4701.1     .05       0
  4839.9     .16       0  4943.6     .05       0  5150.9     .16       0
  5876.9     .12       0  5960.7     .16       0  5990.6     .12       0
Bank Sta=4685.7,5174
XS Rating Curve= 0 ,0
Exp/Cntr=0.3,0.1

Type RM Length L Ch R = 1 ,16421   ,97,97,97
BEGIN DESCRIPTION:
Mapping XS b4bd9f5e
END DESCRIPTION:
XS GIS Cut Line= 4
      3671163.48     10743705.87      3671150.46     10743448.02
      3670996.81      10742932.4      3670970.77     10742737.13
#Sta/Elev= 30
  4383.8  378.29  4419.5     376  4439.6  372.47  4459.6  364.74  4489.6  362.64
  4658.9  362.92  4823.5  361.68  4835.1  362.57  4840.4  359.88  4868.3  362.56
  4870.5  358.65  4873.3  358.15  4876.5  358.65  4906.7  363.21  4911.9  359.46
    4927  361.38    4973  362.84  4978.2  360.36  5036.2  363.93  5049.8  361.55
  5077.7  364.15  5082.9  360.18  5109.3  364.17  5133.9  363.78  5161.4  363.67
  5262.9   364.3  5275.2  368.12  5303.3   369.7  5343.3  377.11    5377  377.21
#Mann= 6 ,-1 , 0
  4383.8     .05       0  4823.5     .16       0  4870.5     .03       0
  4876.5     .16       0    4927     .05       0  5133.9     .16       0
Bank Sta=4658.9,5161.4
XS Rating Curve= 0 ,0
Exp/Cntr=0.3,0.1

Type RM Length L Ch R = 1 ,16324   ,373,373,373
BEGIN DESCRIPTION:
Mapping XS 6b5bc0ad
END DESCRIPTION:
XS GIS Cut Line= 4
      3671244.38     10743724.45      3671236.57     10743385.87
      3671093.34     10742930.14      3671044.24     10742738.92
#Sta/Elev= 30
  4325.4  366.97  4390.7   366.3  4649.8  354.83  4700.1  348.11  4767.5  344.94
  4816.8  341.58  4942.6  337.58  4969.8  335.15    4975   337.3  4989.5  333.76
    4992  332.93  4994.7  332.43    4998  332.93  5002.2  333.03  5007.4  335.89
  5015.9   336.8  5039.8  339.06  5057.9   338.8  5075.6  340.34  5139.7   346.1
    5213  348.11  5218.1   351.2  5234.6  356.79  5253.7  360.74  5258.9  364.03
  5278.8  366.11  5294.5  366.26  5306.9  368.53  5335.2   370.2  5339.2   372.4
#Mann= 8 ,-1 , 0
  4325.4     .16       0  4390.7     .05       0  4767.5     .16       0
  4989.5     .12       0    4992     .07       0    4998     .12       0
  5075.6     .05       0  5278.8     .16       0
Bank Sta=4975,5015.9
XS Rating Curve= 0 ,0
Exp/Cntr=0.3,0.1

Type RM Length L Ch R = 1 ,15951   ,455,455,455
BEGIN DESCRIPTION:
ANDING BRANCH 31.0
END DESCRIPTION:
XS GIS Cut Line= 3
       3671649.6     10743460.16      3671449.61     10742860.19
      3670999.58     10742710.18
#Sta/Elev= 30
  4377.7  356.94  4388.2  355.45  4440.9  354.04  4451.5  352.63  4535.8   348.1
  4704.4  340.49  4894.2  335.72  4925.8  336.62  4957.4   335.1    4970  336.42
    4989  335.89  4996.6  333.95  4999.3  333.45  5002.6  333.95  5020.7  335.29
  5147.2  336.82  5199.9  339.97    5242  343.77  5251.8  345.58  5263.1  346.22
  5284.2     350  5336.9  356.78  5347.4  360.92  5379.1  367.02  5410.7  367.38
  5442.3  372.28  5452.8  372.32  5463.4   375.5  5473.9  377.28  5484.5  377.11
#Mann= 5 ,-1 , 0
  4377.7     .16       0    4970     .12       0  4996.6     .07       0
  5002.6     .12       0  5251.8     .16       0
Bank Sta=4989,5020.7
XS Rating Curve= 0 ,0
Exp/Cntr=0.3,0.1

Type RM Length L Ch R = 1 ,15496   ,489,489,489
BEGIN DESCRIPTION:
ANDING BRANCH 30.0
END DESCRIPTION:
XS GIS Cut Line= 3
      3672249.65     10742960.21      3671649.61     10742560.19
      3671149.56     10742560.19
#Sta/Elev= 30
  4254.7  364.06  4349.4  355.85  4355.4  354.36  4421.5  348.12  4427.5  348.48
  4457.6  345.89  4463.6   344.7  4493.6  344.35  4543.6  340.89  4571.7  338.56
  4658.9  335.52    4746  336.69  4795.6  333.99  4818.1  335.05  4911.3  333.07
  4968.3  333.96  4969.8  332.69  4972.6  332.19  4975.8  332.69  5015.9  333.69
  5099.5   334.3  5145.9  334.42  5198.5  336.43  5245.9  340.41  5297.5  343.37
  5365.9  352.42  5375.9  354.97  5405.9  358.58  5415.9  360.74  5475.9  366.42
#Mann= 7 ,-1 , 0
  4254.7     .16       0  4543.6     .12       0  4969.8     .07       0
  4975.8     .12       0  5099.5     .16       0  5198.5     .12       0
  5297.5     .16       0
Bank Sta=4968.3,5015.9
XS Rating Curve= 0 ,0
Exp/Cntr=0.3,0.1

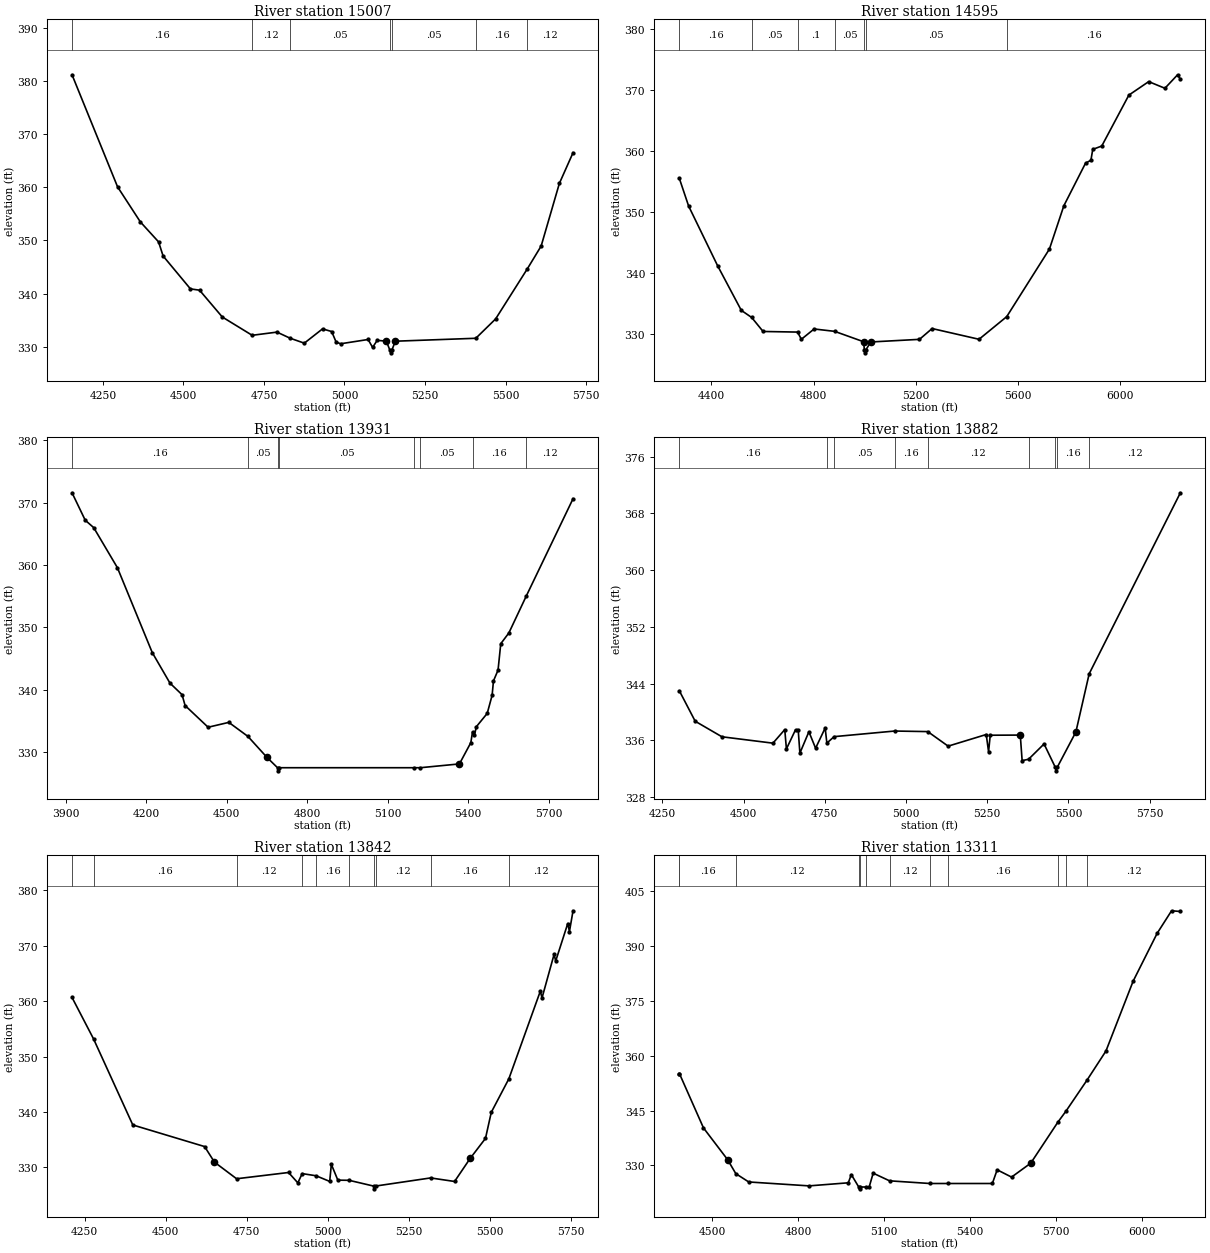
Type RM Length L Ch R = 1 ,15007   ,412,412,412
BEGIN DESCRIPTION:
ANDING BRANCH 29.0
END DESCRIPTION:
XS GIS Cut Line= 3
      3672549.58     10742810.16      3671949.61     10742210.19
       3671449.6     10741710.18
#Sta/Elev= 30
  4154.1  381.17  4295.5  360.08  4366.2  353.49  4422.8  349.73  4436.9  347.07
  4521.8  340.88    4550  340.64  4620.7  335.59  4713.4  332.15  4790.5  332.75
  4830.9  331.61  4875.3  330.67  4931.9  333.36  4960.2  332.86  4974.3  330.85
  4988.4  330.56  5073.3  331.36  5087.4  329.87  5101.6   331.2  5129.9  331.05
    5141  329.35  5143.8  328.85    5147  329.35  5158.1  331.04  5407.8  331.59
  5469.3  335.23  5567.9  344.67  5610.7  348.95  5667.3  360.74  5709.7  366.51
#Mann= 7 ,-1 , 0
  4154.1     .16       0  4713.4     .12       0  4830.9     .05       0
    5141     .03       0    5147     .05       0  5407.8     .16       0
  5567.9     .12       0
Bank Sta=5129.9,5158.1
XS Rating Curve= 0 ,0
Exp/Cntr=0.3,0.1

Type RM Length L Ch R = 1 ,14595   ,664,664,664
BEGIN DESCRIPTION:
ANDING BRANCH 28.0
END DESCRIPTION:
XS GIS Cut Line= 3
      3672599.59     10742460.16      3672149.61     10741860.19
      3671274.78     10741019.58
#Sta/Elev= 30
  4274.2  355.56  4310.6  351.03  4424.2  341.25  4516.9  333.95  4557.7  332.78
  4602.3  330.49  4737.4  330.39  4752.3  329.21  4802.3   330.9  4882.7  330.51
    4996  328.81  4999.3  327.49    5002  326.99  5005.3  327.49  5024.2  328.77
  5215.2   329.2  5264.6  330.97  5448.5  329.21    5557  332.92  5724.3  343.99
  5780.9  351.09  5865.8  358.06  5886.9  358.54  5894.1  360.32  5929.4  360.87
  6035.6  369.21  6113.3  371.42  6176.9  370.33  6226.5  372.54  6237.4   371.8
#Mann= 7 ,-1 , 0
  4274.2     .16       0  4557.7     .05       0  4737.4      .1       0
  4882.7     .05       0  4999.3    .033       0  5005.3     .05       0
    5557     .16       0
Bank Sta=4996,5024.2
XS Rating Curve= 0 ,0
Exp/Cntr=0.3,0.1

Type RM Length L Ch R = 1 ,13931   ,49,49,49
BEGIN DESCRIPTION:
ANDING BRANCH 27.0
END DESCRIPTION:
XS GIS Cut Line= 5
      3672804.21     10742499.38      3672806.08     10742132.94
      3672582.77     10741159.93      3672484.85     10741071.19
      3672432.65     10740703.27
#Sta/Elev= 30
  3922.6  371.57  3971.8  367.17  4003.5  365.98  4091.8  359.56  4221.8  345.95
  4287.9  341.05  4332.9   339.2  4344.3  337.46  4430.1  333.98  4507.3  334.76
  4578.6  332.51  4649.5  329.15    4689  327.49  4691.8  326.99    4695  327.49
  5199.2  327.49  5221.5  327.49  5367.4   328.1  5409.9  331.51  5416.2  333.24
  5423.4  332.73  5430.6  334.07    5471   336.2  5489.3   339.1  5494.3   341.4
  5511.4  343.14  5521.5  347.37  5551.8   349.1  5616.4  354.99  5791.1  370.62
#Mann= 8 ,-1 , 0
  3922.6     .16       0  4578.6     .05       0    4689    .033       0
    4695     .05       0  5199.2     .12       0  5221.5     .05       0
  5416.2     .16       0  5616.4     .12       0
Bank Sta=4649.5,5367.4
XS Rating Curve= 0 ,0
Exp/Cntr=0.3,0.1

Type RM Length L Ch R = 1 ,13882   ,40,40,40
BEGIN DESCRIPTION:
Mapping XS 257b87e3
END DESCRIPTION:
XS GIS Cut Line= 6
      3672861.95     10742117.66      3672629.32     10741169.79
      3672573.77     10741065.62      3672507.79     10741065.62
       3672493.9     10741006.59      3672473.07     10740687.13
#Sta/Elev= 30
  4302.3  342.99  4351.1   338.7  4433.4  336.51  4590.4  335.61  4626.8  337.52
  4631.9   334.8  4659.9   337.5  4668.3   337.4  4673.4  334.21  4701.1  337.22
  4721.7   334.9  4751.2  337.75  4756.4  335.62  4778.8  336.53    4965  337.32
    5067  337.24  5129.7  335.19    5247  336.83  5254.2   334.4  5259.3  336.73
  5351.8  336.75  5357.5  333.15  5377.2  333.34    5425   335.5  5459.6  332.21
  5462.4  331.71  5465.6  332.21  5522.9  337.18  5563.9  345.39  5844.6   370.9
#Mann= 9 ,-1 , 0
  4302.3     .16       0  4756.4     .12       0  4778.8     .05       0
    4965     .16       0    5067     .12       0  5377.2     .16       0
  5459.6     .07       0  5465.6     .16       0  5563.9     .12       0
Bank Sta=5351.8,5522.9
XS Rating Curve= 0 ,0
Exp/Cntr=0.3,0.1

Type RM Length L Ch R = 1 ,13842   ,531,531,531
BEGIN DESCRIPTION:
ANDING BRANCH 26.0
END DESCRIPTION:
XS GIS Cut Line= 3
      3672988.91     10742173.45      3672874.36     10742024.18
       3672561.9     10740704.94
#Sta/Elev= 30
  4211.5  360.66  4277.8  353.18  4398.8  337.64  4620.1  333.74  4650.4  330.93
  4718.6  327.93  4878.7  329.06  4907.3  327.19  4920.8  328.86  4963.5  328.47
  5005.5  327.45  5010.6  330.53  5030.6  327.68  5065.2  327.65  5140.7  326.61
  5143.4  326.11  5146.7  326.61  5316.6  328.08  5390.3  327.44  5438.2  331.59
  5485.6  335.22  5503.4  339.92  5557.5  345.96  5654.6   361.8  5659.8  360.58
  5696.9  368.42    5702  367.25  5739.1  374.01  5744.3  372.56  5755.4  376.31
#Mann= 10 ,-1 , 0
  4211.5     .12       0  4277.8     .16       0  4718.6     .12       0
  4920.8     .05       0  4963.5     .16       0  5065.2     .12       0
  5140.7     .07       0  5146.7     .12       0  5316.6     .16       0
  5557.5     .12       0
Bank Sta=4650.4,5438.2
XS Rating Curve= 0 ,0
Exp/Cntr=0.3,0.1

Type RM Length L Ch R = 1 ,13311   ,333,333,333
BEGIN DESCRIPTION:
ANDING BRANCH 25.0
END DESCRIPTION:
XS GIS Cut Line= 3
      3672999.61     10742110.17      3673199.61     10741510.19
       3672699.6     10740510.17
#Sta/Elev= 30
  4384.7  355.07  4385.2  355.07    4469  340.26  4553.3  331.59    4582  327.76
  4627.1  325.49  4837.9  324.42    4975  325.26  4985.5  327.51  5011.5  324.11
  5014.3  323.61  5017.5  324.11  5036.5  324.11  5047.9  324.11  5061.9  327.89
  5119.1   325.8  5260.1  325.07  5324.5  325.07  5478.3  325.07  5495.1  328.81
  5545.4  326.82  5612.5  330.63  5707.1  341.82  5735.3  344.82  5808.7  353.28
  5875.2  361.28  5970.3  380.39  6054.1  393.45  6104.4  399.61  6135.2  399.42
#Mann= 12 ,-1 , 0
  4384.7     .12       0  4385.2     .16       0    4582     .12       0
  5011.5     .07       0  5017.5     .12       0  5036.5     .07       0
  5119.1     .12       0  5260.1     .05       0  5324.5     .16       0
  5707.1     .12       0  5735.3     .16       0  5808.7     .12       0
Bank Sta=4553.3,5612.5
XS Rating Curve= 0 ,0
Exp/Cntr=0.3,0.1

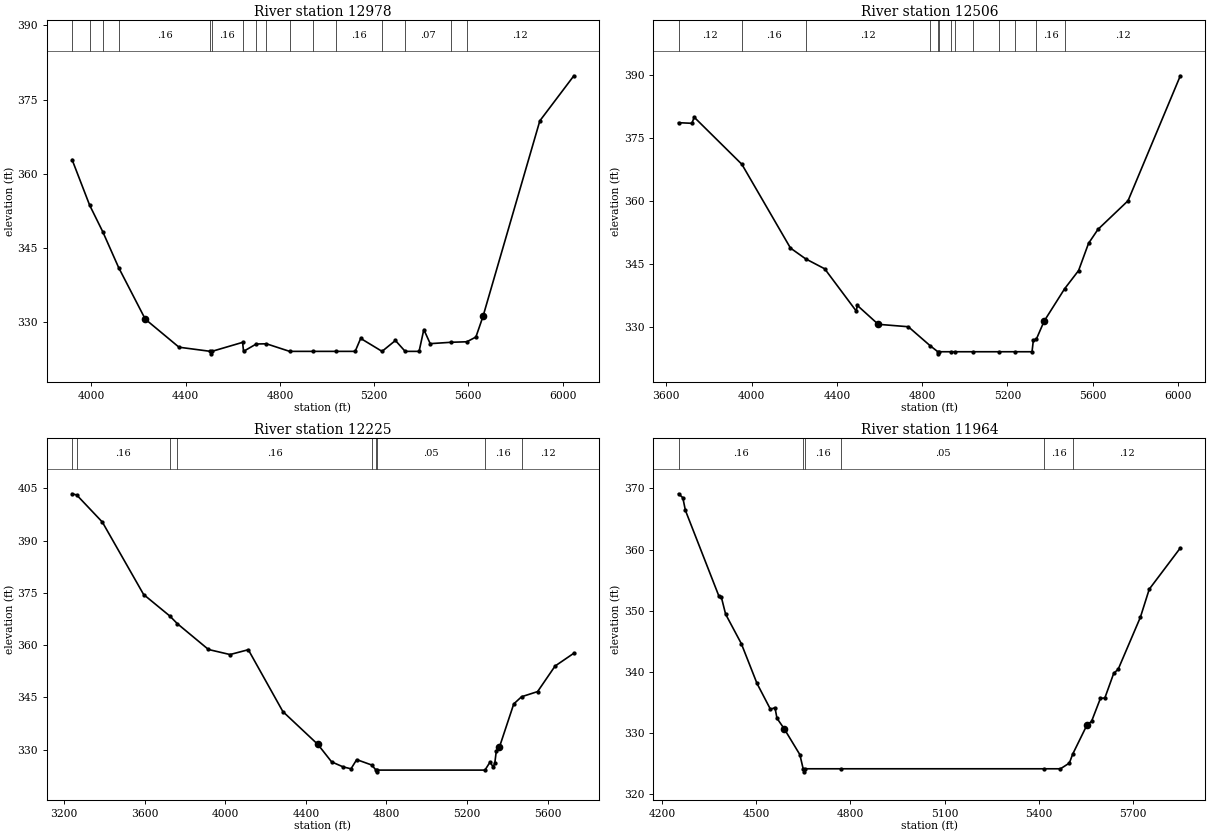
Type RM Length L Ch R = 1 ,12978   ,472,472,472
BEGIN DESCRIPTION:
Mapping XS ca88d821
END DESCRIPTION:
XS GIS Cut Line= 3
      3673205.77     10742684.99      3673445.36     10741888.08
      3673575.57     10740596.37
#Sta/Elev= 30
  3917.7  362.87  3992.3  353.66  4048.5  348.24  4115.3  341.06  4228.5  330.62
  4371.7  324.95  4505.4  324.11  4508.2  323.61  4511.4  324.11  4641.7  325.93
  4645.7  324.11  4699.6   325.6  4742.9  325.64  4841.3  324.11  4939.4  324.11
  5037.5  324.11  5119.6  324.11    5143  326.73  5233.8  324.11  5290.5  326.31
  5331.9  324.11    5391  324.11  5411.1  328.52  5438.2  325.67  5528.2  325.95
  5593.8  326.05  5632.2  327.01  5662.3  331.17  5903.6  370.71  6048.1  379.82
#Mann= 16 ,-1 , 0
  3917.7     .12       0  3992.3     .16       0  4048.5     .12       0
  4115.3     .16       0  4505.4     .07       0  4511.4     .16       0
  4641.7     .12       0  4699.6     .05       0  4742.9     .16       0
  4841.3     .12       0  4939.4     .07       0  5037.5     .16       0
  5233.8      .1       0  5331.9     .07       0  5528.2     .16       0
  5593.8     .12       0
Bank Sta=4228.5,5662.3
XS Rating Curve= 0 ,0
Exp/Cntr=0.3,0.1

Type RM Length L Ch R = 1 ,12506   ,281,281,281
BEGIN DESCRIPTION:
Mapping XS c9871432
END DESCRIPTION:
XS GIS Cut Line= 4
      3673898.49     10742893.27      3673987.03     10741924.53
      3673825.57     10740856.83      3673815.16     10740554.92
#Sta/Elev= 30
  3657.1  378.71  3719.9  378.56  3730.5  380.02  3954.3  368.79  4182.4  348.82
  4253.4  346.26    4343  343.88    4491  333.81  4496.1  335.15  4594.1  330.65
  4735.4  330.07  4838.2  325.53    4874  324.11  4876.7  323.61    4880  324.11
  4937.9  324.11  4953.2  324.11  5037.6  324.11  5159.1  324.11  5237.1  324.11
  5315.9  324.11    5322  326.81  5336.8  327.18  5372.6  331.39  5468.8  339.12
  5534.4  343.46  5581.1  349.95  5625.4  353.28  5766.4   360.1  6011.8  389.89
#Mann= 13 ,-1 , 0
  3657.1     .12       0  3954.3     .16       0  4253.4     .12       0
  4838.2     .16       0    4874     .07       0    4880     .16       0
  4937.9     .05       0  4953.2     .07       0  5037.6     .05       0
  5159.1     .07       0  5237.1      .1       0  5336.8     .16       0
  5468.8     .12       0
Bank Sta=4594.1,5372.6
XS Rating Curve= 0 ,0
Exp/Cntr=0.3,0.1

Type RM Length L Ch R = 1 ,12225   ,261,261,261
BEGIN DESCRIPTION:
ANDING BRANCH 23.0
END DESCRIPTION:
XS GIS Cut Line= 4
       3674721.4     10743143.31      3674638.07     10742396.76
      3674183.21     10741445.37      3673846.38     10740848.12
#Sta/Elev= 30
  3239.3  403.41  3262.2  403.07  3389.5   395.3  3594.6   374.5  3724.2  368.35
  3762.6   366.1  3916.6  358.72  4023.6  357.27  4114.3  358.66    4286   340.9
    4460  331.46    4528  326.47  4585.2  325.03  4624.2  324.48  4652.5  327.12
  4726.5  325.58  4748.5  324.11  4751.2  323.61  4754.5  324.11  5289.3  324.11
    5315  326.45  5329.7     325    5338  326.02  5345.6   329.6  5360.9  330.66
  5432.3   343.1    5471  345.16  5550.7  346.64  5637.4  353.97  5730.7  357.65
#Mann= 9 ,-1 , 0
  3239.3     .12       0  3262.2     .16       0  3724.2     .12       0
  3762.6     .16       0  4726.5     .05       0  4748.5    .033       0
  4754.5     .05       0  5289.3     .16       0    5471     .12       0
Bank Sta=4460,5360.9
XS Rating Curve= 0 ,0
Exp/Cntr=0.3,0.1

Type RM Length L Ch R = 1 ,11964   ,429,429,429
BEGIN DESCRIPTION:
ANDING BRANCH 22.0
END DESCRIPTION:
XS GIS Cut Line= 3
      3675049.64     10741860.21      3674449.61     10741410.19
      3673849.59     10740810.17
#Sta/Elev= 30
  4252.3  369.13  4265.9  368.49  4274.2  366.41  4380.5  352.43  4388.8  352.18
  4402.3  349.42  4452.3   344.6  4502.3  338.08    4545  333.86  4559.6  334.11
  4565.9  332.38  4588.8  330.67  4638.8  326.43  4649.3  324.11  4652.1  323.61
  4655.3  324.11  4771.2  324.11  5418.1  324.11    5469  324.11  5497.3  325.04
  5508.1  326.52  5553.9  331.32    5568  331.86  5596.3  335.63  5610.5  335.71
  5638.7  339.74  5652.9   340.4  5723.6  348.91  5751.9  353.51  5850.9  360.26
#Mann= 6 ,-1 , 0
  4252.3     .16       0  4649.3    .033       0  4655.3     .16       0
  4771.2     .05       0  5418.1     .16       0  5508.1     .12       0
Bank Sta=4588.8,5553.9
XS Rating Curve= 0 ,0
Exp/Cntr=0.3,0.1