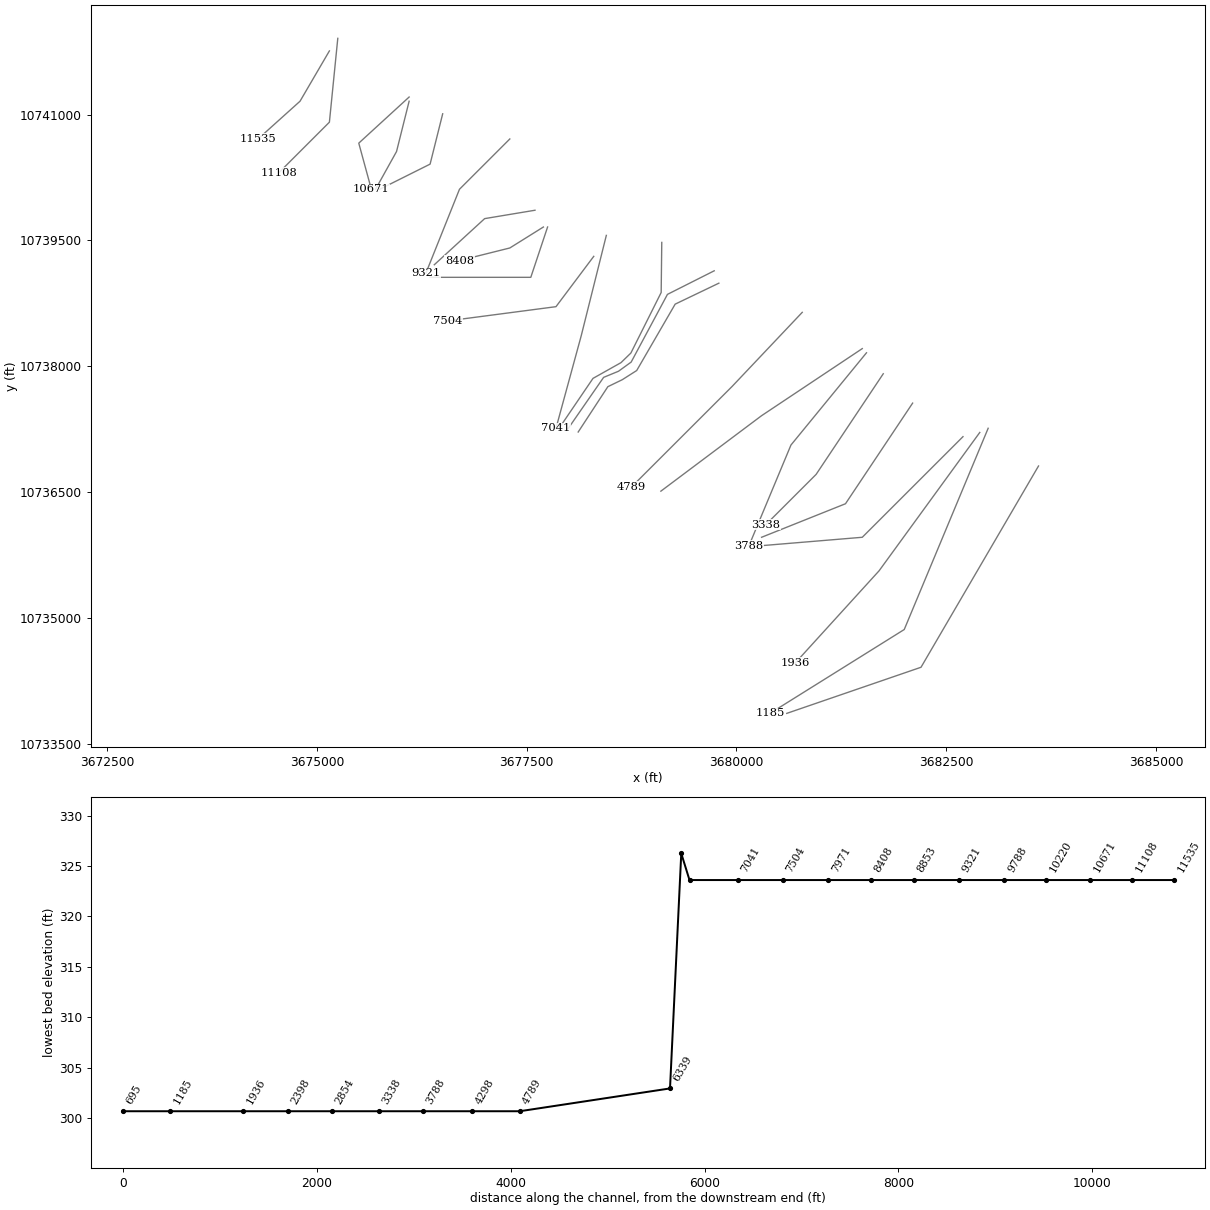
HEC-RAS study ANDING BRANCH.prj: ANDING BRANCH Base Level Engineering

--- ANDING BRANCH.g01 (geometry) --- (continued)

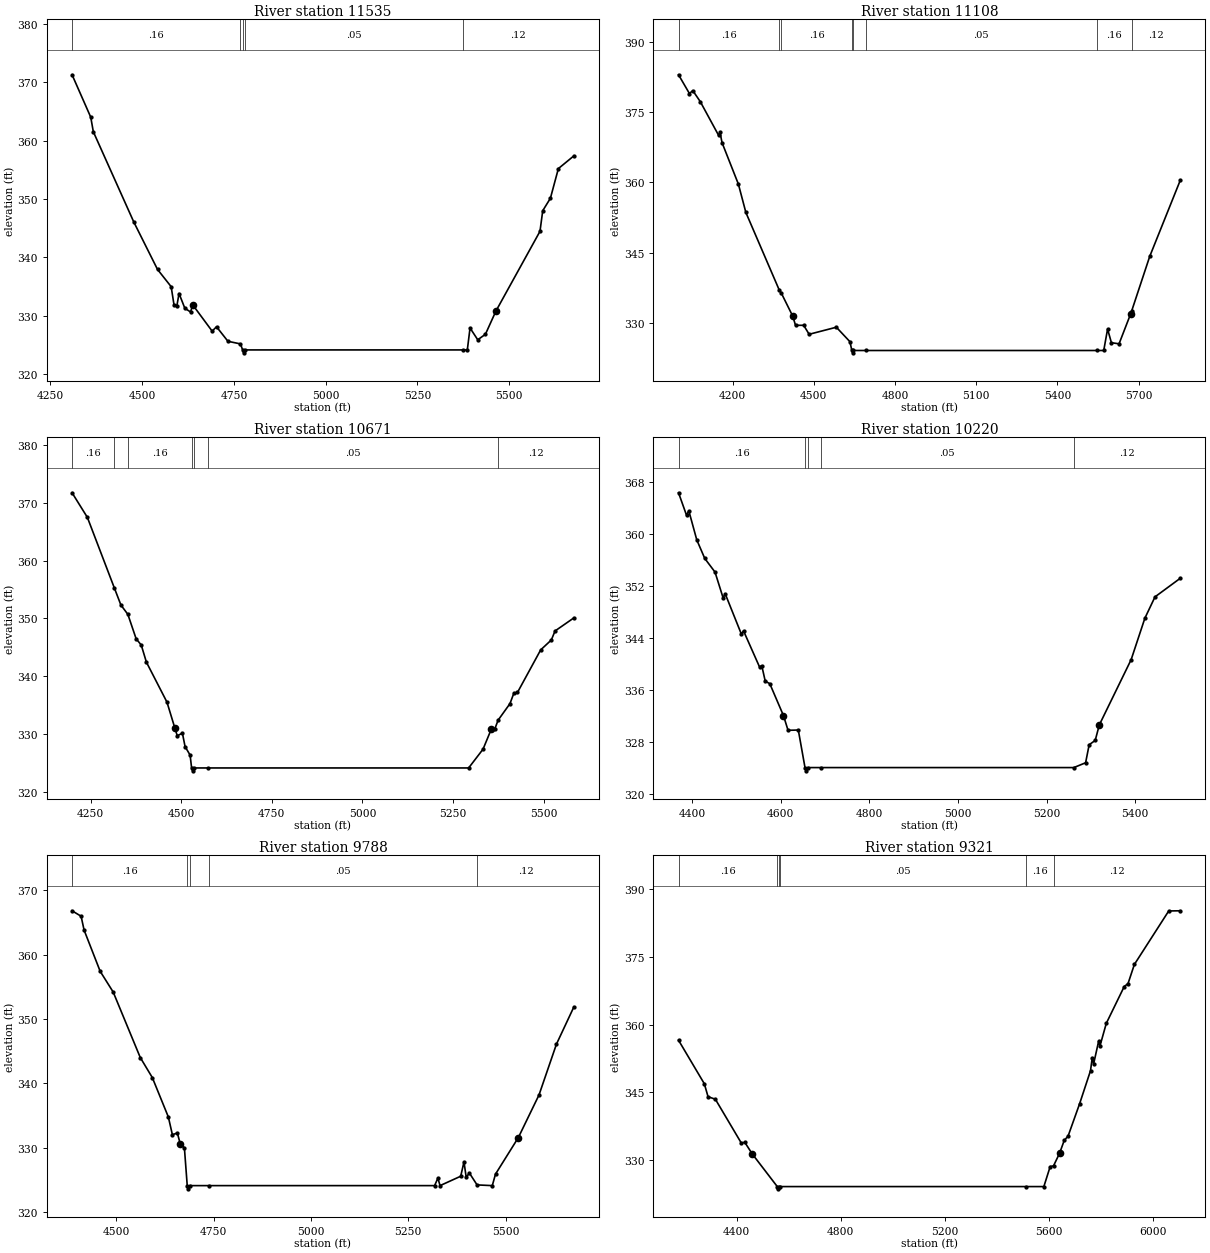
Type RM Length L Ch R = 1 ,11535   ,427,427,427
BEGIN DESCRIPTION:
ANDING BRANCH 21.0
END DESCRIPTION:
XS GIS Cut Line= 3
      3675149.62     10741760.21      3674799.61     10741160.19
      3674299.63     10740710.21
#Sta/Elev= 30
  4308.9  371.27  4359.8     364  4366.8  361.51  4477.2  346.02  4541.7  337.91
  4578.9  334.95  4586.8  331.79  4594.6  331.72  4600.4  333.78  4616.1  331.26
  4631.8  330.61  4637.6  331.84  4690.6  327.33  4702.5  328.08  4733.6  325.59
  4767.8  325.14  4773.6  324.11  4776.3  323.61  4779.6  324.11  5373.6  324.11
  5385.9  324.11  5393.3  327.87  5414.3  325.85  5435.2  326.79  5463.6  330.74
  5583.9  344.44  5591.4  347.97  5612.3  350.11    5634  355.19  5676.2  357.37
#Mann= 5 ,-1 , 0
  4308.9     .16       0  4767.8     .05       0  4773.6    .033       0
  4779.6     .05       0  5373.6     .12       0
Bank Sta=4637.6,5463.6
XS Rating Curve= 0 ,0
Exp/Cntr=0.3,0.1

Type RM Length L Ch R = 1 ,11108   ,437,437,437
BEGIN DESCRIPTION:
ANDING BRANCH 20.0
END DESCRIPTION:
XS GIS Cut Line= 3
      3675249.61     10741910.16      3675149.61     10740910.19
       3674549.6     10740310.18
#Sta/Elev= 30
  4000.6  382.98  4040.8  378.98  4053.3   379.6    4081  377.24  4148.8  370.03
  4153.8  370.67  4161.4  368.47  4221.7  359.63  4249.3  353.58  4373.2  336.94
  4380.1  336.38  4422.7  331.41  4432.7  329.49  4462.9  329.49    4483  327.57
  4583.5  329.08  4633.7  325.99  4640.8  324.11  4643.5  323.61  4646.8  324.11
  4691.3  324.11  5546.8  324.11  5571.2  324.11  5585.4  328.69  5599.5  325.77
  5627.8  325.54  5670.2  331.87  5674.1   332.5    5741  344.19  5854.1  360.48
#Mann= 8 ,-1 , 0
  4000.6     .16       0  4373.2      .1       0  4380.1     .16       0
  4640.8    .033       0  4646.8     .16       0  4691.3     .05       0
  5546.8     .16       0  5674.1     .12       0
Bank Sta=4422.7,5670.2
XS Rating Curve= 0 ,0
Exp/Cntr=0.3,0.1

Type RM Length L Ch R = 1 ,10671   ,451,451,451
BEGIN DESCRIPTION:
Mapping XS d4131427
END DESCRIPTION:
XS GIS Cut Line= 3
      3676099.61     10741210.18      3675499.61     10740660.19
       3675649.6     10740110.21
#Sta/Elev= 30
    4199  371.77  4241.2  367.51    4316  355.22  4333.7  352.33  4352.9  350.71
  4375.7  346.48  4389.8   345.4    4404  342.44  4460.8   335.5  4482.3  331.06
  4489.1  329.69  4503.3  330.13  4510.7  327.81  4524.6  326.33  4528.7  324.11
  4531.4  323.61  4534.7  324.11  4573.4  324.11  5292.8  324.11  5332.5  327.36
    5355  330.78  5365.4  330.94  5374.1  332.39  5406.8  335.25  5417.2  337.01
  5427.5  337.19  5491.5  344.56  5520.8  346.27  5531.2  347.84    5583   350.1
#Mann= 7 ,-1 , 0
    4199     .16       0    4316     .12       0  4352.9     .16       0
  4528.7    .033       0  4534.7     .16       0  4573.4     .05       0
  5374.1     .12       0
Bank Sta=4482.3,5355
XS Rating Curve= 0 ,0
Exp/Cntr=0.3,0.1

Type RM Length L Ch R = 1 ,10220   ,432,432,432
BEGIN DESCRIPTION:
ANDING BRANCH 18.0
END DESCRIPTION:
XS GIS Cut Line= 3
       3676099.6     10741160.15      3675949.61     10740560.19
      3675699.61      10740110.2
#Sta/Elev= 30
    4369  366.27    4387  362.83  4392.2  363.51  4410.2  359.04  4428.2   356.2
  4451.4   354.1  4469.5  350.18  4474.6  350.74  4510.7  344.62  4515.8  345.08
  4551.9  339.55  4557.1   339.7  4564.8  337.37  4575.1  336.98    4606  332.08
  4616.3  329.83  4639.5  329.87  4654.6  324.11  4657.3  323.61  4660.6  324.11
  4690.1  324.11  5261.7  324.11  5288.3  324.85  5296.3  327.61    5310  328.28
  5319.2  330.65  5391.2  340.68  5422.1  347.02    5445   350.3  5502.2  353.16
#Mann= 5 ,-1 , 0
    4369     .16       0  4654.6    .033       0  4660.6     .16       0
  4690.1     .05       0  5261.7     .12       0
Bank Sta=4606,5319.2
XS Rating Curve= 0 ,0
Exp/Cntr=0.3,0.1

Type RM Length L Ch R = 1 ,9788    ,467,467,467
BEGIN DESCRIPTION:
ANDING BRANCH 17.0
END DESCRIPTION:
XS GIS Cut Line= 3
      3676499.61     10741010.19      3676349.61     10740410.19
       3675749.6     10740110.18
#Sta/Elev= 30
  4386.3   366.8  4409.5  365.95  4417.2   363.8  4458.5   357.4    4492  354.17
  4561.5  344.01  4592.5  340.89  4633.7  334.77    4644  332.03  4656.9  332.28
  4664.6   330.5  4674.9     330  4682.2  324.11    4685  323.61  4688.2  324.11
  4738.8  324.11  5317.8  324.11  5326.2  325.27  5331.8  324.11  5384.9  325.57
  5393.3   327.8  5398.9  325.43  5407.3  326.05  5426.9  324.22    5466  324.11
  5474.3   325.9    5533  331.58  5586.1   338.2  5630.9  346.09  5675.6  351.86
#Mann= 5 ,-1 , 0
  4386.3     .16       0  4682.2    .033       0  4688.2     .16       0
  4738.8     .05       0  5426.9     .12       0
Bank Sta=4664.6,5533
XS Rating Curve= 0 ,0
Exp/Cntr=0.3,0.1

Type RM Length L Ch R = 1 ,9321    ,468,468,468
BEGIN DESCRIPTION:
ANDING BRANCH 16.0
END DESCRIPTION:
XS GIS Cut Line= 3
      3677299.62      10740710.2      3676699.61     10740110.19
       3676299.6     10739110.17
#Sta/Elev= 30
  4177.5  356.52  4276.5  346.88  4290.7  344.02  4318.9  343.45  4417.9   333.8
  4432.1  333.88  4460.4  331.34  4556.4  324.11  4559.1  323.61  4562.4  324.11
  4568.3  324.11  5509.3  324.11  5579.4  324.11  5603.6  328.53  5616.5   328.7
    5640  331.52  5657.5  334.33  5672.3  335.28  5716.7  342.47  5758.4  349.77
  5765.2  352.67  5770.5  351.31  5789.4  356.25  5794.8  355.26    5819  360.26
  5887.7   368.4  5902.5  369.08  5926.7   373.3  6058.6  385.15  6103.1  385.19
#Mann= 6 ,-1 , 0
  4177.5     .16       0  4556.4    .033       0  4562.4     .16       0
  4568.3     .05       0  5509.3     .16       0  5616.5     .12       0
Bank Sta=4460.4,5640
XS Rating Curve= 0 ,0
Exp/Cntr=0.3,0.1

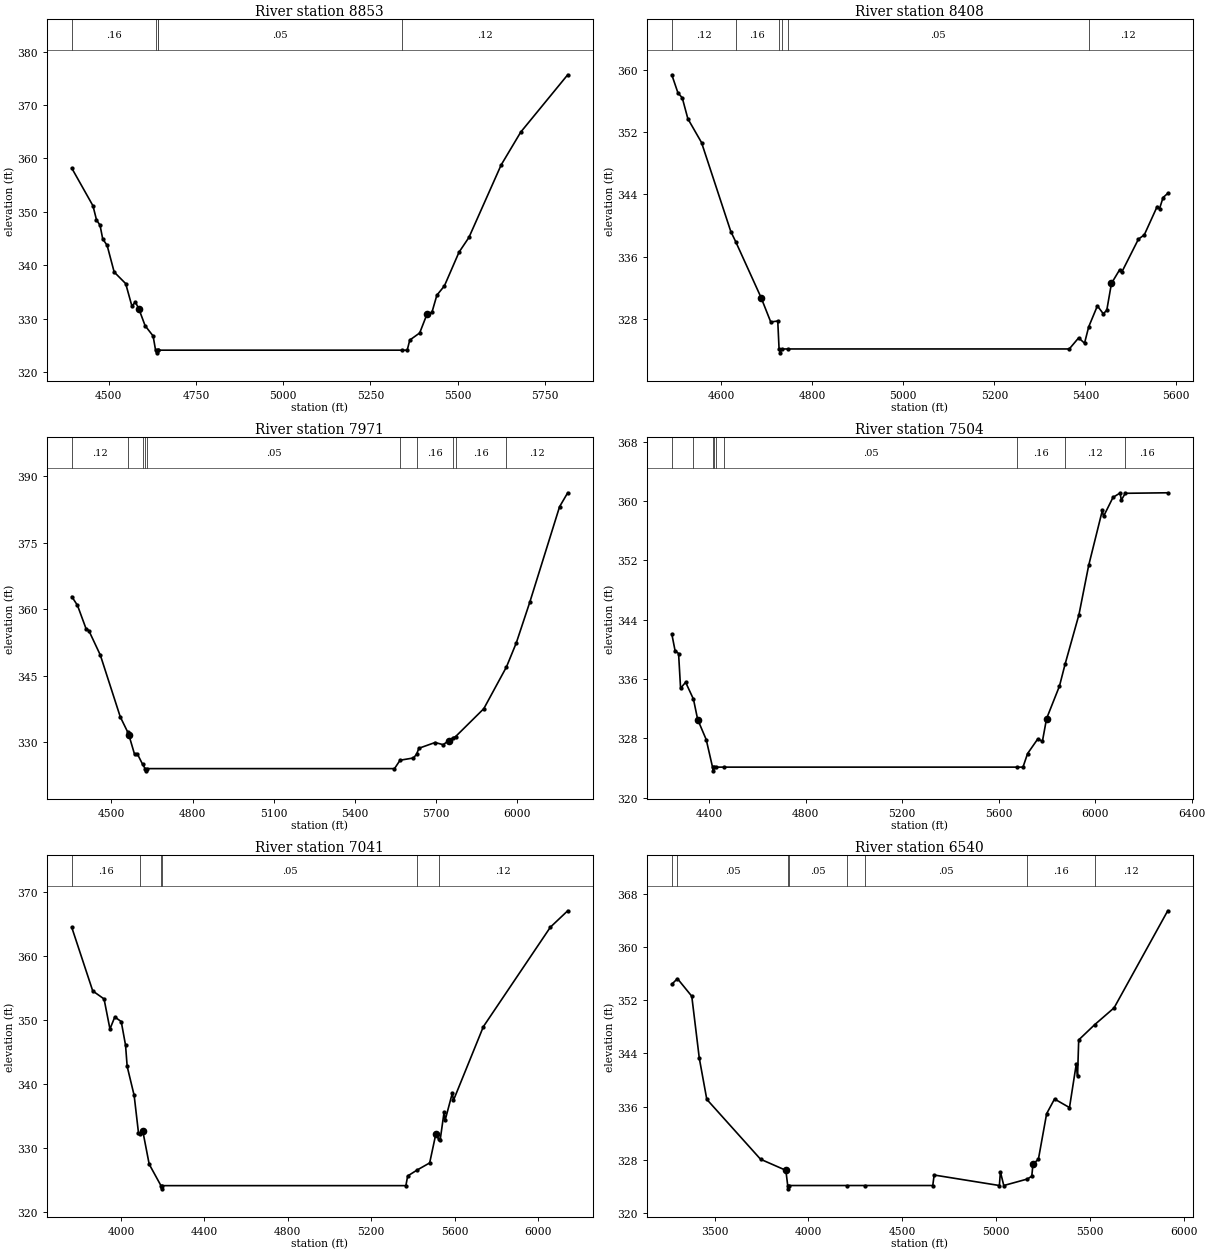
Type RM Length L Ch R = 1 ,8853    ,445,445,445
BEGIN DESCRIPTION:
ANDING BRANCH 15.0
END DESCRIPTION:
XS GIS Cut Line= 3
      3677599.59     10739860.19      3676999.61     10739760.19
      3676399.61     10739210.19
#Sta/Elev= 30
  4393.8  358.18  4454.6  351.13  4464.7   348.5  4474.9  347.48  4482.5  344.94
  4495.2  343.72  4515.4  338.73  4548.4  336.57  4566.1  332.39  4576.3  333.11
  4586.4   331.8  4604.1  328.69    4627  326.77  4634.1  324.11  4636.8  323.61
  4640.1  324.11  4640.8  324.11  5339.7  324.11  5355.7  324.11  5363.1     326
  5391.5  327.33  5412.4  330.84  5426.6  331.18  5440.8   334.4  5462.4  336.14
  5504.3  342.45  5532.7  345.21  5625.2  358.79  5681.3  364.93    5816  375.66
#Mann= 5 ,-1 , 0
  4393.8     .16       0  4634.1    .033       0  4640.1     .16       0
  4640.8     .05       0  5339.7     .12       0
Bank Sta=4586.4,5412.4
XS Rating Curve= 0 ,0
Exp/Cntr=0.3,0.1

Type RM Length L Ch R = 1 ,8408    ,437,437,437
BEGIN DESCRIPTION:
ANDING BRANCH 14.0
END DESCRIPTION:
XS GIS Cut Line= 3
      3677699.57     10739660.17      3677299.61     10739410.19
      3676699.63     10739260.19
#Sta/Elev= 30
    4491  359.41  4504.5  357.08    4514  356.44  4526.3  353.75  4556.4  350.68
  4620.7  339.23  4631.4  337.93  4687.3  330.72  4708.5  327.58  4723.9  327.71
  4726.8  324.11  4729.5  323.61  4732.8  324.11  4745.4  324.11  5364.7  324.11
  5385.3  325.54  5398.2  324.85  5407.4  326.96  5426.5  329.66  5439.4  328.64
  5447.1  329.09  5457.4  332.55  5475.5  334.32  5480.6  334.06  5516.7  338.25
  5529.6   338.8  5557.9  342.45  5563.1  342.17  5570.8   343.6  5581.1  344.14
#Mann= 6 ,-1 , 0
    4491     .12       0  4631.4     .16       0  4726.8    .033       0
  4732.8     .16       0  4745.4     .05       0  5407.4     .12       0
Bank Sta=4687.3,5457.4
XS Rating Curve= 0 ,0
Exp/Cntr=0.3,0.1

Type RM Length L Ch R = 1 ,7971    ,467,467,467
BEGIN DESCRIPTION:
ANDING BRANCH 13.0
END DESCRIPTION:
XS GIS Cut Line= 3
       3677749.6     10739660.18      3677549.61     10739060.19
      3676349.65     10739060.19
#Sta/Elev= 30
  4353.5  362.85  4374.6  360.87  4406.2  355.62  4416.7  355.17  4458.9  349.69
  4532.7  335.76  4560.4  332.31  4564.3  331.72  4585.4  327.34  4595.9  327.41
  4615.2  325.08  4624.6  324.11  4627.3  323.61  4630.6  324.11  5545.9  324.11
  5566.5     326  5615.9  326.51  5627.6  327.35  5635.9  328.69  5695.9  329.99
  5725.9   329.5  5745.9  330.42  5761.9  331.06  5771.4  331.31  5875.9  337.61
  5959.6  347.01  5995.9  352.42  6045.9  361.61  6155.9   383.1  6185.9  386.23
#Mann= 10 ,-1 , 0
  4353.5     .12       0  4560.4     .16       0  4615.2     .05       0
  4624.6    .033       0  4630.6     .05       0  5566.5     .12       0
  5627.6     .16       0  5761.9     .05       0  5771.4     .16       0
  5959.6     .12       0
Bank Sta=4564.3,5745.9
XS Rating Curve= 0 ,0
Exp/Cntr=0.3,0.1

Type RM Length L Ch R = 1 ,7504    ,463,463,463
BEGIN DESCRIPTION:
Mapping XS e1947754
END DESCRIPTION:
XS GIS Cut Line= 3
       3678299.6     10739310.17      3677849.61     10738710.19
      3676554.62     10738540.01
#Sta/Elev= 30
  4244.4  342.06  4257.9  339.82  4272.5  339.42  4280.8  334.74  4301.7  335.55
  4334.2  333.27  4351.7  330.53  4387.1  327.82  4413.3  324.11    4416  323.61
  4419.3  324.11  4425.9  324.11  4460.4  324.11    5676  324.11  5700.4  324.11
  5719.5  325.94  5760.9  327.87  5781.1  327.62  5798.2  330.65  5851.7  335.04
  5874.8  337.97  5932.4  344.66  5972.7  351.29  6029.4  358.71  6034.4  357.91
  6073.6  360.47    6103  361.06  6108.1   360.1  6124.4  361.02  6300.5  361.09
#Mann= 9 ,-1 , 0
  4244.4     .16       0  4334.2     .12       0  4413.3    .033       0
  4419.3     .12       0  4425.9     .16       0  4460.4     .05       0
    5676     .16       0  5874.8     .12       0  6124.4     .16       0
Bank Sta=4351.7,5798.2
XS Rating Curve= 0 ,0
Exp/Cntr=0.3,0.1

Type RM Length L Ch R = 1 ,7041    ,501,501,501
BEGIN DESCRIPTION:
ANDING BRANCH 11.0
END DESCRIPTION:
XS GIS Cut Line= 3
      3678449.62     10739560.23      3678149.61     10738360.19
       3677849.6     10737260.14
#Sta/Elev= 30
  3764.5  364.47    3865  354.54  3919.2  353.29  3947.5  348.59  3970.7  350.47
  4001.6  349.75  4022.2  346.07    4030  342.75  4063.5  338.21  4084.1   332.4
  4091.3  332.18  4104.7  332.68  4135.6  327.46  4191.9  324.11  4194.6  323.61
  4197.9  324.11    5366  324.11  5374.6  325.62  5420.4  326.56    5480  327.66
  5509.4  332.15  5523.1  331.39  5530.1  331.19  5549.1   335.6  5554.3  334.35
  5588.8  338.59    5594  337.44  5737.4  348.96  6058.7  364.51  6141.7  367.07
#Mann= 6 ,-1 , 0
  3764.5     .16       0  4091.3     .05       0  4191.9    .033       0
  4197.9     .05       0  5420.4     .16       0  5523.1     .12       0
Bank Sta=4104.7,5509.4
XS Rating Curve= 0 ,0
Exp/Cntr=0.3,0.1

Type RM Length L Ch R = 1 ,6540    ,85,85,85
BEGIN DESCRIPTION:
ANDING BRANCH 10.0
END DESCRIPTION:
XS GIS Cut Line= 6
      3679110.12     10739476.57      3679103.18      10738879.3
      3678742.06     10738157.08      3678624.01      10738042.5
      3678290.68       10737855.      3677905.24     10737287.26
#Sta/Elev= 30
  3271.9  354.43    3302  355.27  3378.3  352.62  3418.3   343.3  3458.3  337.09
  3744.6  328.07  3879.4   326.4  3889.3  324.11    3892  323.61  3895.3  324.11
  4204.3  324.11  4301.9  324.11    4662  324.11  4669.3  325.69  5016.8  324.11
  5022.2  326.17  5040.2  324.11  5166.1  325.09  5189.4  325.52  5195.7  327.35
  5224.6  328.06  5268.5  334.93  5310.5  337.14  5390.2  335.85  5426.5  342.43
  5433.2  340.59  5439.3  346.04  5523.8  348.32  5627.8  350.87  5913.5  365.49
#Mann= 8 ,-1 , 0
  3271.9     .16       0    3302     .05       0  3889.3     .03       0
  3895.3     .05       0  4204.3     .16       0  4301.9     .05       0
  5166.1     .16       0  5523.8     .12       0
Bank Sta=3879.4,5195.7
XS Rating Curve= 0 ,0
Exp/Cntr=0.3,0.1

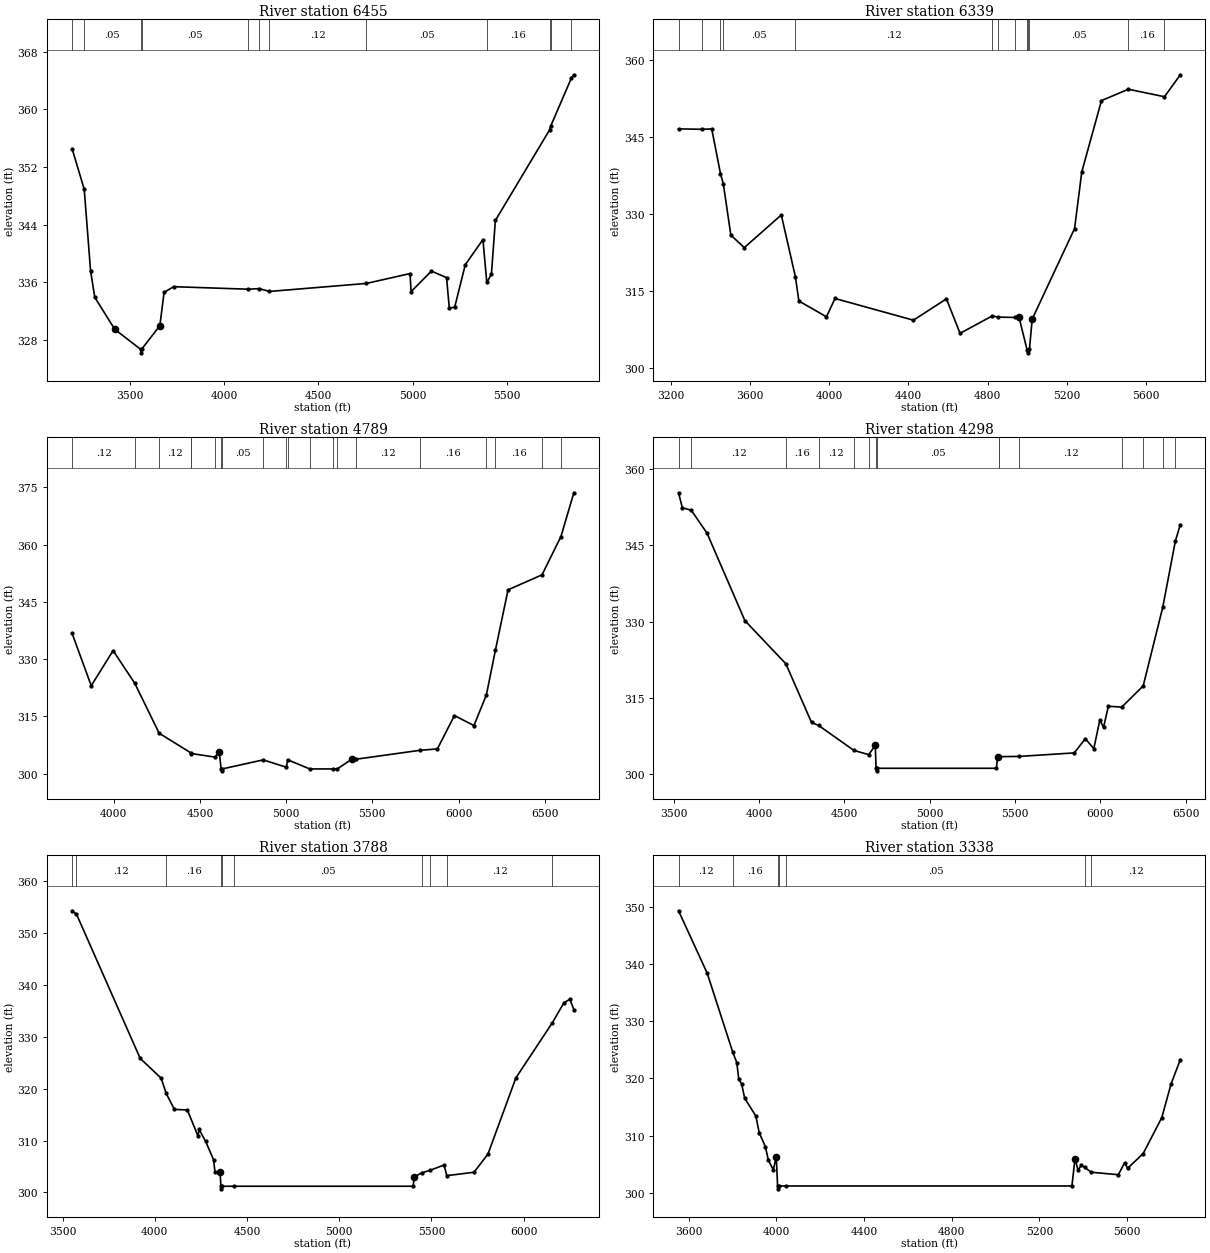
Type RM Length L Ch R = 1 ,6455    ,116,116,116
BEGIN DESCRIPTION:
Mapping XS 8377fda1
END DESCRIPTION:
XS GIS Cut Line= 6
      3679735.11     10739137.98      3679177.83     10738856.73
      3678745.54     10738049.44       3678594.5     10737940.07
      3678417.41     10737867.15      3677995.55      10737257.8
#Sta/Elev= 30
  3193.9  354.56  3258.3  348.92  3292.1  337.59  3314.4  333.94  3420.3  329.51
  3556.7  326.75  3559.4  326.25  3562.7  326.75  3659.3  330.01  3681.7  334.63
  3732.5  335.42  4127.5  335.07  4185.6  335.15  4240.5  334.76  4754.3  335.87
  4985.8  337.24  4991.2  334.73  5099.1  337.58  5179.4  336.67  5193.7  332.47
  5222.2  332.56  5278.6  338.47  5372.1  341.95  5392.7     336  5417.1  337.15
  5438.1   344.6  5725.1  357.13  5732.3  357.73  5841.5  364.36  5854.2  364.79
#Mann= 12 ,-1 , 0
  3193.9     .12       0  3258.3     .05       0  3556.7     .03       0
  3562.7     .05       0  4127.5     .12       0  4185.6     .16       0
  4240.5     .12       0  4754.3     .05       0  5392.7     .16       0
  5725.1     .05       0  5732.3     .16       0  5841.5     .05       0
Bank Sta=3420.3,3659.3
XS Rating Curve= 0 ,0
Exp/Cntr=0.3,0.1

Type RM Length L Ch R = 1 ,6339    ,1550,1550,1550
BEGIN DESCRIPTION:
ANDING BRANCH 9.0
END DESCRIPTION:
XS GIS Cut Line= 6
       3679790.7     10738990.42      3679269.84     10738740.41
      3678811.51     10737948.75      3678639.63     10737839.37
      3678467.76     10737756.04      3678114.38     10737215.57
#Sta/Elev= 30
  3239.5   346.6  3357.6  346.52  3407.1  346.59  3451.3  337.86  3465.4  335.93
  3503.6  325.89  3571.5  323.46  3758.3  329.83  3829.4  317.78    3847  313.06
  3986.2  309.98  4029.3  313.55  4425.3  309.32  4591.8  313.48  4660.6  306.76
  4823.1  310.15  4852.6  309.93  4937.5  309.85    4958  309.91  4999.5  303.46
  5002.2  302.96  5005.5  303.46  5010.8  303.62  5024.7  309.53  5238.7  327.18
  5274.9   338.2  5374.4  352.11  5510.5  354.32  5692.5  352.86  5772.5  357.14
#Mann= 13 ,-1 , 0
  3239.5     .16       0  3357.6     .05       0  3451.3     .16       0
  3465.4     .05       0  3829.4     .12       0  4823.1     .05       0
  4852.6     .07       0  4937.5     .12       0  4999.5     .07       0
  5005.5     .12       0  5010.8     .05       0  5510.5     .16       0
  5692.5     .05       0
Bank Sta=4958,5024.7
XS Rating Curve= 0 ,0
Exp/Cntr=0.3,0.1

Type RM Length L Ch R = 1 ,4789    ,491,491,491
BEGIN DESCRIPTION:
ANDING BRANCH 7.0
END DESCRIPTION:
XS GIS Cut Line= 3
      3680784.26      10738642.6      3679949.61     10737760.19
      3678749.59     10736560.17
#Sta/Elev= 30
  3757.6  336.73  3868.8     323  3995.9  332.21  4121.8  323.61    4263  310.55
  4446.5  305.42  4449.1  305.24  4586.5   304.3  4611.6  305.57  4622.7   301.2
  4625.5   300.7  4628.7   301.2  4866.7  303.57  5001.8  301.63  5007.8  303.61
  5136.6   301.2  5271.3   301.2  5296.2   301.2  5382.3  303.79  5406.1  303.75
  5777.6  306.09  5877.3  306.44  5976.3  315.19  6089.4  312.57  6161.6  320.57
  6214.6  332.42  6287.4  348.13  6484.2  352.05  6594.2  362.08  6669.3  373.56
#Mann= 20 ,-1 , 0
  3757.6     .12       0  4121.8     .05       0    4263     .12       0
  4446.5     .16       0  4449.1     .12       0  4586.5     .05       0
  4622.7    .035       0  4628.7     .05       0  4866.7     .05       0
  5001.8     .12       0  5007.8     .16       0  5136.6     .05       0
  5271.3     .07       0  5296.2     .16       0  5406.1     .12       0
  5777.6     .16       0  6161.6     .05       0  6214.6     .16       0
  6484.2     .05       0  6594.2     .16       0
Bank Sta=4611.6,5382.3
XS Rating Curve= 0 ,0
Exp/Cntr=0.3,0.1

Type RM Length L Ch R = 1 ,4298    ,510,510,510
BEGIN DESCRIPTION:
ANDING BRANCH 6.0
END DESCRIPTION:
XS GIS Cut Line= 3
      3681499.57     10738210.16      3680299.61     10737410.19
      3679099.59     10736510.17
#Sta/Elev= 30
  3527.4  355.26  3549.9  352.31  3601.8  351.84  3694.1  347.36  3916.4  330.18
  4156.7   321.7  4307.1   310.2  4348.1  309.62  4555.9   304.7  4642.2  303.88
  4681.1  305.68  4685.6   301.2  4688.4   300.7  4691.6   301.2  5391.4   301.2
  5397.7  303.32  5404.6  303.44  5406.8  303.48  5524.9  303.53  5847.7  304.22
  5912.3  307.01  5962.3  305.05  5997.7  310.68  6019.6  309.24  6047.7  313.38
    6126   313.2  6251.9  317.37  6366.5  332.78  6440.5  345.77  6469.6  349.03
#Mann= 15 ,-1 , 0
  3527.4     .05       0  3601.8     .12       0  4156.7     .16       0
  4348.1     .12       0  4555.9     .16       0  4642.2     .05       0
  4685.6    .033       0  4691.6     .05       0  5404.6     .16       0
  5406.8     .07       0  5524.9     .12       0    6126     .16       0
  6251.9     .05       0  6366.5     .16       0  6440.5     .05       0
Bank Sta=4681.1,5397.7
XS Rating Curve= 0 ,0
Exp/Cntr=0.3,0.1

Type RM Length L Ch R = 1 ,3788    ,450,450,450
BEGIN DESCRIPTION:
ANDING BRANCH 5.0
END DESCRIPTION:
XS GIS Cut Line= 3
       3681549.6     10738160.18      3680649.61     10737060.19
      3680149.59     10735860.15
#Sta/Elev= 30
    3551  354.24    3575  353.58  3920.7   325.8  4034.1  322.01  4061.6  319.06
  4105.9     316  4176.2  315.88  4233.6  310.89  4240.1  312.13  4275.3  309.84
  4318.3  306.31  4326.2  303.91  4353.5  303.92  4358.4   301.2  4361.1   300.7
  4364.4   301.2  4426.6   301.2  5400.7   301.2  5406.1  302.96  5447.2  303.79
  5493.4  304.28  5568.1  305.29  5583.4  303.24  5730.6  303.89  5806.4  307.39
  5958.1  322.08  6154.6  332.62  6218.1  336.51  6250.6  337.21  6272.3  335.21
#Mann= 10 ,-1 , 0
    3551     .05       0    3575     .12       0  4061.6     .16       0
  4358.4    .033       0  4364.4     .16       0  4426.6     .05       0
  5447.2     .12       0  5493.4     .16       0  5583.4     .12       0
  6154.6     .16       0
Bank Sta=4353.5,5406.1
XS Rating Curve= 0 ,0
Exp/Cntr=0.3,0.1

Type RM Length L Ch R = 1 ,3338    ,484,484,484
BEGIN DESCRIPTION:
ANDING BRANCH 4.0
END DESCRIPTION:
XS GIS Cut Line= 3
      3681749.61     10737910.19      3680949.61     10736710.19
      3680349.64     10736110.22
#Sta/Elev= 30
  3552.8  349.29  3683.5   338.4  3800.8  324.53  3818.7  322.75  3827.7  319.92
  3841.2  318.96  3854.8  316.54  3905.8  313.42  3920.9  310.53  3949.4  308.06
  3962.9   305.7  3985.5  304.03    3999  306.31    4005   301.2  4007.8   300.7
    4011   301.2  4044.4   301.2  5348.6   301.2  5362.7     306  5376.9  303.91
    5391  304.88  5406.6  304.45  5437.1   303.6  5560.7  303.17    5589  305.24
  5603.1   304.3  5673.8  306.86  5758.7  313.13  5801.1  319.01  5843.5  323.28
#Mann= 7 ,-1 , 0
  3552.8     .12       0  3800.8     .16       0    4005    .033       0
    4011     .16       0  4044.4     .05       0  5406.6     .16       0
  5437.1     .12       0
Bank Sta=3999,5362.7
XS Rating Curve= 0 ,0
Exp/Cntr=0.3,0.1

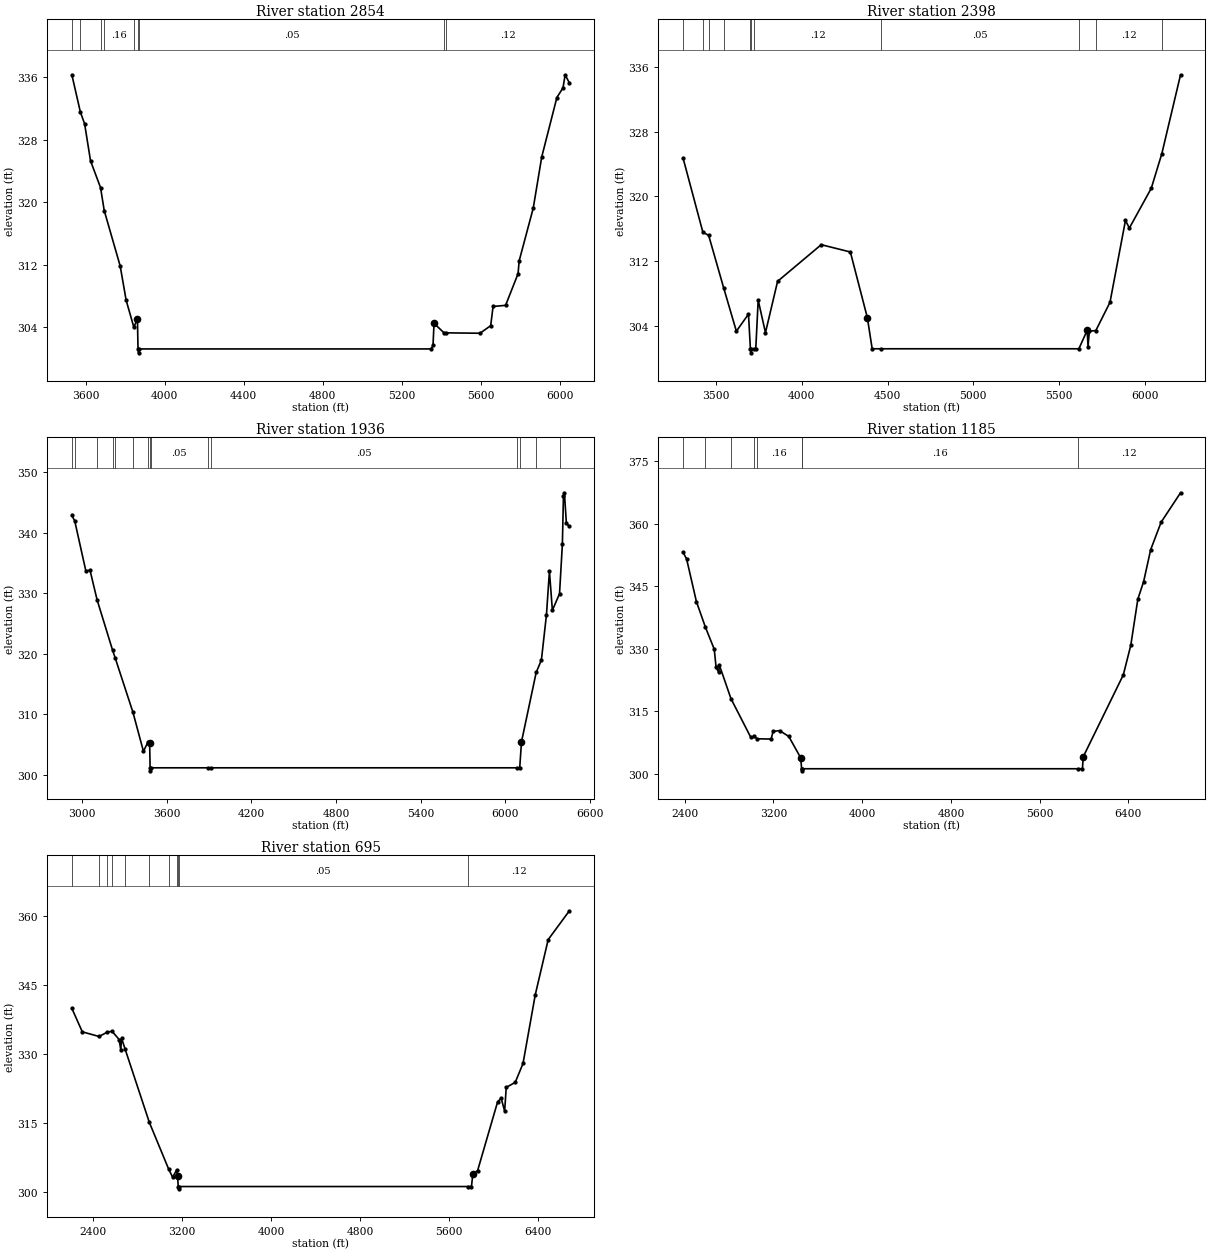
Type RM Length L Ch R = 1 ,2854    ,456,456,456
BEGIN DESCRIPTION:
ANDING BRANCH 3.0
END DESCRIPTION:
XS GIS Cut Line= 3
      3682099.59     10737560.15      3681299.61     10736360.19
      3680299.62     10735960.19
#Sta/Elev= 30
  3530.5  336.31  3573.5  331.55  3595.1  330.03  3625.1  325.28  3675.8  321.86
  3694.4  318.92  3775.3  311.81  3805.4  307.43  3844.5  303.97  3862.5  305.09
  3865.5   301.2  3868.2   300.7  3871.5   301.2  5349.6   301.2  5359.1  301.64
  5364.4  304.48  5413.7  303.29  5425.1  303.26  5597.4  303.21  5651.2  304.18
  5663.3  306.64  5726.6  306.78  5789.9  310.84  5795.3  312.47  5866.6  319.22
  5909.7  325.79  5986.4   333.4  6017.4  334.64  6028.2   336.3  6049.7  335.27
#Mann= 9 ,-1 , 0
  3530.5     .12       0  3573.5     .16       0  3675.8     .05       0
  3694.4     .16       0  3844.5     .05       0  3865.5    .033       0
  3871.5     .05       0  5413.7     .16       0  5425.1     .12       0
Bank Sta=3862.5,5364.4
XS Rating Curve= 0 ,0
Exp/Cntr=0.3,0.1

Type RM Length L Ch R = 1 ,2398    ,462,462,462
BEGIN DESCRIPTION:
ANDING BRANCH 2.0
END DESCRIPTION:
XS GIS Cut Line= 3
       3682699.6     10737160.18      3681499.61     10735960.19
      3680299.62     10735860.19
#Sta/Elev= 30
  3306.9  324.75  3422.6  315.59  3456.6  315.18    3545  308.64    3618  303.37
  3688.7  305.47  3699.9   301.2  3702.6   300.7  3705.9   301.2  3720.9   301.2
  3731.2   301.2  3745.3   307.2  3787.7  303.19  3858.4  309.52    4113  314.04
  4282.7  313.14  4381.7  305.05    4410   301.2  4462.7   301.2  5615.2   301.2
  5663.7  303.47  5668.7  301.47  5676.3  303.37  5714.2  303.45  5796.7  306.93
    5887  317.04  5909.6  316.09  6037.5     321    6099  325.27  6208.1     335
#Mann= 11 ,-1 , 0
  3306.9     .12       0  3422.6     .16       0  3456.6     .12       0
    3545     .16       0  3699.9    .033       0  3705.9     .16       0
  3720.9     .12       0  4462.7     .05       0  5615.2     .16       0
  5714.2     .12       0    6099     .16       0
Bank Sta=4381.7,5663.7
XS Rating Curve= 0 ,0
Exp/Cntr=0.3,0.1

Type RM Length L Ch R = 1 ,1936    ,751,751,751
BEGIN DESCRIPTION:
ANDING BRANCH 1.0
END DESCRIPTION:
XS GIS Cut Line= 3
      3682899.62      10737210.2      3681699.61     10735560.19
      3680699.64     10734460.22
#Sta/Elev= 30
  2927.9  342.81  2948.3  341.91  3027.2  333.65  3056.6  333.78  3106.7   328.9
  3216.6  320.59  3235.8  319.26  3360.6  310.38  3435.3  303.92  3468.3  305.48
  3479.3  305.36  3482.5   301.2  3485.3   300.7  3488.5   301.2  3889.8   301.2
  3911.7   301.2    6082   301.2  6102.6   301.2  6115.2  305.48  6219.3  316.92
  6256.4  318.98  6292.2  326.44  6313.2  333.63  6334.1  327.17  6384.8   329.9
  6405.1  338.12  6412.5  345.98  6419.3  346.55  6433.5  341.49  6454.7  341.02
#Mann= 15 ,-1 , 0
  2927.9     .16       0  2948.3     .05       0  3106.7     .12       0
  3216.6     .16       0  3235.8     .12       0  3360.6     .16       0
  3468.3     .05       0  3482.5    .033       0  3488.5     .05       0
  3889.8     .12       0  3911.7     .05       0    6082     .16       0
  6102.6     .12       0  6219.3     .16       0  6384.8     .12       0
Bank Sta=3479.3,6115.2
XS Rating Curve= 0 ,0
Exp/Cntr=0.3,0.1

Type RM Length L Ch R = 1 ,1185    ,490,490,490
BEGIN DESCRIPTION:
Mapping XS fdjew786
END DESCRIPTION:
XS GIS Cut Line= 3
      3682999.63     10737260.23      3681999.61     10734860.19
      3680399.65     10733860.21
#Sta/Elev= 30
  2384.3  353.17  2416.9  351.52  2505.1  341.31  2585.7  335.21    2666  329.88
  2682.8   325.5  2706.6  324.34  2712.1  326.08  2816.9  318.01  2995.9  308.72
  3025.4     309  3052.3  308.39    3179  308.33  3196.9  310.17  3255.9  310.35
  3338.2  308.95    3446   303.8  3453.9   301.2  3456.6   300.7  3459.9   301.2
  5945.7   301.2  5986.7   301.2  5993.2  304.05  6355.2  323.74  6422.4  330.83
  6486.1   341.9    6538  346.08  6601.7  353.76    6696  360.36  6871.1  367.42
#Mann= 8 ,-1 , 0
  2384.3     .16       0  2585.7     .05       0  2816.9     .12       0
  3025.4     .05       0  3052.3     .16       0  3453.9    .033       0
  3459.9     .16       0  5945.7     .12       0
Bank Sta=3446,5993.2
XS Rating Curve= 0 ,0
Exp/Cntr=0.3,0.1

Type RM Length L Ch R = 1 ,695     ,0,0,0
BEGIN DESCRIPTION:
Mapping XS 145asd57
END DESCRIPTION:
XS GIS Cut Line= 3
      3683599.63     10736810.22      3682199.61     10734410.19
      3680599.63     10733860.19
#Sta/Elev= 30
  2209.2  339.95  2303.1  334.84  2454.4  333.83  2526.5  334.77  2570.5  334.97
  2633.9  333.17  2649.2  330.88  2655.4  333.46  2686.6  331.17  2905.6  315.14
  3079.2  304.98  3115.1  303.21  3151.1  304.82  3158.6  303.55  3165.1   301.2
  3167.8   300.7  3171.1   301.2  5764.2   301.2  5799.8   301.2  5812.5  304.02
  5854.8  304.65  6034.6  319.61  6066.3  320.42    6098   317.6  6112.2  322.75
  6193.2  323.86  6263.1  327.97    6373  342.91  6489.3  354.91  6679.6  361.17
#Mann= 11 ,-1 , 0
  2209.2     .16       0  2454.4     .05       0  2526.5     .16       0
  2570.5     .08       0  2686.6     .16       0  2905.6     .12       0
  3079.2     .16       0  3151.1     .05       0  3165.1    .033       0
  3171.1     .05       0  5764.2     .12       0
Bank Sta=3158.6,5812.5
XS Rating Curve= 0 ,0
Exp/Cntr=0.3,0.1

Chan Stop Cuts=-1
Use User Specified Reach Order=0
Composite Channel Slope=5