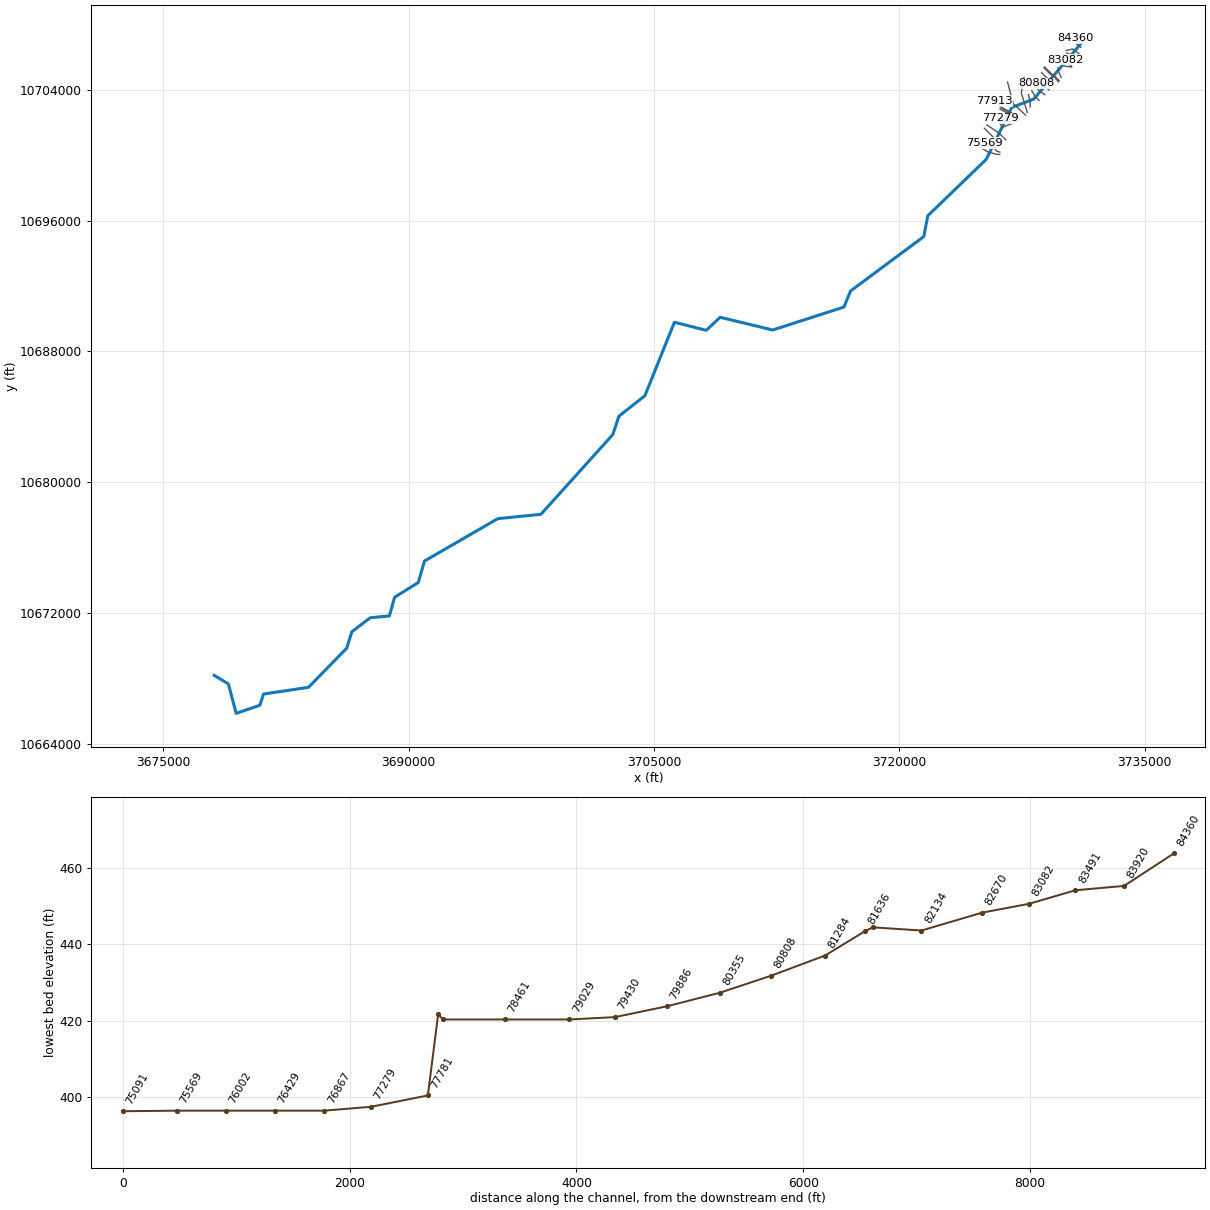
--- BEAVER CREEK.prj (project) ---

Proj Title=BEAVER CREEK Base Level Engineering
Current Plan=p01
Default Exp/Contr=0.3,0.1
English Units
Geom File=g01
Geom File=g02
Flow File=f01
Plan File=p01
Y Axis Title=Elevation
X Axis Title(PF)=Main Channel Distance
X Axis Title(XS)=Station
BEGIN DESCRIPTION:
BEAVER CREEK
END DESCRIPTION:
DSS File=dss
DSS Export Rating Curves= 0
DSS Export Rating Curve Sorted= 0
DSS Export Volume Flow Curves= 0
DXF OffsetX= 0
DXF OffsetY= 0
DXF ScaleX= 1
DXF ScaleY= 10

--- BEAVER CREEK.p01 (plan) ---

Plan Title=Multiple Run
Program Version=4.10
Short Identifier=Multiple Run
Geom File=g01
Flow File=f01
Subcritical Flow
K Sum by GR= 0
Std Step Tol= 0.01
Critical Tol= 0.01
Num of Std Step Trials= 20
Max Error Tol= 0.3
Flow Tol Ratio= 0.001
Split Flow NTrial= 30
Split Flow Tol= 0.02
Split Flow Ratio= 0.02
Log Output Level= 0
Friction Slope Method= 1
Unsteady Friction Slope Method= 2
Unsteady Bridges Friction Slope Method= 1
Parabolic Critical Depth
Global Vel Dist= 1 , 1 , 1
Global Log Level= 0
CheckData=True
Encroach Param=-1 ,0,0, 0
BEGIN DESCRIPTION:
Multiple Run
END DESCRIPTION:
Computation Interval=1HOUR
Output Interval=1HOUR
Run HTab= 0
Run UNet= 0
Run PostProcess= 0
Run WQNet= 0
UNET Theta= 1
UNET Theta Warmup= 1
UNET ZTol= 0.02
UNET ZSATol= 0.05
UNET MxIter= 20
UNET MaxInSteps= 0
UNET DtIC= 0
UNET DtMin= 0
UNET MaxCRTS= 20
UNET WFStab= 2
UNET SFStab= 1
UNET WFX= 1
UNET SFX= 1
UNET DSS MLevel= 4
UNET DZMax Abort= 100
UNET Convert EG Bridges= 0
UNET Use Existing IB Tables=-1
UNET Froude Reduction=False
UNET Froude Limit= 1
UNET Froude Power= 10
UNET Time Slicing=0,0, 5
UNET Junction Losses=0
Instantaneous Interval=1HOUR
DSS File=dss
Write IC File= 0
Write IC File at Sim End=0
Echo Input=False
Echo Parameters=False
Echo Output=False
Write Detailed= 0
WQ AD Non Conservative
WQ ULTIMATE=-1
WQ Max Comp Step=1HOUR
WQ Output Interval=15MIN
WQ Output Selected Increments= 0
WQ Output face flow=0
WQ Output face velocity=0
WQ Output face area=0
WQ Output face dispersion=0
WQ Output cell volume=0
WQ Output cell surface area=0
WQ Output cell continuity=0
WQ Output cumulative cell continuity=0
WQ Output face conc=0
WQ Output face dconc_dx=0
WQ Output face courant=0
WQ Output face peclet=0
WQ Output face adv mass=0
WQ Output face disp mass=0
WQ Output cell mass=0
WQ Output cell source sink temp=0
WQ Output cell source sink nsm=0
WQ Output MaxMinRange=-1
WQ Daily Max Min Mean=-1
WQ Daily Range=0
WQ Daily Time=0
WQ Create Restart=0
WQ Fixed Restart=0
WQ System Summary=0
WQ Use Fixed Temperature=0
Sorting and Armoring Iterations= 10
XS Update Threshold= 0.02
Hydraulics Update Threshold= 0.02
Energy Slope Method= 1
Volume Change Method= 0
XS Weighting Method= 0
Number of US Weighted Cross Sections= 1
Number of DS Weighted Cross Sections= 1
Upstream XS Weight=0.25
Main XS Weight=0.5
Downstream XS Weight=0.25
Number of DS XS's Weighted with US Boundary= 1
Upstream Boundary Weight= 1
Weight of XSs Associated with US Boundary= 0
Number of US XS's Weighted with DS Boundary= 1
Downstream Boundary Weight= 0.5
Weight of XSs Associated with DS Boundary= 0.5
Sediment Output Level= 4
Mass or Volume Output= 0
Output Increment Type= 1
Profile and TS Output Increment= 10
XS Output Flag= 0
XS Output Increment= 10
Disregard all LS=0
Disregard all Conn=0
Disregard all Breaches=0
Disregard all Pumps=0

--- BEAVER CREEK.f01 (steady flow) ---

Flow Title=Multiple
Program Version=4.10
Number of Profiles= 7
Profile Names=10-year,25-year,50-year,1pct_min,100-year,1pct_plu,500-year
River Rch & RM=BEAVER CREEK,Reach-1         ,84360
     838    1175    1463    1340    1812    2451    2791
River Rch & RM=BEAVER CREEK,Reach-1         ,81706
     916    1286    1603    1469    1986    2686    3061
River Rch & RM=BEAVER CREEK,Reach-1         ,77913
    1341    1924    2433    2259    3055    4132    4838
River Rch & RM=BEAVER CREEK,Reach-1         ,77279
    1447    2076    2625    2435    3293    4453    5205
River Rch & RM=BEAVER CREEK,Reach-1         ,73879
    3184    4724    6111    5786    7824   10581   12890
River Rch & RM=BEAVER CREEK,Reach-1         ,72522
    3184    4724    6111    5786    7824   10581   12890
River Rch & RM=BEAVER CREEK,Reach-1         ,71600
    3356    4986    6454    6113    8267   11180   13633
River Rch & RM=BEAVER CREEK,Reach-1         ,70617
    3356    4986    6454    6113    8267   11180   13633
River Rch & RM=BEAVER CREEK,Reach-1         ,69071
    3399    5045    6525    6175    8351   11294   13748
River Rch & RM=BEAVER CREEK,Reach-1         ,66932
    3507    5201    6725    6361    8603   11634   14146
River Rch & RM=BEAVER CREEK,Reach-1         ,66845
    3507    5201    6725    6361    8603   11634   14146
River Rch & RM=BEAVER CREEK,Reach-1         ,63713
    3570    5285    6825    6445    8716   11787   14285
River Rch & RM=BEAVER CREEK,Reach-1         ,58657
    3648    5403    6979    6591    8914   12055   14615
River Rch & RM=BEAVER CREEK,Reach-1         ,57600
    4347    6472    8389    7948   10749   14537   17733
River Rch & RM=BEAVER CREEK,Reach-1         ,55177
    4352    6471    8380    7931   10726   14506   17659
River Rch & RM=BEAVER CREEK,Reach-1         ,50528
    4391    6513    8420    7955   10758   14549   17645
River Rch & RM=BEAVER CREEK,Reach-1         ,45971
    6580    9881   12884   12266   16589   22434   27622
River Rch & RM=BEAVER CREEK,Reach-1         ,41132
    6559    9834   12808   12179   16471   22275   27361
River Rch & RM=BEAVER CREEK,Reach-1         ,38972
    6485    9707   12629   11995   16221   21938   26883
River Rch & RM=BEAVER CREEK,Reach-1         ,38607
    6984   10459   13612   12930   17486   23648   28985
River Rch & RM=BEAVER CREEK,Reach-1         ,34911
    7357   11030   14365   13655   18467   24974   30649
River Rch & RM=BEAVER CREEK,Reach-1         ,31791
    7357   11030   14365   13655   18467   24974   30649
River Rch & RM=BEAVER CREEK,Reach-1         ,30954
    8058   12108   15797   15039   20338   27505   33854
River Rch & RM=BEAVER CREEK,Reach-1         ,30496
    8081   12135   15824   15057   20363   27539   33860
River Rch & RM=BEAVER CREEK,Reach-1         ,28408
    8030   12043   15691   14917   20173   27282   33485
River Rch & RM=BEAVER CREEK,Reach-1         ,27105
    8106   12158   15841   15059   20365   27542   33801
River Rch & RM=BEAVER CREEK,Reach-1         ,25683
    8106   12158   15841   15059   20365   27542   33801
River Rch & RM=BEAVER CREEK,Reach-1         ,25303
    8217   12316   16040   15241   20611   27875   34176
River Rch & RM=BEAVER CREEK,Reach-1         ,22971
    8253   12366   16100   15293   20683   27971   34273
River Rch & RM=BEAVER CREEK,Reach-1         ,20890
    8201   12274   15968   15155   20496   27719   33907
River Rch & RM=BEAVER CREEK,Reach-1         ,17511
    8332   12464   16210   15380   20800   28129   34384
River Rch & RM=BEAVER CREEK,Reach-1         ,14231
    8393   12550   16319   15479   20933   28310   34585
River Rch & RM=BEAVER CREEK,Reach-1         ,12090
    8350   12470   16200   15350   20760   28075   34230
River Rch & RM=BEAVER CREEK,Reach-1         ,8402
    8430   12590   16355   15497   20958   28344   34557
River Rch & RM=BEAVER CREEK,Reach-1         ,7709
    8430   12590   16355   15497   20958   28344   34557
River Rch & RM=BEAVER CREEK,Reach-1         ,7075
    8382   12505   16232   15369   20784   28108   34215
River Rch & RM=BEAVER CREEK,Reach-1         ,3703
    8282   12336   15995   15127   20457   27666   33598
Boundary for River Rch & Prof#=BEAVER CREEK,Reach-1         , 1
Up Type= 0
Dn Type= 3
Dn Slope=0.00046
Boundary for River Rch & Prof#=BEAVER CREEK,Reach-1         , 2
Up Type= 0
Dn Type= 3
Dn Slope=0.00046
Boundary for River Rch & Prof#=BEAVER CREEK,Reach-1         , 3
Up Type= 0
Dn Type= 3
Dn Slope=0.00046
Boundary for River Rch & Prof#=BEAVER CREEK,Reach-1         , 4
Up Type= 0
Dn Type= 3
Dn Slope=0.00046
Boundary for River Rch & Prof#=BEAVER CREEK,Reach-1         , 5
Up Type= 0
Dn Type= 3
Dn Slope=0.00046
Boundary for River Rch & Prof#=BEAVER CREEK,Reach-1         , 6
Up Type= 0
Dn Type= 3
Dn Slope=0.00046
Boundary for River Rch & Prof#=BEAVER CREEK,Reach-1         , 7
Up Type= 0
Dn Type= 3
Dn Slope=0.00046
DSS Import GetInterval= 0
DSS Import GetPeak= 0
DSS Import FillOption= 0

--- BEAVER CREEK.g01 (geometry) ---

Geom Title=Existing Conditions
Program Version=4.10

River Reach=BEAVER CREEK    ,Reach-1
Reach XY= 30
      3731207.39      10706960.9       3728219.5       10703440.
        3726879.       10702934.      3725319.25       10699757.
      3721744.25       10696304.       3721498.5       10695028.
       3717019.5       10691700.      3716612.25       10690715.
        3712259.       10689311.        3709041.       10690091.
      3708198.75       10689291.      3706249.25       10689786.
      3704443.25       10685289.        3702853.       10684034.
      3702481.75       10682914.      3698084.25       10678031.
      3695446.75       10677766.       3690962.5       10675170.
      3690589.25       10673861.      3689135.25       10672953.
        3688819.       10671811.      3687650.25       10671704.
       3686522.5       10670844.        3686212.       10669844.
        3683872.       10667445.      3681123.25       10667033.
        3680896.       10666348.      3679449.75       10665850.
       3678975.5       10667647.        3678102.       10668182.

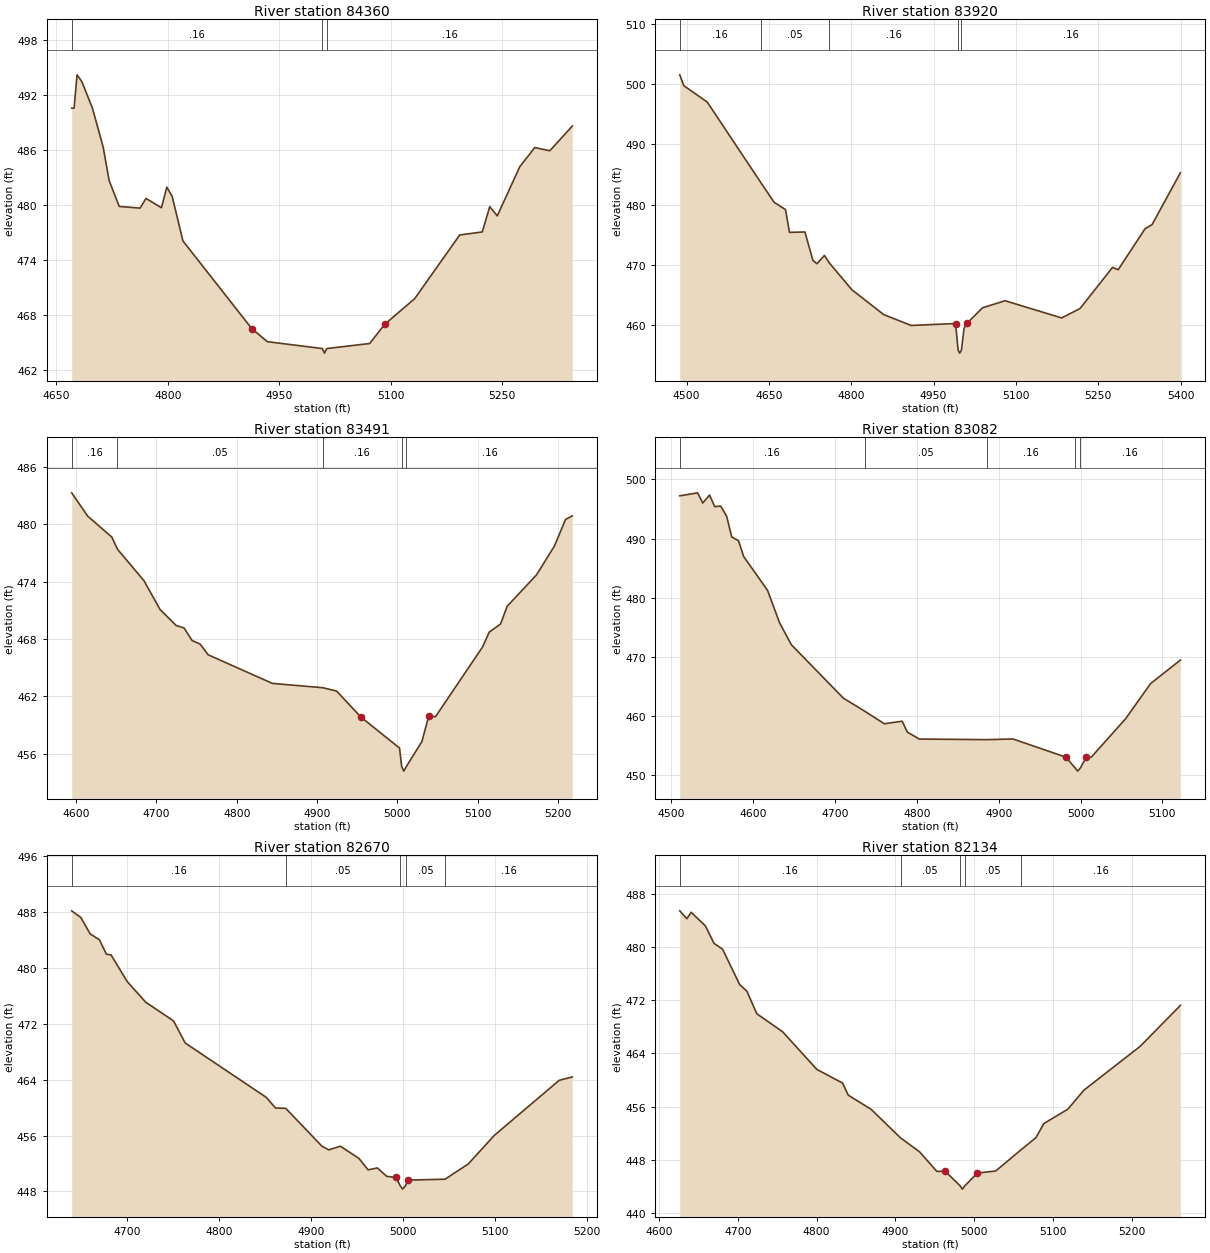
Type RM Length L Ch R = 1 ,84360   ,440,440,440
BEGIN DESCRIPTION:
BEAVER CREEK 139.0
END DESCRIPTION:
XS GIS Cut Line= 3
       3731099.6      10706610.2      3730849.61     10706810.19
      3730799.61      10707160.2
#Sta/Elev= 30
  4670.8  490.59    4674  490.59    4678  494.23  4684.4   493.5  4698.8  490.57
  4713.2  486.33  4721.2  482.69  4734.8  479.86  4762.8  479.68  4770.8  480.74
  4791.6  479.72  4798.8  481.97    4806  480.96  4820.5   476.1  4913.3  466.51
  4934.1   465.1  5008.1  464.35  5010.9  463.85  5014.1  464.35  5071.8   464.9
    5092  466.99  5132.4   469.8    5193  476.75  5223.3  477.08  5233.4  479.84
  5243.5  478.83  5273.8   484.2    5294  486.29  5314.2  485.94  5344.5  488.64
#Mann= 3 ,-1 , 0
  4670.8     .16       0  5008.1     .07       0  5014.1     .16       0
Bank Sta=4913.3,5092
XS Rating Curve= 0 ,0
Exp/Cntr=0.3,0.1

Type RM Length L Ch R = 1 ,83920   ,429,429,429
BEGIN DESCRIPTION:
BEAVER CREEK 138.0
END DESCRIPTION:
XS GIS Cut Line= 3
      3730999.63     10706210.17      3730599.61     10706510.19
      3730199.64      10706410.2
#Sta/Elev= 30
  4487.4  501.58  4494.7  499.78  4537.4  497.06  4635.1  483.67  4659.3   480.4
  4680.1  479.18  4687.4  475.39  4715.5  475.46  4730.1  470.72  4737.4  470.18
    4751  471.56    4760  470.31    4801  465.86  4859.3  461.71  4909.3  459.92
    4990  460.24  4994.7  455.82  4997.5  455.32  5000.7  455.82  5005.5  459.46
  5010.6  460.26    5039  462.85  5080.2  464.03  5183.3  461.17  5216.8  462.73
    5276  469.57  5286.3  469.18  5335.3  475.99  5348.2   476.7  5399.7   485.3
#Mann= 5 ,-1 , 0
  4487.4     .16       0  4635.1     .05       0    4760     .16       0
  4994.7     .07       0  5000.7     .16       0
Bank Sta=4990,5010.6
XS Rating Curve= 0 ,0
Exp/Cntr=0.3,0.1

Type RM Length L Ch R = 1 ,83491   ,409,409,409
BEGIN DESCRIPTION:
BEAVER CREEK 137.0
END DESCRIPTION:
XS GIS Cut Line= 3
      3730849.61     10706160.19      3730449.61     10706160.19
      3730249.61     10706260.19
#Sta/Elev= 30
  4594.4  483.28  4614.4  480.84  4644.4  478.65  4651.4  477.39  4684.4   474.1
  4704.4  471.09  4724.4  469.42  4734.4  469.15  4744.4  467.84  4754.4  467.47
  4764.4  466.35  4844.4  463.36  4907.1  462.91  4924.4  462.56  4954.4  459.86
  5002.8   456.6  5005.4  454.69  5008.1  454.19  5011.4  454.69  5030.7  457.29
  5039.1  459.95  5047.5  459.87  5106.2  467.17  5114.6  468.73  5128.6  469.57
  5136.9  471.43  5173.3  474.69  5195.6   477.7  5209.6   480.5    5218  480.87
#Mann= 5 ,-1 , 0
  4594.4     .16       0  4651.4     .05       0  4907.1     .16       0
  5005.4     .07       0  5011.4     .16       0
Bank Sta=4954.4,5039.1
XS Rating Curve= 0 ,0
Exp/Cntr=0.3,0.1

Type RM Length L Ch R = 1 ,83082   ,412,412,412
BEGIN DESCRIPTION:
BEAVER CREEK 136.0
END DESCRIPTION:
XS GIS Cut Line= 3
      3730549.59     10705410.21      3730249.61     10705810.19
      3730149.59      10705860.2
#Sta/Elev= 30
  4510.2  497.23    4532  497.74  4538.3  496.01  4546.6  497.37  4552.9  495.41
  4560.2   495.5  4567.5  493.78  4573.7  490.28    4582  489.63  4588.3  486.96
  4617.5  481.23    4632  475.79  4646.6  472.02  4710.2  462.98  4736.4  460.76
  4760.2  458.65    4782  459.08  4788.3  457.24  4802.9  456.06  4885.6  455.96
  4917.5  456.07    4982     453  4993.6  451.13  4996.4  450.63  4999.6  451.13
    5007  452.98    5013  452.98  5054.9  459.47  5085.6  465.45    5122  469.43
#Mann= 5 ,-1 , 0
  4510.2     .16       0  4736.4     .05       0  4885.6     .16       0
  4993.6     .07       0  4999.6     .16       0
Bank Sta=4982,5007
XS Rating Curve= 0 ,0
Exp/Cntr=0.3,0.1

Type RM Length L Ch R = 1 ,82670   ,536,536,536
BEGIN DESCRIPTION:
BEAVER CREEK 135.0
END DESCRIPTION:
XS GIS Cut Line= 3
      3730499.56     10705410.19      3730099.61     10705460.19
       3729999.6      10705560.2
#Sta/Elev= 30
  4639.7  488.14  4649.7  487.18  4659.8  484.84  4669.9     484  4677.4  481.94
  4682.5  481.83  4700.1  478.02  4720.3  475.06  4750.5  472.39  4763.1  469.24
  4851.3  461.46  4861.4  459.93  4872.5  459.89  4911.8  454.48  4919.3  453.95
  4931.9  454.47  4952.1  452.73  4962.1  451.09  4972.2  451.36  4982.3  450.16
  4992.4     450  4996.9  448.83  4999.7  448.33  5002.9  448.83    5005  449.62
  5045.8  449.75    5071  451.93  5099.3  456.01    5170   463.9  5184.2  464.38
#Mann= 5 ,-1 , 0
  4639.7     .16       0  4872.5     .05       0  4996.9     .04       0
  5002.9     .05       0  5045.8     .16       0
Bank Sta=4992.4,5005
XS Rating Curve= 0 ,0
Exp/Cntr=0.3,0.1

Type RM Length L Ch R = 1 ,82134   ,428,428,428
BEGIN DESCRIPTION:
BEAVER CREEK 134.0
END DESCRIPTION:
XS GIS Cut Line= 3
       3729899.6     10704760.21      3729749.61     10705110.19
      3729699.61     10705360.17
#Sta/Elev= 30
  4626.3  485.41  4635.3  484.22  4640.8  485.19  4658.9  483.14  4669.8  480.53
  4680.7  479.65  4702.4  474.33  4711.5  473.35  4724.2  469.95  4756.8  467.27
  4800.4   461.6    4833  459.56  4840.2  457.74  4869.3  455.61  4906.6  451.33
  4930.9  449.22  4952.7   446.3  4963.5   446.3  4982.3  444.13  4985.1  443.63
  4988.3  444.13  5004.3  446.05  5027.5  446.35  5059.3   449.5  5078.5  451.35
  5088.7  453.48  5119.2  455.64  5139.6   458.5    5211  465.07    5262  471.21
#Mann= 5 ,-1 , 0
  4626.3     .16       0  4906.6     .05       0  4982.3     .04       0
  4988.3     .05       0  5059.3     .16       0
Bank Sta=4963.5,5004.3
XS Rating Curve= 0 ,0
Exp/Cntr=0.3,0.1

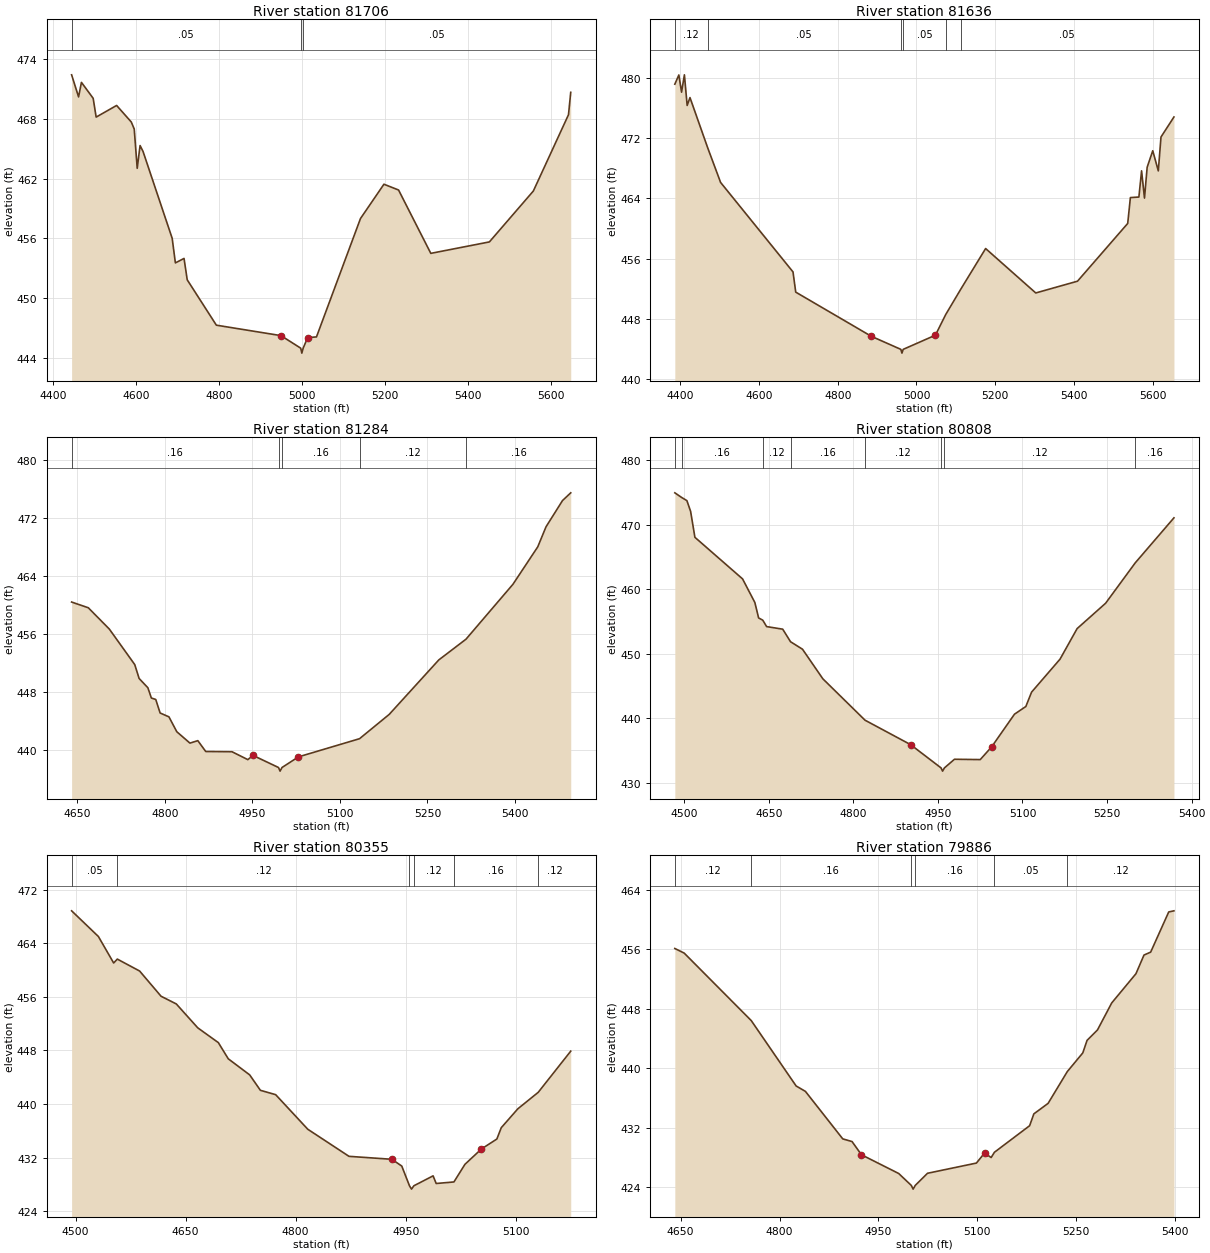
Type RM Length L Ch R = 1 ,81706   ,70,70,70
BEGIN DESCRIPTION:
BEAVER CREEK 133.0
END DESCRIPTION:
XS GIS Cut Line= 4
      3729775.41     10704582.34      3729623.48     10704727.76
      3729278.43     10705020.73      3728893.34     10705401.48
#Sta/Elev= 30
  4443.8  472.45  4460.6  470.23  4467.5  471.69  4495.8  470.09    4503   468.2
  4552.4  469.37  4587.9   467.7  4594.9     467  4602.1  463.05    4609  465.34
  4616.2  464.74  4686.5  456.01  4694.2  453.54  4715.1  453.99  4722.8  451.84
  4793.1  447.28    4949  446.23  4996.6  444.97  4999.4  444.47  5002.6  444.97
  5013.4  446.03  5034.7   446.1  5140.9     458  5197.5  461.45  5232.8  460.87
  5310.6   454.5    5452  455.65  5558.1  460.77  5642.9  468.44  5648.3  470.69
#Mann= 3 ,-1 , 0
  4443.8     .05       0  4996.6     .04       0  5002.6     .05       0
Bank Sta=4949,5013.4
XS Rating Curve= 0 ,0
Exp/Cntr=0.3,0.1

Type RM Length L Ch R = 1 ,81636   ,352,352,352
BEGIN DESCRIPTION:
Mapping XS c25f8cee
END DESCRIPTION:
XS GIS Cut Line= 5
      3729749.31     10704495.59      3729402.12     10704831.92
      3729226.34     10704975.15      3728985.46     10705213.87
      3728837.86     10705374.49
#Sta/Elev= 30
  4386.4  479.13  4396.6  480.35  4403.5  478.07  4410.7  480.37  4417.7  476.31
  4424.9  477.35  4469.8   470.7  4502.6   466.1  4686.5  454.23  4693.4  451.55
  4885.1   445.7  4960.3  443.96  4963.1  443.46  4966.3  443.96  5048.1  445.84
  5074.3  448.58  5111.8  451.88  5175.6  457.33  5302.9  451.44  5408.9     453
  5536.4  460.66  5543.2  464.09  5564.8  464.16  5571.6  467.64    5579  464.02
  5585.8  468.12    5600   470.3  5614.1  467.63  5620.9  472.12  5653.8  474.78
#Mann= 6 ,-1 , 0
  4386.4     .12       0  4469.8     .05       0  4960.3     .04       0
  4966.3     .05       0  5074.3     .16       0  5111.8     .05       0
Bank Sta=4885.1,5048.1
XS Rating Curve= 0 ,0
Exp/Cntr=0.3,0.1

Type RM Length L Ch R = 1 ,81284   ,476,476,476
BEGIN DESCRIPTION:
BEAVER CREEK 132.0
END DESCRIPTION:
XS GIS Cut Line= 3
      3729249.61     10704410.18      3729049.61     10704710.19
      3728699.63     10705060.16
#Sta/Elev= 30
  4640.2  460.44  4668.8  459.65  4704.8  456.71  4748.4   451.8  4755.9  449.88
  4770.9   448.6  4776.9  447.18  4784.4  446.98  4791.9  445.11    4807  444.58
  4820.5  442.52    4843  440.95  4856.5  441.29  4870.1  439.79  4915.1  439.76
  4942.2  438.67  4951.2  439.25  4994.8  437.58  4997.5  437.08  5000.8  437.58
    5029  439.05  5133.7  441.56  5184.6  444.92  5269.5  452.44  5316.2  455.31
  5396.7   462.9  5439.2  468.07  5453.3  470.83  5481.6  474.46  5495.7  475.53
#Mann= 5 ,-1 , 0
  4640.2     .16       0  4994.8     .07       0  5000.8     .16       0
  5133.7     .12       0  5316.2     .16       0
Bank Sta=4951.2,5029
XS Rating Curve= 0 ,0
Exp/Cntr=0.3,0.1

Type RM Length L Ch R = 1 ,80808   ,453,453,453
BEGIN DESCRIPTION:
BEAVER CREEK 131.0
END DESCRIPTION:
XS GIS Cut Line= 3
      3729149.63     10704010.17      3728749.61     10704360.19
       3728399.6     10704410.19
#Sta/Elev= 30
  4483.5  474.96  4496.1  474.21  4504.9  473.75  4511.5  472.08  4519.1  468.06
  4603.6  461.61  4625.4  457.95  4632.1  455.55  4639.4  455.21  4646.3  454.21
  4674.8  453.81  4688.7  451.86  4709.9   450.7    4746  446.11  4820.8  439.69
  4901.6   435.9  4955.6  432.29  4958.3  431.79  4961.6  432.29  4979.4  433.63
  5025.1  433.58  5045.3  435.55  5085.8  440.62    5106  441.82  5116.1  444.04
  5166.6  449.16  5196.9   453.9  5247.4  457.83    5300   464.1  5368.6  471.08
#Mann= 8 ,-1 , 0
  4483.5     .05       0  4496.1     .16       0  4639.4     .12       0
  4688.7     .16       0  4820.8     .12       0  4955.6     .07       0
  4961.6     .12       0    5300     .16       0
Bank Sta=4901.6,5045.3
XS Rating Curve= 0 ,0
Exp/Cntr=0.3,0.1

Type RM Length L Ch R = 1 ,80355   ,469,469,469
BEGIN DESCRIPTION:
BEAVER CREEK 130.0
END DESCRIPTION:
XS GIS Cut Line= 3
      3728899.61     10703710.19      3728499.61     10704010.19
       3728399.6     10704160.21
#Sta/Elev= 30
  4494.7  468.82  4531.2  464.99    4552  461.04    4557  461.62  4587.4  459.84
  4616.6  456.08  4637.4  454.93  4666.6  451.37  4694.7  449.16  4708.2  446.75
  4737.4  444.35    4752  442.05  4772.8   441.4  4816.6  436.24  4872.8   432.2
  4931.2  431.76  4944.7  430.75  4955.2  427.81    4958  427.31  4961.2  427.81
  4987.4  429.29  4991.6  428.15  5015.8  428.38  5030.8  431.01  5053.3   433.3
  5074.3  434.78  5080.3  436.47  5102.9  439.29  5130.7  441.75    5175  447.89
#Mann= 6 ,-1 , 0
  4494.7     .05       0    4557     .12       0  4955.2     .07       0
  4961.2     .12       0  5015.8     .16       0  5130.7     .12       0
Bank Sta=4931.2,5053.3
XS Rating Curve= 0 ,0
Exp/Cntr=0.3,0.1

Type RM Length L Ch R = 1 ,79886   ,456,456,456
BEGIN DESCRIPTION:
BEAVER CREEK 129.0
END DESCRIPTION:
XS GIS Cut Line= 3
      3728549.63     10703360.17      3728299.61     10703610.19
      3728099.61     10703960.19
#Sta/Elev= 30
  4641.3  456.08  4655.5  455.46  4757.2  446.39  4825.2  437.61  4839.3  436.88
  4895.9   430.5    4910  430.14  4924.2  428.37  4980.7  425.85  4999.8  424.25
  5002.6  423.75  5005.8  424.25  5024.4  425.88  5098.5  427.25  5110.8  428.59
  5120.9     428  5125.8   428.7  5179.2  432.27  5185.6  433.86  5207.2  435.27
  5236.3  439.54  5259.8  442.05  5266.3  443.74  5282.1  445.14  5303.7  448.77
  5340.4  452.69  5352.6   455.2  5362.7  455.59  5390.1  460.99    5398  461.14
#Mann= 6 ,-1 , 0
  4641.3     .12       0  4757.2     .16       0  4999.8     .07       0
  5005.8     .16       0  5125.8     .05       0  5236.3     .12       0
Bank Sta=4924.2,5110.8
XS Rating Curve= 0 ,0
Exp/Cntr=0.3,0.1

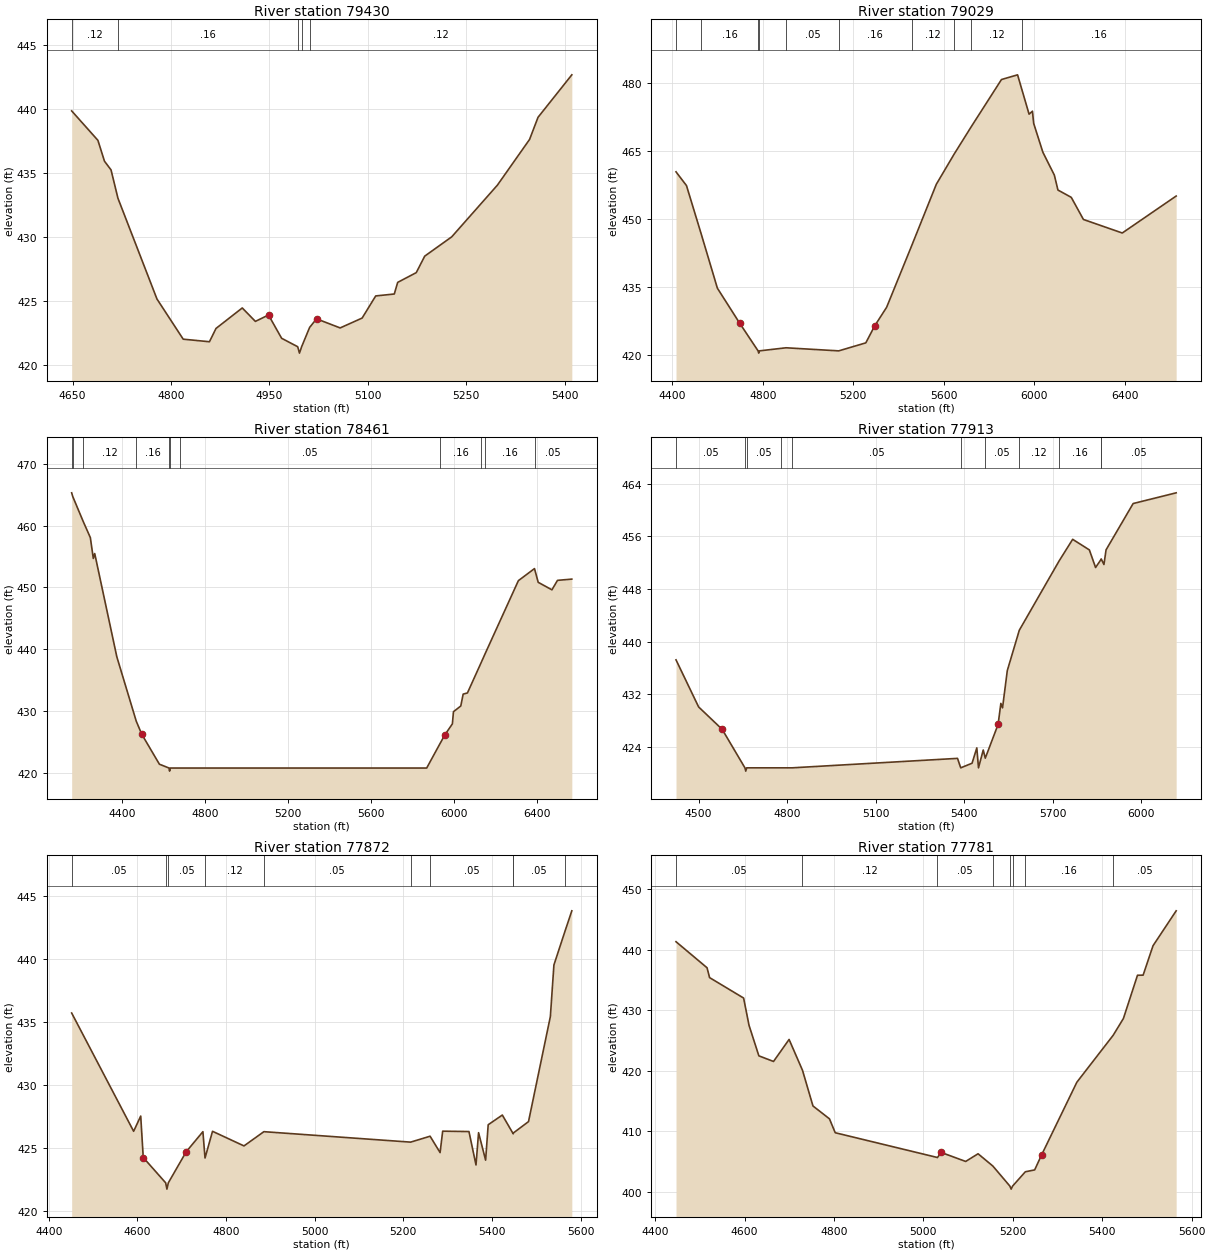
Type RM Length L Ch R = 1 ,79430   ,401,401,401
BEGIN DESCRIPTION:
BEAVER CREEK 128.0
END DESCRIPTION:
XS GIS Cut Line= 3
      3727999.61     10702960.21      3727999.61     10703310.19
      3727899.61      10703710.2
#Sta/Elev= 30
  4648.7  439.86  4688.7  437.56  4698.7  435.93  4708.7  435.25  4719.2  433.04
  4778.7  425.16  4818.7  422.02  4858.7  421.82  4868.7  422.86  4908.7  424.46
  4928.7  423.41  4948.7  423.91  4968.7  422.09  4993.2  421.43  4995.9  420.93
  4999.2  421.43  5011.4  422.94  5021.9  423.61  5057.9   422.9  5091.4  423.67
  5112.1   425.4  5140.4  425.55  5145.6  426.46  5173.9  427.22  5186.8  428.51
    5228  430.02  5297.6  434.06  5346.6  437.63  5359.5  439.36    5411  442.68
#Mann= 5 ,-1 , 0
  4648.7     .12       0  4719.2     .16       0  4993.2     .07       0
  4999.2     .16       0  5011.4     .12       0
Bank Sta=4948.7,5021.9
XS Rating Curve= 0 ,0
Exp/Cntr=0.3,0.1

Type RM Length L Ch R = 1 ,79029   ,568,568,568
BEGIN DESCRIPTION:
Mapping XS 9d8586aa
END DESCRIPTION:
XS GIS Cut Line= 3
      3727827.94     10702620.64      3727459.89     10703828.94
      3727626.56     10704759.52
#Sta/Elev= 30
  4417.2  460.39  4463.4  457.35  4527.9  446.75  4599.9  434.67  4698.5  426.92
  4779.6  420.82  4782.4  420.32  4785.6  420.82    4903   421.5  5135.7  420.82
  5255.3  422.59  5294.8  426.37  5347.1  430.44  5457.3     444  5566.6  457.64
  5646.2  464.38  5721.1  470.38  5854.3  480.79  5925.4  481.83  5943.4  478.75
  5976.2  473.13  5991.1  473.79  5996.5   471.1  6037.1  464.73  6087.9  459.65
  6103.6  456.37  6162.5  454.75  6216.2  449.86  6387.7  446.87  6625.7  455.04
#Mann= 10 ,-1 , 0
  4417.2     .12       0  4527.9     .16       0  4779.6    .033       0
  4785.6     .16       0    4903     .05       0  5135.7     .16       0
  5457.3     .12       0  5646.2     .16       0  5721.1     .12       0
  5943.4     .16       0
Bank Sta=4698.5,5294.8
XS Rating Curve= 0 ,0
Exp/Cntr=0.3,0.1

Type RM Length L Ch R = 1 ,78461   ,548,548,548
BEGIN DESCRIPTION:
Mapping XS 70969a17
END DESCRIPTION:
XS GIS Cut Line= 3
      3727730.74     10702453.92      3726966.84     10703162.27
      3726620.06     10704486.95
#Sta/Elev= 30
  4155.6  465.28  4160.7  464.69  4211.9   460.6  4245.7  458.04  4259.9  454.68
  4266.7  455.47  4373.3  438.79  4466.8   428.4  4493.5  426.28  4578.5  421.44
  4624.9  420.82  4627.6  420.32  4630.9  420.82  4677.4  420.82  5867.1  420.82
  5931.7  424.79  5955.7  426.23    5991  427.96  5996.1  429.92  6031.4  430.84
  6042.9  432.76  6063.5  432.95  6129.2  437.82  6149.2  439.32  6309.1  451.09
  6386.8  453.04  6404.7  450.82  6470.8  449.61  6497.7  451.14  6566.7  451.34
#Mann= 11 ,-1 , 0
  4155.6     .12       0  4160.7     .16       0  4211.9     .12       0
  4466.8     .16       0  4624.9    .033       0  4630.9     .16       0
  4677.4     .05       0  5931.7     .16       0  6129.2     .05       0
  6149.2     .16       0  6386.8     .05       0
Bank Sta=4493.5,5955.7
XS Rating Curve= 0 ,0
Exp/Cntr=0.3,0.1

Type RM Length L Ch R = 1 ,77913   ,41,41,41
BEGIN DESCRIPTION:
BEAVER CREEK 125.0
END DESCRIPTION:
XS GIS Cut Line= 3
      3727226.81     10702404.03      3726177.36     10702979.54
      3725818.55     10703325.32
#Sta/Elev= 30
  4423.8  437.24  4500.4  430.08  4580.3  426.67  4657.4  420.82  4660.1  420.32
  4663.4  420.82  4780.2  420.82  4817.3  420.82  5377.9  422.26  5388.8  420.82
  5427.2  421.52  5443.3  423.85    5449  420.82  5465.1  423.53    5472  422.29
  5515.5  427.43  5524.8  430.62  5530.5  429.94  5546.6   435.6  5587.3  441.74
  5722.1  452.27  5768.2  455.57  5824.8  453.96  5845.9  451.28  5862.9  452.41
  5864.9  452.59  5874.2  451.74  5881.4  453.97  5973.2  461.01    6119  462.64
#Mann= 11 ,-1 , 0
  4423.8     .05       0  4657.4    .033       0  4663.4     .05       0
  4780.2     .12       0  4817.3     .05       0  5388.8      .1       0
    5472     .05       0  5587.3     .12       0  5722.1     .16       0
  5862.9     .12       0  5864.9     .05       0
Bank Sta=4580.3,5515.5
XS Rating Curve= 0 ,0
Exp/Cntr=0.3,0.1

Type RM Length L Ch R = 1 ,77872   ,91,91,91
BEGIN DESCRIPTION:
Mapping XS 8096dad9
END DESCRIPTION:
XS GIS Cut Line= 2
      3727178.68     10702377.96      3726194.41     10702929.99
#Sta/Elev= 30
  4451.7  435.71  4591.5  426.32  4607.5  427.53  4613.2  424.24  4663.8  422.23
  4666.6  421.73  4669.8  422.23  4710.2   424.7  4747.8  426.29  4752.6   424.2
  4769.5  426.32  4840.5  425.16  4885.4  426.29  5216.5  425.46  5260.4  425.93
    5283  424.63  5288.8  426.33  5348.1   426.3    5364  423.65  5369.8  426.21
  5385.7  424.03  5391.5  426.84  5423.4  427.61    5448  426.12  5448.4  426.19
  5482.5  427.09  5531.8  435.43  5539.8  439.52  5564.4  442.16  5580.2  443.82
#Mann= 10 ,-1 , 0
  4451.7     .05       0  4663.8     .03       0  4669.8     .05       0
  4752.6     .12       0  4885.4     .05       0  5216.5     .16       0
  5260.4     .05       0    5448      .1       0  5448.4     .05       0
  5564.4     .16       0
Bank Sta=4613.2,4710.2
XS Rating Curve= 0 ,0
Exp/Cntr=0.3,0.1

Type RM Length L Ch R = 1 ,77781   ,502,502,502
BEGIN DESCRIPTION:
BEAVER CREEK 124.0
END DESCRIPTION:
XS GIS Cut Line= 2
       3727143.5     10702311.57      3726152.98     10702831.53
#Sta/Elev= 30
  4446.7  441.33  4516.1  437.02  4521.8  435.39  4597.9  432.01    4610   427.5
    4632  422.45  4664.8  421.52  4699.6  425.16  4729.6  420.06    4753  414.16
  4789.9  412.03  4802.8  409.73  5031.5  405.63  5039.7  406.47  5094.6  404.98
  5122.3  406.25  5155.5  404.21  5193.5   400.9  5196.3   400.4  5199.5   400.9
    5228  403.27  5248.9  403.58  5264.3  406.04  5343.3  418.09  5424.5  425.85
  5447.4  428.63  5478.9  435.78  5491.5   435.8  5513.6  440.66  5565.4  446.44
#Mann= 8 ,-1 , 0
  4446.7     .05       0  4729.6     .12       0  5031.5     .05       0
  5155.5     .12       0  5193.5     .07       0  5199.5     .12       0
    5228     .16       0  5424.5     .05       0
Bank Sta=5039.7,5264.3
XS Rating Curve= 0 ,0
Exp/Cntr=0.3,0.1

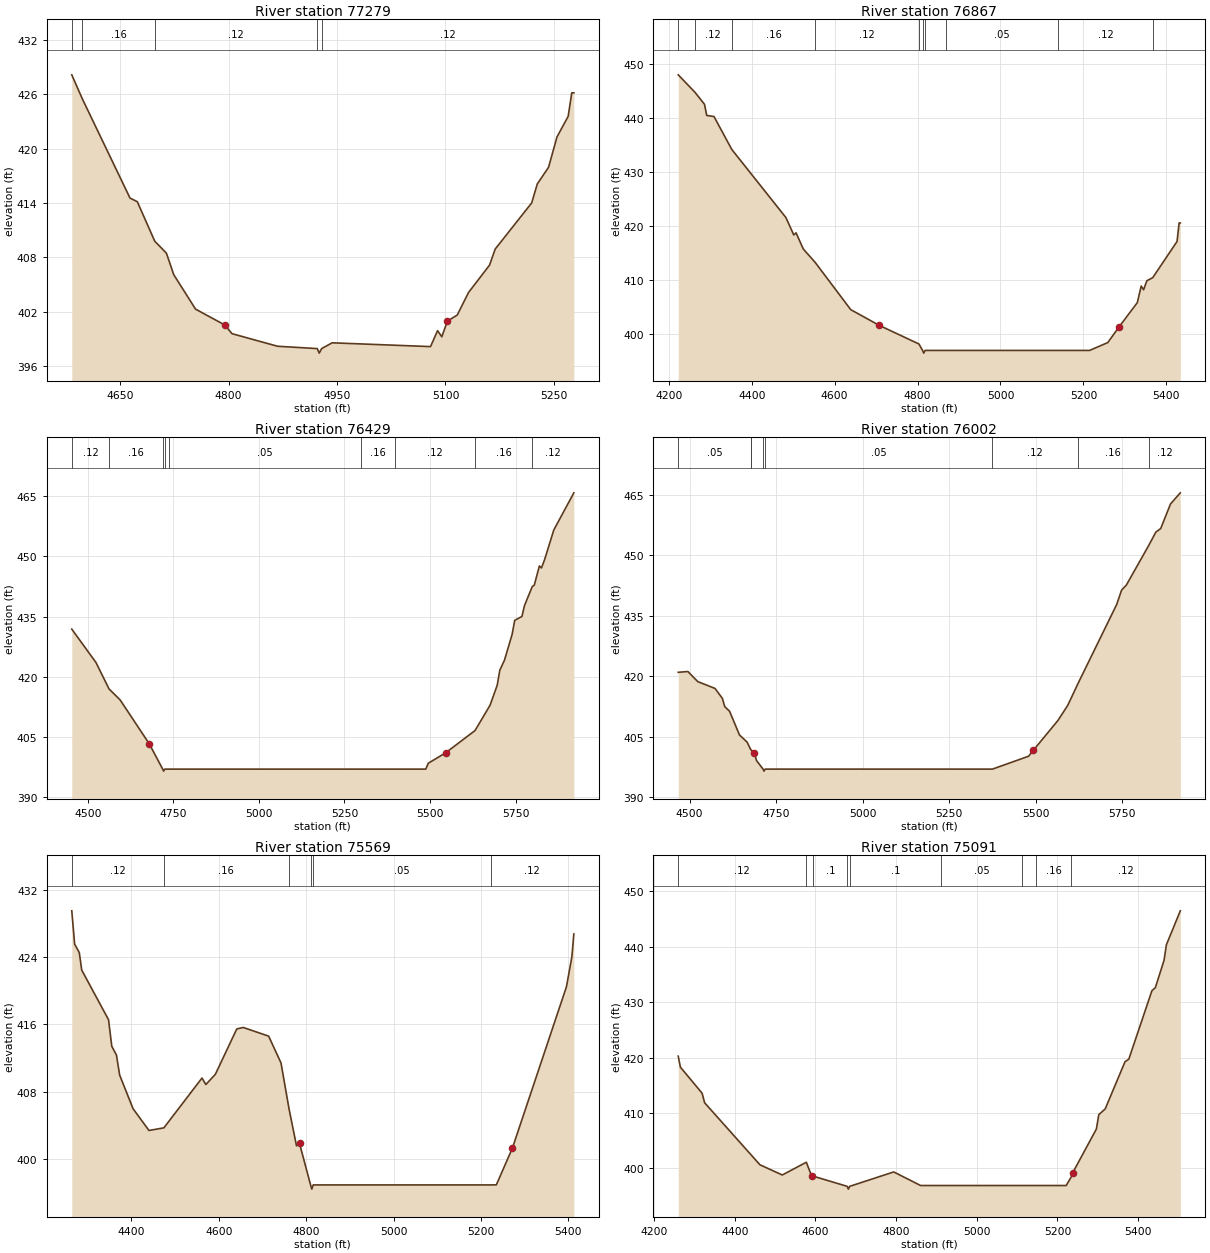
Type RM Length L Ch R = 1 ,77279   ,412,412,412
BEGIN DESCRIPTION:
BEAVER CREEK 123.0
END DESCRIPTION:
XS GIS Cut Line= 3
      3726849.63     10702060.19      3726449.61     10702110.19
       3726199.6      10702260.2
#Sta/Elev= 30
  4582.9  428.17  4597.5  425.52  4663.5  414.55  4673.6  414.15  4697.7  409.79
  4713.9  408.46    4724  406.09  4754.2  402.28  4794.6  400.53  4804.6  399.57
  4867.6  398.18  4922.6  397.92  4925.3  397.42  4928.6  397.92  4943.2  398.56
  5079.3  398.14    5089   399.9  5094.9  399.23  5102.7  400.96  5116.3  401.63
  5131.8  404.11    5161  407.15  5168.7  408.91  5219.3  414.02    5227  416.11
  5242.6  417.95  5254.3  421.31  5269.8  423.59  5274.7  426.18  5277.6  426.18
#Mann= 5 ,-1 , 0
  4582.9     .12       0  4597.5     .16       0  4697.7     .12       0
  4922.6     .07       0  4928.6     .12       0
Bank Sta=4794.6,5102.7
XS Rating Curve= 0 ,0
Exp/Cntr=0.3,0.1

Type RM Length L Ch R = 1 ,76867   ,438,438,438
BEGIN DESCRIPTION:
BEAVER CREEK 122.0
END DESCRIPTION:
XS GIS Cut Line= 3
      3727049.61     10702010.19      3726299.61     10701710.19
       3726099.6      10702060.2
#Sta/Elev= 30
  4222.8  448.04  4262.6  444.85  4286.1  442.58  4291.5  440.51    4309  440.31
    4352  434.19  4482.6  421.55  4501.5  418.33  4506.9  418.73  4524.4  415.73
  4553.2  413.23  4638.8  404.48  4707.5  401.56  4803.2  398.11  4812.2  396.91
  4814.9  396.41  4818.2  396.91  4868.1  396.91  5139.7  396.91  5214.9  396.91
  5258.8  398.37  5286.1  401.29    5330  405.78  5339.4  408.86  5345.1  408.16
  5353.1  409.84  5367.2  410.41  5425.8  417.12  5430.8  420.56  5433.7  420.56
#Mann= 10 ,-1 , 0
  4222.8     .16       0  4262.6     .12       0    4352     .16       0
  4553.2     .12       0  4803.2     .16       0  4812.2    .033       0
  4818.2     .16       0  4868.1     .05       0  5139.7     .12       0
  5367.2     .16       0
Bank Sta=4707.5,5286.1
XS Rating Curve= 0 ,0
Exp/Cntr=0.3,0.1

Type RM Length L Ch R = 1 ,76429   ,427,427,427
BEGIN DESCRIPTION:
BEAVER CREEK 121.0
END DESCRIPTION:
XS GIS Cut Line= 3
      3726499.62     10700960.18      3726099.61     10701360.19
       3725349.6      10701860.2
#Sta/Elev= 30
  4453.1  431.86  4523.8  423.53    4562  416.93  4594.5  414.18  4679.4  403.25
  4718.8  396.91  4721.6  396.41  4724.8  396.91  4736.2  396.91  5298.9  396.91
    5398  396.91  5487.5  396.91    5495  398.39  5546.1  401.01  5631.6  406.55
  5675.3  412.85  5696.3  417.86  5703.9  421.62  5717.4  424.08  5739.9  430.56
  5747.4  434.05  5768.5  435.02    5776  437.74  5798.8   442.5  5804.5  442.82
  5819.5  447.62  5825.5  447.13  5834.6  449.16  5861.6   456.6  5920.2  465.88
#Mann= 9 ,-1 , 0
  4453.1     .12       0    4562     .16       0  4718.8    .033       0
  4724.8     .16       0  4736.2     .05       0  5298.9     .16       0
    5398     .12       0  5631.6     .16       0  5798.8     .12       0
Bank Sta=4679.4,5546.1
XS Rating Curve= 0 ,0
Exp/Cntr=0.3,0.1

Type RM Length L Ch R = 1 ,76002   ,433,433,433
BEGIN DESCRIPTION:
BEAVER CREEK 120.0
END DESCRIPTION:
XS GIS Cut Line= 3
      3726249.57     10700660.22      3725849.61     10701010.19
      3725199.61     10701660.19
#Sta/Elev= 30
  4467.2  420.96  4495.1  421.15  4523.6  418.65  4573.5  416.95  4594.8  414.47
  4601.5  412.45  4615.7  411.26  4644.2  405.39    4666  403.64  4676.4   401.8
  4676.6  401.78  4686.9   400.9  4693.5  399.03  4712.3  396.91  4715.1  396.41
  4718.3  396.91    5375  396.91  5479.5  400.11  5493.6  401.62  5564.3  408.99
  5592.6  412.74  5622.3  418.17    5734  437.79  5748.2  441.36  5762.3  442.67
    5826  452.37  5847.2  455.78  5861.3  456.67  5889.6  462.78  5917.9  465.54
#Mann= 8 ,-1 , 0
  4467.2     .05       0  4676.4     .16       0  4676.6     .05       0
  4712.3    .033       0  4718.3     .05       0    5375     .12       0
  5622.3     .16       0    5826     .12       0
Bank Sta=4686.9,5493.6
XS Rating Curve= 0 ,0
Exp/Cntr=0.3,0.1

Type RM Length L Ch R = 1 ,75569   ,478,478,478
BEGIN DESCRIPTION:
Mapping XS 6673f89c
END DESCRIPTION:
XS GIS Cut Line= 5
      3726145.83     10700197.36      3725928.79      10700275.5
      3725820.28     10700449.11      3725598.93     10700661.78
      3725203.18     10700756.93
#Sta/Elev= 30
  4263.3  429.48  4269.9  425.52  4280.5  424.52  4286.1  422.44  4347.5  416.54
  4354.9  413.39  4365.6  412.34  4372.9  409.97  4403.6  405.97    4440  403.38
  4474.1  403.69  4561.4  409.61  4570.3  408.84  4592.1  410.06    4641  415.44
  4655.8  415.62    4714  414.59  4742.3  411.41  4760.3  406.06  4777.8  401.55
  4784.7  401.84    4810  396.91  4812.8  396.41    4816  396.91  5222.7  396.91
  5235.3  396.92  5272.1  401.29  5395.8  420.46  5408.2  424.02  5412.7  426.73
#Mann= 6 ,-1 , 0
  4263.3     .12       0  4474.1     .16       0  4760.3     .05       0
    4810    .033       0    4816     .05       0  5222.7     .12       0
Bank Sta=4784.7,5272.1
XS Rating Curve= 0 ,0
Exp/Cntr=0.3,0.1

Type RM Length L Ch R = 1 ,75091   ,31,31,31
BEGIN DESCRIPTION:
Mapping XS e2744cc0
END DESCRIPTION:
XS GIS Cut Line= 4
      3726134.96     10700051.97      3725939.64     10700062.82
      3725440.51     10700203.88      3724978.31     10700464.28
#Sta/Elev= 30
  4259.9  420.24  4265.3  418.26  4319.1  413.56  4325.3  411.84  4462.5  400.65
  4517.9  398.81  4577.5  401.11  4590.6  398.63    4595  398.59  4678.9  396.76
  4681.7  396.26  4684.9  396.76  4794.2  399.36  4860.8  396.91  4912.2  396.91
  5111.7  396.91  5146.4  396.91  5221.7  396.91  5234.4  398.47  5237.6  399.16
  5296.6   407.1  5302.6  409.69  5318.5  410.73  5367.6  419.24    5377   419.7
  5434.3  432.05  5442.8   432.6  5464.4  437.54  5470.2  440.34  5504.7  446.46
#Mann= 9 ,-1 , 0
  4259.9     .12       0  4577.5     .16       0    4595      .1       0
  4678.9     .03       0  4684.9      .1       0  4912.2     .05       0
  5111.7     .12       0  5146.4     .16       0  5234.4     .12       0
Bank Sta=4590.6,5237.6
XS Rating Curve= 0 ,0
Exp/Cntr=0.3,0.1