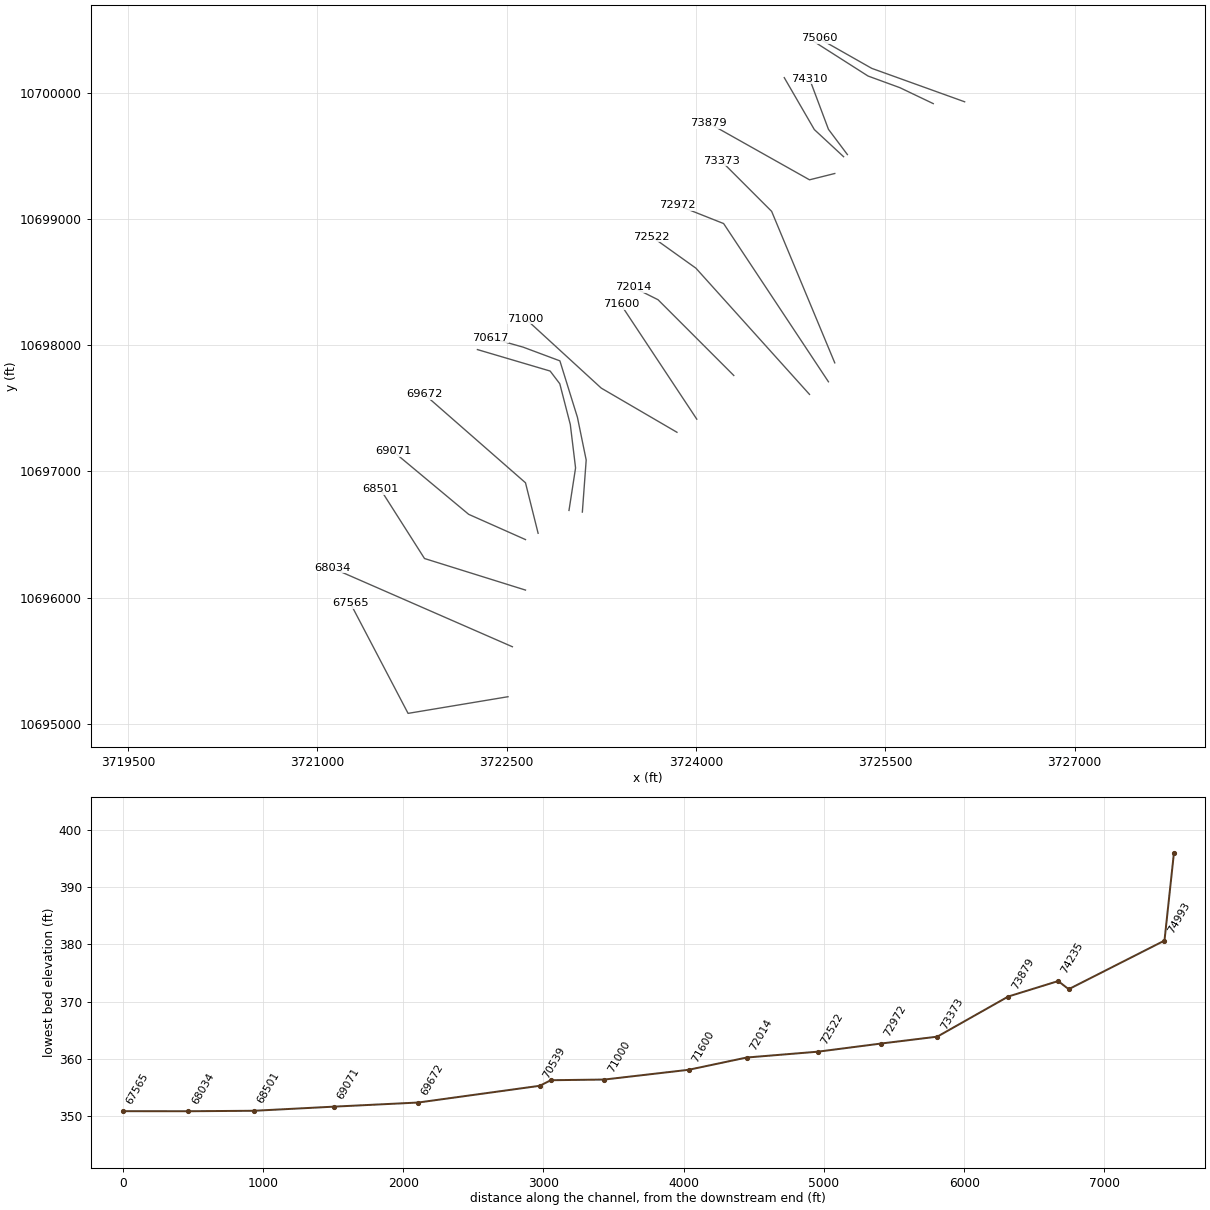
HEC-RAS study BEAVER CREEK.prj: BEAVER CREEK Base Level Engineering

--- BEAVER CREEK.g01 (geometry) --- (continued)

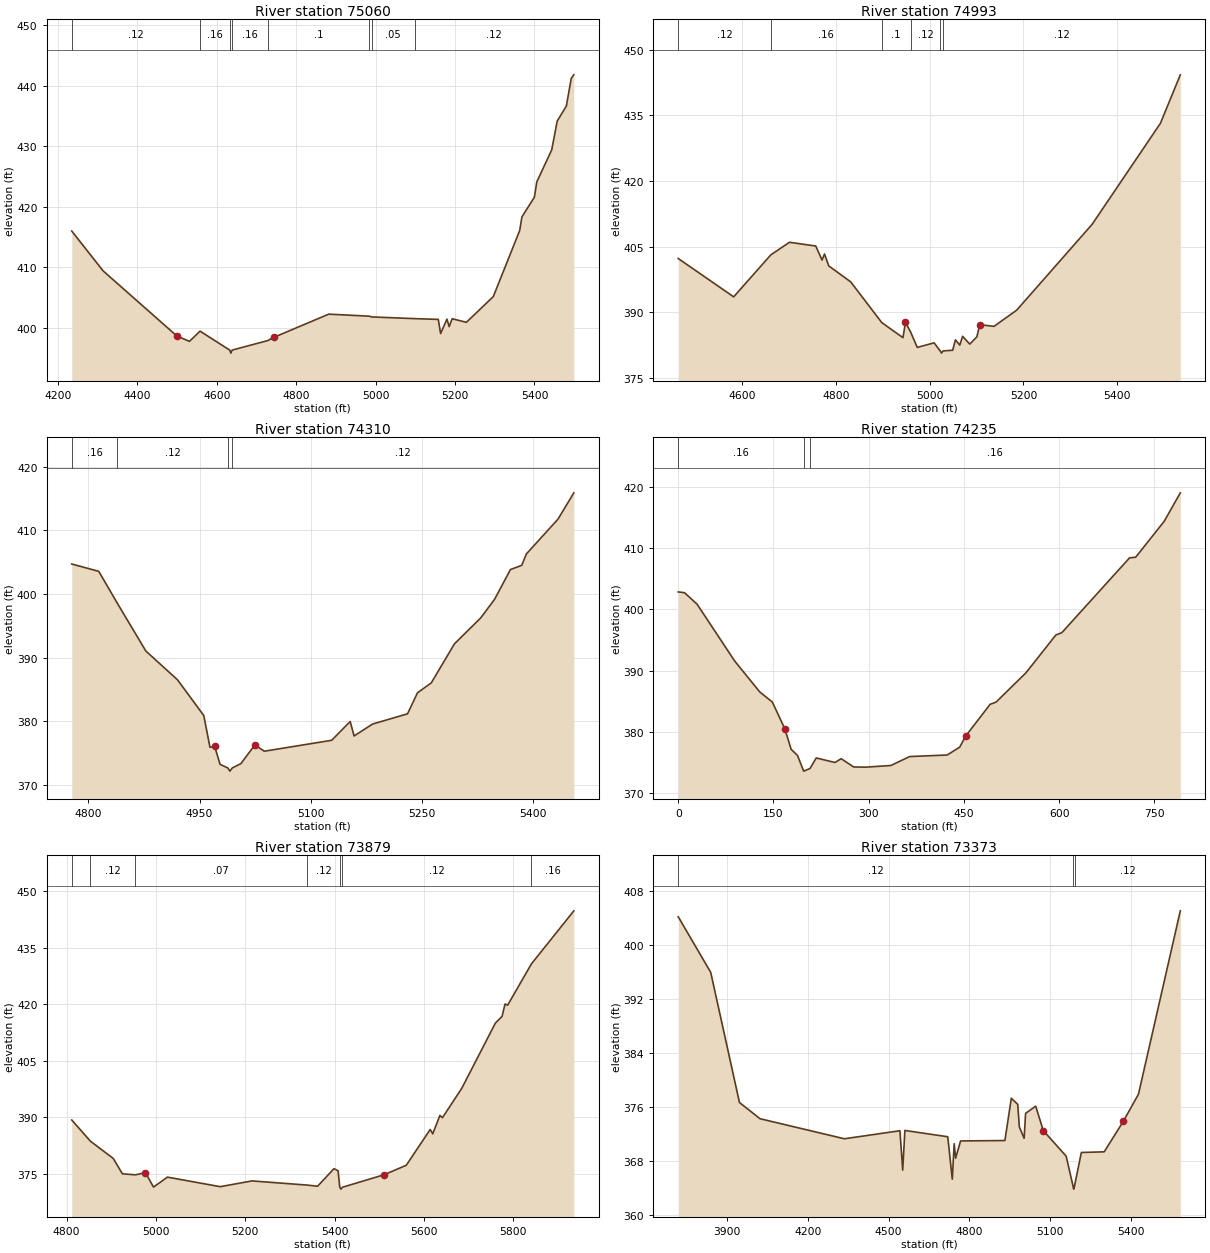
Type RM Length L Ch R = 1 ,75060   ,67,67,67
BEGIN DESCRIPTION:
Mapping XS bbde77fe
END DESCRIPTION:
XS GIS Cut Line= 3
      3726128.44     10699928.27      3725392.76     10700193.03
      3724973.19     10700430.94
#Sta/Elev= 30
  4234.9  416.01  4313.9  409.43  4499.4  398.69  4531.2  397.79  4557.9  399.48
  4632.7  396.35  4635.5  395.85  4638.7  396.35  4728.2  397.92  4743.8  398.46
    4882  402.29  4984.5  401.95  4989.7  401.83  5097.9  401.55  5157.8  401.42
  5163.6  399.08  5179.5  401.47  5185.2  400.23  5192.8  401.53  5228.5  400.94
  5296.3  405.19  5362.7  416.09  5368.4  418.36  5399.7   421.6  5405.9  424.15
  5443.4  429.42  5457.2  434.18  5480.2  436.65  5492.5  441.22  5499.1  441.82
#Mann= 8 ,-1 , 0
  4234.9     .12       0  4557.9     .16       0  4632.7     .03       0
  4638.7     .16       0  4728.2      .1       0  4984.5     .12       0
  4989.7     .05       0  5097.9     .12       0
Bank Sta=4499.4,4743.8
XS Rating Curve= 0 ,0
Exp/Cntr=0.3,0.1

Type RM Length L Ch R = 1 ,74993   ,683,683,683
BEGIN DESCRIPTION:
Mapping XS 7406c0a2
END DESCRIPTION:
XS GIS Cut Line= 4
      3725879.95     10699913.71       3725615.6     10700040.02
        3725363.     10700132.47      3724934.86      10700405.4
#Sta/Elev= 30
  4464.4  402.28  4582.5  393.51  4661.6   403.1  4701.4  405.99  4757.4  405.13
  4770.7  401.93  4776.1   403.3  4785.1  400.59  4831.8  396.94    4898  387.63
  4943.2  384.17  4948.5  387.68  4959.4  385.49  4973.7  381.95  5009.6  382.99
  5022.5  381.14  5025.3  380.64  5028.5  381.14  5049.1   381.3    5055  383.67
  5064.3  382.48  5070.3  384.48  5085.5   382.7  5100.7  384.37  5106.7  387.15
  5137.1  386.76  5185.4  390.45  5346.2  410.09  5491.7  433.19  5534.1  444.28
#Mann= 6 ,-1 , 0
  4464.4     .12       0  4661.6     .16       0    4898      .1       0
  4959.4     .12       0  5022.5     .07       0  5028.5     .12       0
Bank Sta=4948.5,5106.7
XS Rating Curve= 0 ,0
Exp/Cntr=0.3,0.1

Type RM Length L Ch R = 1 ,74310   ,75,75,75
BEGIN DESCRIPTION:
BEAVER CREEK 116.0
END DESCRIPTION:
XS GIS Cut Line= 3
       3725199.6      10699510.2      3725049.61     10699710.19
      3724899.61      10700110.2
#Sta/Elev= 30
  4777.6  404.72    4814  403.57  4838.8   398.6  4877.6  391.03  4920.3  386.51
  4955.7  380.89    4964  375.91  4970.3  376.07  4977.6  373.23  4988.1  372.66
  4990.9  372.16  4994.1  372.66  5005.7  373.34  5024.5  376.27  5037.4  375.29
  5128.2  377.01  5153.1  379.96  5158.4  377.69  5183.3  379.56  5230.5  381.17
  5243.9  384.47  5262.5  386.03  5293.7  392.16  5329.3  396.26    5348  399.19
  5369.3  403.85  5384.5  404.51  5390.7  406.29  5433.4  411.77  5454.8  415.91
#Mann= 4 ,-1 , 0
  4777.6     .16       0  4838.8     .12       0  4988.1     .07       0
  4994.1     .12       0
Bank Sta=4970.3,5024.5
XS Rating Curve= 0 ,0
Exp/Cntr=0.3,0.1

Type RM Length L Ch R = 1 ,74235   ,356,356,356
XS GIS Cut Line= 3
     3725169.568    10699493.308     3724937.797    10699708.152
     3724699.516     10700119.61
#Sta/Elev= 30
       0  402.83    9.88   402.7   29.64  400.83   88.91  391.55  128.42   386.5
  148.18  384.86  167.94  380.47  177.81  377.14  187.69  376.16  197.57  373.58
  207.45     374  217.33  375.73  246.85  374.99  256.62  375.61  276.16  374.26
   295.7  374.23  334.92   374.5  364.45  375.96  423.51  376.21  443.19  377.48
  453.03  379.35  491.13  384.48  500.54  384.85  547.63  389.63  594.71   395.8
  604.13  396.18  710.69  408.38  720.44   408.5   765.3  414.35  790.67     419
#Mann= 3 ,-1 , 0
       0     .16       0  197.57     .07       0  207.45     .16       0
Bank Sta=167.94,453.03
XS Rating Curve= 0 ,0
Exp/Cntr=0.3,0.1

Type RM Length L Ch R = 1 ,73879   ,506,506,506
BEGIN DESCRIPTION:
BEAVER CREEK 115.0
END DESCRIPTION:
XS GIS Cut Line= 3
      3725099.64      10699360.2      3724899.61     10699310.19
      3724099.58     10699760.21
#Sta/Elev= 30
  4811.6  389.25  4853.2  383.64  4904.4  379.04    4925  374.95  4954.2  374.68
  4976.6  375.26  4994.6  371.42  5025.8  374.07    5144  371.53  5215.1  373.06
  5338.3  371.96    5362  371.65  5398.6  376.31  5407.9  375.77  5411.6  371.38
  5414.3  370.88  5417.6  371.38  5511.1  374.71  5560.5  377.22  5614.1  386.73
  5619.8  385.57  5635.8  390.46  5641.5  389.86  5684.8  397.68  5760.1  415.02
    5775  416.79  5781.7  420.09  5787.5  419.76  5840.6  430.72  5935.7  444.84
#Mann= 7 ,-1 , 0
  4811.6     .16       0  4853.2     .12       0  4954.2     .07       0
  5338.3     .12       0  5411.6     .07       0  5417.6     .12       0
  5840.6     .16       0
Bank Sta=4976.6,5511.1
XS Rating Curve= 0 ,0
Exp/Cntr=0.3,0.1

Type RM Length L Ch R = 1 ,73373   ,401,401,401
BEGIN DESCRIPTION:
BEAVER CREEK 114.0
END DESCRIPTION:
XS GIS Cut Line= 3
      3725099.59     10697860.23      3724599.61     10699060.19
      3724199.64     10699460.16
#Sta/Elev= 30
  3718.7  404.18  3839.4  395.96  3946.2   376.7  4022.5   374.3  4336.2  371.33
  4542.5  372.52  4552.8  366.69  4560.9  372.56  4720.2  371.63    4737  365.35
    4744   370.6  4749.4  368.46  4767.9  371.01  4932.5  371.07  4956.4  377.32
  4980.2  376.42  4986.2  373.08    5004   371.4  5009.4  375.09  5046.9  376.15
  5075.2  372.54  5160.1  368.76  5185.4  364.38  5188.1  363.88  5191.4  364.38
  5216.6   369.3  5301.5   369.4  5372.2  373.89  5428.8  377.92  5584.3  405.06
#Mann= 3 ,-1 , 0
  3718.7     .12       0  5185.4     .07       0  5191.4     .12       0
Bank Sta=5075.2,5372.2
XS Rating Curve= 0 ,0
Exp/Cntr=0.3,0.1

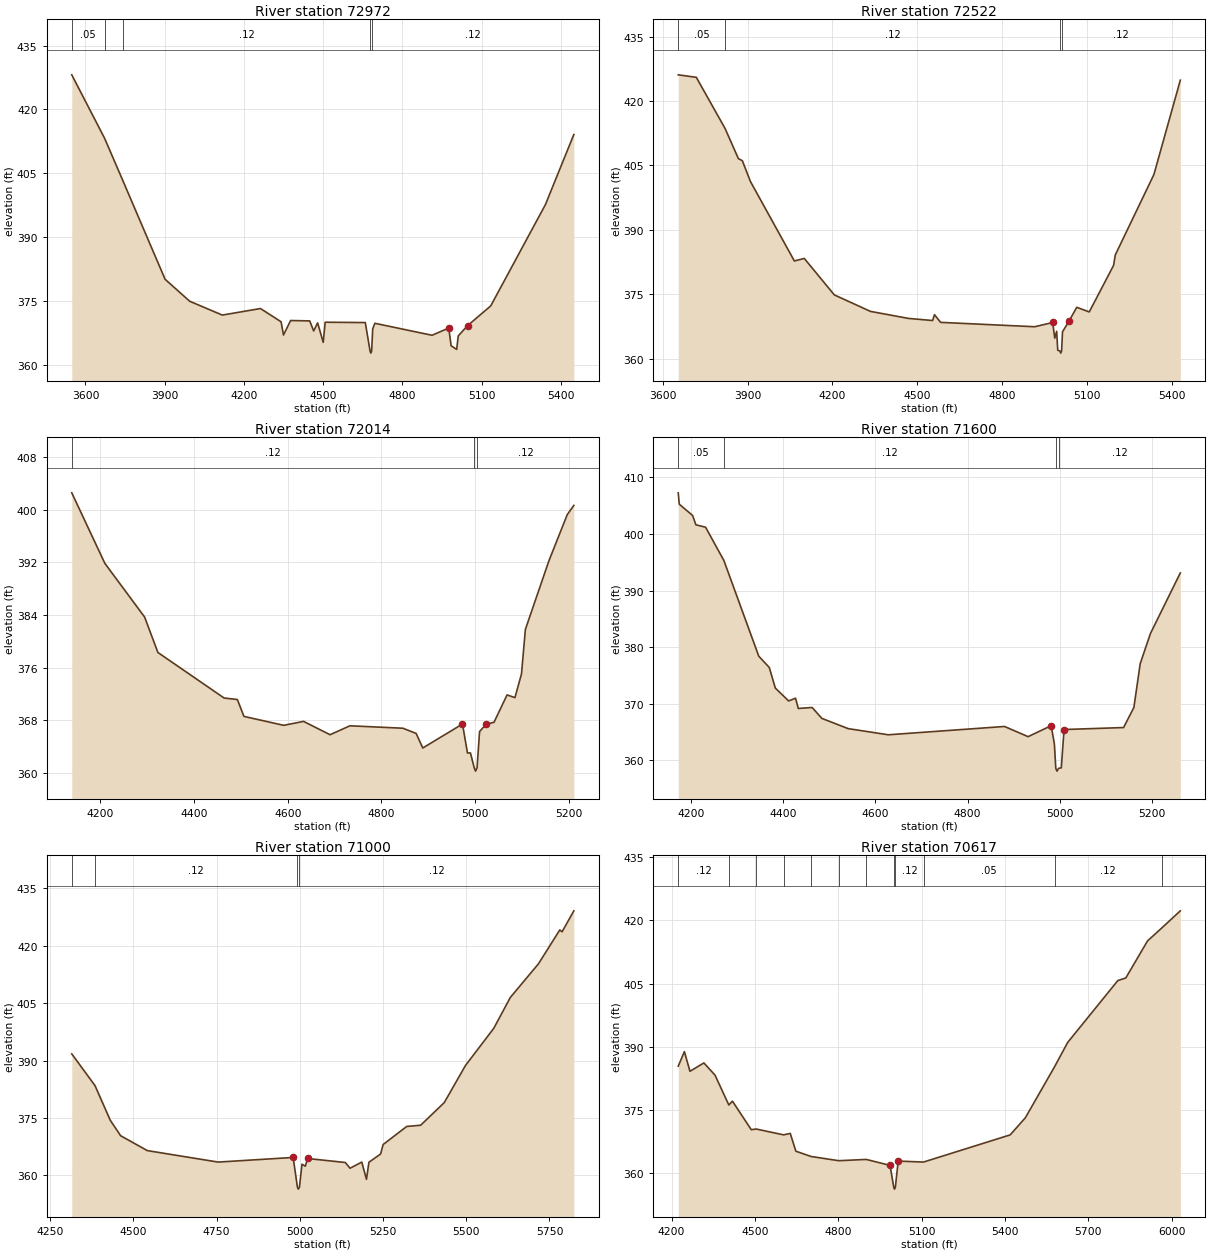
Type RM Length L Ch R = 1 ,72972   ,450,450,450
BEGIN DESCRIPTION:
BEAVER CREEK 113.0
END DESCRIPTION:
XS GIS Cut Line= 3
      3725049.58     10697710.23      3724219.14     10698963.67
       3723849.6     10699110.19
#Sta/Elev= 30
  3548.2  428.15  3672.7   413.2    3743  403.07  3901.6  380.05  3994.9  374.88
  4118.2  371.63  4262.6  373.17  4340.8  370.06  4349.9  366.94  4376.9  370.35
  4449.1  370.26  4464.2   367.9  4479.2   369.8  4500.3  365.21  4507.8  369.95
  4659.7  369.87  4677.7  363.18  4680.5  362.68  4683.7  363.18  4687.7  368.39
  4695.8   369.7  4912.4  366.88  4975.6  368.58  4984.6  364.42  5005.6  363.55
  5011.6  366.73  5046.8  369.14  5134.6  373.79  5341.7  397.62  5449.3  414.11
#Mann= 5 ,-1 , 0
  3548.2     .05       0  3672.7     .07       0    3743     .12       0
  4677.7     .07       0  4683.7     .12       0
Bank Sta=4975.6,5046.8
XS Rating Curve= 0 ,0
Exp/Cntr=0.3,0.1

Type RM Length L Ch R = 1 ,72522   ,508,508,508
BEGIN DESCRIPTION:
BEAVER CREEK 112.0
END DESCRIPTION:
XS GIS Cut Line= 3
       3724899.6     10697610.19      3723999.61     10698610.19
      3723649.58     10698860.21
#Sta/Elev= 30
  3654.9  426.13  3718.8  425.55  3820.6  413.62  3867.5  406.61  3881.7  406.11
  3910.1  401.28  4065.6  382.74  4100.7  383.33  4206.9  374.83  4334.7  370.99
  4469.2  369.35  4554.4  368.86  4561.1  370.21  4582.8  368.43  4915.4  367.41
    4979   368.4  4986.4  364.75  4993.2  366.35  4996.9  361.94  5004.6  361.76
  5007.4  361.26  5010.6  361.76  5013.8  366.22  5037.1  368.76  5064.2  371.94
  5108.4  370.86  5194.4  381.71  5200.6  384.16    5337  402.88  5430.4  424.88
#Mann= 4 ,-1 , 0
  3654.9     .05       0  3820.6     .12       0  5004.6     .07       0
  5010.6     .12       0
Bank Sta=4979,5037.1
XS Rating Curve= 0 ,0
Exp/Cntr=0.3,0.1

Type RM Length L Ch R = 1 ,72014   ,414,414,414
BEGIN DESCRIPTION:
BEAVER CREEK 111.0
END DESCRIPTION:
XS GIS Cut Line= 3
      3724299.63     10697760.17      3723699.61     10698360.19
      3723499.58      10698460.2
#Sta/Elev= 30
  4138.9   402.6  4209.6  391.86  4294.5  383.69  4322.8   378.3  4464.2  371.37
  4492.5  371.14  4506.6  368.57  4591.5  367.21  4633.9  367.81  4690.5  365.78
  4732.9  367.14    4846  366.77  4874.3  365.98  4888.5  363.76  4973.3  367.41
  4983.9  363.01  4990.3  363.01  4998.4  360.74  5001.2  360.24  5004.4  360.74
  5009.8  366.26  5023.8  367.39  5040.6  367.67  5068.5  371.84  5085.3  371.43
  5099.3  375.04  5107.6  381.81    5158  392.28  5197.1  399.29  5211.1  400.68
#Mann= 3 ,-1 , 0
  4138.9     .12       0  4998.4     .07       0  5004.4     .12       0
Bank Sta=4973.3,5023.8
XS Rating Curve= 0 ,0
Exp/Cntr=0.3,0.1

Type RM Length L Ch R = 1 ,71600   ,600,600,600
BEGIN DESCRIPTION:
BEAVER CREEK 110.0
END DESCRIPTION:
XS GIS Cut Line= 2
      3724006.46     10697414.19      3723404.06     10698324.29
#Sta/Elev= 30
  4171.2  407.27  4173.5  405.26  4202.4  403.27  4209.6  401.62  4230.6   401.2
  4270.4  395.32  4346.3   378.4  4369.1  376.42  4382.3  372.77  4411.2   370.5
  4426.2  370.99  4432.2  369.17  4462.3  369.34  4483.4  367.42  4540.5  365.61
  4627.8  364.52  4880.5  365.99  4931.7  364.19  4981.9  366.13  4988.9  362.87
  4991.9   358.6  4994.6   358.1  4997.9   358.6  5003.9  358.68  5009.9  365.45
  5139.3   365.8  5161.7  369.35  5175.4  377.08  5197.7  382.42  5262.6  393.12
#Mann= 4 ,-1 , 0
  4171.2     .05       0  4270.4     .12       0  4991.9     .07       0
  4997.9     .12       0
Bank Sta=4981.9,5009.9
XS Rating Curve= 0 ,0
Exp/Cntr=0.3,0.1

Type RM Length L Ch R = 1 ,71000   ,383,383,383
BEGIN DESCRIPTION:
BEAVER CREEK 109.0
END DESCRIPTION:
XS GIS Cut Line= 3
      3723849.59      10697310.2      3723249.61     10697660.19
      3722649.64     10698210.16
#Sta/Elev= 30
  4314.8  391.75  4384.7  383.45  4430.5   374.4  4461.6  370.36  4541.8  366.47
  4754.7  363.47    4980  364.68  4992.8   356.9  4995.5   356.4  4998.8   356.9
  5006.5  362.91  5016.5   362.4  5023.3  364.41  5136.7  363.36  5150.9  361.86
  5186.1  363.47  5200.2  358.97  5207.6  363.42  5242.8  365.59  5250.2  368.05
  5321.1  372.78    5363   373.1  5433.9  379.01  5497.8  388.73  5582.6  398.42
  5632.5  406.51    5717   415.3  5781.1  424.16  5787.9  423.66  5823.3  429.15
#Mann= 4 ,-1 , 0
  4314.8     .05       0  4384.7     .12       0  4992.8     .07       0
  4998.8     .12       0
Bank Sta=4980,5023.3
XS Rating Curve= 0 ,0
Exp/Cntr=0.3,0.1

Type RM Length L Ch R = 1 ,70617   ,78,78,78
BEGIN DESCRIPTION:
Mapping XS a37a6844
END DESCRIPTION:
XS GIS Cut Line= 6
      3723100.07     10696678.09      3723130.45      10697090.4
      3723061.01     10697428.94      3722922.12     10697875.99
      3722631.32      10697984.5      3722372.75     10698057.76
#Sta/Elev= 30
  4223.8  385.43    4246  388.89    4266  384.22  4316.2   386.2  4356.3   383.3
  4405.9  376.23  4418.9  377.14  4486.7  370.37  4504.5  370.53    4603  369.15
    4627  369.49  4647.2  365.27    4702  364.02  4801.3  363.02  4900.6  363.32
  4986.1  361.91  4999.4  356.78  5002.1  356.28  5005.4  356.78  5015.5  362.93
  5106.6   362.7  5418.5  369.14  5473.2   373.2  5578.5  385.32  5625.6  391.07
    5806  405.73  5834.8  406.36    5913  415.14  5963.3  418.15  6030.9  422.27
#Mann= 12 ,-1 , 0
  4223.8     .12       0  4405.9     .05       0  4504.5     .08       0
    4603     .05       0    4702     .08       0  4801.3      .1       0
  4900.6     .12       0  4999.4     .07       0  5005.4     .12       0
  5106.6     .05       0  5578.5     .12       0  5963.3     .05       0
Bank Sta=4986.1,5015.5
XS Rating Curve= 0 ,0
Exp/Cntr=0.3,0.1

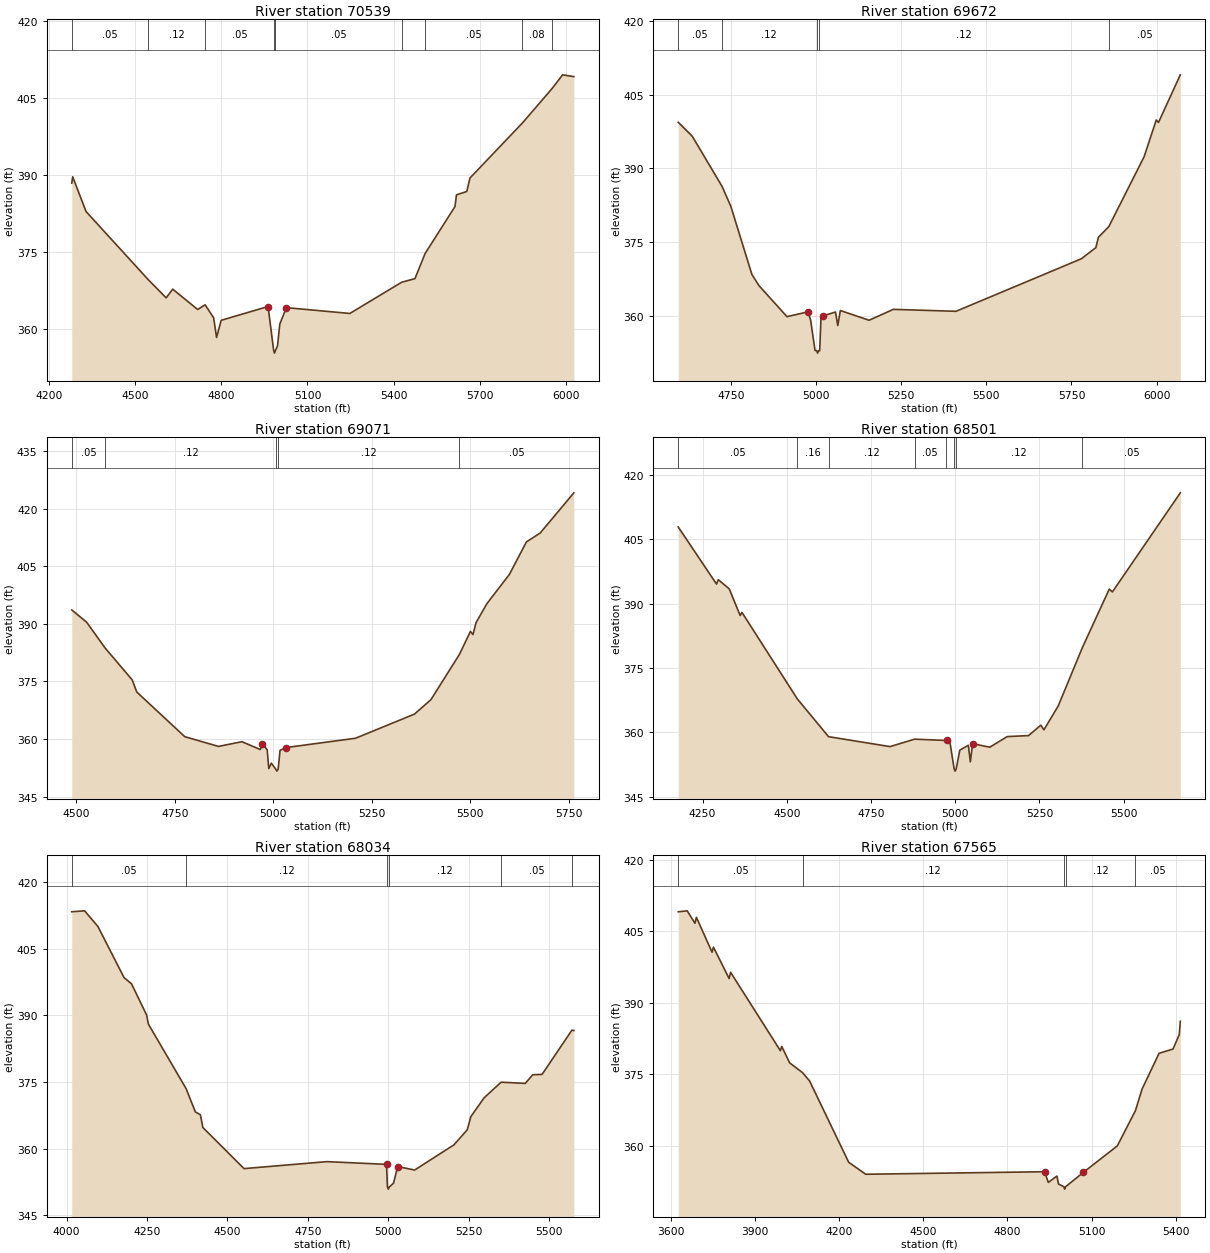
Type RM Length L Ch R = 1 ,70539   ,867,867,867
BEGIN DESCRIPTION:
BEAVER CREEK 108.0
END DESCRIPTION:
XS GIS Cut Line= 6
      3722994.25      10696691.1      3723046.33     10697027.89
      3723004.67     10697371.64      3722921.33     10697694.55
      3722844.94     10697795.25      3722268.94     10697965.29
#Sta/Elev= 30
    4279   388.4  4282.2  389.63  4328.7  382.87  4545.7  369.59  4607.7  366.07
  4630.6  367.76  4717.5   363.8  4743.4  364.71  4773.2  362.19  4783.3  358.36
  4799.4   361.7  4962.8  364.38  4982.2  355.81    4985  355.31  4988.2  355.81
  4995.5  356.67  5003.5  360.96  5026.5  364.16  5247.5  363.03    5428   369.1
  5474.3  369.81  5509.8  374.71  5613.8  383.84  5618.9  386.11  5654.8  386.77
  5666.1   389.4  5848.8  400.11  5951.9   406.8  5988.6  409.47  6027.7  409.12
#Mann= 9 ,-1 , 0
    4279     .05       0  4545.7     .12       0  4743.4     .05       0
  4982.2     .04       0  4988.2     .05       0    5428     .07       0
  5509.8     .05       0  5848.8     .08       0  5951.9     .05       0
Bank Sta=4962.8,5026.5
XS Rating Curve= 0 ,0
Exp/Cntr=0.3,0.1

Type RM Length L Ch R = 1 ,69672   ,601,601,601
BEGIN DESCRIPTION:
BEAVER CREEK 107.0
END DESCRIPTION:
XS GIS Cut Line= 3
       3722749.6     10696510.21      3722649.61     10696910.19
      3721849.61     10697610.19
#Sta/Elev= 30
  4594.6  399.37  4635.8  396.53  4723.3  386.34  4749.2  382.26    4811  368.41
  4831.7  366.14  4914.1  359.81    4976  360.79  4983.7  359.08  4996.6  352.93
  5001.3  352.89  5004.1  352.39  5007.3  352.89  5010.2  352.89    5014  359.42
  5020.7  359.98  5056.7  360.76  5063.4  358.01    5071  361.06  5155.4  359.08
  5226.6   361.3  5410.7   360.9    5779  371.59  5821.7  373.86  5829.3  375.97
    5860  378.16  5963.6  392.37  5999.2  399.83  6005.8  399.34  6069.9  409.03
#Mann= 5 ,-1 , 0
  4594.6     .05       0  4723.3     .12       0  5001.3     .07       0
  5007.3     .12       0    5860     .05       0
Bank Sta=4976,5020.7
XS Rating Curve= 0 ,0
Exp/Cntr=0.3,0.1

Type RM Length L Ch R = 1 ,69071   ,570,570,570
BEGIN DESCRIPTION:
BEAVER CREEK 106.0
END DESCRIPTION:
XS GIS Cut Line= 3
      3722649.65     10696460.17      3722199.61     10696660.19
      3721599.62     10697160.18
#Sta/Elev= 30
  4488.9  393.61  4526.6  390.43  4573.1  383.76  4642.2  375.41  4653.8  372.25
  4775.5  360.64    4861   358.1  4920.5  359.33    4967  357.29  4972.5  358.75
  4984.6  357.23  4988.6  352.33  4995.1  353.74  5006.4  352.17  5009.1  351.67
  5012.4  352.17  5017.2  357.06  5031.5  357.79  5208.5  360.22  5358.2  366.51
  5399.9  370.26  5472.3  382.06  5500.1  388.03  5506.6  387.21  5514.4  390.32
  5541.8  395.24  5599.1  402.89    5642   411.3  5677.2  413.65  5762.4  424.09
#Mann= 5 ,-1 , 0
  4488.9     .05       0  4573.1     .12       0  5006.4     .07       0
  5012.4     .12       0  5472.3     .05       0
Bank Sta=4972.5,5031.5
XS Rating Curve= 0 ,0
Exp/Cntr=0.3,0.1

Type RM Length L Ch R = 1 ,68501   ,467,467,467
BEGIN DESCRIPTION:
BEAVER CREEK 105.0
END DESCRIPTION:
XS GIS Cut Line= 3
      3722649.57      10696060.2      3721849.61     10696310.19
      3721499.63     10696860.16
#Sta/Elev= 30
  4177.9  407.92  4291.5   394.6  4296.8  395.63  4329.3  393.48  4361.7  387.26
    4367  387.99  4531.4  367.79    4624  358.99  4806.5  356.67  4879.3  358.41
  4971.9  358.11  4974.1   358.2  4984.6   357.5  4996.8  351.45  4999.5  350.95
  5002.8  351.45  5013.4  355.84  5038.9  356.98  5044.8  353.13  5051.6  357.36
  5102.4  356.53    5154  359.01  5217.5  359.24  5253.9  361.67  5263.2  360.59
  5305.6  366.16  5377.6  379.84  5457.1  393.42  5466.4  392.77  5667.9  415.89
#Mann= 8 ,-1 , 0
  4177.9     .05       0  4531.4     .16       0    4624     .12       0
  4879.3     .05       0  4971.9     .12       0  4996.8     .07       0
  5002.8     .12       0  5377.6     .05       0
Bank Sta=4974.1,5051.6
XS Rating Curve= 0 ,0
Exp/Cntr=0.3,0.1

Type RM Length L Ch R = 1 ,68034   ,469,469,469
BEGIN DESCRIPTION:
Mapping XS d73e9fa1
END DESCRIPTION:
XS GIS Cut Line= 2
      3722545.73     10695611.23      3721116.39      10696235.7
#Sta/Elev= 30
  4016.3  413.34  4056.2  413.55  4097.5  410.03  4178.6  398.53    4202   397.1
  4248.8  390.09  4254.3  388.04  4371.5  373.51  4400.2  368.26  4415.8  367.63
  4423.6  364.75  4551.5  355.49  4808.7  357.06  4994.2  356.45    4997  351.37
  4999.7  350.87    5003  351.37    5016  352.22  5028.9  355.96  5081.5  355.17
  5203.6  360.84  5244.9  364.23  5256.1  367.19  5297.2  371.43  5350.3  374.96
  5425.1  374.68  5448.5  376.63  5477.4  376.71    5570  386.67  5576.1   386.6
#Mann= 6 ,-1 , 0
  4016.3     .05       0  4371.5     .12       0    4997     .07       0
    5003     .12       0  5350.3     .05       0    5570     .08       0
Bank Sta=4994.2,5028.9
XS Rating Curve= 0 ,0
Exp/Cntr=0.3,0.1

Type RM Length L Ch R = 1 ,67565   ,633,633,633
BEGIN DESCRIPTION:
BEAVER CREEK 104.0
END DESCRIPTION:
XS GIS Cut Line= 3
      3722511.06     10695215.39      3721719.37     10695083.44
      3721261.91     10695956.77
#Sta/Elev= 30
  3627.4  409.05  3659.3  409.25    3687  406.64  3692.1  407.88  3747.9  400.57
  3752.9  401.64  3808.7  395.04  3813.8  396.37  3991.2  379.92  3996.2  380.81
  4024.2  377.37  4070.4   375.3  4095.2  373.58  4234.5  356.52  4295.3     354
  4932.3  354.53  4945.6  352.29  4976.4  353.62  4982.1  351.96  5001.2  351.38
  5003.9  350.88  5007.2  351.38  5070.3  354.38  5191.4  359.94  5256.2  367.36
  5279.7  371.87  5340.3  379.37    5390  380.26  5412.1  383.29  5415.9   386.1
#Mann= 5 ,-1 , 0
  3627.4     .05       0  4070.4     .12       0  5001.2     .07       0
  5007.2     .12       0  5256.2     .05       0
Bank Sta=4932.3,5070.3
XS Rating Curve= 0 ,0
Exp/Cntr=0.3,0.1