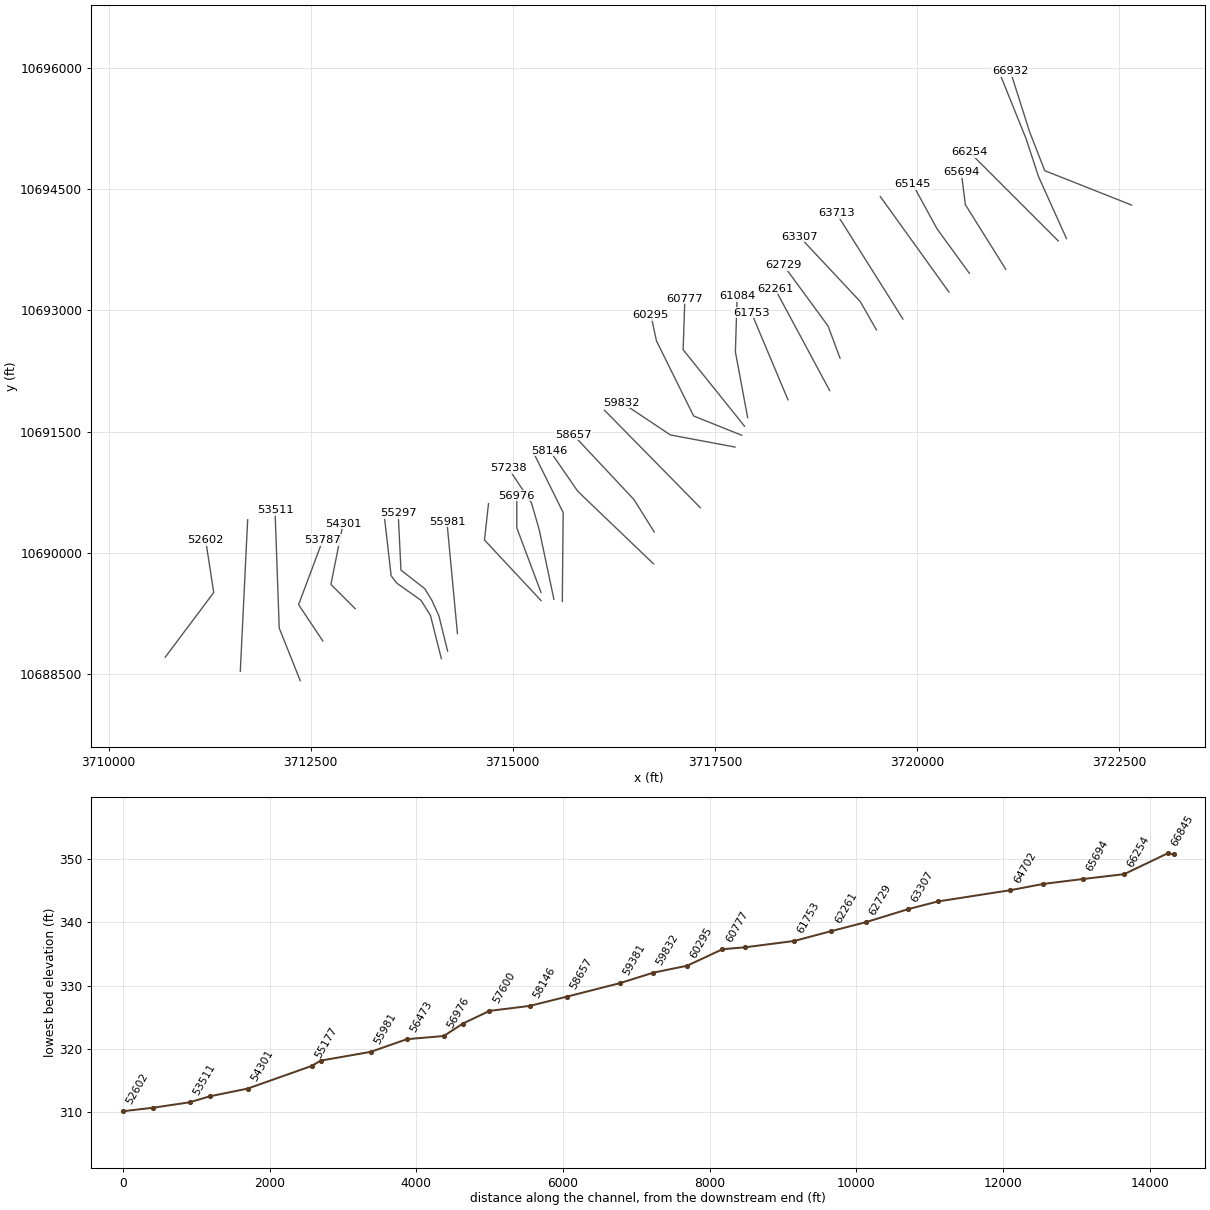
HEC-RAS study BEAVER CREEK.prj: BEAVER CREEK Base Level Engineering

--- BEAVER CREEK.g01 (geometry) --- (continued)

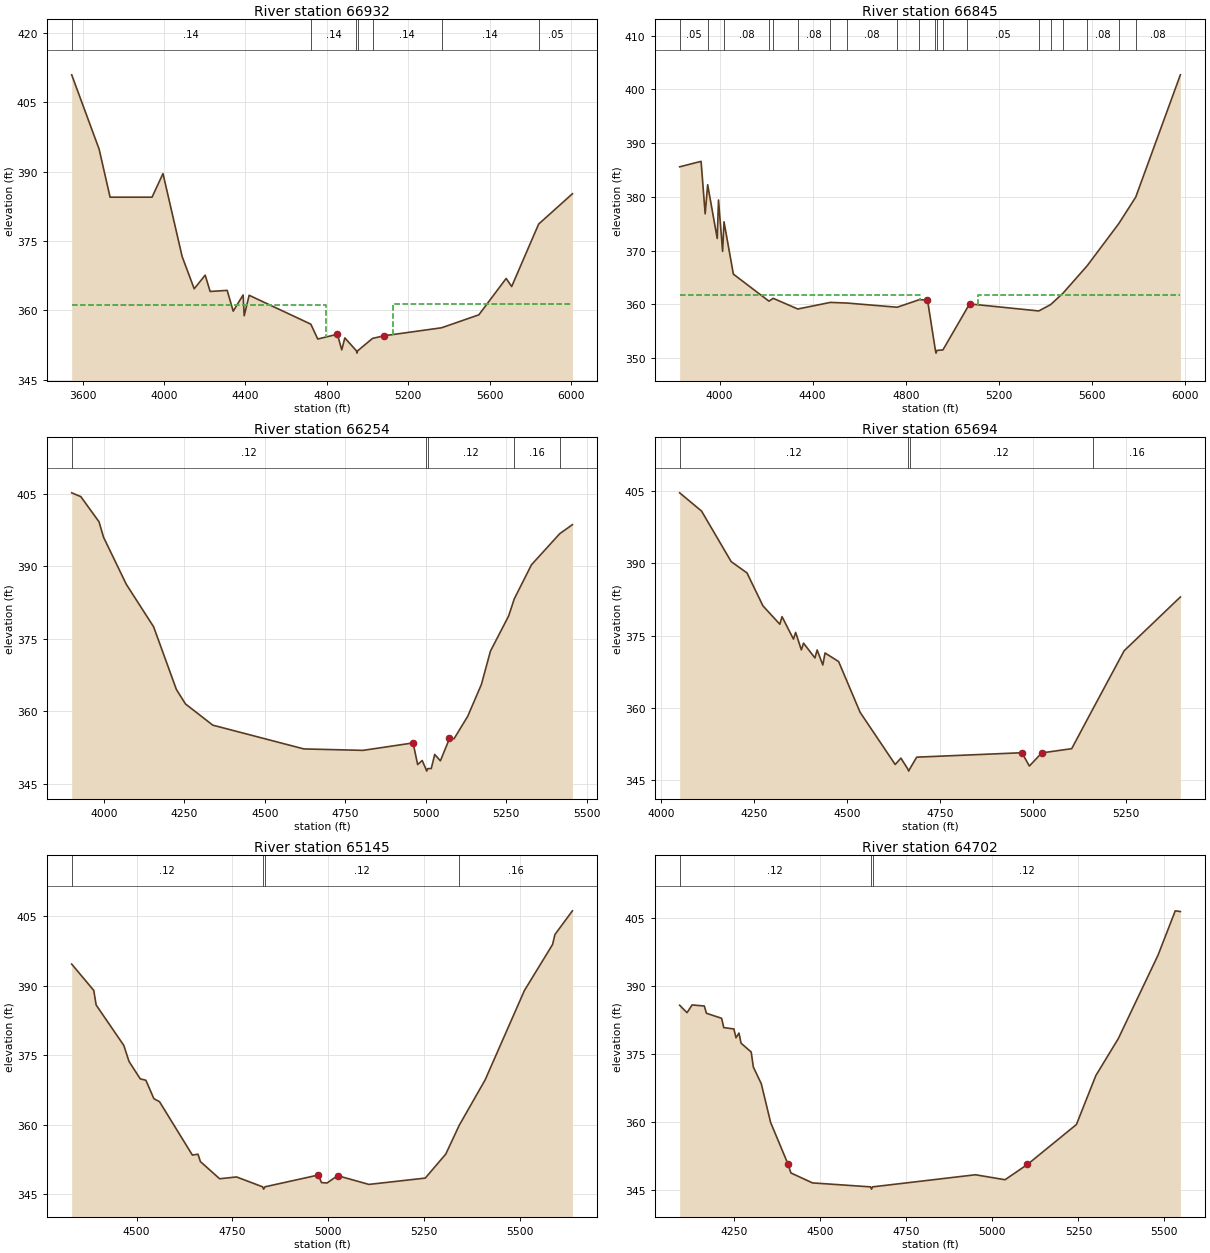
Type RM Length L Ch R = 1 ,66932   ,87,87,87
BEGIN DESCRIPTION:
Mapping XS 115b8afd
END DESCRIPTION:
XS GIS Cut Line= 4
      3722657.02     10694304.43      3721582.41     10694729.76
      3721393.67     10695213.66      3721155.51     10695963.84
#Sta/Elev= 30
  3545.4   410.9  3680.2  394.85  3734.2  384.46  3940.5  384.46  3994.3  389.56
  4088.3  371.66  4147.8  364.67  4201.8  367.61  4226.2  364.08  4309.9  364.32
  4339.6  359.83  4388.3  363.33  4393.7  358.84    4418  363.26  4721.3  357.02
  4755.4  353.81  4851.9  354.84  4873.3  351.47  4888.6  354.05  4945.5  351.26
  4948.2  350.76  4951.5  351.26  5024.7  353.94  5081.5  354.51  5364.4  356.24
  5547.6  359.04  5681.9   366.9  5708.9  365.15  5841.6  378.65  6007.6   385.2
#Mann= 7 ,-1 , 0
  3545.4     .14       0  4721.3     .14       0  4945.5     .07       0
  4951.5     .14       0  5024.7     .14       0  5364.4     .14       0
  5841.6     .05       0
#XS Ineff= 2 , 0
       0 4793.63  361.24 5124.21       0  361.34
Permanent Ineff=
       T       T
Bank Sta=4851.9,5081.5
XS Rating Curve= 0 ,0
Exp/Cntr=0.3,0.1

Type RM Length L Ch R = 1 ,66845   ,591,591,591
BEGIN DESCRIPTION:
BEAVER CREEK 102.0
END DESCRIPTION:
XS GIS Cut Line= 4
      3721851.32     10693888.98      3721504.09     10694659.83
      3721351.31     10695125.11      3721045.74     10695882.09
#Sta/Elev= 30
  3828.8  385.58  3920.8   386.6  3938.4  376.84  3949.1  382.25  3990.2  372.25
  3995.7   379.4  4013.3  369.84  4019.4  375.35  4059.6  365.61  4212.6  360.58
  4230.8  361.11  4336.5  359.12  4476.1  360.35  4547.8  360.23  4763.4  359.45
  4858.1  360.85  4893.7  360.81  4927.8  351.41  4930.5  350.91  4933.8  351.41
    4960  351.51  5061.9  359.13  5074.6  360.07    5372  358.76  5422.8  359.94
  5476.1  362.07  5580.2  367.19  5715.1  374.98  5788.4  379.94  5980.3   402.7
#Mann= 20 ,-1 , 0
  3828.8     .05       0  3949.1     .12       0  4019.4     .08       0
  4212.6     .12       0  4230.8     .05       0  4336.5     .08       0
  4476.1     .12       0  4547.8     .08       0  4763.4     .12       0
  4858.1     .05       0  4927.8     .07       0  4933.8     .05       0
    4960     .08       0  5061.9     .05       0    5372     .08       0
  5422.8     .12       0  5476.1     .05       0  5580.2     .08       0
  5715.1     .05       0  5788.4     .08       0
#XS Ineff= 2 , 0
       0 4861.22  361.67  5109.5       0  361.71
Permanent Ineff=
       T       T
Bank Sta=4893.7,5074.6
XS Rating Curve= 0 ,0
Exp/Cntr=0.3,0.1

Type RM Length L Ch R = 1 ,66254   ,560,560,560
BEGIN DESCRIPTION:
BEAVER CREEK 101.0
END DESCRIPTION:
XS GIS Cut Line= 3
      3721749.62     10693860.17      3720949.61     10694660.19
      3720649.58     10694960.22
#Sta/Elev= 30
    3900  405.15  3928.3  404.37  3984.9  399.16    3999  395.97  4069.7  386.24
  4154.6  377.45  4225.3   364.5  4253.6  361.51  4338.4  357.13  4621.3  352.22
  4805.1  351.92  4960.7  353.46  4974.8  348.99    4989  349.83  5000.1  348.13
  5002.9  347.63  5006.1  348.13  5017.2  348.18  5027.9  351.08  5045.5  349.76
  5073.8  354.38    5088  354.33  5130.4  358.96  5172.8  365.53  5201.1  372.44
  5257.7  379.72    5275  383.23  5328.4  390.27  5416.4  396.71  5455.7  398.57
#Mann= 5 ,-1 , 0
    3900     .12       0  5000.1     .07       0  5006.1     .12       0
    5275     .16       0  5416.4      .1       0
Bank Sta=4960.7,5073.8
XS Rating Curve= 0 ,0
Exp/Cntr=0.3,0.1

Type RM Length L Ch R = 1 ,65694   ,549,549,549
BEGIN DESCRIPTION:
BEAVER CREEK 100.0
END DESCRIPTION:
XS GIS Cut Line= 3
       3721099.6      10693510.2      3720599.61     10694310.19
      3720549.61      10694710.2
#Sta/Elev= 30
  4050.6  404.65  4109.5  400.86  4189.1  390.37  4231.6  388.03  4274.6  381.18
    4320  377.37  4325.9  378.94  4356.6  374.28  4362.5  375.67  4377.8  372.05
  4383.7  373.44  4414.4  370.37  4420.3  372.03  4435.6  368.91  4441.5   371.4
  4478.1  369.62  4535.8  359.09  4630.2  348.25  4645.5  349.57  4663.7  347.37
  4666.5  346.87  4669.7  347.37    4688  349.77    4971  350.69    4991  347.93
  5024.2  350.65  5104.8  351.53  5161.3   359.7  5245.9  371.86  5397.1  383.03
#Mann= 4 ,-1 , 0
  4050.6     .12       0  4663.7     .07       0  4669.7     .12       0
  5161.3     .16       0
Bank Sta=4971,5024.2
XS Rating Curve= 0 ,0
Exp/Cntr=0.3,0.1

Type RM Length L Ch R = 1 ,65145   ,443,443,443
BEGIN DESCRIPTION:
BEAVER CREEK 99.0
END DESCRIPTION:
XS GIS Cut Line= 3
      3720649.61     10693460.19      3720249.61     10694010.19
       3719949.6     10694560.21
#Sta/Elev= 30
  4330.5  394.65  4388.1  388.97  4394.3  385.82  4466.5   377.1    4480  373.65
  4509.4  369.88  4524.1  369.58    4545   365.6  4559.6  364.96  4645.4  353.43
  4660.1  353.62  4666.3  352.03  4716.5  348.32  4760.6  348.71  4828.7  346.58
  4831.4  346.08  4834.7  346.58  4973.9  349.12  4982.4  347.49    4997  347.41
  5024.3  348.99    5106   347.1  5253.1  348.46  5306.7  353.65    5342   359.9
  5409.3  369.65  5511.8  388.94  5585.3  398.88  5591.5  401.04  5637.1  406.15
#Mann= 4 ,-1 , 0
  4330.5     .12       0  4828.7     .07       0  4834.7     .12       0
    5342     .16       0
Bank Sta=4973.9,5024.3
XS Rating Curve= 0 ,0
Exp/Cntr=0.3,0.1

Type RM Length L Ch R = 1 ,64702   ,989,989,989
BEGIN DESCRIPTION:
Mapping XS 8c4eb2a6
END DESCRIPTION:
XS GIS Cut Line= 2
      3720396.79     10693227.46      3719547.78     10694409.82
#Sta/Elev= 30
  4090.8  385.79  4112.2  384.15  4126.9  385.86  4162.5  385.63  4168.6  384.02
  4212.8  382.91    4219  380.85  4248.4  380.55  4254.6  378.59  4263.2  379.64
  4269.3   377.4  4298.8  375.44  4304.9  372.14  4328.1  368.41  4355.3  359.84
  4405.6  350.67  4414.2  348.68  4476.8  346.48  4645.7   345.6  4648.5   345.1
  4651.7   345.6  4950.8  348.28  5036.7  347.18  5101.8  350.56  5244.2   359.4
  5300.7  370.24  5365.8  378.39  5481.2  396.84  5531.5  406.69  5546.4  406.53
#Mann= 3 ,-1 , 0
  4090.8     .12       0  4645.7     .07       0  4651.7     .12       0
Bank Sta=4405.6,5101.8
XS Rating Curve= 0 ,0
Exp/Cntr=0.3,0.1

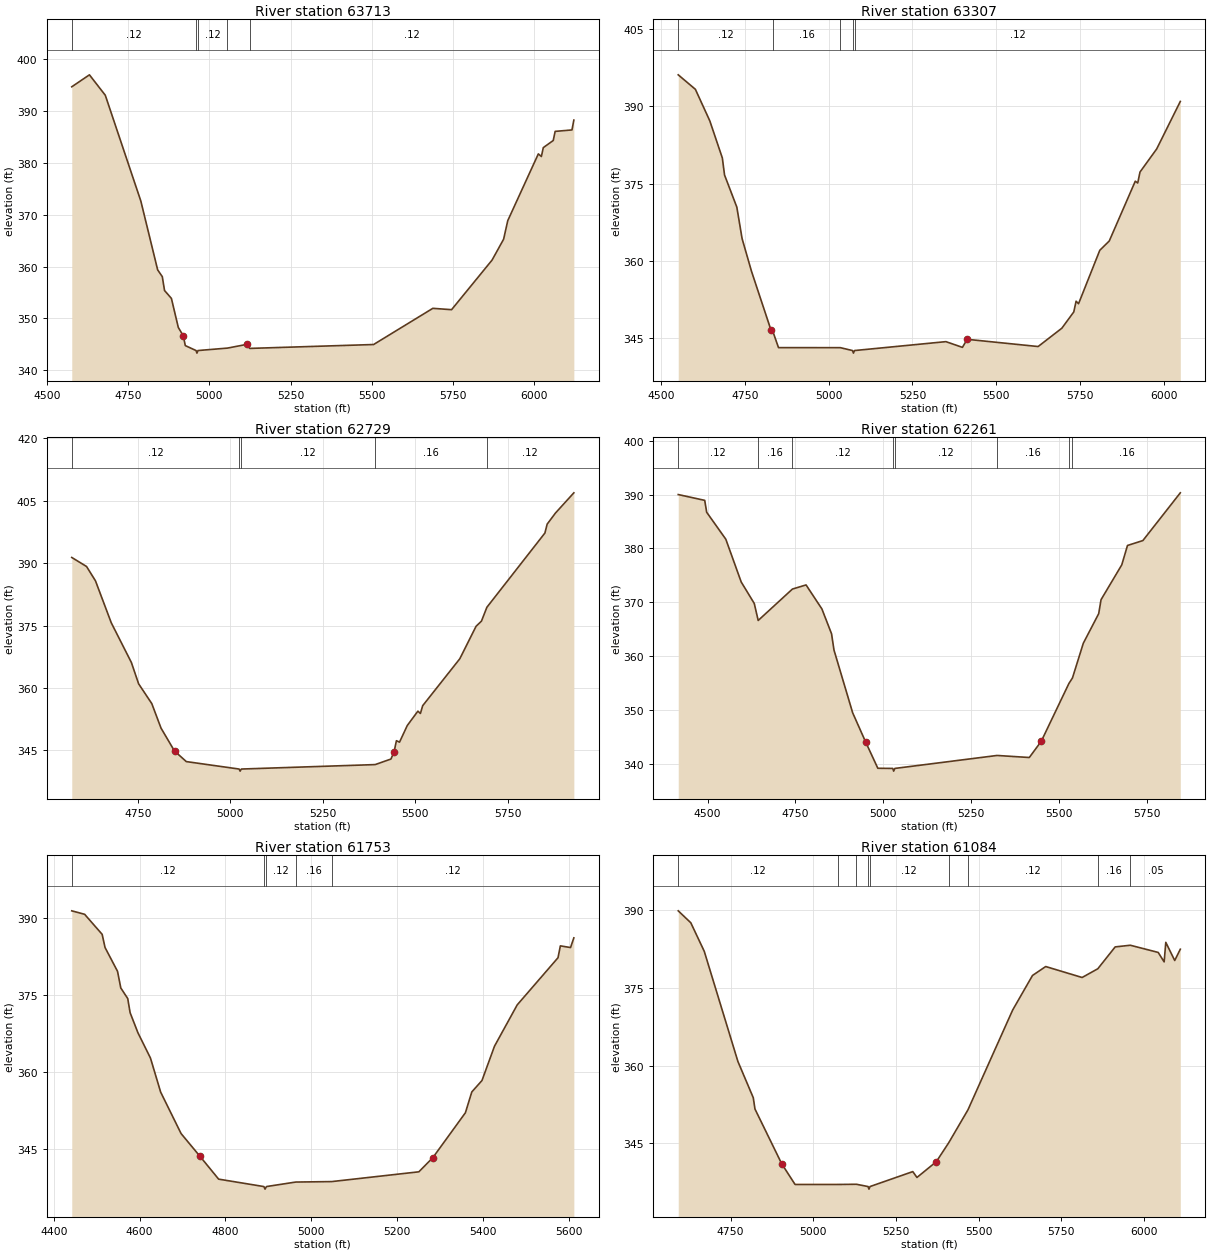
Type RM Length L Ch R = 1 ,63713   ,406,406,406
BEGIN DESCRIPTION:
Mapping XS 1c63e403
END DESCRIPTION:
XS GIS Cut Line= 2
      3719827.33     10692894.15      3719003.63     10694203.39
#Sta/Elev= 30
    4576  394.69  4630.4     397  4679.3  393.06  4788.8  372.65  4840.6  359.38
  4854.9  358.07  4861.8   355.4    4883  353.87  4904.2  348.27  4919.5  346.67
  4925.8  344.77  4958.9  343.82  4961.6  343.32  4964.9  343.82  5055.5  344.29
  5114.8     345  5124.2  344.23  5505.9  344.98  5688.4  351.96  5746.1   351.7
  5870.9  361.27  5906.4  365.29  5919.2  368.87  6013.4  381.75  6022.8  381.25
  6028.7  382.96  6059.3  384.33  6065.2  386.09    6117  386.37  6122.8  388.27
#Mann= 5 ,-1 , 0
    4576     .12       0  4958.9     .07       0  4964.9     .12       0
  5055.5     .16       0  5124.2     .12       0
Bank Sta=4919.5,5114.8
XS Rating Curve= 0 ,0
Exp/Cntr=0.3,0.1

Type RM Length L Ch R = 1 ,63307   ,578,578,578
BEGIN DESCRIPTION:
BEAVER CREEK 96.0
END DESCRIPTION:
XS GIS Cut Line= 3
      3719499.63     10692760.15      3719299.61     10693110.19
      3718549.64     10693910.16
#Sta/Elev= 30
  4550.4  396.15  4601.6  393.34  4644.7  387.21  4682.2  379.99  4688.7   376.7
  4725.4  370.46  4741.2  364.33  4769.3  357.98  4827.6  346.55  4834.6  346.02
  4849.9  343.17  5034.7  343.16    5071   342.6  5073.7   342.1    5077   342.6
  5349.9  344.33  5399.3  343.22  5413.4  344.78  5625.4  343.38  5696.3  346.94
  5731.9   350.1  5738.8  352.18  5746.1  351.69  5809.6  362.07  5837.9  363.88
  5915.6  375.49  5922.9  375.14  5929.7  377.27  5979.6  381.76  6050.1  390.98
#Mann= 5 ,-1 , 0
  4550.4     .12       0  4834.6     .16       0  5034.7     .12       0
    5071     .07       0    5077     .12       0
Bank Sta=4827.6,5413.4
XS Rating Curve= 0 ,0
Exp/Cntr=0.3,0.1

Type RM Length L Ch R = 1 ,62729   ,468,468,468
BEGIN DESCRIPTION:
BEAVER CREEK 95.0
END DESCRIPTION:
XS GIS Cut Line= 3
       3719049.6      10692410.2      3718899.61     10692810.19
      3718349.63     10693560.16
#Sta/Elev= 30
  4571.5  391.37  4611.5   389.2  4635.6  385.75  4678.3  375.67  4732.6  366.15
  4752.2  361.02  4787.8  356.27  4812.7  350.39  4849.2  344.87  4881.2  342.33
  5023.9  340.54  5026.6  340.04  5029.9  340.54  5391.7  341.61  5434.4  342.95
  5442.9  344.74  5449.1  347.35  5457.5     347  5478.4  350.99  5507.1  354.45
  5513.9  353.89  5520.1  355.76  5620.4  367.03  5664.4  374.84    5679  376.08
  5693.6   379.4  5850.4  397.23  5856.6  399.38  5879.1  402.05  5928.7   406.9
#Mann= 5 ,-1 , 0
  4571.5     .12       0  5023.9     .07       0  5029.9     .12       0
  5391.7     .16       0  5693.6     .12       0
Bank Sta=4849.2,5442.9
XS Rating Curve= 0 ,0
Exp/Cntr=0.3,0.1

Type RM Length L Ch R = 1 ,62261   ,508,508,508
BEGIN DESCRIPTION:
BEAVER CREEK 94.0
END DESCRIPTION:
XS GIS Cut Line= 2
      3718920.69      10692009.5      3718244.11     10693268.98
#Sta/Elev= 30
  4416.4  390.02  4491.8  388.94  4497.5  386.72  4551.9  381.72  4595.7  373.78
  4632.9  369.79  4644.1  366.63  4741.5  372.46  4780.4  373.23  4825.5  368.77
    4853  364.15  4859.9  361.14  4913.1  349.48  4950.7  343.96  4984.8  339.17
  5027.2  339.14  5029.9  338.64  5033.2  339.14  5324.3  341.55  5416.1  341.17
  5450.2  344.19  5528.8  354.91    5539  355.95  5569.9   362.4  5613.7  367.89
  5620.4  370.49  5679.4  376.96  5695.7  380.56  5739.5  381.47  5846.1  390.34
#Mann= 8 ,-1 , 0
  4416.4     .12       0  4644.1     .16       0  4741.5     .12       0
  5027.2     .07       0  5033.2     .12       0  5324.3     .16       0
  5528.8     .12       0    5539     .16       0
Bank Sta=4950.7,5450.2
XS Rating Curve= 0 ,0
Exp/Cntr=0.3,0.1

Type RM Length L Ch R = 1 ,61753   ,669,669,669
BEGIN DESCRIPTION:
BEAVER CREEK 93.0
END DESCRIPTION:
XS GIS Cut Line= 2
      3718405.08     10691894.89      3717951.95     10692973.03
#Sta/Elev= 30
    4442  391.41    4472  390.73  4512.8  386.82  4519.5  384.25  4548.6   379.6
  4556.2  376.35  4572.4  374.28  4577.9  371.53  4596.1  367.61  4625.3  362.67
  4649.1  356.01  4696.6  347.93  4740.6  343.49  4784.1  339.03  4889.5  337.58
  4892.2  337.08  4895.5  337.58  4963.6  338.46  5047.4  338.55  5250.5  340.46
    5283  343.22  5358.9  351.99  5373.8  356.05  5397.5  358.28  5426.7  364.99
  5479.6  373.05  5574.6  382.25  5580.1  384.57  5603.8  384.24  5611.5  386.13
#Mann= 5 ,-1 , 0
    4442     .12       0  4889.5     .07       0  4895.5     .12       0
  4963.6     .16       0  5047.4     .12       0
Bank Sta=4740.6,5283
XS Rating Curve= 0 ,0
Exp/Cntr=0.3,0.1

Type RM Length L Ch R = 1 ,61084   ,307,307,307
BEGIN DESCRIPTION:
Mapping XS c5f4612c
END DESCRIPTION:
XS GIS Cut Line= 3
      3717906.32      10691672.8      3717754.41     10692488.77
      3717776.05     10693177.04
#Sta/Elev= 30
  4591.4  389.93  4629.4  387.62  4670.1   382.1  4771.8   360.8  4818.4  353.76
  4823.5  351.58  4904.1  341.02  4944.8  336.98  5074.2  336.98  5130.3  337.02
  5165.5  336.58  5168.3  336.08  5171.5  336.58  5300.8  339.47  5313.5  338.34
    5372  341.39  5409.5  345.05  5467.7  351.42  5602.9  370.73  5662.9  377.42
  5702.9  379.15    5813  377.03  5860.5  378.72    5913  382.95  5958.8  383.27
  6043.1  381.88  6061.1  380.05  6066.1  383.83  6093.1  380.32    6110   382.5
#Mann= 9 ,-1 , 0
  4591.4     .12       0  5074.2     .16       0  5130.3     .12       0
  5165.5     .07       0  5171.5     .12       0  5409.5     .16       0
  5467.7     .12       0  5860.5     .16       0  5958.8     .05       0
Bank Sta=4904.1,5372
XS Rating Curve= 0 ,0
Exp/Cntr=0.3,0.1

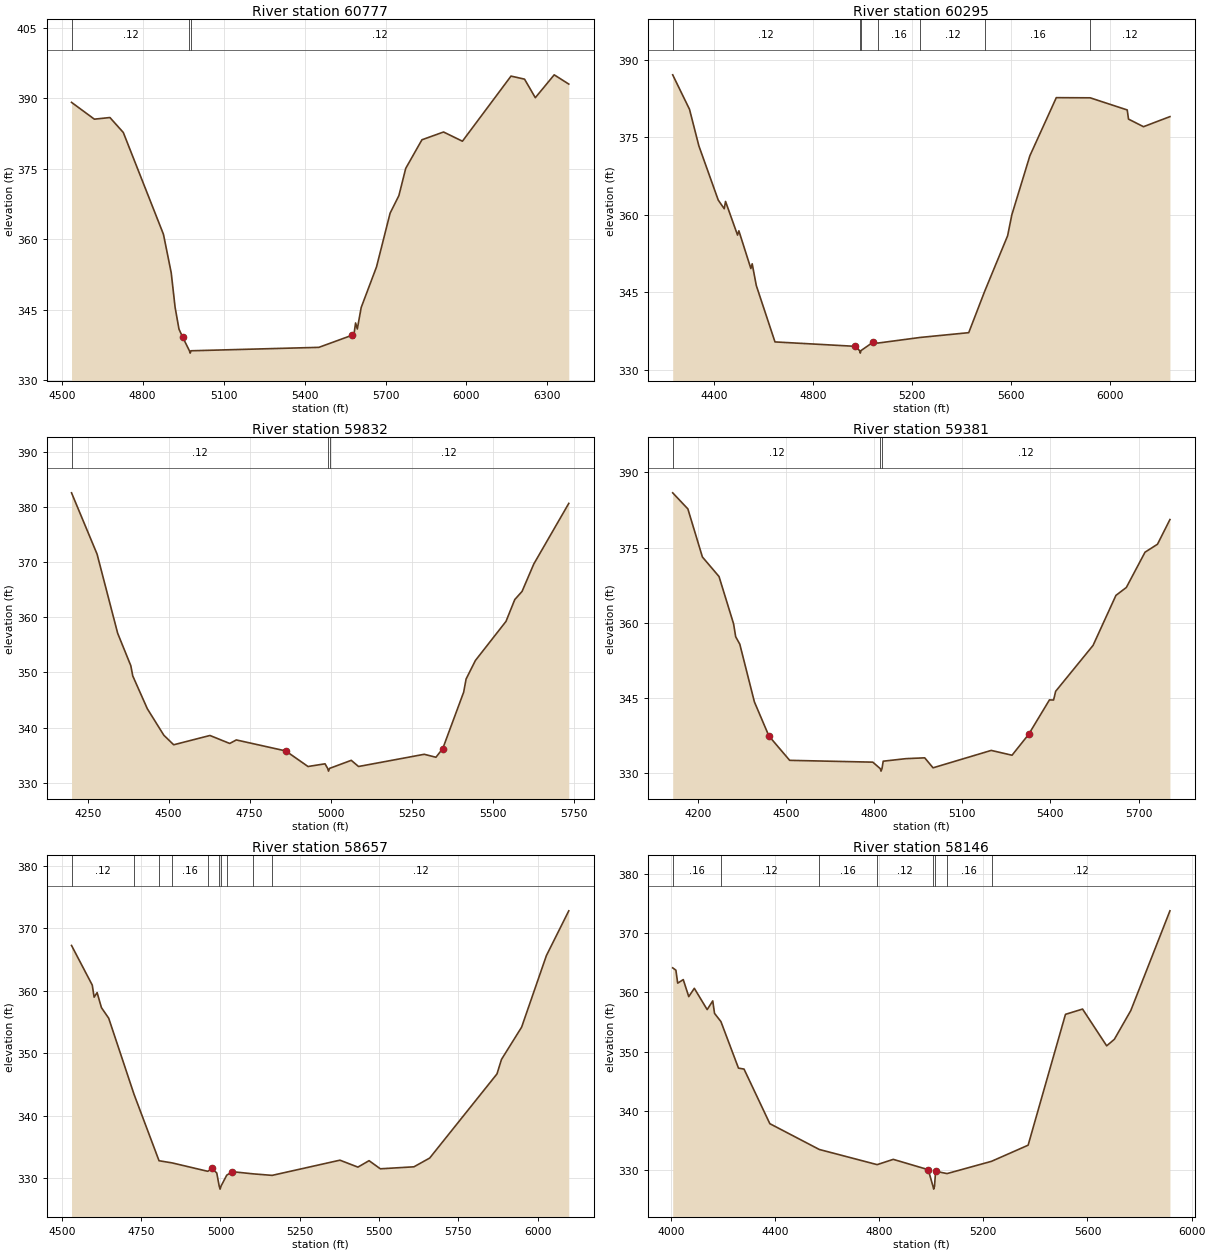
Type RM Length L Ch R = 1 ,60777   ,482,482,482
BEGIN DESCRIPTION:
Mapping XS 34c8e4e5
END DESCRIPTION:
XS GIS Cut Line= 3
      3717867.25     10691568.65      3717107.71     10692514.82
      3717129.41     10693144.13
#Sta/Elev= 30
  4536.3  389.16    4621  385.58  4678.6  385.93  4728.2  382.75    4877  361.08
  4905.8  352.89  4920.2  345.52  4934.6  340.88  4948.6  339.14  4973.3  336.28
    4976  335.78  4979.3  336.28  5453.1  337.01  5574.7  339.56  5581.1  338.96
  5589.1   342.2  5595.5  340.92  5609.9  345.49  5666.7  354.14  5717.1  365.58
  5749.6  369.31    5775  375.11    5835  381.19  5915.1  382.85  5985.1  380.89
  6165.2  394.75  6215.3   394.1  6255.3  390.15  6325.3  395.02  6379.3  393.05
#Mann= 3 ,-1 , 0
  4536.3     .12       0  4973.3     .07       0  4979.3     .12       0
Bank Sta=4948.6,5574.7
XS Rating Curve= 0 ,0
Exp/Cntr=0.3,0.1

Type RM Length L Ch R = 1 ,60295   ,463,463,463
BEGIN DESCRIPTION:
Mapping XS 57a0bd67
END DESCRIPTION:
XS GIS Cut Line= 4
       3717832.5      10691455.8      3717237.91      10691694.5
      3716777.84     10692623.32      3716708.41     10692944.48
#Sta/Elev= 30
  4234.4  387.04  4302.2  380.37    4340  373.29    4418  362.81  4442.2  361.12
  4447.6  362.53    4496  356.02  4501.3  356.85  4549.7  349.55  4555.1  350.46
  4571.6  346.27    4647  335.34  4968.9  334.49  4988.3  333.67  4991.1  333.17
  4994.3  333.67  5041.8  335.26  5062.6  335.12  5233.7  336.21  5428.6  337.13
  5492.6   345.1  5585.5   355.9  5602.4  359.94  5675.2  371.37  5781.8  382.62
  5918.5  382.59  6067.9  380.24  6073.1  378.47  6133.5     377  6240.2  378.95
#Mann= 7 ,-1 , 0
  4234.4     .12       0  4988.3     .07       0  4994.3     .12       0
  5062.6     .16       0  5233.7     .12       0  5492.6     .16       0
  5918.5     .12       0
Bank Sta=4968.9,5041.8
XS Rating Curve= 0 ,0
Exp/Cntr=0.3,0.1

Type RM Length L Ch R = 1 ,59832   ,451,451,451
BEGIN DESCRIPTION:
BEAVER CREEK 90.0
END DESCRIPTION:
XS GIS Cut Line= 3
      3717749.59     10691310.19      3716949.61     10691460.19
      3716349.63     10691860.17
#Sta/Elev= 30
  4200.3  382.66  4279.1  371.53  4342.7  357.14  4383.4  351.22  4389.3  349.38
  4434.3  343.41  4485.2   338.6  4515.7  336.86  4627.6  338.55  4688.6   337.1
    4709  337.74  4861.6  335.74  4930.3  332.91  4982.8   333.4  4990.9  332.57
  4993.6  332.07  4996.9  332.57  5063.8  334.03  5086.3  332.91  5289.1  335.13
  5325.2  334.59  5346.2  336.16  5410.8  346.42  5418.3  348.81  5446.9  352.17
  5541.5  359.29  5568.6  363.26  5591.1  364.74  5627.2  369.71  5735.3  380.74
#Mann= 3 ,-1 , 0
  4200.3     .12       0  4990.9     .07       0  4996.9     .12       0
Bank Sta=4861.6,5346.2
XS Rating Curve= 0 ,0
Exp/Cntr=0.3,0.1

Type RM Length L Ch R = 1 ,59381   ,724,724,724
BEGIN DESCRIPTION:
BEAVER CREEK 89.0
END DESCRIPTION:
XS GIS Cut Line= 2
      3717321.16     10690558.68      3716135.05      10691765.6
#Sta/Elev= 30
  4114.8  385.92  4166.5  382.71  4215.9  373.13  4272.5  369.23  4322.1  359.79
  4329.1  357.24  4343.2  355.74  4392.8  344.25  4442.2  337.44  4512.9  332.58
  4795.8  332.22  4821.1  330.93  4823.8  330.43  4827.1  330.93  4831.2  332.41
    4909  332.92  4972.5  333.08  5000.8  331.09  5198.8  334.56  5269.6   333.6
  5326.1  337.75  5396.9  344.63    5411  344.61  5418.1  346.35  5545.4   355.5
  5623.2  365.47  5658.6  367.05  5722.2  374.08  5764.6  375.67    5807  380.59
#Mann= 3 ,-1 , 0
  4114.8     .12       0  4821.1     .07       0  4827.1     .12       0
Bank Sta=4442.2,5326.1
XS Rating Curve= 0 ,0
Exp/Cntr=0.3,0.1

Type RM Length L Ch R = 1 ,58657   ,511,511,511
BEGIN DESCRIPTION:
BEAVER CREEK 88.0
END DESCRIPTION:
XS GIS Cut Line= 3
      3716749.59     10690260.22      3716499.61     10690660.19
      3715749.58     10691460.22
#Sta/Elev= 30
  4530.3  367.26  4595.7  360.92  4601.6  358.99    4611  359.72  4624.6  357.32
  4647.6  355.62  4727.2  343.49  4806.3  332.83  4847.1  332.49    4960  331.14
  4973.1  331.59  4988.4  330.87    4996  328.79  4998.8  328.29    5002  328.79
  5019.8  330.52  5037.4  331.08  5103.7  330.73    5163  330.49  5376.9  332.92
  5433.5  331.81  5468.7  332.84  5504.3  331.54  5610.3  331.86  5659.9  333.26
  5872.2  346.72  5886.3  349.03  5949.8  354.19    6028  365.64  6098.6   372.8
#Mann= 10 ,-1 , 0
  4530.3     .12       0  4727.2     .16       0  4806.3     .12       0
  4847.1     .16       0    4960     .07       0    4996     .07       0
    5002     .07       0  5019.8     .12       0  5103.7     .05       0
    5163     .12       0
Bank Sta=4973.1,5037.4
XS Rating Curve= 0 ,0
Exp/Cntr=0.3,0.1

Type RM Length L Ch R = 1 ,58146   ,546,546,546
BEGIN DESCRIPTION:
Mapping XS 1fe27e14
END DESCRIPTION:
XS GIS Cut Line= 3
      3716741.37     10689864.66      3715803.89     10690763.08
      3715457.16     10691265.84
#Sta/Elev= 30
  4007.4  364.14  4019.7  363.75  4026.6  361.56    4048  362.16  4069.1  359.29
  4090.5  360.69  4139.8   357.1  4161.2  358.57  4168.1  356.46  4192.6  355.08
    4260  347.23  4281.3  347.07  4380.4  337.86  4570.2  333.51  4792.4  330.95
  4854.3  331.84  4988.6   330.1  5006.7  327.32  5009.5  326.82  5012.7  327.32
  5016.9  329.83  5060.8  329.44  5231.5  331.51  5372.1  334.23  5515.5   356.3
  5581.1  357.19  5673.7  350.99  5703.2  352.09  5766.3  356.94  5916.6  373.76
#Mann= 8 ,-1 , 0
  4007.4     .16       0  4192.6     .12       0  4570.2     .16       0
  4792.4     .12       0  5006.7     .07       0  5012.7     .12       0
  5060.8     .16       0  5231.5     .12       0
Bank Sta=4988.6,5016.9
XS Rating Curve= 0 ,0
Exp/Cntr=0.3,0.1

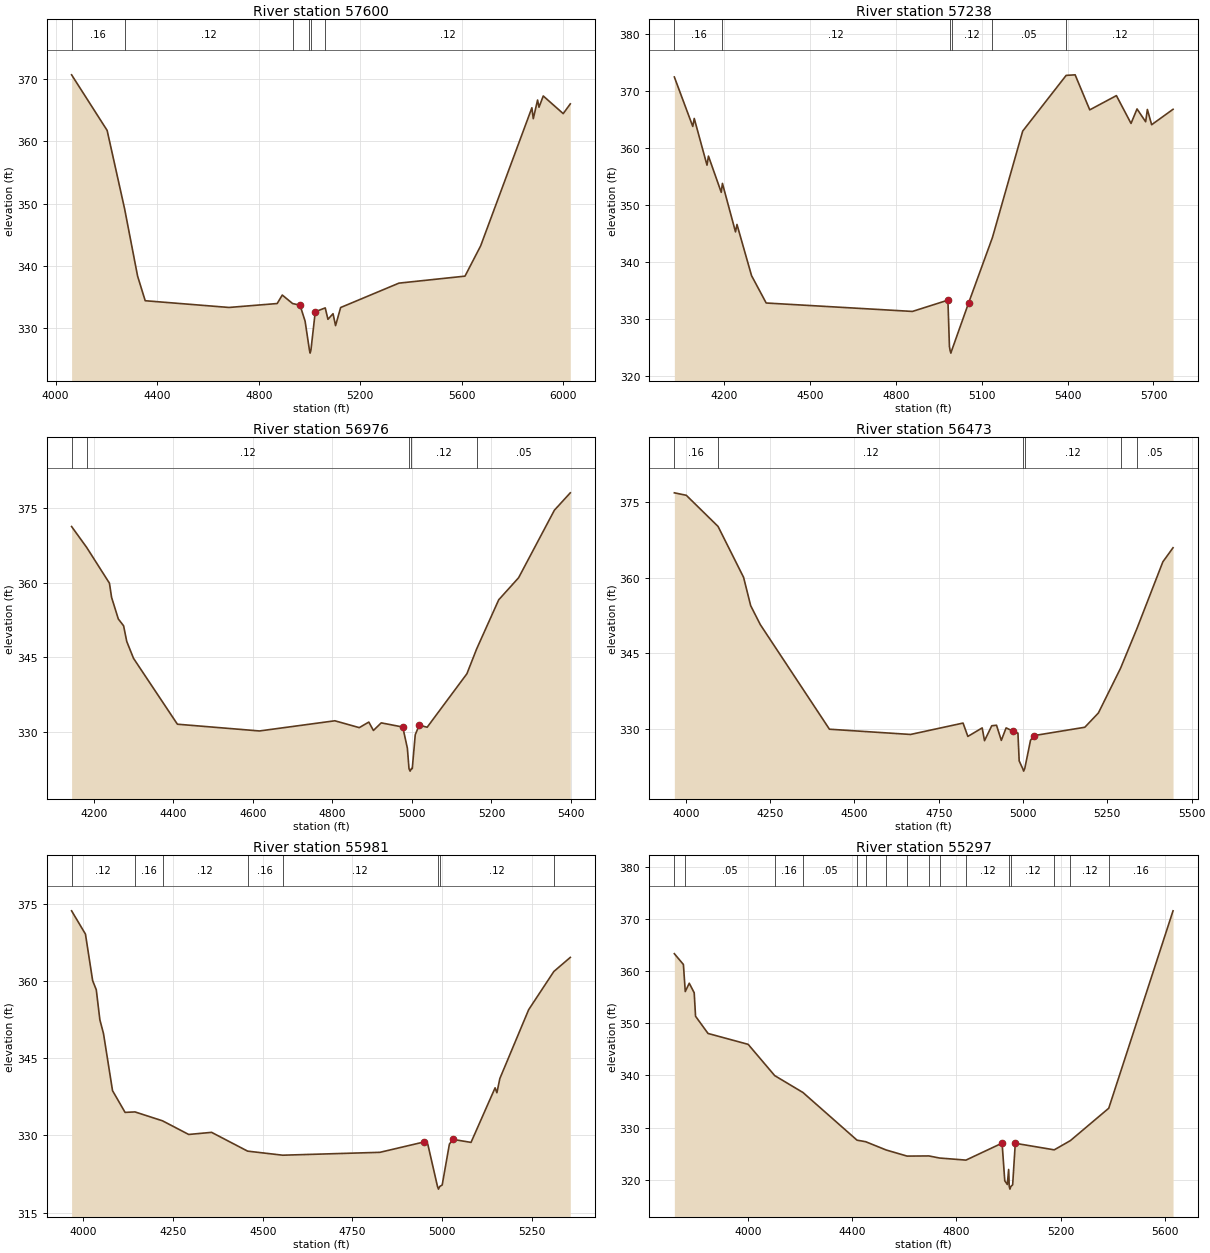
Type RM Length L Ch R = 1 ,57600   ,362,362,362
BEGIN DESCRIPTION:
BEAVER CREEK 86.0
END DESCRIPTION:
XS GIS Cut Line= 3
      3715612.91     10689400.23       3715623.6     10690499.14
      3715239.67      10691275.2
#Sta/Elev= 30
  4062.8  370.65  4202.8  361.74  4271.7  349.16  4322.8  338.39  4352.8  334.44
  4682.8  333.36  4872.8  333.99  4892.8  335.35  4933.5  333.99  4962.8  333.72
  4982.8  331.16  4999.8  326.54  5002.6  326.04  5005.8  326.54  5022.8  332.67
  5062.1  333.29  5072.8  331.46  5092.8  332.36  5102.8  330.45  5122.8  333.35
  5352.6  337.26  5612.7  338.38  5674.4  343.23  5876.3  365.37  5881.8  363.62
  5898.7  366.61  5904.3  365.46  5921.1  367.26  5999.7  364.43  6027.6  365.99
#Mann= 6 ,-1 , 0
  4062.8     .16       0  4271.7     .12       0  4933.5     .16       0
  4999.8     .07       0  5005.8     .16       0  5062.1     .12       0
Bank Sta=4962.8,5022.8
XS Rating Curve= 0 ,0
Exp/Cntr=0.3,0.1

Type RM Length L Ch R = 1 ,57238   ,262,262,262
BEGIN DESCRIPTION:
Mapping XS d9579b68
END DESCRIPTION:
XS GIS Cut Line= 4
      3715508.75     10689426.24      3715326.46     10690289.99
      3715230.97     10690619.85      3714944.57     10691049.46
#Sta/Elev= 30
    4026  372.52  4090.4  363.84  4095.5  365.24  4140.1  357.04  4145.2  358.63
  4189.9  352.27    4194  353.84  4239.7  345.33  4244.8  346.63  4295.8  337.64
  4346.9  332.84  4857.9  331.36  4981.9  333.34  4987.2   325.2  4989.4  324.54
  4992.2  324.04  4995.4  324.54  5054.4  332.88  5137.4  344.33  5243.2  363.02
    5395   372.8  5426.4   372.9  5477.5  366.75  5570.6  369.25  5621.7  364.37
  5642.7  366.91  5672.8  364.66  5678.8  366.82  5693.8  364.14  5768.5  366.85
#Mann= 6 ,-1 , 0
    4026     .16       0    4194     .12       0  4989.4     .07       0
  4995.4     .12       0  5137.4     .05       0    5395     .12       0
Bank Sta=4981.9,5054.4
XS Rating Curve= 0 ,0
Exp/Cntr=0.3,0.1

Type RM Length L Ch R = 1 ,56976   ,503,503,503
BEGIN DESCRIPTION:
BEAVER CREEK 85.0
END DESCRIPTION:
XS GIS Cut Line= 3
      3715349.61     10689510.18      3715049.61     10690310.19
      3715049.61     10690710.18
#Sta/Elev= 30
  4144.1  371.33  4181.9  367.14  4239.3  359.92  4244.7  357.06  4261.6  352.72
  4274.9  351.34  4282.9  348.17  4299.9  344.78  4410.2  331.52  4616.7  330.16
  4806.3  332.21  4867.7  330.83  4891.7  331.95  4903.3  330.26  4922.9  331.79
  4977.1  330.95  4988.7  326.69  4992.8  322.57  4995.6  322.07  4998.8  322.57
    5001  322.57  5008.5   329.4  5018.5  331.32  5038.5  330.91  5138.5  341.69
  5162.9  346.67  5218.5  356.58  5268.5  361.02  5358.5  374.62  5398.5  378.12
#Mann= 5 ,-1 , 0
  4144.1     .16       0  4181.9     .12       0  4992.8     .07       0
  4998.8     .12       0  5162.9     .05       0
Bank Sta=4977.1,5018.5
XS Rating Curve= 0 ,0
Exp/Cntr=0.3,0.1

Type RM Length L Ch R = 1 ,56473   ,492,492,492
BEGIN DESCRIPTION:
BEAVER CREEK 84.0
END DESCRIPTION:
XS GIS Cut Line= 3
      3715349.61     10689410.19      3714649.61     10690160.19
      3714699.61     10690610.21
#Sta/Elev= 30
  3966.1  376.82  4001.5  376.33  4095.7  370.15  4171.3  360.06  4192.5  354.41
  4220.9  350.67    4426  329.89  4666.4  328.85  4822.2  331.11  4836.4  328.46
  4878.9  330.15  4885.8  327.61  4907.3  330.58  4921.4  330.68  4935.6  327.67
  4949.8  330.15  4970.8  329.49  4984.9  329.11  4988.6   323.6  4999.1  322.07
  5001.8  321.57  5005.1  322.07  5022.2  327.69  5032.3  328.62  5183.2  330.28
  5223.4  333.11  5289.2     342  5338.7  350.03  5414.6  363.12  5444.8  365.92
#Mann= 6 ,-1 , 0
  3966.1     .16       0  4095.7     .12       0  4999.1     .07       0
  5005.1     .12       0  5289.2     .16       0  5338.7     .05       0
Bank Sta=4970.8,5032.3
XS Rating Curve= 0 ,0
Exp/Cntr=0.3,0.1

Type RM Length L Ch R = 1 ,55981   ,684,684,684
BEGIN DESCRIPTION:
BEAVER CREEK 83.0
END DESCRIPTION:
XS GIS Cut Line= 2
       3714315.3     10689001.71      3714185.15      10690385.7
#Sta/Elev= 30
  3967.2  373.64  4005.8  369.12  4025.9  360.07    4036   358.3    4046  352.47
  4056.1   349.8  4081.3   338.7  4116.3  334.48  4143.9  334.57  4220.7  332.84
  4293.6  330.19  4357.4   330.6  4457.9  326.95  4555.8  326.16  4826.7  326.72
    4950  328.74    4960  328.33  4987.2  320.07  4989.9  319.57  4993.2  320.07
  5000.2  320.37  5020.3  328.31  5030.3  329.23  5080.6  328.65  5147.7  339.25
  5152.7  338.29  5160.9  341.05  5241.3  354.44  5311.5  361.86  5357.3  364.59
#Mann= 8 ,-1 , 0
  3967.2     .12       0  4143.9     .16       0  4220.7     .12       0
  4457.9     .16       0  4555.8     .12       0  4987.2     .07       0
  4993.2     .12       0  5311.5     .16       0
Bank Sta=4950,5030.3
XS Rating Curve= 0 ,0
Exp/Cntr=0.3,0.1

Type RM Length L Ch R = 1 ,55297   ,120,120,120
BEGIN DESCRIPTION:
BEAVER CREEK 82.0
END DESCRIPTION:
XS GIS Cut Line= 6
      3714193.78     10688784.65      3714085.27     10689223.03
      3713998.47       10689414.      3713911.66     10689557.23
      3713616.52     10689787.26       3713581.8     10690494.71
#Sta/Elev= 30
  3717.3  363.37  3752.1   361.3  3759.2   356.1  3774.5   357.7  3793.5  355.87
  3798.7  351.36  3846.6  348.06  4000.6  345.97  4102.4  339.97  4210.8  336.73
  4418.3  327.58  4451.6  327.28  4530.3  325.69  4610.5  324.52  4694.4  324.55
    4735  324.15  4836.4  323.75  4975.1  327.01  4985.3  319.79  4995.1  319.07
  5000.2  321.96  5002.5  318.68  5005.2  318.18  5008.5  318.68  5015.6     319
  5025.7  326.98  5175.2  325.72  5237.1  327.49  5384.4  333.71  5631.1   371.6
#Mann= 16 ,-1 , 0
  3717.3     .16       0  3759.2     .05       0  4102.4     .16       0
  4210.8     .05       0  4418.3     .12       0  4451.6     .05       0
  4530.3     .16       0  4610.5     .08       0  4694.4     .16       0
    4735     .05       0  4836.4     .12       0  5002.5     .07       0
  5008.5     .12       0  5175.2     .05       0  5237.1     .12       0
  5384.4     .16       0
Bank Sta=4975.1,5025.7
XS Rating Curve= 0 ,0
Exp/Cntr=0.3,0.1

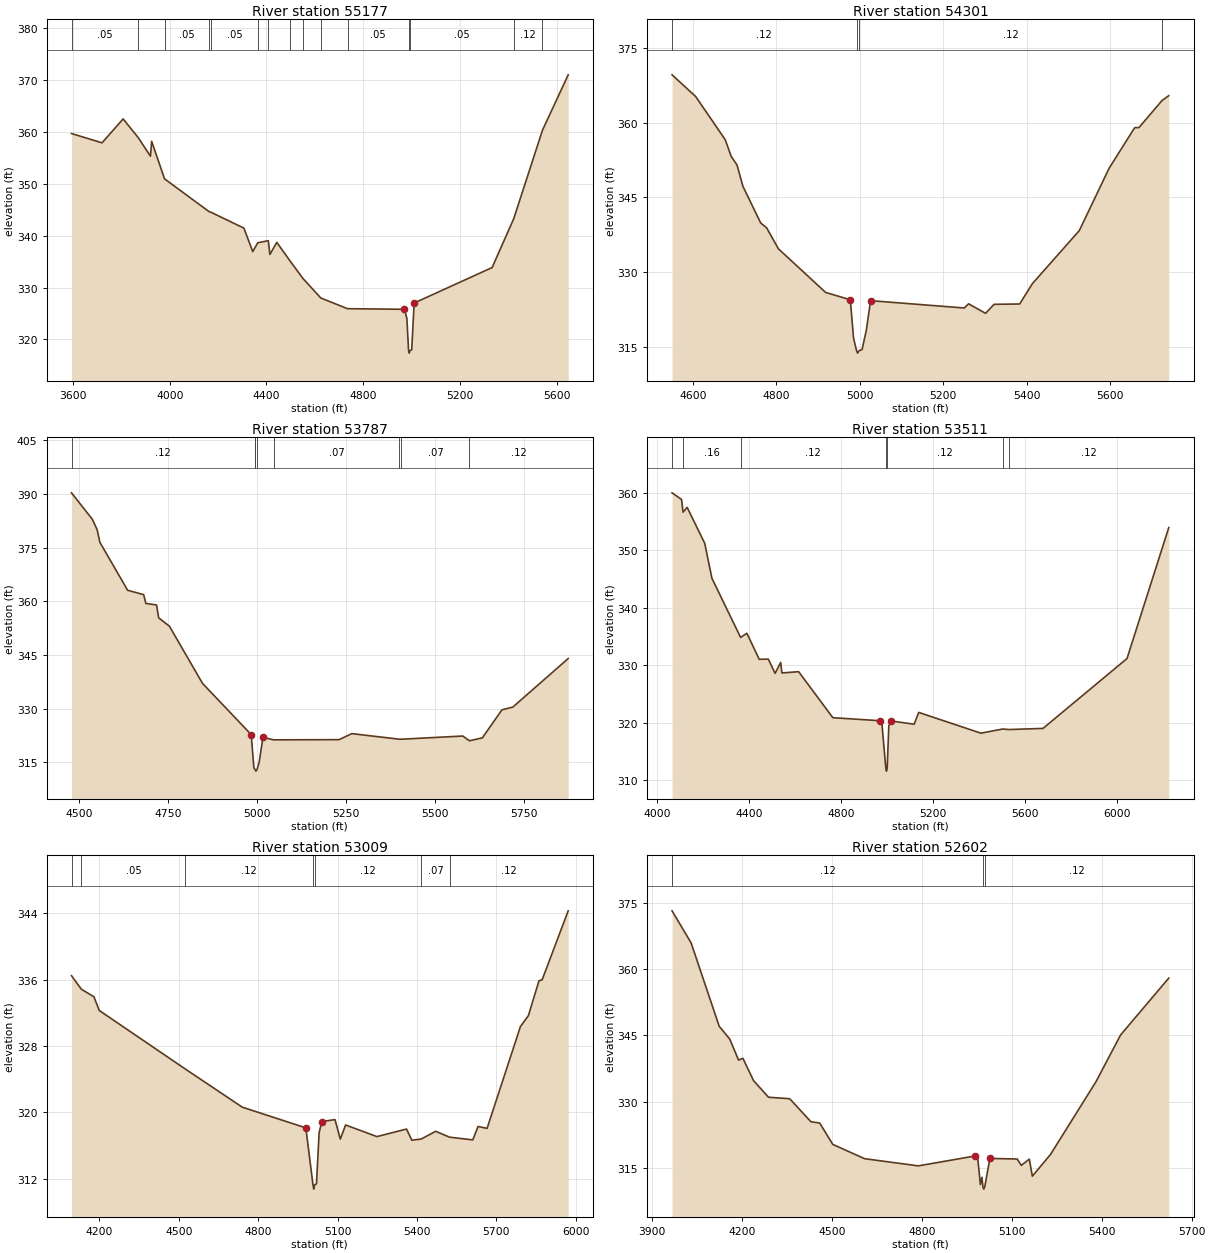
Type RM Length L Ch R = 1 ,55177   ,876,876,876
BEGIN DESCRIPTION:
BEAVER CREEK 81.0
END DESCRIPTION:
XS GIS Cut Line= 6
      3714115.66     10688693.47      3713981.11     10689227.37
      3713863.92       10689414.      3713564.44     10689626.67
      3713494.99     10689717.82      3713403.85      10690512.1
#Sta/Elev= 30
  3593.3  359.69  3719.6   357.9  3806.9  362.51  3868.6  358.95  3919.9  355.33
    3925  358.19  3978.1  350.96    4162  344.65  4172.2  344.47  4306.6  341.45
  4343.1  336.92  4363.9  338.63  4407.5  339.03  4414.1  336.38  4442.6  338.71
  4499.1  335.02  4551.3  331.72  4624.7  327.98  4735.2  325.92  4970.8   325.8
  4980.8  324.01  4987.8  317.85  4990.6  317.35  4993.8  317.85  5000.8  317.99
  5010.8  327.01  5333.4  333.85  5422.8  343.26  5541.8  360.34  5648.2  371.01
#Mann= 15 ,-1 , 0
  3593.3     .05       0  3868.6     .12       0  3978.1     .05       0
    4162     .12       0  4172.2     .05       0  4363.9      .1       0
  4407.5     .05       0  4499.1     .16       0  4551.3     .05       0
  4624.7      .1       0  4735.2     .05       0  4987.8     .04       0
  4993.8     .05       0  5422.8     .12       0  5541.8     .05       0
Bank Sta=4970.8,5010.8
XS Rating Curve= 0 ,0
Exp/Cntr=0.3,0.1

Type RM Length L Ch R = 1 ,54301   ,514,514,514
BEGIN DESCRIPTION:
BEAVER CREEK 80.0
END DESCRIPTION:
XS GIS Cut Line= 3
      3713049.63     10689310.16      3712749.61     10689610.19
      3712899.62     10690360.24
#Sta/Elev= 30
  4550.5  369.62  4607.1  365.26  4677.8   356.6    4692  353.27  4706.1  351.51
  4720.2  347.23  4762.7  339.88  4776.8  338.92  4805.1   334.7  4918.2  325.94
  4977.3  324.47    4985  316.77  4992.2  314.26  4994.9  313.76  4998.2  314.26
  5005.4  314.48  5015.6  318.35  5025.8  324.29  5250.1  322.82  5260.3  323.66
  5301.1  321.75  5321.5  323.56  5382.7  323.62  5413.3  327.72  5525.5  338.35
  5596.9  350.87  5658.1  359.02  5668.3  359.03  5723.8  364.48  5739.7  365.43
#Mann= 4 ,-1 , 0
  4550.5     .12       0  4992.2     .07       0  4998.2     .12       0
  5723.8     .05       0
Bank Sta=4977.3,5025.8
XS Rating Curve= 0 ,0
Exp/Cntr=0.3,0.1

Type RM Length L Ch R = 1 ,53787   ,276,276,276
BEGIN DESCRIPTION:
BEAVER CREEK 79.0
END DESCRIPTION:
XS GIS Cut Line= 3
      3712649.61     10688910.19      3712349.61     10689360.19
       3712649.6     10690160.16
#Sta/Elev= 30
  4479.2  390.33  4537.8  382.93  4551.3  380.01  4558.8  376.52  4636.9   363.1
    4682  361.87    4688  359.42  4718.1  358.99  4724.1  355.39  4754.1  353.07
  4847.3  337.06    4984  322.76  4991.5  313.44  4993.9  313.13  4994.5  313.05
  4997.3  312.55  5000.5  313.05  5006.5  315.13    5017  322.03  5046.9  321.29
    5231  321.35  5266.6  323.03  5400.3  321.47  5405.8  321.47  5578.1  322.36
    5597  321.03  5633.2  321.85  5688.4  329.69  5718.7  330.44  5874.4  344.02
#Mann= 8 ,-1 , 0
  4479.2     .12       0  4993.9     .16       0  4994.5     .07       0
  5000.5     .16       0  5046.9     .07       0  5400.3     .12       0
  5405.8     .07       0    5597     .12       0
Bank Sta=4984,5017
XS Rating Curve= 0 ,0
Exp/Cntr=0.3,0.1

Type RM Length L Ch R = 1 ,53511   ,502,502,502
BEGIN DESCRIPTION:
Mapping XS c2429761
END DESCRIPTION:
XS GIS Cut Line= 3
      3712370.59     10688418.26      3712110.17     10689069.34
      3712058.12     10690526.48
#Sta/Elev= 30
  4066.4  359.99  4107.8  358.83  4114.2  356.63    4132  357.46  4208.5   351.2
  4239.7  345.13  4364.3  334.85  4391.6  335.57  4445.4  331.04  4484.8  331.08
  4514.4   328.6  4538.6   330.5    4544  328.67  4616.7  328.89  4765.4  320.89
  4968.6  320.37  4978.6  319.92  4995.6   312.1  4998.4   311.6  5001.6   312.1
  5008.6  319.46  5018.6  320.32  5118.7  319.76  5138.7  321.81  5408.9   318.2
  5503.9  318.92  5530.9  318.83  5679.1  319.03  6044.2  331.18  6225.7  353.95
#Mann= 7 ,-1 , 0
  4066.4     .12       0  4114.2     .16       0  4364.3     .12       0
  4995.6     .07       0  5001.6     .12       0  5503.9     .07       0
  5530.9     .12       0
Bank Sta=4968.6,5018.6
XS Rating Curve= 0 ,0
Exp/Cntr=0.3,0.1

Type RM Length L Ch R = 1 ,53009   ,407,407,407
BEGIN DESCRIPTION:
Mapping XS 9b56d19b
END DESCRIPTION:
XS GIS Cut Line= 2
       3711628.4     10688535.52      3711719.54     10690410.51
#Sta/Elev= 30
  4094.2  336.49  4131.5  334.86    4179  333.95    4199   332.3  4524.4  325.23
  4739.6  320.63  4979.9  318.13  5006.9  311.24  5009.7  310.74  5012.9  311.24
    5020  311.38    5030  317.53    5040  318.89    5090  319.13  5110.1  316.77
  5130.1  318.48  5248.6  317.08  5360.4  317.99  5380.4  316.64  5416.3  316.79
  5470.5  317.72  5522.8  317.01  5610.7  316.68  5630.7   318.3  5664.8  318.07
  5790.9  330.36  5820.9  331.67    5861  335.89  5872.9     336  5971.4  344.32
#Mann= 7 ,-1 , 0
  4094.2     .16       0  4131.5     .05       0  4524.4     .12       0
  5006.9     .07       0  5012.9     .12       0  5416.3     .07       0
  5522.8     .12       0
Bank Sta=4979.9,5040
XS Rating Curve= 0 ,0
Exp/Cntr=0.3,0.1

Type RM Length L Ch R = 1 ,52602   ,527,527,527
BEGIN DESCRIPTION:
BEAVER CREEK 77.0
END DESCRIPTION:
XS GIS Cut Line= 3
      3710699.59     10688710.17      3711299.61     10689510.19
       3711199.6     10690160.22
#Sta/Elev= 30
  3965.9  373.12  4029.5  365.87  4123.2  347.02  4158.6   344.1  4187.8  339.37
  4202.4  339.77  4237.8  334.73  4287.8  330.97  4358.6  330.63  4429.5  325.42
  4458.6  325.14  4502.4   320.3  4608.6  317.07  4787.8  315.45    4976  317.67
  4986.2  317.03    4995  311.23  5000.1  312.87  5003.4  310.69  5006.1  310.19
  5009.4  310.69  5026.6  317.13  5117.7     317  5131.6  315.57  5158.2  316.97
  5168.3  313.12    5229  318.04  5380.7  334.48    5463  345.07  5623.6  357.91
#Mann= 3 ,-1 , 0
  3965.9     .12       0  5003.4     .07       0  5009.4     .12       0
Bank Sta=4976,5026.6
XS Rating Curve= 0 ,0
Exp/Cntr=0.3,0.1