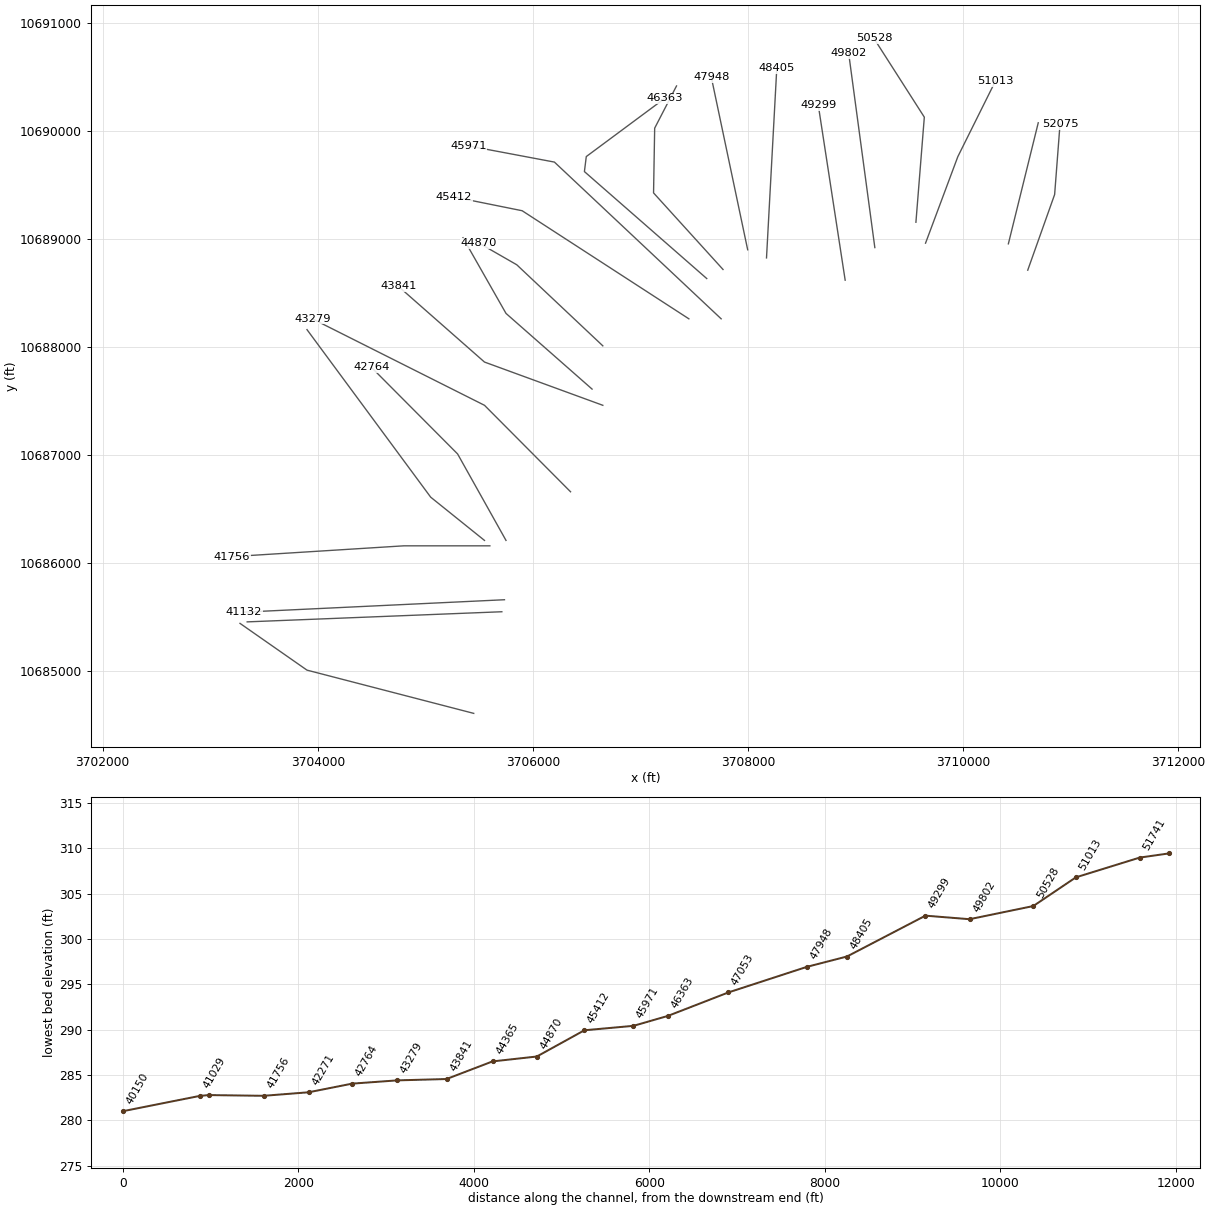
HEC-RAS study BEAVER CREEK.prj: BEAVER CREEK Base Level Engineering

--- BEAVER CREEK.g01 (geometry) --- (continued)

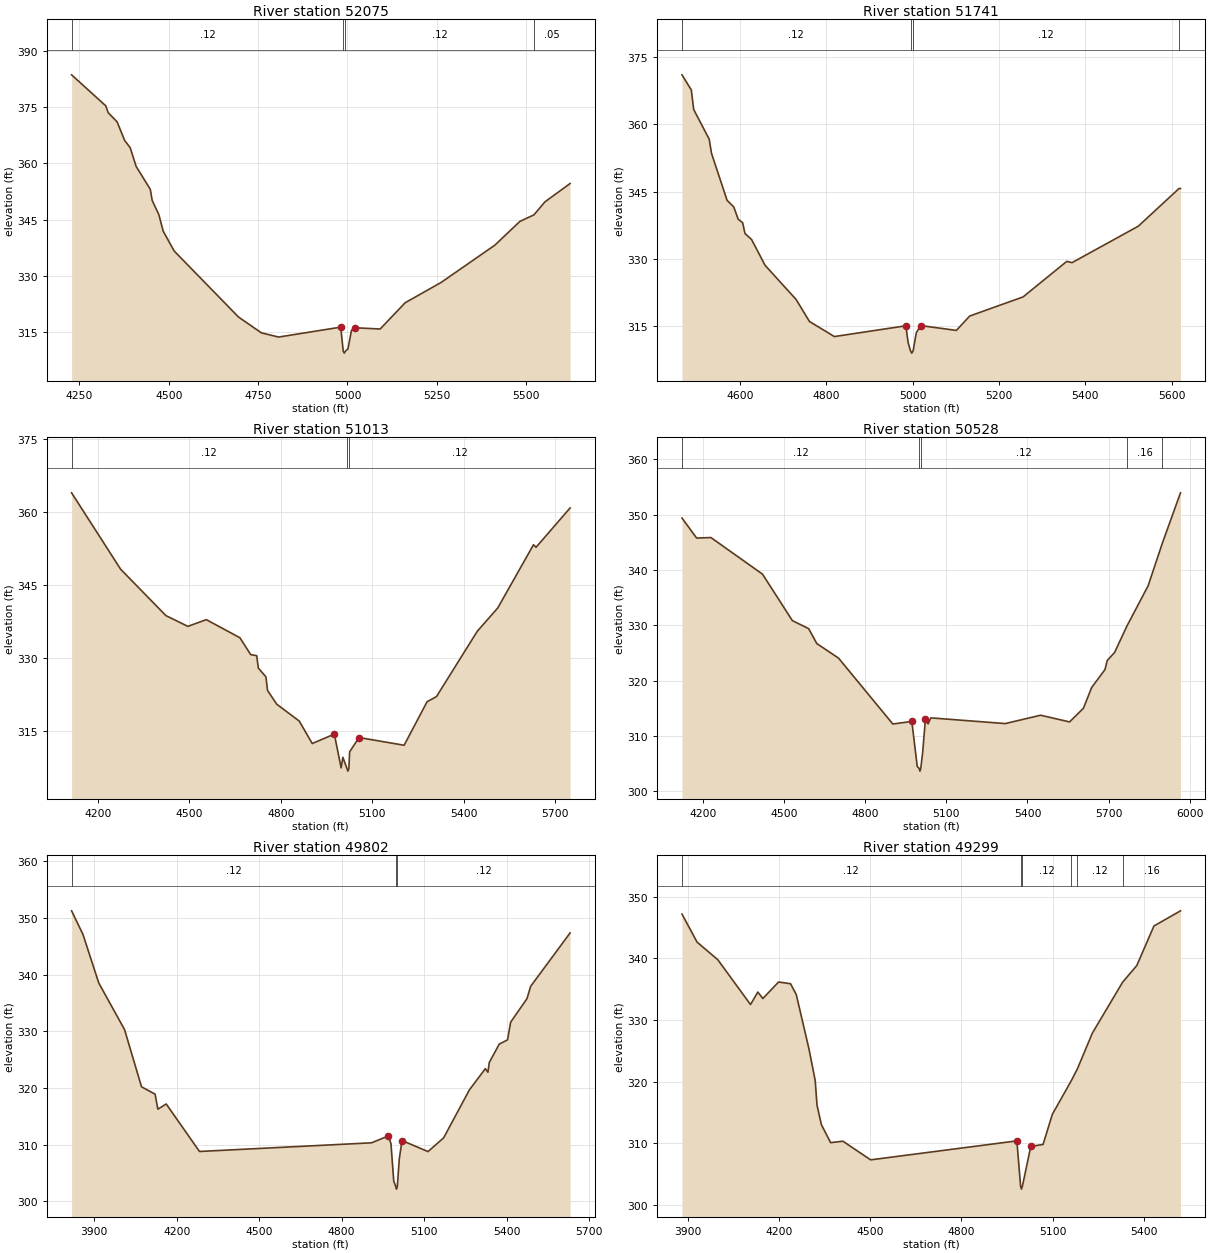
Type RM Length L Ch R = 1 ,52075   ,334,334,334
BEGIN DESCRIPTION:
BEAVER CREEK 76.0
END DESCRIPTION:
XS GIS Cut Line= 3
      3710599.62     10688710.21      3710849.61     10689410.19
      3710899.61     10690060.18
#Sta/Elev= 30
  4227.9  383.59  4323.4  375.34  4330.4  373.49  4355.3  371.06  4376.5  366.09
  4391.9  364.18  4408.4  359.21  4448.2  353.07  4453.5   350.1  4472.1  346.33
  4484.3  341.93  4515.1  336.63  4695.1  319.04  4758.8  314.84  4807.1   313.7
  4981.2  316.35  4988.2  309.92    4991  309.42  4994.2  309.92  5001.3  310.54
  5011.3  315.49  5021.3  316.18  5091.5  315.85  5161.7  322.86    5262  328.25
  5412.5  338.19  5482.7  344.53  5521.8  346.26  5552.9  349.75  5623.1  354.62
#Mann= 4 ,-1 , 0
  4227.9     .12       0  4988.2     .07       0  4994.2     .12       0
  5521.8     .05       0
Bank Sta=4981.2,5021.3
XS Rating Curve= 0 ,0
Exp/Cntr=0.3,0.1

Type RM Length L Ch R = 1 ,51741   ,728,728,728
BEGIN DESCRIPTION:
BEAVER CREEK 75.0
END DESCRIPTION:
XS GIS Cut Line= 2
      3710419.47     10688953.91      3710697.24     10690073.68
#Sta/Elev= 30
  4466.4  371.08    4488   367.7  4493.5  363.34  4529.4  356.71  4534.7  353.56
  4570.8  343.06  4586.2   341.6  4596.5  338.84  4606.8  338.07  4612.2  335.66
  4627.4  334.33  4658.7  328.56  4730.4  320.95  4761.4  316.03    4819  312.66
  4984.5  315.06  4989.7  311.34  4995.3  309.46  4998.1  308.96  5001.3  309.46
  5008.6  313.48  5018.9  315.11  5101.4  314.03  5132.3  317.24  5255.9  321.51
  5356.9  329.44  5369.2  329.16  5522.4  337.29  5616.8  345.71  5620.1  345.71
#Mann= 4 ,-1 , 0
  4466.4     .12       0  4995.3     .07       0  5001.3     .12       0
  5616.8     .05       0
Bank Sta=4984.5,5018.9
XS Rating Curve= 0 ,0
Exp/Cntr=0.3,0.1

Type RM Length L Ch R = 1 ,51013   ,485,485,485
BEGIN DESCRIPTION:
BEAVER CREEK 74.0
END DESCRIPTION:
XS GIS Cut Line= 3
       3709649.6     10688960.17      3709949.61     10689760.19
      3710299.59     10690460.15
#Sta/Elev= 30
    4113  363.86  4274.1  348.19  4422.7  338.68  4494.8  336.47  4555.4  337.85
  4665.7  334.14  4701.3  330.67  4720.9  330.46  4726.2  327.93  4751.2  326.11
  4756.5  323.33  4786.8   320.5  4860.6  317.05  4903.3  312.44  4975.8  314.37
  4998.2  307.44  5003.8  309.62  5017.5  307.28  5020.3  306.78  5023.5  307.28
  5026.1  310.74  5056.9  313.67    5205  312.09  5280.5  321.02  5311.2  322.06
  5445.4  335.48  5512.5  340.25  5629.9  353.22  5638.2  352.69    5750  360.76
#Mann= 3 ,-1 , 0
    4113     .12       0  5017.5     .07       0  5023.5     .12       0
Bank Sta=4975.8,5056.9
XS Rating Curve= 0 ,0
Exp/Cntr=0.3,0.1

Type RM Length L Ch R = 1 ,50528   ,726,726,726
BEGIN DESCRIPTION:
BEAVER CREEK 73.0
END DESCRIPTION:
XS GIS Cut Line= 3
       3709560.1     10689153.57      3709638.22      10690125.8
      3709169.48     10690854.96
#Sta/Elev= 30
  4123.4  349.39  4177.5  345.77  4230.4  345.86    4421  339.24  4531.3  330.84
  4591.5  329.39  4621.6  326.69  4701.9  324.06  4902.5  312.14  4972.8  312.61
  4992.8  304.46  4999.8  304.12  5002.6  303.62  5005.8  304.12  5012.9  307.06
  5022.9  312.98  5032.9  312.16    5043  313.25    5318  312.22  5448.7  313.73
  5555.7  312.52    5607     315  5637.4  318.75  5686.5  321.98  5694.8  323.62
  5722.2  325.09  5767.4  329.83  5846.1  337.15  5898.7  344.86  5965.6  353.95
#Mann= 5 ,-1 , 0
  4123.4     .12       0  4999.8     .07       0  5005.8     .12       0
  5767.4     .16       0  5898.7     .12       0
Bank Sta=4972.8,5022.9
XS Rating Curve= 0 ,0
Exp/Cntr=0.3,0.1

Type RM Length L Ch R = 1 ,49802   ,503,503,503
BEGIN DESCRIPTION:
BEAVER CREEK 72.0
END DESCRIPTION:
XS GIS Cut Line= 2
      3709178.15     10688919.21      3708935.16     10690715.65
#Sta/Elev= 30
    3818  351.26  3859.4   347.1  3916.9  338.53  4010.7   330.3  4072.3  320.22
  4121.7  318.92  4131.8  316.27  4162.1  317.19  4283.2  308.81  4908.8  310.34
  4969.4  311.54  4979.5  310.19  4989.5  303.58  4996.6  302.67  4999.4  302.17
  5002.6  302.67  5009.7  307.53  5019.8  310.74  5114.2  308.79  5171.2  311.23
  5264.5  319.67  5322.6  323.42    5332  322.79  5337.1  324.52    5373  327.74
  5403.3   328.5  5414.8  331.63  5473.9  335.76  5487.4  337.94  5630.8  347.36
#Mann= 3 ,-1 , 0
    3818     .12       0  4996.6     .07       0  5002.6     .12       0
Bank Sta=4969.4,5019.8
XS Rating Curve= 0 ,0
Exp/Cntr=0.3,0.1

Type RM Length L Ch R = 1 ,49299   ,894,894,894
BEGIN DESCRIPTION:
Mapping XS 871e6e66
END DESCRIPTION:
XS GIS Cut Line= 2
      3708902.42     10688617.64      3708652.58     10690236.38
#Sta/Elev= 30
  3881.7  347.19  3931.3  342.64  3999.5  339.78  4106.9  332.51  4130.9  334.54
  4147.4  333.49  4199.1  336.17  4238.4  335.89  4257.1  334.15  4299.1  325.27
  4319.4  320.19  4325.3  316.21  4339.6  313.04    4370   310.1  4410.4  310.34
  4501.5  307.31    4982  310.39  4994.3  303.06    4997  302.56  5000.3  303.06
  5027.7  309.49  5068.1  309.81  5098.5  314.69  5161.4  320.21  5180.8  322.07
    5230  327.87  5329.2  336.12    5376  338.84  5432.4  345.26  5519.6  347.72
#Mann= 6 ,-1 , 0
  3881.7     .12       0  4994.3     .07       0  5000.3     .12       0
  5161.4     .16       0  5180.8     .12       0  5329.2     .16       0
Bank Sta=4982,5027.7
XS Rating Curve= 0 ,0
Exp/Cntr=0.3,0.1

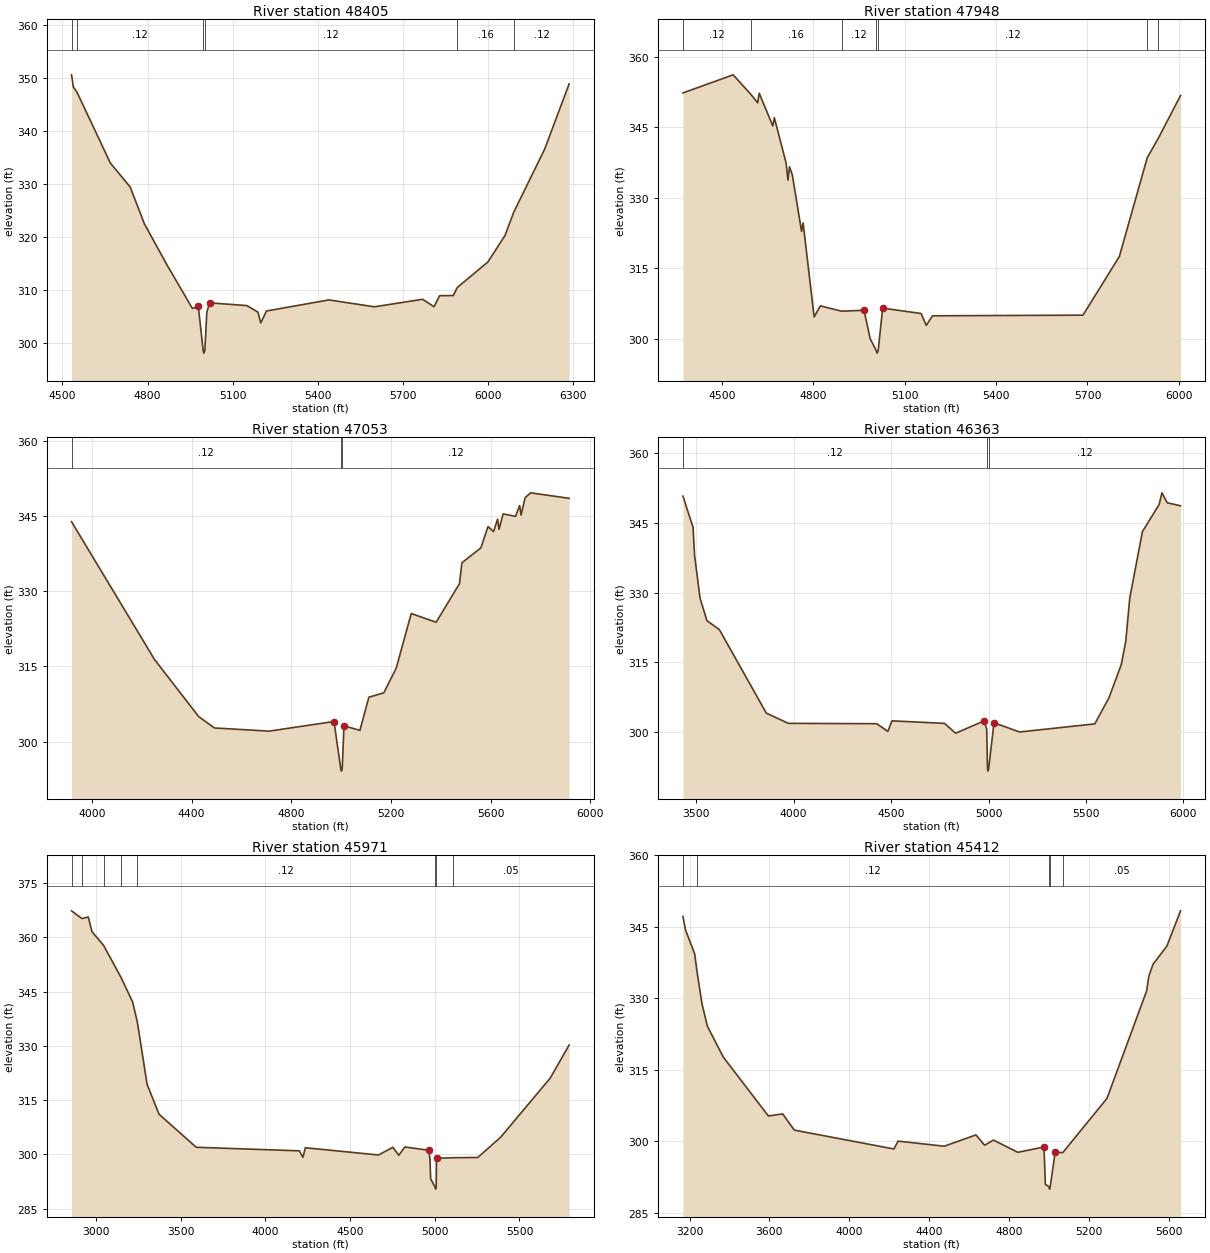
Type RM Length L Ch R = 1 ,48405   ,457,457,457
BEGIN DESCRIPTION:
BEAVER CREEK 71.0
END DESCRIPTION:
XS GIS Cut Line= 2
      3708171.21     10688823.69      3708266.64      10690576.2
#Sta/Elev= 30
    4532  350.58  4538.5  348.25  4550.9  347.34  4668.7  333.95  4738.8  329.41
  4788.9  322.47    4869  314.68  4958.2   306.5  4979.2  306.86  4996.2  298.56
  4998.9  298.06  5002.2  298.56  5009.2  305.79  5019.2  307.55  5150.3  307.03
  5189.5   305.8  5199.5  303.76  5219.5  306.01  5439.8   308.1  5600.1   306.8
  5770.3  308.22  5810.4  306.82  5830.4   308.9  5878.7  308.93  5892.5  310.44
  6000.7  315.27  6060.8  320.25  6091.9  324.67    6201  336.58  6287.1  348.87
#Mann= 6 ,-1 , 0
    4532     .16       0  4550.9     .12       0  4996.2     .07       0
  5002.2     .12       0  5892.5     .16       0  6091.9     .12       0
Bank Sta=4979.2,5019.2
XS Rating Curve= 0 ,0
Exp/Cntr=0.3,0.1

Type RM Length L Ch R = 1 ,47948   ,895,895,895
BEGIN DESCRIPTION:
Mapping XS f91bc3bb
END DESCRIPTION:
XS GIS Cut Line= 2
      3707996.16     10688898.91      3707657.91      10690496.5
#Sta/Elev= 30
  4372.4  352.28  4537.3  356.13  4595.2  351.98  4617.6  350.17  4622.7  352.22
  4667.3  345.26  4672.4     347    4711  337.36    4717  333.72  4722.1  336.58
  4731.5  334.79  4761.6  322.82  4766.7  324.63    4803  304.62  4823.5  306.97
  4893.4  305.84  4966.6  306.04    4987  299.97    5007  297.42  5009.8  296.92
    5013  297.42  5027.9  306.49    5154  305.35    5171  302.83  5191.4  304.86
  5685.3     305  5804.7  317.49    5896  338.46    5933   342.7  6005.4  351.72
#Mann= 7 ,-1 , 0
  4372.4     .12       0  4595.2     .16       0  4893.4     .12       0
    5007     .07       0    5013     .12       0    5896     .16       0
    5933     .12       0
Bank Sta=4966.6,5027.9
XS Rating Curve= 0 ,0
Exp/Cntr=0.3,0.1

Type RM Length L Ch R = 1 ,47053   ,690,690,690
BEGIN DESCRIPTION:
Mapping XS 3a522033
END DESCRIPTION:
XS GIS Cut Line= 4
      3707766.98     10688716.66      3707121.16     10689424.97
      3707131.58     10690023.93      3707334.67      10690414.5
#Sta/Elev= 30
  3917.9  343.92  4251.1   316.4  4428.1  305.01  4491.6  302.72  4711.2  302.09
  4971.7  304.01  4998.7   294.6  5001.4   294.1  5004.7   294.6  5011.7  303.16
  5075.7  302.24  5111.7  308.87  5171.7  309.74  5221.7   314.7  5281.7  325.58
  5381.7  323.84  5475.5  331.55  5485.1  335.71  5561.4   338.7    5590  342.95
  5612.1  341.94  5628.6  344.45  5634.2   342.4  5650.7  345.48  5700.6     345
    5717  347.15  5722.7  345.25  5739.1  348.73  5761.3  349.69  5915.7  348.59
#Mann= 3 ,-1 , 0
  3917.9     .12       0  4998.7     .07       0  5004.7     .12       0
Bank Sta=4971.7,5011.7
XS Rating Curve= 0 ,0
Exp/Cntr=0.3,0.1

Type RM Length L Ch R = 1 ,46363   ,392,392,392
BEGIN DESCRIPTION:
BEAVER CREEK 68.0
END DESCRIPTION:
XS GIS Cut Line= 4
      3707615.66     10688632.74       3706478.5     10689622.33
      3706495.86     10689761.22      3707224.79     10690299.24
#Sta/Elev= 30
  3431.8  350.78  3483.7  344.06  3491.3  338.07  3519.4  328.83  3554.9  323.94
  3618.6  322.02  3859.7  304.01  3972.7  301.81  4426.5  301.73  4483.5  300.08
  4504.4  302.35  4774.1   301.8    4831  299.68  4977.4  302.34  4990.5  300.57
  4994.6  292.01  4997.3  291.51  5000.6  292.01  5027.8  301.93    5159  299.95
  5545.3  301.69  5618.3  307.35    5681  314.46    5704  319.46  5724.9  328.85
  5789.6  343.14  5875.2  348.96  5889.9   351.5  5916.9  349.35  5985.2  348.71
#Mann= 3 ,-1 , 0
  3431.8     .12       0  4994.6     .07       0  5000.6     .12       0
Bank Sta=4977.4,5027.8
XS Rating Curve= 0 ,0
Exp/Cntr=0.3,0.1

Type RM Length L Ch R = 1 ,45971   ,559,559,559
BEGIN DESCRIPTION:
BEAVER CREEK 67.0
END DESCRIPTION:
XS GIS Cut Line= 3
      3707749.62     10688260.18      3706199.61     10689710.19
      3705399.57      10689860.2
#Sta/Elev= 30
  2856.5  367.34    2918   365.2  2955.4  365.64  2976.9  361.59  3045.5   357.8
  3149.1  348.87  3217.3  342.11  3245.2   336.5  3302.3  319.38  3373.1  311.11
  3592.4  301.99  4200.6     301  4222.1  299.23  4236.3  301.86  4667.6  299.85
  4752.6  301.98  4787.8  299.79  4823.4  302.07  4965.1  301.16  4971.9  298.56
  4975.6  293.31  5002.3  290.92    5005  290.42  5008.3  290.92  5010.4  298.94
  5107.1   299.1  5253.7  299.17  5388.5  304.75    5681  321.08    5793  330.25
#Mann= 8 ,-1 , 0
  2856.5     .12       0    2918     .16       0  3045.5     .12       0
  3149.1     .16       0  3245.2     .12       0  5002.3     .07       0
  5008.3     .12       0  5107.1     .05       0
Bank Sta=4965.1,5010.4
XS Rating Curve= 0 ,0
Exp/Cntr=0.3,0.1

Type RM Length L Ch R = 1 ,45412   ,542,542,542
BEGIN DESCRIPTION:
BEAVER CREEK 66.0
END DESCRIPTION:
XS GIS Cut Line= 3
       3707449.6     10688260.19      3705899.61     10689260.19
      3705263.87     10689387.83
#Sta/Elev= 30
  3166.9  347.16  3180.4  344.29  3225.9  339.29  3237.9  335.45  3262.1  328.89
  3289.3  324.14  3369.2  317.65  3594.9  305.29  3666.7  305.72  3724.9  302.32
  4223.8  298.36  4244.9  300.01    4476  298.94    4635  301.31  4678.3  299.14
  4722.7  300.23  4844.9  297.66  4975.8  298.78  4982.8  290.94  5000.9  290.43
  5003.6  289.93  5006.9  290.43  5031.8  297.67    5070   297.6  5291.4  308.98
  5489.9  331.52  5501.1  334.63  5521.5   337.1  5591.7  340.97  5659.9  348.36
#Mann= 5 ,-1 , 0
  3166.9     .16       0  3237.9     .12       0  5000.9     .07       0
  5006.9     .12       0    5070     .05       0
Bank Sta=4975.8,5031.8
XS Rating Curve= 0 ,0
Exp/Cntr=0.3,0.1

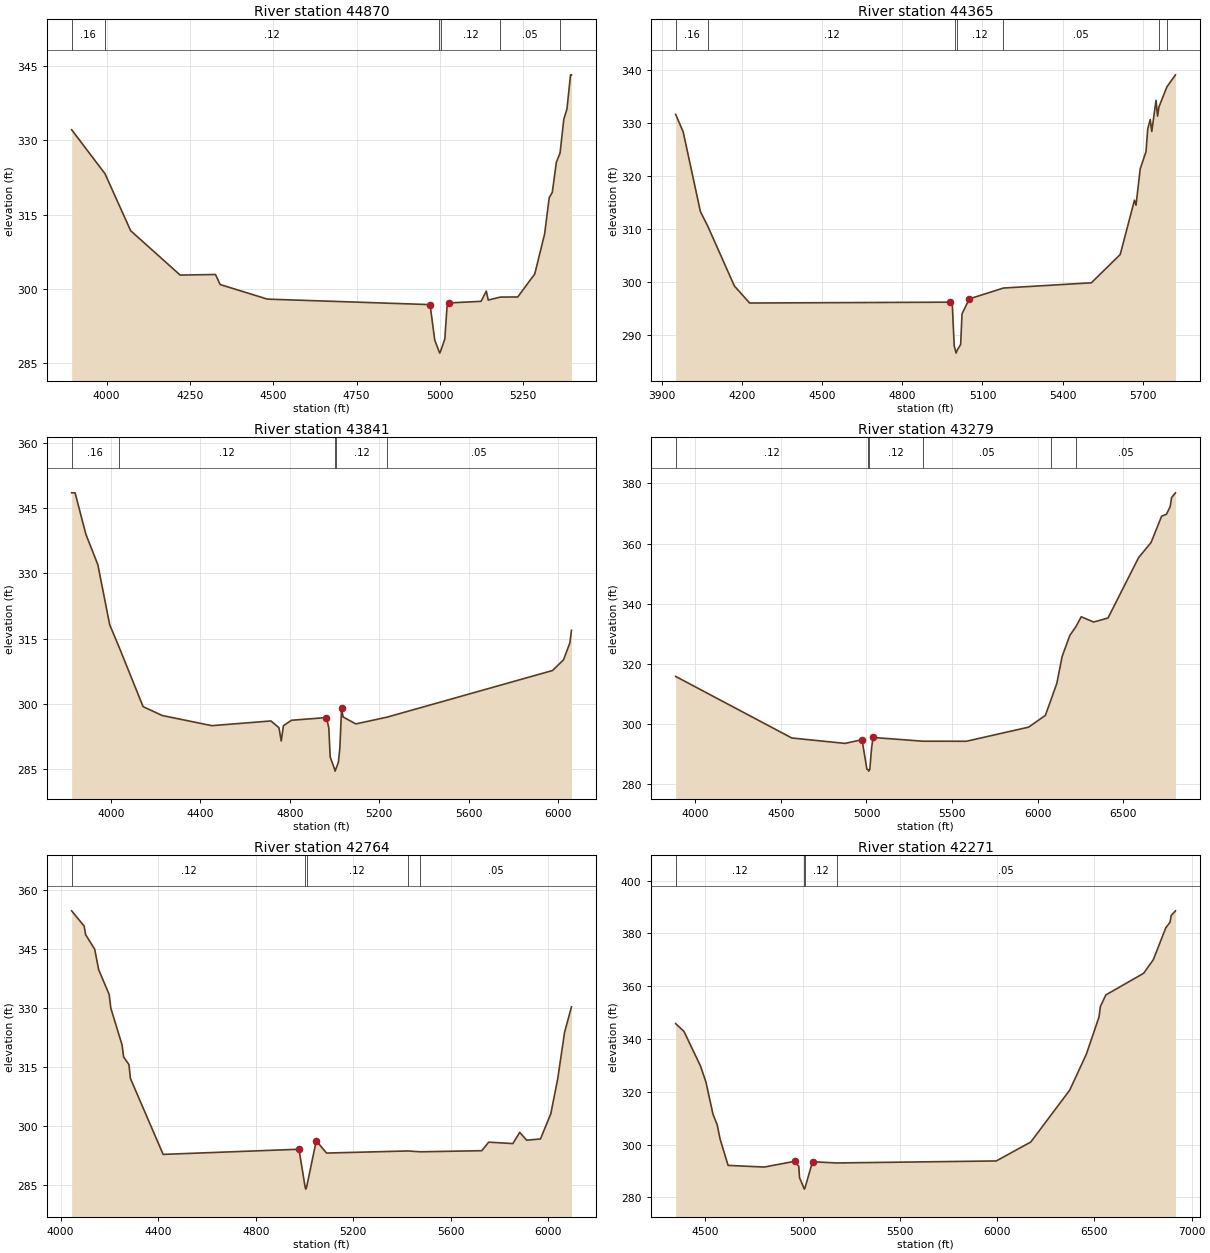
Type RM Length L Ch R = 1 ,44870   ,505,505,505
BEGIN DESCRIPTION:
BEAVER CREEK 65.0
END DESCRIPTION:
XS GIS Cut Line= 3
      3706649.64     10688010.16      3705849.61     10688760.19
      3705499.64     10688960.17
#Sta/Elev= 30
  3894.9  332.12    3995  323.24    4072  311.74  4220.5  302.79  4326.5  302.91
  4340.4  300.88  4482.3  297.94  4970.3  296.83  4984.4  289.65  4996.4  287.54
  4999.2  287.04  5002.4  287.54  5014.6   289.9    5021  296.33  5026.8  297.17
  5123.3  297.49  5139.1  299.56  5144.8  297.75  5181.1  298.35  5233.4  298.37
  5284.5  303.03    5314   311.1  5327.7  318.39    5337  319.47  5349.3  325.59
  5360.3   327.4  5371.6  334.27    5381  336.29  5391.8   343.2  5394.6   343.2
#Mann= 6 ,-1 , 0
  3894.9     .16       0    3995     .12       0  4996.4     .07       0
  5002.4     .12       0  5181.1     .05       0  5360.3     .16       0
Bank Sta=4970.3,5026.8
XS Rating Curve= 0 ,0
Exp/Cntr=0.3,0.1

Type RM Length L Ch R = 1 ,44365   ,524,524,524
BEGIN DESCRIPTION:
BEAVER CREEK 64.0
END DESCRIPTION:
XS GIS Cut Line= 3
      3706549.63     10687610.17      3705749.61     10688310.19
      3705349.59     10689010.22
#Sta/Elev= 30
  3952.4  331.62  3980.4  328.35    4045  313.25  4072.5   310.5  4172.1  299.19
  4229.1  295.97  4979.8  296.13  4987.4  295.43  4994.1  287.92  4998.7     287
  5001.4   286.5  5004.7     287  5018.3  288.14  5023.4  293.93  5050.7  296.75
  5178.2   298.8  5507.1  299.79  5615.1  305.14  5668.3  315.39  5674.1  314.45
  5689.9  321.33  5711.5  324.57    5718  328.86  5727.4  330.65  5733.1  328.38
    5749  334.28  5754.7  331.29  5759.9  333.02  5789.6  336.81  5821.7  339.09
#Mann= 7 ,-1 , 0
  3952.4     .16       0  4072.5     .12       0  4998.7     .07       0
  5004.7     .12       0  5178.2     .05       0  5759.9     .16       0
  5789.6     .05       0
Bank Sta=4979.8,5050.7
XS Rating Curve= 0 ,0
Exp/Cntr=0.3,0.1

Type RM Length L Ch R = 1 ,43841   ,562,562,562
BEGIN DESCRIPTION:
BEAVER CREEK 63.0
END DESCRIPTION:
XS GIS Cut Line= 3
      3706649.61     10687460.19      3705549.61     10687860.19
       3704749.6      10688560.2
#Sta/Elev= 30
  3825.4  348.52  3840.7  348.52  3889.2  338.97  3942.4  332.02  3995.6  318.17
  4035.2  313.34  4144.6  299.38  4229.7  297.35  4451.2  295.01  4715.9  296.09
  4751.8  294.54  4761.8  291.49  4771.8     295  4807.7  296.25  4963.9  296.87
  4974.6  294.48  4980.6  287.83    5000  285.06  5002.7  284.56    5006  285.06
  5017.2  286.57  5023.9  289.88  5031.5  299.05  5038.1  297.02  5095.1  295.41
    5235  296.97  5973.9  307.68  6023.3  310.14  6051.8  314.04  6058.9  316.92
#Mann= 5 ,-1 , 0
  3825.4     .16       0  4035.2     .12       0    5000     .07       0
    5006     .12       0    5235     .05       0
Bank Sta=4963.9,5031.5
XS Rating Curve= 0 ,0
Exp/Cntr=0.3,0.1

Type RM Length L Ch R = 1 ,43279   ,515,515,515
BEGIN DESCRIPTION:
BEAVER CREEK 62.0
END DESCRIPTION:
XS GIS Cut Line= 3
      3706349.62     10686660.17      3705549.61     10687460.19
      3703949.65     10688260.17
#Sta/Elev= 30
  3885.2  315.87    4564  295.41  4875.2  293.62  4974.2  294.87  5002.5  285.04
  5010.1  284.91  5012.8  284.41  5016.1  284.91  5019.4  284.91  5030.6  292.43
    5039  295.59  5329.9  294.35    5584  294.33  5947.4  299.02  6045.2  302.92
  6080.8  308.54  6112.3  313.57    6143  322.44  6187.7  329.44  6224.6  332.48
  6254.8  335.68  6327.5  333.93  6411.3  335.27  6590.2  355.34  6662.9  360.34
  6724.4  369.08  6752.3  369.71  6774.7  372.28  6783.1  375.32  6805.4  376.84
#Mann= 6 ,-1 , 0
  3885.2     .12       0  5010.1     .07       0  5016.1     .12       0
  5329.9     .05       0  6080.8     .16       0  6224.6     .05       0
Bank Sta=4974.2,5039
XS Rating Curve= 0 ,0
Exp/Cntr=0.3,0.1

Type RM Length L Ch R = 1 ,42764   ,493,493,493
BEGIN DESCRIPTION:
BEAVER CREEK 61.0
END DESCRIPTION:
XS GIS Cut Line= 3
       3705749.6      10686210.2      3705299.61     10687010.19
      3704499.63     10687810.17
#Sta/Elev= 30
  4045.5   354.8  4096.8  350.92  4102.8  348.74  4140.1  345.02  4156.1  339.86
  4199.4  333.52  4206.1  330.06    4252  320.74  4258.7  317.64  4280.4  315.71
  4286.4  312.19  4420.6  292.88  4977.5  294.19  5002.8  284.55  5005.5  284.05
  5008.8  284.55  5048.2  296.33  5090.6  293.22  5422.8  293.75  5474.9  293.54
    5727  293.82  5755.3  295.99  5854.3  295.63  5882.6  298.48  5910.9  296.49
  5967.5   296.8  6009.9  303.21  6038.2  312.06  6066.4  323.93  6094.7  330.39
#Mann= 5 ,-1 , 0
  4045.5     .12       0  5002.8     .07       0  5008.8     .12       0
  5422.8     .07       0  5474.9     .05       0
Bank Sta=4977.5,5048.2
XS Rating Curve= 0 ,0
Exp/Cntr=0.3,0.1

Type RM Length L Ch R = 1 ,42271   ,515,515,515
BEGIN DESCRIPTION:
BEAVER CREEK 60.0
END DESCRIPTION:
XS GIS Cut Line= 3
      3705549.58     10686210.22      3705049.61     10686610.19
      3703899.61     10688160.19
#Sta/Elev= 30
  4346.5  345.84  4388.9  342.94  4474.5  329.74  4502.5  323.64  4538.6  311.48
  4560.2  307.49  4574.6  302.21  4616.2   292.1  4801.9  291.47  4958.8  293.64
  4979.6  291.75  4983.6   287.4  5005.7   283.6  5008.4   283.1  5011.7   283.6
  5050.4  293.47  5173.8  293.02  5995.4  293.78  6172.9  300.97  6373.2  320.65
  6458.8  334.31  6523.5  348.31  6530.8  352.37  6558.9  356.72    6753  364.91
  6803.1   370.1    6867  382.16  6888.6  384.22  6894.9  386.84  6916.8  388.59
#Mann= 4 ,-1 , 0
  4346.5     .12       0  5005.7     .07       0  5011.7     .12       0
  5173.8     .05       0
Bank Sta=4958.8,5050.4
XS Rating Curve= 0 ,0
Exp/Cntr=0.3,0.1

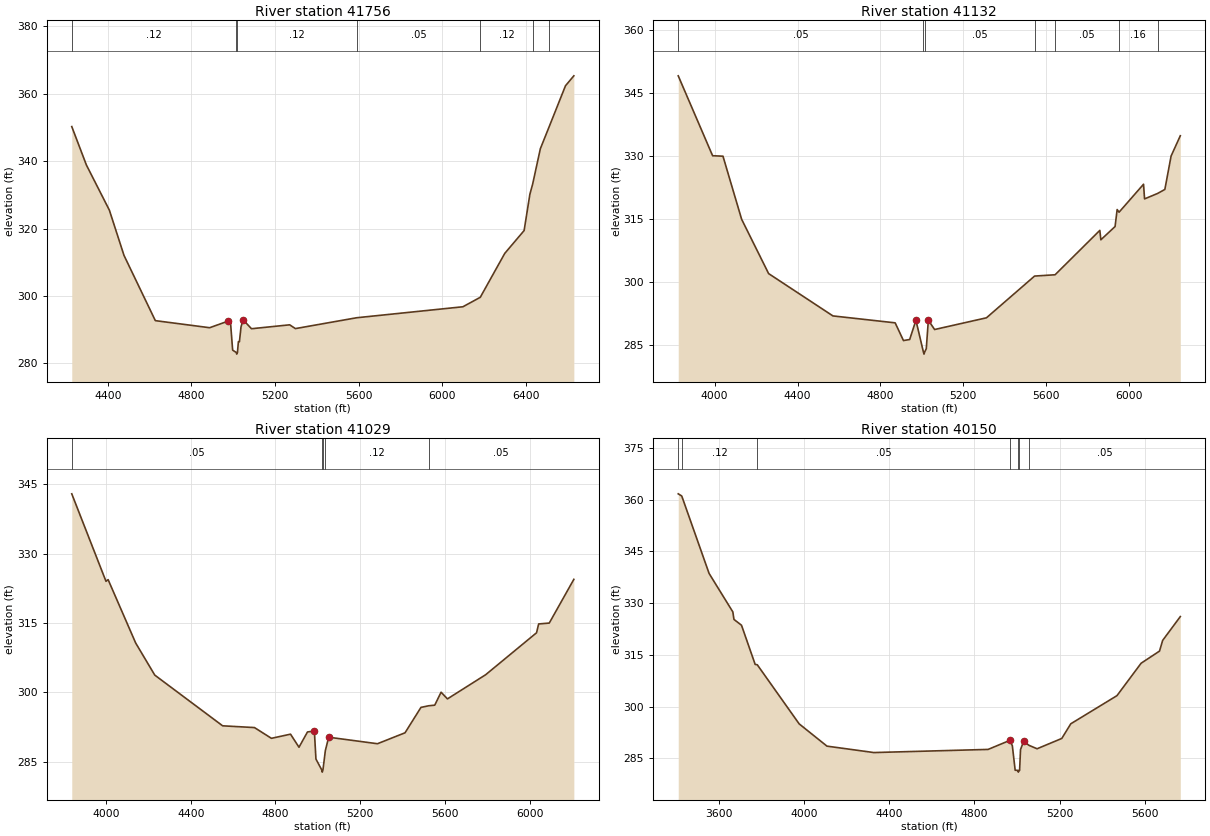
Type RM Length L Ch R = 1 ,41756   ,624,624,624
BEGIN DESCRIPTION:
BEAVER CREEK 59.0
END DESCRIPTION:
XS GIS Cut Line= 3
      3705599.59     10686160.19      3704799.61     10686160.19
      3703199.61     10686060.19
#Sta/Elev= 30
  4227.6  350.26  4297.6  338.86  4407.6  325.45  4477.6  312.02  4627.6  292.65
  4887.6  290.55  4977.6  292.55  4987.6  291.95  4997.6   283.9  5014.6  283.21
  5017.3  282.71  5020.6  283.21  5025.1   286.4  5030.1   286.4  5037.6  290.76
  5047.6  292.91  5087.7  290.25  5270.6  291.41  5298.1  290.29  5591.4  293.51
  6099.7  296.77  6182.8  299.58  6300.1  312.62  6392.7   319.4  6420.3  330.18
  6433.4  333.15  6470.4  343.69  6511.7  350.08  6590.6  362.37  6630.7  365.33
#Mann= 7 ,-1 , 0
  4227.6     .12       0  5014.6     .07       0  5020.6     .12       0
  5591.4     .05       0  6182.8     .12       0  6433.4     .16       0
  6511.7     .12       0
Bank Sta=4977.6,5047.6
XS Rating Curve= 0 ,0
Exp/Cntr=0.3,0.1

Type RM Length L Ch R = 1 ,41132   ,103,103,103
BEGIN DESCRIPTION:
BEAVER CREEK 58.0
END DESCRIPTION:
XS GIS Cut Line= 2
      3705735.31     10685661.48      3703315.12      10685546.9
#Sta/Elev= 30
  3824.2  349.07  3990.1  330.04  4040.1  329.93  4130.2   314.9  4260.4  301.97
  4570.7  291.89  4871.1  290.24  4911.1  286.02  4941.1  286.27  4971.2  290.85
  5007.4  283.29  5010.1  282.79  5013.4  283.29  5021.2  284.08  5031.2  290.87
  5061.3  288.65  5311.6  291.44  5543.9  301.38  5642.8  301.69  5858.7  312.26
  5863.7  310.02  5932.3  313.18  5942.3  317.22  5951.5  316.59  6069.6  323.25
  6074.6  319.76  6137.2  321.05  6172.5  322.01  6202.6  329.96  6247.1   334.8
#Mann= 7 ,-1 , 0
  3824.2     .05       0  5007.4     .04       0  5013.4     .05       0
  5543.9     .08       0  5642.8     .05       0  5951.5     .16       0
  6137.2     .05       0
Bank Sta=4971.2,5031.2
XS Rating Curve= 0 ,0
Exp/Cntr=0.3,0.1

Type RM Length L Ch R = 1 ,41029   ,879,879,879
BEGIN DESCRIPTION:
BEAVER CREEK 57.0
END DESCRIPTION:
XS GIS Cut Line= 2
      3705710.96     10685550.37      3703343.71     10685456.65
#Sta/Elev= 30
  3838.8  342.97  4000.3  324.02  4010.3  324.39  4140.4  310.66  4230.5  303.71
  4550.7  292.73  4700.8  292.35  4780.9  290.02    4871  290.92    4911  288.09
    4951   291.4  4983.5   291.6    4991  285.53  5018.1   283.2  5020.8   282.7
  5024.1   283.2  5035.4  287.37  5051.1  290.26  5281.3  288.85  5411.4  291.22
  5486.5  296.72  5522.8  297.07  5551.5   297.2  5581.5  300.01  5611.5  298.56
  5791.7  303.79  6031.9  312.88  6041.9  314.79  6091.9  314.98  6207.9  324.45
#Mann= 5 ,-1 , 0
  3838.8     .05       0  5018.1     .03       0  5024.1     .05       0
  5035.4     .12       0  5522.8     .05       0
Bank Sta=4983.5,5051.1
XS Rating Curve= 0 ,0
Exp/Cntr=0.3,0.1

Type RM Length L Ch R = 1 ,40150   ,535,535,535
BEGIN DESCRIPTION:
BEAVER CREEK 56.0
END DESCRIPTION:
XS GIS Cut Line= 3
      3705449.66     10684610.18      3703899.61     10685010.19
      3703276.93     10685442.74
#Sta/Elev= 30
  3408.2  361.65  3424.7  361.02  3553.2  338.58  3664.8  327.43    3670  325.26
  3705.5  323.57  3769.7  312.22  3779.6  312.12  3976.3     295    4107  288.54
  4327.4  286.68  4864.1  287.59  4966.3  290.21    4978  288.67  4991.3  281.56
  5003.4  281.51  5006.2  281.01  5009.4  281.51  5012.1  281.51  5016.5  287.55
  5031.3  289.97    5056  288.78  5094.3  287.78  5210.3  290.77  5252.5  295.01
  5469.6  303.17    5583  312.56  5669.5  316.08  5684.3  319.18  5767.2  326.08
#Mann= 7 ,-1 , 0
  3408.2     .05       0  3424.7     .12       0  3779.6     .05       0
  4966.3     .12       0  5003.4     .07       0  5009.4     .12       0
    5056     .05       0
Bank Sta=4966.3,5031.3
XS Rating Curve= 0 ,0
Exp/Cntr=0.3,0.1