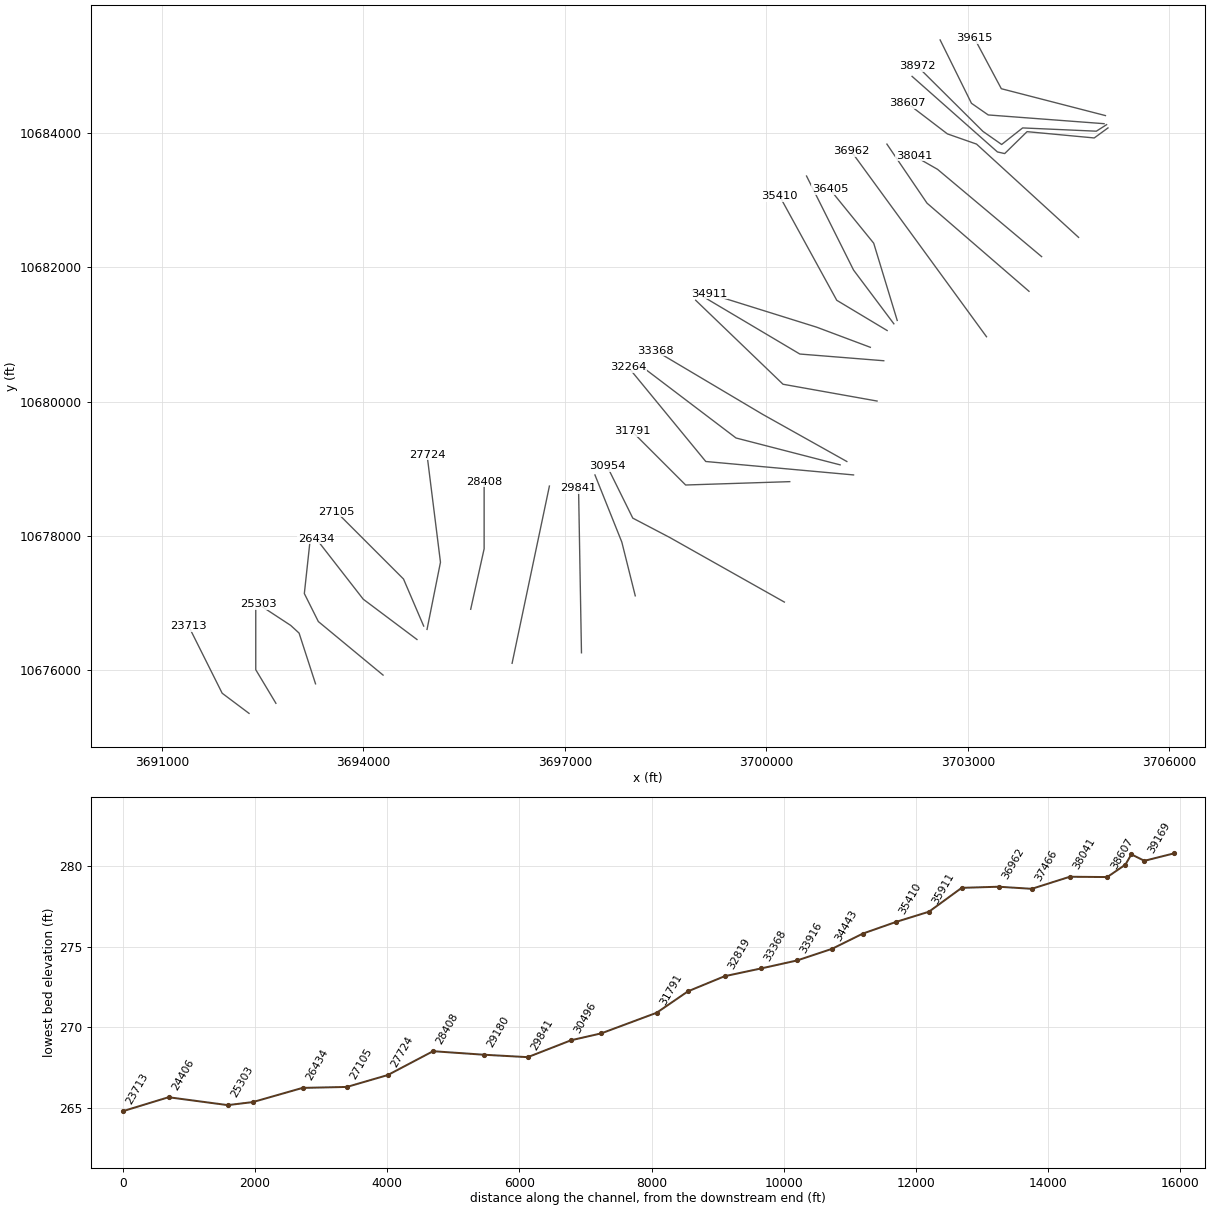
HEC-RAS study BEAVER CREEK.prj: BEAVER CREEK Base Level Engineering

--- BEAVER CREEK.g01 (geometry) --- (continued)

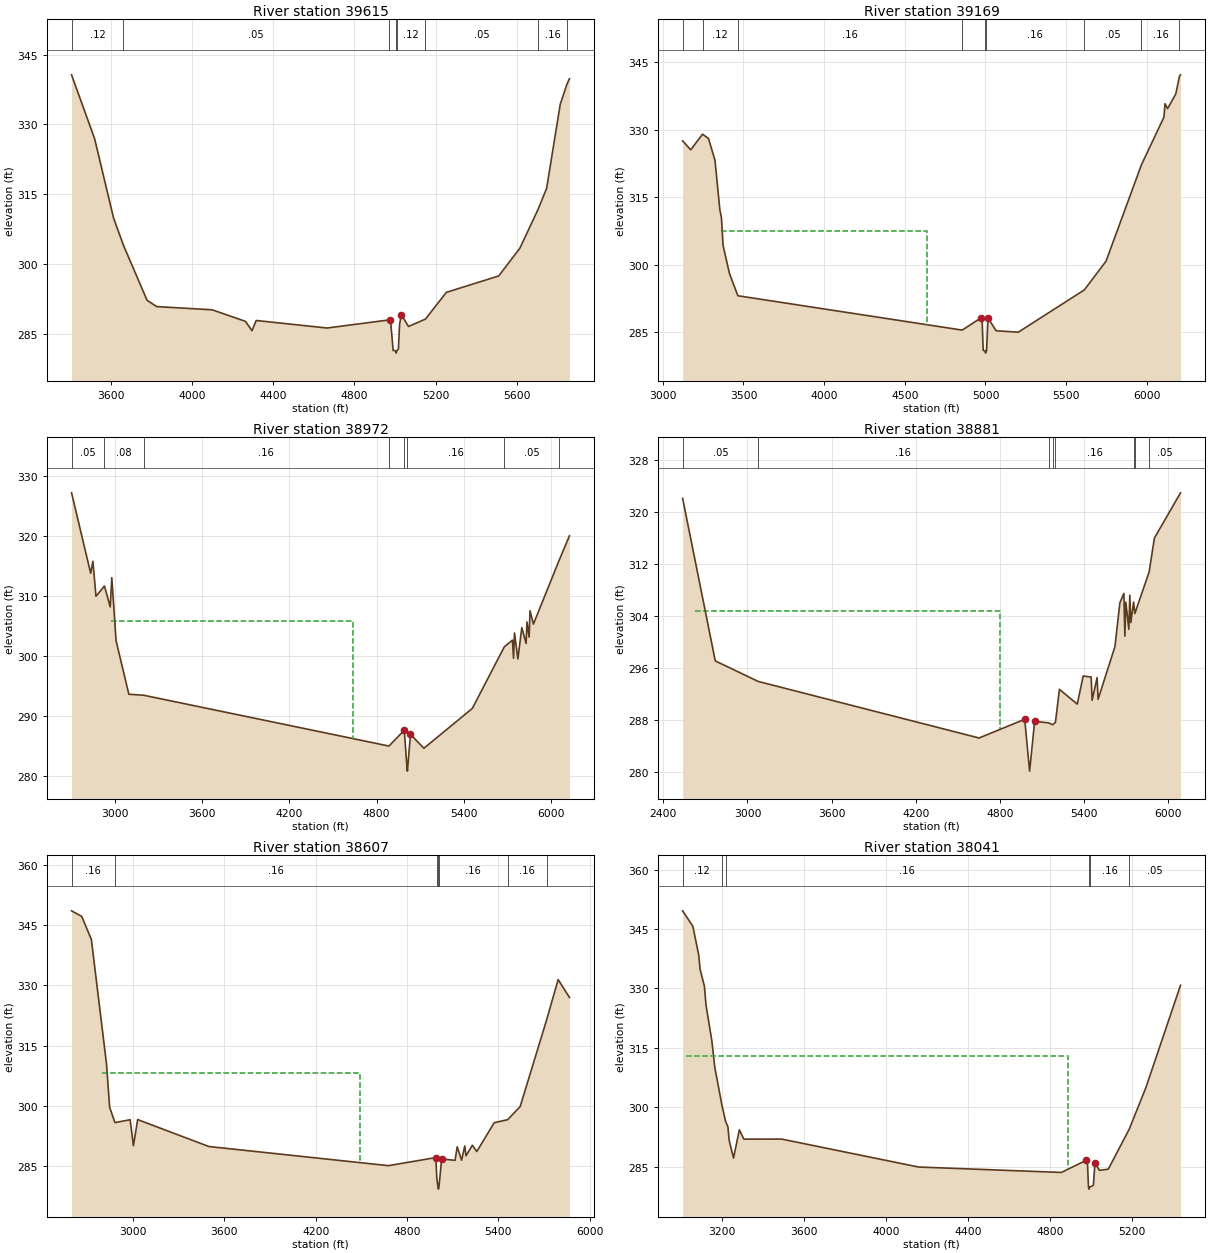
Type RM Length L Ch R = 1 ,39615   ,446,446,446
BEGIN DESCRIPTION:
BEAVER CREEK 55.0
END DESCRIPTION:
XS GIS Cut Line= 3
      3705049.63     10684260.18      3703499.61     10684660.19
      3703099.61     10685410.19
#Sta/Elev= 30
  3407.5  340.66  3521.1  326.91  3614.1  309.88  3662.5  304.05  3779.3  292.16
  3826.8  290.81  4099.5  290.12  4263.7  287.63  4295.7  285.62  4316.3  287.82
  4665.2   286.2  4969.1  287.93  4977.3  288.02  4990.5  281.37  5002.7   281.3
  5005.5   280.8  5008.7   281.3  5016.4   281.7  5022.1  286.95    5031   289.1
    5066  286.53  5149.4  288.12  5252.3  293.87  5510.2   297.4  5614.3  303.37
  5704.1  311.74    5746  316.26    5813  334.31  5846.6  338.72  5858.3  339.81
#Mann= 8 ,-1 , 0
  3407.5     .12       0  3662.5     .05       0  4969.1     .12       0
  5002.7     .07       0  5008.7     .12       0  5149.4     .05       0
  5704.1     .16       0  5846.6     .05       0
Bank Sta=4977.3,5031
XS Rating Curve= 0 ,0
Exp/Cntr=0.3,0.1

Type RM Length L Ch R = 1 ,39169   ,197,197,197
BEGIN DESCRIPTION:
BEAVER CREEK 54.0
END DESCRIPTION:
XS GIS Cut Line= 4
      3705029.51     10684139.52      3703304.28     10684269.73
      3703054.71     10684443.34      3702588.65     10685386.29
#Sta/Elev= 30
  3122.8  327.54  3172.8  325.55  3246.3  329.02  3283.2  328.05  3323.3  323.23
  3353.4  312.24  3363.4  310.42  3373.4  304.28  3413.5     298  3465.2   293.1
  4855.4  285.46    4971  288.15  4979.7   287.1  4985.8  280.94  4997.7  280.84
  5000.4  280.34  5003.7  280.84  5006.7  280.84  5015.5  288.17  5065.7  285.32
    5203  284.99  5612.5  294.39  5747.1  300.78  5966.7  322.23  6106.1  332.81
  6112.8   335.8  6128.6  334.71  6179.7     338  6201.8  341.83  6208.8  342.22
#Mann= 9 ,-1 , 0
  3122.8     .05       0  3246.3     .12       0  3465.2     .16       0
  4855.4     .16       0  4997.7     .07       0  5003.7     .16       0
  5612.5     .05       0  5966.7     .16       0  6201.8     .05       0
#XS Ineff= 1 ,-1
 3359.94 4636.65307.4174
Permanent Ineff=
       F
Bank Sta=4971,5015.5
XS Rating Curve= 0 ,0
Exp/Cntr=0.3,0.1

Type RM Length L Ch R = 1 ,38972   ,91,91,91
BEGIN DESCRIPTION:
Mapping XS d016df7b
END DESCRIPTION:
XS GIS Cut Line= 6
       3705066.9     10684125.04      3704914.09      10684027.8
      3703816.87     10684076.41      3703504.37     10683829.88
      3703226.59     10684024.33       3702248.4     10684995.85
#Sta/Elev= 30
  2702.3  327.14  2833.9  313.73  2849.1  315.72  2870.3   309.9  2928.6   311.6
  2968.2  308.12  2979.1     313  3008.3   302.5  3096.3  293.56  3198.9  293.39
  4884.7  284.92  4990.3  287.56    5009  281.24  5011.7  280.74    5033  286.88
    5125  284.55    5458  291.19  5678.1  301.46  5734.1  302.58  5741.7  299.56
  5748.3  303.78  5771.5  299.44  5798.4  304.67  5827.9  302.03    5834  305.61
  5848.8   303.1  5854.9  307.48  5878.3  305.25  6054.5  315.85    6126  319.97
#Mann= 8 ,-1 , 0
  2702.3     .05       0  2928.6     .08       0  3198.9     .16       0
  4884.7     .16       0  4990.3     .05       0    5009     .16       0
  5678.1     .05       0  6054.5     .16       0
#XS Ineff= 1 ,-1
 2970.45 4638.64305.7146
Permanent Ineff=
       F
Bank Sta=4990.3,5033
XS Rating Curve= 0 ,0
Exp/Cntr=0.3,0.1

Type RM Length L Ch R = 1 ,38881   ,274,274,274
BEGIN DESCRIPTION:
Mapping XS 30ec4409
END DESCRIPTION:
XS GIS Cut Line= 6
      3705087.71     10684076.41      3704882.84     10683927.11
      3703882.84     10684020.86      3703549.51     10683694.47
      3703441.87     10683718.77      3702171.01     10684843.78
#Sta/Elev= 30
  2537.9  322.09  2770.7  297.07  3076.1  293.91  4651.9   285.2  4977.4  288.08
  5012.4   280.1  5048.2  287.76  5147.2  287.53  5176.6  287.24  5196.6   287.6
  5224.9  292.69  5352.2  290.42  5394.6  294.74  5451.2  294.59  5458.2  291.01
  5493.7  294.49  5500.7  291.15    5621  299.27  5656.2  306.02  5684.5  307.46
  5691.7  300.89  5698.7  306.11    5720  301.93    5727  307.18  5734.1  302.96
  5753.9  306.13  5762.9  304.36  5864.7  310.76  5902.6  315.99  6088.6  322.94
#Mann= 8 ,-1 , 0
  2537.9     .05       0  3076.1     .16       0  5147.2     .12       0
  5176.6     .05       0  5196.6     .16       0  5753.9     .05       0
  5762.9     .16       0  5864.7     .05       0
#XS Ineff= 1 ,-1
 2627.27    4800304.7785
Permanent Ineff=
       F
Bank Sta=4977.4,5048.2
XS Rating Curve= 0 ,0
Exp/Cntr=0.3,0.1

Type RM Length L Ch R = 1 ,38607   ,566,566,566
BEGIN DESCRIPTION:
BEAVER CREEK 53.0
END DESCRIPTION:
XS GIS Cut Line= 4
      3704649.75     10682446.82      3703130.66      10683835.7
      3702696.64     10683987.61      3702099.88     10684443.31
#Sta/Elev= 30
  2597.3  348.56  2663.7  347.18  2727.2  341.47  2826.5  310.59  2847.5  299.69
  2882.1  295.88  2981.9  296.59  3003.5  290.13  3031.3  296.63  3498.7  289.93
  4677.9  285.17  4988.7  287.18  4995.8  281.89  5003.3  279.83  5006.1  279.33
  5009.3  279.83  5027.5  286.84  5115.4  286.49  5129.3  289.85  5158.3  286.52
  5179.1  290.08  5187.2  287.61    5229  290.26  5258.1  288.68  5372.4  295.86
  5460.4   296.6  5542.8  299.87  5717.4  321.55  5792.2  331.46  5866.3  327.02
#Mann= 7 ,-1 , 0
  2597.3     .16       0  2882.1     .16       0  4995.8     .12       0
  5003.3     .07       0  5009.3     .16       0  5460.4     .16       0
  5717.4     .05       0
#XS Ineff= 1 ,-1
 2800.28 4490.62308.2498
Permanent Ineff=
       F
Bank Sta=4988.7,5027.5
XS Rating Curve= 0 ,0
Exp/Cntr=0.3,0.1

Type RM Length L Ch R = 1 ,38041   ,575,575,575
BEGIN DESCRIPTION:
BEAVER CREEK 52.0
END DESCRIPTION:
XS GIS Cut Line= 3
      3704099.59      10682160.2      3702549.61     10683460.19
       3702199.6      10683660.2
#Sta/Elev= 30
  3008.7   349.6  3058.8  345.67    3087  338.47  3093.9  334.82  3114.7  330.59
  3122.5  325.84  3151.1  316.78  3165.3  310.12  3199.7  300.67    3218  296.44
  3229.2  295.12  3235.7   291.6  3256.7  287.18  3285.1  294.33  3307.2  291.97
  3491.6  291.98  4158.1  284.93  4854.1  283.56  4975.1  286.63  4981.6   285.7
  4986.4  279.85  4989.1  279.35  4992.4  279.85  5010.2  280.33    5018  285.98
  5039.6  284.09  5082.8  284.39    5185   294.5  5265.6  304.91  5434.8   330.8
#Mann= 6 ,-1 , 0
  3008.7     .12       0  3199.7     .16       0    3218     .16       0
  4986.4     .03       0  4992.4     .16       0    5185     .05       0
#XS Ineff= 1 ,-1
 3024.15 4887.78  313.05
Permanent Ineff=
       F
Bank Sta=4975.1,5018
XS Rating Curve= 0 ,0
Exp/Cntr=0.3,0.1

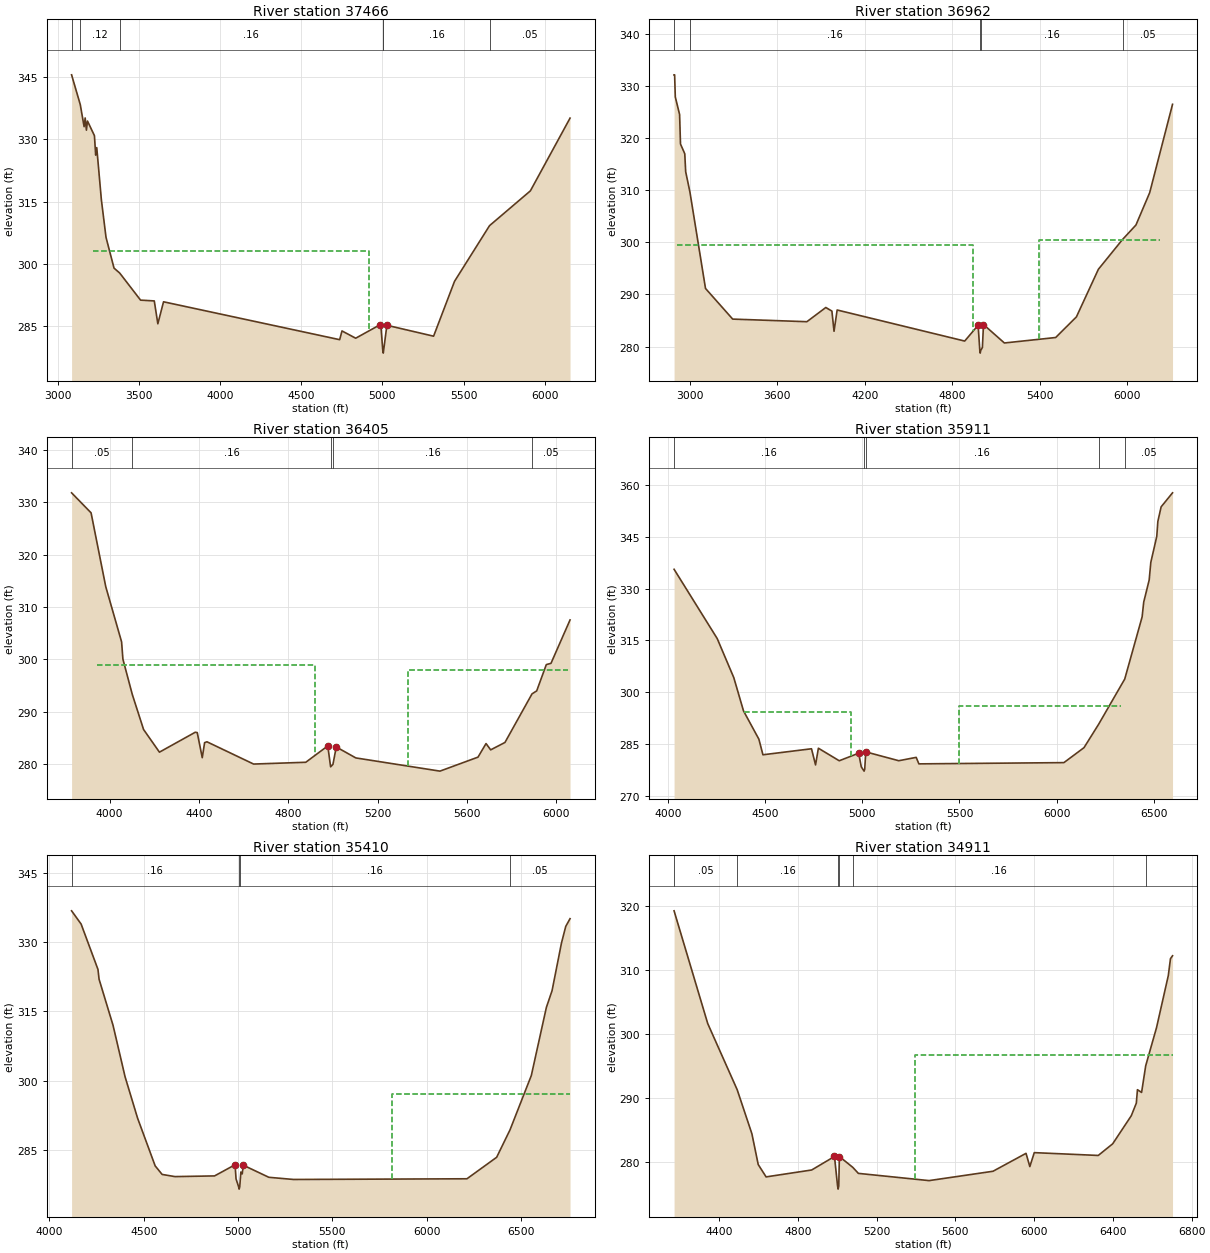
Type RM Length L Ch R = 1 ,37466   ,504,504,504
BEGIN DESCRIPTION:
BEAVER CREEK 51.0
END DESCRIPTION:
XS GIS Cut Line= 3
      3703911.89     10681643.88      3702392.82     10682956.79
      3701796.19     10683835.46
#Sta/Elev= 30
    3086  345.45  3139.5   338.3  3163.1     333  3169.7  335.09  3177.3  332.16
  3183.9  334.35  3226.7  330.84  3234.4  326.16    3241  327.97  3269.5  315.42
    3298  306.42  3347.4  299.02  3382.5  297.83  3510.8  291.33  3595.3  291.14
  3617.2  285.65  3652.3  290.93  4737.1  281.83  4751.4  283.93  4835.8  282.18
    4985   285.4  4992.3  284.53  5002.9   279.1  5005.6   278.6  5027.8  285.29
  5315.5  282.67  5444.5  295.85  5660.1  309.22  5911.7  317.58  6155.9  335.05
#Mann= 6 ,-1 , 0
    3086     .16       0  3139.5     .12       0  3382.5     .16       0
  5002.9     .07       0  5005.6     .16       0  5660.1     .05       0
#XS Ineff= 1 ,-1
 3218.75 4919.03  303.04
Permanent Ineff=
       F
Bank Sta=4985,5027.8
XS Rating Curve= 0 ,0
Exp/Cntr=0.3,0.1

Type RM Length L Ch R = 1 ,36962   ,557,557,557
BEGIN DESCRIPTION:
BEAVER CREEK 50.0
END DESCRIPTION:
XS GIS Cut Line= 2
      3703278.95     10680967.51      3701266.04     10683726.59
#Sta/Elev= 30
  2893.6  332.22  2897.3  332.22    2902  327.96  2931.4   324.6  2937.6  318.92
  2966.9  317.05  2973.1   313.6  3002.4  309.67    3109  291.16  3295.2  285.27
  3803.5  284.77  3933.2   287.5    3975  286.81  3989.6  282.93    4011  287.02
  4884.9  281.05  4976.8  284.09  4988.5  279.23  4991.2  278.73  4994.5  279.23
  5006.2  279.81  5013.6  284.23  5156.8  280.68  5508.2  281.73  5650.4   285.7
    5801  294.85  5966.3  300.57  6058.2  303.35  6152.4  309.57  6308.9  326.55
#Mann= 5 ,-1 , 0
  2893.6     .12       0  3002.4     .16       0  4988.5     .03       0
  4994.5     .16       0  5966.3     .05       0
#XS Ineff= 2 ,-1
 2913.64 4943.18  299.44 5395.45 6222.73300.4005
Permanent Ineff=
       F       F
Bank Sta=4976.8,5013.6
XS Rating Curve= 0 ,0
Exp/Cntr=0.3,0.1

Type RM Length L Ch R = 1 ,36405   ,494,494,494
BEGIN DESCRIPTION:
BEAVER CREEK 49.0
END DESCRIPTION:
XS GIS Cut Line= 3
       3701949.6     10681210.21      3701599.61     10682360.19
      3700949.63     10683160.16
#Sta/Elev= 30
  3829.6  331.77  3916.9  327.95  3982.6  313.87  4053.6  303.33  4059.5  300.03
  4101.4  293.31  4152.1   286.6  4223.1  282.28  4383.6  286.08  4392.5  286.01
  4414.9  281.22  4425.4  284.09  4435.8  284.26  4644.9  280.01  4878.6  280.35
  4977.2  283.47  4989.9  279.48  5000.3  279.94  5015.2  283.27  5102.8  281.18
  5479.7  278.66  5650.1  281.33  5686.1  283.92  5706.9  282.72  5770.8  284.13
  5892.2  293.41    5913  293.97  5956.1  298.99    5977  299.23  6062.4  307.51
#Mann= 5 ,-1 , 0
  3829.6     .05       0  4101.4     .16       0  4989.9     .07       0
  5000.3     .16       0  5892.2     .05       0
#XS Ineff= 2 ,-1
 3943.18 4921.59     299  5335.8 6053.41297.9474
Permanent Ineff=
       F       F
Bank Sta=4977.2,5015.2
XS Rating Curve= 0 ,0
Exp/Cntr=0.3,0.1

Type RM Length L Ch R = 1 ,35911   ,501,501,501
BEGIN DESCRIPTION:
BEAVER CREEK 48.0
END DESCRIPTION:
XS GIS Cut Line= 3
      3701899.62     10681160.18      3701299.61     10681960.19
      3700599.59     10683360.22
#Sta/Elev= 30
  4031.1  335.59    4253  315.55  4338.4  304.24  4388.4  294.62  4467.6  286.42
  4488.4  281.91  4738.4  283.65  4759.2  278.98  4773.8  283.81  4881.1  280.18
  4981.1  282.37  4994.7   278.4    5009  277.18  5012.2  277.68  5017.6  282.75
  5187.6  280.19  5277.1  281.16  5291.1  279.28  6037.3  279.64  6140.8  283.97
  6216.2  290.75  6350.4  303.82  6439.8  321.79  6448.2  326.11  6476.2  332.48
  6484.6  337.58  6515.3  345.11  6520.9  349.44  6537.7  353.65  6596.4  357.71
#Mann= 5 ,-1 , 0
  4031.1     .16       0    5009     .07       0  5017.6     .16       0
  6216.2     .16       0  6350.4     .05       0
#XS Ineff= 2 ,-1
 4392.05  4939.2 294.418    5500 6331.82  296.05
Permanent Ineff=
       F       F
Bank Sta=4981.1,5017.6
XS Rating Curve= 0 ,0
Exp/Cntr=0.3,0.1

Type RM Length L Ch R = 1 ,35410   ,499,499,499
BEGIN DESCRIPTION:
BEAVER CREEK 47.0
END DESCRIPTION:
XS GIS Cut Line= 3
      3701799.58     10681060.21      3701049.61     10681510.19
       3700199.6     10683060.21
#Sta/Elev= 30
  4117.5  336.78    4168  333.92  4257.4  324.09  4263.2  321.98  4337.1  312.02
  4401.2  300.84  4467.3  291.91  4560.6  281.57  4597.5  279.72  4665.6  279.25
  4875.5   279.4  4984.3  281.82  4989.2  278.78  5002.9  277.04  5005.6  276.54
  5008.9  277.04  5014.9  280.24    5022  279.84  5027.7  281.72  5163.2   279.1
    5294  278.63  6213.4  278.78  6370.8  283.43  6441.9  289.39  6554.6  301.13
  6634.4  315.87  6664.6   319.5  6714.3  329.78  6737.1  333.41  6759.9  335.08
#Mann= 4 ,-1 , 0
  4117.5     .16       0  5002.9     .07       0  5008.9     .16       0
  6441.9     .05       0
#XS Ineff= 2 , 0
                         5815.34          297.07
Permanent Ineff=
       F       F
Bank Sta=4984.3,5027.7
XS Rating Curve= 0 ,0
Exp/Cntr=0.3,0.1

Type RM Length L Ch R = 1 ,34911   ,468,468,468
BEGIN DESCRIPTION:
BEAVER CREEK 46.0
END DESCRIPTION:
XS GIS Cut Line= 3
      3701549.63     10680810.18      3700749.61     10681110.19
      3699149.64     10681610.18
#Sta/Elev= 30
  4172.2  319.29  4343.1  301.68  4492.6  291.35  4567.4  284.46  4599.4  279.66
  4639.5  277.73  4870.9  278.81  4986.6  280.92  5002.3  276.32    5005  275.82
  5008.3  276.32  5011.5  280.91  5079.2  279.23  5107.8  278.28  5466.7  277.15
  5791.4  278.61  5959.1  281.41  5978.4  279.34    6001  281.52  6325.8  281.08
  6399.1   282.9  6493.4  287.28  6519.1  289.25  6524.8  291.35  6545.8  290.92
  6566.7  295.09  6621.7  301.05  6681.4  309.17  6692.5  311.82  6702.9  312.27
#Mann= 6 ,-1 , 0
  4172.2     .05       0  4492.6     .16       0  5002.3     .07       0
  5008.3     .07       0  5079.2     .16       0  6566.7     .05       0
#XS Ineff= 2 , 0
                         5394.32          296.78
Permanent Ineff=
       F       F
Bank Sta=4986.6,5011.5
XS Rating Curve= 0 ,0
Exp/Cntr=0.3,0.1

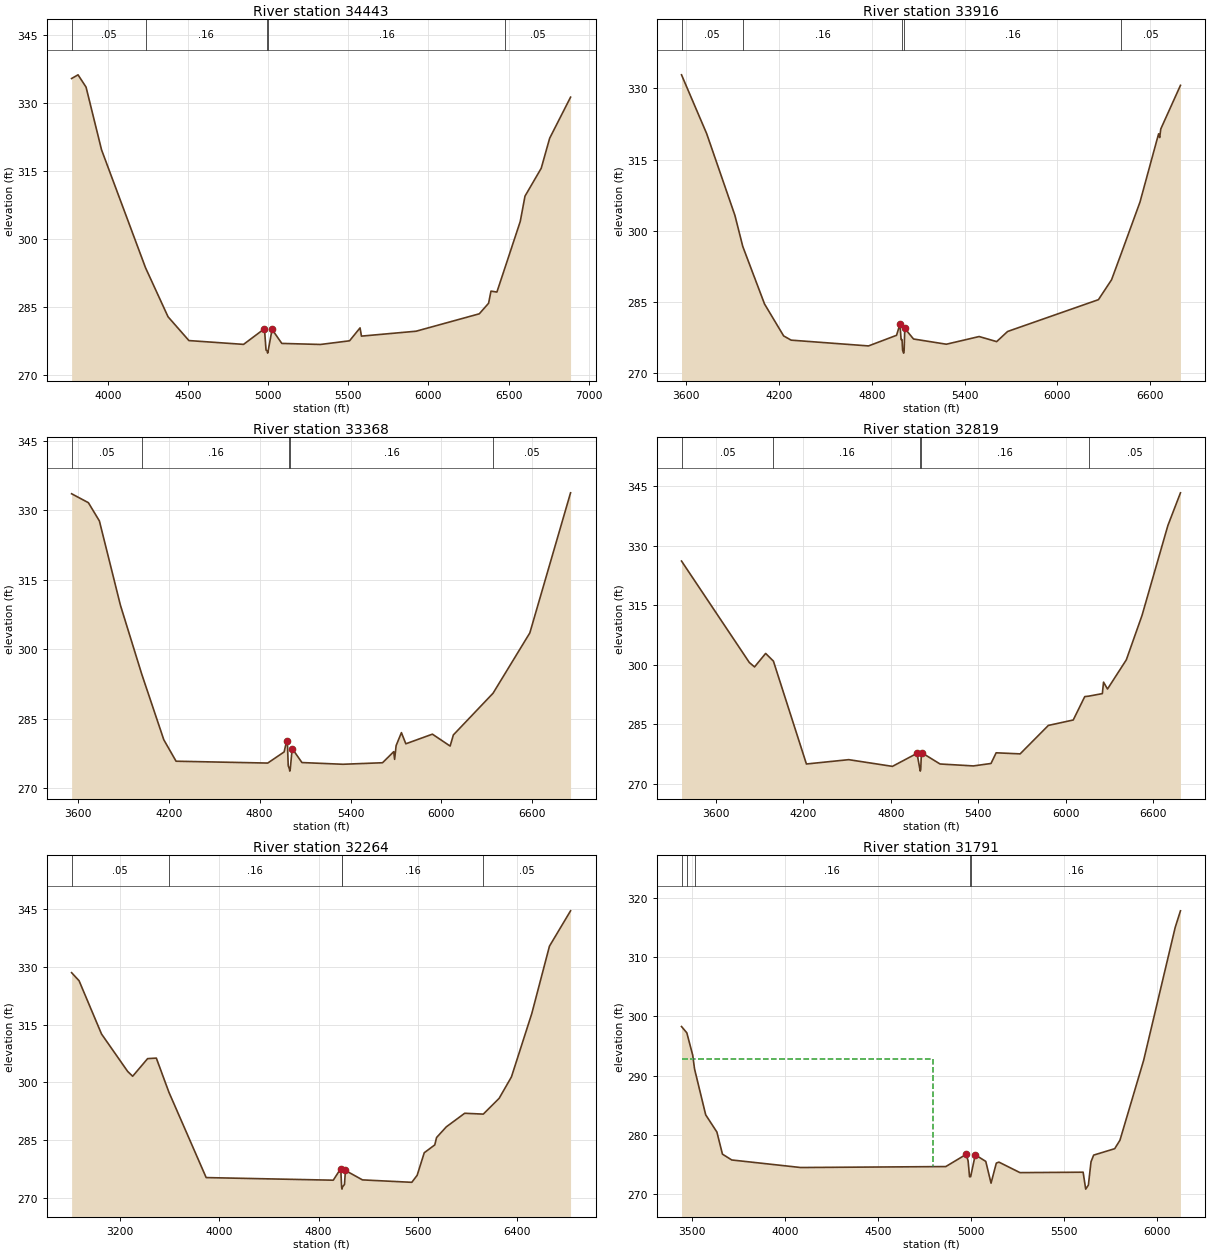
Type RM Length L Ch R = 1 ,34443   ,527,527,527
BEGIN DESCRIPTION:
BEAVER CREEK 45.0
END DESCRIPTION:
XS GIS Cut Line= 3
      3701749.57     10680610.19      3700499.61     10680710.19
      3698899.64     10681660.17
#Sta/Elev= 30
  3772.5  335.43  3812.6  336.24  3862.7  333.53  3959.3  319.71  4233.9   293.7
  4374.4  282.89  4504.8  277.64  4845.9   276.8  4976.3  280.25  4986.3  275.51
  4993.4  275.37  4996.1  274.87  4999.4  275.37  5023.9   280.1  5084.6  277.01
  5326.5  276.78  5507.7  277.59  5573.1  280.44  5581.8  278.62  5922.7   279.7
  6317.4  283.54  6375.5  285.87  6390.4  288.54  6427.4  288.34    6480  293.94
  6573.2  303.91  6602.8  309.49  6704.1  315.64  6756.7  322.25  6887.2  331.31
#Mann= 5 ,-1 , 0
  3772.5     .05       0  4233.9     .16       0  4993.4     .07       0
  4999.4     .16       0    6480     .05       0
Bank Sta=4976.3,5023.9
XS Rating Curve= 0 ,0
Exp/Cntr=0.3,0.1

Type RM Length L Ch R = 1 ,33916   ,548,548,548
BEGIN DESCRIPTION:
BEAVER CREEK 44.0
END DESCRIPTION:
XS GIS Cut Line= 3
      3701649.58     10680010.19      3700249.61     10680260.19
       3698949.6      10681510.2
#Sta/Elev= 30
  3570.5  332.88    3733  320.48  3915.8  303.21  3966.6  296.65  4107.3  284.51
  4230.8  277.78    4279  276.89  4779.3  275.67  4960.6  277.91  4982.5  280.26
  4990.1  277.01  4996.1  277.01  4999.7  274.77  5006.4  274.15  5006.9  274.15
  5009.6  274.65  5013.8  279.37  5070.4  277.13  5282.7  276.03  5494.7  277.65
  5607.9  276.58  5678.6  278.72  6265.7  285.43  6350.6  289.63  6414.2  295.26
  6534.3  306.02  6654.7  320.43  6661.7  319.64  6668.9  321.46  6796.1  330.66
#Mann= 5 ,-1 , 0
  3570.5     .05       0  3966.6     .16       0  4996.1     .07       0
  5006.9     .16       0  6414.2     .05       0
Bank Sta=4982.5,5013.8
XS Rating Curve= 0 ,0
Exp/Cntr=0.3,0.1

Type RM Length L Ch R = 1 ,33368   ,549,549,549
BEGIN DESCRIPTION:
BEAVER CREEK 43.0
END DESCRIPTION:
XS GIS Cut Line= 3
      3701199.64     10679110.17      3699949.61     10679810.19
      3698349.58     10680760.21
#Sta/Elev= 30
  3558.7  333.52  3669.5  331.59  3742.1  327.65  3880.7  309.48  4021.1  294.64
  4167.2  280.42  4248.2  275.79  4853.2  275.39  4961.7   277.8  4977.7  280.16
  4983.4  279.56  4988.5  274.81  4996.2  274.15  4998.9  273.65  5002.2  274.15
  5014.6  278.53  5079.1   275.5  5349.9  275.13    5611  275.46    5685  277.85
  5690.9  276.19  5700.7  279.15  5735.7  281.96  5764.9  279.55  5940.3  281.63
  6057.2  279.06  6078.6  281.46  6340.5  290.46  6583.3  303.48  6852.2  333.72
#Mann= 5 ,-1 , 0
  3558.7     .05       0  4021.1     .16       0  4996.2     .07       0
  5002.2     .16       0  6340.5     .05       0
Bank Sta=4977.7,5014.6
XS Rating Curve= 0 ,0
Exp/Cntr=0.3,0.1

Type RM Length L Ch R = 1 ,32819   ,555,555,555
BEGIN DESCRIPTION:
BEAVER CREEK 42.0
END DESCRIPTION:
XS GIS Cut Line= 3
      3701099.64     10679060.18      3699549.61     10679460.19
      3698099.64     10680560.16
#Sta/Elev= 30
  3364.9  326.13    3830  300.55  3865.5  299.44  3941.7  302.84  3994.9  300.91
  4221.2  274.97  4511.3  276.06  4810.8  274.37  4979.3  277.65  4999.1  273.67
  5001.8  273.17  5005.1  273.67  5008.4  276.76  5015.9  277.72  5137.3  274.97
  5366.1  274.48  5486.8   275.1  5522.1  277.79  5686.5  277.52  5879.9  284.69
  6050.5  286.06  6129.5  291.96  6158.1  292.08  6250.1  292.71  6258.4   295.6
  6285.5  293.87  6414.5  301.23  6522.2  312.43  6699.4  335.09  6785.7  343.33
#Mann= 5 ,-1 , 0
  3364.9     .05       0  3994.9     .16       0  4999.1     .07       0
  5005.1     .16       0  6158.1     .05       0
Bank Sta=4979.3,5015.9
XS Rating Curve= 0 ,0
Exp/Cntr=0.3,0.1

Type RM Length L Ch R = 1 ,32264   ,473,473,473
BEGIN DESCRIPTION:
BEAVER CREEK 41.0
END DESCRIPTION:
XS GIS Cut Line= 3
      3701299.59     10678910.19      3699099.61     10679110.19
      3697949.62     10680510.17
#Sta/Elev= 30
  2809.2  328.47  2869.4  326.37  3050.2  312.54    3261  302.81  3301.2  301.56
  3421.7  306.14    3492  306.27  3592.4  297.48  3893.6  275.23  4917.8  274.55
  4978.1  277.57  4985.1  272.73  4987.9  272.23  4991.1  272.73  5008.2  273.46
  5015.7  277.08  5153.1  274.63  5550.7     274  5593.7  275.82  5651.1  281.69
  5735.8  283.72  5750.1  285.63  5828.3   288.4  5976.9  291.94  6126.8  291.72
  6254.6  295.83  6353.6  301.39  6517.9  317.89    6660  335.36    6830  344.54
#Mann= 5 ,-1 , 0
  2809.2     .05       0  3592.4     .16       0  4985.1     .07       0
  4991.1     .16       0  6126.8     .05       0
Bank Sta=4978.1,5015.7
XS Rating Curve= 0 ,0
Exp/Cntr=0.3,0.1

Type RM Length L Ch R = 1 ,31791   ,837,837,837
BEGIN DESCRIPTION:
BEAVER CREEK 40.0
END DESCRIPTION:
XS GIS Cut Line= 3
      3700349.59     10678810.19      3698799.61     10678760.19
      3697999.58     10679560.22
#Sta/Elev= 30
  3442.2  298.29  3470.7  297.23  3502.2  293.49  3512.2  291.15  3572.2  283.41
  3632.3  280.52  3662.3  276.79  3712.3  275.81  4082.5  274.54  4862.9   274.7
    4973  276.77    4983  275.63  4990.5  272.99  4996.5  272.99  5021.3  276.68
  5077.8  275.57  5106.1   271.9  5134.4  275.28  5148.5  275.45  5261.7  273.68
  5601.1  273.75    5615   270.9  5629.4  271.58  5643.5   275.5  5657.7  276.63
  5770.8  277.71  5799.1  279.14  5926.4  292.59  6096.1  314.99  6124.4  317.78
#Mann= 5 ,-1 , 0
  3442.2     .05       0  3470.7     .16       0  3512.2     .16       0
  4990.5     .07       0  4996.5     .16       0
#XS Ineff= 2 , 0
         4791.76  292.84
Permanent Ineff=
       F       F
Bank Sta=4973,5021.3
XS Rating Curve= 0 ,0
Exp/Cntr=0.3,0.1

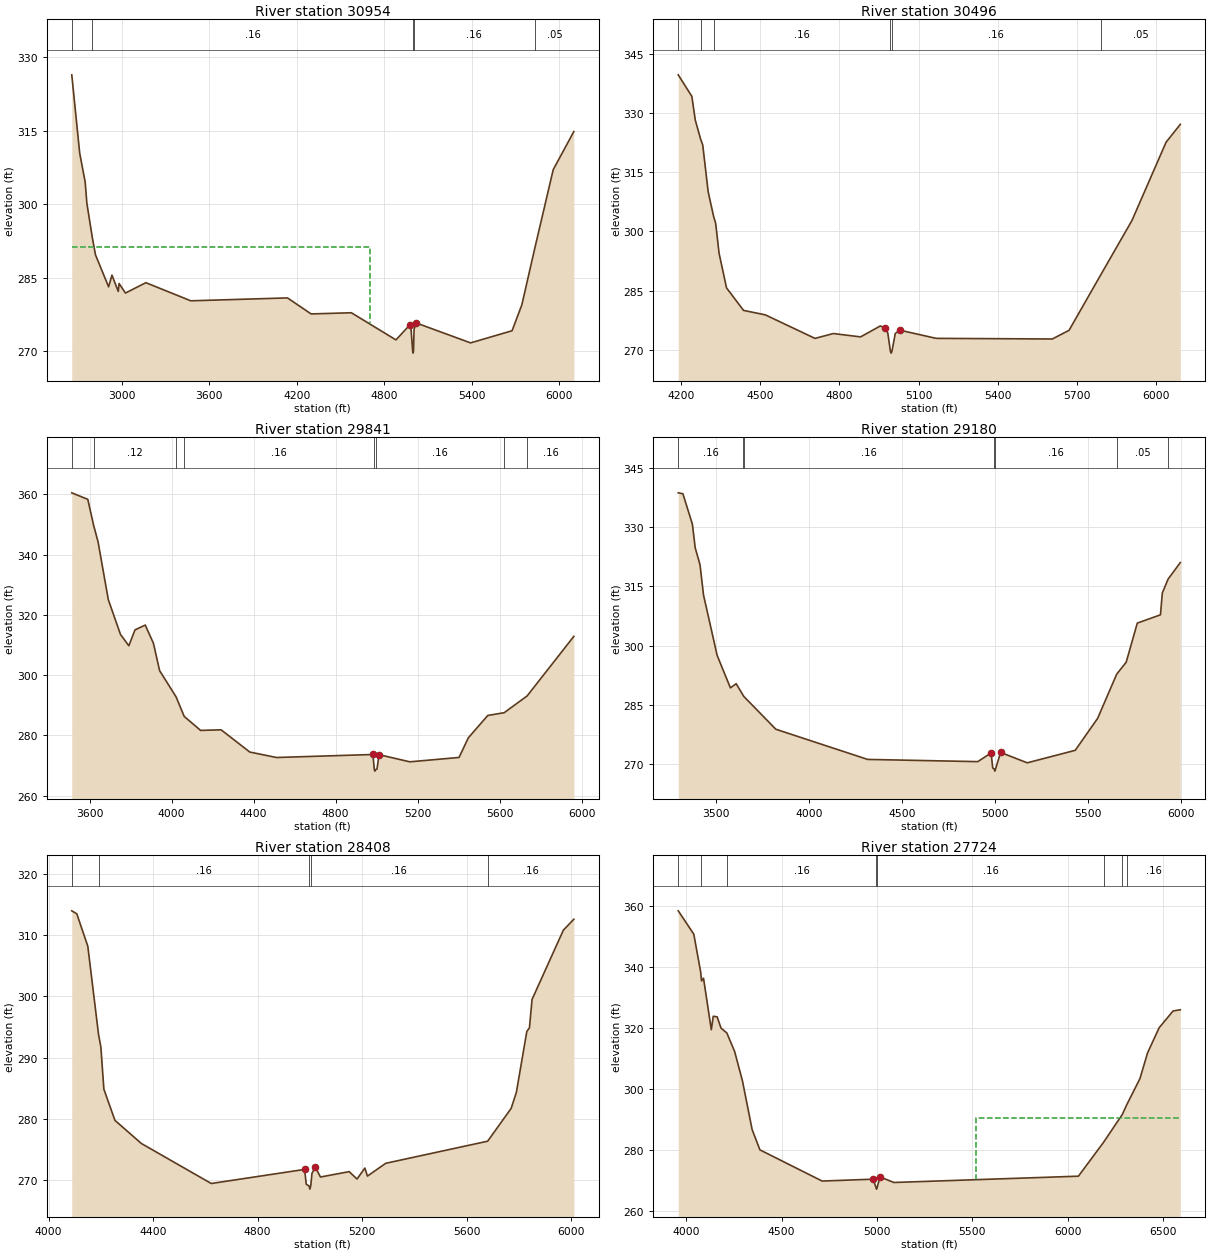
Type RM Length L Ch R = 1 ,30954   ,458,458,458
BEGIN DESCRIPTION:
BEAVER CREEK 39.0
END DESCRIPTION:
XS GIS Cut Line= 4
      3700269.69     10677017.19      3698559.66     10677980.71
      3698012.78     10678267.17      3697630.83     10679039.75
#Sta/Elev= 30
  2656.8  326.43  2711.2  310.44  2748.7  304.55  2760.3  300.22  2797.8  293.18
  2819.5  289.68  2909.4  283.15  2932.3  285.54  2975.6  282.22  2981.3  283.83
  3024.7  281.88  3164.8     284  3472.6   280.3  4135.8  280.89  4297.7  277.62
  4573.7  277.86  4879.3  272.32  4974.7  275.39  4980.9  275.24  4993.7  270.12
  4996.5  269.62  4999.7  270.12  5003.5  274.49  5018.8  275.77  5390.9  271.71
  5675.4  274.19  5742.3  279.48  5831.6  291.09  5957.4  307.07  6098.8  314.85
#Mann= 5 ,-1 , 0
  2656.8     .16       0  2797.8     .16       0  4993.7     .07       0
  4999.7     .16       0  5831.6     .05       0
#XS Ineff= 2 , 0
         4702.27  291.19
Permanent Ineff=
       F       F
Bank Sta=4974.7,5018.8
XS Rating Curve= 0 ,0
Exp/Cntr=0.3,0.1

Type RM Length L Ch R = 1 ,30496   ,655,655,655
BEGIN DESCRIPTION:
BEAVER CREEK 38.0
END DESCRIPTION:
XS GIS Cut Line= 3
      3698049.62     10677110.15      3697849.61     10677910.19
      3697449.61     10678910.19
#Sta/Elev= 30
  4189.3  339.67  4240.9  334.22  4253.8  328.23    4274   323.4  4282.1  321.91
  4302.7  310.05  4323.3  303.82  4331.1  302.06    4344  294.47  4372.3  285.71
  4436.7  280.01  4519.2  278.88  4707.3  272.92  4776.9  274.15    4880   273.3
  4954.7  276.07  4972.7  275.55    4983   274.3  4992.9  269.69  4995.7  269.19
  4998.9  269.69  5011.4  274.17  5028.8     275  5166.1  272.93  5606.3  272.77
  5669.6  274.97  5789.4  288.99  5907.9  302.78  6037.1   322.6    6091  327.13
#Mann= 6 ,-1 , 0
  4189.3     .12       0    4274     .05       0  4323.3     .16       0
  4992.9     .07       0  4998.9     .16       0  5789.4     .05       0
Bank Sta=4972.7,5028.8
XS Rating Curve= 0 ,0
Exp/Cntr=0.3,0.1

Type RM Length L Ch R = 1 ,29841   ,661,661,661
BEGIN DESCRIPTION:
BEAVER CREEK 37.0
END DESCRIPTION:
XS GIS Cut Line= 2
      3697248.89     10676261.98      3697205.49     10678709.89
#Sta/Elev= 30
  3513.2   360.5  3591.4  358.34  3619.7  349.74  3641.4  344.26  3691.4  325.05
  3750.7  313.52  3791.5  309.75  3821.5  315.02  3871.5  316.61  3911.5  310.57
  3941.5   301.5  4021.8   292.8  4061.5   286.3  4141.5  281.65  4241.5  281.85
  4381.5  274.47  4511.6  272.66  4981.6  273.66  4988.6  268.64  4991.4  268.14
  4994.6  268.64  5001.6  268.81  5011.6   273.6  5161.7  271.23  5401.7  272.68
  5446.9  279.18  5541.7  286.61  5621.7  287.53  5733.4  293.07  5961.5  312.87
#Mann= 8 ,-1 , 0
  3513.2     .16       0  3619.7     .12       0  4021.8     .05       0
  4061.5     .16       0  4988.6     .07       0  4994.6     .16       0
  5621.7     .05       0  5733.4     .16       0
Bank Sta=4981.6,5011.6
XS Rating Curve= 0 ,0
Exp/Cntr=0.3,0.1

Type RM Length L Ch R = 1 ,29180   ,772,772,772
BEGIN DESCRIPTION:
BEAVER CREEK 36.0
END DESCRIPTION:
XS GIS Cut Line= 2
       3696215.9     10676105.68      3696771.47     10678744.64
#Sta/Elev= 30
  3299.2  338.64  3324.2  338.41  3375.3  330.71  3390.3  324.76  3416.2  320.46
    3435  312.81  3508.2  297.55  3579.4  289.34  3610.4  290.39  3647.8  287.46
  3651.3  287.18  3823.4  278.88  4316.5  271.25  4908.2  270.69  4979.8  272.89
  4988.4   269.1  4997.2  268.79  4999.9  268.29  5003.2  268.79  5030.9  273.01
  5173.9  270.39  5431.6  273.55    5552  281.63  5654.2  292.79  5705.3  295.82
    5765  305.71  5889.3   307.8  5899.5  313.34  5930.6  316.85    5996  321.01
#Mann= 7 ,-1 , 0
  3299.2     .16       0  3647.8     .05       0  3651.3     .16       0
  4997.2     .07       0  5003.2     .16       0  5654.2     .05       0
  5930.6     .16       0
Bank Sta=4979.8,5030.9
XS Rating Curve= 0 ,0
Exp/Cntr=0.3,0.1

Type RM Length L Ch R = 1 ,28408   ,684,684,684
BEGIN DESCRIPTION:
BEAVER CREEK 35.0
END DESCRIPTION:
XS GIS Cut Line= 3
      3695599.61     10676910.21      3695799.61     10677810.19
      3695799.61     10678810.15
#Sta/Elev= 30
  4088.5  313.98  4107.7   313.5  4149.9   308.2  4190.9  293.81  4199.9  291.72
  4211.4  284.84  4253.7  279.75  4354.8  275.97  4622.4  269.43  4979.7  271.73
  4986.1  269.31  4997.2  269.01  4999.9  268.51  5003.2  269.01  5007.9  271.06
  5020.4  272.15  5040.4  270.49  5150.4  271.37  5180.4  270.16  5210.4  271.95
  5220.4  270.64  5290.4  272.73  5680.4  276.34  5770.4   281.7  5790.4  284.32
  5830.4  294.27  5840.4  294.86  5850.4   299.5  5970.4  310.83  6010.4  312.61
#Mann= 5 ,-1 , 0
  4088.5     .12       0  4190.9     .16       0  4997.2     .07       0
  5003.2     .16       0  5680.4     .16       0
Bank Sta=4979.7,5020.4
XS Rating Curve= 0 ,0
Exp/Cntr=0.3,0.1

Type RM Length L Ch R = 1 ,27724   ,619,619,619
BEGIN DESCRIPTION:
BEAVER CREEK 34.0
END DESCRIPTION:
XS GIS Cut Line= 3
      3694949.61     10676610.19      3695149.61     10677610.19
       3694949.6     10679210.24
#Sta/Elev= 30
  3957.9  358.41  4039.5  350.75  4075.4  338.37  4080.3  335.42  4090.5  336.27
  4131.3  319.38  4141.5  323.79  4161.9   323.6  4182.3   319.9  4212.8   318.3
  4253.6  312.23  4294.4  302.63  4345.4  286.57  4386.2  279.92  4712.6  269.68
  4980.2   270.3  4994.9  267.53  4997.6  267.03  5000.9  267.53  5015.5  271.05
  5088.6  269.21    6056  271.28  6188.1  282.43  6286.4  291.58  6309.1   294.7
  6378.5  303.31  6418.8  311.81  6479.3  320.03  6552.4  325.53  6590.2  325.92
#Mann= 8 ,-1 , 0
  3957.9     .05       0  4075.4     .12       0  4212.8     .16       0
  4994.9     .07       0  5000.9     .16       0  6188.1     .16       0
  6286.4     .05       0  6309.1     .16       0
#XS Ineff= 2 , 0
                         5516.48          290.29
Permanent Ineff=
       F       F
Bank Sta=4980.2,5015.5
XS Rating Curve= 0 ,0
Exp/Cntr=0.3,0.1

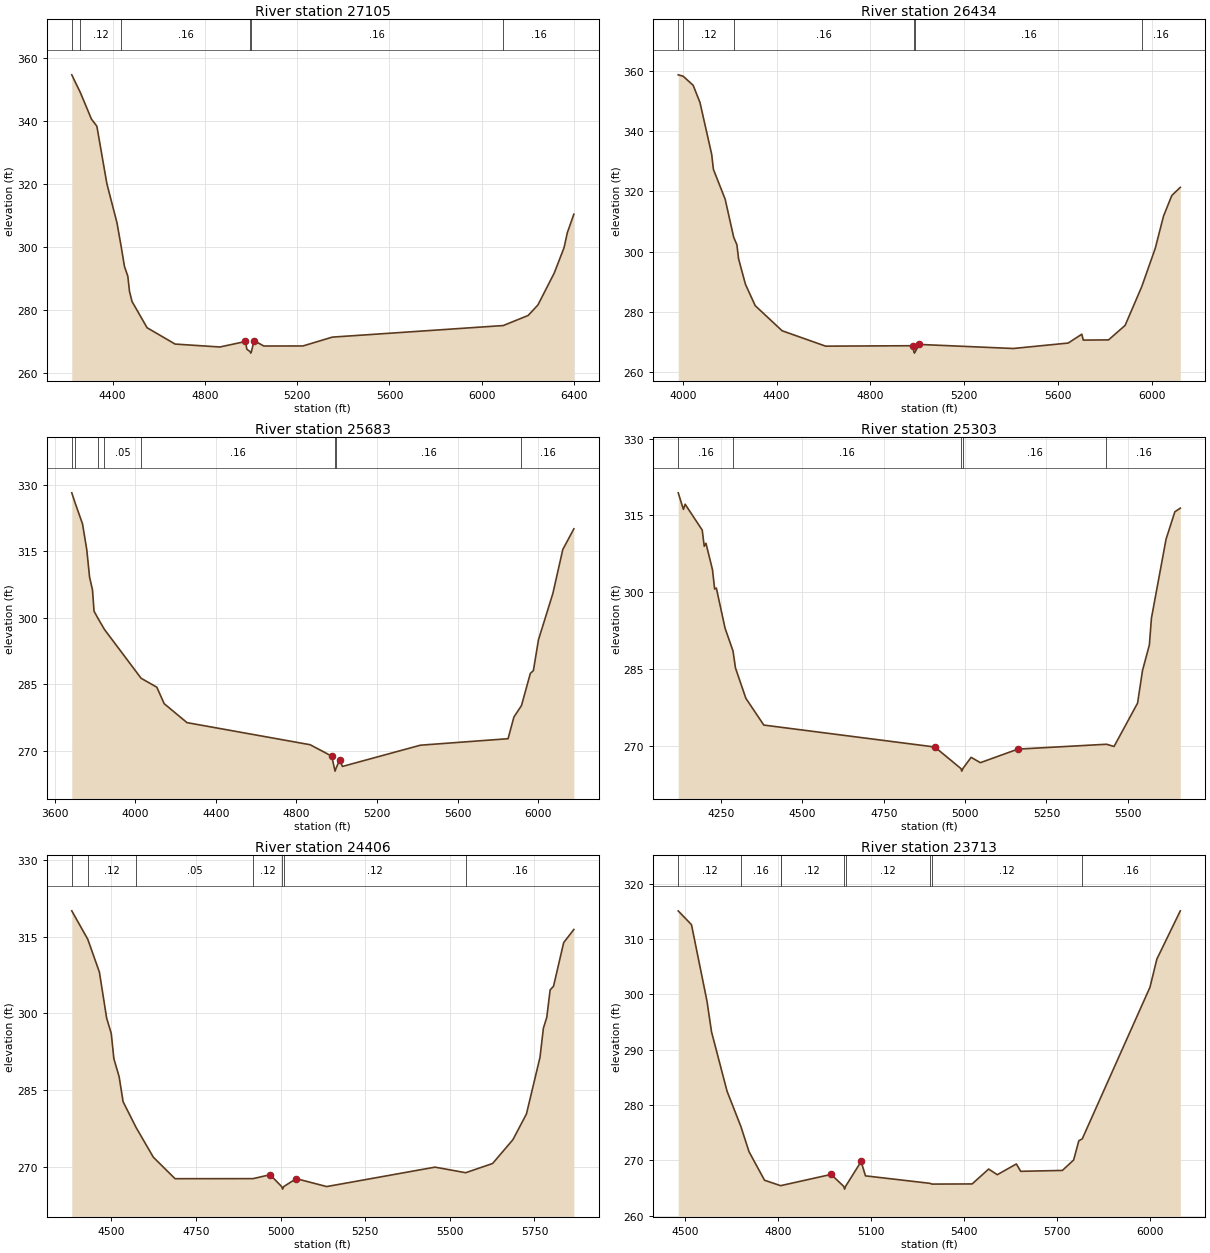
Type RM Length L Ch R = 1 ,27105   ,671,671,671
BEGIN DESCRIPTION:
BEAVER CREEK 33.0
END DESCRIPTION:
XS GIS Cut Line= 3
      3694899.61     10676660.18      3694599.61     10677360.19
      3693599.61     10678360.19
#Sta/Elev= 30
  4223.1  354.77  4260.9  349.04  4308.3  340.71  4331.9  338.43  4375.4  320.11
  4418.9  307.77  4437.1  300.22  4451.6  293.81  4466.1  290.73  4473.3   285.9
  4484.2  282.71  4549.5  274.36    4671  269.17    4865  268.24  4975.6  269.99
    4982  267.51  4995.8  266.79  4998.6  266.29  5001.8  266.79    5013  270.27
  5055.4  268.55  5225.1  268.57  5352.4  271.38    6093  275.06  6200.9  278.26
  6243.3  281.61    6314  291.76  6356.5  299.82  6370.6  304.56  6398.9  310.45
#Mann= 6 ,-1 , 0
  4223.1     .05       0  4260.9     .12       0  4437.1     .16       0
  4995.8     .07       0  5001.8     .16       0    6093     .16       0
Bank Sta=4975.6,5013
XS Rating Curve= 0 ,0
Exp/Cntr=0.3,0.1

Type RM Length L Ch R = 1 ,26434   ,751,751,751
BEGIN DESCRIPTION:
BEAVER CREEK 32.0
END DESCRIPTION:
XS GIS Cut Line= 3
      3694799.63     10676460.17      3693999.61     10677060.19
      3693299.61     10677960.18
#Sta/Elev= 30
  3980.6  358.74  4001.4  358.28  4044.2  355.27  4073.3  349.54  4123.3  332.28
  4130.6   327.3  4180.6   317.4  4217.1  304.73  4230.6  302.28  4237.9  297.57
  4267.1  289.12  4308.8     282  4423.3  273.67  4608.8  268.55  4980.6  268.69
  4984.9  266.73  4987.6  266.23  4990.9  266.73  5008.7  269.12  5408.6  267.77
    5643  269.58  5700.9  272.52  5707.3  270.56    5815  270.63  5885.5  275.45
  5956.4  288.32    6014  301.07  6049.3   311.8  6084.6  318.63  6120.8  321.34
#Mann= 6 ,-1 , 0
  3980.6     .05       0  4001.4     .12       0  4217.1     .16       0
  4984.9     .07       0  4990.9     .16       0  5956.4     .16       0
Bank Sta=4980.6,5008.7
XS Rating Curve= 0 ,0
Exp/Cntr=0.3,0.1

Type RM Length L Ch R = 1 ,25683   ,380,380,380
BEGIN DESCRIPTION:
BEAVER CREEK 31.0
END DESCRIPTION:
XS GIS Cut Line= 4
      3694294.78     10675930.28      3693331.21     10676727.18
      3693122.87     10677143.85      3693206.21      10677914.7
#Sta/Elev= 30
  3685.4  328.25  3700.8  326.14  3738.8  321.21  3759.7  315.44    3774  309.14
  3788.3  306.31  3795.9  301.51  3814.5  299.96  3847.8  297.36  4029.5  286.34
  4107.5  284.32    4144   280.6  4257.3  276.31  4868.2  271.32  4975.6  268.74
  4989.4  265.85  4992.1  265.35  4995.4  265.85  5014.7  267.86  5028.6  266.41
  5415.4  271.21  5850.6  272.68  5879.4  277.56  5917.1  280.17  5961.2  287.44
  5976.2  288.06  6001.5  295.04    6073  305.52  6122.2  315.44    6177  320.11
#Mann= 8 ,-1 , 0
  3685.4     .16       0  3700.8     .12       0  3814.5     .16       0
  3847.8     .05       0  4029.5     .16       0  4989.4     .07       0
  4995.4     .16       0  5917.1     .16       0
Bank Sta=4975.6,5014.7
XS Rating Curve= 0 ,0
Exp/Cntr=0.3,0.1

Type RM Length L Ch R = 1 ,25303   ,897,897,897
BEGIN DESCRIPTION:
BEAVER CREEK 30.0
END DESCRIPTION:
XS GIS Cut Line= 4
      3693289.54     10675800.09      3693044.75     10676555.31
      3692919.75     10676669.89      3692435.41     10676987.58
#Sta/Elev= 30
  4118.7  319.42  4134.6  316.19  4139.9   317.2  4192.4  312.16  4198.6     309
  4203.9  309.58  4223.9  304.45  4230.6  300.66  4235.8  300.86  4262.6  293.02
    4287  288.59  4294.6  285.27  4326.5  279.36  4381.6  274.14  4907.2  269.86
  4987.3  265.66    4990  265.16  4993.3  265.66  5018.7  267.85    5047  266.81
  5162.4  269.45  5434.6   270.4  5457.8  269.97  5530.1  278.42  5545.2  284.77
  5566.3  289.76  5572.7  294.99  5617.6  310.38  5644.6  315.72  5661.4  316.43
#Mann= 5 ,-1 , 0
  4118.7     .16       0    4287     .16       0  4987.3     .07       0
  4993.3     .16       0  5434.6     .16       0
Bank Sta=4907.2,5162.4
XS Rating Curve= 0 ,0
Exp/Cntr=0.3,0.1

Type RM Length L Ch R = 1 ,24406   ,693,693,693
BEGIN DESCRIPTION:
BEAVER CREEK 29.0
END DESCRIPTION:
XS GIS Cut Line= 3
       3692699.6     10675510.21      3692399.61     10676010.19
      3692399.61     10676910.22
#Sta/Elev= 30
  4383.3  320.07  4430.6  314.51  4464.9  308.09  4486.3  299.11  4499.9  296.11
  4507.7  291.15  4523.2  287.64  4534.9  282.75  4573.4  277.69  4624.3  271.89
  4688.4  267.69  4918.9   267.7  4968.9  268.47  5003.4  266.15  5006.1  265.65
  5009.4  266.15  5046.4   267.7  5136.4  266.15  5456.4  269.95  5546.9  268.86
  5626.4  270.66  5686.4  275.32  5726.4  280.35  5766.4  291.42  5776.4   297.1
  5786.4  299.23  5796.4   304.6  5806.4  305.33  5836.4  313.86  5866.4  316.42
#Mann= 7 ,-1 , 0
  4383.3     .16       0  4430.6     .12       0  4573.4     .05       0
  4918.9     .12       0  5003.4     .07       0  5009.4     .12       0
  5546.9     .16       0
Bank Sta=4968.9,5046.4
XS Rating Curve= 0 ,0
Exp/Cntr=0.3,0.1

Type RM Length L Ch R = 1 ,23713   ,742,742,742
BEGIN DESCRIPTION:
BEAVER CREEK 28.0
END DESCRIPTION:
XS GIS Cut Line= 3
      3692299.59      10675360.2      3691899.61     10675660.19
      3691399.61     10676660.18
#Sta/Elev= 30
  4478.9  315.08  4521.6   312.6  4571.6  298.76  4586.2  293.22  4636.2  282.49
  4681.1  276.06    4707  271.55    4757  266.39  4808.5  265.41    4810  265.42
  4971.6  267.44  5012.2  265.28    5015  264.78  5018.2  265.28  5068.3  269.78
  5082.3  267.18  5289.9  265.83  5296.7  265.69  5426.1  265.72  5479.2  268.41
  5507.1  267.39  5568.6  269.33  5582.6     268  5716.8  268.16  5753.1  270.04
  5769.9  273.53  5780.9  273.87  5999.1  301.28  6021.4  306.38  6096.9   315.1
#Mann= 9 ,-1 , 0
  4478.9     .12       0  4681.1     .16       0  4808.5     .05       0
    4810     .12       0  5012.2     .07       0  5018.2     .12       0
  5289.9     .07       0  5296.7     .12       0  5780.9     .16       0
Bank Sta=4971.6,5068.3
XS Rating Curve= 0 ,0
Exp/Cntr=0.3,0.1