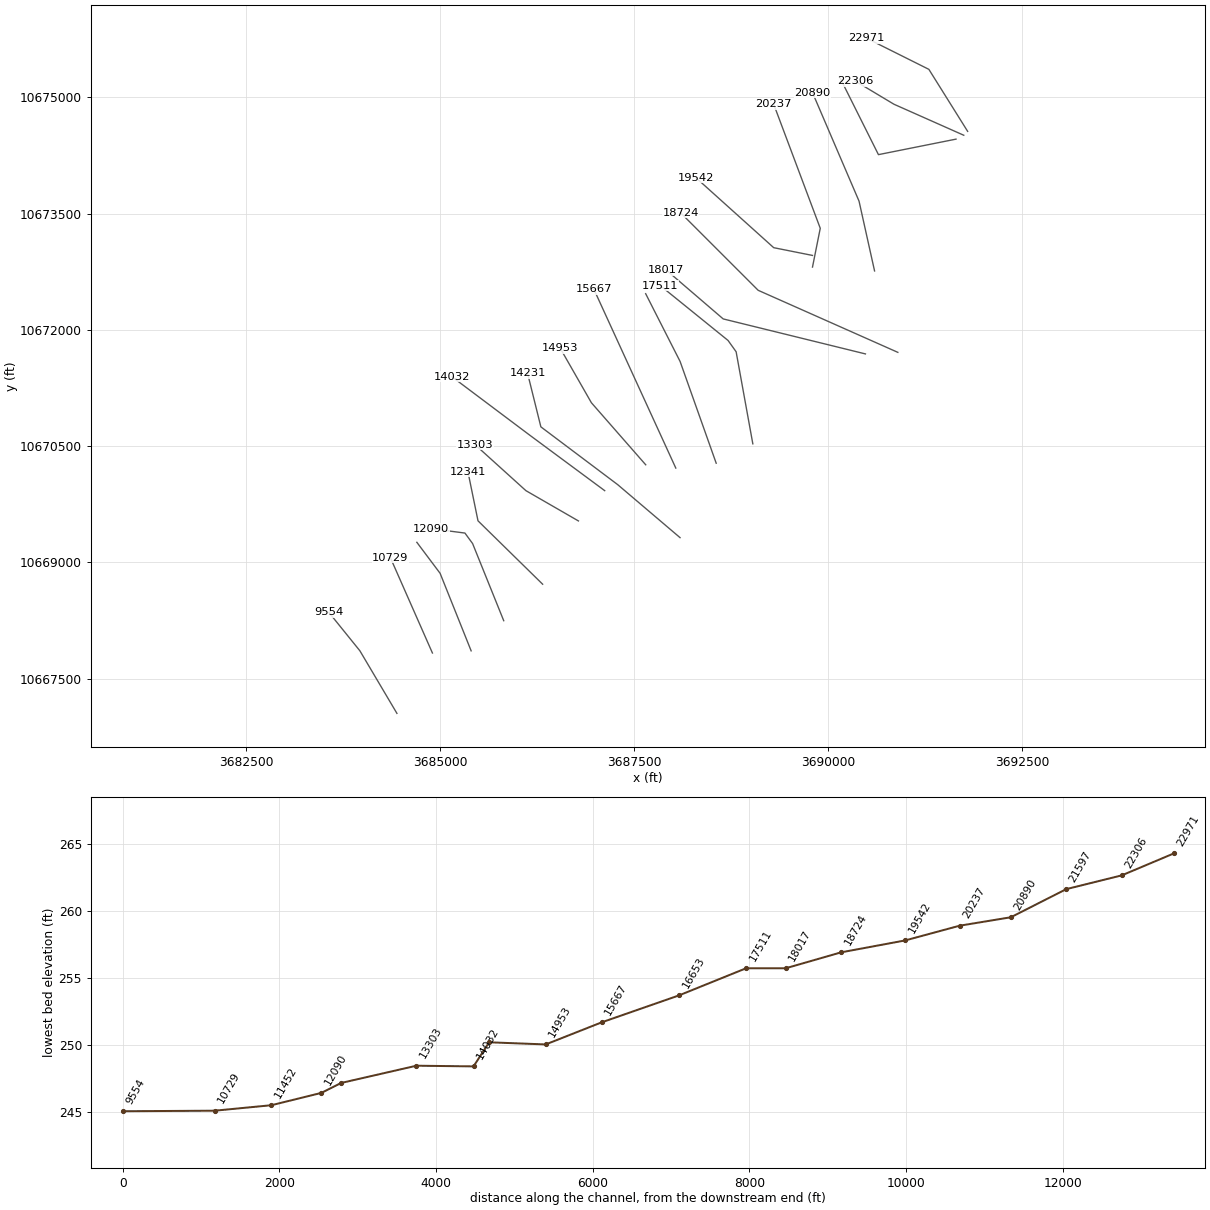
HEC-RAS study BEAVER CREEK.prj: BEAVER CREEK Base Level Engineering

--- BEAVER CREEK.g01 (geometry) --- (continued)

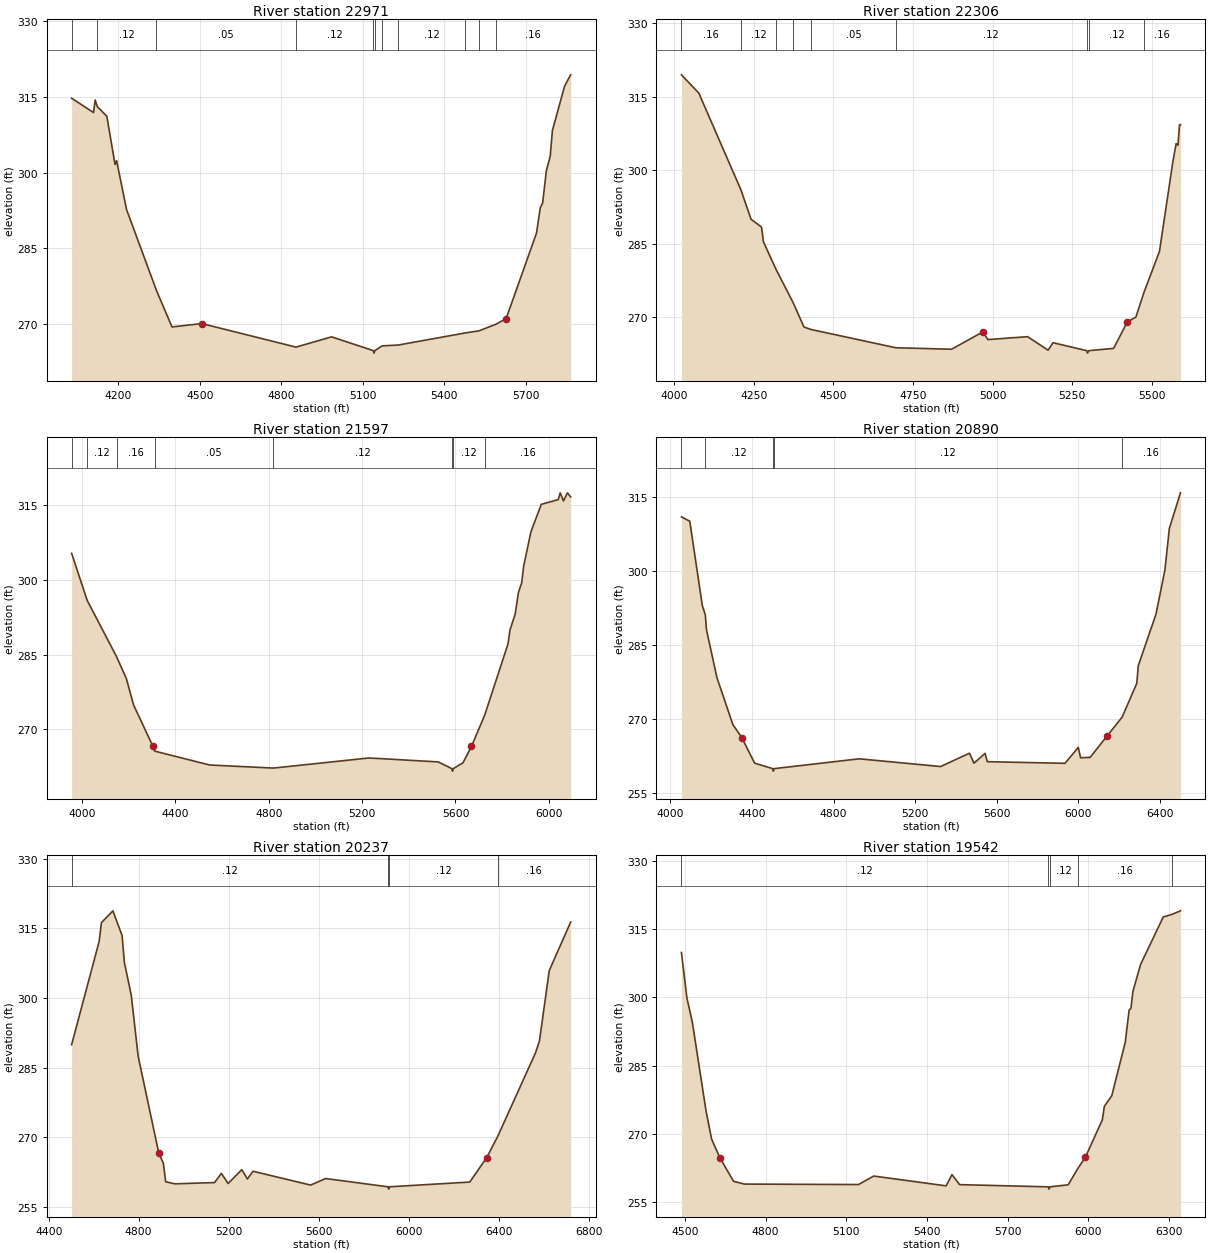
Type RM Length L Ch R = 1 ,22971   ,665,665,665
BEGIN DESCRIPTION:
BEAVER CREEK 27.0
END DESCRIPTION:
XS GIS Cut Line= 3
       3691799.6      10674560.2      3691299.61     10675360.19
      3690499.62     10675760.18
#Sta/Elev= 30
  4028.3  314.73  4109.1  311.89    4115  314.38  4122.8  313.08    4158  311.16
  4188.1  301.63    4194  302.37  4230.5  292.72  4340.7  276.69    4398  269.46
  4507.6  270.13  4854.5  265.47  4985.7   267.5  5139.2  264.78  5141.9  264.28
  5145.2  264.78  5171.9  265.72  5231.3  265.88  5477.2  268.27  5528.4  268.69
    5590  269.98  5628.5  271.11  5740.3  288.04  5754.3  293.07  5762.7  293.93
  5776.7  300.43  5790.6  303.17    5799  308.36  5843.7  317.11  5866.1  319.36
#Mann= 11 ,-1 , 0
  4028.3     .16       0  4122.8     .12       0  4340.7     .05       0
  4854.5     .12       0  5139.2     .07       0  5145.2     .12       0
  5171.9     .05       0  5231.3     .12       0  5477.2     .05       0
  5528.4     .12       0    5590     .16       0
Bank Sta=4507.6,5628.5
XS Rating Curve= 0 ,0
Exp/Cntr=0.3,0.1

Type RM Length L Ch R = 1 ,22306   ,709,709,709
BEGIN DESCRIPTION:
BEAVER CREEK 26.0
END DESCRIPTION:
XS GIS Cut Line= 3
      3691749.59      10674510.2      3690849.61     10674910.19
      3690349.58     10675210.21
#Sta/Elev= 30
  4022.5   319.5  4077.2  315.77  4209.4  296.01  4241.3  289.99  4274.2  288.39
  4280.3  285.37  4319.6  279.78    4374  272.89  4407.5  267.98  4429.7  267.47
    4696  263.74  4871.3  263.43  4969.7  266.98  4985.5  265.41  5110.4     266
  5174.5  263.24  5190.1  264.77  5295.9  263.14  5298.7  262.64  5301.9  263.14
  5380.5  263.61  5423.3     269  5450.5  270.01  5476.8  275.22  5524.4  283.38
  5567.1  301.92  5576.9  305.43  5582.7  305.12  5587.5  309.31  5590.5  309.31
#Mann= 9 ,-1 , 0
  4022.5     .16       0  4209.4     .12       0  4319.6     .16       0
    4374     .12       0  4429.7     .05       0    4696     .12       0
  5295.9     .07       0  5301.9     .12       0  5476.8     .16       0
Bank Sta=4969.7,5423.3
XS Rating Curve= 0 ,0
Exp/Cntr=0.3,0.1

Type RM Length L Ch R = 1 ,21597   ,707,707,707
BEGIN DESCRIPTION:
BEAVER CREEK 25.0
END DESCRIPTION:
XS GIS Cut Line= 3
      3691649.66      10674460.2      3690649.61     10674260.19
       3690149.6      10675260.2
#Sta/Elev= 30
  3955.7  305.31  4022.5  295.86  4148.3  284.57  4190.3  280.17  4220.9  274.91
  4302.5  266.74  4311.9  265.62  4547.2  262.84  4819.9  262.22  5229.9  264.25
  5526.2  263.46  5584.7  262.11  5587.4  261.61  5590.7  262.11  5632.4  263.28
  5668.7  266.58  5725.4  272.85  5825.3  287.15  5833.6  289.91    5856  293.12
    5870  297.47    5884  299.43  5892.3  302.74  5923.1  309.58  5967.8  315.14
  6040.5  316.09  6048.9  317.45  6062.8  315.83  6079.6  317.44  6093.6  316.63
#Mann= 8 ,-1 , 0
  3955.7     .16       0  4022.5     .12       0  4148.3     .16       0
  4311.9     .05       0  4819.9     .12       0  5584.7     .07       0
  5590.7     .12       0  5725.4     .16       0
Bank Sta=4302.5,5668.7
XS Rating Curve= 0 ,0
Exp/Cntr=0.3,0.1

Type RM Length L Ch R = 1 ,20890   ,653,653,653
BEGIN DESCRIPTION:
BEAVER CREEK 24.0
END DESCRIPTION:
XS GIS Cut Line= 3
       3690599.6     10672760.21      3690399.61     10673660.19
       3689799.6      10675060.2
#Sta/Elev= 30
  4054.5  310.96  4095.5  310.07  4156.9  293.01  4171.7   291.1  4177.4  288.08
  4228.6  278.41  4306.7  268.92  4350.3   266.3    4413  261.13  4502.2  260.01
    4505  259.51  4508.2  260.01  4925.2     262  5324.6  260.44    5466  263.14
  5487.8  261.11  5542.2  263.11  5553.1  261.42  5933.8  261.09  5999.1  264.32
    6010  262.22  6057.1  262.29  6140.6  266.65  6214.1  270.45  6285.6  277.27
  6292.9  280.82  6379.9   291.3  6423.4   300.2  6445.2  308.62  6499.6  315.82
#Mann= 5 ,-1 , 0
  4054.5     .16       0  4171.7     .12       0  4502.2     .07       0
  4508.2     .12       0  6214.1     .16       0
Bank Sta=4350.3,6140.6
XS Rating Curve= 0 ,0
Exp/Cntr=0.3,0.1

Type RM Length L Ch R = 1 ,20237   ,695,695,695
BEGIN DESCRIPTION:
BEAVER CREEK 23.0
END DESCRIPTION:
XS GIS Cut Line= 3
       3689799.6     10672810.16      3689899.61     10673310.19
      3689299.62     10674910.16
#Sta/Elev= 30
  4501.9  289.96  4624.3  312.18  4634.5  316.23  4685.5  318.78  4726.3  313.45
  4736.5  307.66  4767.1  300.61  4797.7  287.48  4889.5  266.63  4909.8  264.46
    4920  260.47  4960.8  260.02  5137.3  260.29  5167.6  262.27  5197.8  260.09
  5258.4  263.08  5283.3  261.06  5308.2  262.73  5564.5  259.75  5631.3  261.16
  5908.6  259.38  5911.4  258.88  5914.6  259.38  6272.1   260.4  6346.8  265.62
  6397.1  270.31  6564.9  288.28  6581.8  290.75  6625.4  305.91  6720.6  316.36
#Mann= 4 ,-1 , 0
  4501.9     .12       0  5908.6     .07       0  5914.6     .12       0
  6397.1     .16       0
Bank Sta=4889.5,6346.8
XS Rating Curve= 0 ,0
Exp/Cntr=0.3,0.1

Type RM Length L Ch R = 1 ,19542   ,818,818,818
BEGIN DESCRIPTION:
BEAVER CREEK 22.0
END DESCRIPTION:
XS GIS Cut Line= 3
      3689799.58     10672960.19      3689299.61     10673060.19
      3688299.64     10673960.16
#Sta/Elev= 30
  4487.2  309.91  4507.6  299.92    4528  294.49    4579  274.91  4599.4  268.81
  4629.9  264.74  4680.9   259.5  4721.7  258.89  5145.4  258.79  5202.2  260.66
  5471.3   258.5    5493  260.98  5521.4  258.77    5851  258.28  5853.7  257.78
    5857  258.28    5925  258.73  5960.4  262.28  5988.5  264.75  6052.1  273.07
  6059.5  276.03  6087.2  278.37  6137.3  290.17  6151.5  297.24  6158.2  297.59
  6165.7  301.34  6194.1  307.26  6278.5  317.74  6311.1  318.31  6342.4  319.09
#Mann= 5 ,-1 , 0
  4487.2     .12       0    5851     .07       0    5857     .12       0
  5960.4     .16       0  6311.1     .05       0
Bank Sta=4629.9,5988.5
XS Rating Curve= 0 ,0
Exp/Cntr=0.3,0.1

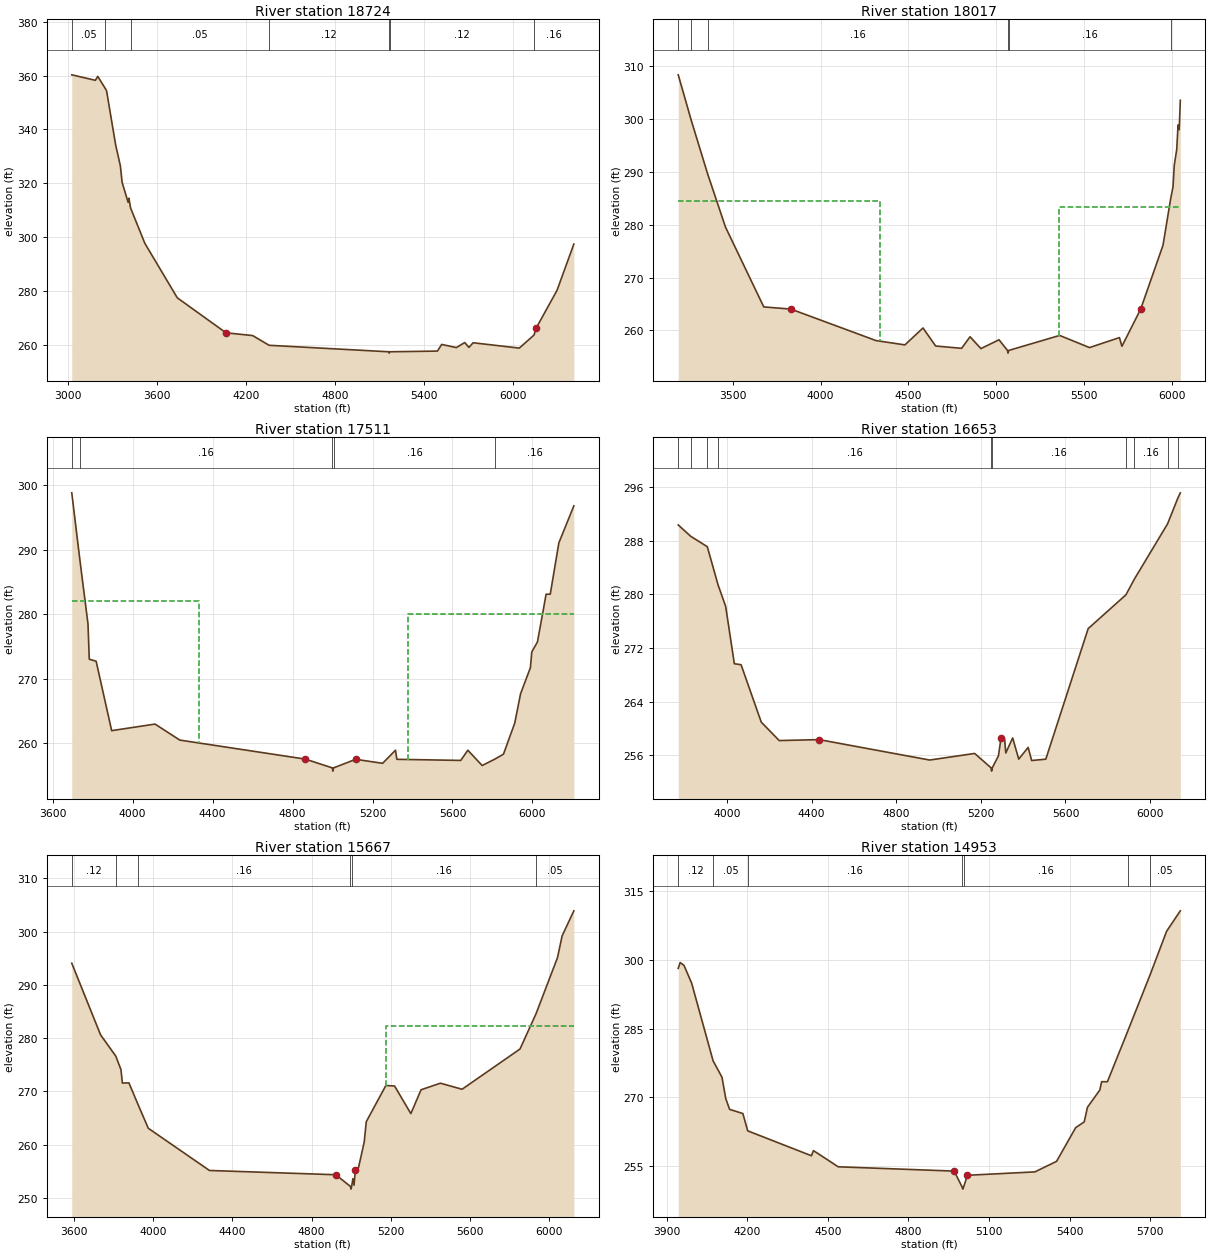
Type RM Length L Ch R = 1 ,18724   ,707,707,707
BEGIN DESCRIPTION:
BEAVER CREEK 21.0
END DESCRIPTION:
XS GIS Cut Line= 3
      3690899.63     10671710.18      3689099.61     10672510.19
      3688099.61     10673510.18
#Sta/Elev= 30
  3024.8   360.3  3184.2  358.26  3199.9  359.73  3248.3  355.44  3259.4  354.38
  3320.3  334.34  3352.4  326.47  3364.1  320.38  3404.4  312.95  3409.9  314.45
  3421.2  310.83  3517.3  297.69  3736.1  277.44  4064.4  264.44  4244.3  263.41
  4354.9   259.8  5161.3  257.39    5164  256.89  5167.3  257.39  5489.6  257.65
  5517.9  260.12  5616.8  258.95  5673.4  260.82  5701.7  259.02    5730  260.74
  6041.1  258.76  6140.5  263.61  6154.2  266.12  6295.7  280.24  6408.8  297.42
#Mann= 7 ,-1 , 0
  3024.8     .05       0  3248.3     .16       0  3421.2     .05       0
  4354.9     .12       0  5161.3     .07       0  5167.3     .12       0
  6140.5     .16       0
Bank Sta=4064.4,6154.2
XS Rating Curve= 0 ,0
Exp/Cntr=0.3,0.1

Type RM Length L Ch R = 1 ,18017   ,506,506,506
BEGIN DESCRIPTION:
BEAVER CREEK 20.0
END DESCRIPTION:
XS GIS Cut Line= 3
      3690481.88       10671690.      3688648.52      10672141.4
      3687913.53     10672772.38
#Sta/Elev= 30
  3190.2   308.4  3264.7  299.74  3357.3  289.66    3459  279.58  3676.9  264.45
  3831.1  264.04  4315.1  258.08  4479.9  257.26  4582.9  260.46  4654.9  257.05
  4802.8  256.61  4850.6   258.8  4912.4  256.56  5015.5  258.23  5063.9   256.2
  5066.6   255.7  5069.9   256.2  5360.4  259.05  5530.5  256.75  5700.6  258.64
  5714.8  256.99  5821.3  264.02  5948.6  276.13  5991.4  284.79  6005.6  287.22
  6012.6  291.26  6026.5  294.24  6034.2  298.91  6040.8  298.01    6047  303.58
#Mann= 6 ,-1 , 0
  3190.2     .16       0  3264.7     .05       0  3357.3     .16       0
  5063.9     .07       0  5069.9     .16       0  5991.4     .16       0
#XS Ineff= 2 ,-1
  3190.2 4338.35   284.6 5356.53 6090.34  283.31
Permanent Ineff=
       F       F
Bank Sta=3831.1,5821.3
XS Rating Curve= 0 ,0
Exp/Cntr=0.3,0.1

Type RM Length L Ch R = 1 ,17511   ,858,858,858
BEGIN DESCRIPTION:
BEAVER CREEK 19.0
END DESCRIPTION:
XS GIS Cut Line= 4
      3689030.47     10670530.26      3688815.19     10671717.78
      3688711.02     10671863.62        3687836.     10672571.97
#Sta/Elev= 30
  3695.3  298.82  3735.9  288.43  3776.5   278.5  3782.9  273.04  3817.2  272.73
  3894.9  261.97  4111.9  262.99  4235.8  260.51    4864  257.56  4998.9   256.2
  5001.6   255.7  5004.9   256.2  5115.5  257.53  5250.5  256.91  5314.8  258.94
  5321.8  257.53  5641.5  257.36  5676.7  258.94  5748.6  256.57  5814.4   257.6
  5855.2  258.33  5911.7  263.16  5940.5  267.67    5990  271.74  5996.7  274.16
  6025.2  275.72  6068.4  283.11  6089.2  283.12  6132.3  291.07  6207.2   296.8
#Mann= 5 ,-1 , 0
  3695.3     .16       0  3735.9     .16       0  4998.9     .07       0
  5004.9     .16       0  5814.4     .16       0
#XS Ineff= 2 , 0
         4333.52  282.07  5376.7          280.04
Permanent Ineff=
       F       F
Bank Sta=4864,5115.5
XS Rating Curve= 0 ,0
Exp/Cntr=0.3,0.1

Type RM Length L Ch R = 1 ,16653   ,986,986,986
BEGIN DESCRIPTION:
BEAVER CREEK 18.0
END DESCRIPTION:
XS GIS Cut Line= 3
      3688558.24     10670280.31      3688092.97     10671592.78
      3687649.16     10672466.53
#Sta/Elev= 30
  3770.1  290.32  3828.6  288.64  3907.5  287.08  3958.1  281.41  3994.3  278.19
  4035.2  269.66    4067  269.51  4162.5  260.96  4247.4  258.22  4436.2  258.36
  4958.3  255.32  5170.9   256.3  5248.2  254.17  5250.9  253.67  5254.2  254.17
  5283.1  255.94  5295.7  258.64  5312.3  258.45  5317.9  256.37  5350.4  258.61
  5379.1  255.46  5423.6   257.2  5440.1  255.25    5507  255.45  5707.3  274.89
  5885.4  279.91    5926  282.28  6082.4  290.48  6131.5  294.36  6142.6   295.1
#Mann= 10 ,-1 , 0
  3770.1     .12       0  3828.6     .16       0  3907.5     .12       0
  3958.1     .16       0  5248.2     .07       0  5254.2     .16       0
  5885.4     .12       0    5926     .16       0  6082.4     .12       0
  6131.5     .16       0
Bank Sta=4436.2,5295.7
XS Rating Curve= 0 ,0
Exp/Cntr=0.3,0.1

Type RM Length L Ch R = 1 ,15667   ,714,714,714
BEGIN DESCRIPTION:
BEAVER CREEK 17.0
END DESCRIPTION:
XS GIS Cut Line= 2
       3688037.4     10670217.82      3686981.84     10672523.38
#Sta/Elev= 30
  3588.9  294.05  3734.4  280.61  3811.3  276.61  3837.4  274.08  3844.5  271.56
  3877.5   271.6  3924.7  267.44  3975.4  263.08  4284.4  255.16  4922.3  254.36
  4996.3  252.16    4999  251.66  5002.3  252.16  5008.8  253.63  5014.3   252.4
  5021.3  255.27  5037.4  255.75  5065.9  260.51  5076.3  264.31  5175.2   271.1
  5219.2  271.01  5301.5  265.83    5353   270.3  5450.5  271.54  5560.1   270.4
  5852.7  277.95  5934.1  284.61  6042.2  295.11  6065.3  299.17  6124.6  303.88
#Mann= 6 ,-1 , 0
  3588.9     .12       0  3811.3     .05       0  3924.7     .16       0
  4996.3     .07       0  5002.3     .16       0  5934.1     .05       0
#XS Ineff= 2 , 0
                         5173.86          282.24
Permanent Ineff=
       F       F
Bank Sta=4922.3,5021.3
XS Rating Curve= 0 ,0
Exp/Cntr=0.3,0.1

Type RM Length L Ch R = 1 ,14953   ,722,722,722
BEGIN DESCRIPTION:
BEAVER CREEK 16.0
END DESCRIPTION:
XS GIS Cut Line= 3
      3687649.62     10670260.17      3686949.61     10671060.19
      3686549.59     10671760.22
#Sta/Elev= 30
  3942.7  298.15  3949.8  299.43  3964.1   298.8  3992.6  294.94  4072.5  277.99
  4105.5  274.43  4119.7  269.75    4134   267.4  4183.3   266.5  4201.4  262.72
  4438.6  257.29  4446.2  258.41  4538.3  254.88  4970.1  253.94  4999.4  250.51
  5002.2  250.01  5005.4  250.51  5019.4  253.03  5270.6  253.77  5351.3  256.07
  5422.5  263.42  5454.2  264.67  5466.4  267.87  5512.5  271.64    5519  273.44
  5540.6  273.43  5615.4  284.33  5700.1  296.83  5760.9  306.23    5812   310.7
#Mann= 7 ,-1 , 0
  3942.7     .12       0  4072.5     .05       0  4201.4     .16       0
  4999.4     .07       0  5005.4     .16       0  5615.4     .16       0
  5700.1     .05       0
Bank Sta=4970.1,5019.4
XS Rating Curve= 0 ,0
Exp/Cntr=0.3,0.1

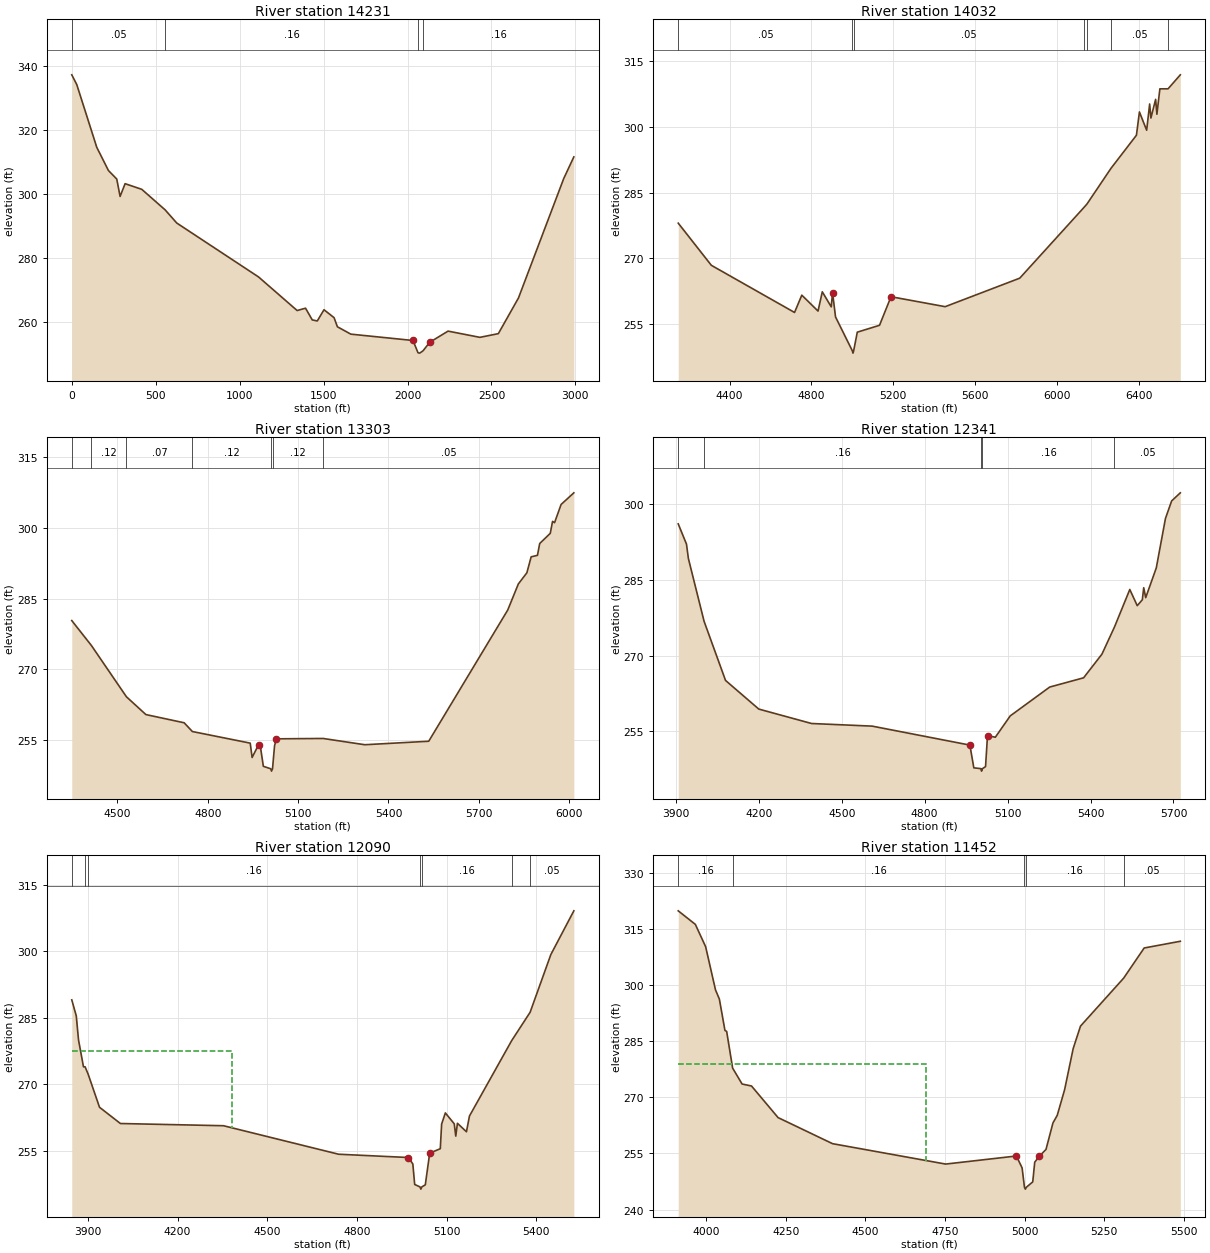
Type RM Length L Ch R = 1 ,14231   ,199,199,199
BEGIN DESCRIPTION:
BEAVER CREEK 15.0
END DESCRIPTION:
XS GIS Cut Line= 4
     3688092.159    10669320.529      3687287.87     10670004.48
      3686298.29     10670749.27      3686126.41     10671442.02
#Sta/Elev= 30
       0  337.28   29.78  334.24  148.92  314.59  218.42  307.33  268.06  304.65
  287.92  299.22   317.7  303.21  416.99  301.44  555.98  295.02  625.48  290.89
 1112.46  274.02 1342.46   263.5 1392.46  264.24 1432.46  260.57 1462.46  260.24
 1502.46  263.75 1562.46  261.27 1582.46  258.41 1662.45  256.11 2032.45  254.13
 2062.45  250.29 2072.45  250.17 2092.45   250.9  2132.3  253.57 2241.49  257.06
 2431.09  255.11 2541.02  256.27 2660.94  267.44 2930.75  304.85 2990.71  311.59
#Mann= 4 ,-1 , 0
       0     .05       0  555.98     .16       0 2062.45     .07       0
 2092.45     .16       0
Bank Sta=2032.45,2132.3
XS Rating Curve= 0 ,0
Exp/Cntr=0.3,0.1

Type RM Length L Ch R = 1 ,14032   ,729,729,729
BEGIN DESCRIPTION:
BEAVER CREEK 14.0
END DESCRIPTION:
XS GIS Cut Line= 3
      3687121.17     10669926.38      3686157.67     10670639.89
      3685153.52      10671394.3
#Sta/Elev= 30
  4148.9  278.03  4310.7  268.41  4717.6  257.65  4753.1   261.6  4832.4  257.97
  4853.3  262.36  4897.1  258.93  4903.4   262.2    4918  256.63  5000.5  248.87
  5003.3  248.37  5006.5  248.87  5024.4  253.15    5133  254.72  5189.3  261.24
  5454.1  258.97  5818.6  265.47  6133.1  281.63  6147.5   282.4  6264.9  290.54
  6389.3  298.09  6403.9   303.4  6439.3  299.23  6453.9  305.22  6460.1  302.01
  6483.1  306.27  6489.3  302.88  6503.9  308.67    6544  308.68  6603.8  311.87
#Mann= 7 ,-1 , 0
  4148.9     .05       0  5000.5     .07       0  5006.5     .05       0
  6133.1     .05       0  6147.5     .08       0  6264.9     .05       0
    6544     .08       0
Bank Sta=4903.4,5189.3
XS Rating Curve= 0 ,0
Exp/Cntr=0.3,0.1

Type RM Length L Ch R = 1 ,13303   ,962,962,962
BEGIN DESCRIPTION:
Mapping XS 063ace02
END DESCRIPTION:
XS GIS Cut Line= 3
      3686782.69     10669535.71      3686105.58     10669926.35
      3685449.34      10670520.1
#Sta/Elev= 30
  4348.6  280.36  4413.8  275.07  4530.1  264.19  4594.6  260.42  4721.6  258.68
    4749  256.82    4941  254.36  4947.3  251.32  4968.9  254.03  4975.6  253.28
  4984.6  249.44    5009  248.92  5011.7  248.42    5015  248.92  5021.8  253.81
  5027.7  255.27  5182.9  255.35  5321.4  254.02  5533.6  254.76  5795.9   282.6
    5831  288.12  5859.4   290.5  5873.6  293.88  5894.5   294.2    5902  296.71
  5937.1  298.87  5944.6   301.4  5951.3  301.13    5973  304.99  6015.3  307.46
#Mann= 7 ,-1 , 0
  4348.6     .16       0  4413.8     .12       0  4530.1     .07       0
    4749     .12       0    5009     .07       0    5015     .12       0
  5182.9     .05       0
Bank Sta=4968.9,5027.7
XS Rating Curve= 0 ,0
Exp/Cntr=0.3,0.1

Type RM Length L Ch R = 1 ,12341   ,251,251,251
BEGIN DESCRIPTION:
BEAVER CREEK 13.0
END DESCRIPTION:
XS GIS Cut Line= 3
      3686321.18     10668719.74      3685487.88     10669537.42
      3685357.67     10670172.84
#Sta/Elev= 30
  3908.6  296.14  3938.4  292.14  3945.4  289.27    4002  276.85  4079.7  265.11
    4200  259.43  4390.9  256.57  4610.2  256.05  4963.6  252.29  4977.8  247.78
  5003.1  247.63  5005.8  247.13  5009.1  247.63  5020.2  248.02  5027.3  254.18
  5055.6  253.85  5109.5  258.08  5252.4   263.8  5374.9  265.63  5441.2  270.32
  5486.5  275.69    5542  283.14  5568.9  279.93  5587.3   281.1  5592.4  283.49
  5599.5  281.52  5637.8  287.41    5671  297.22  5693.3  300.69  5724.7   302.3
#Mann= 5 ,-1 , 0
  3908.6     .16       0    4002     .16       0  5003.1     .07       0
  5009.1     .16       0  5486.5     .05       0
Bank Sta=4963.6,5027.3
XS Rating Curve= 0 ,0
Exp/Cntr=0.3,0.1

Type RM Length L Ch R = 1 ,12090   ,638,638,638
BEGIN DESCRIPTION:
BEAVER CREEK 12.0
END DESCRIPTION:
XS GIS Cut Line= 4
      3685819.47     10668249.24      3685418.43     10669244.01
      3685319.47     10669379.43      3684883.29     10669436.55
#Sta/Elev= 30
  3845.9  289.08    3861  285.47  3868.5  280.05  3885.1  273.97  3890.5  273.98
  3900.8   272.3  3938.8  264.85  4008.7  261.19  4353.7  260.69    4739  254.26
  4972.6  253.52  4987.3  252.06  4993.5  247.44  5011.4  246.89  5014.1  246.39
  5017.4  246.89    5029  247.36  5043.7   254.5  5079.2  255.51  5083.6  261.05
  5096.1  263.58  5125.9  261.12    5131  258.35  5136.5  261.24  5166.7  259.33
  5176.8  262.88    5318  279.88  5379.7  286.27  5449.1  299.29  5526.1  309.16
#Mann= 7 ,-1 , 0
  3845.9     .12       0  3890.5     .16       0  3900.8     .16       0
  5011.4     .07       0  5017.4     .16       0    5318     .16       0
  5379.7     .05       0
#XS Ineff= 2 , 0
         4381.93  277.53
Permanent Ineff=
       F       F
Bank Sta=4972.6,5043.7
XS Rating Curve= 0 ,0
Exp/Cntr=0.3,0.1

Type RM Length L Ch R = 1 ,11452   ,723,723,723
BEGIN DESCRIPTION:
BEAVER CREEK 11.0
END DESCRIPTION:
XS GIS Cut Line= 3
      3685399.59     10667860.22      3684999.61     10668860.19
      3684699.61     10669260.19
#Sta/Elev= 30
  3912.2   319.9    3966  316.27  3998.3   310.3  4029.3  298.75  4041.4   296.3
  4058.9  287.92  4064.3  287.66  4083.1  277.83  4112.8  273.58  4142.4  273.05
  4225.8   264.6  4396.8  257.63  4752.2  252.17  4974.4  254.33  4992.3  251.15
  4999.7  245.97  5002.5  245.47  5005.7  245.97  5025.7  247.41  5031.9  252.66
  5046.5   254.3  5067.3  256.08  5089.2  263.17  5102.7  265.22  5125.7  272.03
  5152.7  283.05  5175.7  289.07  5311.1  301.88  5375.7  309.96  5489.2  311.76
#Mann= 5 ,-1 , 0
  3912.2     .16       0  4083.1     .16       0  4999.7     .07       0
  5005.7     .16       0  5311.1     .05       0
#XS Ineff= 2 , 0
         4691.82   278.9
Permanent Ineff=
       F       F
Bank Sta=4974.4,5046.5
XS Rating Curve= 0 ,0
Exp/Cntr=0.3,0.1

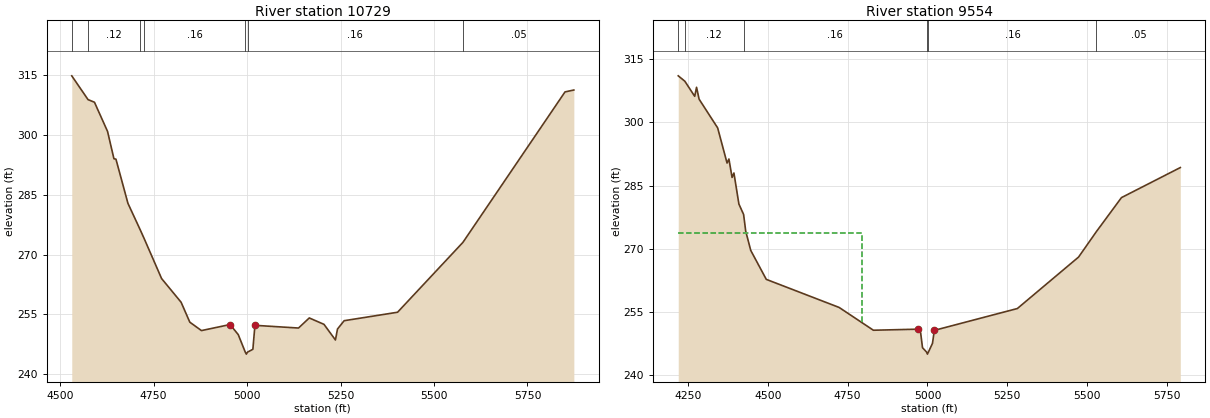
Type RM Length L Ch R = 1 ,10729   ,1175,1175,1175
BEGIN DESCRIPTION:
Mapping XS aac11626
END DESCRIPTION:
XS GIS Cut Line= 2
      3684900.38     10667832.64      3684358.72     10669061.79
#Sta/Elev= 30
  4530.9  314.83  4574.4  308.87  4591.6  308.21  4626.6   300.9  4643.7  294.05
  4649.1  293.93  4681.2  282.86  4714.3  276.17  4724.9  273.96  4771.2  264.01
  4823.4  258.07  4846.7  253.07  4877.9  250.96  4954.4  252.48  4976.3  249.95
  4995.1  245.56  4997.9  245.06  5001.1  245.56  5015.4  246.27  5020.9  252.28
  5137.5   251.6  5166.3  254.13  5205.7  252.52  5236.3  248.61  5241.8  251.35
  5259.6  253.44  5402.5  255.56  5577.3  273.07  5850.5   310.8  5874.1  311.27
#Mann= 7 ,-1 , 0
  4530.9     .16       0  4574.4     .12       0  4714.3     .16       0
  4724.9     .16       0  4995.1     .07       0  5001.1     .16       0
  5577.3     .05       0
Bank Sta=4954.4,5020.9
XS Rating Curve= 0 ,0
Exp/Cntr=0.3,0.1

Type RM Length L Ch R = 1 ,9554    ,857,857,857
BEGIN DESCRIPTION:
BEAVER CREEK 10.0
END DESCRIPTION:
XS GIS Cut Line= 3
      3684442.75     10667053.89      3683965.31      10667861.2
      3683566.34     10668355.57
#Sta/Elev= 30
  4219.1  311.06  4239.8  309.78  4270.7   306.2  4276.5  308.34  4284.5  305.52
  4342.6  298.71  4372.1  290.36  4377.9  291.32  4387.8  286.95  4393.6     288
  4409.2  280.63  4423.9  278.17  4430.6  274.18  4446.3  269.63    4495  262.76
  4723.2   256.1  4830.6  250.69    4970  250.94  4978.7  250.07  4984.5  246.55
  4997.1  245.52  4999.9  245.02  5003.1  245.52  5015.8  247.59  5021.6  250.66
  5281.7  255.84  5473.6  268.06  5529.6  274.12  5607.9  282.16  5792.3  289.29
#Mann= 6 ,-1 , 0
  4219.1     .16       0  4239.8     .12       0  4423.9     .16       0
  4997.1     .07       0  5003.1     .16       0  5529.6     .05       0
#XS Ineff= 2 , 0
         4795.45  273.87
Permanent Ineff=
       F       F
Bank Sta=4970,5021.6
XS Rating Curve= 0 ,0
Exp/Cntr=0.3,0.1