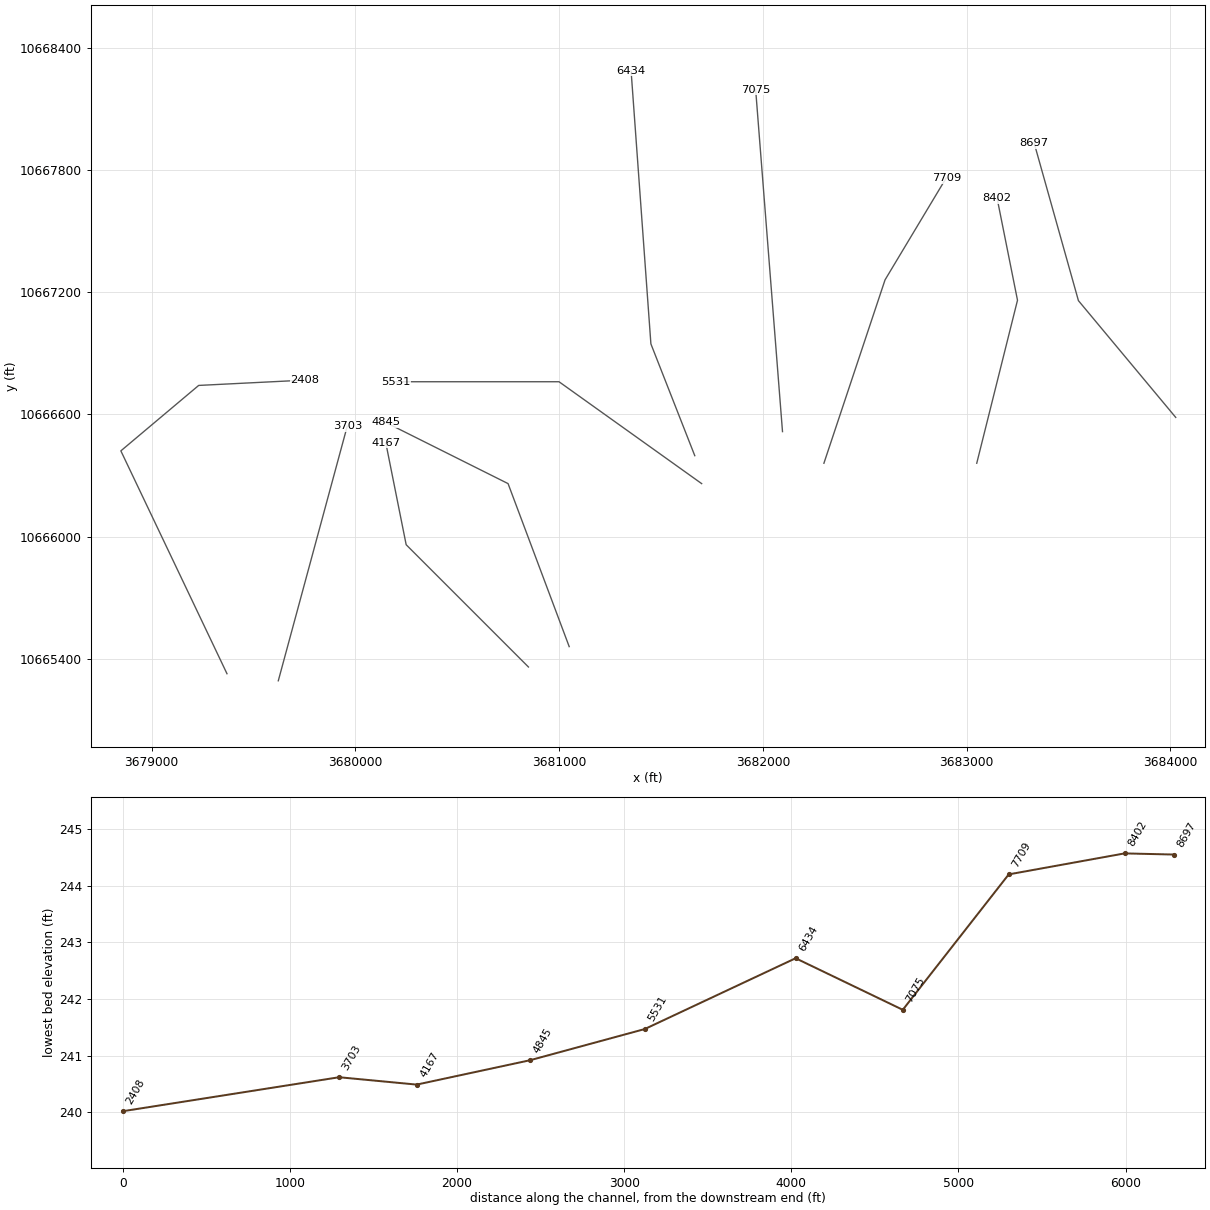
HEC-RAS study BEAVER CREEK.prj: BEAVER CREEK Base Level Engineering

--- BEAVER CREEK.g01 (geometry) --- (continued)

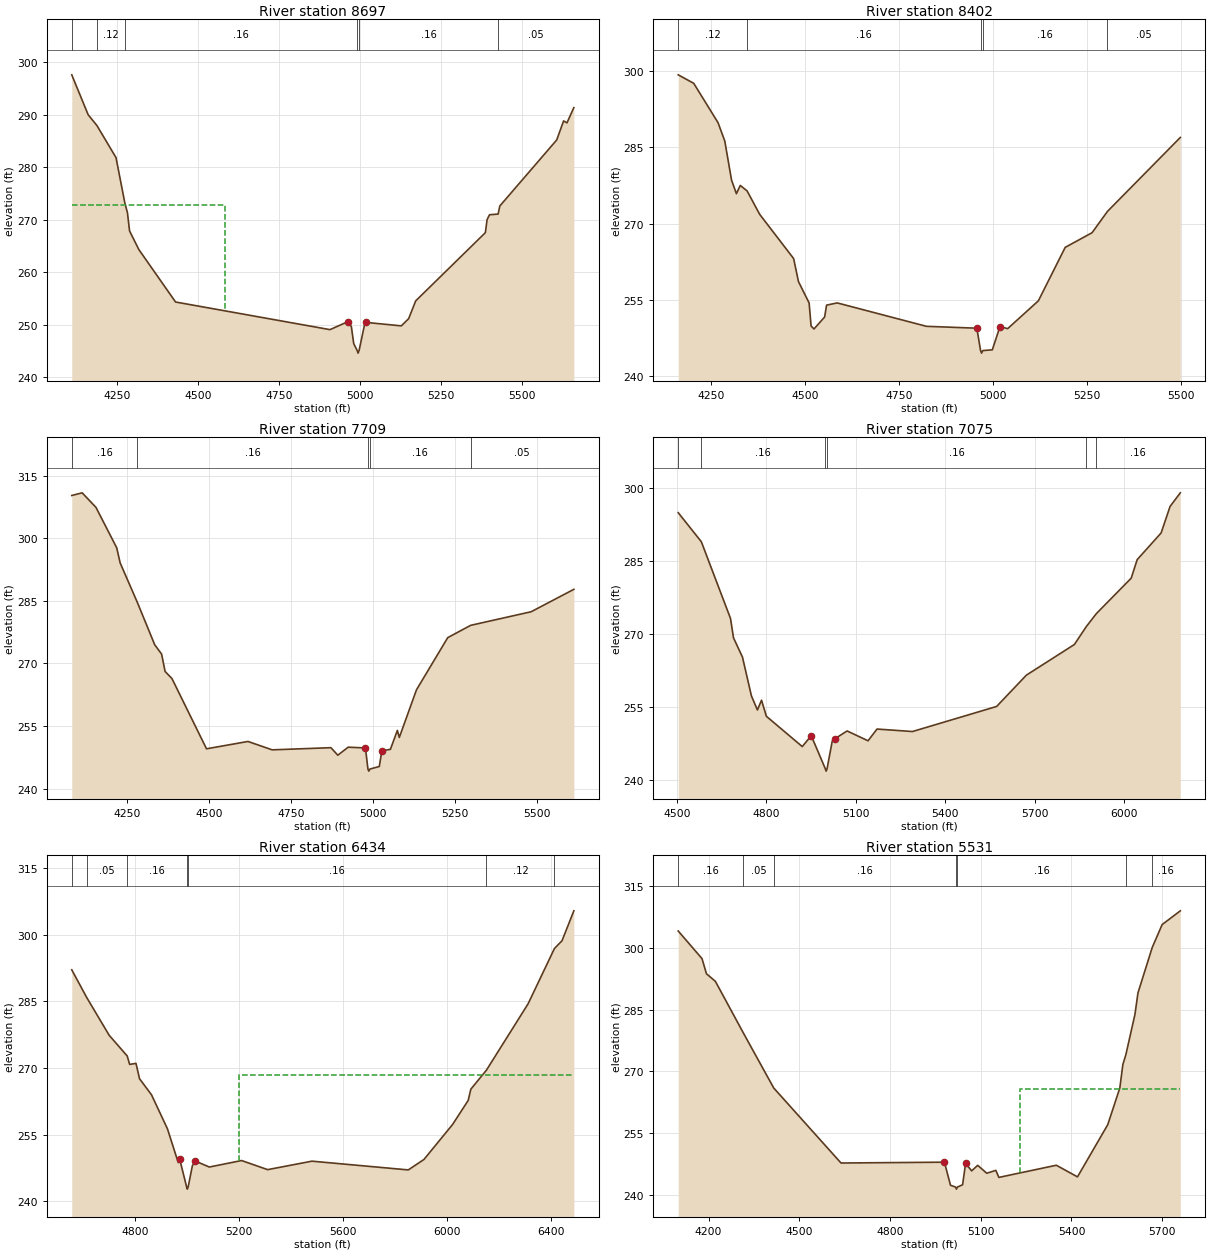
Type RM Length L Ch R = 1 ,8697    ,295,295,295
BEGIN DESCRIPTION:
BEAVER CREEK 9.0
END DESCRIPTION:
XS GIS Cut Line= 3
      3684026.08     10666585.15      3683548.64     10667158.08
      3683331.64      10667930.6
#Sta/Elev= 30
  4110.7  297.63  4161.3  290.01  4188.4  287.95  4247.2  281.83  4274.6  273.11
  4282.4  271.33  4288.9  267.86  4317.5  264.31  4430.8   254.3  4906.9  249.03
  4962.5  250.56  4972.9  249.59  4980.2  246.35  4990.7  245.05  4993.5  244.55
  4996.7  245.05  5014.3  250.22  5019.5   250.4  5126.9  249.75  5149.5  251.12
  5171.3  254.52  5386.1  267.53  5391.3  269.99  5398.8  270.94  5425.4  271.07
  5430.6  272.61  5606.1  285.21  5627.3  288.84  5637.7  288.47  5658.9  291.38
#Mann= 6 ,-1 , 0
  4110.7     .16       0  4188.4     .12       0  4274.6     .16       0
  4990.7     .07       0  4996.7     .16       0  5425.4     .05       0
#XS Ineff= 2 , 0
         4582.95  272.78
Permanent Ineff=
       F       F
Bank Sta=4962.5,5019.5
XS Rating Curve= 0 ,0
Exp/Cntr=0.3,0.1

Type RM Length L Ch R = 1 ,8402    ,693,693,693
BEGIN DESCRIPTION:
BEAVER CREEK 8.0
END DESCRIPTION:
XS GIS Cut Line= 3
      3683049.61     10666360.18      3683249.61     10667160.19
      3683149.62     10667660.15
#Sta/Elev= 30
  4162.7  299.27  4203.9   297.6  4268.4  289.88  4286.4  286.27  4304.4  278.59
  4317.3  275.91  4327.6  277.53  4345.7  276.46  4379.2  271.85  4469.4  263.16
  4482.3  258.63  4510.6  254.42  4515.8  249.91  4523.5  249.32  4551.8  251.67
    4557     254  4585.3  254.44  4822.4  249.84  4956.4  249.47  4966.3  245.07
    4969  244.57  4972.3  245.07  4997.5  245.22  5017.9  249.79  5038.3  249.38
  5119.9  254.85  5191.3  265.36  5262.7  268.24  5303.5  272.42  5497.2  286.96
#Mann= 5 ,-1 , 0
  4162.7     .12       0  4345.7     .16       0  4966.3     .07       0
  4972.3     .16       0  5303.5     .05       0
Bank Sta=4956.4,5017.9
XS Rating Curve= 0 ,0
Exp/Cntr=0.3,0.1

Type RM Length L Ch R = 1 ,7709    ,634,634,634
BEGIN DESCRIPTION:
BEAVER CREEK 7.0
END DESCRIPTION:
XS GIS Cut Line= 3
      3682299.59     10666360.14      3682599.61     10667260.19
       3682899.6     10667760.17
#Sta/Elev= 30
  4081.2  310.26  4112.9   310.9    4155  307.42  4218.3  297.73  4228.8  294.11
  4281.5   284.6  4334.2   274.5  4355.3  272.25  4365.9  268.09  4386.9  266.38
  4492.3  249.55  4618.8  251.31  4692.6   249.3  4871.8  249.82  4892.9  248.02
  4924.5  249.94  4977.2  249.76  4984.8   244.7  4987.5   244.2  4990.8   244.7
  5019.4  245.31  5027.3  249.08  5053.3  249.42  5074.6  253.96  5080.5  252.27
  5132.9  263.69  5228.2  276.19  5298.2  279.14  5482.8   282.4    5613  287.77
#Mann= 5 ,-1 , 0
  4081.2     .16       0  4281.5     .16       0  4984.8     .07       0
  4990.8     .16       0  5298.2     .05       0
Bank Sta=4977.2,5027.3
XS Rating Curve= 0 ,0
Exp/Cntr=0.3,0.1

Type RM Length L Ch R = 1 ,7075    ,641,641,641
BEGIN DESCRIPTION:
BEAVER CREEK 6.0
END DESCRIPTION:
XS GIS Cut Line= 2
      3682096.38      10666515.4      3681964.56     10668194.43
#Sta/Elev= 30
    4504  294.87  4581.5  288.91  4679.3  273.17  4689.4  269.18  4719.5  265.22
  4749.5  257.26  4769.6  254.37  4783.4  256.37  4799.7  253.07  4920.1  246.85
  4950.2  249.09  4997.3  242.31  5000.1  241.81  5003.3  242.31  5020.4  247.92
  5030.4  248.49  5070.5  250.06  5140.7  248.04  5170.8  250.45  5289.7  249.94
  5572.1  255.09  5671.9  261.52  5832.9  267.81    5873   271.5  5906.6  274.15
  6023.5  281.43  6043.5  285.23  6123.8  290.71  6153.9  296.16  6188.2  298.95
#Mann= 6 ,-1 , 0
    4504     .16       0  4581.5     .16       0  4997.3     .07       0
  5003.3     .16       0    5873     .05       0  5906.6     .16       0
Bank Sta=4950.2,5030.4
XS Rating Curve= 0 ,0
Exp/Cntr=0.3,0.1

Type RM Length L Ch R = 1 ,6434    ,903,903,903
BEGIN DESCRIPTION:
BEAVER CREEK 5.0
END DESCRIPTION:
XS GIS Cut Line= 3
      3681665.82     10666397.33      3681450.55     10666945.92
      3681353.37     10668285.69
#Sta/Elev= 30
  4556.7  292.13    4614  285.92  4700.8  277.37  4770.1  272.72  4779.5  270.82
  4803.9  271.05  4817.6  267.59  4863.5  263.99    4925  256.31  4966.6  248.69
    4972   249.5  4998.8  243.22  5001.5  242.72  5004.8  243.22  5020.9  247.98
  5032.4  249.04  5086.1   247.7  5210.4  249.16  5310.7  247.11  5481.2  249.02
  5852.1  247.05  5912.3   249.4  6022.6  257.29  6082.7  262.71  6092.8  265.24
  6152.9  269.53  6313.3  284.48  6414.7  296.94  6443.7  298.67  6489.3  305.42
#Mann= 7 ,-1 , 0
  4556.7     .16       0    4614     .05       0  4770.1     .16       0
  4998.8     .07       0  5004.8     .16       0  6152.9     .12       0
  6414.7     .16       0
#XS Ineff= 2 , 0
                            5200          268.39
Permanent Ineff=
       F       F
Bank Sta=4972,5032.4
XS Rating Curve= 0 ,0
Exp/Cntr=0.3,0.1

Type RM Length L Ch R = 1 ,5531    ,686,686,686
BEGIN DESCRIPTION:
BEAVER CREEK 4.0
END DESCRIPTION:
XS GIS Cut Line= 3
      3681699.62     10666260.18      3680999.61     10666760.19
      3680199.56     10666760.19
#Sta/Elev= 30
  4099.7  304.03  4178.4  297.33  4193.1  293.66  4222.6  291.83  4314.6  279.38
  4415.5  265.98    4638   247.8    4980     248    5000  242.41    5017  241.97
  5019.7  241.47    5023  241.97    5040  242.52    5050  247.71    5070  245.89
    5090  247.24    5120  245.32    5150  246.02    5160  244.31    5350  247.26
    5420  244.44    5520  257.08    5560  265.98    5570  271.67    5580  274.06
    5610  283.82    5620  289.04  5667.3  300.07    5700  305.59    5760  308.92
#Mann= 7 ,-1 , 0
  4099.7     .16       0  4314.6     .05       0  4415.5     .16       0
    5017     .07       0    5023     .16       0    5580     .12       0
  5667.3     .16       0
#XS Ineff= 2 , 0
                         5229.32          265.82
Permanent Ineff=
       F       F
Bank Sta=4980,5050
XS Rating Curve= 0 ,0
Exp/Cntr=0.3,0.1

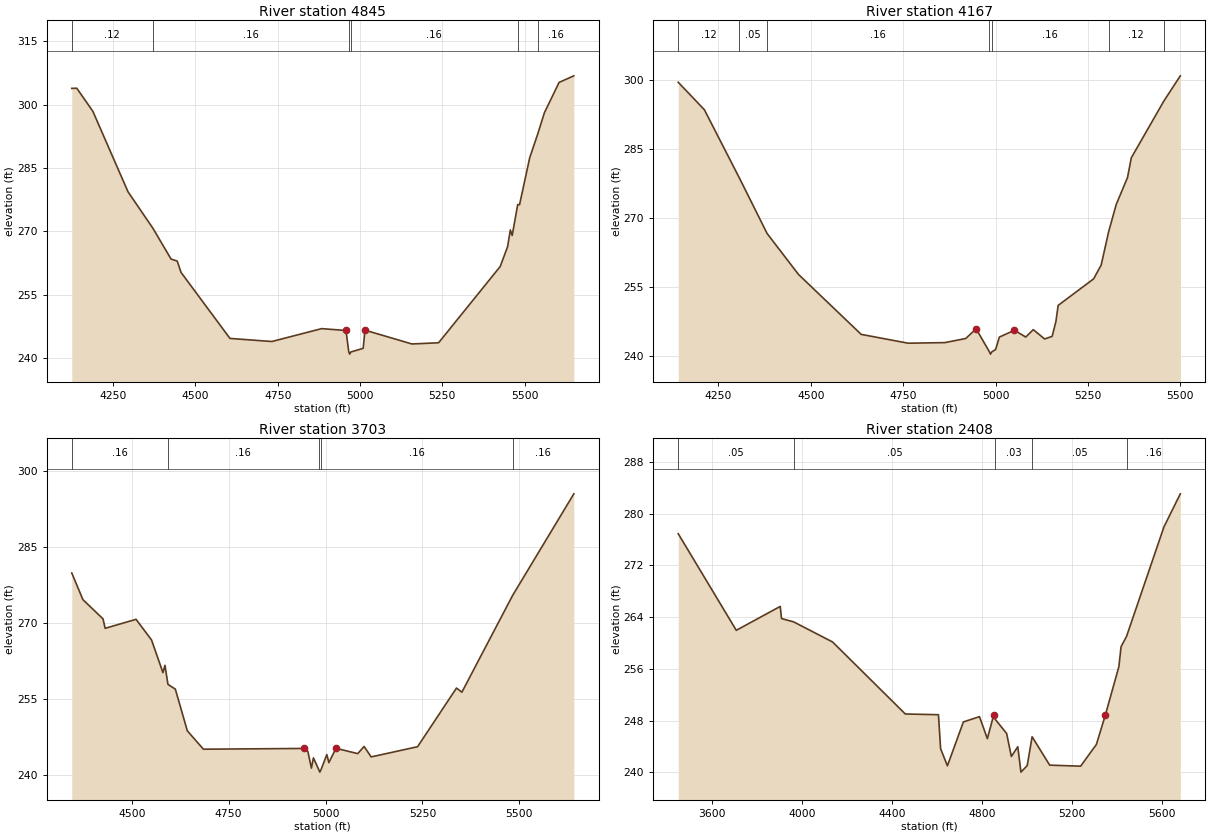
Type RM Length L Ch R = 1 ,4845    ,678,678,678
BEGIN DESCRIPTION:
BEAVER CREEK 3.0
END DESCRIPTION:
XS GIS Cut Line= 3
      3681049.62     10665460.16      3680749.61     10666260.19
      3680149.57     10666560.21
#Sta/Elev= 30
  4124.3  303.88  4139.5  303.93  4188.4  298.45  4295.2  279.38  4370.9  270.73
    4426  263.44  4444.7  262.97  4456.3  260.28  4604.9  244.64  4732.2  243.91
  4883.5  246.96  4957.4  246.52  4965.9  241.42  4968.7  240.92  4971.9  241.42
  5009.5  242.29  5015.1   246.6  5157.6  243.33  5238.7  243.61  5425.9  261.68
  5448.3  266.37  5456.7  270.34  5462.3  269.03  5479.1  276.36  5484.6  276.31
  5515.4  287.41  5539.7  293.03  5560.1   298.1  5604.8   305.3  5649.6  306.86
#Mann= 6 ,-1 , 0
  4124.3     .12       0  4370.9     .16       0  4965.9     .07       0
  4971.9     .16       0  5479.1     .12       0  5539.7     .16       0
Bank Sta=4957.4,5015.1
XS Rating Curve= 0 ,0
Exp/Cntr=0.3,0.1

Type RM Length L Ch R = 1 ,4167    ,464,464,464
BEGIN DESCRIPTION:
BEAVER CREEK 2.0
END DESCRIPTION:
XS GIS Cut Line= 3
      3680849.63     10665360.17      3680249.61     10665960.19
       3680149.6     10666460.23
#Sta/Elev= 30
  4141.3  299.51    4212  293.55  4306.6  278.76  4381.7  266.69  4466.6   257.8
  4636.3  244.78  4763.6  242.86  4862.6  242.99  4919.1  243.88  4947.4  245.98
  4983.3  240.99  4986.1  240.49  4989.9  240.99    5000  241.49  5010.2  244.19
    5051  245.67  5081.6   244.2    5102  245.81  5132.6  243.78    5153  244.34
  5163.2  247.57  5169.3  251.07  5265.2  256.83  5285.6  259.81    5306  267.09
  5326.4  272.98    5357  278.85  5367.2  283.11  5455.1  295.41  5499.8  300.91
#Mann= 7 ,-1 , 0
  4141.3     .12       0  4306.6     .05       0  4381.7     .16       0
  4983.3     .07       0  4989.9     .16       0    5306     .12       0
  5455.1     .16       0
Bank Sta=4947.4,5051
XS Rating Curve= 0 ,0
Exp/Cntr=0.3,0.1

Type RM Length L Ch R = 1 ,3703    ,1295,1295,1295
BEGIN DESCRIPTION:
Mapping XS 77539628
END DESCRIPTION:
XS GIS Cut Line= 2
      3679621.99     10665292.42      3679960.52     10666542.38
#Sta/Elev= 30
  4345.4  279.89  4374.2  274.63    4426  270.84  4431.5  268.98  4511.2  270.75
  4551.1  266.69  4580.6  260.24  4585.8  261.69  4593.5  257.92  4612.5  256.99
  4643.5  248.76    4685  245.14    4944  245.29  4954.3  244.72  4963.5  241.41
  4968.7  243.43  4982.4  241.12  4985.2  240.62  4988.4  241.12  5003.3  244.08
  5008.5  242.49  5026.9  245.32    5083  244.27  5099.4  245.68  5117.7  243.62
  5237.3  245.63  5337.7   257.2  5351.6  256.38  5482.7  275.49  5640.4   295.5
#Mann= 5 ,-1 , 0
  4345.4     .16       0  4593.5     .16       0  4982.4     .07       0
  4988.4     .16       0  5482.7     .16       0
Bank Sta=4944,5026.9
XS Rating Curve= 0 ,0
Exp/Cntr=0.3,0.1

Type RM Length L Ch R = 1 ,2408    ,0,0,0
BEGIN DESCRIPTION:
BEAVER CREEK 1.0
END DESCRIPTION:
XS GIS Cut Line= 4
      3679370.26     10665327.13      3678849.42      10666420.9
      3679231.37     10666742.08      3679752.23     10666768.12
#Sta/Elev= 30
  3450.7  276.89  3708.8  261.95  3904.2  265.65  3909.8  263.77  3963.6  263.26
  4136.8  260.15  4460.2  249.01  4607.5   248.9  4617.1  243.64  4647.4  240.99
  4718.3  247.78  4789.8   248.6    4825   245.2  4853.6  248.91  4860.1  248.18
  4910.6     246  4931.6  242.44  4960.2  243.95  4974.3  240.02  5002.1  241.03
  5023.9  245.49    5102   241.1  5239.5  240.94  5309.6   244.3  5349.7  248.87
  5409.7  256.34  5419.3  259.41  5443.7  261.02    5610  277.95  5682.7  283.06
#Mann= 5 ,-1 , 0
  3450.7     .05       0  3963.6     .05       0  4860.1     .03       0
  5023.9     .05       0  5443.7     .16       0
Bank Sta=4853.6,5349.7
XS Rating Curve= 0 ,0
Exp/Cntr=0.3,0.1

Chan Stop Cuts=-1
Use User Specified Reach Order=0
Composite Channel Slope=5

--- BEAVER CREEK.g02 (geometry) ---

Geom Title=TEST Existing Conditions
Program Version=4.10

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
River Reach=BEAVER CREEK    ,Reach-1

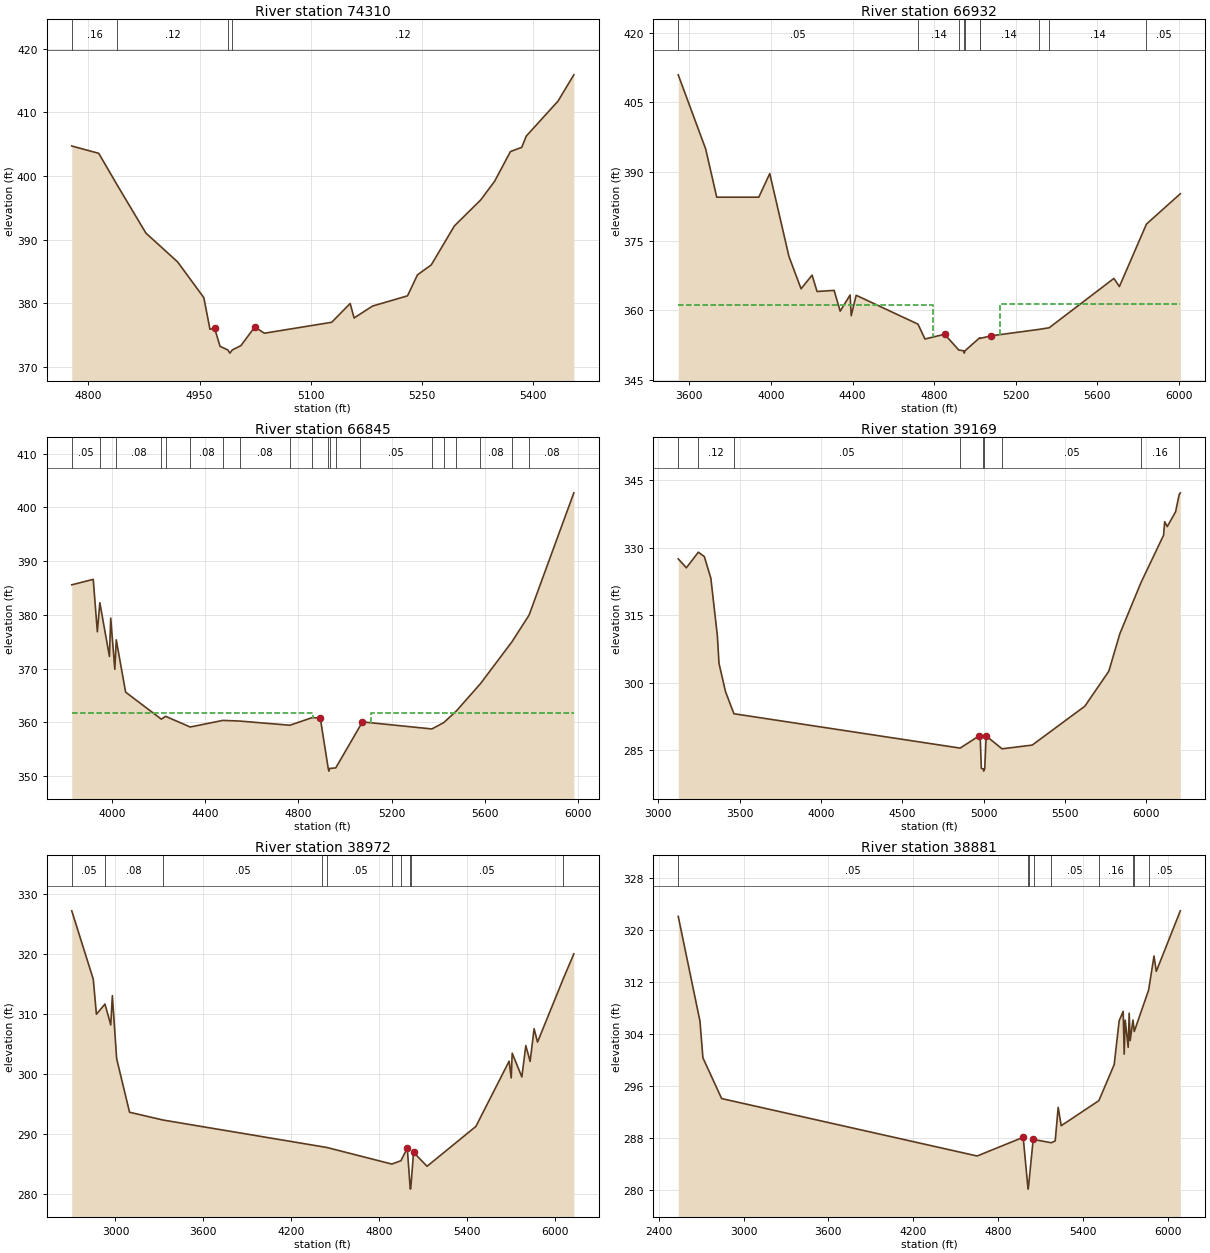
Type RM Length L Ch R = 1 ,74310   ,431,431,431
BEGIN DESCRIPTION:
BEAVER CREEK 116.0
END DESCRIPTION:
XS GIS Cut Line= 3
       3725199.6      10699510.2      3725049.61     10699710.19
      3724899.61      10700110.2
#Sta/Elev= 30
  4777.6  404.72    4814  403.57  4838.8   398.6  4877.6  391.03  4920.3  386.51
  4955.7  380.89    4964  375.91  4970.3  376.07  4977.6  373.23  4988.1  372.66
  4990.9  372.16  4994.1  372.66  5005.7  373.34  5024.5  376.27  5037.4  375.29
  5128.2  377.01  5153.1  379.96  5158.4  377.69  5183.3  379.56  5230.5  381.17
  5243.9  384.47  5262.5  386.03  5293.7  392.16  5329.3  396.26    5348  399.19
  5369.3  403.85  5384.5  404.51  5390.7  406.29  5433.4  411.77  5454.8  415.91
#Mann= 4 ,-1 , 0
  4777.6     .16       0  4838.8     .12       0  4988.1     .07       0
  4994.1     .12       0
Bank Sta=4970.3,5024.5
XS Rating Curve= 0 ,0
Exp/Cntr=0.3,0.1

Type RM Length L Ch R = 1 ,66932   ,87,87,87
BEGIN DESCRIPTION:
Mapping XS 115b8afd
END DESCRIPTION:
XS GIS Cut Line= 4
      3722657.02     10694304.43      3721582.41     10694729.76
      3721393.67     10695213.66      3721155.51     10695963.84
#Sta/Elev= 30
  3545.4   410.9  3680.2  394.85  3734.2  384.46  3940.5  384.46  3994.3  389.56
  4088.3  371.66  4147.8  364.67  4201.8  367.61  4226.2  364.08  4309.9  364.32
  4339.6  359.83  4388.3  363.33  4393.7  358.84    4418  363.26  4721.3  357.02
  4755.4  353.81  4851.9  354.84  4921.1  351.43  4945.5  351.26  4948.2  350.76
  4951.5  351.26  5023.5  354.07  5024.7  353.94  5081.5  354.51  5313.2  355.88
  5364.4  356.24  5681.9   366.9  5708.9  365.15  5841.6  378.65  6007.6   385.2
#Mann= 10 ,-1 , 0
  3545.4     .05       0  4721.3     .14       0  4921.1     .12       0
  4945.5     .07       0  4951.5     .14       0  5023.5     .08       0
  5024.7     .14       0  5313.2     .12       0  5364.4     .14       0
  5841.6     .05       0
#XS Ineff= 2 , 0
         4793.63  361.24 5124.21          361.34
Permanent Ineff=
       F       F
Bank Sta=4851.9,5081.5
XS Rating Curve= 0 ,0
Exp/Cntr=0.3,0.1

Type RM Length L Ch R = 1 ,66845   ,591,591,591
BEGIN DESCRIPTION:
BEAVER CREEK 102.0
END DESCRIPTION:
XS GIS Cut Line= 4
      3721851.32     10693888.98      3721504.09     10694659.83
      3721351.31     10695125.11      3721045.74     10695882.09
#Sta/Elev= 30
  3828.8  385.58  3920.8   386.6  3938.4  376.84  3949.1  382.25  3990.2  372.25
  3995.7   379.4  4013.3  369.84  4019.4  375.35  4059.6  365.61  4212.6  360.58
  4230.8  361.11  4336.5  359.12  4476.1  360.35  4547.8  360.23  4763.4  359.45
  4858.1  360.85  4893.7  360.81  4927.8  351.41  4930.5  350.91  4933.8  351.41
    4960  351.51  5061.9  359.13  5074.6  360.07    5372  358.76  5422.8  359.94
  5476.1  362.07  5580.2  367.19  5715.1  374.98  5788.4  379.94  5980.3   402.7
#Mann= 20 ,-1 , 0
  3828.8     .05       0  3949.1     .12       0  4019.4     .08       0
  4212.6     .12       0  4230.8     .05       0  4336.5     .08       0
  4476.1     .12       0  4547.8     .08       0  4763.4     .12       0
  4858.1     .05       0  4927.8     .07       0  4933.8     .05       0
    4960     .08       0  5061.9     .05       0    5372     .08       0
  5422.8     .12       0  5476.1     .05       0  5580.2     .08       0
  5715.1     .05       0  5788.4     .08       0
#XS Ineff= 2 , 0
         4861.22  361.67  5109.5          361.71
Permanent Ineff=
       F       F
Bank Sta=4893.7,5074.6
XS Rating Curve= 0 ,0
Exp/Cntr=0.3,0.1

Type RM Length L Ch R = 1 ,39169   ,197,197,197
BEGIN DESCRIPTION:
BEAVER CREEK 54.0
END DESCRIPTION:
XS GIS Cut Line= 4
      3705029.51     10684139.52      3703304.28     10684269.73
      3703054.71     10684443.34      3702588.65     10685386.29
#Sta/Elev= 30
  3122.8  327.54  3172.8  325.55  3246.3  329.02  3283.2  328.05  3323.3  323.23
  3363.4  310.42  3373.4  304.28  3413.5     298  3465.2   293.1  4855.4  285.46
    4971  288.15  4979.7   287.1  4985.8  280.94  4997.7  280.84  5000.4  280.34
  5003.7  280.84  5006.7  280.84  5015.5  288.17    5113   285.3  5298.5  286.13
  5621.9  294.77  5769.5  302.56  5836.9  310.87  5966.7  322.23  6106.1  332.81
  6112.8   335.8  6128.6  334.71  6179.7     338  6201.8  341.83  6208.8  342.22
#Mann= 9 ,-1 , 0
  3122.8     .05       0  3246.3     .12       0  3465.2     .05       0
  4855.4     .12       0  4997.7     .07       0  5003.7     .12       0
    5113     .05       0  5966.7     .16       0  6201.8     .05       0
Bank Sta=4971,5015.5
XS Rating Curve= 0 ,0
Exp/Cntr=0.3,0.1

Type RM Length L Ch R = 1 ,38972   ,91,91,91
BEGIN DESCRIPTION:
Mapping XS d016df7b
END DESCRIPTION:
XS GIS Cut Line= 6
       3705066.9     10684125.04      3704914.09      10684027.8
      3703816.87     10684076.41      3703504.37     10683829.88
      3703226.59     10684024.33       3702248.4     10684995.85
#Sta/Elev= 30
  2702.3  327.14  2849.1  315.72  2870.3   309.9  2928.6   311.6  2968.2  308.12
  2979.1     313  3008.3   302.5  3096.3  293.56    3327  292.25  4408.9  287.82
  4442.5  287.68  4884.7  284.92  4946.5  285.47  4990.3  287.56    5009  281.24
  5011.7  280.74    5015  281.24    5033  286.88    5125  284.55    5458  291.19
  5684.8  302.08    5699  299.28  5705.7  303.41  5771.5  299.44  5798.4  304.67
  5827.9  302.03  5854.9  307.48  5878.3  305.25  6054.5  315.85    6126  319.97
#Mann= 10 ,-1 , 0
  2702.3     .05       0  2928.6     .08       0    3327     .05       0
  4408.9     .08       0  4442.5     .05       0  4884.7     .12       0
  4946.5     .05       0    5009     .04       0    5015     .05       0
  6054.5     .16       0
Bank Sta=4990.3,5033
XS Rating Curve= 0 ,0
Exp/Cntr=0.3,0.1

Type RM Length L Ch R = 1 ,38881   ,274,274,274
BEGIN DESCRIPTION:
Mapping XS 30ec4409
END DESCRIPTION:
XS GIS Cut Line= 6
      3705087.71     10684076.41      3704882.84     10683927.11
      3703882.84     10684020.86      3703549.51     10683694.47
      3703441.87     10683718.77      3702171.01     10684843.78
#Sta/Elev= 30
  2537.9  322.09  2691.5  305.97  2712.4  300.32  2844.9  294.04  4651.9   285.2
  4977.4  288.08  5009.6   280.6  5012.4   280.1  5015.6   280.6  5048.2  287.76
  5056.9  287.72  5176.6  287.24  5203.8  287.52  5224.9  292.69  5246.2  289.86
  5512.6  293.72    5621  299.27  5656.2  306.02  5684.5  307.46  5691.7  300.89
  5698.7  306.11    5720  301.93    5727  307.18  5734.1  302.96  5753.9  306.13
  5762.9  304.36  5864.7  310.76  5902.6  315.99  5918.8  313.62  6088.6  322.94
#Mann= 9 ,-1 , 0
  2537.9     .05       0  5009.6     .04       0  5015.6     .05       0
  5056.9     .12       0  5176.6     .05       0  5512.6     .16       0
  5753.9     .05       0  5762.9     .16       0  5864.7     .05       0
Bank Sta=4977.4,5048.2
XS Rating Curve= 0 ,0
Exp/Cntr=0.3,0.1

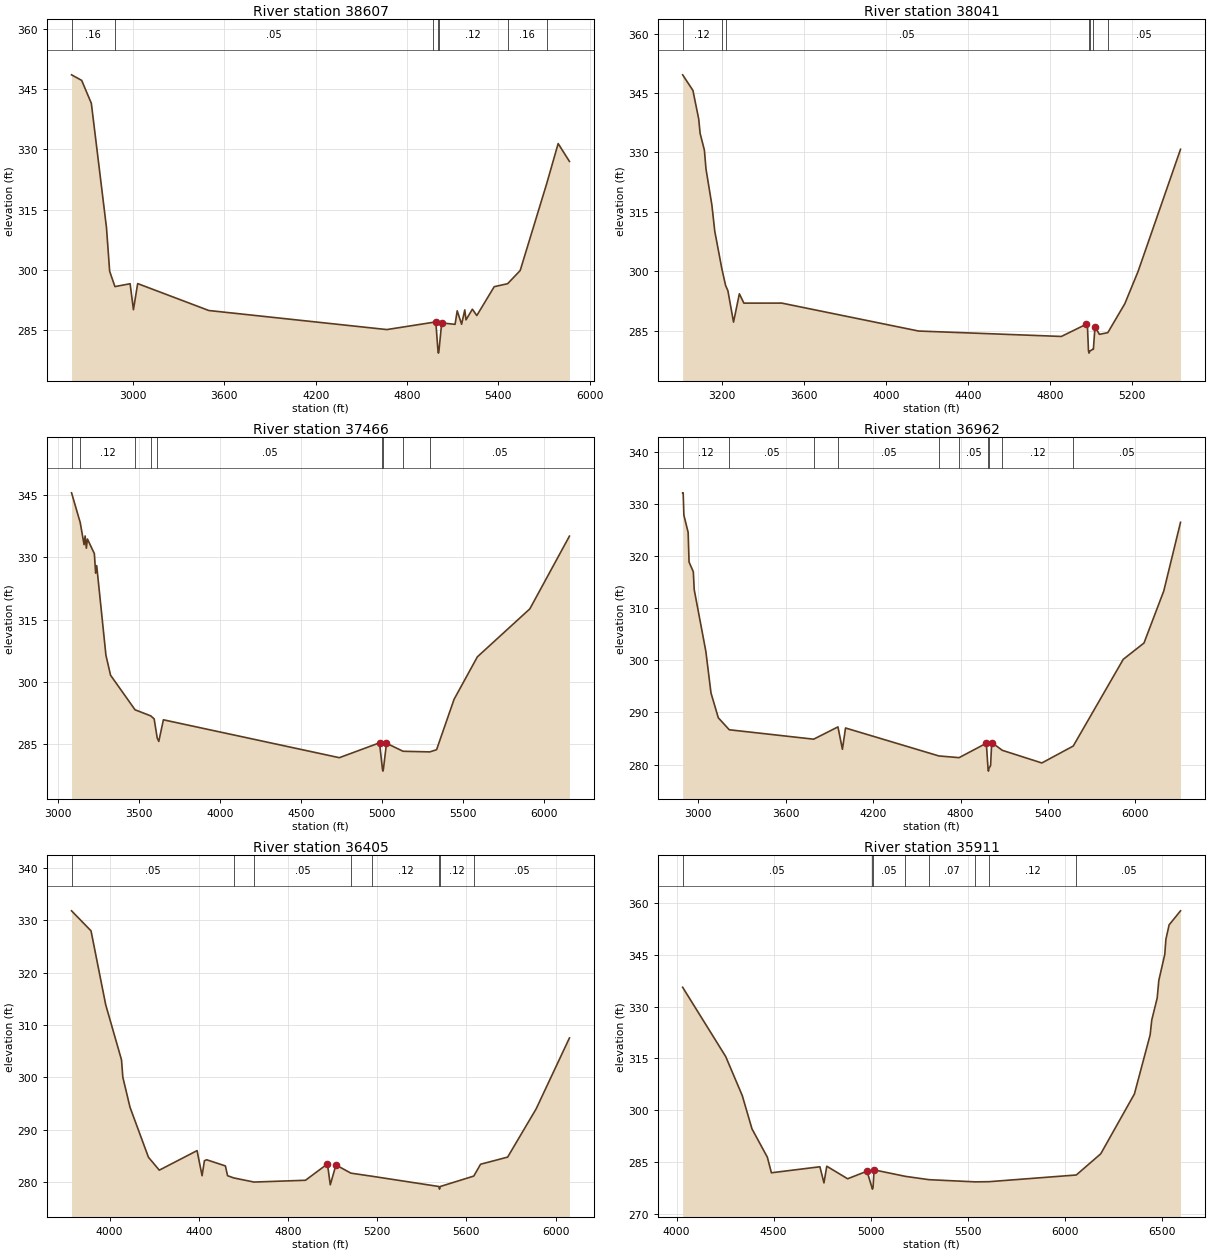
Type RM Length L Ch R = 1 ,38607   ,566,566,566
BEGIN DESCRIPTION:
BEAVER CREEK 53.0
END DESCRIPTION:
XS GIS Cut Line= 4
      3704649.75     10682446.82      3703130.66      10683835.7
      3702696.64     10683987.61      3702099.88     10684443.31
#Sta/Elev= 30
  2597.3  348.56  2663.7  347.18  2727.2  341.47  2826.5  310.59  2847.5  299.69
  2882.1  295.88  2981.9  296.59  3003.5  290.13  3031.3  296.63  3498.7  289.93
  4667.3  285.19  4967.3  286.97  4988.7  287.18  5003.3  279.83  5006.1  279.33
  5009.3  279.83  5027.5  286.84  5115.4  286.49  5129.3  289.85  5158.3  286.52
  5179.1  290.08  5187.2  287.61    5229  290.26  5258.1  288.68  5372.4  295.86
  5460.4   296.6  5542.8  299.87  5717.4  321.55  5792.2  331.46  5866.3  327.02
#Mann= 7 ,-1 , 0
  2597.3     .16       0  2882.1     .05       0  4967.3     .12       0
  5003.3     .07       0  5009.3     .12       0  5460.4     .16       0
  5717.4     .05       0
Bank Sta=4988.7,5027.5
XS Rating Curve= 0 ,0
Exp/Cntr=0.3,0.1

Type RM Length L Ch R = 1 ,38041   ,575,575,575
BEGIN DESCRIPTION:
BEAVER CREEK 52.0
END DESCRIPTION:
XS GIS Cut Line= 3
      3704099.59      10682160.2      3702549.61     10683460.19
       3702199.6      10683660.2
#Sta/Elev= 30
  3008.7   349.6  3058.8  345.67    3087  338.47  3093.9  334.82  3114.7  330.59
  3122.5  325.84  3151.1  316.78  3165.3  310.12  3199.7  300.67    3218  296.44
  3229.2  295.12  3256.7  287.18  3285.1  294.33  3307.2  291.97  3491.6  291.98
  4158.1  284.93  4854.1  283.56  4975.1  286.63  4981.6   285.7  4986.4  279.85
  4989.1  279.35  4992.4  279.85  5006.8   280.3  5010.2  280.33    5018  285.98
  5039.6  284.09  5080.3  284.51  5163.4  291.82  5228.2     300  5434.8   330.8
#Mann= 7 ,-1 , 0
  3008.7     .12       0  3199.7     .16       0    3218     .05       0
  4986.4     .03       0  4992.4     .05       0  5006.8     .12       0
  5080.3     .05       0
Bank Sta=4975.1,5018
XS Rating Curve= 0 ,0
Exp/Cntr=0.3,0.1

Type RM Length L Ch R = 1 ,37466   ,504,504,504
BEGIN DESCRIPTION:
BEAVER CREEK 51.0
END DESCRIPTION:
XS GIS Cut Line= 3
      3703911.89     10681643.88      3702392.82     10682956.79
      3701796.19     10683835.46
#Sta/Elev= 30
    3086  345.45  3139.5   338.3  3163.1     333  3169.7  335.09  3177.3  332.16
  3183.9  334.35  3226.7  330.84  3234.4  326.16    3241  327.97    3298  306.42
  3326.5  301.64  3477.6  293.33    3575  291.86  3595.3  291.14  3614.2  286.56
  3623.8  285.73  3652.3  290.93  4737.1  281.83    4985   285.4  5002.9   279.1
  5005.6   278.6  5008.9   279.1  5027.8  285.29  5130.1  283.37  5294.8  283.22
  5336.7  283.75  5444.5  295.85  5588.3  306.06  5911.7  317.58  6155.9  335.05
#Mann= 9 ,-1 , 0
    3086     .16       0  3139.5     .12       0  3477.6     .05       0
    3575     .12       0  3614.2     .05       0  5002.9     .03       0
  5008.9     .05       0  5130.1     .12       0  5294.8     .05       0
Bank Sta=4985,5027.8
XS Rating Curve= 0 ,0
Exp/Cntr=0.3,0.1

Type RM Length L Ch R = 1 ,36962   ,557,557,557
BEGIN DESCRIPTION:
BEAVER CREEK 50.0
END DESCRIPTION:
XS GIS Cut Line= 2
      3703278.95     10680967.51      3701266.04     10683726.59
#Sta/Elev= 30
  2893.6  332.22  2897.3  332.22    2902  327.96  2931.4   324.6  2937.6  318.92
  2966.9  317.05  2973.1   313.6  3052.7  301.77  3088.2  293.74  3138.4  288.98
  3213.5  286.68  3792.4  284.87    3959  287.23  3989.6  282.93    4011  287.02
  4651.2  281.65    4790  281.32  4976.8  284.09  4988.5  279.23  4991.2  278.73
  4994.5  279.23  5006.2  279.81  5013.6  284.23  5086.5  282.73  5357.6   280.3
  5572.9  283.55  5916.1  300.22  6058.2  303.35  6194.2  313.37  6308.9  326.55
#Mann= 10 ,-1 , 0
  2893.6     .12       0  3213.5     .05       0  3792.4     .16       0
    3959     .05       0  4651.2     .12       0    4790     .05       0
  4988.5     .03       0  4994.5     .05       0  5086.5     .12       0
  5572.9     .05       0
Bank Sta=4976.8,5013.6
XS Rating Curve= 0 ,0
Exp/Cntr=0.3,0.1

Type RM Length L Ch R = 1 ,36405   ,494,494,494
BEGIN DESCRIPTION:
BEAVER CREEK 49.0
END DESCRIPTION:
XS GIS Cut Line= 3
       3701949.6     10681210.21      3701599.61     10682360.19
      3700949.63     10683160.16
#Sta/Elev= 30
  3829.6  331.77  3916.9  327.95  3982.6  313.87  4053.6  303.33  4059.5  300.03
  4091.7  294.29  4174.5  284.74  4223.1  282.28  4392.5  286.01  4414.9  281.22
  4425.4  284.09  4435.8  284.26  4519.5  283.09  4529.2  281.22  4557.9  280.79
  4647.8  280.01  4878.6  280.35  4977.2  283.47  4989.9  279.48  5015.2  283.27
  5082.4  281.71  5176.8  281.12  5476.9  279.16  5479.7  278.66  5482.9  279.16
  5633.4  281.15  5663.8  283.41  5785.2  284.77    5913  293.97  6062.4  307.51
#Mann= 8 ,-1 , 0
  3829.6     .05       0  4557.9     .07       0  4647.8     .05       0
  5082.4     .07       0  5176.8     .12       0  5476.9     .03       0
  5482.9     .12       0  5633.4     .05       0
Bank Sta=4977.2,5015.2
XS Rating Curve= 0 ,0
Exp/Cntr=0.3,0.1

Type RM Length L Ch R = 1 ,35911   ,501,501,501
BEGIN DESCRIPTION:
BEAVER CREEK 48.0
END DESCRIPTION:
XS GIS Cut Line= 3
      3701899.62     10681160.18      3701299.61     10681960.19
      3700599.59     10683360.22
#Sta/Elev= 30
  4031.1  335.59    4253  315.55  4338.4  304.24  4388.4  294.62  4467.6  286.42
  4488.4  281.91  4738.4  283.65  4759.2  278.98  4773.8  283.81  4881.1  280.18
  4981.1  282.37  5006.2  277.68    5009  277.18  5012.2  277.68  5017.6  282.75
  5178.5  280.88  5299.7  279.92  5539.5  279.28  5608.6  279.33  6059.3  281.27
  6185.5  287.41  6358.8  304.72  6439.8  321.79  6448.2  326.11  6476.2  332.48
  6484.6  337.58  6515.3  345.11  6520.9  349.44  6537.7  353.65  6596.4  357.71
#Mann= 8 ,-1 , 0
  4031.1     .05       0  5006.2     .03       0  5012.2     .05       0
  5178.5     .12       0  5299.7     .07       0  5539.5     .05       0
  5608.6     .12       0  6059.3     .05       0
Bank Sta=4981.1,5017.6
XS Rating Curve= 0 ,0
Exp/Cntr=0.3,0.1

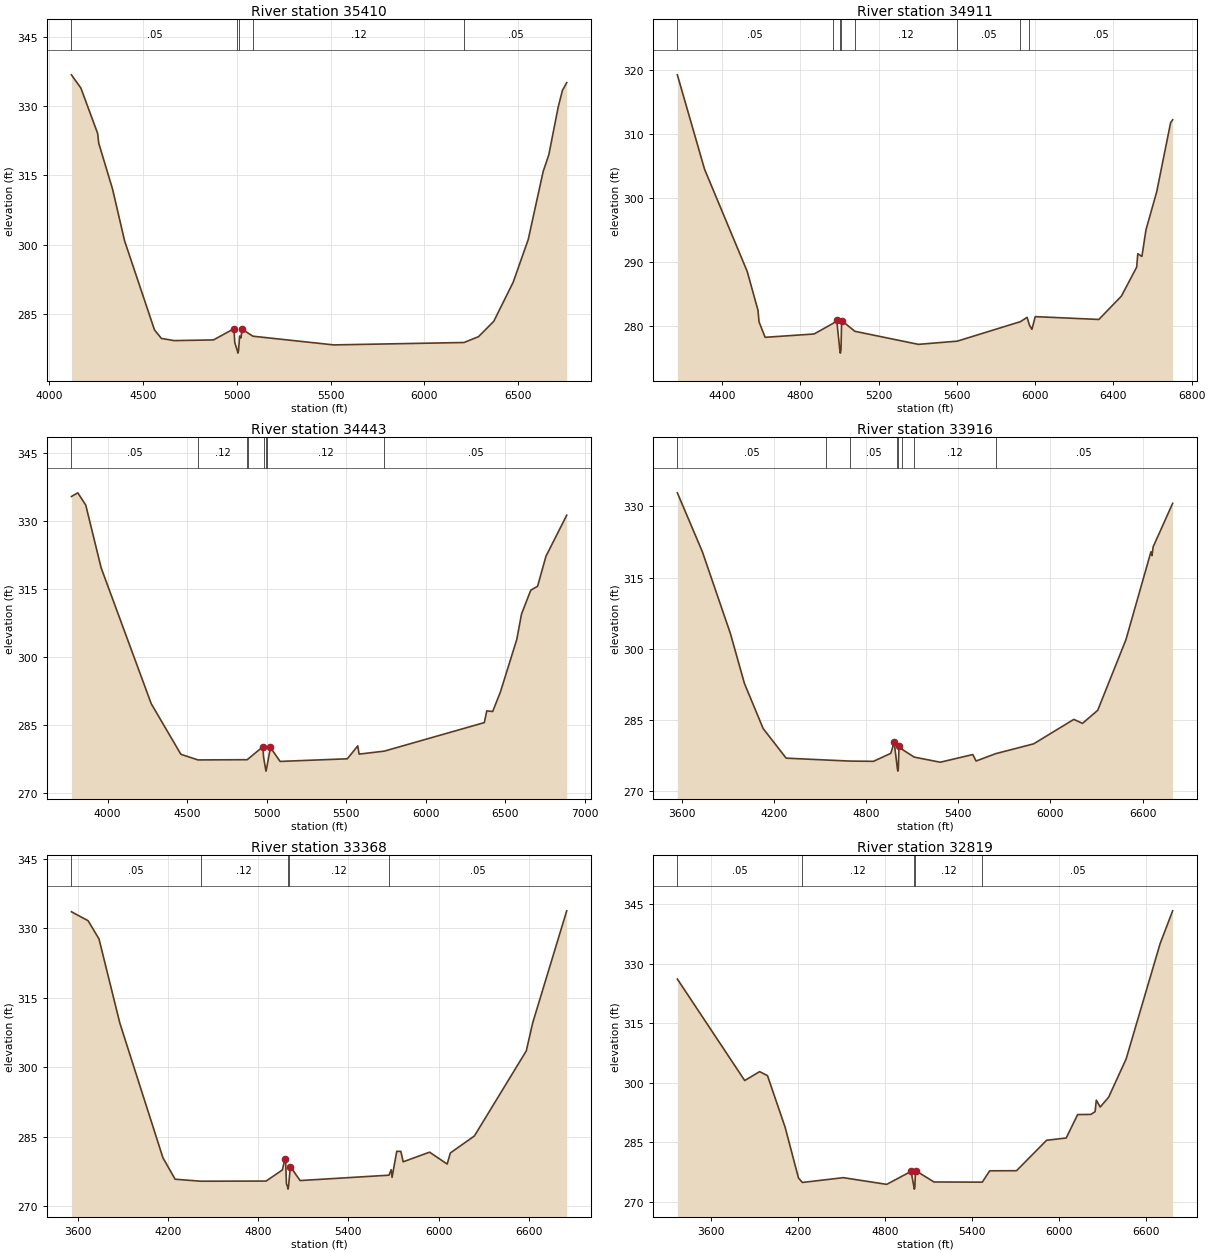
Type RM Length L Ch R = 1 ,35410   ,499,499,499
BEGIN DESCRIPTION:
BEAVER CREEK 47.0
END DESCRIPTION:
XS GIS Cut Line= 3
      3701799.58     10681060.21      3701049.61     10681510.19
       3700199.6     10683060.21
#Sta/Elev= 30
  4117.5  336.78    4168  333.92  4257.4  324.09  4263.2  321.98  4337.1  312.02
  4401.2  300.84  4560.6  281.57  4597.5  279.72  4665.6  279.25  4875.5   279.4
  4984.3  281.82  4989.2  278.78  5002.9  277.04  5005.6  276.54  5008.9  277.04
  5014.9  280.24    5022  279.84  5027.7  281.72  5085.9   280.2  5516.7  278.32
  6212.1  278.84  6289.2   280.1  6370.8  283.43  6474.1  291.87  6554.6  301.13
  6634.4  315.87  6664.6   319.5  6714.3  329.78  6737.1  333.41  6759.9  335.08
#Mann= 5 ,-1 , 0
  4117.5     .05       0  5002.9     .03       0  5008.9     .05       0
  5085.9     .12       0  6212.1     .05       0
Bank Sta=4984.3,5027.7
XS Rating Curve= 0 ,0
Exp/Cntr=0.3,0.1

Type RM Length L Ch R = 1 ,34911   ,468,468,468
BEGIN DESCRIPTION:
BEAVER CREEK 46.0
END DESCRIPTION:
XS GIS Cut Line= 3
      3701549.63     10680810.18      3700749.61     10681110.19
      3699149.64     10681610.18
#Sta/Elev= 30
  4172.2  319.29  4311.1  304.55  4529.1  288.58  4584.3   282.5  4589.6  280.69
  4620.8  278.29  4870.9  278.81  4966.9  280.45  4986.6  280.92  5002.3  276.32
    5005  275.82  5008.3  276.32  5011.5  280.91  5079.2  279.23  5403.8  277.19
  5602.4  277.69  5925.4  280.74  5959.1  281.41  5971.4  280.19  5983.7  279.53
    6001  281.52  6325.8  281.08    6441  284.72  6519.1  289.25  6524.8  291.35
  6545.8  290.92  6566.7  295.09  6621.7  301.05  6692.5  311.82  6702.9  312.27
#Mann= 8 ,-1 , 0
  4172.2     .05       0  4966.9     .07       0  5002.3     .07       0
  5008.3     .07       0  5079.2     .12       0  5602.4     .05       0
  5925.4     .12       0  5971.4     .05       0
Bank Sta=4986.6,5011.5
XS Rating Curve= 0 ,0
Exp/Cntr=0.3,0.1

Type RM Length L Ch R = 1 ,34443   ,527,527,527
BEGIN DESCRIPTION:
BEAVER CREEK 45.0
END DESCRIPTION:
XS GIS Cut Line= 3
      3701749.57     10680610.19      3700499.61     10680710.19
      3698899.64     10681660.17
#Sta/Elev= 30
  3772.5  335.43  3812.6  336.24  3862.7  333.53  3959.3  319.71  4274.1  289.76
  4460.9  278.58  4568.5  277.34  4878.9  277.39  4881.8   277.5  4976.3  280.25
  4981.3  277.88  4993.4  275.37  4996.1  274.87  4999.4  275.37  5023.9   280.1
  5084.6  277.01  5507.7  277.59  5573.1  280.44  5581.8  278.62  5740.2  279.28
  6368.9  285.57  6384.5  288.15  6421.6  288.02  6470.2  292.32  6573.2  303.91
  6602.8  309.49  6661.2  314.77  6704.1  315.64  6756.7  322.25  6887.2  331.31
#Mann= 8 ,-1 , 0
  3772.5     .05       0  4568.5     .12       0  4878.9     .05       0
  4881.8     .07       0  4981.3     .12       0  4993.4     .07       0
  4999.4     .12       0  5740.2     .05       0
Bank Sta=4976.3,5023.9
XS Rating Curve= 0 ,0
Exp/Cntr=0.3,0.1

Type RM Length L Ch R = 1 ,33916   ,548,548,548
BEGIN DESCRIPTION:
BEAVER CREEK 44.0
END DESCRIPTION:
XS GIS Cut Line= 3
      3701649.58     10680010.19      3700249.61     10680260.19
       3698949.6      10681510.2
#Sta/Elev= 30
  3570.5  332.88    3733  320.48  3915.8  303.21  4007.3  292.66  4129.2  283.14
    4279  276.89  4535.7   276.5  4694.8  276.27  4847.9  276.22  4960.6  277.91
  4982.5  280.26  5003.6  274.65  5006.4  274.15  5009.6  274.65  5013.8  279.37
  5032.7  278.78    5113  277.11  5282.7  276.03  5494.7  277.65    5516  276.28
  5643.1  277.83  5890.9  279.91  6152.5  285.07  6209.1  284.23  6308.2  286.99
  6491.9  301.89  6654.7  320.43  6661.7  319.64  6668.9  321.46  6796.1  330.66
#Mann= 8 ,-1 , 0
  3570.5     .05       0  4535.7     .12       0  4694.8     .05       0
  5003.6     .03       0  5009.6     .05       0  5032.7     .07       0
    5113     .12       0  5643.1     .05       0
Bank Sta=4982.5,5013.8
XS Rating Curve= 0 ,0
Exp/Cntr=0.3,0.1

Type RM Length L Ch R = 1 ,33368   ,549,549,549
BEGIN DESCRIPTION:
BEAVER CREEK 43.0
END DESCRIPTION:
XS GIS Cut Line= 3
      3701199.64     10679110.17      3699949.61     10679810.19
      3698349.58     10680760.21
#Sta/Elev= 30
  3558.7  333.52  3669.5  331.59  3742.1  327.65  3880.7  309.48  4167.2  280.42
  4248.2  275.79  4417.9  275.36  4853.2  275.39  4961.7   277.8  4977.7  280.16
  4983.4  279.56  4988.5  274.81  4996.2  274.15  4998.9  273.65  5002.2  274.15
  5014.6  278.53  5079.1   275.5  5670.4  276.66    5685  277.85  5690.9  276.19
  5722.1  281.82  5749.3   281.8  5764.9  279.55  5940.3  281.63  6057.2  279.06
  6078.6  281.46  6238.4  285.13  6583.3  303.48  6626.1  309.55  6852.2  333.72
#Mann= 5 ,-1 , 0
  3558.7     .05       0  4417.9     .12       0  4996.2     .07       0
  5002.2     .12       0  5670.4     .05       0
Bank Sta=4977.7,5014.6
XS Rating Curve= 0 ,0
Exp/Cntr=0.3,0.1

Type RM Length L Ch R = 1 ,32819   ,555,555,555
BEGIN DESCRIPTION:
BEAVER CREEK 42.0
END DESCRIPTION:
XS GIS Cut Line= 3
      3701099.64     10679060.18      3699549.61     10679460.19
      3698099.64     10680560.16
#Sta/Elev= 30
  3364.9  326.13    3830  300.55    3933  302.79  3987.5  301.78  4109.5  288.73
  4201.5  275.98  4228.5  274.85  4511.3  276.06  4810.8  274.37  4979.3  277.65
  4999.1  273.67  5001.8  273.17  5005.1  273.67  5008.4  276.76  5015.9  277.72
  5137.3  274.97  5470.8  274.93  5522.1  277.79  5707.3  277.81  5915.2  285.49
  6050.5  286.06  6129.5  291.96  6221.1  292.01  6250.1  292.71  6258.4   295.6
  6285.5  293.87  6343.7  296.35  6464.4  305.99  6699.4  335.09  6785.7  343.33
#Mann= 5 ,-1 , 0
  3364.9     .05       0  4228.5     .12       0  4999.1     .07       0
  5005.1     .12       0  5470.8     .05       0
Bank Sta=4979.3,5015.9
XS Rating Curve= 0 ,0
Exp/Cntr=0.3,0.1