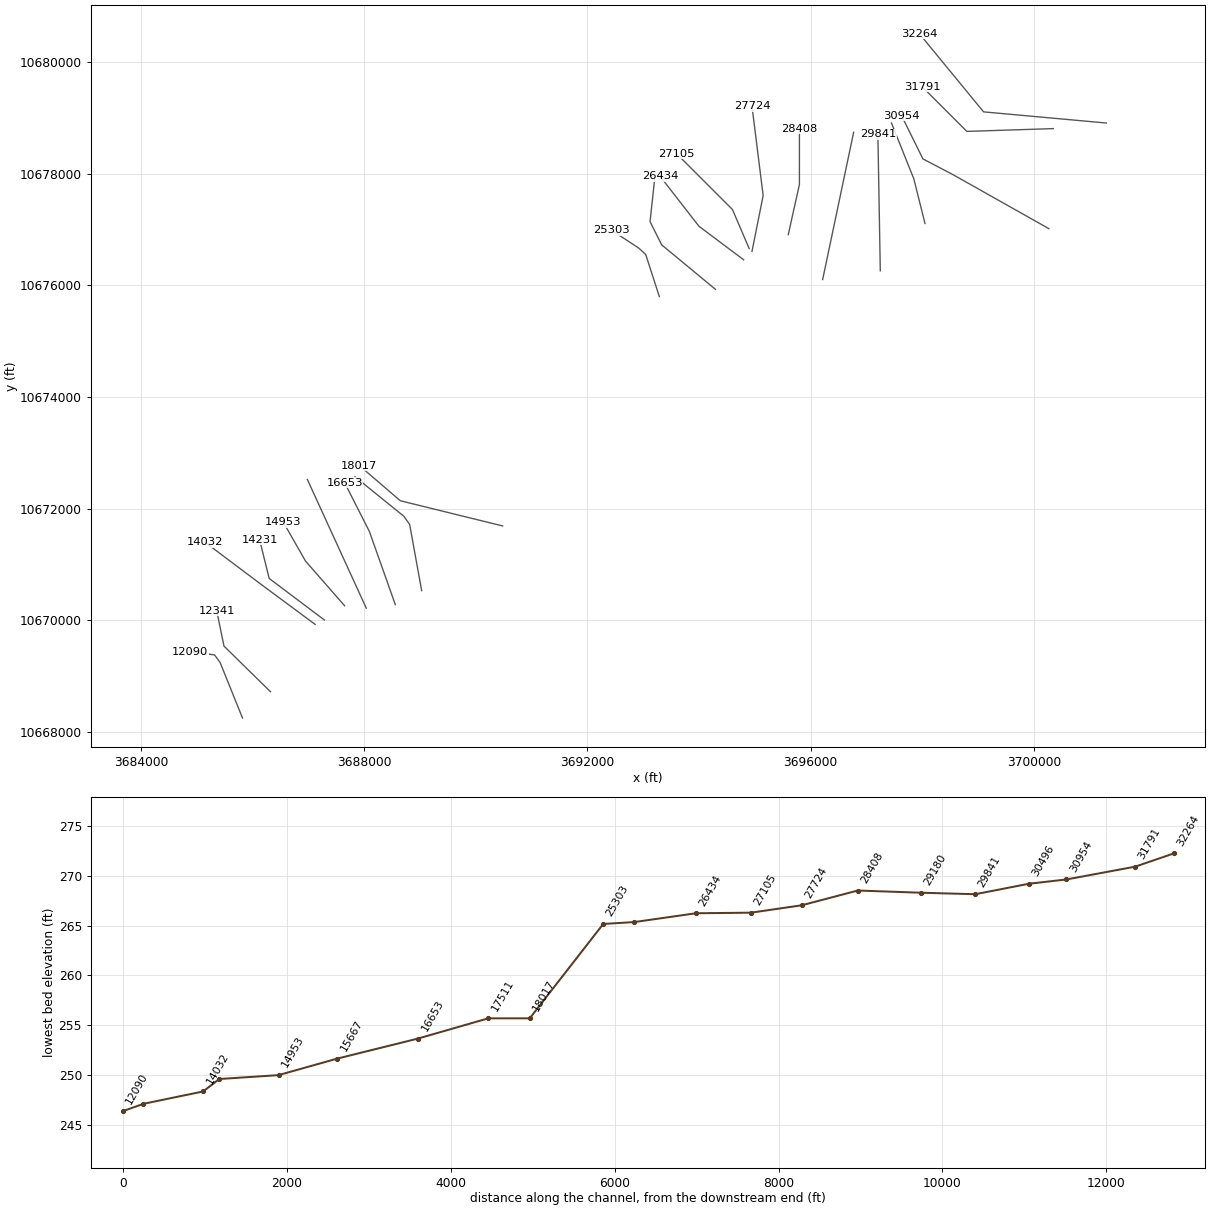
HEC-RAS study BEAVER CREEK.prj: BEAVER CREEK Base Level Engineering

--- BEAVER CREEK.g02 (geometry) --- (continued)

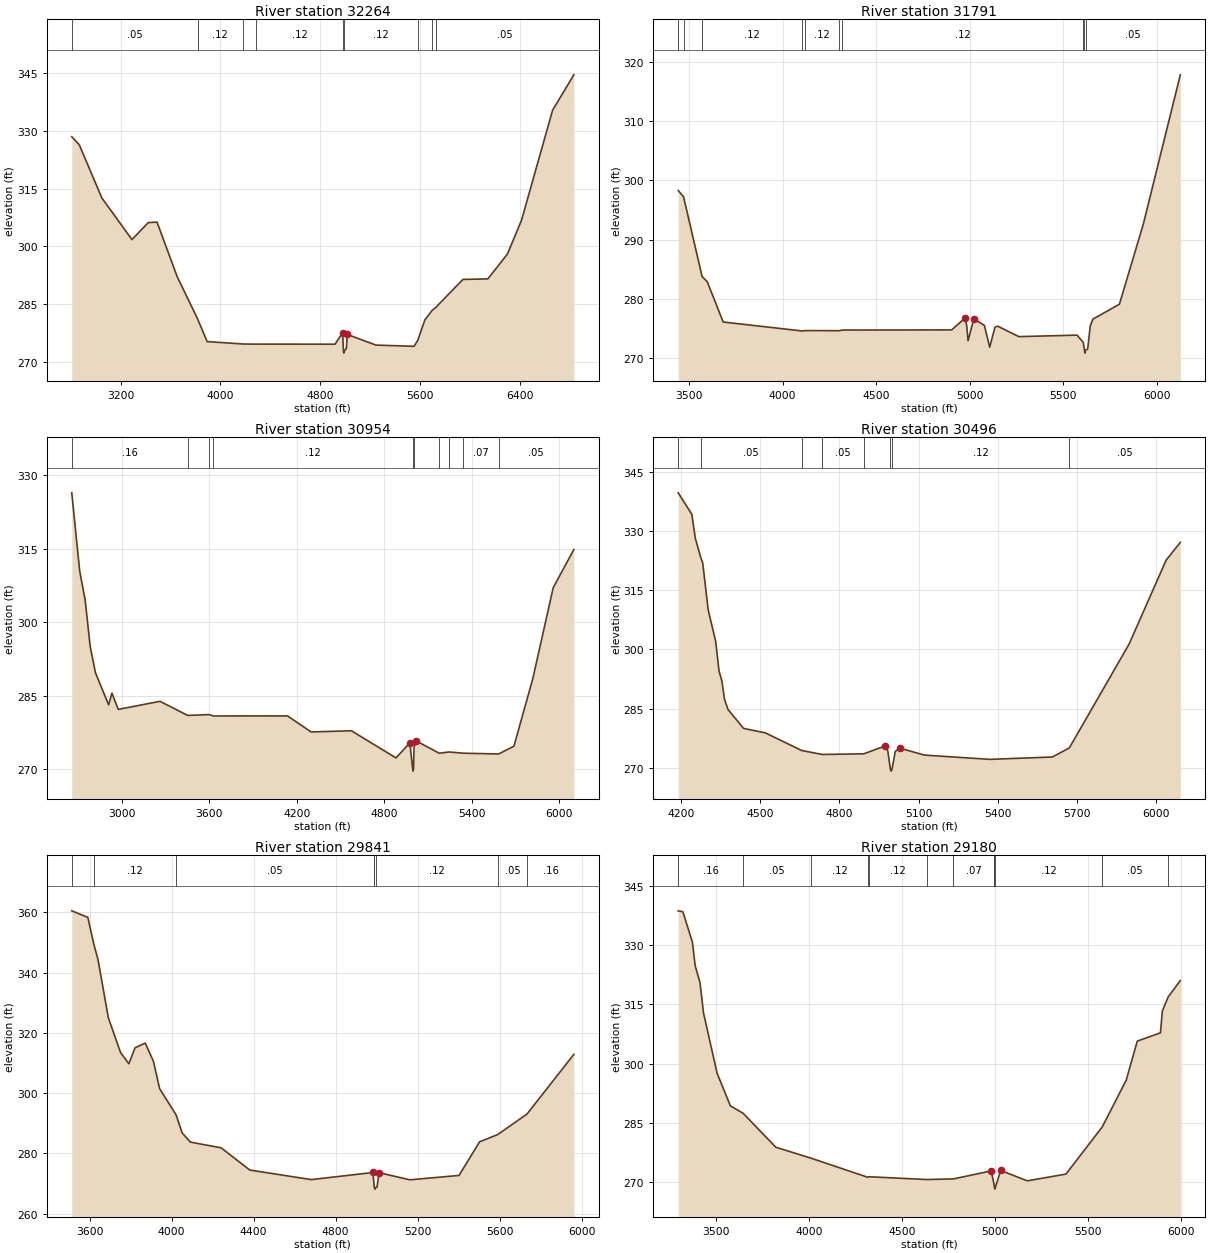
Type RM Length L Ch R = 1 ,32264   ,473,473,473
BEGIN DESCRIPTION:
BEAVER CREEK 41.0
END DESCRIPTION:
XS GIS Cut Line= 3
      3701299.59     10678910.19      3699099.61     10679110.19
      3697949.62     10680510.17
#Sta/Elev= 30
  2809.2  328.47  2869.4  326.37  3050.2  312.54  3291.2  301.73  3421.7  306.14
    3492  306.27  3652.6  292.16  3816.3  281.16  3893.6  275.23  4181.2   274.6
  4284.7  274.57  4917.8  274.55  4978.1  277.57  4985.1  272.73  4987.9  272.23
  4991.1  272.73  5008.2  273.46  5015.7  277.08  5245.7  274.32  5550.7     274
  5580.2  275.57  5636.8  280.85  5695.4  283.34  5724.4  284.11  5941.7  291.38
  6141.2  291.52  6297.6  297.94    6411  306.76    6660  335.36    6830  344.54
#Mann= 9 ,-1 , 0
  2809.2     .05       0  3816.3     .12       0  4181.2     .07       0
  4284.7     .12       0  4985.1     .07       0  4991.1     .12       0
  5580.2     .05       0  5695.4     .07       0  5724.4     .05       0
Bank Sta=4978.1,5015.7
XS Rating Curve= 0 ,0
Exp/Cntr=0.3,0.1

Type RM Length L Ch R = 1 ,31791   ,837,837,837
BEGIN DESCRIPTION:
BEAVER CREEK 40.0
END DESCRIPTION:
XS GIS Cut Line= 3
      3700349.59     10678810.19      3698799.61     10678760.19
      3697999.58     10679560.22
#Sta/Elev= 30
  3442.2  298.29  3470.7  297.23  3569.6  283.81  3597.3  282.92  3682.3  276.14
  4105.7  274.63  4121.3   274.7  4302.9  274.68  4319.5  274.79  4902.9  274.81
    4973  276.77    4983  275.63  4990.5  272.99  5021.3  276.68  5077.8  275.57
  5106.1   271.9  5134.4  275.28  5148.5  275.45  5261.7  273.68  5572.8  273.93
  5606.1  272.69  5612.2   271.4    5615   270.9  5618.2   271.4  5629.4  271.58
  5643.5   275.5  5657.7  276.63  5799.1  279.14  5926.4  292.59  6124.4  317.78
#Mann= 10 ,-1 , 0
  3442.2     .05       0  3470.7     .16       0  3569.6     .12       0
  4105.7     .07       0  4121.3     .12       0  4302.9     .07       0
  4319.5     .12       0  5606.1     .05       0  5612.2     .07       0
  5618.2     .05       0
Bank Sta=4973,5021.3
XS Rating Curve= 0 ,0
Exp/Cntr=0.3,0.1

Type RM Length L Ch R = 1 ,30954   ,458,458,458
BEGIN DESCRIPTION:
BEAVER CREEK 39.0
END DESCRIPTION:
XS GIS Cut Line= 4
      3700269.69     10677017.19      3698559.66     10677980.71
      3698012.78     10678267.17      3697630.83     10679039.75
#Sta/Elev= 30
  2656.8  326.43  2711.2  310.44  2748.7  304.55  2783.2  295.03  2819.5  289.68
  2909.4  283.15  2932.3  285.54  2975.6  282.22  3261.7  283.87  3451.5  280.99
  3599.1  281.16  3628.3  280.88  4135.8  280.89  4297.7  277.62  4573.7  277.86
  4879.3  272.32  4974.7  275.39  4993.7  270.12  4996.5  269.62  4999.7  270.12
  5003.5  274.49  5018.8  275.77  5175.5  273.28  5243.6  273.53  5341.6  273.28
  5582.9  273.12  5688.1  274.71  5817.2  288.46  5957.4  307.07  6098.8  314.85
#Mann= 10 ,-1 , 0
  2656.8     .16       0  3451.5     .12       0  3599.1     .16       0
  3628.3     .12       0  4993.7     .07       0  4999.7     .12       0
  5175.5     .07       0  5243.6     .12       0  5341.6     .07       0
  5582.9     .05       0
Bank Sta=4974.7,5018.8
XS Rating Curve= 0 ,0
Exp/Cntr=0.3,0.1

Type RM Length L Ch R = 1 ,30496   ,655,655,655
BEGIN DESCRIPTION:
BEAVER CREEK 38.0
END DESCRIPTION:
XS GIS Cut Line= 3
      3698049.62     10677110.15      3697849.61     10677910.19
      3697449.61     10678910.19
#Sta/Elev= 30
  4189.3  339.67  4240.9  334.22  4253.8  328.23    4274   323.4  4282.1  321.91
  4302.7  310.05  4331.1  302.06    4344  294.47  4354.3  292.14  4364.6   287.4
  4377.5  284.84  4436.7  280.01  4519.2  278.88  4656.7  274.42  4734.6  273.41
    4892  273.57  4972.7  275.55    4983   274.3  4992.9  269.69  4995.7  269.19
  4998.9  269.69  5011.4  274.17  5028.8     275  5121.7  273.25  5369.4  272.17
  5606.3  272.77  5670.7  275.07  5897.1  301.37  6037.1   322.6    6091  327.13
#Mann= 8 ,-1 , 0
  4189.3     .12       0    4274     .05       0  4656.7     .07       0
  4734.6     .05       0    4892     .12       0  4992.9     .07       0
  4998.9     .12       0  5670.7     .05       0
Bank Sta=4972.7,5028.8
XS Rating Curve= 0 ,0
Exp/Cntr=0.3,0.1

Type RM Length L Ch R = 1 ,29841   ,661,661,661
BEGIN DESCRIPTION:
BEAVER CREEK 37.0
END DESCRIPTION:
XS GIS Cut Line= 2
      3697248.89     10676261.98      3697205.49     10678709.89
#Sta/Elev= 30
  3513.2   360.5  3591.4  358.34  3619.7  349.74  3641.4  344.26  3691.4  325.05
  3750.7  313.52  3791.5  309.75  3821.5  315.02  3871.5  316.61  3911.5  310.57
  3941.5   301.5  4021.8   292.8  4051.5  286.81  4091.5  283.75  4241.5  281.85
  4381.5  274.47  4681.6   271.3  4981.6  273.66  4988.5  268.71  4988.6  268.64
  4991.4  268.14  4994.6  268.64  5001.6  268.81  5011.6   273.6  5161.7  271.23
  5401.7  272.68  5501.7  283.83  5590.1  286.25  5733.4  293.07  5961.5  312.87
#Mann= 8 ,-1 , 0
  3513.2     .16       0  3619.7     .12       0  4021.8     .05       0
  4988.5     .12       0  4988.6     .07       0  4994.6     .12       0
  5590.1     .05       0  5733.4     .16       0
Bank Sta=4981.6,5011.6
XS Rating Curve= 0 ,0
Exp/Cntr=0.3,0.1

Type RM Length L Ch R = 1 ,29180   ,772,772,772
BEGIN DESCRIPTION:
BEAVER CREEK 36.0
END DESCRIPTION:
XS GIS Cut Line= 2
       3696215.9     10676105.68      3696771.47     10678744.64
#Sta/Elev= 30
  3299.2  338.64  3324.2  338.41  3375.3  330.71  3390.3  324.76  3416.2  320.46
    3435  312.81  3508.2  297.55  3579.4  289.34  3647.8  287.46  3823.4  278.88
  4013.9  276.09  4317.9  271.28  4323.6  271.42  4633.1  270.72  4777.2  270.87
  4979.8  272.89  4995.5  269.58  4997.2  268.79  4999.9  268.29  5003.2  268.79
  5030.9  273.01  5173.9  270.39  5381.8  272.09  5576.7  284.01  5705.3  295.82
    5765  305.71  5889.3   307.8  5899.5  313.34  5930.6  316.85    5996  321.01
#Mann= 12 ,-1 , 0
  3299.2     .16       0  3647.8     .05       0  4013.9     .12       0
  4317.9     .05       0  4323.6     .12       0  4633.1     .05       0
  4777.2     .07       0  4995.5     .12       0  4997.2     .07       0
  5003.2     .12       0  5576.7     .05       0  5930.6     .16       0
Bank Sta=4979.8,5030.9
XS Rating Curve= 0 ,0
Exp/Cntr=0.3,0.1

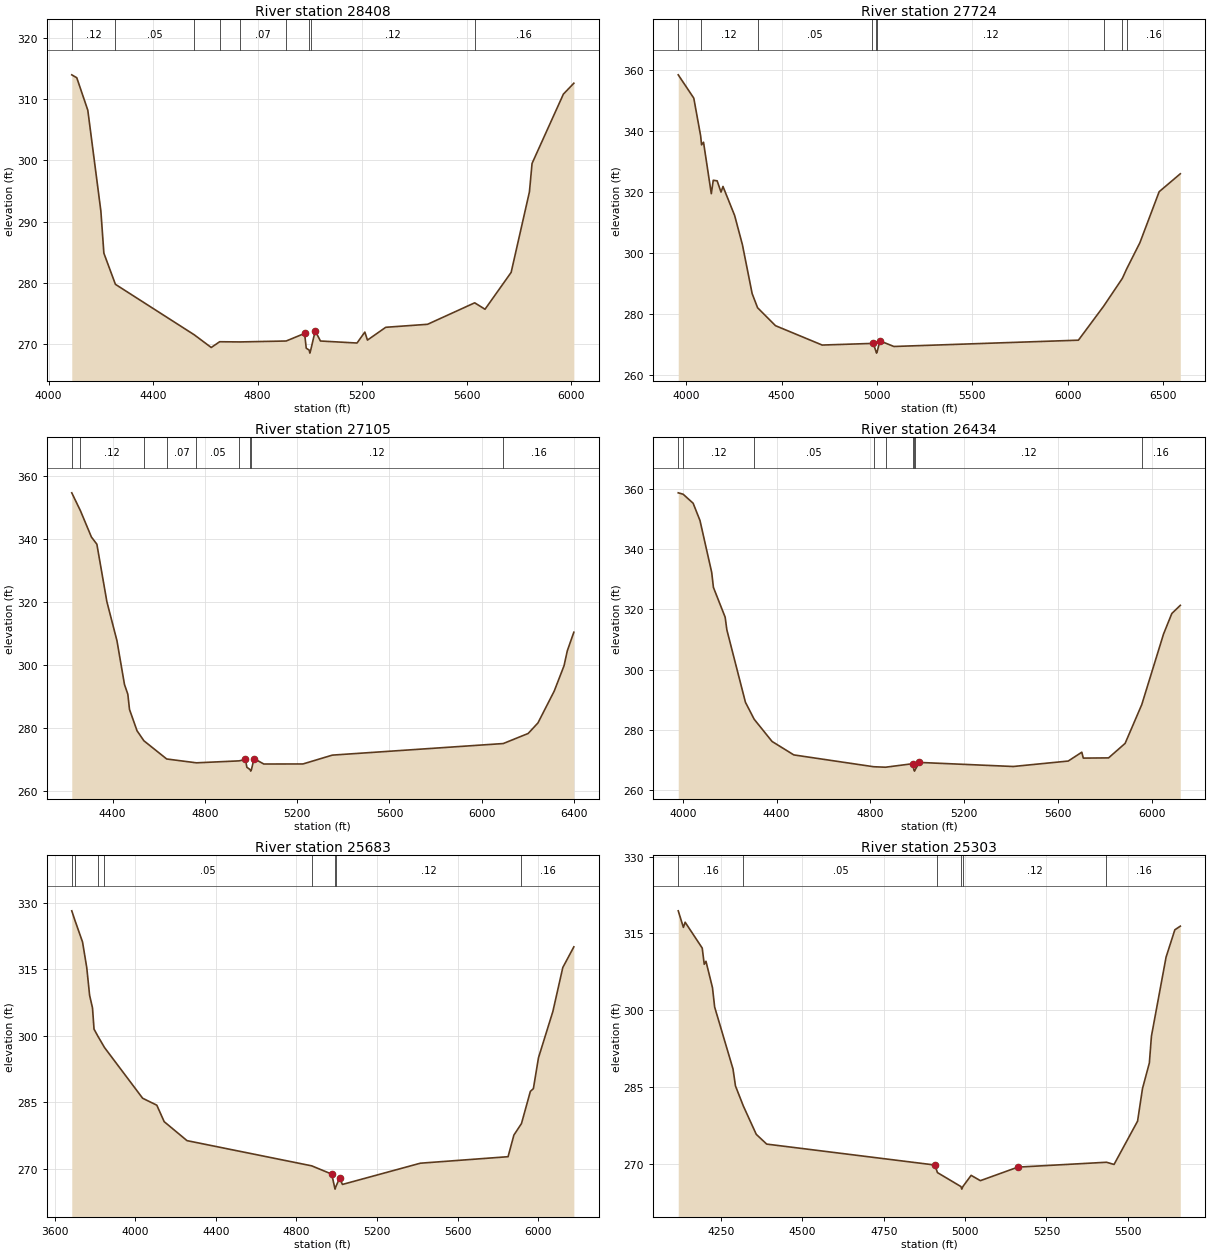
Type RM Length L Ch R = 1 ,28408   ,684,684,684
BEGIN DESCRIPTION:
BEAVER CREEK 35.0
END DESCRIPTION:
XS GIS Cut Line= 3
      3695599.61     10676910.21      3695799.61     10677810.19
      3695799.61     10678810.15
#Sta/Elev= 30
  4088.5  313.98  4107.7   313.5  4149.9   308.2  4199.9  291.72  4211.4  284.84
  4255.6  279.75  4557.2  271.51  4622.4  269.43  4654.5  270.37  4733.6  270.34
  4909.2  270.49  4979.7  271.73  4986.1  269.31  4997.2  269.01  4999.9  268.51
  5003.2  269.01  5020.4  272.15  5040.4  270.49  5180.4  270.16  5210.4  271.95
  5220.4  270.64  5290.4  272.73  5450.4  273.22  5630.9  276.73  5670.4  275.68
  5770.4   281.7  5840.4  294.86  5850.4   299.5  5970.4  310.83  6010.4  312.61
#Mann= 9 ,-1 , 0
  4088.5     .12       0  4255.6     .05       0  4557.2     .07       0
  4654.5     .12       0  4733.6     .07       0  4909.2     .12       0
  4997.2     .07       0  5003.2     .12       0  5630.9     .16       0
Bank Sta=4979.7,5020.4
XS Rating Curve= 0 ,0
Exp/Cntr=0.3,0.1

Type RM Length L Ch R = 1 ,27724   ,619,619,619
BEGIN DESCRIPTION:
BEAVER CREEK 34.0
END DESCRIPTION:
XS GIS Cut Line= 3
      3694949.61     10676610.19      3695149.61     10677610.19
       3694949.6     10679210.24
#Sta/Elev= 30
  3957.9  358.41  4039.5  350.75  4075.4  338.37  4080.3  335.42  4090.5  336.27
  4131.3  319.38  4141.5  323.79  4161.9   323.6  4182.3   319.9  4192.5  321.76
  4253.6  312.23  4294.4  302.63  4345.4  286.57  4373.9  281.93  4467.8  276.04
  4712.6  269.68  4971.2  270.21  4980.2   270.3  4994.9  267.53  4997.6  267.03
  5000.9  267.53  5015.5  271.05  5088.6  269.21    6056  271.28  6188.1  282.43
  6286.4  291.58  6309.1   294.7  6378.5  303.31  6479.3  320.03  6590.2  325.92
#Mann= 9 ,-1 , 0
  3957.9     .05       0  4075.4     .12       0  4373.9     .05       0
  4971.2     .12       0  4994.9     .07       0  5000.9     .12       0
  6188.1     .16       0  6286.4     .05       0  6309.1     .16       0
Bank Sta=4980.2,5015.5
XS Rating Curve= 0 ,0
Exp/Cntr=0.3,0.1

Type RM Length L Ch R = 1 ,27105   ,671,671,671
BEGIN DESCRIPTION:
BEAVER CREEK 33.0
END DESCRIPTION:
XS GIS Cut Line= 3
      3694899.61     10676660.18      3694599.61     10677360.19
      3693599.61     10678360.19
#Sta/Elev= 30
  4223.1  354.77  4260.9  349.04  4308.3  340.71  4331.9  338.43  4375.4  320.11
  4418.9  307.77  4451.6  293.81  4466.1  290.73  4473.3   285.9    4506  279.12
  4535.8  275.93  4634.5  270.15  4763.3  268.93    4948  269.55  4975.6  269.99
    4982  267.51  4995.8  266.79  4998.6  266.29  5001.8  266.79    5013  270.27
  5055.4  268.55  5225.1  268.57  5352.4  271.38    6093  275.06  6200.9  278.26
  6243.3  281.61    6314  291.76  6356.5  299.82  6370.6  304.56  6398.9  310.45
#Mann= 9 ,-1 , 0
  4223.1     .05       0  4260.9     .12       0  4535.8     .05       0
  4634.5     .07       0  4763.3     .05       0    4948     .12       0
  4995.8     .07       0  5001.8     .12       0    6093     .16       0
Bank Sta=4975.6,5013
XS Rating Curve= 0 ,0
Exp/Cntr=0.3,0.1

Type RM Length L Ch R = 1 ,26434   ,751,751,751
BEGIN DESCRIPTION:
BEAVER CREEK 32.0
END DESCRIPTION:
XS GIS Cut Line= 3
      3694799.63     10676460.17      3693999.61     10677060.19
      3693299.61     10677960.18
#Sta/Elev= 30
  3980.6  358.74  4001.4  358.28  4044.2  355.27  4073.3  349.54  4123.3  332.28
  4130.6   327.3  4180.6   317.4  4187.9  313.18  4267.1  289.12  4304.2  283.49
  4380.6  276.09  4473.3  271.62  4813.7  267.69  4864.3  267.53  4979.2  268.69
  4980.6  268.69  4984.9  266.73  4987.6  266.23  4990.9  266.73  5008.7  269.12
  5408.6  267.77    5643  269.58  5700.9  272.52  5707.3  270.56    5815  270.63
  5885.5  275.45  5956.4  288.32  6049.3   311.8  6084.6  318.63  6120.8  321.34
#Mann= 9 ,-1 , 0
  3980.6     .05       0  4001.4     .12       0  4304.2     .05       0
  4813.7     .07       0  4864.3     .05       0  4979.2     .12       0
  4984.9     .07       0  4990.9     .12       0  5956.4     .16       0
Bank Sta=4980.6,5008.7
XS Rating Curve= 0 ,0
Exp/Cntr=0.3,0.1

Type RM Length L Ch R = 1 ,25683   ,380,380,380
BEGIN DESCRIPTION:
BEAVER CREEK 31.0
END DESCRIPTION:
XS GIS Cut Line= 4
      3694294.78     10675930.28      3693331.21     10676727.18
      3693122.87     10677143.85      3693206.21      10677914.7
#Sta/Elev= 30
  3685.4  328.25  3700.8  326.14  3738.8  321.21  3759.7  315.44    3774  309.14
  3788.3  306.31  3795.9  301.51  3814.5  299.96  3847.8  297.36  4037.1  285.89
  4107.5  284.32    4144   280.6  4257.3  276.31  4876.4  270.61  4975.6  268.74
  4989.4  265.85  4992.1  265.35  4995.4  265.85  5014.7  267.86  5028.6  266.41
  5415.4  271.21  5850.6  272.68  5879.4  277.56  5917.1  280.17  5961.2  287.44
  5976.2  288.06  6001.5  295.04    6073  305.52  6122.2  315.44    6177  320.11
#Mann= 8 ,-1 , 0
  3685.4     .16       0  3700.8     .12       0  3814.5     .16       0
  3847.8     .05       0  4876.4     .12       0  4989.4     .07       0
  4995.4     .12       0  5917.1     .16       0
Bank Sta=4975.6,5014.7
XS Rating Curve= 0 ,0
Exp/Cntr=0.3,0.1

Type RM Length L Ch R = 1 ,25303   ,897,897,897
BEGIN DESCRIPTION:
BEAVER CREEK 30.0
END DESCRIPTION:
XS GIS Cut Line= 4
      3693289.54     10675800.09      3693044.75     10676555.31
      3692919.75     10676669.89      3692435.41     10676987.58
#Sta/Elev= 30
  4118.7  319.42  4134.6  316.19  4139.9   317.2  4192.4  312.16  4198.6     309
  4203.9  309.58  4223.9  304.45  4230.6  300.66    4287  288.59  4294.6  285.27
    4319  281.33  4358.5  275.84  4390.5  273.94  4907.2  269.86  4915.2  268.38
  4987.3  265.66    4990  265.16  4993.3  265.66  5018.7  267.85    5047  266.81
  5162.4  269.45  5434.6   270.4  5457.8  269.97  5530.1  278.42  5545.2  284.77
  5566.3  289.76  5572.7  294.99  5617.6  310.38  5644.6  315.72  5661.4  316.43
#Mann= 6 ,-1 , 0
  4118.7     .16       0    4319     .05       0  4915.2     .12       0
  4987.3     .07       0  4993.3     .12       0  5434.6     .16       0
Bank Sta=4907.2,5162.4
XS Rating Curve= 0 ,0
Exp/Cntr=0.3,0.1

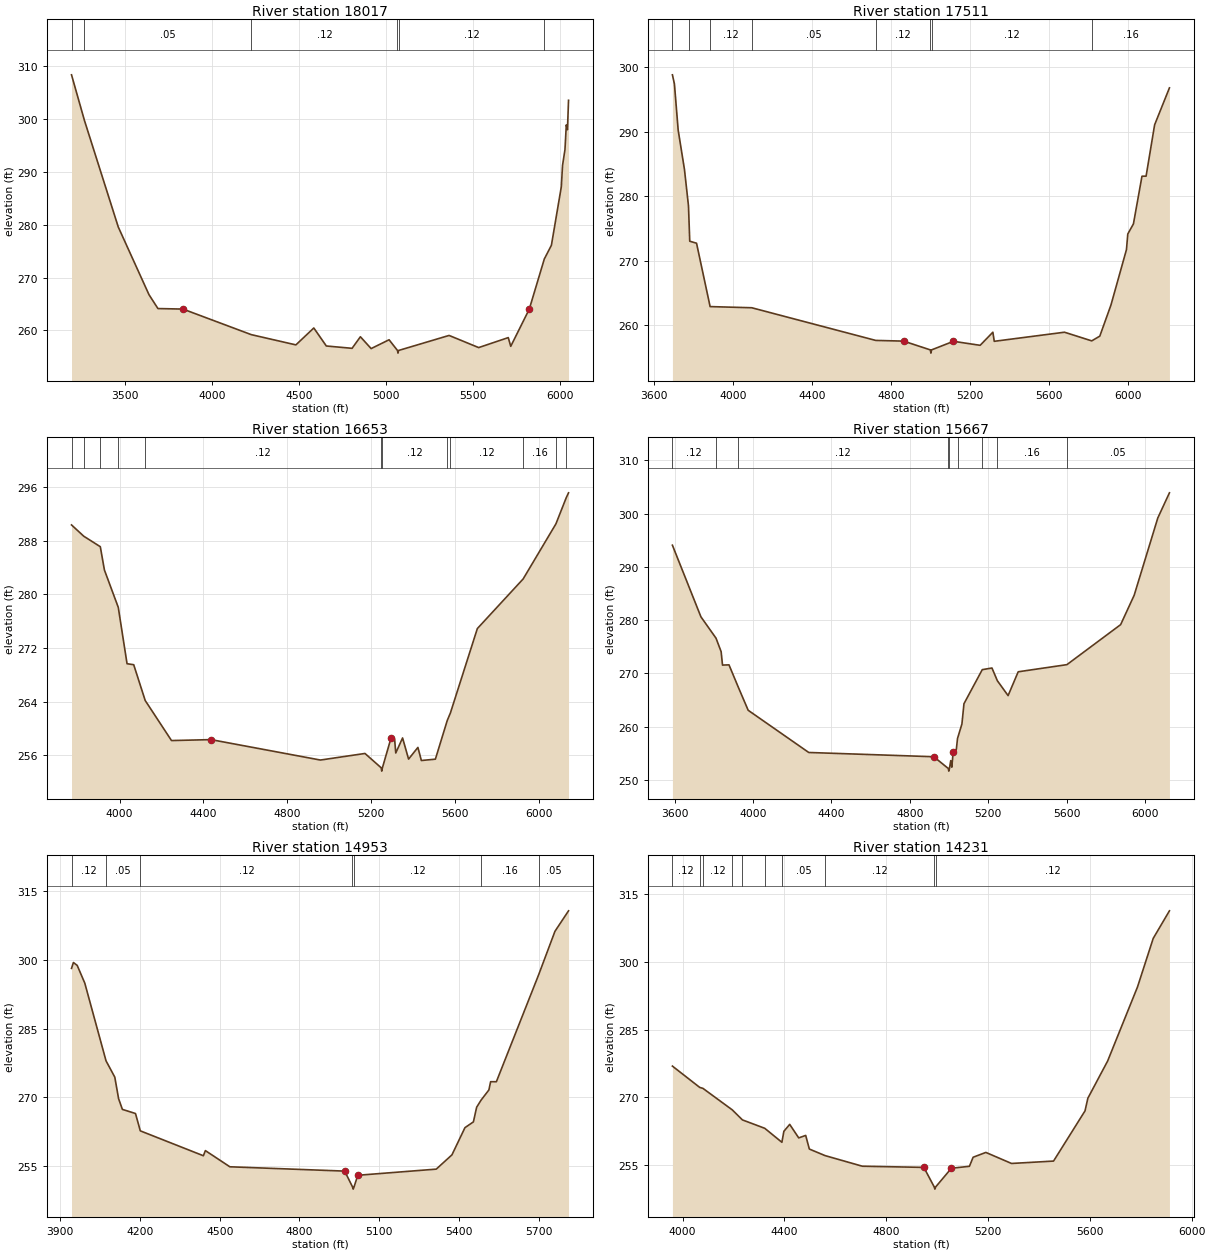
Type RM Length L Ch R = 1 ,18017   ,506,506,506
BEGIN DESCRIPTION:
BEAVER CREEK 20.0
END DESCRIPTION:
XS GIS Cut Line= 3
      3690481.88       10671690.      3688648.52      10672141.4
      3687913.53     10672772.38
#Sta/Elev= 30
  3190.2   308.4  3264.7  299.74    3459  279.58  3635.4  266.78  3686.9  264.14
  3831.1  264.04  4223.4   259.2  4479.9  257.26  4582.9  260.46  4654.9  257.05
  4802.8  256.61  4850.6   258.8  4912.4  256.56  5015.5  258.23  5063.9   256.2
  5066.6   255.7  5069.9   256.2  5360.4  259.05  5530.5  256.75  5700.6  258.64
  5714.8  256.99  5821.3  264.02  5907.7  273.52  5948.6  276.13  6005.6  287.22
  6012.6  291.26  6026.5  294.24  6034.2  298.91  6040.8  298.01    6047  303.58
#Mann= 6 ,-1 , 0
  3190.2     .16       0  3264.7     .05       0  4223.4     .12       0
  5063.9     .07       0  5069.9     .12       0  5907.7     .16       0
Bank Sta=3831.1,5821.3
XS Rating Curve= 0 ,0
Exp/Cntr=0.3,0.1

Type RM Length L Ch R = 1 ,17511   ,858,858,858
BEGIN DESCRIPTION:
BEAVER CREEK 19.0
END DESCRIPTION:
XS GIS Cut Line= 4
      3689030.47     10670530.26      3688815.19     10671717.78
      3688711.02     10671863.62        3687836.     10672571.97
#Sta/Elev= 30
  3695.3  298.82  3705.4  297.41  3724.4  290.25  3756.2  284.15  3776.5   278.5
  3779.7  275.77  3782.9  273.04  3817.2  272.73  3885.8  262.91  4096.4  262.73
  4722.6  257.67    4864  257.56  4998.9   256.2  5001.6   255.7  5004.9   256.2
  5115.5  257.53  5250.5  256.91  5314.8  258.94  5321.8  257.53  5676.7  258.94
  5814.4   257.6  5855.2  258.33  5911.7  263.16    5990  271.74  5996.7  274.16
  6025.2  275.72  6068.4  283.11  6089.2  283.12  6132.3  291.07  6207.2   296.8
#Mann= 8 ,-1 , 0
  3695.3     .16       0  3779.7     .05       0  3885.8     .12       0
  4096.4     .05       0  4722.6     .12       0  4998.9     .07       0
  5004.9     .12       0  5814.4     .16       0
Bank Sta=4864,5115.5
XS Rating Curve= 0 ,0
Exp/Cntr=0.3,0.1

Type RM Length L Ch R = 1 ,16653   ,986,986,986
BEGIN DESCRIPTION:
BEAVER CREEK 18.0
END DESCRIPTION:
XS GIS Cut Line= 3
      3688558.24     10670280.31      3688092.97     10671592.78
      3687649.16     10672466.53
#Sta/Elev= 30
  3770.1  290.32  3828.6  288.64  3907.5  287.08  3927.2  283.61  3993.3  278.05
  4035.2  269.66    4067  269.51  4121.9  264.18  4247.4  258.22  4436.2  258.36
  4958.3  255.32  5170.9   256.3  5248.2  254.17  5250.9  253.67  5254.2  254.17
  5295.7  258.64  5312.3  258.45  5317.9  256.37  5350.4  258.61  5379.1  255.46
  5423.6   257.2  5440.1  255.25    5507  255.45  5563.7  261.21  5578.7  262.33
  5707.3  274.89    5926  282.28  6082.4  290.48  6131.5  294.36  6142.6   295.1
#Mann= 12 ,-1 , 0
  3770.1     .12       0  3828.6     .16       0  3907.5     .12       0
  3993.3     .05       0  4121.9     .12       0  5248.2     .07       0
  5254.2     .12       0  5563.7     .16       0  5578.7     .12       0
    5926     .16       0  6082.4     .12       0  6131.5     .16       0
Bank Sta=4436.2,5295.7
XS Rating Curve= 0 ,0
Exp/Cntr=0.3,0.1

Type RM Length L Ch R = 1 ,15667   ,714,714,714
BEGIN DESCRIPTION:
BEAVER CREEK 17.0
END DESCRIPTION:
XS GIS Cut Line= 2
       3688037.4     10670217.82      3686981.84     10672523.38
#Sta/Elev= 30
  3588.9  294.05  3734.4  280.61  3811.3  276.61  3837.4  274.08  3844.5  271.56
  3877.5   271.6  3924.7  267.44  3975.4  263.08  4284.4  255.16  4922.3  254.36
  4996.3  252.16    4999  251.66  5002.3  252.16  5008.8  253.63  5014.3   252.4
  5021.3  255.27  5037.4  255.75  5043.4  257.78  5065.9  260.51  5076.3  264.31
  5169.7   270.7  5219.2  271.01  5246.7  268.62  5301.5  265.83    5353   270.3
  5601.5  271.64  5875.7  279.15  5944.7  284.66  6065.3  299.17  6124.6  303.88
#Mann= 9 ,-1 , 0
  3588.9     .12       0  3811.3     .05       0  3924.7     .12       0
  4996.3     .07       0  5002.3     .12       0  5043.4     .16       0
  5169.7     .12       0  5246.7     .16       0  5601.5     .05       0
Bank Sta=4922.3,5021.3
XS Rating Curve= 0 ,0
Exp/Cntr=0.3,0.1

Type RM Length L Ch R = 1 ,14953   ,722,722,722
BEGIN DESCRIPTION:
BEAVER CREEK 16.0
END DESCRIPTION:
XS GIS Cut Line= 3
      3687649.62     10670260.17      3686949.61     10671060.19
      3686549.59     10671760.22
#Sta/Elev= 30
  3942.7  298.15  3949.8  299.43  3964.1   298.8  3992.6  294.94  4072.5  277.99
  4105.5  274.43  4119.7  269.75    4134   267.4  4183.3   266.5  4201.4  262.72
  4438.6  257.29  4446.2  258.41  4538.3  254.88  4970.1  253.94  4999.4  250.51
  5002.2  250.01  5005.4  250.51  5019.4  253.03  5314.5  254.37  5373.6  257.49
  5422.5  263.42  5454.2  264.67  5466.4  267.87  5483.2  269.43  5512.5  271.64
    5519  273.44  5540.6  273.43  5700.1  296.83  5760.9  306.23    5812   310.7
#Mann= 7 ,-1 , 0
  3942.7     .12       0  4072.5     .05       0  4201.4     .12       0
  4999.4     .07       0  5005.4     .12       0  5483.2     .16       0
  5700.1     .05       0
Bank Sta=4970.1,5019.4
XS Rating Curve= 0 ,0
Exp/Cntr=0.3,0.1

Type RM Length L Ch R = 1 ,14231   ,199,199,199
BEGIN DESCRIPTION:
BEAVER CREEK 15.0
END DESCRIPTION:
XS GIS Cut Line= 3
      3687287.87     10670004.48      3686298.29     10670749.27
      3686126.41     10671442.02
#Sta/Elev= 30
  3960.4   276.9  4067.8  272.17  4080.3  271.96  4195.4   267.2  4235.4  264.97
    4323  263.11  4390.4  260.01  4398.2  262.44  4421.1  263.98  4456.5  260.98
  4483.9  261.53  4498.2  258.51  4559.7  257.06  4706.4   254.7    4948  254.44
  4988.7  250.12  4991.4  249.62  4994.7  250.12  5056.2  254.25    5127  254.68
  5141.6  256.69  5191.6  257.76  5292.4  255.31  5457.5  255.84  5581.1  266.97
  5592.3  269.78  5669.9  278.02  5787.2  294.44    5849  305.22  5912.7  311.33
#Mann= 10 ,-1 , 0
  3960.4     .12       0  4067.8     .05       0  4080.3     .12       0
  4195.4     .05       0  4235.4     .12       0    4323     .08       0
  4390.4     .05       0  4559.7     .12       0  4988.7     .07       0
  4994.7     .12       0
Bank Sta=4948,5056.2
XS Rating Curve= 0 ,0
Exp/Cntr=0.3,0.1

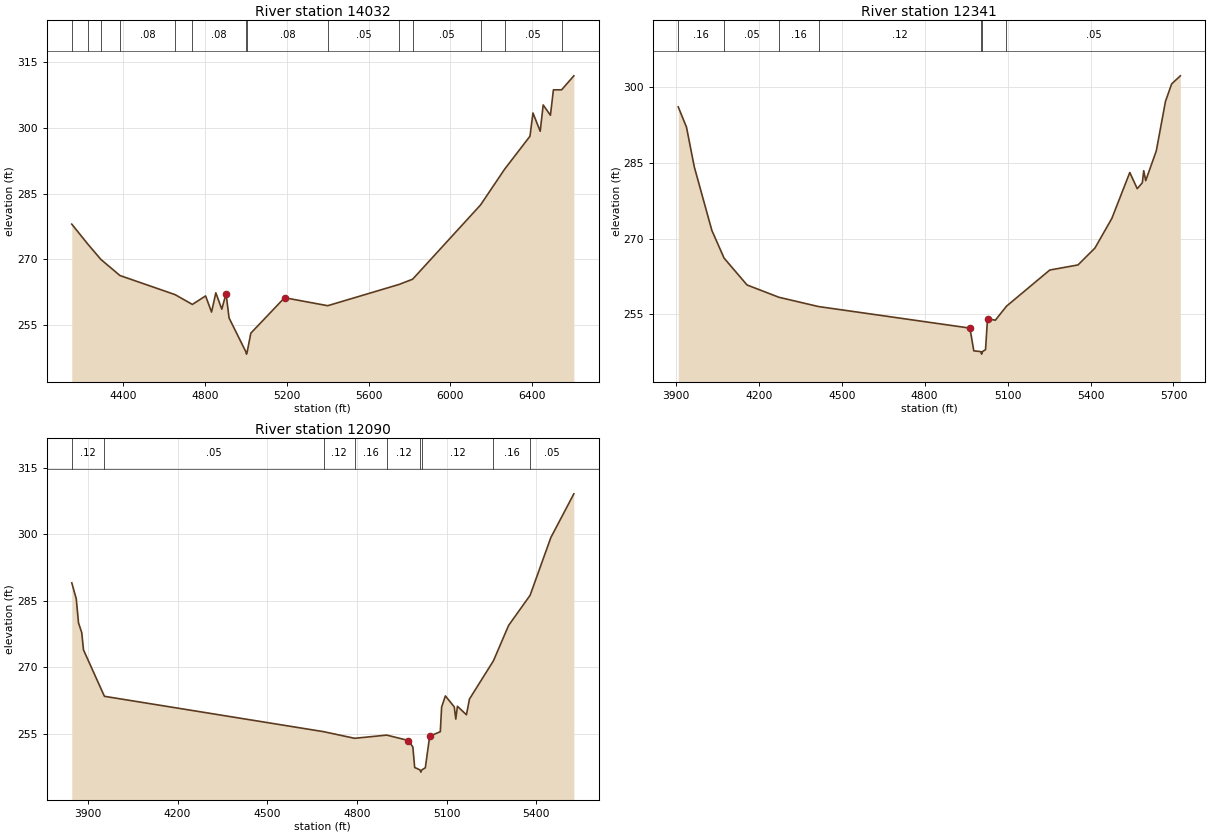
Type RM Length L Ch R = 1 ,14032   ,729,729,729
BEGIN DESCRIPTION:
BEAVER CREEK 14.0
END DESCRIPTION:
XS GIS Cut Line= 3
      3687121.17     10669926.38      3686157.67     10670639.89
      3685153.52      10671394.3
#Sta/Elev= 30
  4148.9  278.03  4227.8  273.45  4291.7  269.96  4384.3  266.31  4654.4  261.94
  4738.5  259.71  4803.2  261.65  4832.4  257.97  4853.3  262.36  4882.5  258.63
  4903.4   262.2    4918  256.63  5000.5  248.87  5003.3  248.37  5006.5  248.87
  5024.4  253.15  5189.3  261.24  5400.4  259.42  5749.3  264.27  5815.5  265.46
  6147.5   282.4  6264.9  290.54  6389.3  298.09  6403.9   303.4  6439.3  299.23
  6453.9  305.22  6489.3  302.88  6503.9  308.67    6544  308.68  6603.8  311.87
#Mann= 14 ,-1 , 0
  4148.9     .16       0  4227.8     .08       0  4291.7     .16       0
  4384.3     .08       0  4654.4     .12       0  4738.5     .08       0
  5000.5     .07       0  5006.5     .08       0  5400.4     .05       0
  5749.3     .08       0  5815.5     .05       0  6147.5     .08       0
  6264.9     .05       0    6544     .08       0
Bank Sta=4903.4,5189.3
XS Rating Curve= 0 ,0
Exp/Cntr=0.3,0.1

Type RM Length L Ch R = 1 ,12341   ,251,251,251
BEGIN DESCRIPTION:
BEAVER CREEK 13.0
END DESCRIPTION:
XS GIS Cut Line= 3
      3686321.18     10668719.74      3685487.88     10669537.42
      3685357.67     10670172.84
#Sta/Elev= 30
  3908.6  296.14  3938.4  292.14  3966.7  284.25  4030.2  271.66  4074.4  266.17
  4157.5  260.84  4272.9   258.4  4416.1  256.56  4963.6  252.29  4977.8  247.78
  5003.1  247.63  5005.8  247.13  5009.1  247.63  5020.2  248.02  5027.3  254.18
  5055.6  253.85  5095.9  256.63  5252.4   263.8  5354.5  264.81  5415.8  268.15
    5477  274.03    5542  283.14  5568.9  279.93  5587.3   281.1  5592.4  283.49
  5599.5  281.52  5637.8  287.41    5671  297.22  5693.3  300.69  5724.7   302.3
#Mann= 7 ,-1 , 0
  3908.6     .16       0  4074.4     .05       0  4272.9     .16       0
  4416.1     .12       0  5003.1     .07       0  5009.1     .12       0
  5095.9     .05       0
Bank Sta=4963.6,5027.3
XS Rating Curve= 0 ,0
Exp/Cntr=0.3,0.1

Type RM Length L Ch R = 1 ,12090   ,638,638,638
BEGIN DESCRIPTION:
BEAVER CREEK 12.0
END DESCRIPTION:
XS GIS Cut Line= 4
      3685819.47     10668249.24      3685418.43     10669244.01
      3685319.47     10669379.43      3684883.29     10669436.55
#Sta/Elev= 30
  3845.9  289.08    3861  285.47  3868.5  280.05  3879.3  277.86  3885.1  273.97
  3955.2  263.49  4688.4  255.52  4792.5  254.02  4900.1  254.74  4972.6  253.52
  4987.3  252.06  4993.5  247.44  5011.4  246.89  5014.1  246.39  5017.4  246.89
    5029  247.36  5043.7   254.5  5079.2  255.51  5083.6  261.05  5096.1  263.58
  5125.9  261.12    5131  258.35  5136.5  261.24  5166.7  259.33  5176.8  262.88
  5257.1  271.51  5307.9  279.49  5379.7  286.27  5449.1  299.29  5526.1  309.16
#Mann= 9 ,-1 , 0
  3845.9     .12       0  3955.2     .05       0  4688.4     .12       0
  4792.5     .16       0  4900.1     .12       0  5011.4     .07       0
  5017.4     .12       0  5257.1     .16       0  5379.7     .05       0
Bank Sta=4972.6,5043.7
XS Rating Curve= 0 ,0
Exp/Cntr=0.3,0.1