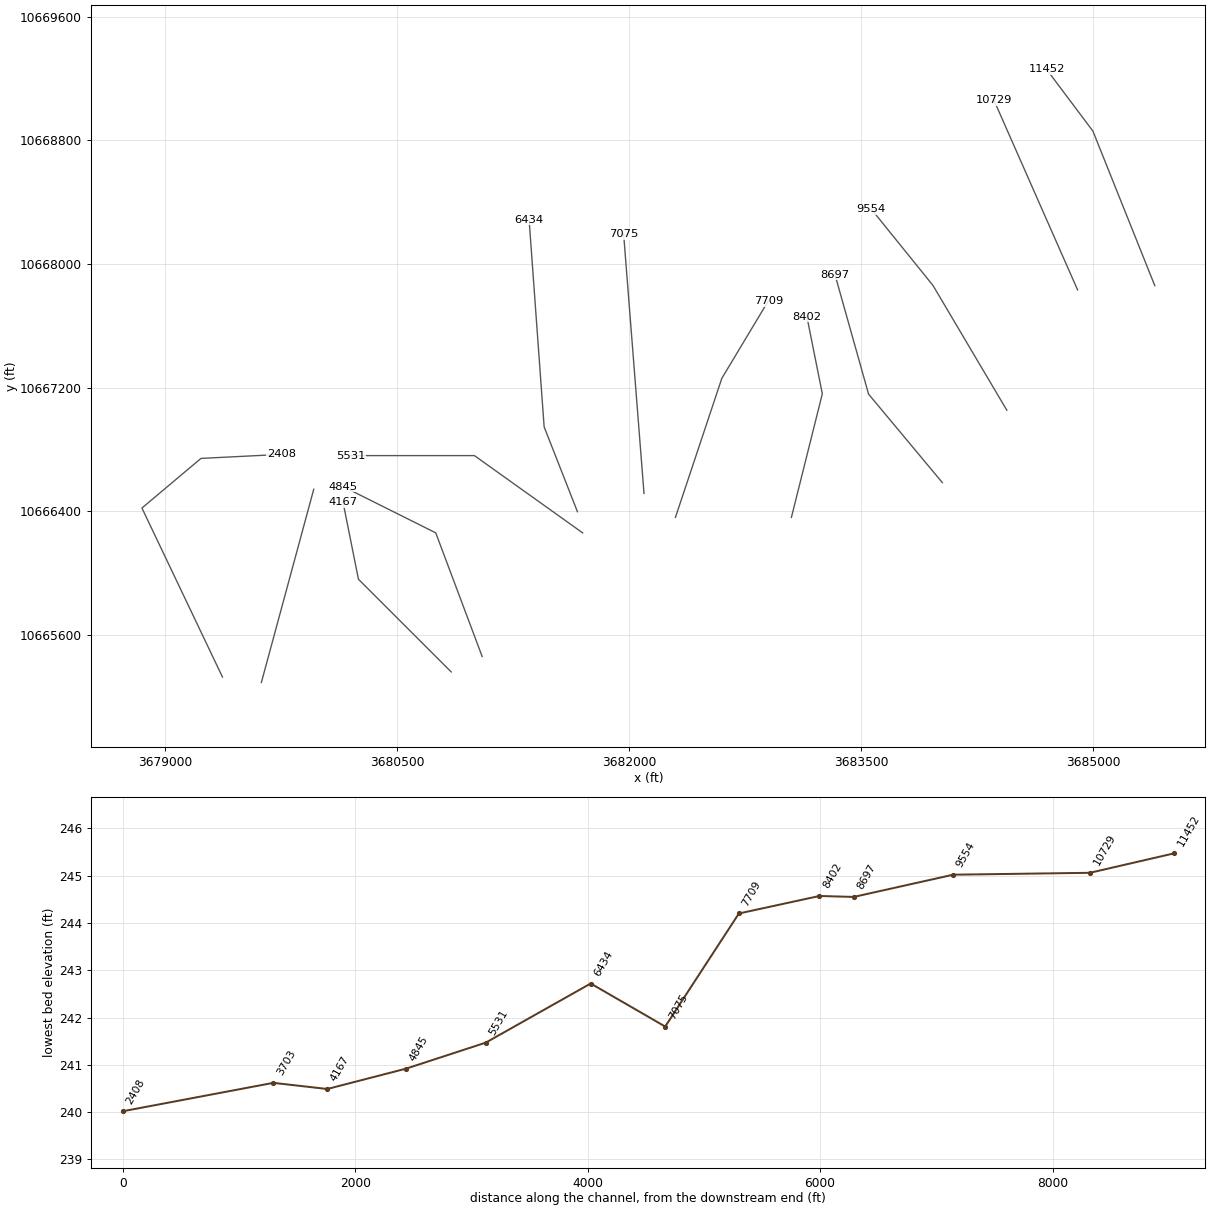
HEC-RAS study BEAVER CREEK.prj: BEAVER CREEK Base Level Engineering

--- BEAVER CREEK.g02 (geometry) --- (continued)

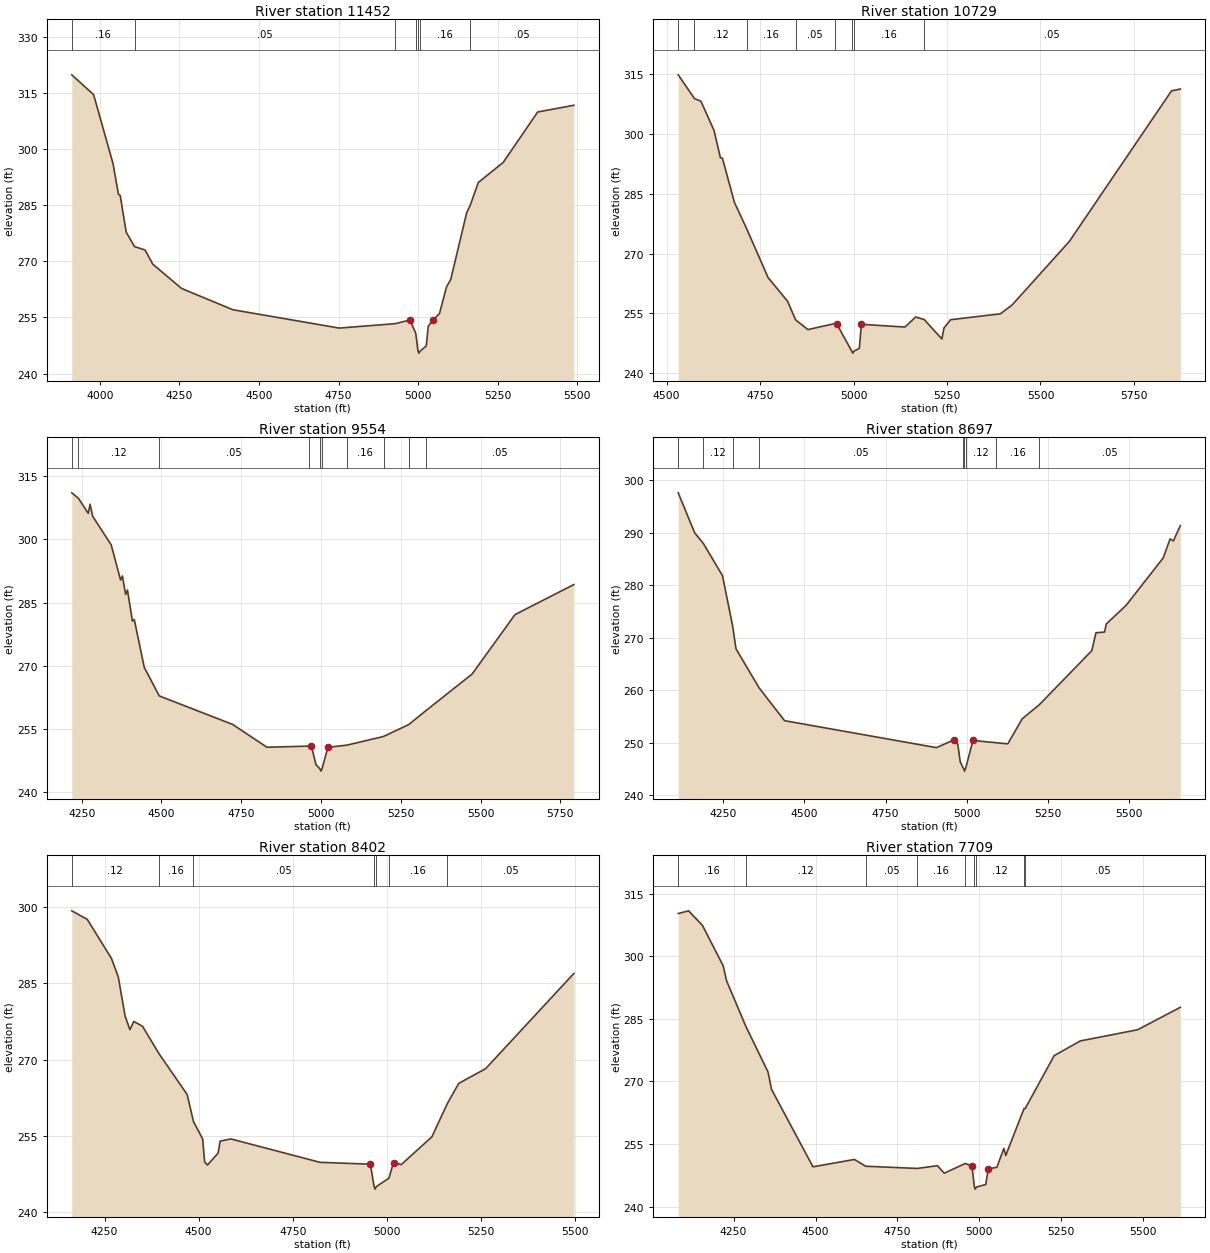
Type RM Length L Ch R = 1 ,11452   ,723,723,723
BEGIN DESCRIPTION:
BEAVER CREEK 11.0
END DESCRIPTION:
XS GIS Cut Line= 3
      3685399.59     10667860.22      3684999.61     10668860.19
      3684699.61     10669260.19
#Sta/Elev= 30
  3912.2   319.9  3980.8  314.59  4041.4   296.3  4058.9  287.92  4064.3  287.66
  4083.1  277.83  4109.3  273.97  4142.4  273.05  4166.6  269.27  4256.8  262.78
  4418.4  257.07  4752.2  252.17  4928.2  253.35  4974.4  254.33  4992.7  250.78
  4999.7  245.97  5002.5  245.47  5005.7  245.97  5025.7  247.41  5031.9  252.66
  5046.5   254.3  5067.3  256.08  5089.2  263.17  5102.7  265.22  5152.7  283.05
  5162.6  284.76  5189.2  291.11  5267.3  296.47  5375.7  309.96  5489.2  311.76
#Mann= 7 ,-1 , 0
  3912.2     .16       0  4109.3     .05       0  4928.2     .12       0
  4992.7     .16       0  4999.7     .07       0  5005.7     .16       0
  5162.6     .05       0
Bank Sta=4974.4,5046.5
XS Rating Curve= 0 ,0
Exp/Cntr=0.3,0.1

Type RM Length L Ch R = 1 ,10729   ,1175,1175,1175
BEGIN DESCRIPTION:
Mapping XS aac11626
END DESCRIPTION:
XS GIS Cut Line= 2
      3684900.38     10667832.64      3684358.72     10669061.79
#Sta/Elev= 30
  4530.9  314.83  4574.4  308.87  4591.6  308.21  4626.6   300.9  4643.7  294.05
  4649.1  293.93  4681.2  282.86  4714.3  276.17  4771.2  264.01  4823.4  258.07
  4844.8  253.41  4877.9  250.96  4950.1  252.48  4954.4  252.48  4995.1  245.56
  4997.9  245.06  5001.1  245.56  5015.4  246.27  5020.9  252.28  5137.5   251.6
  5166.3  254.13  5188.9  253.48  5236.3  248.61  5241.8  251.35  5259.6  253.44
  5392.7  254.91  5424.3  257.15  5577.3  273.07  5850.5   310.8  5874.1  311.27
#Mann= 8 ,-1 , 0
  4530.9     .16       0  4574.4     .12       0  4714.3     .16       0
  4844.8     .05       0  4950.1     .16       0  4995.1     .07       0
  5001.1     .16       0  5188.9     .05       0
Bank Sta=4954.4,5020.9
XS Rating Curve= 0 ,0
Exp/Cntr=0.3,0.1

Type RM Length L Ch R = 1 ,9554    ,857,857,857
BEGIN DESCRIPTION:
BEAVER CREEK 10.0
END DESCRIPTION:
XS GIS Cut Line= 3
      3684442.75     10667053.89      3683965.31      10667861.2
      3683566.34     10668355.57
#Sta/Elev= 30
  4219.1  311.06  4239.8  309.78  4270.7   306.2  4276.5  308.34  4284.5  305.52
  4342.6  298.71  4372.1  290.36  4377.9  291.32  4387.8  286.95  4393.6     288
  4409.2  280.63    4415  280.99  4446.3  269.63  4493.2  262.87  4723.2   256.1
  4830.6  250.69  4962.8  250.96    4970  250.94  4984.5  246.55  4997.1  245.52
  4999.9  245.02  5003.1  245.52  5021.6  250.66  5081.1  251.19  5195.9  253.24
  5275.2  256.08  5329.5  259.41  5473.6  268.06  5607.9  282.16  5792.3  289.29
#Mann= 10 ,-1 , 0
  4219.1     .16       0  4239.8     .12       0  4493.2     .05       0
  4962.8     .12       0  4997.1     .07       0  5003.1     .12       0
  5081.1     .16       0  5195.9     .05       0  5275.2     .12       0
  5329.5     .05       0
Bank Sta=4970,5021.6
XS Rating Curve= 0 ,0
Exp/Cntr=0.3,0.1

Type RM Length L Ch R = 1 ,8697    ,295,295,295
BEGIN DESCRIPTION:
BEAVER CREEK 9.0
END DESCRIPTION:
XS GIS Cut Line= 3
      3684026.08     10666585.15      3683548.64     10667158.08
      3683331.64      10667930.6
#Sta/Elev= 30
  4110.7  297.63  4161.3  290.01  4188.4  287.95  4247.2  281.83  4278.4  272.24
  4288.9  267.86  4360.1  260.43  4438.6  254.17  4906.9  249.03  4962.5  250.56
  4972.9  249.59  4980.2  246.35  4989.9  245.07  4990.7  245.05  4993.5  244.55
  4996.7  245.05  5019.5   250.4  5090.7  249.97  5126.9  249.75  5171.3  254.52
  5224.4  257.23  5386.1  267.53  5398.8  270.94  5425.4  271.07  5430.6  272.61
  5492.3  276.21  5606.1  285.21  5627.3  288.84  5637.7  288.47  5658.9  291.38
#Mann= 9 ,-1 , 0
  4110.7     .16       0  4188.4     .12       0  4278.4     .16       0
  4360.1     .05       0  4989.9     .12       0  4990.7     .07       0
  4996.7     .12       0  5090.7     .16       0  5224.4     .05       0
Bank Sta=4962.5,5019.5
XS Rating Curve= 0 ,0
Exp/Cntr=0.3,0.1

Type RM Length L Ch R = 1 ,8402    ,693,693,693
BEGIN DESCRIPTION:
BEAVER CREEK 8.0
END DESCRIPTION:
XS GIS Cut Line= 3
      3683049.61     10666360.18      3683249.61     10667160.19
      3683149.62     10667660.15
#Sta/Elev= 30
  4162.7  299.27  4203.9   297.6  4268.4  289.88  4286.4  286.27  4304.4  278.59
  4317.3  275.91  4327.6  277.53  4350.8  276.58  4393.8  271.27  4469.4  263.16
  4486.2  257.85  4510.6  254.42  4515.8  249.91  4523.5  249.32  4551.8  251.67
    4557     254  4585.3  254.44  4822.4  249.84  4956.4  249.47  4966.3  245.07
    4969  244.57  4972.3  245.07  5005.7  246.73  5017.9  249.79  5038.3  249.38
  5119.9  254.85  5161.2  261.42  5191.3  265.36  5262.7  268.24  5497.2  286.96
#Mann= 7 ,-1 , 0
  4162.7     .12       0  4393.8     .16       0  4486.2     .05       0
  4966.3     .03       0  4972.3     .05       0  5005.7     .16       0
  5161.2     .05       0
Bank Sta=4956.4,5017.9
XS Rating Curve= 0 ,0
Exp/Cntr=0.3,0.1

Type RM Length L Ch R = 1 ,7709    ,634,634,634
BEGIN DESCRIPTION:
BEAVER CREEK 7.0
END DESCRIPTION:
XS GIS Cut Line= 3
      3682299.59     10666360.14      3682599.61     10667260.19
       3682899.6     10667760.17
#Sta/Elev= 30
  4081.2  310.26  4112.9   310.9    4155  307.42  4218.3  297.73  4228.8  294.11
  4287.3  283.24  4355.3  272.25  4365.9  268.09  4492.3  249.55  4618.8  251.31
  4652.9  249.69  4810.9  249.16  4871.8  249.82  4892.9  248.02  4956.8  250.34
  4977.2  249.76  4984.8   244.7  4987.5   244.2  4990.8   244.7  5019.4  245.31
  5027.3  249.08  5053.3  249.42  5074.6  253.96  5080.5  252.27  5136.2  263.51
  5139.6  263.49  5228.2  276.19  5307.9  279.72  5482.8   282.4    5613  287.77
#Mann= 9 ,-1 , 0
  4081.2     .16       0  4287.3     .12       0  4652.9     .05       0
  4810.9     .16       0  4956.8     .12       0  4984.8     .07       0
  4990.8     .12       0  5136.2     .16       0  5139.6     .05       0
Bank Sta=4977.2,5027.3
XS Rating Curve= 0 ,0
Exp/Cntr=0.3,0.1

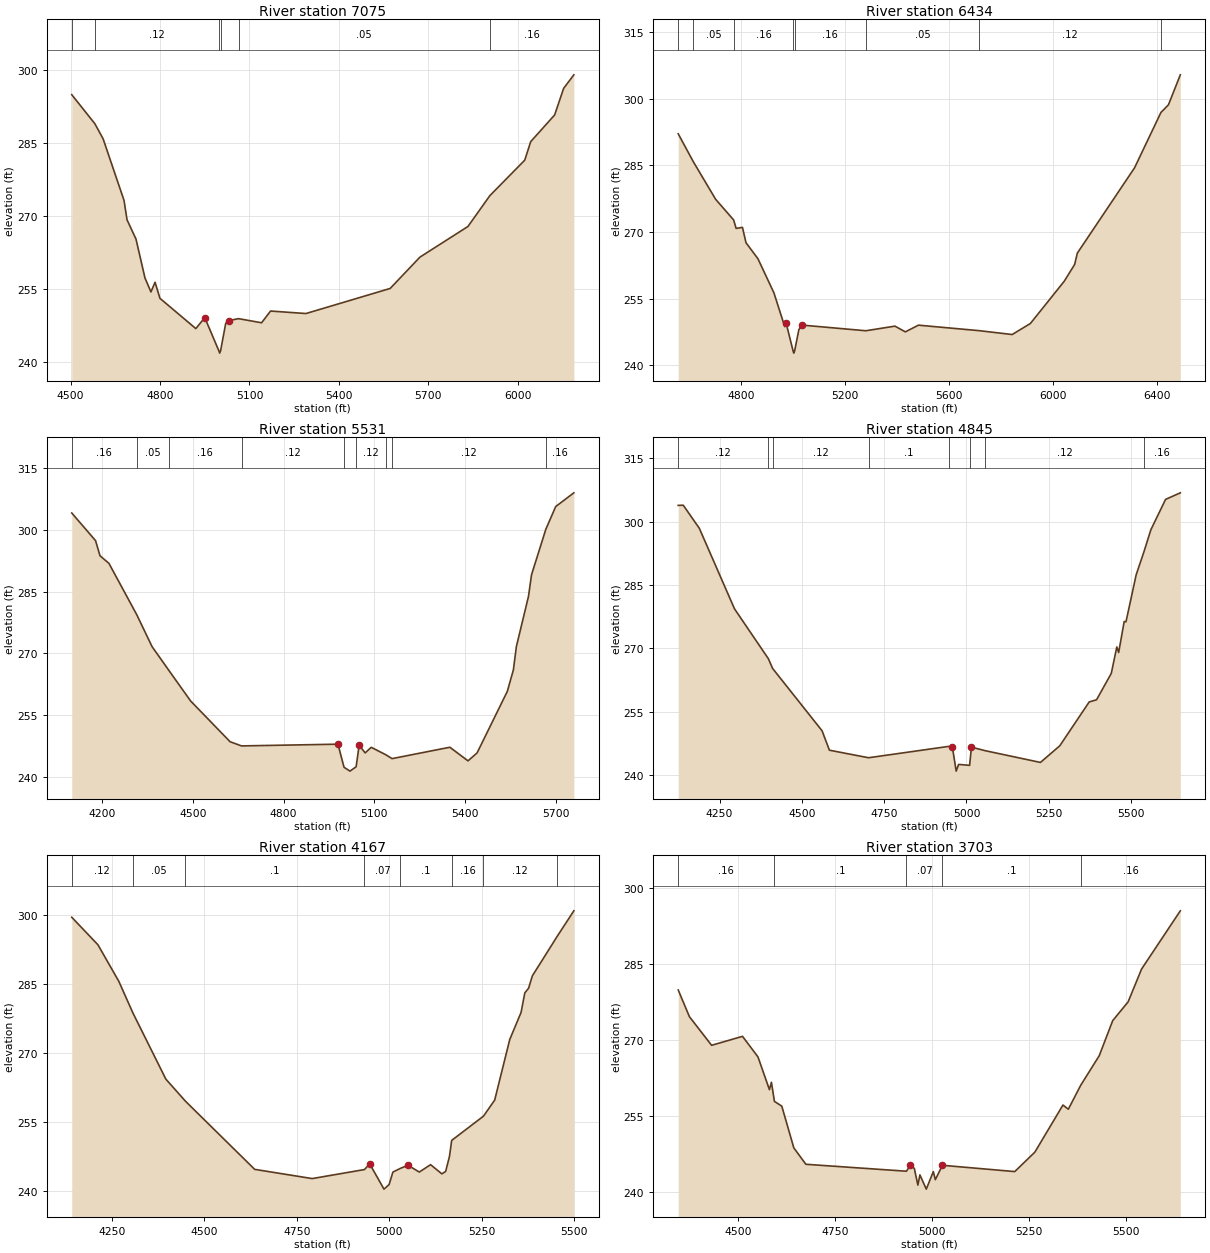
Type RM Length L Ch R = 1 ,7075    ,641,641,641
BEGIN DESCRIPTION:
BEAVER CREEK 6.0
END DESCRIPTION:
XS GIS Cut Line= 2
      3682096.38      10666515.4      3681964.56     10668194.43
#Sta/Elev= 30
    4504  294.87  4581.5  288.91  4609.1  285.82  4679.3  273.17  4689.4  269.18
  4719.5  265.22  4749.5  257.26  4769.6  254.37  4783.4  256.37  4799.7  253.07
  4920.1  246.85  4950.2  249.09  4997.3  242.31  5000.1  241.81  5003.3  242.31
  5020.4  247.92  5030.4  248.49  5063.3  248.89  5140.7  248.04  5170.8  250.45
  5289.7  249.94  5572.1  255.09  5671.9  261.52  5832.9  267.81  5906.6  274.15
  6023.5  281.43  6043.5  285.23  6123.8  290.71  6153.9  296.16  6188.2  298.95
#Mann= 6 ,-1 , 0
    4504     .16       0  4581.5     .12       0  4997.3     .07       0
  5003.3     .12       0  5063.3     .05       0  5906.6     .16       0
Bank Sta=4950.2,5030.4
XS Rating Curve= 0 ,0
Exp/Cntr=0.3,0.1

Type RM Length L Ch R = 1 ,6434    ,903,903,903
BEGIN DESCRIPTION:
BEAVER CREEK 5.0
END DESCRIPTION:
XS GIS Cut Line= 3
      3681665.82     10666397.33      3681450.55     10666945.92
      3681353.37     10668285.69
#Sta/Elev= 30
  4556.7  292.13    4614  285.92  4700.8  277.37  4770.1  272.72  4779.5  270.82
  4803.9  271.05  4817.6  267.59  4863.5  263.99    4925  256.31  4966.6  248.69
    4972   249.5  4998.8  243.22  5001.5  242.72  5004.8  243.22  5020.9  247.98
  5032.4  249.04  5278.9  247.76  5390.9   248.8    5431  247.51  5481.2  249.02
  5715.2  247.78  5842.1  246.91  5912.3   249.4  6042.6  258.92  6082.7  262.71
  6092.8  265.24  6313.3  284.48  6414.7  296.94  6443.7  298.67  6489.3  305.42
#Mann= 8 ,-1 , 0
  4556.7     .16       0    4614     .05       0  4770.1     .16       0
  4998.8     .07       0  5004.8     .16       0  5278.9     .05       0
  5715.2     .12       0  6414.7     .16       0
Bank Sta=4972,5032.4
XS Rating Curve= 0 ,0
Exp/Cntr=0.3,0.1

Type RM Length L Ch R = 1 ,5531    ,686,686,686
BEGIN DESCRIPTION:
BEAVER CREEK 4.0
END DESCRIPTION:
XS GIS Cut Line= 3
      3681699.62     10666260.18      3680999.61     10666760.19
      3680199.56     10666760.19
#Sta/Elev= 30
  4099.7  304.03  4178.4  297.33  4193.1  293.66  4222.6  291.83  4314.6  279.38
  4365.2  271.65  4421.7  265.79    4493  258.45  4623.2   248.6  4661.1  247.58
    4980     248    5000  242.41  5019.7  241.47    5040  242.52    5050  247.71
    5070  245.89    5090  247.24  5137.9  245.45  5158.9   244.5    5350  247.26
    5410  243.96    5440  245.88    5540   260.8    5560  265.98    5570  271.67
    5610  283.82    5620  289.04  5667.3  300.07    5700  305.59    5760  308.92
#Mann= 9 ,-1 , 0
  4099.7     .16       0  4314.6     .05       0  4421.7     .16       0
  4661.1     .12       0    5000     .07       0    5040     .12       0
  5137.9     .16       0  5158.9     .12       0  5667.3     .16       0
Bank Sta=4980,5050
XS Rating Curve= 0 ,0
Exp/Cntr=0.3,0.1

Type RM Length L Ch R = 1 ,4845    ,678,678,678
BEGIN DESCRIPTION:
BEAVER CREEK 3.0
END DESCRIPTION:
XS GIS Cut Line= 3
      3681049.62     10665460.16      3680749.61     10666260.19
      3680149.57     10666560.21
#Sta/Elev= 30
  4124.3  303.88  4139.5  303.93  4188.4  298.45  4295.2  279.38  4398.1  267.56
    4411  265.25  4561.3  250.48  4583.6  245.88  4702.5  244.09  4946.7  246.79
  4957.4  246.52  4968.7  240.92  4976.1  242.51  5009.5  242.29  5015.1   246.6
  5056.5  245.77  5224.7  242.98  5283.4  246.92  5372.8  257.31  5395.2  257.83
  5439.9  264.08  5456.7  270.34  5462.3  269.03  5479.1  276.36  5484.6  276.31
  5515.4  287.41  5539.7  293.03  5560.1   298.1  5604.8   305.3  5649.6  306.86
#Mann= 8 ,-1 , 0
  4124.3     .12       0  4398.1     .16       0    4411     .12       0
  4702.5      .1       0  4946.7     .07       0  5009.5      .1       0
  5056.5     .12       0  5539.7     .16       0
Bank Sta=4957.4,5015.1
XS Rating Curve= 0 ,0
Exp/Cntr=0.3,0.1

Type RM Length L Ch R = 1 ,4167    ,464,464,464
BEGIN DESCRIPTION:
BEAVER CREEK 2.0
END DESCRIPTION:
XS GIS Cut Line= 3
      3680849.63     10665360.17      3680249.61     10665960.19
       3680149.6     10666460.23
#Sta/Elev= 30
  4141.3  299.51    4212  293.55  4268.6  285.61  4306.6  278.76  4395.9  264.37
  4448.9  259.58  4636.3  244.78  4791.9  242.78  4933.3  244.74  4947.4  245.98
  4986.1  240.49    5000  241.49  5010.2  244.19  5030.6     245    5051  245.67
  5081.6   244.2  5112.2   245.8  5142.8   243.8    5153  244.34  5163.2  247.57
  5169.3  251.07  5255.1  256.32  5285.6  259.81  5326.4  272.98    5357  278.85
  5367.2  283.11  5377.4  284.11  5387.6   286.8  5455.1  295.41  5499.8  300.91
#Mann= 8 ,-1 , 0
  4141.3     .12       0  4306.6     .05       0  4448.9      .1       0
  4933.3     .07       0  5030.6      .1       0  5169.3     .16       0
  5255.1     .12       0  5455.1     .16       0
Bank Sta=4947.4,5051
XS Rating Curve= 0 ,0
Exp/Cntr=0.3,0.1

Type RM Length L Ch R = 1 ,3703    ,1295,1295,1295
BEGIN DESCRIPTION:
Mapping XS 77539628
END DESCRIPTION:
XS GIS Cut Line= 2
      3679621.99     10665292.42      3679960.52     10666542.38
#Sta/Elev= 30
  4345.4  279.89  4374.2  274.63  4431.5  268.98  4511.2  270.75  4551.1  266.69
  4580.6  260.24  4585.8  261.69  4593.5  257.92  4612.5  256.99  4643.5  248.76
  4674.6  245.52    4934  244.15    4944  245.29  4954.3  244.72  4963.5  241.41
  4968.7  243.43  4985.2  240.62  5003.3  244.08  5008.5  242.49  5026.9  245.32
  5213.4  244.08  5265.2  247.91  5337.7   257.2  5351.6  256.38  5383.5   261.1
  5431.3  266.93    5466  273.84  5505.8  277.55  5540.5  284.02  5640.4   295.5
#Mann= 5 ,-1 , 0
  4345.4     .16       0  4593.5      .1       0    4934     .07       0
  5026.9      .1       0  5383.5     .16       0
Bank Sta=4944,5026.9
XS Rating Curve= 0 ,0
Exp/Cntr=0.3,0.1

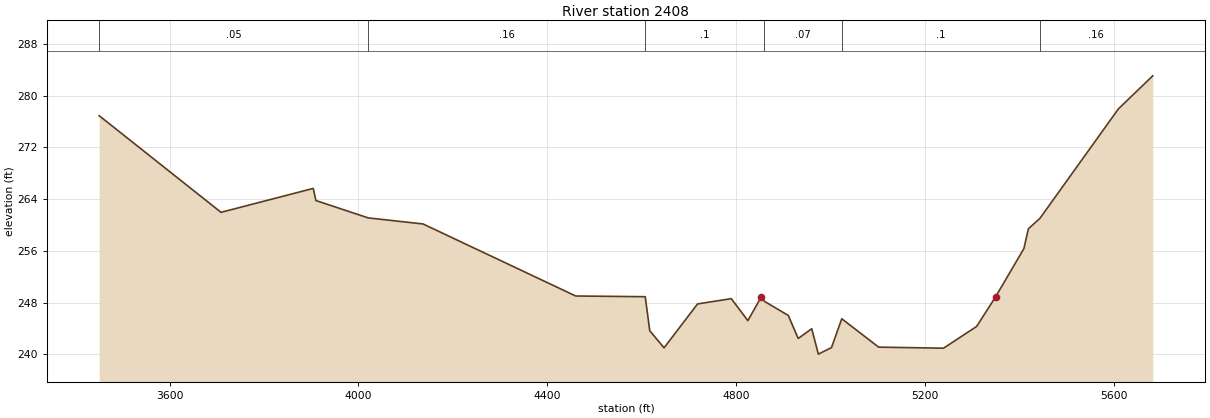
Type RM Length L Ch R = 1 ,2408    ,0,0,0
BEGIN DESCRIPTION:
BEAVER CREEK 1.0
END DESCRIPTION:
XS GIS Cut Line= 4
      3679370.26     10665327.13      3678849.42      10666420.9
      3679231.37     10666742.08      3679752.23     10666768.12
#Sta/Elev= 30
  3450.7  276.89  3708.8  261.95  3904.2  265.65  3909.8  263.77  4020.6  261.09
  4136.8  260.15  4460.2  249.01  4607.5   248.9  4617.1  243.64  4647.4  240.99
  4718.3  247.78  4789.8   248.6    4825   245.2  4853.6  248.91  4860.1  248.18
  4910.6     246  4931.6  242.44  4960.2  243.95  4974.3  240.02  5002.1  241.03
  5023.9  245.49    5102   241.1  5239.5  240.94  5309.6   244.3  5349.7  248.87
  5409.7  256.34  5419.3  259.41  5443.7  261.02    5610  277.95  5682.7  283.06
#Mann= 6 ,-1 , 0
  3450.7     .05       0  4020.6     .16       0  4607.5      .1       0
  4860.1     .07       0  5023.9      .1       0  5443.7     .16       0
Bank Sta=4853.6,5349.7
XS Rating Curve= 0 ,0
Exp/Cntr=0.3,0.1