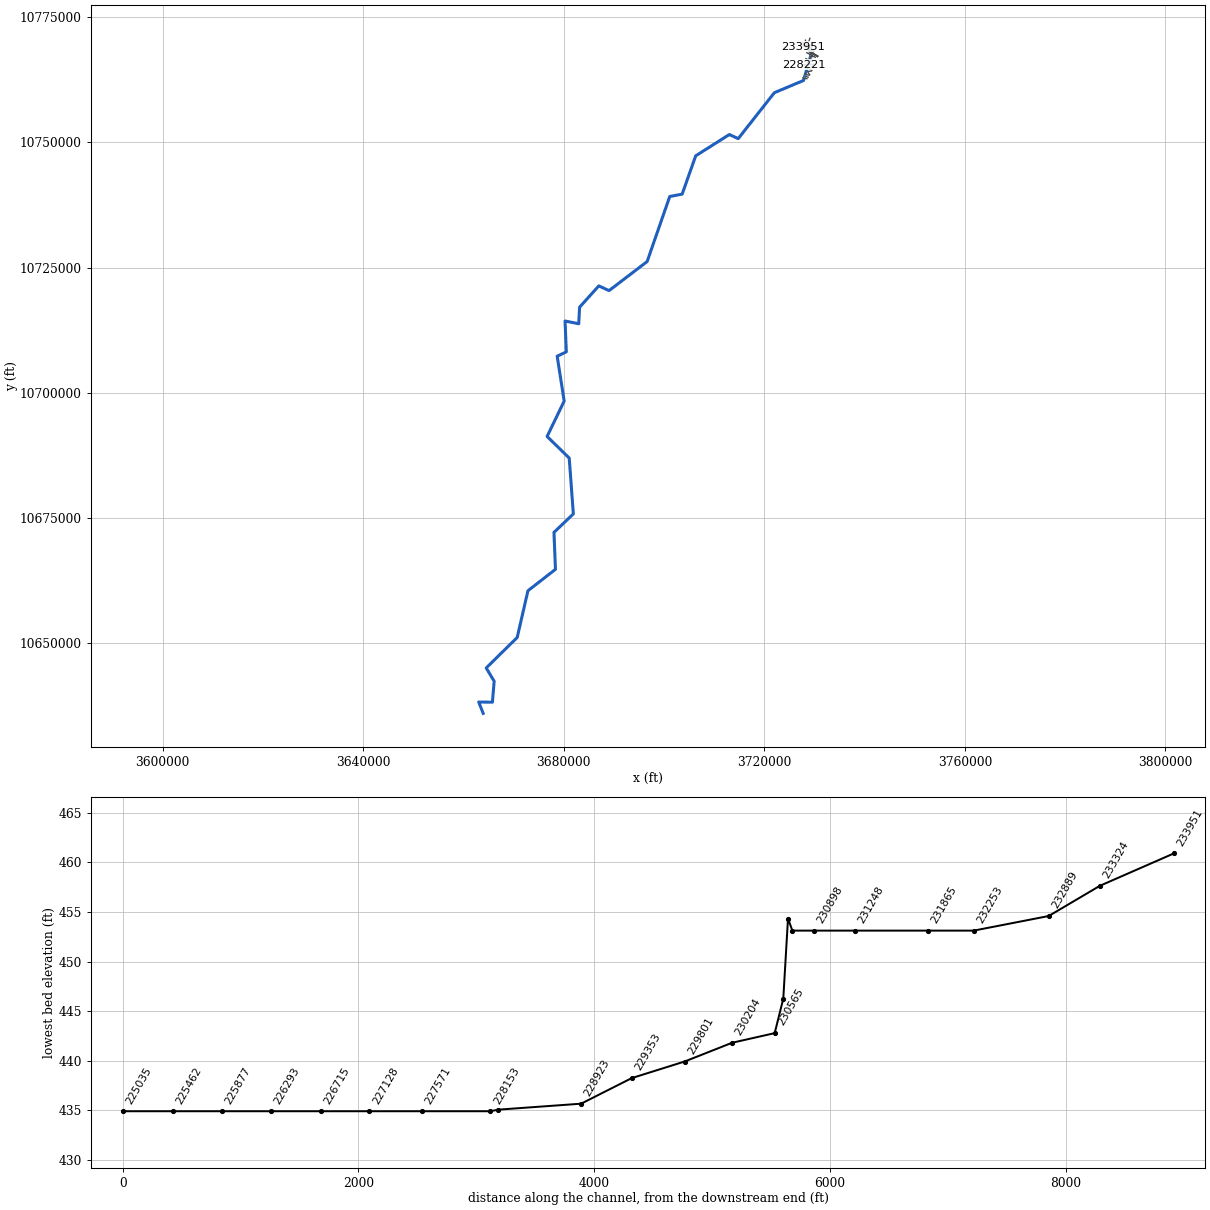
--- CATFISH CREEK.prj (project) ---

Proj Title=CATFISH CREEK Base Level Engineering
Current Plan=p01
Default Exp/Contr=0.3,0.1
English Units
Geom File=g01
Flow File=f01
Plan File=p01
Y Axis Title=Elevation
X Axis Title(PF)=Main Channel Distance
X Axis Title(XS)=Station
BEGIN DESCRIPTION:
CATFISH CREEK
END DESCRIPTION:
DSS Export Rating Curves= 0
DSS Export Rating Curve Sorted= 0
DSS Export Volume Flow Curves= 0
DXF OffsetX= 0
DXF OffsetY= 0
DXF ScaleX= 1
DXF ScaleY= 10

--- CATFISH CREEK.p01 (plan) ---

Plan Title=Multiple Run
Short Identifier=Multiple
Geom File=g01
Flow File=f01
Subcritical Flow
K Sum by GR= 0
Std Step Tol= 0.01
Critical Tol= 0.01
Num of Std Step Trials= 20
Max Error Tol= 0.3
Flow Tol Ratio= 0.001
Split Flow NTrial= 30
Split Flow Tol= 0.02
Split Flow Ratio= 0.02
Log Output Level= 0
Friction Slope Method= 1
Unsteady Friction Slope Method= 2
Unsteady Bridges Friction Slope Method= 1
Parabolic Critical Depth
Global Vel Dist=  1 , 1 , 1
Global Log Level= 0
CheckData=True
Encroach Param= -1, 0, 0, 0
BEGIN DESCRIPTION:
Multiple Run
END DESCRIPTION:

--- CATFISH CREEK.f01 (steady flow) ---

Flow Title=Multiple
Program Version=4.10
Number of Profiles= 7
Profile Names=10-year,25-year,50-year,1pct_min,100-year,1pct_plu,500-year
River Rch & RM=CATFISH CREEK,Reach-1         ,233951
     816    1123    1379    1243    1680    2273    2499
River Rch & RM=CATFISH CREEK,Reach-1         ,230204
     982    1367    1692    1535    2075    2807    3131
River Rch & RM=CATFISH CREEK,Reach-1         ,228153
    1020    1413    1742    1573    2128    2878    3181
River Rch & RM=CATFISH CREEK,Reach-1         ,222835
    1339    1889    2358    2155    2914    3941    4461
River Rch & RM=CATFISH CREEK,Reach-1         ,220815
    1744    2488    3130    2879    3893    5265    6040
River Rch & RM=CATFISH CREEK,Reach-1         ,218369
    1767    2519    3167    2911    3937    5324    6101
River Rch & RM=CATFISH CREEK,Reach-1         ,215829
    1943    2777    3497    3218    4352    5886    6761
River Rch & RM=CATFISH CREEK,Reach-1         ,212564
    1926    2745    3450    3167    4283    5793    6624
River Rch & RM=CATFISH CREEK,Reach-1         ,209345
    2625    3790    4805    4447    6014    8134    9451
River Rch & RM=CATFISH CREEK,Reach-1         ,208032
    3601    5263    6730    6277    8488   11480   13544
River Rch & RM=CATFISH CREEK,Reach-1         ,207451
    3601    5263    6730    6277    8488   11480   13544
River Rch & RM=CATFISH CREEK,Reach-1         ,203983
    4646    6838    8783    8225   11123   15043   17888
River Rch & RM=CATFISH CREEK,Reach-1         ,203251
    4646    6838    8783    8225   11123   15043   17888
River Rch & RM=CATFISH CREEK,Reach-1         ,198857
    4658    6839    8770    8198   11087   14994   17766
River Rch & RM=CATFISH CREEK,Reach-1         ,194134
    4622    6776    8682    8106   10963   14826   17529
River Rch & RM=CATFISH CREEK,Reach-1         ,191292
    4737    6949    8905    8317   11248   15211   17993
River Rch & RM=CATFISH CREEK,Reach-1         ,190671
    5276    7747    9936    9284   12556   16980   20101
River Rch & RM=CATFISH CREEK,Reach-1         ,183700
    5249    7698    9865    9208   12453   16842   19899
River Rch & RM=CATFISH CREEK,Reach-1         ,182085
    5390    7898   10115    9435   12760   17257   20358
River Rch & RM=CATFISH CREEK,Reach-1         ,181564
    5390    7898   10115    9435   12760   17257   20358
River Rch & RM=CATFISH CREEK,Reach-1         ,177844
    5478    8025   10276    9584   12961   17528   20670
River Rch & RM=CATFISH CREEK,Reach-1         ,174496
    5677    8315   10645    9925   13422   18151   21388
River Rch & RM=CATFISH CREEK,Reach-1         ,173482
    5677    8315   10645    9925   13422   18151   21388
River Rch & RM=CATFISH CREEK,Reach-1         ,170604
    5936    8698   11140   10388   14048   18998   22395
River Rch & RM=CATFISH CREEK,Reach-1         ,165153
    5973    8744   11192   10429   14104   19073   22451
River Rch & RM=CATFISH CREEK,Reach-1         ,162138
    5947    8698   11124   10358   14008   18944   22266
River Rch & RM=CATFISH CREEK,Reach-1         ,158941
    8480   12511   16104   15085   20400   27589   32811
River Rch & RM=CATFISH CREEK,Reach-1         ,153099
    8465   12476   16047   15021   20314   27472   32622
River Rch & RM=CATFISH CREEK,Reach-1         ,151249
    8459   12462   16025   14995   20279   27425   32545
River Rch & RM=CATFISH CREEK,Reach-1         ,149553
    8720   12854   16534   15478   20932   28308   33620
River Rch & RM=CATFISH CREEK,Reach-1         ,148796
    8794   12967   16683   15620   21124   28568   33940
River Rch & RM=CATFISH CREEK,Reach-1         ,145872
    8685   12779   16418   15349   20758   28073   33254
River Rch & RM=CATFISH CREEK,Reach-1         ,139904
    8644   12704   16307   15232   20599   27858   32940
River Rch & RM=CATFISH CREEK,Reach-1         ,135684
    8676   12745   16355   15272   20654   27932   33009
River Rch & RM=CATFISH CREEK,Reach-1         ,133898
    8676   12745   16355   15272   20654   27932   33009
River Rch & RM=CATFISH CREEK,Reach-1         ,129986
   14684   21657   27884   26096   35292   47728   56604
River Rch & RM=CATFISH CREEK,Reach-1         ,123003
   14536   21414   27549   25761   34839   47116   55785
River Rch & RM=CATFISH CREEK,Reach-1         ,121394
   14578   21467   27609   25811   34907   47207   55867
River Rch & RM=CATFISH CREEK,Reach-1         ,120515
   14578   21467   27609   25811   34907   47207   55867
River Rch & RM=CATFISH CREEK,Reach-1         ,119185
   14798   21765   27971   26131   35339   47792   56482
River Rch & RM=CATFISH CREEK,Reach-1         ,113634
   14704   21604   27746   25902   35029   47373   55905
River Rch & RM=CATFISH CREEK,Reach-1         ,108759
   14586   21412   27482   25640   34675   46894   55273
River Rch & RM=CATFISH CREEK,Reach-1         ,105936
   14530   21310   27333   25485   34466   46611   54870
River Rch & RM=CATFISH CREEK,Reach-1         ,103209
   14543   21320   27338   25481   34460   46603   54825
River Rch & RM=CATFISH CREEK,Reach-1         ,102597
   14543   21320   27338   25481   34460   46603   54825
River Rch & RM=CATFISH CREEK,Reach-1         ,99465
   14598   21386   27411   25539   34538   46709   54903
River Rch & RM=CATFISH CREEK,Reach-1         ,98561
   14598   21386   27411   25539   34538   46709   54903
River Rch & RM=CATFISH CREEK,Reach-1         ,96762
   14647   21456   27499   25620   34648   46857   55077
River Rch & RM=CATFISH CREEK,Reach-1         ,96106
   14647   21456   27499   25620   34648   46857   55077
River Rch & RM=CATFISH CREEK,Reach-1         ,94707
   14647   21456   27499   25620   34648   46857   55077
River Rch & RM=CATFISH CREEK,Reach-1         ,93811
   14667   21471   27507   25617   34644   46851   55024
River Rch & RM=CATFISH CREEK,Reach-1         ,89290
   14597   21349   27333   25438   34402   46525   54569
River Rch & RM=CATFISH CREEK,Reach-1         ,83657
   14751   21566   27605   25686   34738   46979   55080
River Rch & RM=CATFISH CREEK,Reach-1         ,80095
   14580   21280   27208   25287   34197   46248   54096
River Rch & RM=CATFISH CREEK,Reach-1         ,74210
   14632   21357   27307   25380   34324   46419   54299
River Rch & RM=CATFISH CREEK,Reach-1         ,71228
   14632   21357   27307   25380   34324   46419   54299
River Rch & RM=CATFISH CREEK,Reach-1         ,70895
   14473   21100   26956   25032   33853   45783   53466
River Rch & RM=CATFISH CREEK,Reach-1         ,64644
   14302   20818   26566   24642   33326   45070   52513
River Rch & RM=CATFISH CREEK,Reach-1         ,56644
   16513   24048   30714   28521   38572   52164   60911
River Rch & RM=CATFISH CREEK,Reach-1         ,54848
   16513   24048   30714   28521   38572   52164   60911
River Rch & RM=CATFISH CREEK,Reach-1         ,52040
   16500   24007   30643   28438   38459   52011   60658
River Rch & RM=CATFISH CREEK,Reach-1         ,46803
   16441   23908   30505   28298   38270   51756   60311
River Rch & RM=CATFISH CREEK,Reach-1         ,43876
   16306   23688   30204   27999   37866   51209   59593
River Rch & RM=CATFISH CREEK,Reach-1         ,32816
   16320   23697   30205   27991   37855   51194   59532
River Rch & RM=CATFISH CREEK,Reach-1         ,28738
   16227   23542   29989   27773   37560   50796   58995
Boundary for River Rch & Prof#=CATFISH CREEK,Reach-1         , 1
Up Type= 0
Dn Type= 3
Dn Slope=0.0012
Boundary for River Rch & Prof#=CATFISH CREEK,Reach-1         , 2
Up Type= 0
Dn Type= 3
Dn Slope=0.0012
Boundary for River Rch & Prof#=CATFISH CREEK,Reach-1         , 3
Up Type= 0
Dn Type= 3
Dn Slope=0.0012
Boundary for River Rch & Prof#=CATFISH CREEK,Reach-1         , 4
Up Type= 0
Dn Type= 3
Dn Slope=0.0012
Boundary for River Rch & Prof#=CATFISH CREEK,Reach-1         , 5
Up Type= 0
Dn Type= 3
Dn Slope=0.0012
Boundary for River Rch & Prof#=CATFISH CREEK,Reach-1         , 6
Up Type= 0
Dn Type= 3
Dn Slope=0.0012
Boundary for River Rch & Prof#=CATFISH CREEK,Reach-1         , 7
Up Type= 0
Dn Type= 3
Dn Slope=0.0012
DSS Import GetInterval= 0
DSS Import GetPeak= 0
DSS Import FillOption= 0

--- CATFISH CREEK.g01 (geometry) ---

Geom Title=Existing Conditions
Program Version=4.10

River Reach=CATFISH CREEK   ,Reach-1
Reach XY= 30
      3727794.08     10769479.18        3729570.       10768374.
       3727816.5       10762342.        3722002.       10759903.
      3714794.25       10750731.      3713026.75       10751554.
      3706319.25       10747302.       3703614.5       10739656.
      3701139.25       10739181.        3696632.       10726194.
      3689038.25       10720393.       3686988.5       10721334.
      3683157.75       10717077.        3682989.       10713781.
       3680262.5       10714318.       3680509.5       10708166.
      3678690.25       10707295.        3680085.       10698341.
       3676680.5       10691275.        3681092.       10686964.
       3681911.5       10675810.       3678049.5       10672120.
      3678346.25       10664742.       3672857.5       10660467.
        3670716.       10651142.      3664537.25       10645057.
        3666123.       10642400.       3665771.5       10638215.
      3663037.25       10638258.      3663934.05     10635986.57

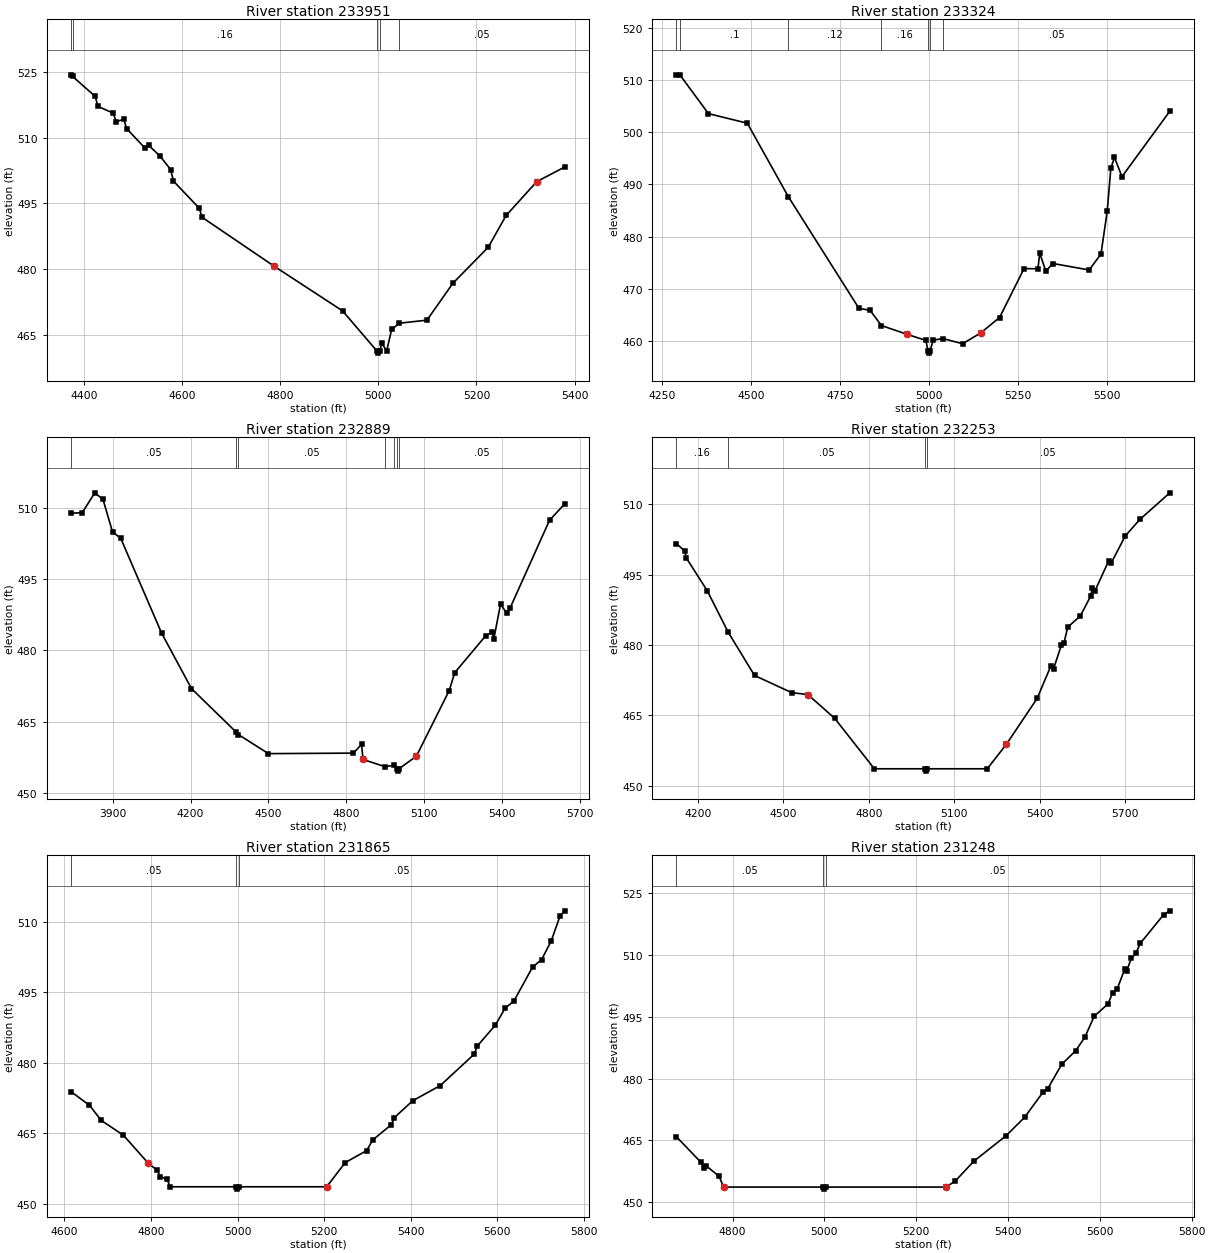
Type RM Length L Ch R = 1 ,233951  ,627,627,627
BEGIN DESCRIPTION:
CATFISH CREEK 242.0
END DESCRIPTION:
XS GIS Cut Line= 4
      3727719.17     10770015.74      3727891.03     10769726.72
      3727888.42     10769375.15       3727784.8     10769074.65
#Sta/Elev= 30
  4374.2  524.31  4376.8  523.94  4422.7  519.41  4428.5  517.12  4459.7  515.58
  4465.5  513.64  4481.1  514.17  4486.9  512.06  4523.9  507.67  4531.9  508.24
  4555.1  505.78  4576.6  502.73  4582.4  500.09    4635   493.9  4640.8  491.84
    4787  480.75    4927  470.53    4997   461.4  4999.8   460.9    5003   461.4
    5007  463.17    5017   461.4    5027  466.29  5042.7  467.72    5099  468.41
  5151.9  476.82  5223.9  485.02  5260.4  492.26  5322.8  499.97  5379.9  503.31
#Mann= 5 ,-1 , 0
  4374.2     .05       0  4376.8     .16       0    4997     .07       0
    5003     .16       0  5042.7     .05       0
Bank Sta=4787,5322.8
XS Rating Curve= 0 ,0
Exp/Cntr=0.3,0.1

Type RM Length L Ch R = 1 ,233324  ,435,435,435
BEGIN DESCRIPTION:
Mapping XS 8fde0b54
END DESCRIPTION:
XS GIS Cut Line= 3
      3728198.32     10770390.75      3728419.67     10769661.61
       3728310.3     10769047.07
#Sta/Elev= 30
  4290.2  511.02  4301.1  510.91  4380.2  503.58  4489.4  501.74  4604.9  487.62
  4802.9  466.24  4834.2  465.85  4866.3  462.93  4938.7  461.24    4991  460.08
    4997  458.14  4999.8  457.64    5003  458.14  5011.9  460.14  5038.9  460.43
  5094.3  459.44  5145.1  461.51  5198.1  464.47  5266.9  473.86  5305.9  473.81
    5311  476.82  5327.9  473.38  5348.2  474.83  5449.8  473.59    5483  476.65
  5500.6  484.88  5510.7  493.09  5520.9  495.18    5542  491.49  5676.4  504.04
#Mann= 7 ,-1 , 0
  4290.2     .05       0  4301.1      .1       0  4604.9     .12       0
  4866.3     .16       0    4997     .07       0    5003     .16       0
  5038.9     .05       0
Bank Sta=4938.7,5145.1
XS Rating Curve= 0 ,0
Exp/Cntr=0.3,0.1

Type RM Length L Ch R = 1 ,232889  ,636,636,636
BEGIN DESCRIPTION:
Mapping XS bf15db59
END DESCRIPTION:
XS GIS Cut Line= 2
      3729093.95     10770759.75      3728486.29     10768958.48
#Sta/Elev= 30
  3740.7  508.86  3782.5  508.96  3831.2  513.14  3862.7  511.76  3899.4  504.92
  3930.9  503.58  4088.5  483.62  4203.6  471.95  4373.5  462.92    4384  462.29
  4500.1  458.27  4827.3  458.38  4858.9  460.22  4864.5  457.04  4948.1  455.55
  4983.7  455.79    4997  455.09  4999.8  454.59    5003  455.09    5070  457.72
  5196.6  471.55  5217.8   475.3  5336.6  483.04  5362.8  483.83  5368.1  482.29
  5394.3  489.71  5418.3  487.82    5431  488.89  5583.1  507.37  5641.7  510.82
#Mann= 7 ,-1 , 0
  3740.7     .05       0  4373.5     .07       0    4384     .05       0
  4948.1     .16       0  4983.7     .05       0    4997     .03       0
    5003     .05       0
Bank Sta=4864.5,5070
XS Rating Curve= 0 ,0
Exp/Cntr=0.3,0.1

Type RM Length L Ch R = 1 ,232253  ,388,388,388
BEGIN DESCRIPTION:
Mapping XS 72d50cac
END DESCRIPTION:
XS GIS Cut Line= 2
      3729963.96     10769854.33      3728508.22     10768916.82
#Sta/Elev= 30
    4125  501.59    4154  500.02  4160.1   498.5  4232.8   491.6  4306.1  482.79
  4399.1   473.5  4529.2  469.85  4586.6  469.42  4680.4  464.37  4819.7  453.62
    4997  453.62  4999.8  453.12    5003  453.62  5215.8  453.62  5282.5   458.8
    5391  468.62  5439.6   475.6  5448.8  474.97  5475.9  479.94  5485.2  480.41
    5498  483.77  5542.6  486.19  5578.9  490.42  5584.9  492.09  5593.2  491.45
  5642.3  497.95  5651.5  497.54  5700.2  503.22  5751.2  506.73  5856.5  512.41
#Mann= 4 ,-1 , 0
    4125     .16       0  4306.1     .05       0    4997    .033       0
    5003     .05       0
Bank Sta=4586.6,5282.5
XS Rating Curve= 0 ,0
Exp/Cntr=0.3,0.1

Type RM Length L Ch R = 1 ,231865  ,617,617,617
BEGIN DESCRIPTION:
Mapping XS d6bfe56d
END DESCRIPTION:
XS GIS Cut Line= 3
      3729610.43     10769305.72      3729497.58      10769132.1
      3728785.81     10768528.83
#Sta/Elev= 30
  4615.9  473.79  4657.8  470.94  4684.9  467.73  4736.2  464.57  4793.6  458.64
  4814.7  457.09  4821.1  455.79  4836.8  455.22  4844.5  453.62    4997  453.62
  4999.8  453.12    5003  453.62  5205.9  453.62  5248.8  458.77  5298.2   461.3
  5312.5   463.6  5355.4  466.81  5361.9  468.29  5404.8  471.91  5468.5  475.14
  5546.5  481.78  5554.2  483.56  5595.9  488.01  5617.9  491.53  5638.8  493.13
  5681.6  500.31  5702.5   501.9  5724.5  505.82  5745.3  511.22    5756  512.27
#Mann= 3 ,-1 , 0
  4615.9     .05       0    4997    .033       0    5003     .05       0
Bank Sta=4793.6,5205.9
XS Rating Curve= 0 ,0
Exp/Cntr=0.3,0.1

Type RM Length L Ch R = 1 ,231248  ,350,350,350
BEGIN DESCRIPTION:
Mapping XS 8875f23c
END DESCRIPTION:
XS GIS Cut Line= 2
      3729881.71     10768483.41       3728816.2     10768342.35
#Sta/Elev= 30
  4677.6  465.86  4730.2  459.73  4737.7  458.24  4742.8  458.76  4770.5  456.24
  4780.6  453.62    4997  453.62  4999.8  453.12    5003  453.62  5264.8  453.62
    5285  455.08  5325.3  459.88  5395.9  466.11  5436.3   470.6  5476.6  476.74
  5486.7  477.57    5517  483.46  5547.2  486.74  5567.4  490.05  5587.6  495.11
  5617.8  498.15  5627.9  500.81    5638  501.81  5653.9  506.53  5658.9  506.25
  5668.3  509.18  5678.4  510.47  5688.4   512.9  5738.9  519.81  5752.4  520.76
#Mann= 3 ,-1 , 0
  4677.6     .05       0    4997    .033       0    5003     .05       0
Bank Sta=4780.6,5264.8
XS Rating Curve= 0 ,0
Exp/Cntr=0.3,0.1

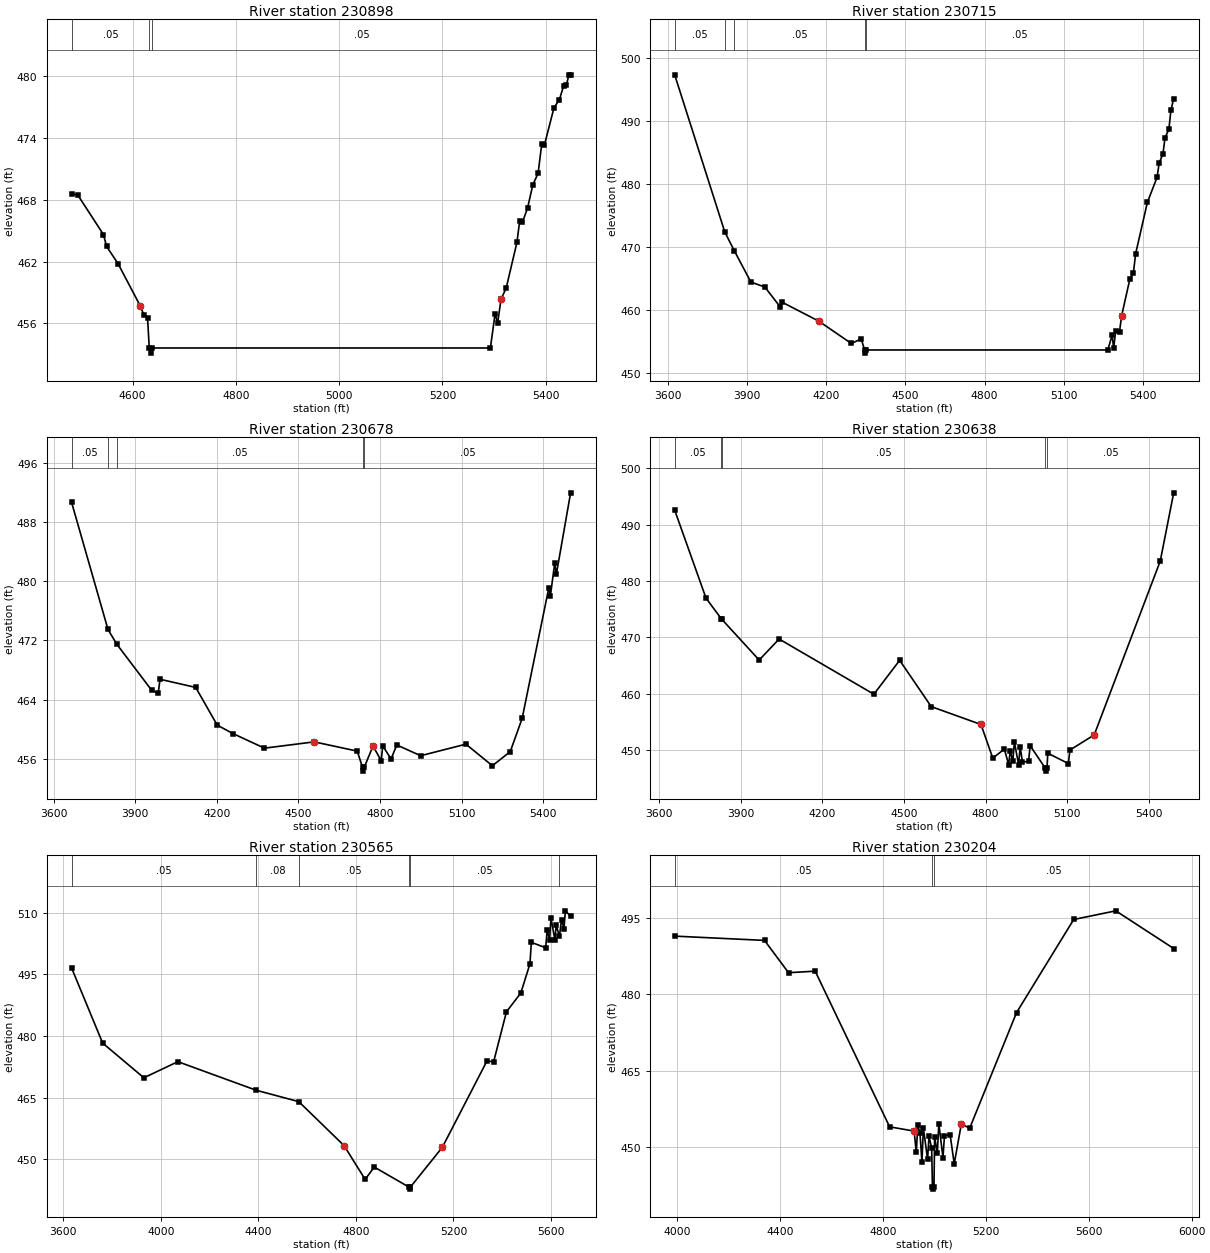
Type RM Length L Ch R = 1 ,230898  ,183,183,183
BEGIN DESCRIPTION:
Mapping XS d8ea857d
END DESCRIPTION:
XS GIS Cut Line= 3
      3729971.55     10768253.87      3729704.65     10768054.23
      3729088.37     10768197.45
#Sta/Elev= 30
  4482.1  468.57  4493.7  468.49  4543.7  464.63  4549.9  463.47  4571.9  461.81
  4614.6  457.74  4621.9  456.84  4629.1  456.54  4632.4  453.62  4635.1  453.12
  4638.4  453.62  5292.8  453.62  5301.8   456.9  5306.9  456.09  5313.4  458.33
  5323.6  459.48  5344.2  463.87  5349.5  465.96  5354.7  465.81  5364.7  467.19
    5375  469.46  5385.2  470.58  5392.1  473.37  5397.3   473.3    5416  476.95
  5426.3  477.71  5434.8  479.09  5439.9  479.15  5444.9  480.13  5448.1  480.13
#Mann= 3 ,-1 , 0
  4482.1     .05       0  4632.4    .033       0  4638.4     .05       0
Bank Sta=4614.6,5313.4
XS Rating Curve= 0 ,0
Exp/Cntr=0.3,0.1

Type RM Length L Ch R = 1 ,230715  ,37,37,37
BEGIN DESCRIPTION:
Mapping XS 23b1d2b8
END DESCRIPTION:
XS GIS Cut Line= 3
      3730686.01     10767231.73      3729550.57     10767886.26
      3729033.45     10768149.16
#Sta/Elev= 30
  3626.1  497.28    3816  472.33  3852.5  469.32  3914.8   464.4  3967.9   463.6
  4025.9  460.45  4032.6  461.21  4171.9   458.2  4295.5  454.65  4332.8  455.38
  4345.6  453.62  4348.4  453.12  4351.6  453.62    5267  453.62  5283.6  455.96
  5289.3  453.87  5296.7  456.58  5311.5  456.47  5319.2  458.99  5350.4  464.81
  5364.1  465.87  5372.7  468.91  5417.2  477.06  5453.8  481.01  5461.7  483.27
  5476.2  484.75  5483.9  487.26  5498.7  488.67  5506.2  491.64  5516.8  493.52
#Mann= 5 ,-1 , 0
  3626.1     .05       0    3816     .08       0  3852.5     .05       0
  4345.6    .035       0  4351.6     .05       0
Bank Sta=4171.9,5319.2
XS Rating Curve= 0 ,0
Exp/Cntr=0.3,0.1

Type RM Length L Ch R = 1 ,230678  ,40,40,40
BEGIN DESCRIPTION:
Mapping XS 8e206fb9
END DESCRIPTION:
XS GIS Cut Line= 4
      3730609.99     10767173.18      3729726.78      10767722.2
      3729446.84     10767902.32      3729040.98     10768121.53
#Sta/Elev= 30
  3666.5  490.61  3800.2  473.46    3832   471.5  3961.3  465.23  3984.9  464.86
  3991.5  466.74  4122.6  465.64  4201.7  460.55  4259.5  459.41  4375.2  457.44
  4558.2  458.29  4716.4  457.04  4735.8  454.84  4738.5  454.34  4741.8  454.84
  4774.4  457.73  4804.3  455.75  4810.2  457.75  4840.6  455.98  4861.7  457.87
  4949.5  456.42  5115.7  457.98    5213  455.07  5278.7  456.97  5322.5  461.46
  5420.5  479.09  5426.2  477.98  5442.4  482.48  5448.1  480.89  5500.6  491.91
#Mann= 5 ,-1 , 0
  3666.5     .05       0  3800.2     .08       0    3832     .05       0
  4735.8     .03       0  4741.8     .05       0
Bank Sta=4558.2,4774.4
XS Rating Curve= 0 ,0
Exp/Cntr=0.3,0.1

Type RM Length L Ch R = 1 ,230638  ,73,73,73
BEGIN DESCRIPTION:
Mapping XS 7b535d31
END DESCRIPTION:
XS GIS Cut Line= 3
      3730609.62     10767143.19      3729472.44     10767839.82
       3729033.3     10768079.95
#Sta/Elev= 30
  3657.3  492.58  3772.4  476.97  3829.3  473.26  3829.5  473.26  3967.8  465.98
  4041.2  469.71  4389.4  459.91  4484.2  465.93  4600.3  457.71  4783.1  454.54
  4826.5  448.56  4869.1  450.18  4884.6  447.42  4890.4  449.75    4900  448.09
  4905.9  451.42  4921.3  447.43  4927.2  450.54  4935.6  447.85    4958  448.02
  4963.9  450.76  5019.8  446.76  5022.5  446.26  5025.8  446.76  5028.5  449.44
  5104.3  447.61    5110     450  5199.3  452.69  5442.1  483.56  5491.4  495.66
#Mann= 5 ,-1 , 0
  3657.3     .05       0  3829.3     .08       0  3829.5     .05       0
  5019.8     .03       0  5025.8     .05       0
Bank Sta=4783.1,5199.3
XS Rating Curve= 0 ,0
Exp/Cntr=0.3,0.1

Type RM Length L Ch R = 1 ,230565  ,361,361,361
BEGIN DESCRIPTION:
CATFISH CREEK 241.0
END DESCRIPTION:
XS GIS Cut Line= 2
      3730619.95     10767096.79      3728846.11     10768115.99
#Sta/Elev= 30
  3634.8  496.57  3762.1  478.31    3931  469.87  4070.4  473.79    4391  466.85
  4566.1  464.07  4751.9  453.37  4838.2  445.15  4875.5  448.16  5017.8  443.29
  5020.5  442.79  5023.8  443.29  5154.5  452.94    5337  473.89  5365.2  473.82
  5417.6  485.93  5476.5  490.49  5513.9   497.6  5519.6  502.82  5578.6  501.49
  5584.3  505.84  5594.4  503.42  5600.1  508.76  5615.9  503.48  5621.7  506.94
  5634.9  504.29  5643.3  508.37  5653.3  506.13  5659.1  510.48  5680.6  509.17
#Mann= 6 ,-1 , 0
  3634.8     .05       0    4391     .08       0  4566.1     .05       0
  5017.8     .03       0  5023.8     .05       0  5634.9     .08       0
Bank Sta=4751.9,5154.5
XS Rating Curve= 0 ,0
Exp/Cntr=0.3,0.1

Type RM Length L Ch R = 1 ,230204  ,403,403,403
BEGIN DESCRIPTION:
CATFISH CREEK 240.0
END DESCRIPTION:
XS GIS Cut Line= 2
      3730177.23     10766966.59      3728473.04     10767890.24
#Sta/Elev= 30
  3991.8  491.42  4340.8  490.58    4434  484.25  4537.6  484.55  4826.7  454.03
  4921.8   453.2  4930.4  449.05    4936  454.35  4944.5  452.86  4952.2  447.18
  4957.9  453.81  4974.1  447.68  4979.8  452.18    4990  449.84    4993  442.32
  4995.7  441.82    4999  442.32  5001.6  452.08  5012.1  448.89  5017.8  454.63
    5034     448  5039.7  452.27  5061.6  452.51  5077.7  446.79  5105.3  454.59
  5137.7  453.76  5319.9  476.44  5541.8  494.68  5705.3  496.38  5930.2  488.99
#Mann= 3 ,-1 , 0
  3991.8     .05       0    4993     .03       0    4999     .05       0
Bank Sta=4921.8,5105.3
XS Rating Curve= 0 ,0
Exp/Cntr=0.3,0.1

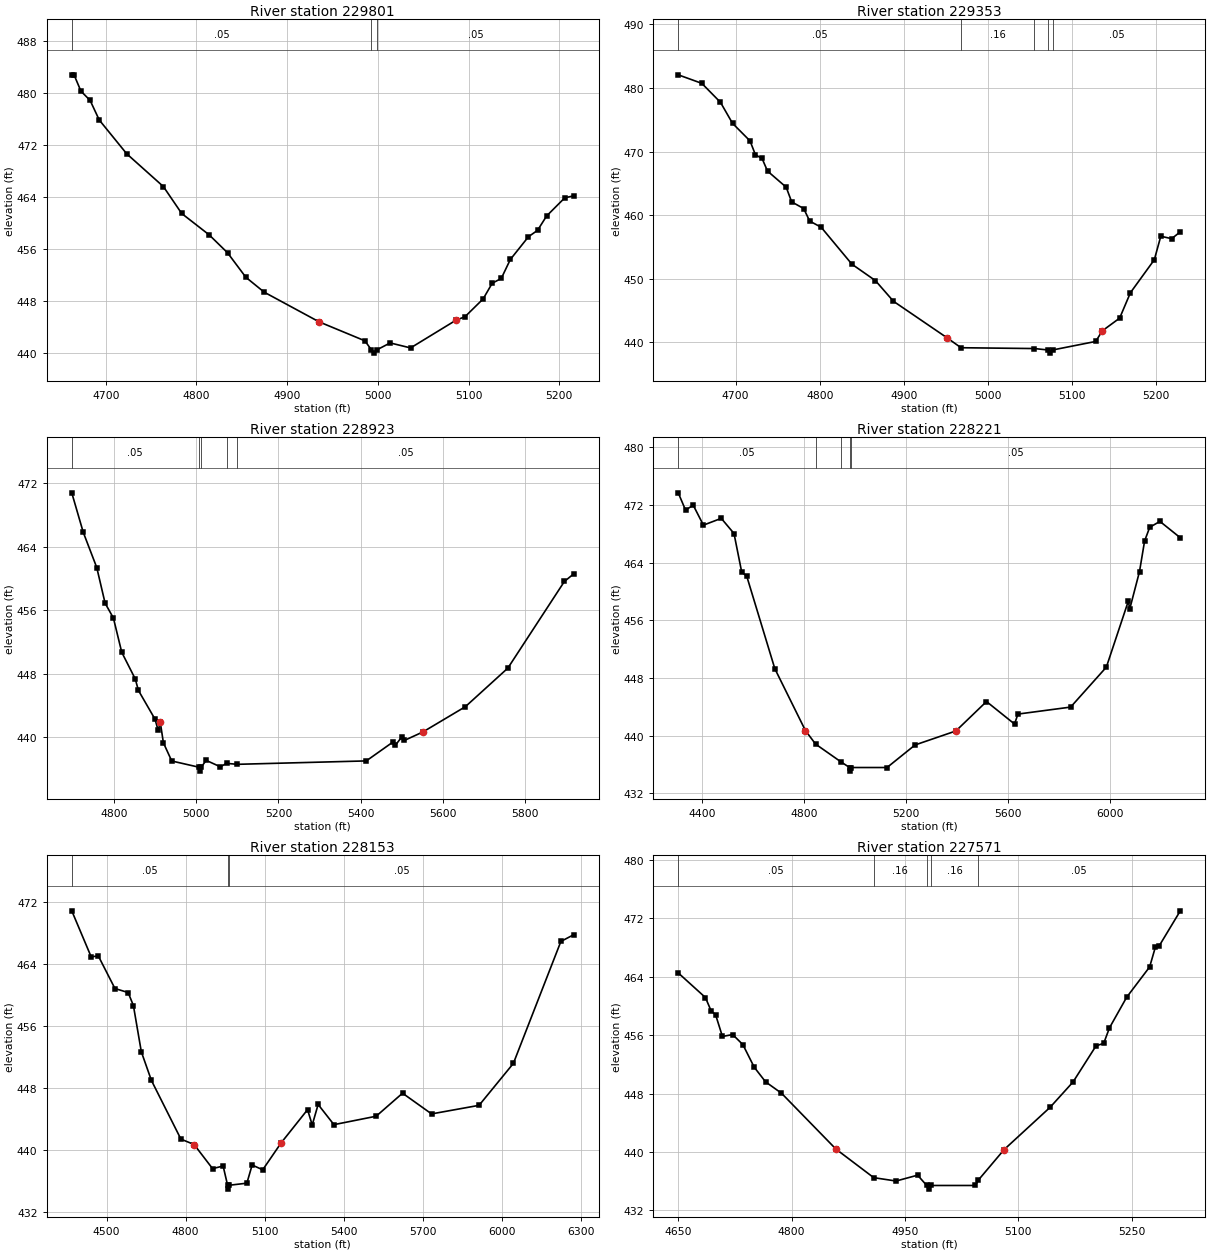
Type RM Length L Ch R = 1 ,229801  ,448,448,448
BEGIN DESCRIPTION:
CATFISH CREEK 239.0
END DESCRIPTION:
XS GIS Cut Line= 3
      3729649.59     10767110.19      3729299.61     10767060.19
      3729099.64     10767060.19
#Sta/Elev= 30
  4662.5  482.74    4665  482.74  4672.6  480.23  4682.7  478.81  4692.8  475.79
  4723.1  470.59  4763.5  465.55  4783.7  461.41    4814  458.12  4834.2  455.37
  4854.4   451.6  4874.6  449.31  4935.2  444.74  4985.7  441.82  4992.8  440.43
  4995.6  439.93  4998.8  440.43  5013.5   441.5    5036  440.73    5086  444.99
    5096  445.53    5116  448.27    5126  450.68    5136  451.42    5146  454.34
    5166  457.84    5176  458.82    5186  461.03    5206  463.82    5216  464.13
#Mann= 3 ,-1 , 0
  4662.5     .05       0  4992.8     .03       0  4998.8     .05       0
Bank Sta=4935.2,5086
XS Rating Curve= 0 ,0
Exp/Cntr=0.3,0.1

Type RM Length L Ch R = 1 ,229353  ,430,430,430
BEGIN DESCRIPTION:
CATFISH CREEK 238.0
END DESCRIPTION:
XS GIS Cut Line= 3
      3729549.64     10766410.16      3729249.61     10766660.19
      3729049.61     10766710.19
#Sta/Elev= 30
  4631.8  482.07  4659.8  480.73    4682  477.74  4696.3  474.44  4717.1  471.67
  4723.6  469.47  4731.4  468.91  4737.9  466.92  4760.1  464.38  4766.6  462.07
  4780.9  461.02    4788  459.05  4801.7  458.07  4838.2  452.26  4866.1  449.68
  4887.6  446.42  4951.4  440.66  4967.9  439.11  5055.2  438.98  5070.9  438.76
  5073.6  438.26  5076.9  438.76    5128   440.1  5135.7  441.76  5156.4  443.77
  5169.2  447.77  5197.6  452.96  5205.3  456.66  5218.2  456.28  5228.5  457.35
#Mann= 5 ,-1 , 0
  4631.8     .05       0  4967.9     .16       0  5055.2     .05       0
  5070.9     .07       0  5076.9     .05       0
Bank Sta=4951.4,5135.7
XS Rating Curve= 0 ,0
Exp/Cntr=0.3,0.1

Type RM Length L Ch R = 1 ,228923  ,702,702,702
BEGIN DESCRIPTION:
CATFISH CREEK 237.0
END DESCRIPTION:
XS GIS Cut Line= 3
      3729399.58     10766210.19      3729099.61     10766260.19
       3728299.6     10766710.19
#Sta/Elev= 30
    4697  470.82  4724.9  465.84  4757.8  461.39  4778.1  456.89  4798.4     455
  4818.6  450.69  4851.6  447.31  4859.2  445.87  4899.7  442.23  4907.3  440.81
  4912.4  441.86    4920  439.26  4940.3  436.96  5006.1  436.18  5008.8  435.68
  5012.1  436.18  5024.1  437.04  5058.5  436.23  5073.8  436.66    5100  436.54
  5413.8  436.97  5478.9  439.36  5484.6  438.95  5500.5  440.01  5506.3  439.55
  5551.8  440.63  5655.1  443.82  5758.4  448.69    5896  459.63    5919   460.6
#Mann= 5 ,-1 , 0
    4697     .05       0  5006.1    .035       0  5012.1     .05       0
  5073.8     .16       0    5100     .05       0
Bank Sta=4912.4,5551.8
XS Rating Curve= 0 ,0
Exp/Cntr=0.3,0.1

Type RM Length L Ch R = 1 ,228221  ,68,68,68
BEGIN DESCRIPTION:
CATFISH CREEK 236.0
END DESCRIPTION:
XS GIS Cut Line= 2
      3729778.32     10765596.19      3727809.59     10765505.91
#Sta/Elev= 30
    4306  473.67  4334.7  471.27  4364.8  471.96  4404.8  469.19  4474.9  470.13
  4524.9  468.03    4555   462.7    4575   462.1  4685.1  449.29  4805.2  440.71
  4845.1  438.83  4944.1  436.38  4978.6  435.58  4981.4  435.08  4984.6  435.58
  5125.6  435.58  5235.7  438.71  5395.9  440.65    5516  444.73  5626.1  441.61
  5639.4  442.99  5846.3  443.96  5986.5   449.5    6073  458.68    6078  457.53
  6116.6  462.75  6136.6  466.99  6156.7  468.89  6196.7  469.71  6276.8  467.44
#Mann= 5 ,-1 , 0
    4306     .05       0  4845.1     .08       0  4944.1     .05       0
  4978.6     .04       0  4984.6     .05       0
Bank Sta=4805.2,5395.9
XS Rating Curve= 0 ,0
Exp/Cntr=0.3,0.1

Type RM Length L Ch R = 1 ,228153  ,582,582,582
BEGIN DESCRIPTION:
CATFISH CREEK 235.0
END DESCRIPTION:
XS GIS Cut Line= 2
      3729733.23     10765530.22      3727830.44     10765436.47
#Sta/Elev= 30
  4367.8  470.92  4441.5  464.96  4468.3   465.1  4531.6  460.87  4581.7  460.35
  4601.7  458.66  4631.7  452.69    4670  448.98  4781.9  441.39    4832  440.69
  4902.1  437.57  4942.1  437.91  4959.1  435.42  4961.9  434.92  4965.1  435.42
  5032.2  435.69  5052.2  438.04  5092.3  437.42  5162.4  440.91  5262.5   445.2
  5280.2  443.22  5302.6  445.87  5362.6  443.26  5522.8  444.35  5622.9  447.33
  5733.1  444.65  5913.3  445.76  6043.4  451.18  6223.7  466.96  6272.9  467.84
#Mann= 3 ,-1 , 0
  4367.8     .05       0  4959.1     .03       0  4965.1     .05       0
Bank Sta=4832,5162.4
XS Rating Curve= 0 ,0
Exp/Cntr=0.3,0.1

Type RM Length L Ch R = 1 ,227571  ,443,443,443
BEGIN DESCRIPTION:
CATFISH CREEK 234.0
END DESCRIPTION:
XS GIS Cut Line= 3
      3729599.57     10765160.17      3729299.61     10764960.19
      3728999.56     10764910.18
#Sta/Elev= 30
  4649.9  464.52  4685.9  461.15  4693.4  459.33  4699.4  458.78  4708.4  455.82
    4722  456.08  4735.5   454.7  4750.5  451.61  4765.5  449.61  4786.6  448.05
  4858.7   440.4  4908.7  436.49  4938.3  436.03  4966.8  436.83  4978.9  435.42
  4981.6  434.92  4984.9  435.42  5043.4  435.42    5047  436.13  5081.4  440.34
  5142.2  446.12  5172.6  449.59    5203  454.53  5213.2  454.88  5220.8     457
  5243.6  461.19    5274  465.34  5281.6  468.06  5286.7  468.23  5314.6  473.02
#Mann= 5 ,-1 , 0
  4649.9     .05       0  4908.7     .16       0  4978.9     .07       0
  4984.9     .16       0    5047     .05       0
Bank Sta=4858.7,5081.4
XS Rating Curve= 0 ,0
Exp/Cntr=0.3,0.1

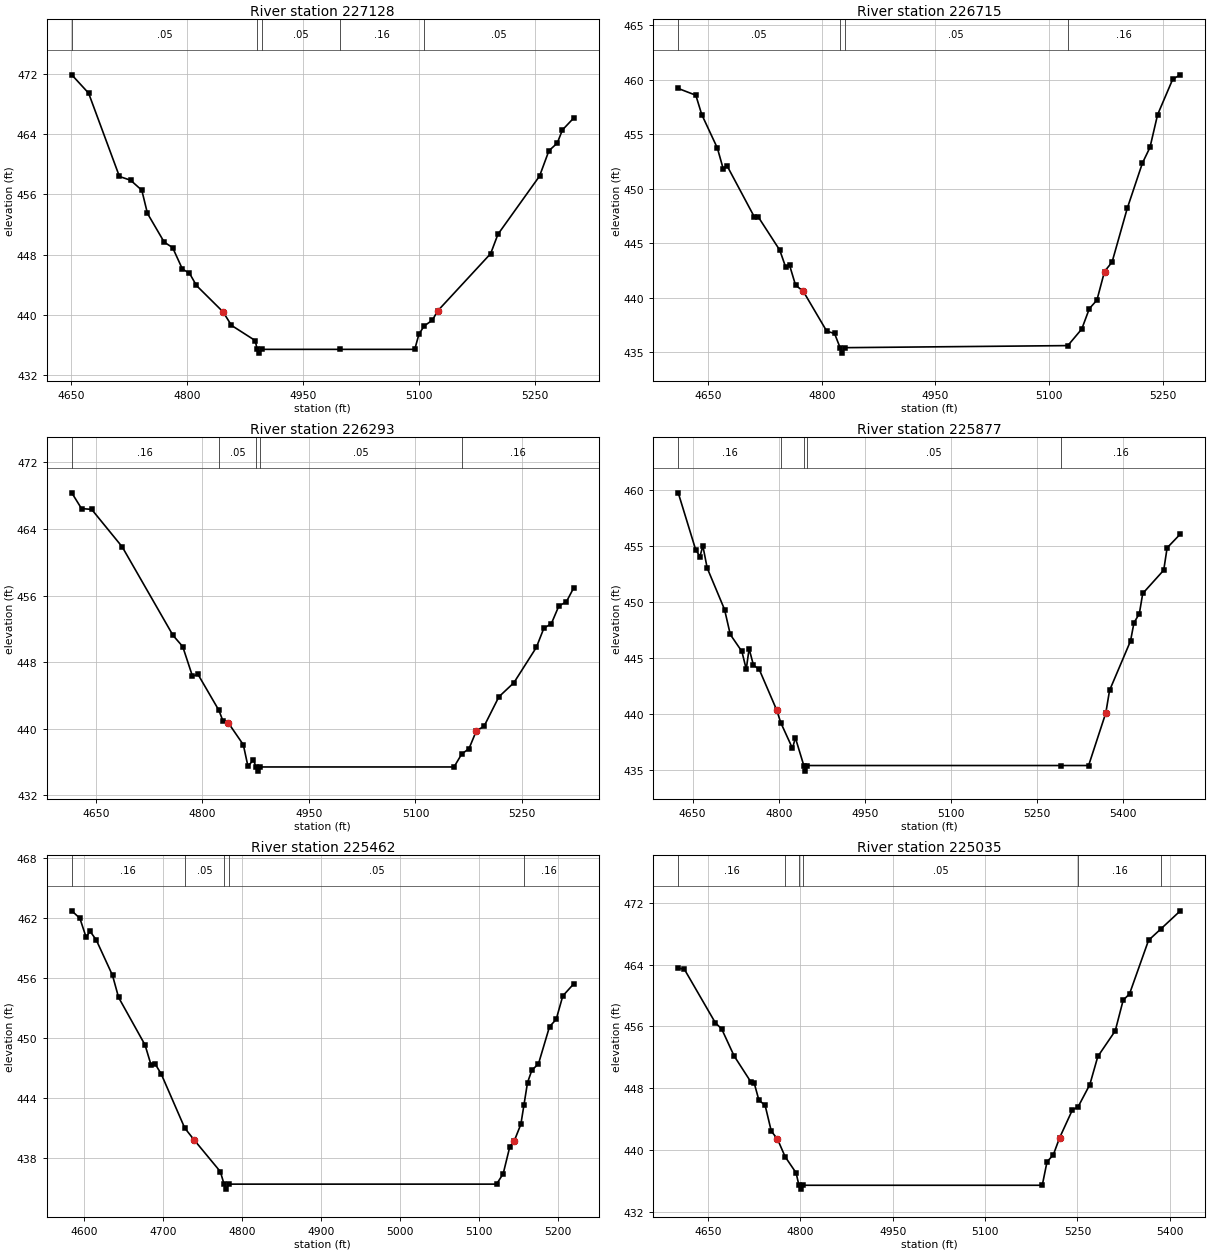
Type RM Length L Ch R = 1 ,227128  ,413,413,413
BEGIN DESCRIPTION:
CATFISH CREEK 233.0
END DESCRIPTION:
XS GIS Cut Line= 3
      3729499.65     10764410.17      3729149.61     10764560.19
       3728899.6     10764660.19
#Sta/Elev= 30
  4650.8  471.83  4672.6   469.4  4712.5  458.35    4727  457.85  4741.5  456.52
  4748.8  453.45  4770.5  449.64  4781.4  448.91  4794.1  446.06  4803.2  445.52
  4812.2  443.89  4846.7  440.39  4857.6   438.6  4888.4  436.58  4890.8  435.42
  4893.6  434.92  4896.8  435.42  4998.4  435.42  5094.9  435.42  5100.3  437.43
    5107  438.51  5117.8   439.3  5124.5  440.51  5193.2  448.12  5202.6  450.68
  5256.5   458.4  5268.6  461.76  5279.4  462.77  5286.1  464.52  5300.9  466.12
#Mann= 5 ,-1 , 0
  4650.8     .05       0  4890.8     .07       0  4896.8     .05       0
  4998.4     .16       0    5107     .05       0
Bank Sta=4846.7,5124.5
XS Rating Curve= 0 ,0
Exp/Cntr=0.3,0.1

Type RM Length L Ch R = 1 ,226715  ,422,422,422
BEGIN DESCRIPTION:
CATFISH CREEK 232.0
END DESCRIPTION:
XS GIS Cut Line= 3
      3729399.65      10764260.2      3728999.61     10764160.19
      3728749.66     10764160.19
#Sta/Elev= 30
  4610.7  459.18  4633.9  458.56  4641.7  456.79  4662.3  453.72    4670  451.82
  4675.2  452.08  4711.2  447.39  4716.4  447.39  4744.7  444.35  4752.5  442.78
  4757.6  442.97  4765.4  441.16  4775.7  440.58  4806.6  436.93  4816.9  436.72
  4824.2  435.42    4827  434.92  4830.2  435.42  5124.6  435.61    5143  437.13
    5153     439    5163  439.78    5173   442.4    5183  443.27    5203  448.19
    5223  452.34    5233  453.78    5243  456.77    5263  460.03    5273  460.43
#Mann= 4 ,-1 , 0
  4610.7     .05       0  4824.2    .033       0  4830.2     .05       0
  5124.6     .16       0
Bank Sta=4775.7,5173
XS Rating Curve= 0 ,0
Exp/Cntr=0.3,0.1

Type RM Length L Ch R = 1 ,226293  ,416,416,416
BEGIN DESCRIPTION:
CATFISH CREEK 231.0
END DESCRIPTION:
XS GIS Cut Line= 3
      3729049.62     10763510.18      3728799.61     10763810.19
      3728699.59     10764110.24
#Sta/Elev= 30
  4616.2  468.35  4629.9  466.46  4644.2  466.36  4687.2  461.86  4758.7  451.23
  4772.4  449.88  4786.1  446.33  4793.9  446.54  4823.4  442.21    4829  440.95
  4836.8  440.69  4857.7  438.09  4864.2  435.51    4872  436.27  4875.5  435.42
  4878.3  434.92  4881.5  435.42  5154.3  435.42  5165.2  436.98  5175.4  437.62
  5185.9  439.79  5196.5  440.29  5217.5  443.85  5238.6  445.54  5270.2  449.78
  5280.8  452.09  5291.3  452.63  5301.9  454.76  5312.4  455.25    5323  456.96
#Mann= 5 ,-1 , 0
  4616.2     .16       0  4823.4     .05       0  4875.5    .033       0
  4881.5     .05       0  5165.2     .16       0
Bank Sta=4836.8,5185.9
XS Rating Curve= 0 ,0
Exp/Cntr=0.3,0.1

Type RM Length L Ch R = 1 ,225877  ,415,415,415
BEGIN DESCRIPTION:
CATFISH CREEK 230.0
END DESCRIPTION:
XS GIS Cut Line= 3
      3728949.65     10763410.18      3728549.61     10763460.19
      3728149.57     10763710.21
#Sta/Elev= 30
  4624.9  459.75  4655.2  454.69  4662.7  454.06  4667.8  455.02  4675.3  453.05
  4705.6  449.34  4715.6  447.11  4735.8   445.6  4743.4  444.01  4748.4  445.84
    4756  444.37    4766     444  4796.3  440.39  4803.6  439.24    4824  436.95
    4829   437.9  4843.7  435.42  4846.4  434.92  4849.7  435.42  5292.1  435.42
    5340  435.42    5370  440.12  5376.5  442.12  5413.1  446.54    5419  448.15
  5428.4  448.97  5434.3  450.77  5470.9  452.85  5476.8  454.84  5499.8  456.07
#Mann= 5 ,-1 , 0
  4624.9     .16       0  4803.6     .05       0  4843.7    .033       0
  4849.7     .05       0  5292.1     .16       0
Bank Sta=4796.3,5370
XS Rating Curve= 0 ,0
Exp/Cntr=0.3,0.1

Type RM Length L Ch R = 1 ,225462  ,427,427,427
BEGIN DESCRIPTION:
CATFISH CREEK 229.0
END DESCRIPTION:
XS GIS Cut Line= 3
      3728749.64     10763010.18      3728349.61     10763110.19
      3728149.57     10763210.21
#Sta/Elev= 30
  4584.5  462.75  4594.8     462  4602.6  460.12  4607.7   460.7  4615.5  459.84
  4636.1   456.3  4643.8  454.09  4677.3  449.34    4685  447.32  4690.2  447.43
  4697.9  446.42  4727.6  441.03  4739.2  439.87  4772.7  436.67  4777.4  435.42
  4780.1  434.92  4783.4  435.42  5122.6  435.42    5131  436.46  5139.4  439.17
    5145  439.74  5153.4  441.41  5157.3  443.34  5161.8  445.57  5167.3  446.81
  5175.7  447.45  5189.7  451.17  5198.1  451.89  5206.5  454.24  5220.5  455.46
#Mann= 5 ,-1 , 0
  4584.5     .16       0  4727.6     .05       0  4777.4    .033       0
  4783.4     .05       0  5157.3     .16       0
Bank Sta=4739.2,5145
XS Rating Curve= 0 ,0
Exp/Cntr=0.3,0.1

Type RM Length L Ch R = 1 ,225035  ,431,431,431
BEGIN DESCRIPTION:
CATFISH CREEK 228.0
END DESCRIPTION:
XS GIS Cut Line= 3
      3728499.57     10762710.19      3728099.61     10762760.19
       3727699.6     10762860.19
#Sta/Elev= 30
  4601.6  463.58  4611.6  463.41    4662  456.46  4672.1  455.69  4692.3  452.19
    4720  448.76    4725  448.66  4732.6  446.45  4742.7  445.78  4752.7  442.44
  4762.8   441.4  4775.2  439.12    4793  437.03  4797.6  435.42  4800.4  434.92
  4803.6  435.42  5192.8  435.42  5200.5  438.45  5210.8  439.38  5221.1   441.6
  5241.8   445.2  5250.9  445.57  5270.1  448.48    5283  452.11  5311.3  455.43
  5324.2  459.41  5334.5  460.22  5365.4  467.17  5385.5  468.65    5417  470.99
#Mann= 6 ,-1 , 0
  4601.6     .16       0  4775.2     .05       0  4797.6    .033       0
  4803.6     .05       0  5250.9     .16       0  5385.5     .05       0
Bank Sta=4762.8,5221.1
XS Rating Curve= 0 ,0
Exp/Cntr=0.3,0.1