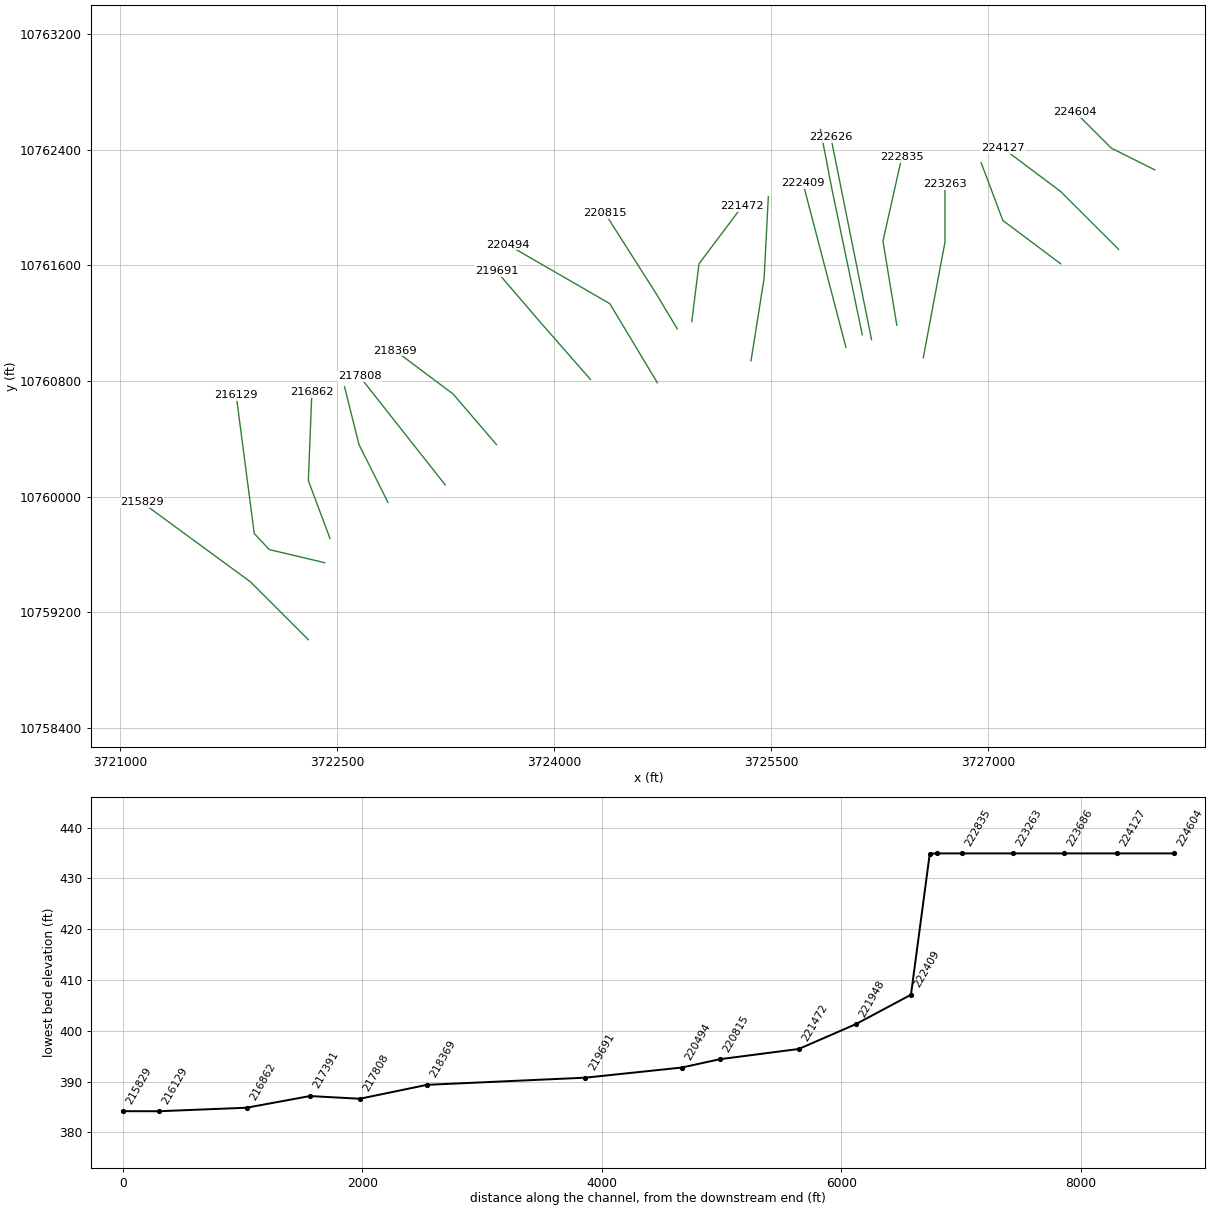
HEC-RAS study CATFISH CREEK.prj: CATFISH CREEK Base Level Engineering

--- CATFISH CREEK.g01 (geometry) --- (continued)

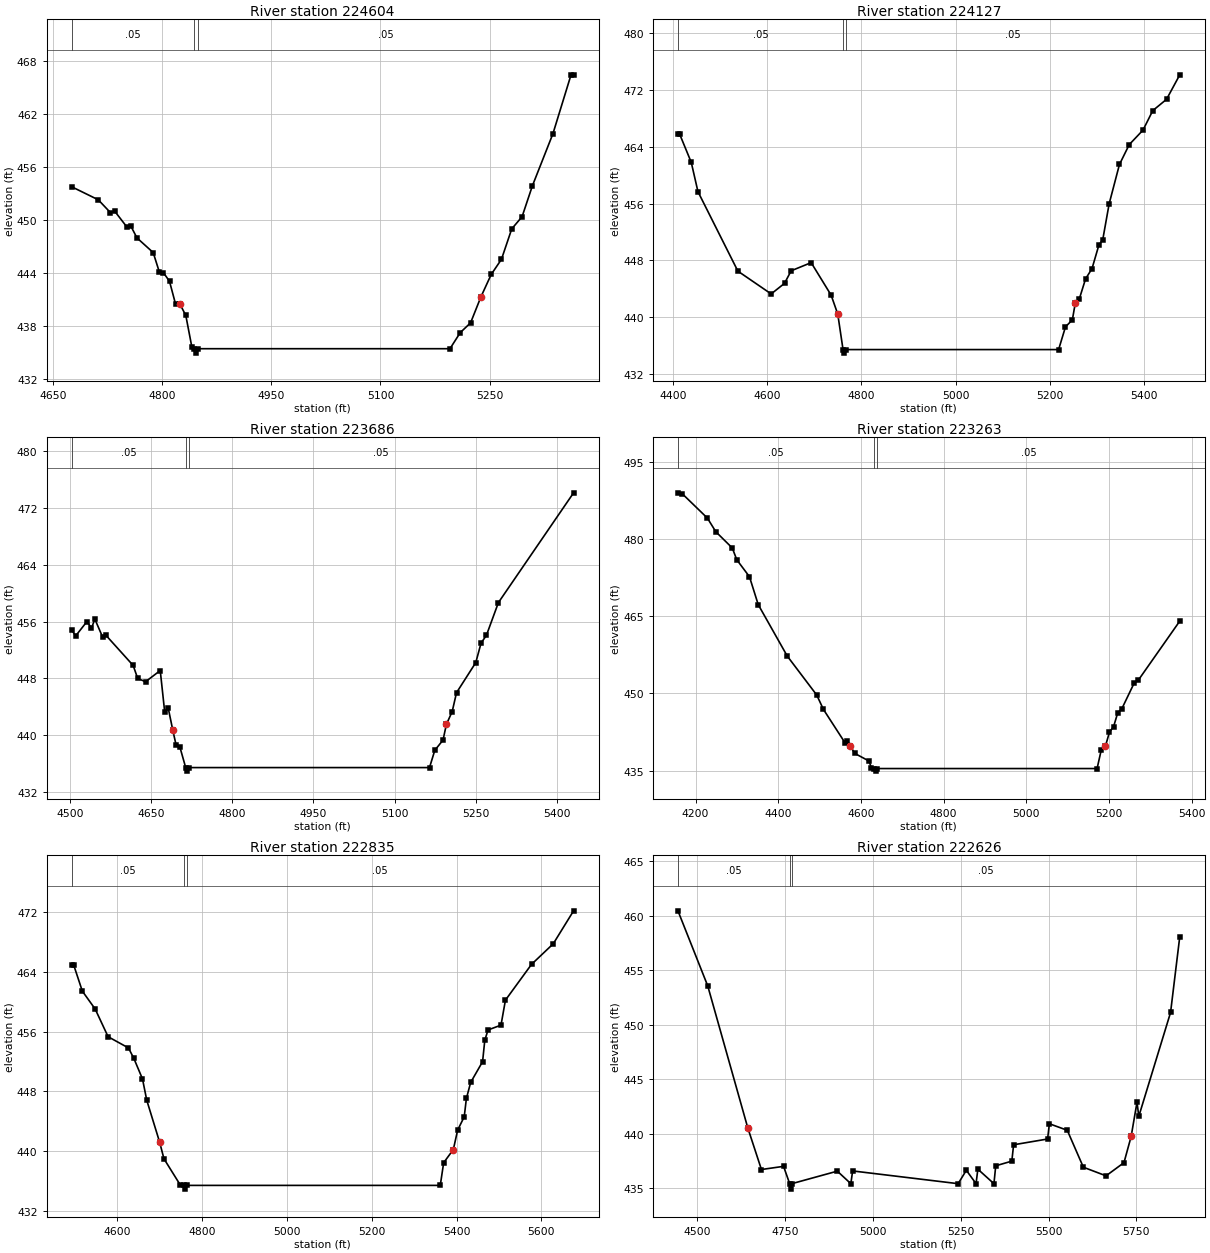
Type RM Length L Ch R = 1 ,224604  ,477,477,477
BEGIN DESCRIPTION:
CATFISH CREEK 227.0
END DESCRIPTION:
XS GIS Cut Line= 3
      3728149.63     10762260.18      3727849.61     10762410.19
       3727599.6     10762660.19
#Sta/Elev= 30
  4676.1  453.74  4712.5  452.27  4729.2  450.82  4734.8  451.01  4751.6  449.21
  4757.2   449.3  4765.6  447.96  4787.9   446.3  4796.3  444.11  4801.9  444.03
  4810.3  443.05  4818.7  440.44  4824.3  440.52  4832.7  439.18    4841  435.61
  4843.6  435.42  4846.4  434.92  4849.6  435.42  5195.4  435.42  5209.5  437.24
  5223.7  438.35  5237.8  441.27    5252  443.82  5266.1  445.54  5280.2  448.98
  5294.4  450.36  5308.5  453.84  5336.8  459.76  5361.6  466.41  5365.1  466.41
#Mann= 3 ,-1 , 0
  4676.1     .05       0  4843.6    .033       0  4849.6     .05       0
Bank Sta=4824.3,5237.8
XS Rating Curve= 0 ,0
Exp/Cntr=0.3,0.1

Type RM Length L Ch R = 1 ,224127  ,441,441,441
BEGIN DESCRIPTION:
CATFISH CREEK 226.0
END DESCRIPTION:
XS GIS Cut Line= 3
      3727899.63     10761710.17      3727499.61     10762110.19
      3727099.62     10762410.18
#Sta/Elev= 30
  4410.5  465.78  4414.1  465.78  4438.8  461.79    4453  457.67  4537.8  446.47
  4608.5  443.26  4636.8  444.75  4650.9  446.52  4693.4  447.67  4735.8  443.09
  4749.9  440.42  4761.1  435.42  4763.8  434.92  4767.1  435.42  5218.9  435.42
  5233.5  438.62  5248.1  439.61  5254.3  441.96  5262.7  442.52  5276.2  445.39
  5289.8  446.82  5304.3  450.12  5312.7  450.92  5326.2  455.95  5348.1   461.5
  5368.9   464.3  5398.1  466.34  5418.9  469.09  5448.1  470.68  5476.2  474.13
#Mann= 3 ,-1 , 0
  4410.5     .05       0  4761.1    .033       0  4767.1     .05       0
Bank Sta=4749.9,5254.3
XS Rating Curve= 0 ,0
Exp/Cntr=0.3,0.1

Type RM Length L Ch R = 1 ,223686  ,423,423,423
BEGIN DESCRIPTION:
CATFISH CREEK 225.0
END DESCRIPTION:
XS GIS Cut Line= 3
      3727499.57     10761610.22      3727099.61     10761910.19
      3726949.59     10762310.23
#Sta/Elev= 30
  4503.5  454.82  4510.7  453.99  4531.6  456.02  4539.9  455.08  4546.2  456.36
  4560.7  453.79    4567  454.05    4617  449.82  4625.3  447.99  4639.9  447.53
    4667  449.11  4675.3   443.2  4681.6  443.87  4689.9  440.79  4696.2  438.63
  4703.5  438.26    4714  435.42  4716.7  434.92    4720  435.42  5164.5  435.42
  5174.3  437.86  5189.5   439.3  5195.7  441.52  5206.4  443.32  5214.4  445.98
    5250  450.23  5259.8  452.99  5269.6  454.06  5291.8  458.69  5430.7  474.17
#Mann= 3 ,-1 , 0
  4503.5     .05       0    4714    .033       0    4720     .05       0
Bank Sta=4689.9,5195.7
XS Rating Curve= 0 ,0
Exp/Cntr=0.3,0.1

Type RM Length L Ch R = 1 ,223263  ,428,428,428
BEGIN DESCRIPTION:
CATFISH CREEK 224.0
END DESCRIPTION:
XS GIS Cut Line= 3
      3726549.61     10760960.19      3726699.61     10761760.19
      3726699.61     10762160.15
#Sta/Elev= 30
  4157.4  488.93  4167.6  488.77  4228.6  484.03    4249  481.38  4288.8  478.23
  4299.8  475.93  4330.4  472.65  4351.6  467.23  4421.9  457.24  4493.1  449.69
  4509.3   446.9  4561.8  440.39  4566.9  440.77  4574.5  439.82  4584.7  438.38
  4619.5  436.88  4625.4  435.55  4632.6  435.42  4635.3  434.92  4638.6  435.42
  5171.3  435.42  5181.3     439  5191.3  439.72  5201.3   442.5  5211.3  443.58
  5221.3  446.25  5231.3  447.05  5261.3  452.06  5271.3   452.6  5371.3  464.04
#Mann= 3 ,-1 , 0
  4157.4     .05       0  4632.6    .033       0  4638.6     .05       0
Bank Sta=4574.5,5191.3
XS Rating Curve= 0 ,0
Exp/Cntr=0.3,0.1

Type RM Length L Ch R = 1 ,222835  ,209,209,209
BEGIN DESCRIPTION:
CATFISH CREEK 223.0
END DESCRIPTION:
XS GIS Cut Line= 3
      3726366.65     10761185.62      3726271.16     10761767.26
      3726400.94     10762346.98
#Sta/Elev= 30
  4492.5  464.88  4497.4  464.88  4517.4  461.44  4547.8  459.03  4578.2  455.33
  4626.2  453.83    4639  452.42  4659.3  449.68  4669.4  446.82  4699.8   441.2
  4709.9  438.99  4748.7  435.45  4757.6  435.42  4760.4  434.92  4763.6  435.42
  5361.6  435.42  5369.6  438.46  5392.4  440.22  5402.6  442.83  5418.1  444.61
  5423.2  447.06  5433.3  449.21  5461.4  451.99  5466.6  454.86  5474.3  456.24
  5504.8  456.88  5515.3  460.23  5576.8  465.02  5628.1  467.78    5676  472.19
#Mann= 3 ,-1 , 0
  4492.5     .05       0  4757.6    .033       0  4763.6     .05       0
Bank Sta=4699.8,5392.4
XS Rating Curve= 0 ,0
Exp/Cntr=0.3,0.1

Type RM Length L Ch R = 1 ,222626  ,60,60,60
BEGIN DESCRIPTION:
CATFISH CREEK 222.0
END DESCRIPTION:
XS GIS Cut Line= 2
      3726192.03     10761085.49      3725910.92     10762485.85
#Sta/Elev= 30
  4445.1  460.46    4530  453.56  4643.7  440.56  4682.7  436.72  4745.7  437.01
  4763.1  435.42  4765.8  434.92  4769.1  435.42  4898.7  436.57  4937.2  435.42
  4942.3  436.59  5242.6  435.42  5265.9  436.65  5293.6  435.42  5298.7  436.75
  5344.5  435.42  5349.6  437.06  5395.4  437.49  5400.5  438.99  5497.2  439.52
  5502.3  440.92  5553.2  440.32    5599  436.93  5663.6  436.14  5714.6  437.35
    5735  439.75  5751.7   442.9  5756.8   441.6  5847.2  451.13  5873.4  458.09
#Mann= 3 ,-1 , 0
  4445.1     .05       0  4763.1     .03       0  4769.1     .05       0
Bank Sta=4643.7,5735
XS Rating Curve= 0 ,0
Exp/Cntr=0.3,0.1

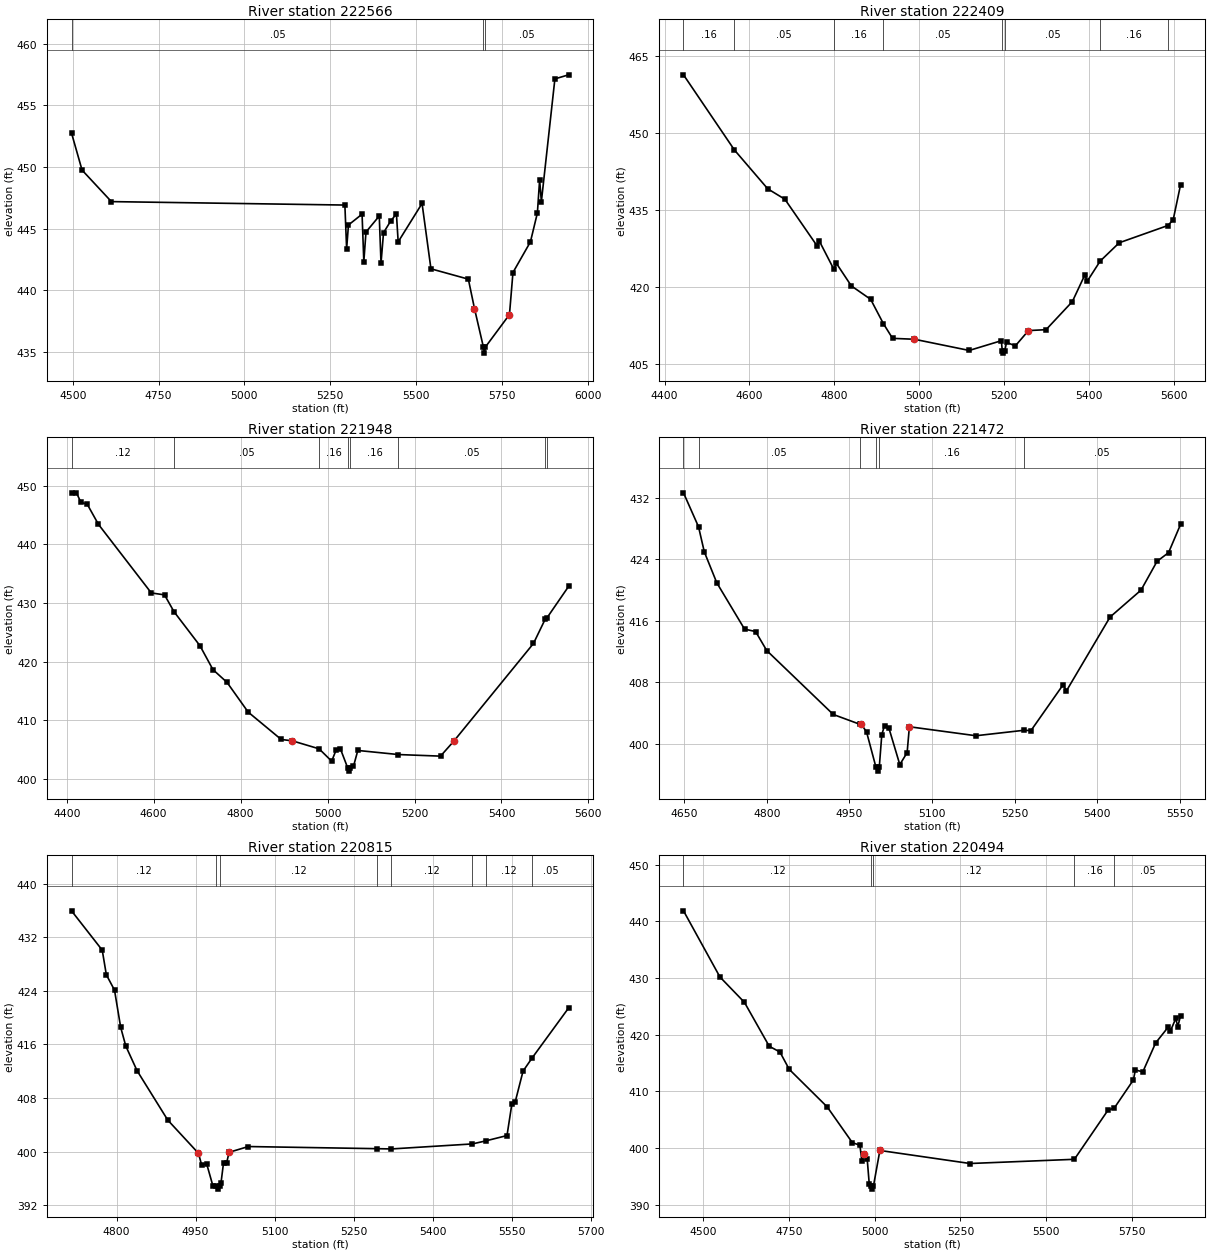
Type RM Length L Ch R = 1 ,222566  ,157,157,157
BEGIN DESCRIPTION:
Mapping XS c79cb669
END DESCRIPTION:
XS GIS Cut Line= 3
        3726128.     10761120.09      3725917.06     10762133.14
      3725838.93     10762539.42
#Sta/Elev= 30
  4496.2  452.76  4526.9  449.75  4612.4  447.19  5292.8  446.91  5297.9  443.35
  5303.2  445.29  5342.9  446.17    5348  442.31  5354.3  444.72    5393  446.02
  5398.1  442.19  5405.4  444.66  5425.8  445.59    5443   446.2  5448.1  443.92
  5517.7  447.04  5543.6  441.73  5652.6  440.89  5670.5   438.5  5696.4  435.38
  5699.2  434.88  5702.4  435.38  5772.4  438.01  5782.6  441.43  5833.5  443.92
  5853.8  446.27  5860.3  448.96  5865.4  447.19  5904.8  457.16  5944.7  457.49
#Mann= 3 ,-1 , 0
  4496.2     .05       0  5696.4     .03       0  5702.4     .05       0
Bank Sta=5670.5,5772.4
XS Rating Curve= 0 ,0
Exp/Cntr=0.3,0.1

Type RM Length L Ch R = 1 ,222409  ,461,461,461
BEGIN DESCRIPTION:
Mapping XS 42ef63d8
END DESCRIPTION:
XS GIS Cut Line= 2
      3726014.95     10761033.42      3725718.55     10762167.01
#Sta/Elev= 30
  4444.6  461.31  4564.7  446.66  4643.2   439.1  4683.6  437.07  4759.3  428.01
  4764.5  428.97  4798.8  423.46    4805  424.58  4840.2  420.19  4885.8  417.57
  4915.6  412.86  4937.4  409.97  4989.1  409.79  5118.1  407.61  5193.8  409.51
    5196  407.59  5198.7  407.09    5202  407.59  5206.1  409.19  5226.8   408.5
  5257.8  411.48  5299.2  411.66  5361.2  417.13  5390.9  422.37    5396  421.06
  5426.8  425.02  5471.7  428.59  5586.3  431.95  5598.9  433.07  5616.3  439.89
#Mann= 8 ,-1 , 0
  4444.6     .16       0  4564.7     .05       0  4798.8     .16       0
  4915.6     .05       0    5196     .03       0    5202     .05       0
  5426.8     .16       0  5586.3     .05       0
Bank Sta=4989.1,5257.8
XS Rating Curve= 0 ,0
Exp/Cntr=0.3,0.1

Type RM Length L Ch R = 1 ,221948  ,476,476,476
BEGIN DESCRIPTION:
CATFISH CREEK 221.0
END DESCRIPTION:
XS GIS Cut Line= 3
      3725359.08     10760938.94      3725449.61     10761510.19
      3725478.88     10762074.35
#Sta/Elev= 30
  4411.1  448.79  4422.5   448.8  4432.6  447.18  4447.1  446.87  4473.1  443.41
  4594.6  431.71    4625  431.38  4646.9   428.5  4706.5   422.7  4736.4  418.62
  4768.8  416.44  4817.4  411.37  4893.5  406.69  4918.6  406.47  4980.5   405.1
  5009.5  402.99  5019.5  404.86  5029.5  405.11  5046.6  401.79  5049.3  401.29
  5052.6  401.79  5059.6   402.1  5069.6  404.82    5163  404.12  5259.8  403.85
  5289.9  406.36  5473.6  423.08  5500.7  427.24    5504  427.38  5554.4  432.82
#Mann= 8 ,-1 , 0
  4411.1     .12       0  4646.9     .05       0  4980.5     .16       0
  5046.6     .07       0  5052.6     .16       0    5163     .05       0
  5500.7     .16       0    5504     .05       0
Bank Sta=4918.6,5289.9
XS Rating Curve= 0 ,0
Exp/Cntr=0.3,0.1

Type RM Length L Ch R = 1 ,221472  ,657,657,657
BEGIN DESCRIPTION:
CATFISH CREEK 220.0
END DESCRIPTION:
XS GIS Cut Line= 3
      3724949.61     10761210.17      3724999.61     10761610.19
      3725299.59     10762010.17
#Sta/Elev= 30
  4648.5  432.66  4675.8  428.24  4686.3  424.97    4709  420.94  4759.4  414.91
  4779.5  414.59  4799.7  412.12  4920.6  403.79    4969  402.51    4971  402.58
  4981.1  401.51  4998.2  396.91    5001  396.41  5004.2  396.91  5008.8  401.18
  5013.8  402.35  5021.4  402.09  5041.5  397.26  5054.8  398.82  5058.9  402.19
  5179.8  401.02    5267  401.73  5279.8  401.69  5338.1  407.65  5344.3  406.87
  5423.5  416.48  5479.8  419.99  5508.9  423.74  5529.8  424.87  5551.6  428.55
#Mann= 6 ,-1 , 0
  4648.5     .12       0  4675.8     .05       0    4969     .16       0
  4998.2     .07       0  5004.2     .16       0    5267     .05       0
Bank Sta=4971,5058.9
XS Rating Curve= 0 ,0
Exp/Cntr=0.3,0.1

Type RM Length L Ch R = 1 ,220815  ,321,321,321
BEGIN DESCRIPTION:
CATFISH CREEK 219.0
END DESCRIPTION:
XS GIS Cut Line= 3
      3724849.61     10761160.19      3724699.61     10761410.19
      3724349.59     10761960.21
#Sta/Elev= 30
  4714.5  435.96  4772.8  430.09  4780.6  426.41  4796.1  424.12  4807.8  418.57
  4817.5  415.77  4838.9  412.09  4897.2  404.71  4955.5  399.75  4961.3  398.06
  4971.1  398.16  4982.7  394.93  4989.4   394.9  4992.2   394.4  4995.4   394.9
  4998.3  395.36  5003.1  398.37    5009  398.37  5013.7   399.9  5050.1  400.76
  5294.9  400.44  5321.6   400.4  5475.4  401.15  5500.5   401.6  5541.1   402.4
  5550.4  407.15  5556.4  407.34  5571.6  412.03  5588.8  413.99    5658  421.45
#Mann= 8 ,-1 , 0
  4714.5     .12       0  4989.4     .07       0  4995.4     .12       0
  5294.9     .16       0  5321.6     .12       0  5475.4     .16       0
  5500.5     .12       0  5588.8     .05       0
Bank Sta=4955.5,5013.7
XS Rating Curve= 0 ,0
Exp/Cntr=0.3,0.1

Type RM Length L Ch R = 1 ,220494  ,803,803,803
BEGIN DESCRIPTION:
CATFISH CREEK 218.0
END DESCRIPTION:
XS GIS Cut Line= 3
      3724711.55     10760787.79      3724383.43     10761334.65
      3723680.29     10761740.91
#Sta/Elev= 30
  4442.1  441.84  4548.4  430.17  4619.8   425.7  4692.2  417.95  4723.3  416.94
  4750.5  413.88  4861.3  407.25  4934.7  400.94  4956.6   400.5  4962.4  397.66
  4969.7   398.9  4977.9  398.06  4983.8  393.72    4990  393.25  4992.8  392.75
    4996  393.25  5014.9  399.57  5277.8  397.27  5582.2  398.01  5679.8  406.64
  5699.1   407.1  5754.1  411.99  5760.2  413.78  5781.8  413.43  5819.1  418.53
  5856.4  421.37  5862.2  420.62  5877.9  422.85  5883.7  421.43  5891.9   423.3
#Mann= 5 ,-1 , 0
  4442.1     .12       0    4990     .07       0    4996     .12       0
  5582.2     .16       0  5699.1     .05       0
Bank Sta=4969.7,5014.9
XS Rating Curve= 0 ,0
Exp/Cntr=0.3,0.1

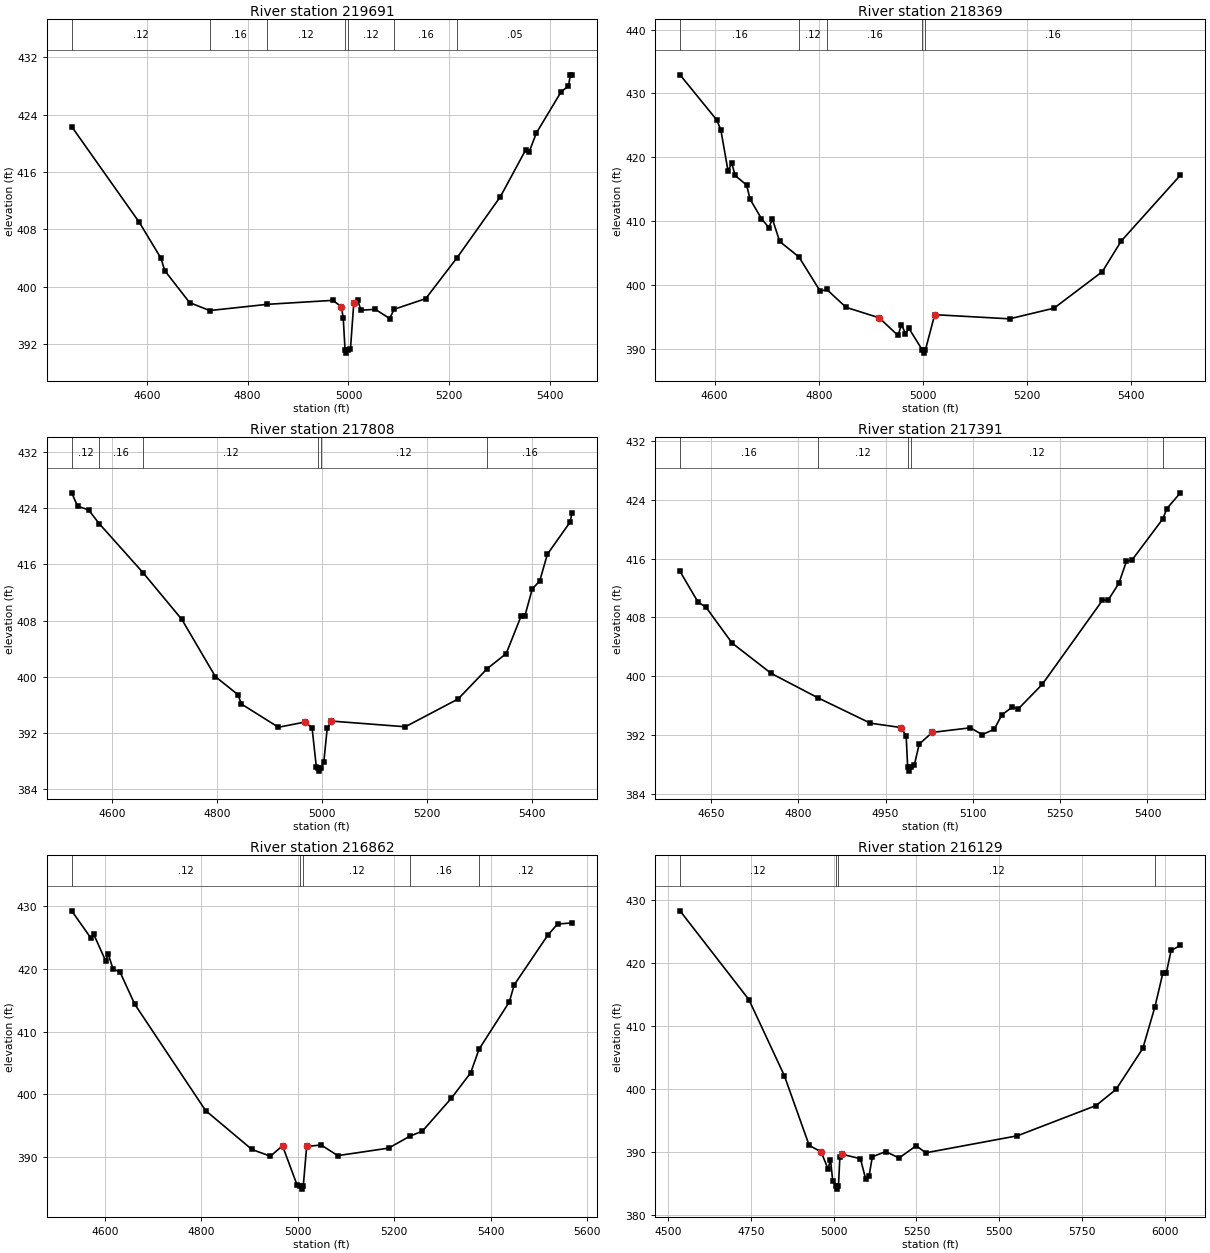
Type RM Length L Ch R = 1 ,219691  ,1322,1322,1322
BEGIN DESCRIPTION:
CATFISH CREEK 217.0
END DESCRIPTION:
XS GIS Cut Line= 3
       3724249.6      10760810.2      3723899.61     10761210.19
      3723599.59     10761560.21
#Sta/Elev= 30
    4451  422.32  4585.3  408.96    4628  403.99  4635.6  402.25  4684.9   397.8
  4724.6  396.69  4839.4  397.56  4968.7  398.11  4985.8  397.25  4989.6  395.66
  4993.2  391.26    4996  390.76  4999.2  391.26  5003.9  391.28  5010.5  397.68
  5018.2  398.18  5024.7  396.74  5053.3  396.86  5081.8  395.58  5090.5  396.87
  5153.2  398.35  5215.5  404.06  5301.3  412.55  5351.3  419.04  5358.4  418.79
  5372.7  421.42  5422.1   427.2  5436.3  427.95  5440.2  429.53  5443.5  429.53
#Mann= 7 ,-1 , 0
    4451     .12       0  4724.6     .16       0  4839.4     .12       0
  4993.2     .07       0  4999.2     .12       0  5090.5     .16       0
  5215.5     .05       0
Bank Sta=4985.8,5010.5
XS Rating Curve= 0 ,0
Exp/Cntr=0.3,0.1

Type RM Length L Ch R = 1 ,218369  ,561,561,561
BEGIN DESCRIPTION:
CATFISH CREEK 215.0
END DESCRIPTION:
XS GIS Cut Line= 3
      3723599.62     10760360.18      3723299.61     10760710.19
       3722899.6     10761010.19
#Sta/Elev= 30
  4533.6  432.92  4604.4  425.83  4612.1  424.25  4625.8  417.87  4632.9  419.09
  4639.5  417.16  4661.5  415.66  4668.1  413.46    4690   410.4  4704.3  408.99
  4710.9  410.36  4725.1  406.83  4762.1  404.39  4803.1  399.01    4815  399.35
  4852.5  396.52  4916.1  394.88  4952.3  392.11  4958.9   393.8  4966.6  392.42
  4973.2  393.22  4998.9  389.85  5001.6  389.35  5004.9  389.85  5022.7  395.37
  5166.5  394.72  5251.9  396.39  5344.6   402.1    5381   406.9  5494.6  417.21
#Mann= 5 ,-1 , 0
  4533.6     .16       0  4762.1     .12       0    4815     .16       0
  4998.9     .07       0  5004.9     .16       0
Bank Sta=4916.1,5022.7
XS Rating Curve= 0 ,0
Exp/Cntr=0.3,0.1

Type RM Length L Ch R = 1 ,217808  ,417,417,417
BEGIN DESCRIPTION:
CATFISH CREEK 214.0
END DESCRIPTION:
XS GIS Cut Line= 2
      3723245.43     10760081.15      3722654.45     10760830.94
#Sta/Elev= 30
  4522.2  426.19  4533.5  424.28  4554.3  423.77  4574.8   421.8  4658.5  414.82
  4732.3  408.19  4796.4  400.05  4839.3  397.49  4846.1  396.15  4916.7  392.85
  4966.6  393.58  4980.8  392.81  4988.9  387.25  4992.2  387.11    4995  386.61
  4998.2  387.11  5003.3  387.94  5009.7  392.68  5017.6  393.73  5158.8  392.92
  5259.5  396.87  5315.1  401.19  5351.2  403.32  5380.1  408.74  5386.8  408.66
  5400.9   412.5  5415.3  413.68  5429.8  417.45  5473.1  422.02  5476.9  423.38
#Mann= 6 ,-1 , 0
  4522.2     .12       0  4574.8     .16       0  4658.5     .12       0
  4992.2     .07       0  4998.2     .12       0  5315.1     .16       0
Bank Sta=4966.6,5017.6
XS Rating Curve= 0 ,0
Exp/Cntr=0.3,0.1

Type RM Length L Ch R = 1 ,217391  ,529,529,529
BEGIN DESCRIPTION:
CATFISH CREEK 213.0
END DESCRIPTION:
XS GIS Cut Line= 3
      3722849.62     10759960.17      3722649.61     10760360.19
       3722549.6     10760760.24
#Sta/Elev= 30
    4597  414.25  4627.8   410.1  4641.7  409.38  4686.5  404.52  4753.6  400.41
    4834  397.09  4924.1  393.65  4977.2  393.05  4985.5  391.88  4988.1  387.64
  4990.9  387.14  4994.1  387.64  4999.5  387.97  5007.9  390.81  5030.3   392.4
  5095.8  393.02  5116.4  392.09    5137  392.85  5149.9  394.78  5167.9  395.84
  5178.2  395.59  5219.5  398.94  5322.5  410.31  5332.9   410.4  5350.9  412.64
  5363.8   415.6  5374.1  415.86  5426.4  421.38  5433.4  422.79  5456.6  424.92
#Mann= 5 ,-1 , 0
    4597     .16       0    4834     .12       0  4988.1     .07       0
  4994.1     .12       0  5426.4     .16       0
Bank Sta=4977.2,5030.3
XS Rating Curve= 0 ,0
Exp/Cntr=0.3,0.1

Type RM Length L Ch R = 1 ,216862  ,733,733,733
BEGIN DESCRIPTION:
CATFISH CREEK 212.0
END DESCRIPTION:
XS GIS Cut Line= 3
      3722449.62     10759710.17      3722299.61     10760110.19
      3722324.21     10760720.17
#Sta/Elev= 30
  4531.2  429.28  4571.3   424.9  4576.6  425.59  4601.5  421.31  4606.9  422.37
  4616.7  420.06  4631.8  419.44  4662.1  414.35  4808.9  397.39    4905  391.17
  4943.3   390.1  4968.4  391.76  4998.5  385.53  5005.5  385.34  5008.2  384.84
  5011.5  385.34  5018.5  391.65  5048.5  391.89    5083  390.19  5188.6  391.39
    5232  393.27  5258.7  394.11  5318.7  399.37  5358.7  403.42  5375.9  407.17
  5438.8  414.73  5448.8  417.44  5518.9  425.43  5538.9  427.17  5568.9  427.35
#Mann= 5 ,-1 , 0
  4531.2     .12       0  5005.5     .07       0  5011.5     .12       0
    5232     .16       0  5375.9     .12       0
Bank Sta=4968.4,5018.5
XS Rating Curve= 0 ,0
Exp/Cntr=0.3,0.1

Type RM Length L Ch R = 1 ,216129  ,300,300,300
BEGIN DESCRIPTION:
CATFISH CREEK 211.0
END DESCRIPTION:
XS GIS Cut Line= 4
      3722412.02     10759542.98      3722030.09     10759633.26
      3721925.92     10759744.37      3721800.93     10760702.69
#Sta/Elev= 30
  4535.9  428.22  4743.9  414.16  4850.8  402.14    4926  391.07    4962  390.06
    4983  387.34  4990.3  388.81  4997.2   385.4  5008.4  384.65  5011.1  384.15
  5014.4  384.65  5018.7  389.27  5025.5  389.67  5080.7  388.97  5096.6  385.75
  5106.7  386.23  5116.8  389.27  5157.1   390.1  5197.5  389.08  5249.2  391.02
  5278.1   389.9  5555.1   392.6  5792.5  397.39    5853  399.96  5933.6  406.44
    5970  412.98  5994.2  418.37  6004.2   418.3    6019  421.94  6047.1  422.74
#Mann= 4 ,-1 , 0
  4535.9     .12       0  5008.4     .07       0  5014.4     .12       0
    5970     .16       0
Bank Sta=4962,5025.5
XS Rating Curve= 0 ,0
Exp/Cntr=0.3,0.1

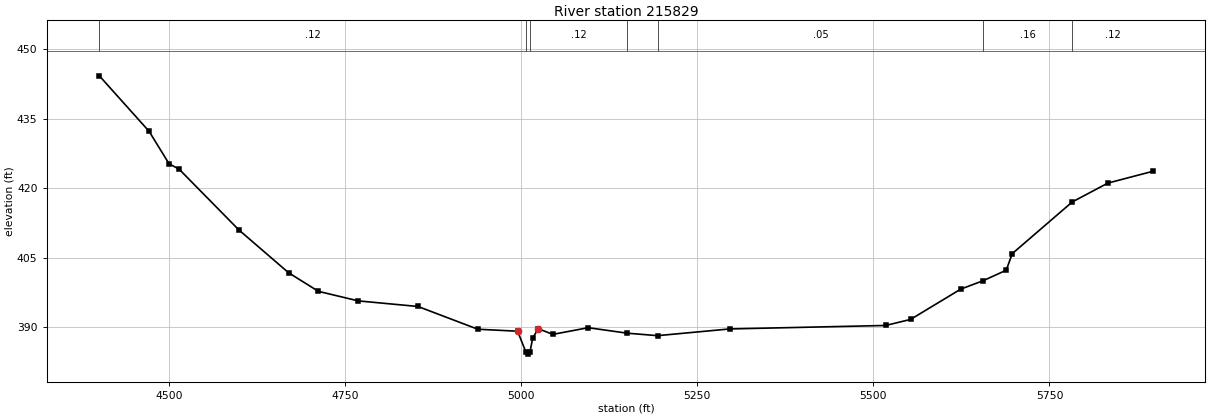
Type RM Length L Ch R = 1 ,215829  ,698,698,698
BEGIN DESCRIPTION:
CATFISH CREEK 210.0
END DESCRIPTION:
XS GIS Cut Line= 3
       3722299.6      10759010.2      3721899.61     10759410.19
      3721149.63     10759960.18
#Sta/Elev= 30
  4400.9  444.28  4471.6  432.28  4499.9  425.28    4514  424.14  4598.9  411.01
  4669.6  401.74    4712  397.72  4768.6  395.66  4853.4  394.45  4938.3  389.54
  4994.8  389.11  5006.4  384.66  5009.2  384.16  5012.4  384.66  5016.2  387.63
  5024.1  389.64  5044.9  388.43  5095.1  389.87  5150.6  388.68  5193.5  388.15
  5295.8   389.6  5517.3  390.35  5552.8  391.66  5623.8  398.19  5655.9  400.03
  5688.6  402.29  5697.1  405.87  5782.2  417.02  5832.9  421.11  5896.6  423.65
#Mann= 7 ,-1 , 0
  4400.9     .12       0  5006.4     .07       0  5012.4     .12       0
  5150.6     .16       0  5193.5     .05       0  5655.9     .16       0
  5782.2     .12       0
Bank Sta=4994.8,5024.1
XS Rating Curve= 0 ,0
Exp/Cntr=0.3,0.1