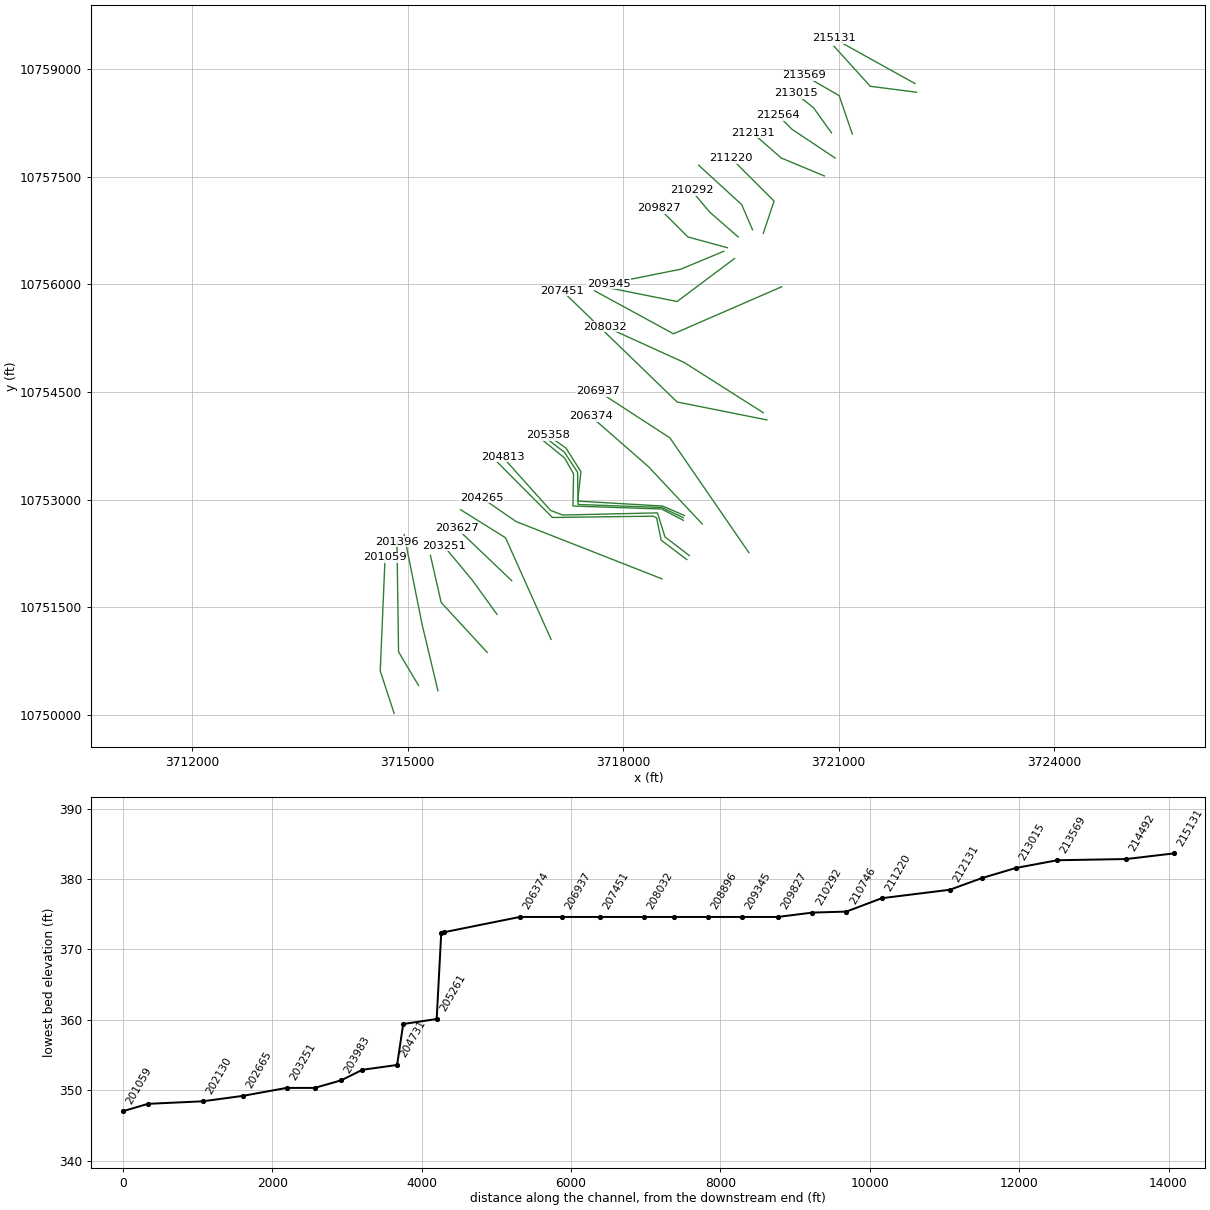
HEC-RAS study CATFISH CREEK.prj: CATFISH CREEK Base Level Engineering

--- CATFISH CREEK.g01 (geometry) --- (continued)

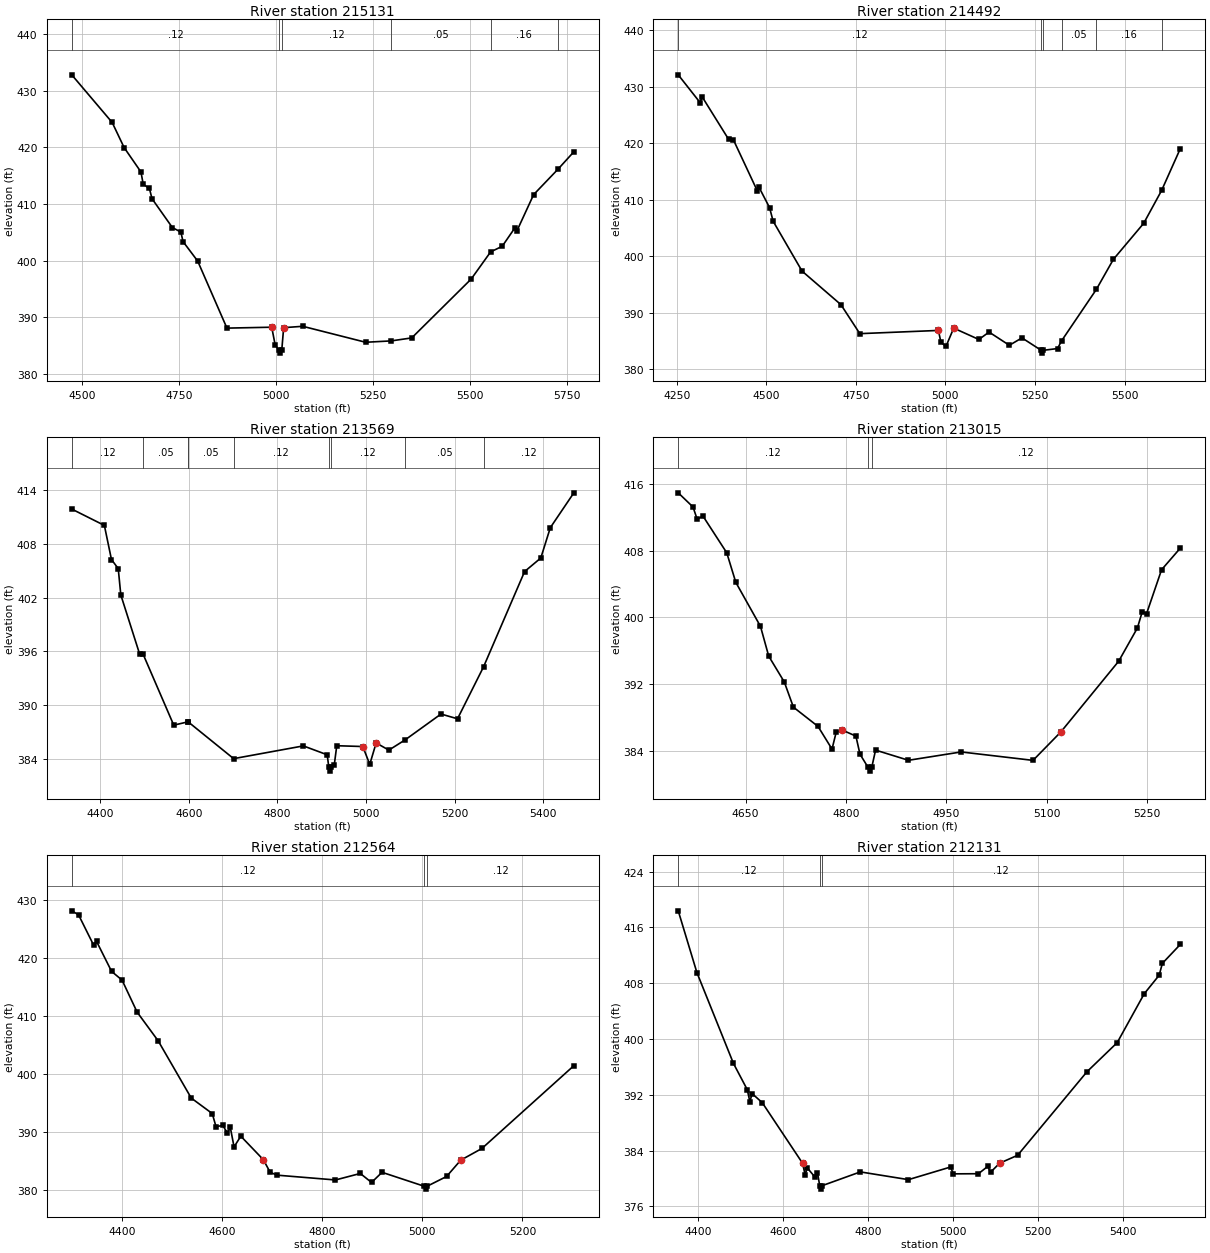
Type RM Length L Ch R = 1 ,215131  ,639,639,639
BEGIN DESCRIPTION:
CATFISH CREEK 209.0
END DESCRIPTION:
XS GIS Cut Line= 2
      3722060.77     10758798.52      3720927.95     10759427.86
#Sta/Elev= 30
  4472.4  432.82  4576.7   424.4  4607.5  419.97    4651  415.65  4656.8  413.48
  4672.7  412.75  4679.6  410.92  4732.2  405.82  4753.9  405.04  4759.7  403.34
  4797.4  399.91  4872.9  388.06  4988.5  388.22  4997.6  385.01  5008.4  384.14
  5011.1  383.64  5014.4  384.14  5019.3  388.14  5068.6  388.38  5230.9  385.56
  5296.8   385.8  5349.9  386.33  5503.3  396.73  5553.5  401.53  5583.4  402.52
  5615.3  405.69    5621  405.19  5664.5  411.65  5727.6  416.16  5768.3  419.22
#Mann= 6 ,-1 , 0
  4472.4     .12       0  5008.4     .07       0  5014.4     .12       0
  5296.8     .05       0  5553.5     .16       0  5727.6     .05       0
Bank Sta=4988.5,5019.3
XS Rating Curve= 0 ,0
Exp/Cntr=0.3,0.1

Type RM Length L Ch R = 1 ,214492  ,923,923,923
BEGIN DESCRIPTION:
CATFISH CREEK 208.0
END DESCRIPTION:
XS GIS Cut Line= 3
      3722082.45     10758677.01      3721440.07     10758759.47
      3720933.42     10759318.09
#Sta/Elev= 30
    4254  432.14  4315.3   427.2  4320.3  428.29  4394.9  420.69  4408.1  420.62
  4474.5  411.62  4479.5  412.22  4508.9  408.63    4519   406.2  4599.7  397.37
  4708.2  391.43    4761  386.29  4980.5  386.86  4987.3  384.78  5001.5  384.03
  5023.1  387.27  5093.4  385.26  5121.8  386.57  5178.5  384.23  5213.7  385.54
  5267.4  383.34  5270.2  382.84  5273.4  383.34    5313  383.65  5324.4  385.03
  5421.4  394.13  5469.1  399.47  5553.6  405.84  5603.6  411.66  5655.8  419.07
#Mann= 6 ,-1 , 0
    4254     .12       0  5267.4     .07       0  5273.4     .12       0
  5324.4     .05       0  5421.4     .16       0  5603.6     .05       0
Bank Sta=4980.5,5023.1
XS Rating Curve= 0 ,0
Exp/Cntr=0.3,0.1

Type RM Length L Ch R = 1 ,213569  ,554,554,554
BEGIN DESCRIPTION:
CATFISH CREEK 206.0
END DESCRIPTION:
XS GIS Cut Line= 3
      3721188.33     10758095.42      3721006.05     10758629.27
      3720513.37      10758914.5
#Sta/Elev= 30
  4335.7  411.86  4409.3  410.04  4425.3  406.24  4440.6  405.23  4446.4   402.3
  4488.7  395.74  4496.7   395.7  4565.9  387.79    4598  388.16  4598.9  388.14
  4701.1  384.06  4858.5  385.48  4912.3  384.49  4915.8  383.17  4918.6  382.67
  4921.8  383.17  4928.1   383.3  4933.9   385.5  4992.7  385.41  5008.4  383.42
  5022.8  385.81  5051.5  385.01  5088.2  386.15  5169.2  389.03  5206.5   388.5
  5265.3  394.29  5357.9   404.9  5394.5  406.41    5416  409.79  5469.1  413.67
#Mann= 9 ,-1 , 0
  4335.7     .12       0  4496.7     .05       0    4598     .12       0
  4598.9     .05       0  4701.1     .12       0  4915.8     .07       0
  4921.8     .12       0  5088.2     .05       0  5265.3     .12       0
Bank Sta=4992.7,5022.8
XS Rating Curve= 0 ,0
Exp/Cntr=0.3,0.1

Type RM Length L Ch R = 1 ,213015  ,451,451,451
BEGIN DESCRIPTION:
CATFISH CREEK 205.0
END DESCRIPTION:
XS GIS Cut Line= 3
      3720899.61     10758110.18      3720649.61     10758460.19
      3720399.59      10758660.2
#Sta/Elev= 30
  4549.4  414.94  4571.5  413.24  4577.7  411.77  4586.3  412.16  4621.9  407.75
  4635.4  404.21  4672.3  398.93  4684.6  395.36  4707.9  392.26  4721.5  389.24
  4758.3  386.93  4779.2  384.21  4785.4  386.22    4794  386.51  4814.9  385.77
    4821   383.6  4832.7  382.07  4835.5  381.57  4838.7  382.07  4844.3  384.09
  4893.5  382.87  4972.2  383.87  5079.6  382.86  5121.2  386.27  5207.6  394.75
  5235.6  398.74  5242.9  400.71  5249.3  400.46  5271.7  405.72  5299.7  408.31
#Mann= 3 ,-1 , 0
  4549.4     .12       0  4832.7     .07       0  4838.7     .12       0
Bank Sta=4794,5121.2
XS Rating Curve= 0 ,0
Exp/Cntr=0.3,0.1

Type RM Length L Ch R = 1 ,212564  ,433,433,433
BEGIN DESCRIPTION:
CATFISH CREEK 204.0
END DESCRIPTION:
XS GIS Cut Line= 3
       3720949.6     10757760.19      3720349.61     10758160.19
      3720149.64     10758360.16
#Sta/Elev= 30
    4299  428.13  4312.5  427.45  4342.6  422.23  4348.6  422.85  4378.6  417.69
  4399.6  416.18  4429.7  410.66  4471.8  405.71  4537.9  395.85  4579.9  393.18
  4587.4  390.92    4601  391.13    4610  389.83    4616  390.78  4623.5  387.43
    4637  389.28  4682.1  385.22  4695.6  383.06  4709.1  382.56  4826.3  381.73
  4875.9  382.85  4898.4   381.3  4919.4  383.05  5003.6  380.65  5006.3  380.15
  5009.6  380.65  5048.4  382.33  5076.7  385.14  5119.1  387.16  5302.9  401.43
#Mann= 3 ,-1 , 0
    4299     .12       0  5003.6     .07       0  5009.6     .12       0
Bank Sta=4682.1,5076.7
XS Rating Curve= 0 ,0
Exp/Cntr=0.3,0.1

Type RM Length L Ch R = 1 ,212131  ,911,911,911
BEGIN DESCRIPTION:
CATFISH CREEK 203.0
END DESCRIPTION:
XS GIS Cut Line= 3
      3720799.63     10757510.18      3720199.61     10757760.19
      3719799.63     10758110.17
#Sta/Elev= 30
  4353.4  418.39  4397.3  409.54  4483.4   396.5  4515.9  392.74  4521.9  391.03
  4527.3  392.18  4551.1  390.88  4645.9   382.2  4651.9  380.57  4657.3  381.51
  4675.7  380.16  4681.1  380.83  4686.3  378.98    4689  378.48  4692.3  378.98
  4781.9  380.95  4895.1  379.84  4994.2  381.65  5000.7  380.67  5059.9  380.69
  5081.7  381.74  5088.4   380.9  5109.7   382.2    5152  383.33  5315.2  395.31
  5386.4  399.49    5450   406.5  5485.1  409.15  5492.7  410.86  5534.9  413.57
#Mann= 3 ,-1 , 0
  4353.4     .12       0  4686.3     .07       0  4692.3     .12       0
Bank Sta=4645.9,5109.7
XS Rating Curve= 0 ,0
Exp/Cntr=0.3,0.1

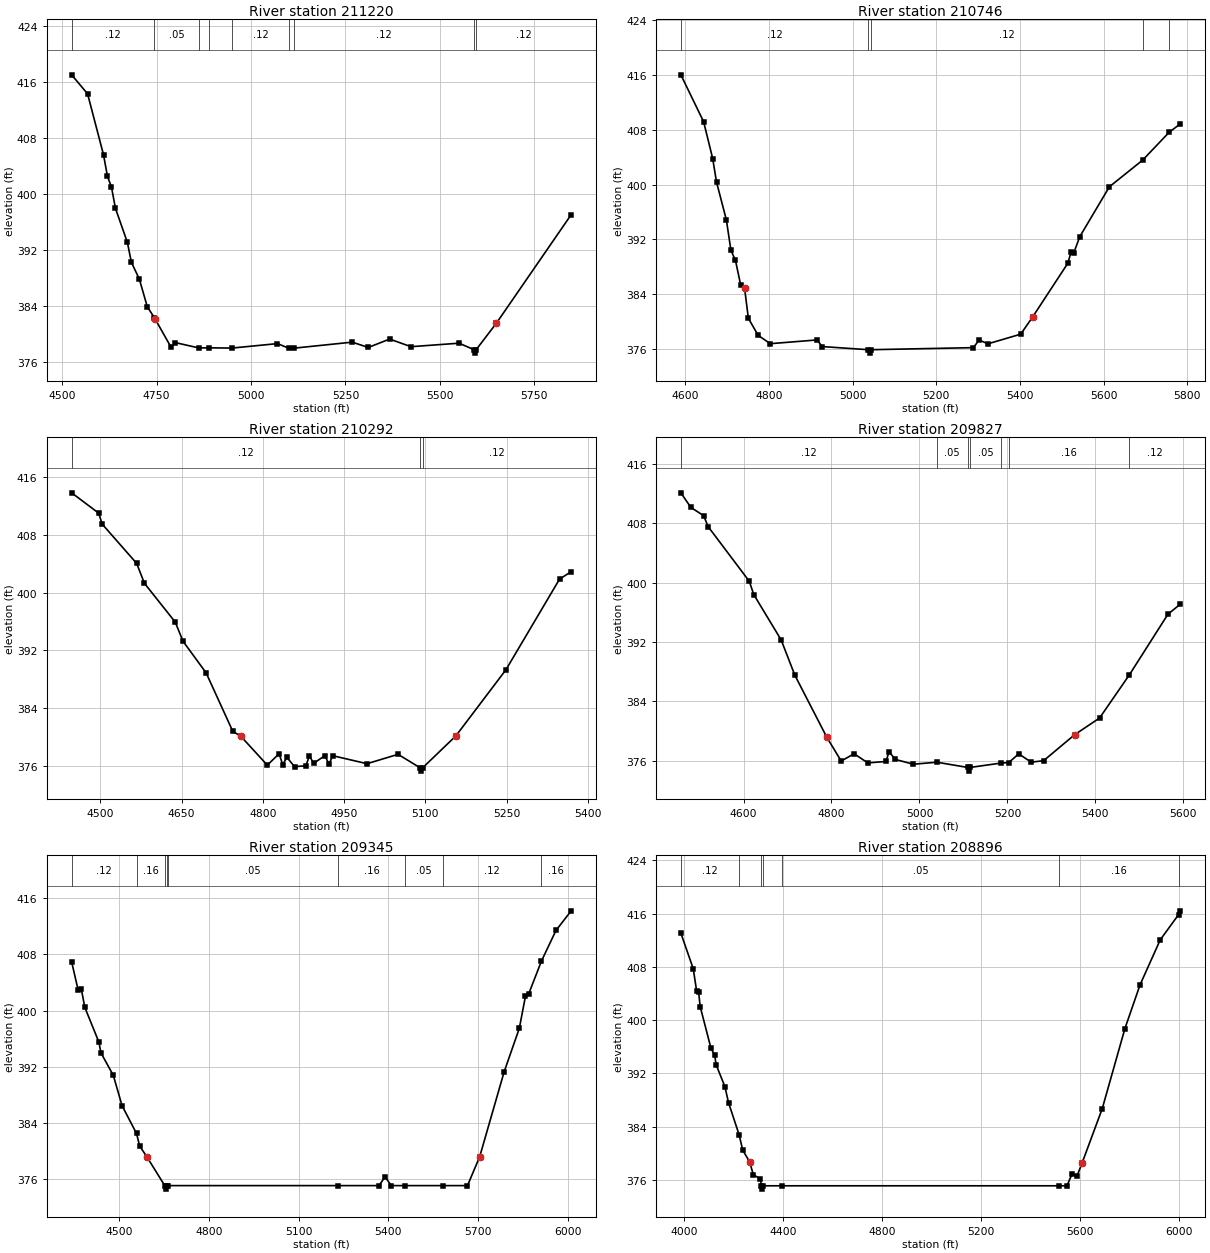
Type RM Length L Ch R = 1 ,211220  ,474,474,474
BEGIN DESCRIPTION:
CATFISH CREEK 202.0
END DESCRIPTION:
XS GIS Cut Line= 3
       3719949.6     10756710.15      3720099.61     10757160.19
      3719499.61     10757760.18
#Sta/Elev= 30
  4524.9  417.07  4567.1  414.35  4609.3  405.64  4619.8  402.54  4630.3  401.04
  4640.9  397.98  4672.5  393.11  4683.1  390.27  4704.1  387.87  4725.2  383.91
  4743.7  382.37  4746.3  382.13  4788.5  378.09    4799  378.79  4861.9  378.02
  4887.7  378.04  4948.9     378    5070  378.64  5101.2  377.95  5113.9  377.99
    5268  378.85  5310.4  378.09    5367  379.29  5423.5   378.2  5550.8   378.7
  5590.2  377.78    5593  377.28  5596.2  377.78  5649.8  381.57  5847.8  397.08
#Mann= 9 ,-1 , 0
  4524.9     .12       0  4743.7     .05       0  4861.9     .12       0
  4887.7     .05       0  4948.9     .12       0  5101.2     .05       0
  5113.9     .12       0  5590.2     .07       0  5596.2     .12       0
Bank Sta=4746.3,5649.8
XS Rating Curve= 0 ,0
Exp/Cntr=0.3,0.1

Type RM Length L Ch R = 1 ,210746  ,454,454,454
BEGIN DESCRIPTION:
CATFISH CREEK 201.0
END DESCRIPTION:
XS GIS Cut Line= 3
       3719799.6     10756760.21      3719649.61     10757110.19
      3719049.62     10757660.18
#Sta/Elev= 30
  4589.1  416.03  4643.5  409.18  4665.2   403.8  4674.3  400.38  4697.9  394.84
  4708.8   390.4  4719.6  388.94  4732.3  385.28  4741.4  384.89  4750.5  380.47
    4774  377.97    4803  376.76  4915.5  377.31  4926.4  376.34  5037.5  375.88
  5040.2  375.38  5043.5  375.88  5288.4  376.18  5302.5  377.29  5323.5  376.74
  5401.8  378.15  5430.2  380.65  5514.7  388.53  5522.1  390.14  5528.8  390.03
    5543  392.38  5613.9  399.68  5693.4  403.57    5757  407.65  5783.8  408.88
#Mann= 5 ,-1 , 0
  4589.1     .12       0  5037.5     .07       0  5043.5     .12       0
  5693.4     .16       0    5757     .12       0
Bank Sta=4741.4,5430.2
XS Rating Curve= 0 ,0
Exp/Cntr=0.3,0.1

Type RM Length L Ch R = 1 ,210292  ,465,465,465
BEGIN DESCRIPTION:
CATFISH CREEK 200.0
END DESCRIPTION:
XS GIS Cut Line= 3
      3719599.59      10756660.2      3719199.61     10757010.19
      3718949.61     10757310.19
#Sta/Elev= 30
  4447.1  413.82  4496.9  411.01  4503.5  409.48  4567.1  404.04  4581.4  401.28
  4638.3   395.9  4652.6  393.25  4695.3  388.86  4744.6  380.74  4758.9  380.11
  4808.2  376.07    4830  377.65  4836.7  376.13  4844.3  377.15  4858.5  375.86
  4879.4  375.98    4886  377.38  4893.6  376.31  4914.5  377.39  4922.1  376.18
  4928.8  377.38  4992.3  376.27  5049.5  377.57  5089.5  375.74  5092.2  375.24
  5095.5  375.74  5156.3  380.13  5248.7   389.3  5347.6  401.86  5369.1  402.89
#Mann= 3 ,-1 , 0
  4447.1     .12       0  5089.5     .07       0  5095.5     .12       0
Bank Sta=4758.9,5156.3
XS Rating Curve= 0 ,0
Exp/Cntr=0.3,0.1

Type RM Length L Ch R = 1 ,209827  ,482,482,482
BEGIN DESCRIPTION:
CATFISH CREEK 199.0
END DESCRIPTION:
XS GIS Cut Line= 3
       3719449.6     10756510.19      3718899.61     10756660.19
      3718499.59     10757060.21
#Sta/Elev= 30
  4457.6   412.1  4480.1  410.15  4509.4  409.02  4519.8  407.53  4613.1  400.19
  4623.4  398.39  4685.6  392.29  4716.7  387.54  4789.3  379.19  4822.1  375.98
  4851.5  376.96  4882.6  375.73    4924  375.92  4930.9  377.26  4944.8   376.2
  4986.2  375.55  5039.4  375.82  5109.5  375.12  5112.3  374.62  5115.5  375.12
  5185.1   375.7  5203.3  375.78  5225.7  376.95    5254  375.83  5282.2  376.02
    5353  379.53  5409.5  381.77    5477  387.56  5565.1  395.76  5593.4  397.12
#Mann= 7 ,-1 , 0
  4457.6     .12       0  5039.4     .05       0  5109.5     .07       0
  5115.5     .05       0  5185.1     .12       0  5203.3     .16       0
    5477     .12       0
Bank Sta=4789.3,5353
XS Rating Curve= 0 ,0
Exp/Cntr=0.3,0.1

Type RM Length L Ch R = 1 ,209345  ,449,449,449
BEGIN DESCRIPTION:
CATFISH CREEK 198.0
END DESCRIPTION:
XS GIS Cut Line= 3
      3719399.65      10756460.2      3718799.61     10756210.19
      3717799.65      10756010.2
#Sta/Elev= 30
  4341.7  406.95  4363.4  402.94  4374.2  403.05  4385.6  400.49  4433.3  395.48
  4439.2  394.04    4481   390.8  4510.2  386.49  4558.5  382.54  4569.2  380.74
  4592.5  379.26  4652.9  375.12  4655.7  374.62  4658.9  375.12  4664.1  375.12
  5233.5  375.12  5369.1  375.12  5389.5  376.38  5409.9  375.12  5457.5  375.12
  5582.3  375.12  5664.8  375.12  5705.6  379.23  5787.2  391.29  5838.2  397.52
  5858.6  402.07  5868.8  402.33  5911.9  407.05  5960.6  411.42  6011.5  414.21
#Mann= 9 ,-1 , 0
  4341.7     .12       0  4558.5     .16       0  4652.9    .033       0
  4658.9     .16       0  4664.1     .05       0  5233.5     .16       0
  5457.5     .05       0  5582.3     .12       0  5911.9     .16       0
Bank Sta=4592.5,5705.6
XS Rating Curve= 0 ,0
Exp/Cntr=0.3,0.1

Type RM Length L Ch R = 1 ,208896  ,452,452,452
BEGIN DESCRIPTION:
CATFISH CREEK 197.0
END DESCRIPTION:
XS GIS Cut Line= 3
       3719549.6     10756360.18      3718749.61     10755760.19
      3717749.61     10755960.19
#Sta/Elev= 30
    3988  413.06    4038  407.71  4051.5  404.43  4059.9  404.15  4066.1  402.03
  4109.9  395.74  4124.5  394.76  4130.7  393.28  4166.1     390  4180.7   387.6
  4223.6  382.77    4238  380.48  4266.1  378.71  4280.7   376.8  4309.9  376.12
  4313.1  375.12  4315.9  374.62  4319.1  375.12  4395.8  375.12  5518.6  375.12
  5548.9  375.12  5569.3  376.87  5589.7  376.59  5610.1  378.54  5691.7  386.71
  5783.4  398.74  5844.6  405.31  5926.2  412.06  6000.1  415.83  6007.8  416.41
#Mann= 7 ,-1 , 0
    3988     .12       0  4223.6     .16       0  4313.1    .033       0
  4319.1     .16       0  4395.8     .05       0  5518.6     .16       0
  6000.1     .12       0
Bank Sta=4266.1,5610.1
XS Rating Curve= 0 ,0
Exp/Cntr=0.3,0.1

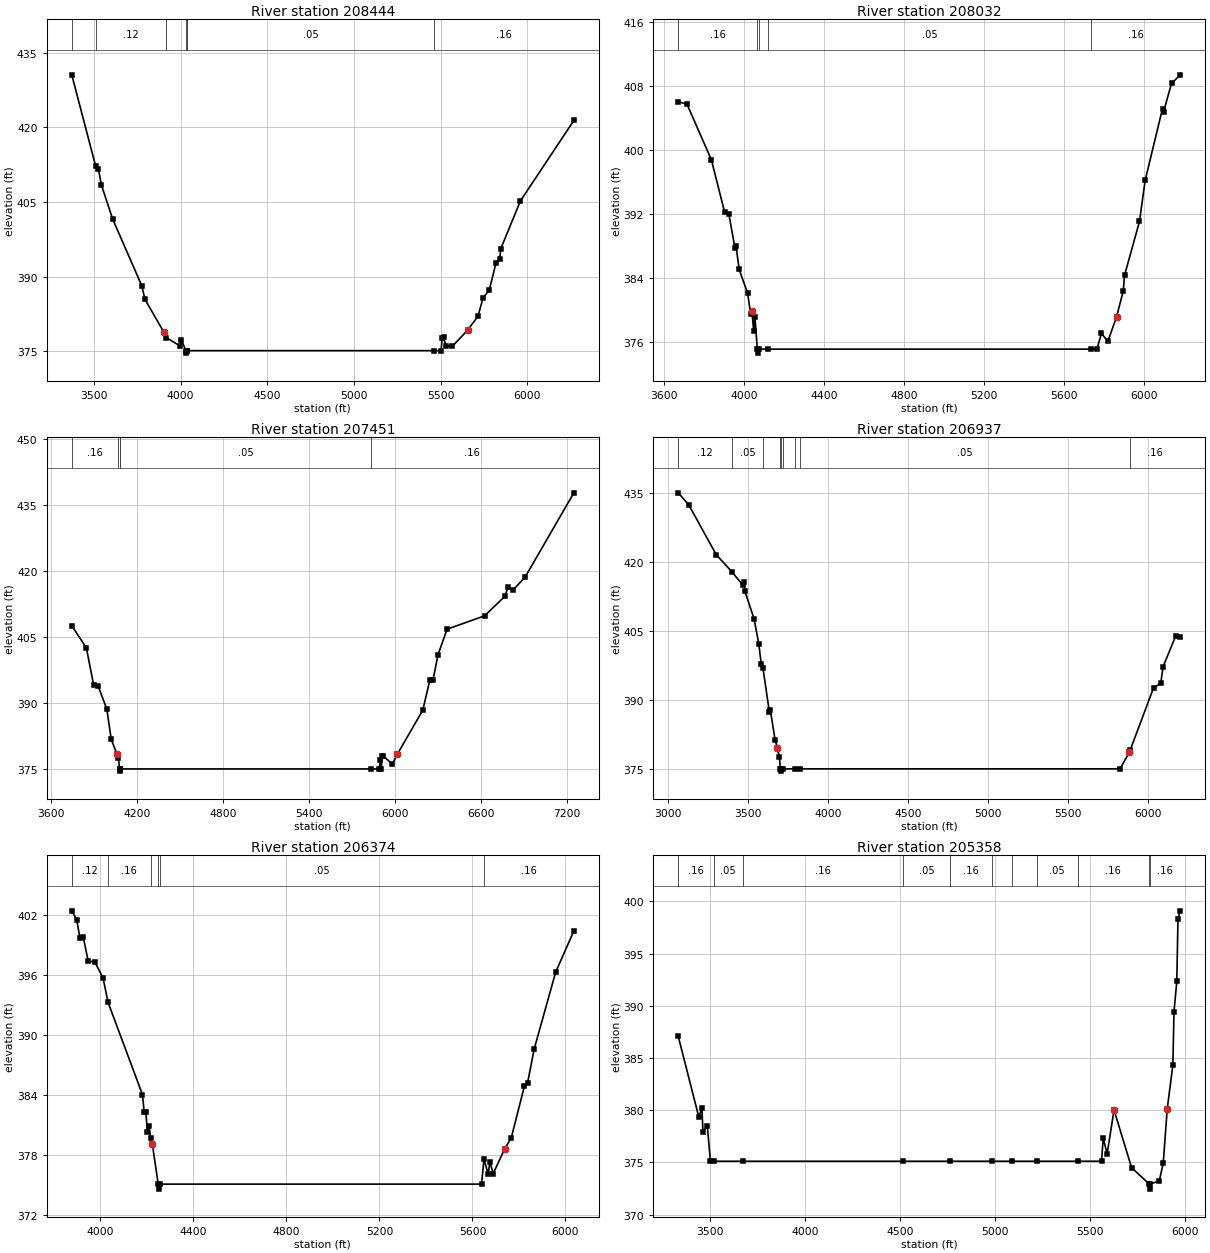
Type RM Length L Ch R = 1 ,208444  ,412,412,412
BEGIN DESCRIPTION:
CATFISH CREEK 196.0
END DESCRIPTION:
XS GIS Cut Line= 3
       3720206.2     10755965.85      3718699.61     10755310.19
      3717599.58      10755910.2
#Sta/Elev= 30
  3372.6  430.56  3510.5   412.2  3525.8  411.71  3543.4  408.44  3608.8  401.53
  3776.5  388.17  3794.2  385.46  3904.6  378.79  3917.2  377.75  3998.4  376.04
  4003.8  377.35  4031.1  375.12  4033.9  374.62  4037.1  375.12    4038  375.12
  5461.7  375.12  5503.1  375.12  5508.8  377.62  5516.9  377.87  5530.6  376.08
  5568.6  376.01  5655.9  379.24  5715.7  382.03  5744.7  385.69  5781.2  387.34
  5819.2  392.69    5841  393.48  5847.2   395.6  5960.6  405.22  6268.7  421.38
#Mann= 7 ,-1 , 0
  3372.6     .16       0  3510.5     .12       0  3917.2     .16       0
  4031.1    .033       0  4037.1     .16       0    4038     .05       0
  5461.7     .16       0
Bank Sta=3904.6,5655.9
XS Rating Curve= 0 ,0
Exp/Cntr=0.3,0.1

Type RM Length L Ch R = 1 ,208032  ,581,581,581
BEGIN DESCRIPTION:
CATFISH CREEK 195.0
END DESCRIPTION:
XS GIS Cut Line= 3
      3719949.64     10754210.17      3718849.61     10754910.19
       3717749.6     10755410.19
#Sta/Elev= 30
  3671.2  406.05  3715.3  405.73  3837.2  398.78  3903.2  392.25  3924.4  392.02
  3954.9  387.76  3960.8  387.97    3976  385.09  4018.4  382.11  4033.6  379.52
  4039.5   379.9  4048.8  377.43  4054.8  379.15    4067  375.12  4069.8  374.62
    4073  375.12  4120.4  375.12  5738.1  375.12    5766  375.12    5789  377.08
  5820.9  376.09  5864.8  379.19  5897.8  382.38  5904.4  384.35  5979.1  391.08
  6007.6  396.23  6094.4   405.2  6099.9  404.81  6139.4  408.34  6183.4  409.41
#Mann= 5 ,-1 , 0
  3671.2     .16       0    4067    .033       0    4073     .16       0
  4120.4     .05       0  5738.1     .16       0
Bank Sta=4039.5,5864.8
XS Rating Curve= 0 ,0
Exp/Cntr=0.3,0.1

Type RM Length L Ch R = 1 ,207451  ,514,514,514
BEGIN DESCRIPTION:
CATFISH CREEK 194.0
END DESCRIPTION:
XS GIS Cut Line= 3
      3719999.62     10754110.19      3718749.61     10754360.19
      3717149.63     10755910.17
#Sta/Elev= 30
  3745.2  407.62  3847.2  402.57  3898.2  394.09  3928.8  393.96    3990  388.67
  4020.6  381.82  4061.3  378.43  4070.8  377.53  4078.7  375.12  4081.5  374.62
  4084.7  375.12  5831.7  375.12  5889.8  375.12    5897   377.1    5904  375.12
    5911  377.94  5918.1  378.03  5981.7  376.25  6017.1   378.5  6193.9  388.46
  6243.5  395.35  6264.6  395.24  6300.1  401.03  6363.6  406.83  6625.3  409.86
  6766.7   414.3  6788.1  416.37  6823.3  415.71  6908.2  418.67  7247.6  437.77
#Mann= 5 ,-1 , 0
  3745.2     .16       0  4070.8     .05       0  4078.7    .033       0
  4084.7     .05       0  5831.7     .16       0
Bank Sta=4061.3,6017.1
XS Rating Curve= 0 ,0
Exp/Cntr=0.3,0.1

Type RM Length L Ch R = 1 ,206937  ,563,563,563
BEGIN DESCRIPTION:
CATFISH CREEK 193.0
END DESCRIPTION:
XS GIS Cut Line= 3
      3719749.63     10752260.17      3718649.61     10753860.19
      3717649.58     10754510.21
#Sta/Elev= 30
    3065  435.11  3129.3  432.57  3302.5  421.66  3399.8  417.95  3466.9  415.11
  3475.7  415.79  3481.8  413.68  3538.6  407.68  3568.4   402.2  3583.3   397.8
  3593.8  397.02    3634  387.47  3640.1  387.86  3669.9  381.36  3683.9   379.7
  3696.9  377.64  3702.7  375.12  3705.5  374.62  3708.7  375.12    3717  375.12
    3797  375.12  3822.8  375.12  5823.4  375.12  5880.8  378.71  5885.6  379.11
  6032.4  392.73  6077.1   393.7    6092  397.33  6170.7  404.01  6199.4  403.84
#Mann= 9 ,-1 , 0
    3065     .12       0  3399.8     .05       0  3593.8     .16       0
  3702.7    .033       0  3708.7     .16       0    3717     .05       0
    3797     .16       0  3822.8     .05       0  5885.6     .16       0
Bank Sta=3683.9,5880.8
XS Rating Curve= 0 ,0
Exp/Cntr=0.3,0.1

Type RM Length L Ch R = 1 ,206374  ,1016,1016,1016
BEGIN DESCRIPTION:
CATFISH CREEK 192.0
END DESCRIPTION:
XS GIS Cut Line= 3
      3719099.62     10752660.18      3718349.61     10753460.19
      3717549.62     10754160.18
#Sta/Elev= 30
  3876.5  402.41  3897.8  401.52  3911.9  399.65  3926.1  399.77  3947.1  397.39
  3975.4  397.31  4011.1  395.71  4032.4  393.28  4180.6  384.06  4187.9  382.33
  4194.7  382.35  4202.1  380.37  4208.9  380.92  4215.7  379.73  4223.1   379.1
  4248.4  375.12  4251.2  374.62  4254.4  375.12  5638.9  375.12  5649.6   377.6
  5667.4  376.13    5675  377.34  5689.2  376.17  5738.6  378.64    5767  379.75
  5823.5  384.91  5837.3  385.26  5865.7  388.63  5957.8  396.28  6036.1   400.4
#Mann= 6 ,-1 , 0
  3876.5     .12       0  4032.4     .16       0  4215.7     .05       0
  4248.4    .033       0  4254.4     .05       0  5649.6     .16       0
Bank Sta=4223.1,5738.6
XS Rating Curve= 0 ,0
Exp/Cntr=0.3,0.1

Type RM Length L Ch R = 1 ,205358  ,36,36,36
BEGIN DESCRIPTION:
Mapping XS 7ab6a2eb
END DESCRIPTION:
XS GIS Cut Line= 6
      3718851.61     10752777.59      3718549.57     10752909.51
      3717365.54     10752978.96      3717410.68     10753388.68
      3717202.35     10753718.54      3716949.16     10753895.42
#Sta/Elev= 30
    3331  387.08  3438.9  379.38  3455.8  380.17  3461.3  377.94  3483.8  378.53
  3500.5  375.12  3517.4  375.12  3671.1  375.12  4516.2  375.12  4762.4  375.12
  4985.6  375.12    5086  375.12  5219.1  375.12  5434.2  375.12  5560.1  375.12
  5568.6  377.31  5589.6  375.84  5625.8  380.02  5718.3   374.5  5810.4  372.95
  5813.2  372.45  5816.4  372.95    5864  373.23  5884.9  374.94  5905.9  380.13
  5935.5  384.31  5941.6  389.45  5956.4  392.35  5962.5  398.35  5974.8  399.09
#Mann= 11 ,-1 , 0
    3331     .16       0  3517.4     .05       0  3671.1     .16       0
  4516.2     .05       0  4762.4     .16       0  4985.6     .05       0
    5086     .16       0  5219.1     .05       0  5434.2     .16       0
  5810.4    .033       0  5816.4     .16       0
Bank Sta=5625.8,5905.9
XS Rating Curve= 0 ,0
Exp/Cntr=0.3,0.1

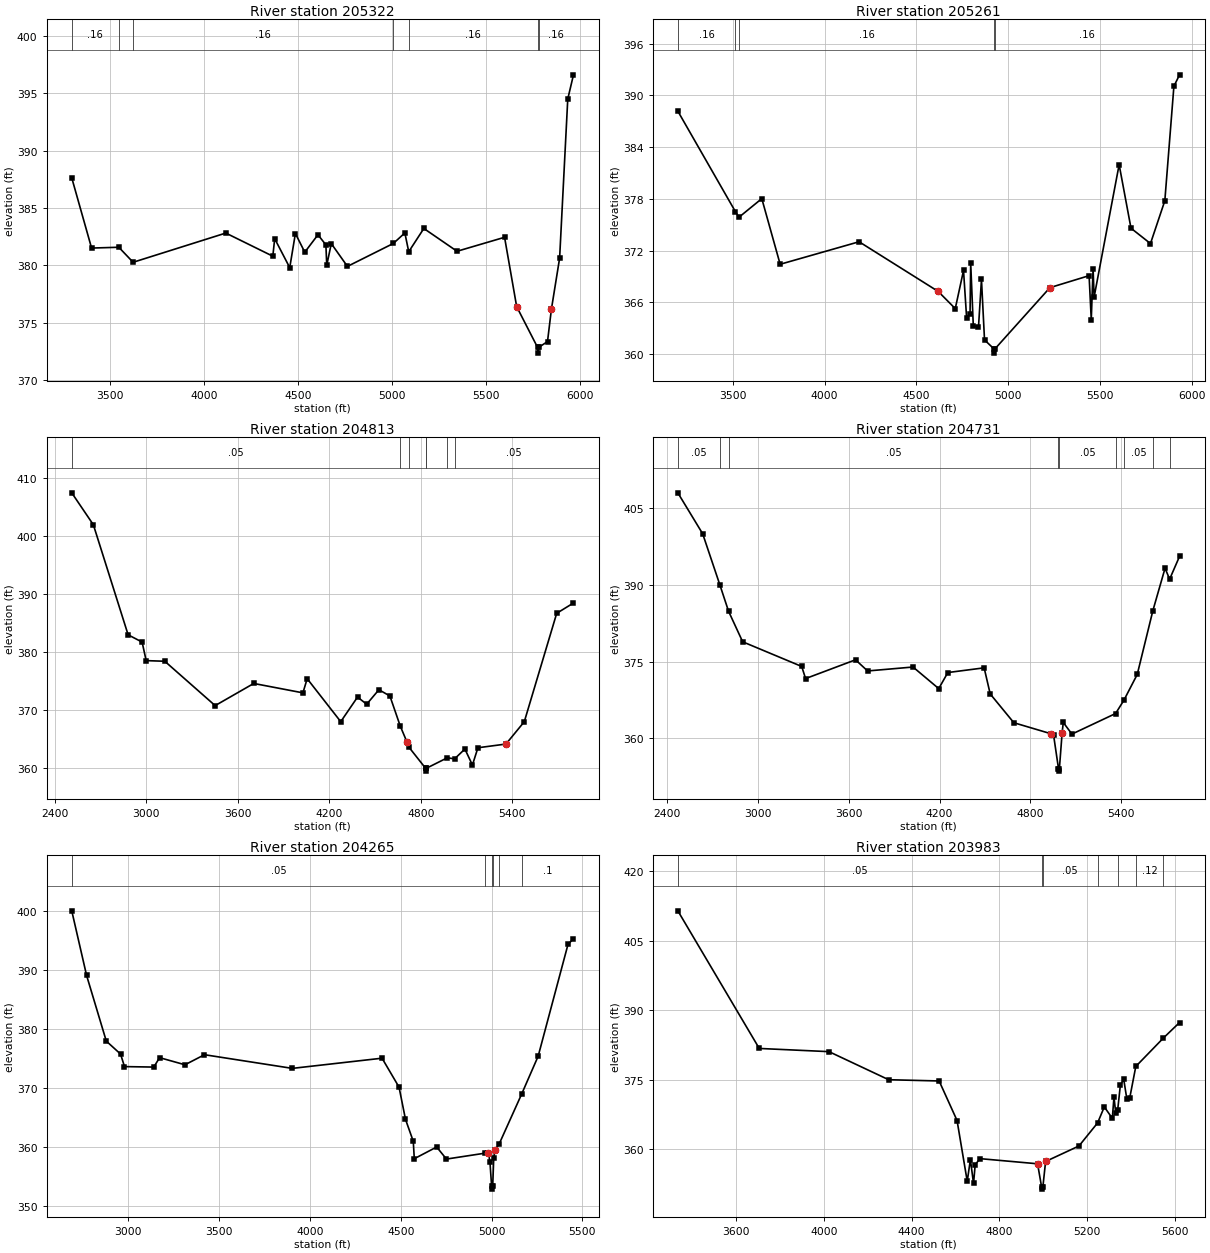
Type RM Length L Ch R = 1 ,205322  ,61,61,61
BEGIN DESCRIPTION:
Mapping XS 275b1338
END DESCRIPTION:
XS GIS Cut Line= 6
      3718836.49     10752747.61      3718534.38     10752889.98
      3717371.18     10752931.65      3717364.24     10753379.56
      3717180.21     10753660.81      3716895.46     10753879.58
#Sta/Elev= 30
  3296.7  387.63  3402.1   381.5  3546.9  381.57    3623  380.26  4115.8  382.81
  4365.8  380.79  4375.8  382.32  4455.8  379.79  4485.8  382.77  4535.8  381.14
  4605.8  382.66    4648  381.78  4652.6     380  4676.7  381.89  4762.6   379.9
  5006.4   381.9  5067.9  382.82  5088.5  381.18  5168.8  383.21  5345.4  381.22
  5598.1  382.44  5662.4  376.39  5773.6  372.83  5776.3  372.33  5779.6  372.83
  5826.4  373.34  5847.2  376.17  5890.8  380.62  5934.1  394.51  5964.5  396.62
#Mann= 7 ,-1 , 0
  3296.7     .16       0  3546.9     .05       0    3623     .16       0
  5006.4     .05       0  5088.5     .16       0  5773.6     .07       0
  5779.6     .16       0
Bank Sta=5662.4,5847.2
XS Rating Curve= 0 ,0
Exp/Cntr=0.3,0.1

Type RM Length L Ch R = 1 ,205261  ,448,448,448
BEGIN DESCRIPTION:
Mapping XS 16b2896d
END DESCRIPTION:
XS GIS Cut Line= 6
      3718838.22     10752710.28      3718534.38     10752868.71
      3717299.57     10752909.95      3717308.25     10753356.99
      3717184.55     10753578.35      3716854.71     10753847.86
#Sta/Elev= 30
  3200.6  388.18  3514.1  376.54  3533.6  375.88  3658.1  378.04  3758.1  370.43
  4188.2  373.04  4619.3  367.28  4712.2  365.29  4757.2  369.71    4774  364.25
  4792.7  364.66  4796.3  370.55  4810.5  363.29  4838.8  363.16    4855  368.67
  4871.6  361.66  4922.8  360.63  4925.6  360.13  4928.8  360.63  5227.9  367.72
  5441.4  369.11  5453.2  364.02  5463.1  369.91  5468.8  366.64  5605.1  381.98
  5669.7  374.61  5775.8  372.83    5854  377.79  5903.5  391.07  5934.3  392.39
#Mann= 5 ,-1 , 0
  3200.6     .16       0  3514.1     .05       0  3533.6     .16       0
  4922.8     .07       0  4928.8     .16       0
Bank Sta=4619.3,5227.9
XS Rating Curve= 0 ,0
Exp/Cntr=0.3,0.1

Type RM Length L Ch R = 1 ,204813  ,82,82,82
BEGIN DESCRIPTION:
CATFISH CREEK 191.0
END DESCRIPTION:
XS GIS Cut Line= 6
       3718919.2     10752220.15      3718580.67     10752480.55
      3718476.51     10752814.75      3717157.06     10752784.37
      3716987.79     10752849.47      3716319.77     10753595.57
#Sta/Elev= 30
  2510.8  407.42  2652.5  401.91  2880.4  382.93    2972  381.68  2998.7  378.48
  3120.8  378.37    3451  370.72  3704.1  374.54  4026.4  372.92  4054.3  375.36
  4274.4  367.95  4384.5  372.19  4444.5  370.96  4524.6  373.46  4596.7  372.38
  4664.6  367.19  4709.4  364.39  4719.6  363.61  4830.5  359.92  4833.2  359.42
  4836.5  359.92  4973.1  361.72  5020.8  361.54  5088.4  363.23  5137.8  360.47
  5173.7  363.45  5357.6  364.09  5477.9  367.95  5690.3  386.64  5800.3  388.42
#Mann= 7 ,-1 , 0
  2510.8     .05       0  4664.6     .16       0  4719.6     .05       0
  4830.5     .07       0  4836.5     .05       0  4973.1     .12       0
  5020.8     .05       0
Bank Sta=4709.4,5357.6
XS Rating Curve= 0 ,0
Exp/Cntr=0.3,0.1

Type RM Length L Ch R = 1 ,204731  ,466,466,466
BEGIN DESCRIPTION:
CATFISH CREEK 190.0
END DESCRIPTION:
XS GIS Cut Line= 6
      3718883.84     10752164.58      3718527.07     10752435.41
      3718464.57      10752745.3      3718415.09     10752768.74
      3717014.05     10752750.51       3716246.5     10753522.62
#Sta/Elev= 30
  2470.2  408.01  2634.5     400  2748.1  390.01  2805.5  384.86  2898.7  378.89
    3289  374.07  3314.5   371.7  3644.6  375.37  3724.6  373.19  4024.7  373.96
  4194.7  369.74  4254.8  372.88  4494.8   373.8  4534.8   368.7  4691.1  363.07
  4939.8  360.89  4954.1  360.58  4986.2  354.11    4989  353.61  4992.2  354.11
  5010.1  361.07  5017.8  363.12    5075  360.85  5363.7  364.87  5419.1   367.5
  5506.7  372.51  5610.1  384.99  5690.5  393.27  5720.8  391.13  5786.4   395.6
#Mann= 9 ,-1 , 0
  2470.2     .05       0  2748.1     .16       0  2805.5     .05       0
  4986.2     .04       0  4992.2     .05       0  5363.7     .16       0
  5419.1     .05       0  5610.1     .16       0  5720.8     .05       0
Bank Sta=4939.8,5010.1
XS Rating Curve= 0 ,0
Exp/Cntr=0.3,0.1

Type RM Length L Ch R = 1 ,204265  ,282,282,282
BEGIN DESCRIPTION:
CATFISH CREEK 189.0
END DESCRIPTION:
XS GIS Cut Line= 3
      3718539.86     10751894.92      3716508.63     10752693.53
      3716031.18      10753023.4
#Sta/Elev= 30
  2688.1  399.96  2769.9  389.03  2878.3  377.94  2956.9  375.75  2978.5  373.63
  3139.7  373.55  3171.9  375.14  3311.6  373.94    3419  375.64  3902.6  373.33
  4396.8  375.05  4490.4  370.16  4525.8  364.73  4568.8     361  4574.4  358.06
  4697.7  360.04  4751.4     358  4966.5  359.01  4982.1  359.03  4990.9  357.57
  5000.2  353.42  5002.9  352.92  5006.2  353.42  5011.8  358.13  5017.9  359.48
  5041.6  360.54  5165.2  368.96  5256.5  375.39  5420.7  394.27    5451  395.26
#Mann= 6 ,-1 , 0
  2688.1     .05       0  4966.5     .12       0  5000.2     .07       0
  5006.2     .12       0  5041.6     .05       0  5165.2      .1       0
Bank Sta=4982.1,5017.9
XS Rating Curve= 0 ,0
Exp/Cntr=0.3,0.1

Type RM Length L Ch R = 1 ,203983  ,356,356,356
BEGIN DESCRIPTION:
CATFISH CREEK 188.0
END DESCRIPTION:
XS GIS Cut Line= 3
      3716994.73      10751052.9      3716361.06     10752467.83
      3715736.03     10752858.47
#Sta/Elev= 30
    3334  411.41  3705.2  381.75  4023.1  381.06  4295.2  375.01  4525.3  374.74
    4607  366.22  4653.4  353.12  4667.8   357.8  4682.1  352.65  4689.7   356.7
  4711.6     358  4974.1  356.89  4992.3  351.93  4995.1  351.43  4998.3  351.93
  5010.7  357.39  5162.8  360.73  5247.7   365.7  5278.3  369.15  5314.9  366.69
  5322.4  371.31  5330.2  367.92  5339.3  368.52  5351.5  373.81  5366.8  375.12
  5381.3  370.79  5393.9     371  5421.9  377.87  5547.8     384  5621.4  387.34
#Mann= 7 ,-1 , 0
    3334     .05       0  4992.3     .03       0  4998.3     .05       0
  5247.7     .12       0  5339.3     .16       0  5421.9     .12       0
  5547.8      .1       0
Bank Sta=4974.1,5010.7
XS Rating Curve= 0 ,0
Exp/Cntr=0.3,0.1

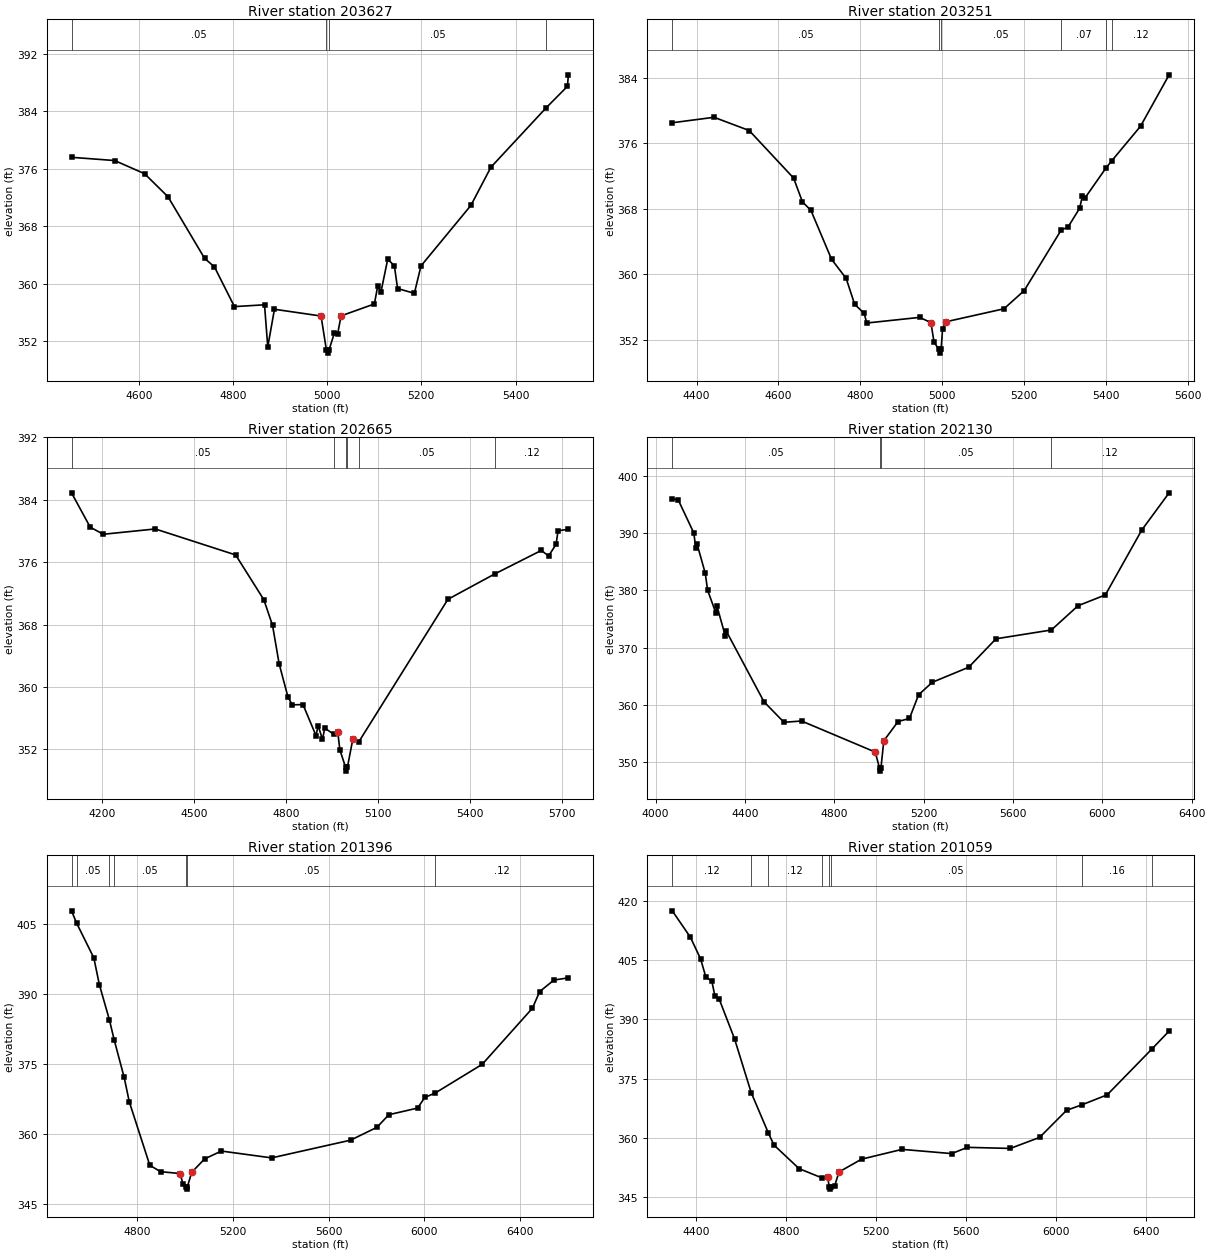
Type RM Length L Ch R = 1 ,203627  ,376,376,376
BEGIN DESCRIPTION:
CATFISH CREEK 187.0
END DESCRIPTION:
XS GIS Cut Line= 2
      3716447.83     10751868.91      3715684.33      10752597.7
#Sta/Elev= 30
  4456.8  377.58  4548.5  377.13    4612   375.3  4661.7   372.1  4739.4  363.54
  4760.5  362.33  4802.9  356.82  4866.8  357.07  4873.7  351.22  4887.9  356.45
  4986.9  355.51  4998.1  350.85  5000.8  350.35  5004.1  350.85  5015.2  353.14
  5022.1  353.01  5029.4  355.53  5100.2  357.19  5107.1  359.62  5114.3   358.9
  5128.5   363.4  5142.6  362.51  5149.5  359.33  5185.1  358.67  5199.2  362.48
  5305.2  370.89  5347.7   376.2  5464.4  384.42  5510.3  387.45  5512.3  389.05
#Mann= 4 ,-1 , 0
  4456.8     .05       0  4998.1     .03       0  5004.1     .05       0
  5464.4     .12       0
Bank Sta=4986.9,5029.4
XS Rating Curve= 0 ,0
Exp/Cntr=0.3,0.1

Type RM Length L Ch R = 1 ,203251  ,586,586,586
BEGIN DESCRIPTION:
CATFISH CREEK 186.0
END DESCRIPTION:
XS GIS Cut Line= 3
      3716242.56     10751400.06      3715898.79     10751875.79
      3715499.51      10752358.4
#Sta/Elev= 30
  4340.6  378.51  4442.6  379.18  4528.5  377.56  4636.9  371.75  4658.4  368.85
  4679.3  367.79  4729.6  361.82  4765.2  359.49    4786  356.32  4809.3  355.21
  4815.5  354.03  4944.8  354.72  4972.2  354.08  4979.9  351.68  4991.2  350.85
    4994  350.35  4997.2  350.85  5000.7   353.3  5008.6  354.18  5150.6  355.77
    5200  357.99  5290.5  365.41  5306.9  365.75  5335.5  368.07    5342  369.54
  5348.6  369.33  5400.4  373.03  5413.8  373.86    5484  378.08  5553.9  384.37
#Mann= 6 ,-1 , 0
  4340.6     .05       0  4991.2     .03       0  4997.2     .05       0
  5290.5     .07       0  5400.4     .16       0  5413.8     .12       0
Bank Sta=4972.2,5008.6
XS Rating Curve= 0 ,0
Exp/Cntr=0.3,0.1

Type RM Length L Ch R = 1 ,202665  ,535,535,535
BEGIN DESCRIPTION:
CATFISH CREEK 185.0
END DESCRIPTION:
XS GIS Cut Line= 3
      3716105.94     10750870.32      3715464.76     10751566.76
      3715315.45     10752223.04
#Sta/Elev= 30
  4100.7  384.88  4161.7  380.48  4204.2  379.57  4373.8  380.25  4635.8  376.92
  4727.7  371.18    4756   367.9  4777.6  362.96  4805.9  358.77  4820.1  357.71
  4855.3  357.75  4897.8  353.76  4904.6  355.06  4918.8  353.28  4926.2  354.73
  4955.6  353.95  4968.7   354.2  4975.5  351.94  4994.1  349.72  4996.8  349.22
  5000.1  349.72    5018  353.38  5037.8  353.01  5327.8  371.24  5479.6  374.47
  5632.2   377.5  5655.9  376.79  5680.3  378.28  5686.7  380.02  5720.4  380.21
#Mann= 6 ,-1 , 0
  4100.7     .05       0  4955.6     .07       0  4994.1     .07       0
  5000.1     .07       0  5037.8     .05       0  5479.6     .12       0
Bank Sta=4968.7,5018
XS Rating Curve= 0 ,0
Exp/Cntr=0.3,0.1

Type RM Length L Ch R = 1 ,202130  ,734,734,734
BEGIN DESCRIPTION:
CATFISH CREEK 184.0
END DESCRIPTION:
XS GIS Cut Line= 3
      3715420.19     10750336.48      3715199.61     10751260.19
      3714949.62     10752510.15
#Sta/Elev= 30
  4074.7  395.97  4101.5  395.81    4171  390.06  4180.5  387.34  4185.7  388.11
  4222.5     383  4232.9  380.05  4269.8  376.08    4275  377.26  4311.9  372.08
  4317.1  372.86  4485.4  360.56  4574.7  356.98  4653.8   357.2  4983.3  351.78
  5002.9  348.95  5005.7  348.45  5008.9  348.95  5021.8  353.75  5085.6  357.11
  5136.6  357.65  5177.4  361.77  5238.5  363.96  5401.7  366.59  5524.1  371.56
  5772.1   373.1  5891.2  377.33  6013.6  379.22  6176.8  390.56  6299.1  397.05
#Mann= 4 ,-1 , 0
  4074.7     .05       0  5002.9     .03       0  5008.9     .05       0
  5772.1     .12       0
Bank Sta=4983.3,5021.8
XS Rating Curve= 0 ,0
Exp/Cntr=0.3,0.1

Type RM Length L Ch R = 1 ,201396  ,337,337,337
BEGIN DESCRIPTION:
CATFISH CREEK 183.0
END DESCRIPTION:
XS GIS Cut Line= 3
      3715149.59     10750410.23      3714871.83     10750877.39
      3714849.61     10752410.23
#Sta/Elev= 30
  4525.8  407.87  4547.4   405.2  4619.2  397.75  4642.1  392.02    4684  384.48
  4704.2  380.14  4745.9  372.08  4767.3  366.84    4853  353.21    4898  351.84
  4979.5  351.44  4991.3  349.24  5003.9  348.59  5006.6  348.09  5009.9  348.59
  5028.3  351.71  5082.1  354.58  5152.1  356.27  5362.1   354.8  5692.2  358.61
  5802.2  361.37  5852.2  364.08  5972.2   365.5  6002.2  367.78  6046.6  368.76
  6242.2   374.9  6452.2  386.96  6482.2  390.52  6542.2  393.01  6602.3  393.47
#Mann= 7 ,-1 , 0
  4525.8     .12       0  4547.4     .05       0    4684     .07       0
  4704.2     .05       0  5003.9     .03       0  5009.9     .05       0
  6046.6     .12       0
Bank Sta=4979.5,5028.3
XS Rating Curve= 0 ,0
Exp/Cntr=0.3,0.1

Type RM Length L Ch R = 1 ,201059  ,830,830,830
BEGIN DESCRIPTION:
CATFISH CREEK 182.0
END DESCRIPTION:
XS GIS Cut Line= 3
       3714810.2     10750020.61      3714616.62     10750611.77
      3714684.33     10752195.07
#Sta/Elev= 30
  4294.2  417.46  4374.6   410.8    4420  405.31  4443.5  400.68  4470.1  399.64
  4483.2  396.02    4502  395.23  4570.9  385.06  4644.7  371.48  4720.9  361.26
  4746.2  358.18  4857.6  352.22  4957.6  349.92  4984.7  349.99  4991.7  347.54
  4994.5  347.04  4997.7  347.54  5014.8  347.73  5034.8  351.38  5134.9  354.62
    5315   357.1  5535.2  356.03  5605.3  357.61  5795.5  357.34  5925.6  360.12
  6045.7  366.99    6113  368.36  6225.9   370.9  6423.2  382.42    6501  387.04
#Mann= 8 ,-1 , 0
  4294.2     .12       0  4644.7     .07       0  4720.9     .12       0
  4957.6     .05       0  4991.7     .03       0  4997.7     .05       0
    6113     .16       0  6423.2     .12       0
Bank Sta=4984.7,5034.8
XS Rating Curve= 0 ,0
Exp/Cntr=0.3,0.1