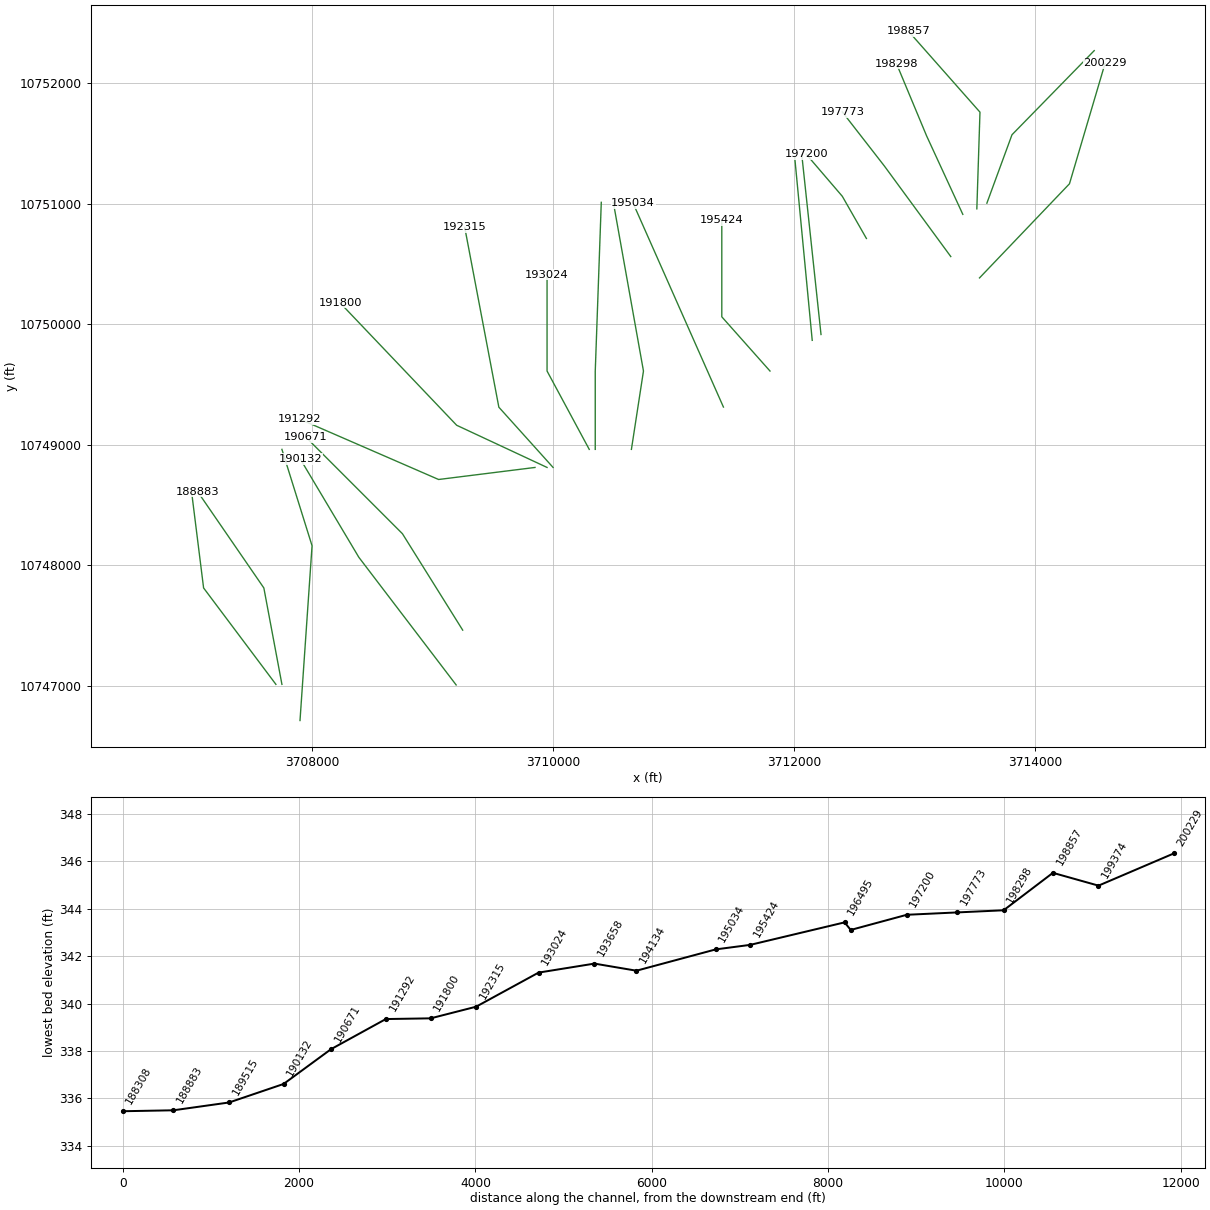
HEC-RAS study CATFISH CREEK.prj: CATFISH CREEK Base Level Engineering

--- CATFISH CREEK.g01 (geometry) --- (continued)

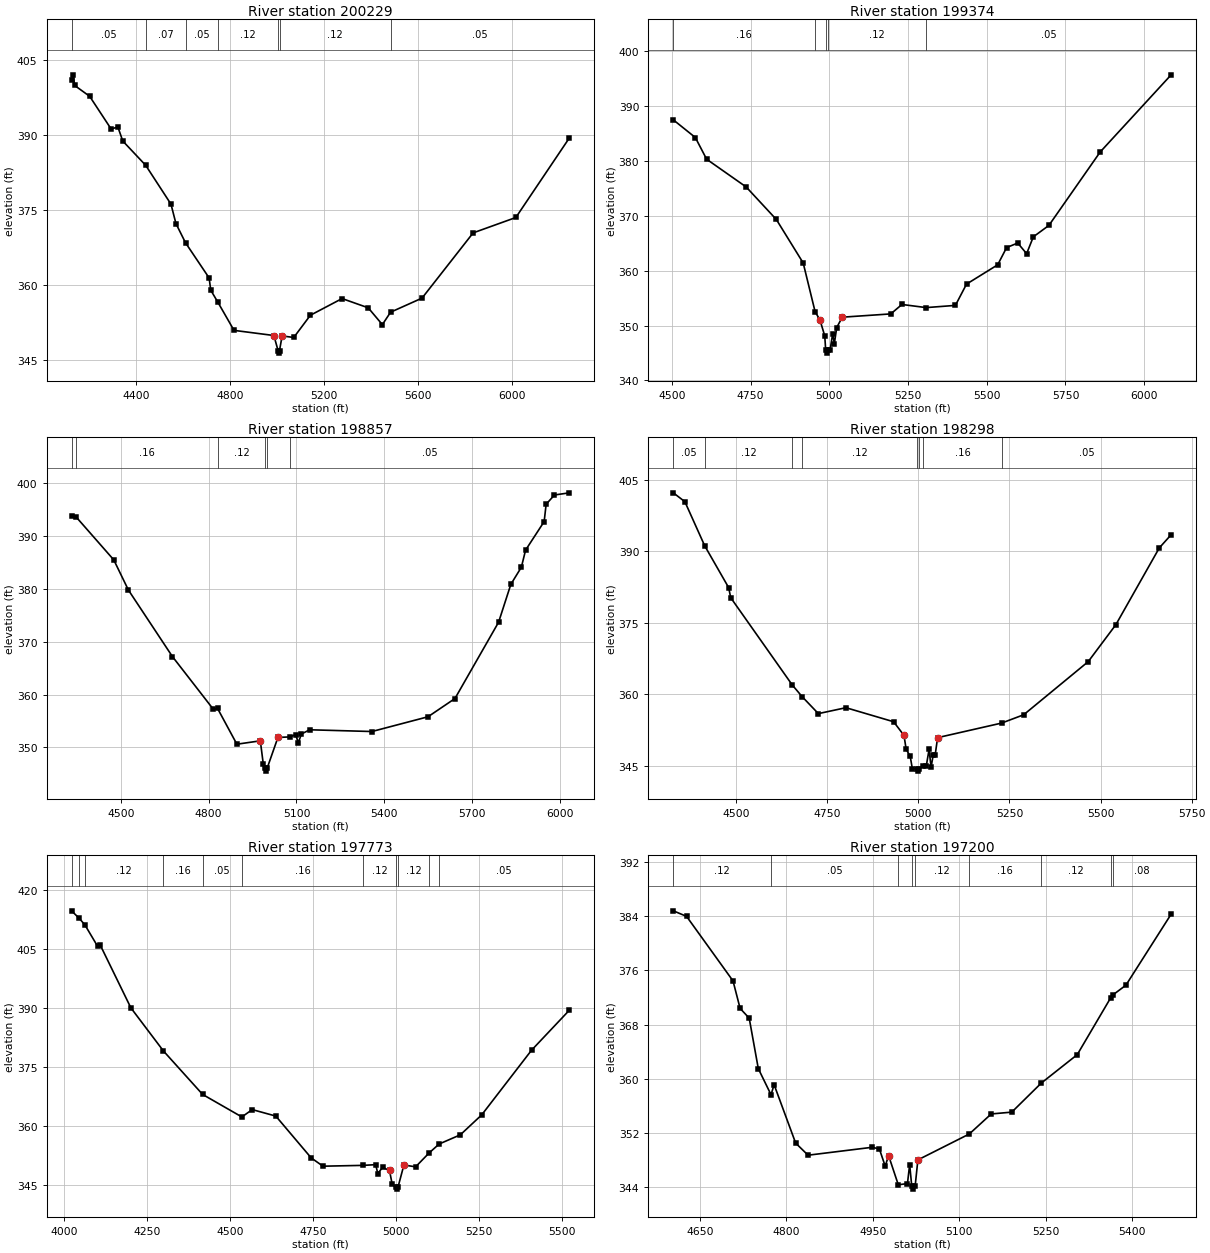
Type RM Length L Ch R = 1 ,200229  ,855,855,855
BEGIN DESCRIPTION:
CATFISH CREEK 181.0
END DESCRIPTION:
XS GIS Cut Line= 3
       3713538.1     10750382.84       3714284.6     10751164.06
      3714579.73     10752162.31
#Sta/Elev= 30
  4124.2  401.06  4130.5  402.09  4137.4  399.96  4201.3  397.79  4293.1  391.22
  4321.4  391.66  4342.5  388.83  4440.2  383.96  4547.9  376.18    4569   372.3
  4609.8  368.45  4710.5   361.4  4717.4  358.95  4747.6  356.55  4816.5   350.9
  4986.3  349.87  5004.4  346.84  5007.1  346.34  5010.4  346.84  5021.5  349.78
  5071.2  349.48    5142  353.93  5277.1  357.27  5388.4  355.42  5448.7  352.05
  5483.8  354.54  5617.8  357.36  5835.6  370.43  6017.6  373.51  6245.7  389.45
#Mann= 7 ,-1 , 0
  4124.2     .05       0  4440.2     .07       0  4609.8     .05       0
  4747.6     .12       0  5004.4     .07       0  5010.4     .12       0
  5483.8     .05       0
Bank Sta=4986.3,5021.5
XS Rating Curve= 0 ,0
Exp/Cntr=0.3,0.1

Type RM Length L Ch R = 1 ,199374  ,517,517,517
BEGIN DESCRIPTION:
CATFISH CREEK 180.0
END DESCRIPTION:
XS GIS Cut Line= 3
      3713599.25     10751003.08      3713807.59      10751570.8
      3714489.91     10752268.74
#Sta/Elev= 30
  4504.7   387.5  4574.6  384.28  4610.4  380.33    4736  375.27  4831.8  369.34
  4917.1  361.41  4954.9  352.53  4970.3  351.03  4985.5  348.12  4988.6  345.48
  4991.4  344.98  4994.6  345.48  5002.3  345.52  5010.7   348.5    5016  346.73
  5023.6  349.65  5041.1  351.53  5195.2  352.13  5230.7  353.85  5307.5  353.28
  5400.4  353.68  5435.7  357.56  5534.7  361.08    5563  364.22  5598.3  365.05
  5626.6  363.11  5647.9  366.18  5697.3  368.26  5860.1  381.64  6085.5  395.71
#Mann= 5 ,-1 , 0
  4504.7     .16       0  4954.9     .12       0  4988.6     .07       0
  4994.6     .12       0  5307.5     .05       0
Bank Sta=4970.3,5041.1
XS Rating Curve= 0 ,0
Exp/Cntr=0.3,0.1

Type RM Length L Ch R = 1 ,198857  ,559,559,559
BEGIN DESCRIPTION:
CATFISH CREEK 179.0
END DESCRIPTION:
XS GIS Cut Line= 3
      3713515.92     10750956.19      3713541.97      10751758.3
      3712948.19      10752430.2
#Sta/Elev= 30
  4332.3  393.73  4346.7  393.66  4476.4  385.47  4526.4  379.76  4676.5  367.19
  4816.6  357.19  4830.7  357.37  4896.6  350.61  4976.6  351.25  4986.6  346.92
  4993.6  346.02  4996.4  345.52  4999.6  346.02  5036.7  351.89  5077.8  351.99
  5096.7  352.41  5106.7  350.93  5116.7  352.53    5145  353.34  5357.5  353.01
    5549   355.8    5641  359.25  5789.9  373.68  5831.7  380.84  5867.7  384.09
    5882  387.31  5945.5  392.72  5952.2  395.99  5980.6  397.74  6031.5  398.15
#Mann= 6 ,-1 , 0
  4332.3     .05       0  4346.7     .16       0  4830.7     .12       0
  4993.6     .07       0  4999.6     .12       0  5077.8     .05       0
Bank Sta=4976.6,5036.7
XS Rating Curve= 0 ,0
Exp/Cntr=0.3,0.1

Type RM Length L Ch R = 1 ,198298  ,525,525,525
BEGIN DESCRIPTION:
CATFISH CREEK 178.0
END DESCRIPTION:
XS GIS Cut Line= 3
      3713399.63     10750910.15      3713099.61     10751560.19
      3712849.62     10752160.16
#Sta/Elev= 30
  4327.8  402.21  4359.5  400.35  4413.8  391.13  4479.7  382.35  4485.2  380.26
    4654  361.99    4681  359.55  4725.7  355.98  4801.4  357.22  4932.2  354.28
  4960.7  351.42  4966.6  348.51  4977.7  347.05  4983.6  344.45  4996.7  344.44
  4999.4  343.94  5002.7  344.44  5013.6   345.1  5021.7  344.96  5029.5  348.47
    5035  344.74    5041  347.41  5046.4  347.41  5052.9  350.95  5228.5     354
  5289.1  355.74  5466.2  366.87  5542.1  374.61  5661.2  390.68  5693.7  393.44
#Mann= 8 ,-1 , 0
  4327.8     .05       0  4413.8     .12       0    4654     .16       0
    4681     .12       0  4996.7     .07       0  5002.7     .12       0
  5013.6     .16       0  5228.5     .05       0
Bank Sta=4960.7,5052.9
XS Rating Curve= 0 ,0
Exp/Cntr=0.3,0.1

Type RM Length L Ch R = 1 ,197773  ,573,573,573
BEGIN DESCRIPTION:
CATFISH CREEK 177.0
END DESCRIPTION:
XS GIS Cut Line= 3
       3713299.6      10750560.2      3712749.61     10751310.19
      3712399.62     10751760.17
#Sta/Elev= 30
  4023.1   414.6  4046.7  412.65  4063.5     411  4101.4  405.61  4109.9  405.83
  4201.8  389.94  4299.9  378.98  4418.1  367.92  4536.3   362.2  4567.6  364.07
  4638.6  362.42  4745.1   351.8  4780.7  349.68    4902  349.89  4939.6  350.07
  4945.8  347.82  4960.4  349.36  4981.2   348.6  4989.3  345.07  5000.8  344.35
  5003.6  343.85  5006.8  344.35  5024.6  349.98  5059.9  349.52  5100.7  353.06
  5130.8  355.32  5194.7  357.66    5259  362.72  5409.2  379.16  5523.2  389.34
#Mann= 11 ,-1 , 0
  4023.1     .07       0  4046.7     .16       0  4063.5     .12       0
  4299.9     .16       0  4418.1     .05       0  4536.3     .16       0
    4902     .12       0  5000.8     .07       0  5006.8     .12       0
  5100.7     .16       0  5130.8     .05       0
Bank Sta=4981.2,5024.6
XS Rating Curve= 0 ,0
Exp/Cntr=0.3,0.1

Type RM Length L Ch R = 1 ,197200  ,636,636,636
BEGIN DESCRIPTION:
CATFISH CREEK 176.0
END DESCRIPTION:
XS GIS Cut Line= 3
       3712599.6     10750710.21      3712399.61     10751060.19
      3712099.59     10751410.21
#Sta/Elev= 30
  4603.9  384.77  4626.9  383.95  4707.5  374.44  4719.8  370.39  4735.6  368.95
  4751.4  361.51  4773.5  357.66  4778.8  359.15  4816.2  350.54  4837.8  348.75
  4949.4  349.92  4961.6  349.66  4971.7  347.13  4977.5   348.7  4994.4  344.39
  5010.3  344.57  5014.1  347.37  5017.7  344.25  5020.5  343.75  5023.7  344.25
  5028.4  348.06  5117.7  351.88  5155.7  354.83  5191.4   355.1  5242.7  359.39
    5305  363.57  5363.2  371.97  5367.6  372.42  5389.5  373.81    5468  384.28
#Mann= 9 ,-1 , 0
  4603.9     .12       0  4773.5     .05       0  4994.4     .12       0
  5017.7     .07       0  5023.7     .12       0  5117.7     .16       0
  5242.7     .12       0  5363.2     .16       0  5367.6     .08       0
Bank Sta=4977.5,5028.4
XS Rating Curve= 0 ,0
Exp/Cntr=0.3,0.1

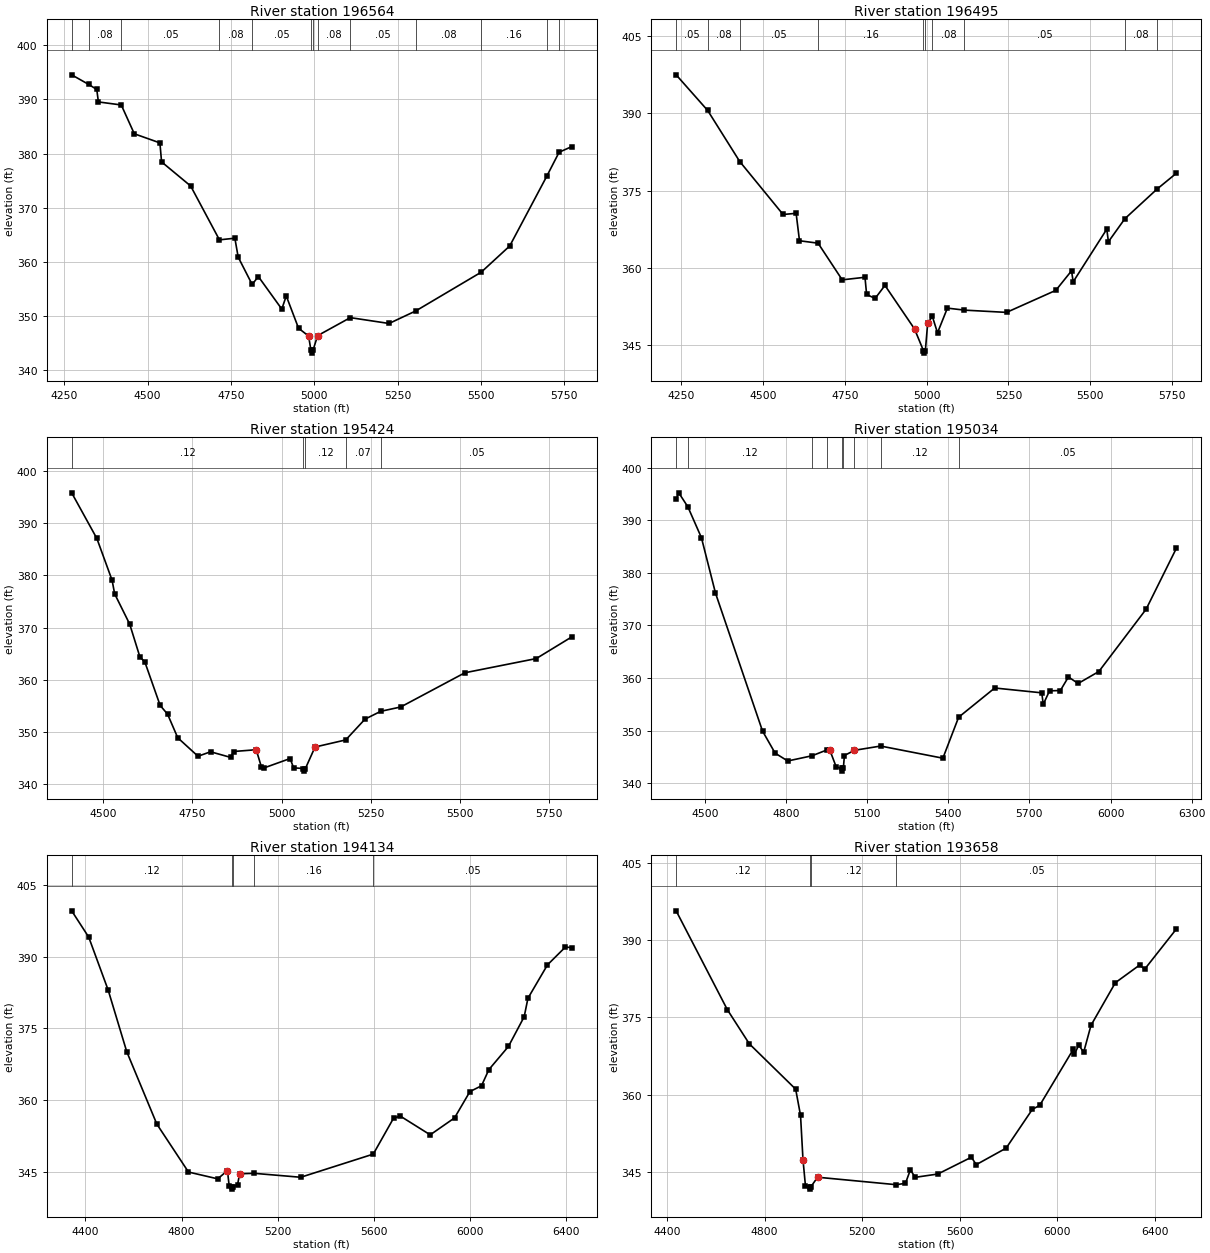
Type RM Length L Ch R = 1 ,196564  ,69,69,69
BEGIN DESCRIPTION:
CATFISH CREEK 175.0
END DESCRIPTION:
XS GIS Cut Line= 2
      3712222.92     10749913.39      3712063.27     10751405.77
#Sta/Elev= 30
  4272.3  394.55  4322.9  392.79  4347.5  391.85  4352.5  389.54  4421.1  388.98
  4460.2  383.65    4537  381.97    4542  378.46  4629.3     374  4715.6  364.05
  4761.9  364.35  4771.9  360.85  4813.8   355.8  4832.3  357.27  4902.7  351.25
  4916.1  353.68    4953  347.71  4983.1  346.27  4990.2  343.61  4992.9  343.11
  4996.2  343.61  5010.2  346.34  5108.3  349.67  5224.5  348.59  5304.7  350.91
    5501  358.07  5586.6  362.92  5697.4  375.77  5734.7  380.24  5773.2   381.3
#Mann= 13 ,-1 , 0
  4272.3     .05       0  4322.9     .08       0  4421.1     .05       0
  4715.6     .08       0  4813.8     .05       0  4990.2     .04       0
  4996.2     .05       0  5010.2     .08       0  5108.3     .05       0
  5304.7     .08       0    5501     .16       0  5697.4     .08       0
  5734.7     .05       0
Bank Sta=4983.1,5010.2
XS Rating Curve= 0 ,0
Exp/Cntr=0.3,0.1

Type RM Length L Ch R = 1 ,196495  ,1071,1071,1071
BEGIN DESCRIPTION:
CATFISH CREEK 174.0
END DESCRIPTION:
XS GIS Cut Line= 2
        3712150.     10749864.79      3712004.35     10751387.13
#Sta/Elev= 30
  4234.2  397.47  4330.6  390.55  4428.7  380.63  4561.1  370.35    4601  370.58
  4611.3  365.25  4668.1  364.78  4741.9  357.66  4811.5  358.16  4816.5  354.83
  4842.4  354.04  4872.5  356.58  4962.9  348.13  4990.1  343.93  4992.8  343.43
  4996.1  343.93  5003.1  349.19  5017.4  350.57  5033.2  347.37  5063.4  352.17
  5115.5  351.78  5244.2  351.34  5394.9  355.62  5442.9  359.41    5448  357.28
  5550.7   367.5  5555.7  365.06    5606  369.53  5704.1  375.27  5763.5  378.36
#Mann= 10 ,-1 , 0
  4234.2     .05       0  4330.6     .08       0  4428.7     .05       0
  4668.1     .16       0  4990.1     .07       0  4996.1     .16       0
  5017.4     .08       0  5115.5     .05       0    5606     .08       0
  5704.1     .05       0
Bank Sta=4962.9,5003.1
XS Rating Curve= 0 ,0
Exp/Cntr=0.3,0.1

Type RM Length L Ch R = 1 ,195424  ,390,390,390
BEGIN DESCRIPTION:
CATFISH CREEK 173.0
END DESCRIPTION:
XS GIS Cut Line= 3
      3711799.59     10749610.21      3711399.61     10750060.19
      3711399.61     10750860.23
#Sta/Elev= 30
  4411.9  395.81  4482.5  387.06  4525.2  379.05  4532.3  376.46  4574.5  370.65
    4603  364.39  4617.2  363.35  4659.8  355.08  4680.7  353.39  4709.2  348.87
    4766  345.33  4801.1  346.19    4858   345.1  4865.5  346.24  4929.1  346.58
  4943.3  343.36    4950  343.07    5024  344.89    5034  343.11    5061  342.98
  5063.7  342.48    5067  342.98    5094   347.1    5180  348.46    5234  352.44
    5278  353.94    5334  354.77    5514  361.33    5714  364.05    5814  368.22
#Mann= 5 ,-1 , 0
  4411.9     .12       0    5061     .07       0    5067     .12       0
    5180     .07       0    5278     .05       0
Bank Sta=4929.1,5094
XS Rating Curve= 0 ,0
Exp/Cntr=0.3,0.1

Type RM Length L Ch R = 1 ,195034  ,900,900,900
BEGIN DESCRIPTION:
CATFISH CREEK 172.0
END DESCRIPTION:
XS GIS Cut Line= 2
      3711413.19     10749311.28      3710663.89     10751002.42
#Sta/Elev= 30
  4393.9  394.03  4403.6  395.22  4437.3  392.55  4487.4  386.69  4539.4  376.15
  4713.3  349.91  4759.9  345.71  4806.5  344.22  4896.3  345.21  4951.9  346.33
  4962.5  346.24  4985.8  343.08  5006.1  342.79  5008.9  342.29  5012.1  342.79
  5016.1  345.26  5053.2  346.25  5150.1  347.06  5380.2  344.75  5438.4  352.54
  5571.9   358.1  5745.8  357.18  5751.3     355  5774.6  357.56  5814.6  357.62
  5844.4   360.2  5880.2  358.96  5956.8  361.23  6131.8   373.1  6243.6  384.68
#Mann= 9 ,-1 , 0
  4393.9     .05       0  4437.3     .12       0  4896.3     .16       0
  4951.9     .12       0  5006.1     .07       0  5012.1     .12       0
  5053.2     .16       0  5150.1     .12       0  5438.4     .05       0
Bank Sta=4962.5,5053.2
XS Rating Curve= 0 ,0
Exp/Cntr=0.3,0.1

Type RM Length L Ch R = 1 ,194134  ,476,476,476
BEGIN DESCRIPTION:
CATFISH CREEK 171.0
END DESCRIPTION:
XS GIS Cut Line= 3
      3710649.61     10748960.19      3710749.61     10749610.19
      3710499.61     10751010.19
#Sta/Elev= 30
  4343.2  399.57    4414  394.08    4495  382.99  4572.1  370.13  4697.3  354.98
  4828.8  344.96  4950.3  343.54  4990.7  345.26  4998.3  341.95    5008  341.89
  5010.8  341.39    5014  341.89  5032.8  342.31  5041.5  344.61  5102.5  344.69
  5295.4  343.87    5597  348.71  5681.4  356.22  5709.4  356.66  5833.8  352.74
  5934.9  356.28  5998.9  361.78  6047.1     363  6077.6  366.37  6158.9  371.21
  6224.4  377.42  6240.1  381.29  6321.4  388.28  6396.1  392.01    6423  391.86
#Mann= 5 ,-1 , 0
  4343.2     .12       0    5008     .07       0    5014     .12       0
  5102.5     .16       0    5597     .05       0
Bank Sta=4990.7,5041.5
XS Rating Curve= 0 ,0
Exp/Cntr=0.3,0.1

Type RM Length L Ch R = 1 ,193658  ,634,634,634
BEGIN DESCRIPTION:
CATFISH CREEK 170.0
END DESCRIPTION:
XS GIS Cut Line= 3
      3710349.61     10748960.18      3710349.61     10749610.19
      3710399.61     10751010.18
#Sta/Elev= 30
  4437.4   395.7  4647.4  376.51  4737.4  369.89  4927.4  361.09  4947.4  355.99
  4957.4  347.43  4967.4  342.38  4984.4  342.19  4987.2  341.69  4990.4  342.19
  5017.4     344  5339.9  342.55  5377.6  342.82  5397.6  345.43  5417.6  343.98
  5510.2  344.62  5647.8  347.88  5667.8  346.44  5790.4  349.65  5897.9  357.18
  5927.9  357.94  6065.5  368.82  6070.5  367.88    6088  369.66  6108.1  368.24
  6138.1  373.47  6238.1  381.75  6338.2   385.2  6358.2  384.37  6488.3  392.18
#Mann= 4 ,-1 , 0
  4437.4     .12       0  4984.4     .07       0  4990.4     .12       0
  5339.9     .05       0
Bank Sta=4957.4,5017.4
XS Rating Curve= 0 ,0
Exp/Cntr=0.3,0.1

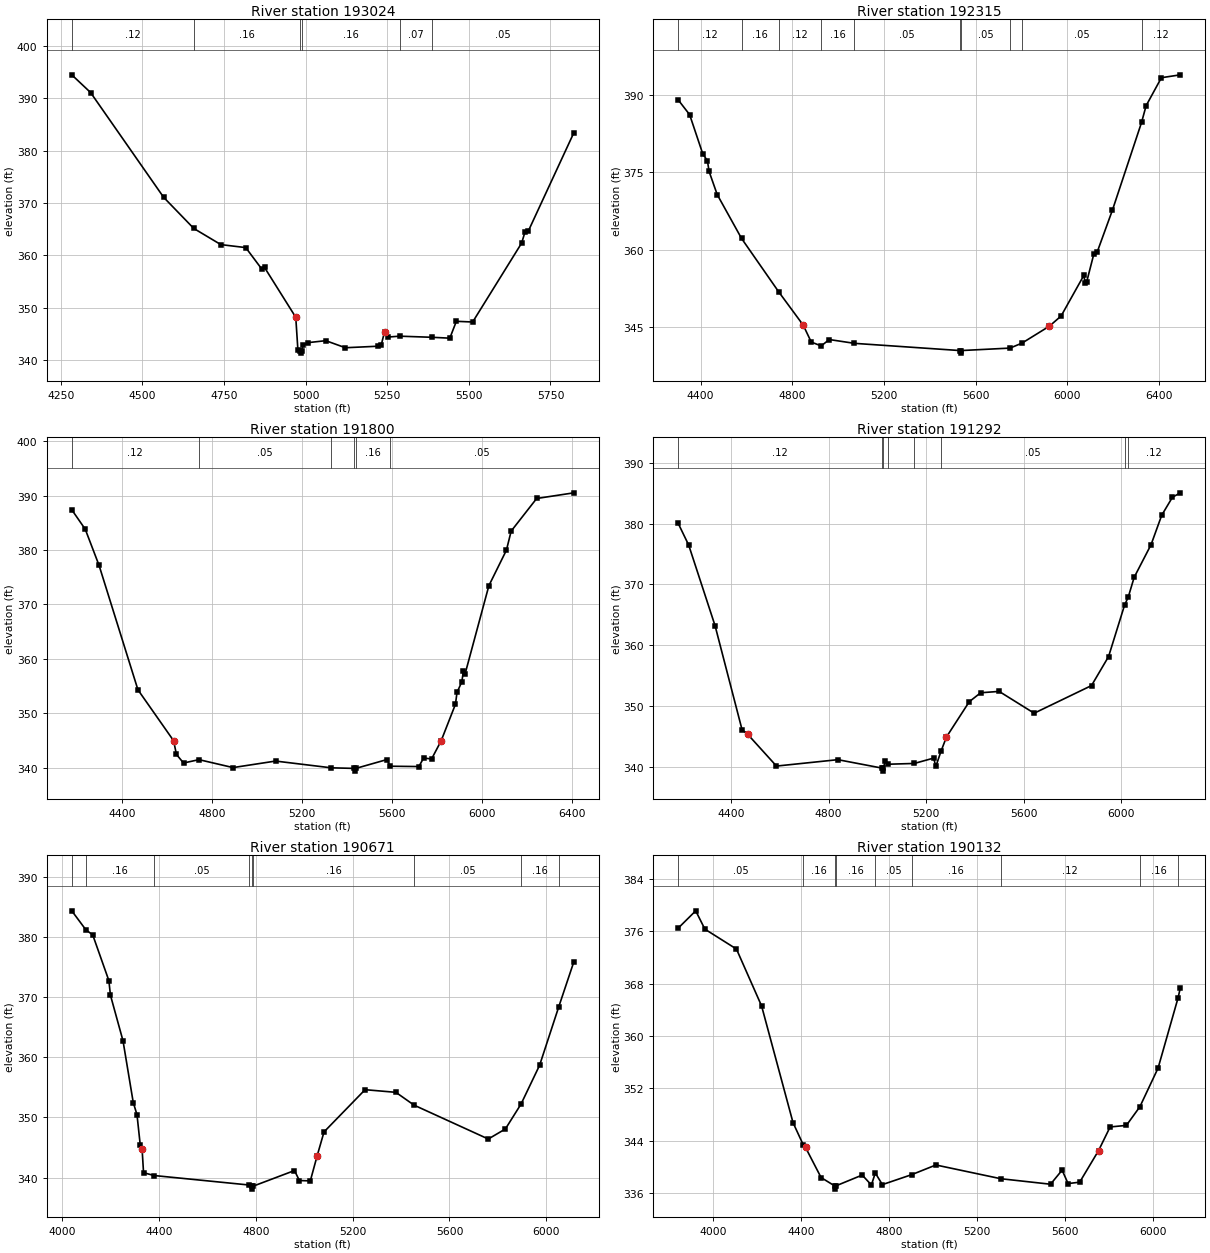
Type RM Length L Ch R = 1 ,193024  ,709,709,709
BEGIN DESCRIPTION:
CATFISH CREEK 169.0
END DESCRIPTION:
XS GIS Cut Line= 3
      3710299.62     10748960.17      3709949.61     10749610.19
      3709949.61     10750410.23
#Sta/Elev= 30
  4283.4   394.5    4341  391.12  4564.9  371.09  4657.2  365.14  4740.2  362.05
  4816.4  361.48  4865.9  357.35    4874  357.68  4969.7  348.16  4976.2  341.95
    4983  341.81  4985.7  341.31    4989  341.81  4991.6  342.78  5007.9  343.32
  5061.7  343.69  5121.7  342.34  5221.7  342.63  5231.7   342.9  5241.7   345.4
  5251.7  344.38  5287.6  344.55  5385.6  344.34  5441.7  344.17  5461.7  347.39
  5511.7  347.26  5661.7  362.34  5671.7  364.39  5681.7  364.57  5821.7  383.43
#Mann= 6 ,-1 , 0
  4283.4     .12       0  4657.2     .16       0    4983     .07       0
    4989     .16       0  5287.6     .07       0  5385.6     .05       0
Bank Sta=4969.7,5241.7
XS Rating Curve= 0 ,0
Exp/Cntr=0.3,0.1

Type RM Length L Ch R = 1 ,192315  ,515,515,515
BEGIN DESCRIPTION:
CATFISH CREEK 168.0
END DESCRIPTION:
XS GIS Cut Line= 3
      3709999.58     10748810.22      3709549.61     10749310.19
      3709266.71     10750801.24
#Sta/Elev= 30
  4302.7  389.07  4352.4  386.21  4409.2  378.66  4430.1  377.22  4437.2  375.19
  4472.7  370.68    4579  362.15  4741.3  351.76  4847.9  345.31    4883  342.02
  4926.4  341.27  4961.5  342.51  5071.6  341.77  5531.4  340.37  5534.1  339.87
  5537.4  340.37  5750.3  340.85  5802.5  341.82  5921.9  345.11  5972.9  347.08
  6072.3  354.99  6077.4  353.43  6084.8  353.76  6115.3  359.06  6129.7  359.43
  6196.8  367.65  6323.9   384.7  6343.8  387.95  6410.5  393.39    6493  393.95
#Mann= 10 ,-1 , 0
  4302.7     .12       0    4579     .16       0  4741.3     .12       0
  4926.4     .16       0  5071.6     .05       0  5531.4     .07       0
  5537.4     .05       0  5750.3     .12       0  5802.5     .05       0
  6323.9     .12       0
Bank Sta=4847.9,5921.9
XS Rating Curve= 0 ,0
Exp/Cntr=0.3,0.1

Type RM Length L Ch R = 1 ,191800  ,508,508,508
BEGIN DESCRIPTION:
CATFISH CREEK 167.0
END DESCRIPTION:
XS GIS Cut Line= 3
      3709949.59      10748810.2      3709199.61     10749160.19
      3708231.99     10750176.22
#Sta/Elev= 30
  4177.5  387.41  4237.4  383.83  4298.9  377.17  4471.5  354.32  4629.9  344.97
  4642.5  342.45  4674.1  340.87  4742.6  341.49    4894  340.03    5083  341.23
  5329.6  339.99  5433.5  339.88  5436.3  339.38  5439.5  339.88  5578.1  341.51
  5592.2  340.28  5719.6  340.22  5740.7  341.78  5776.2  341.62  5818.7  344.96
  5882.2  351.67  5889.1  353.84  5910.5  355.79  5917.4  357.72  5924.7   357.2
  6030.7  373.46  6108.7  379.99  6129.7  383.49    6243  389.48  6408.2  390.52
#Mann= 6 ,-1 , 0
  4177.5     .12       0  4742.6     .05       0  5329.6     .16       0
  5433.5     .03       0  5439.5     .16       0  5592.2     .05       0
Bank Sta=4629.9,5818.7
XS Rating Curve= 0 ,0
Exp/Cntr=0.3,0.1

Type RM Length L Ch R = 1 ,191292  ,621,621,621
BEGIN DESCRIPTION:
CATFISH CREEK 166.0
END DESCRIPTION:
XS GIS Cut Line= 3
      3709849.63     10748810.19      3709049.61     10748710.19
      3707899.65     10749210.17
#Sta/Elev= 30
  4182.7  380.02  4225.6  376.47  4333.9  363.22  4444.7  346.13  4467.4  345.41
  4585.8  340.18  4837.8  341.23  5018.4  339.85  5021.1  339.35  5024.4  339.85
  5032.6  341.08  5041.5  340.48  5151.2  340.61  5230.8  341.49  5239.7  340.12
    5261  342.62  5283.4  344.96  5376.9  350.75  5423.8  352.22  5499.5  352.44
  5643.2  348.86  5878.5   353.4  5948.5  358.16  6013.9  366.58  6029.5  367.96
  6053.5  371.17    6123  376.55  6166.6  381.37  6210.5  384.32  6242.9  385.05
#Mann= 8 ,-1 , 0
  4182.7     .12       0  5018.4     .07       0  5024.4     .12       0
  5041.5     .07       0  5151.2     .16       0    5261     .05       0
  6013.9     .16       0  6029.5     .12       0
Bank Sta=4467.4,5283.4
XS Rating Curve= 0 ,0
Exp/Cntr=0.3,0.1

Type RM Length L Ch R = 1 ,190671  ,539,539,539
BEGIN DESCRIPTION:
CATFISH CREEK 165.0
END DESCRIPTION:
XS GIS Cut Line= 3
      3709249.61     10747460.19      3708749.61     10748260.19
      3707949.59     10749060.21
#Sta/Elev= 30
  4039.2  384.34  4097.2   381.2  4125.9  380.33  4192.5  372.74    4199  370.32
  4250.9  362.74  4293.3  352.47  4308.7  350.46  4322.2  345.41  4329.9  344.69
  4335.8  340.81  4379.7  340.34  4770.6  338.77  4783.3  338.58    4786  338.08
  4789.3  338.58  4959.6  341.17  4979.7  339.51    5025  339.45  5053.3  343.63
  5081.6  347.59  5251.3  354.61  5378.6  354.17  5453.7  352.04  5760.4  346.41
  5831.1  348.08  5895.9  352.23  5972.6  358.68    6052  368.43    6114  375.87
#Mann= 9 ,-1 , 0
  4039.2     .05       0  4097.2     .16       0  4379.7     .05       0
  4770.6     .16       0  4783.3     .07       0  4789.3     .16       0
  5453.7     .05       0  5895.9     .16       0    6052     .12       0
Bank Sta=4329.9,5053.3
XS Rating Curve= 0 ,0
Exp/Cntr=0.3,0.1

Type RM Length L Ch R = 1 ,190132  ,617,617,617
BEGIN DESCRIPTION:
CATFISH CREEK 164.0
END DESCRIPTION:
XS GIS Cut Line= 3
      3709195.32     10747005.35      3708388.04     10748064.35
      3707901.93     10748880.32
#Sta/Elev= 30
    3842   376.5  3921.4  379.14  3963.1  376.34  4106.5   373.3  4220.8   364.6
  4363.6  346.77  4410.6  343.34  4420.4  342.98  4491.1  338.38  4552.5  337.11
  4555.2  336.61  4558.5  337.11    4678  338.76  4719.7  337.24  4737.4  339.08
  4769.6   337.3  4903.5  338.83  5012.8   340.3  5307.7   338.2  5533.7  337.36
  5586.3  339.51  5613.5  337.46  5666.1  337.67  5751.8  342.49  5804.4  346.11
  5878.3  346.35  5939.5  349.19  6022.4  355.11  6113.2  365.84  6123.4  367.37
#Mann= 9 ,-1 , 0
    3842     .05       0  4410.6     .16       0  4552.5     .07       0
  4558.5     .16       0  4737.4     .05       0  4903.5     .16       0
  5307.7     .12       0  5939.5     .16       0  6113.2     .12       0
Bank Sta=4420.4,5751.8
XS Rating Curve= 0 ,0
Exp/Cntr=0.3,0.1

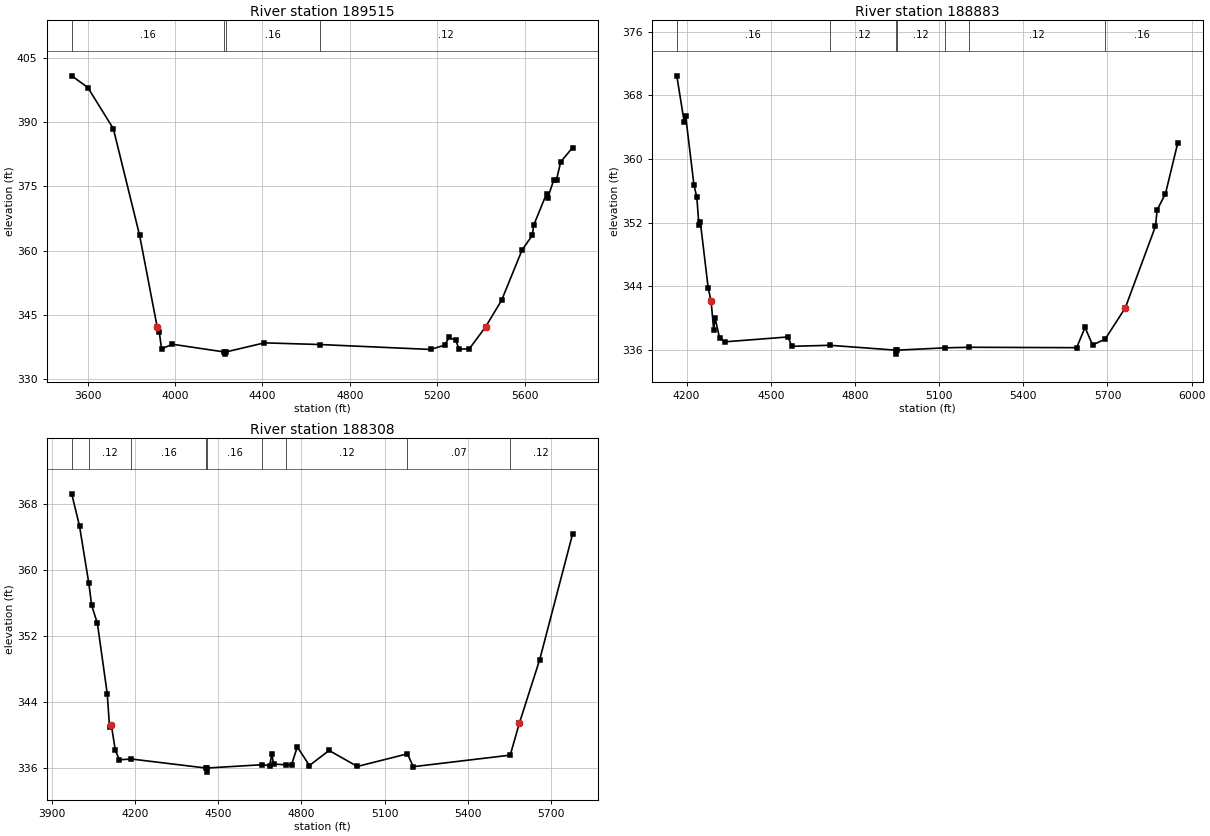
Type RM Length L Ch R = 1 ,189515  ,632,632,632
BEGIN DESCRIPTION:
CATFISH CREEK 163.0
END DESCRIPTION:
XS GIS Cut Line= 3
      3707899.61     10746710.17      3707999.61     10748160.19
      3707749.61     10748960.18
#Sta/Elev= 30
  3527.4  400.78  3601.3  398.04  3717.9  388.44  3838.1  363.54  3918.3  342.22
  3928.4  340.89  3938.4  337.08  3988.5  338.13  4226.1  336.33  4228.8  335.83
  4232.1  336.33  4409.5  338.46  4663.6  338.07    5170  336.92  5234.9  337.94
  5253.3  339.72  5284.7  339.07  5299.9  336.95  5347.5  337.12  5420.9  342.17
  5494.2  348.38  5588.5  360.18  5635.1  363.55  5640.9  365.87  5700.1  373.28
  5705.3  372.27  5732.6   376.4  5745.7  376.55  5765.1  380.73    5819     384
#Mann= 4 ,-1 , 0
  3527.4     .16       0  4226.1     .07       0  4232.1     .16       0
  4663.6     .12       0
Bank Sta=3918.3,5420.9
XS Rating Curve= 0 ,0
Exp/Cntr=0.3,0.1

Type RM Length L Ch R = 1 ,188883  ,575,575,575
BEGIN DESCRIPTION:
CATFISH CREEK 162.0
END DESCRIPTION:
XS GIS Cut Line= 3
      3707749.62     10747010.15      3707599.61     10747810.19
      3707049.61     10748610.18
#Sta/Elev= 30
  4165.3  370.46  4191.6  364.66  4196.7  365.46  4226.4  356.74  4236.6  355.21
  4244.2   351.7  4249.3  352.06  4277.3  343.76  4287.4  342.18  4296.8  338.54
  4301.8  340.03    4318  337.48  4338.3  337.05  4562.1  337.66  4574.9  336.48
  4710.5  336.61  4944.9     336  4947.7   335.5  4950.9     336    5122  336.29
  5206.6  336.36  5590.2  336.31    5620  338.85    5647  336.65  5691.8  337.39
  5763.4   341.3    5871  351.55  5877.3  353.64  5906.8  355.66  5950.1  361.97
#Mann= 7 ,-1 , 0
  4165.3     .16       0  4710.5     .12       0  4944.9     .07       0
  4950.9     .12       0    5122     .07       0  5206.6     .12       0
  5691.8     .16       0
Bank Sta=4287.4,5763.4
XS Rating Curve= 0 ,0
Exp/Cntr=0.3,0.1

Type RM Length L Ch R = 1 ,188308  ,454,454,454
BEGIN DESCRIPTION:
CATFISH CREEK 161.0
END DESCRIPTION:
XS GIS Cut Line= 3
       3707699.6      10747010.2      3707099.61     10747810.19
      3706999.61     10748610.18
#Sta/Elev= 30
  3971.5  369.24  3999.6  365.34  4033.2  358.38  4043.4  355.71  4064.2  353.51
  4099.6  344.97  4107.9  340.98  4114.2  341.22  4128.8  338.11  4143.4  336.96
  4186.7  337.05  4454.9  335.96  4457.7  335.46  4460.9  335.96  4658.1  336.36
    4685  336.25  4693.4  337.61  4699.6  336.44  4743.3  336.35  4764.2  336.32
    4785  338.53  4828.8  336.26  4899.6  338.09  5001.7  336.15  5182.2  337.68
  5203.3  336.12  5552.9  337.52  5586.2  341.43  5659.3  349.12  5777.7  364.34
#Mann= 9 ,-1 , 0
  3971.5     .16       0  4033.2     .12       0  4186.7     .16       0
  4454.9     .07       0  4460.9     .16       0  4658.1     .07       0
  4743.3     .12       0  5182.2     .07       0  5552.9     .12       0
Bank Sta=4114.2,5586.2
XS Rating Curve= 0 ,0
Exp/Cntr=0.3,0.1