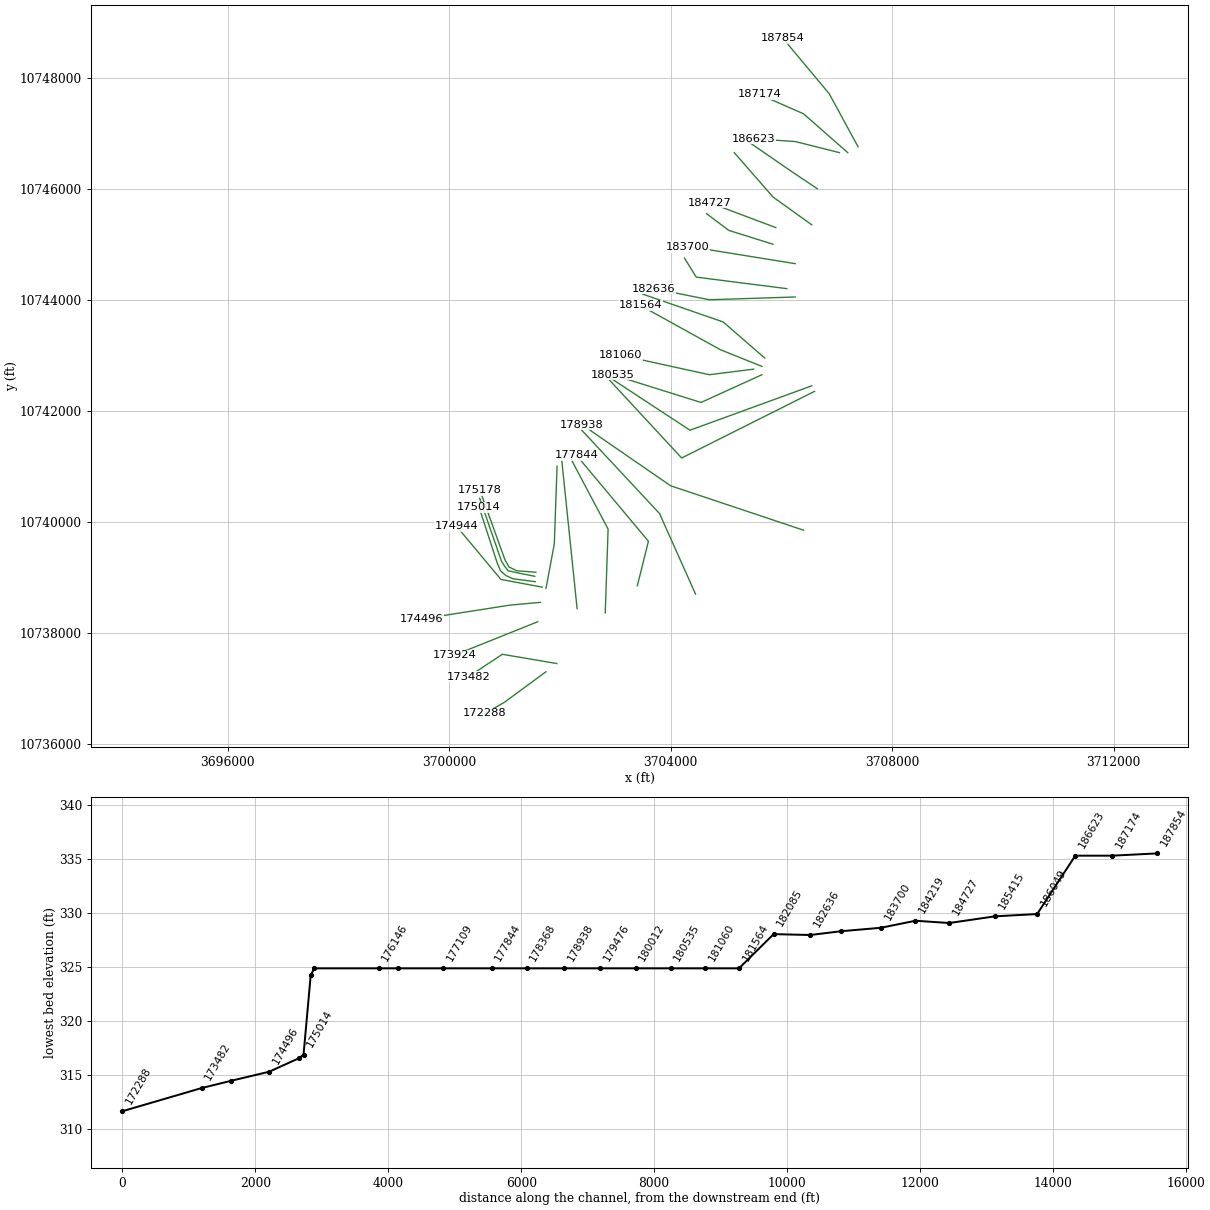
HEC-RAS study CATFISH CREEK.prj: CATFISH CREEK Base Level Engineering

--- CATFISH CREEK.g01 (geometry) --- (continued)

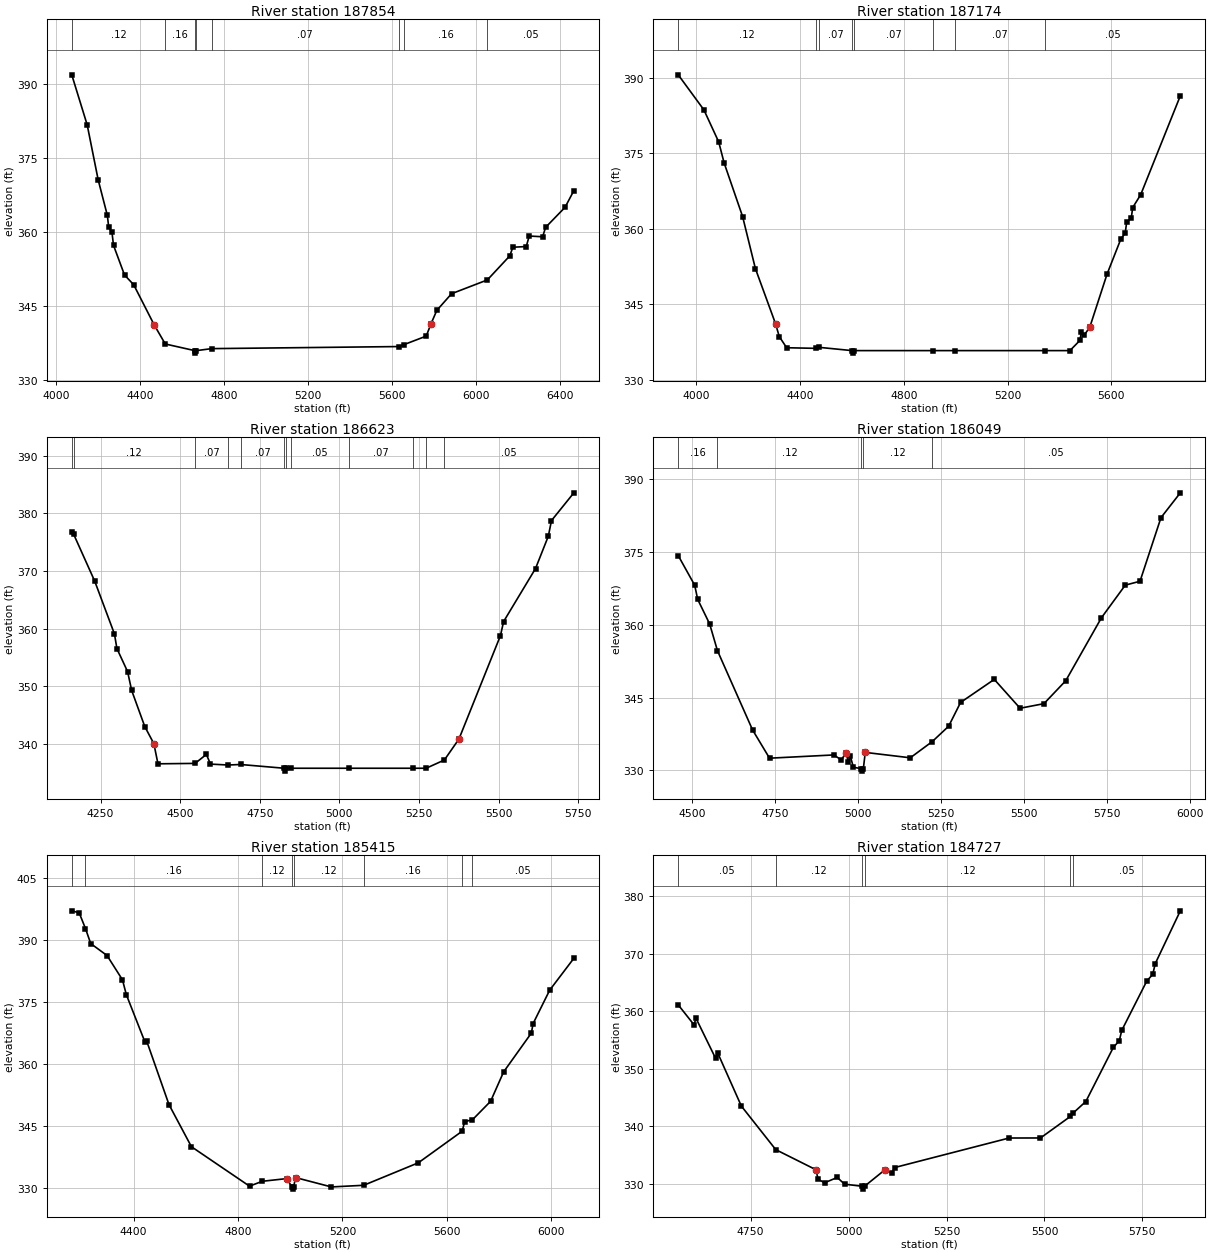
Type RM Length L Ch R = 1 ,187854  ,680,680,680
BEGIN DESCRIPTION:
CATFISH CREEK 160.0
END DESCRIPTION:
XS GIS Cut Line= 3
      3707385.33     10746765.75      3706864.51     10747720.59
      3706029.02     10748718.84
#Sta/Elev= 30
  4076.1  391.84  4149.5   381.7  4201.8  370.57  4245.5  363.36    4252  360.95
  4267.3     360  4274.8  357.31  4327.1  351.31  4370.8  349.34  4468.4   341.2
  4521.1  337.34  4662.1  335.99  4664.8  335.49  4668.1  335.99  4741.9   336.4
  5632.8  336.82  5655.8  337.19  5763.1  338.94  5784.7  341.33  5813.4  344.15
  5883.6  347.52  6053.8  350.31  6160.8  355.19  6175.1  356.93  6238.9  357.07
  6253.2   359.2  6316.9  359.05  6331.2  360.96  6423.6  365.01  6465.5  368.39
#Mann= 8 ,-1 , 0
  4076.1     .12       0  4521.1     .16       0  4662.1     .07       0
  4668.1     .16       0  4741.9     .07       0  5632.8     .12       0
  5655.8     .16       0  6053.8     .05       0
Bank Sta=4468.4,5784.7
XS Rating Curve= 0 ,0
Exp/Cntr=0.3,0.1

Type RM Length L Ch R = 1 ,187174  ,551,551,551
BEGIN DESCRIPTION:
CATFISH CREEK 159.0
END DESCRIPTION:
XS GIS Cut Line= 3
      3707199.58     10746660.21      3706399.61     10747360.19
       3705599.6     10747710.19
#Sta/Elev= 30
  3929.7  390.55  4028.8  383.58  4085.8  377.22  4106.7  373.05  4177.9  362.41
  4227.2  352.08    4305  341.11  4319.3  338.57  4347.8  336.35  4460.5  336.23
  4472.8  336.43  4600.1  335.78  4602.8  335.28  4606.1  335.78  4912.8  335.78
    4998  335.78  5342.3  335.78  5440.2  335.78  5478.8  337.81  5484.3  339.48
  5494.8  338.83  5516.6   340.4  5583.3  350.96  5636.7  357.96  5653.4  359.09
  5658.9  361.25  5676.8  362.13  5682.3  364.19  5713.1  366.74  5865.9  386.38
#Mann= 8 ,-1 , 0
  3929.7     .12       0  4460.5     .05       0  4472.8     .07       0
  4600.1     .07       0  4606.1     .07       0  4912.8     .12       0
    4998     .07       0  5342.3     .05       0
Bank Sta=4305,5516.6
XS Rating Curve= 0 ,0
Exp/Cntr=0.3,0.1

Type RM Length L Ch R = 1 ,186623  ,574,574,574
BEGIN DESCRIPTION:
CATFISH CREEK 158.0
END DESCRIPTION:
XS GIS Cut Line= 3
      3707049.59     10746660.19      3706249.61     10746860.19
      3705499.58     10746910.19
#Sta/Elev= 30
  4159.8  376.73  4165.7  376.38  4231.9  368.23  4293.8  359.08  4301.5  356.55
    4335  352.55  4347.9  349.27  4389.1     343  4417.5  340.05  4430.4  336.55
  4546.9  336.62  4582.4  338.18  4595.3   336.5  4650.4  336.34  4689.6  336.43
  4826.8  335.78  4829.5  335.28  4832.8  335.78  4848.8  335.78  5031.2  335.78
  5230.1  335.78  5272.4  335.78  5329.6  337.21  5375.3  340.84  5505.6  358.78
  5515.6  361.23  5615.8  370.43  5655.9  376.03  5665.9  378.75  5736.1  383.56
#Mann= 12 ,-1 , 0
  4159.8     .16       0  4165.7     .12       0  4546.9     .07       0
  4650.4     .05       0  4689.6     .07       0  4826.8    .033       0
  4832.8     .07       0  4848.8     .05       0  5031.2     .07       0
  5230.1     .05       0  5272.4     .07       0  5329.6     .05       0
Bank Sta=4417.5,5375.3
XS Rating Curve= 0 ,0
Exp/Cntr=0.3,0.1

Type RM Length L Ch R = 1 ,186049  ,634,634,634
BEGIN DESCRIPTION:
CATFISH CREEK 157.0
END DESCRIPTION:
XS GIS Cut Line= 3
      3706649.58     10746010.21      3706199.61     10746310.19
      3705399.63     10746860.18
#Sta/Elev= 30
  4458.5  374.18    4508   368.1  4517.1  365.18  4553.1  360.13  4576.6  354.63
  4682.3  338.34  4733.4  332.53  4927.2   333.2  4949.7  332.15  4963.2  333.67
  4970.8  331.74  4976.8  332.89  4985.8  330.67  5009.8  330.37  5012.6  329.87
  5015.8  330.37  5021.6  333.72  5157.1  332.61  5223.2  335.94  5272.6   339.1
  5308.5  343.99    5410  348.73  5487.7   342.8  5559.5  343.74  5625.1  348.45
  5732.7  361.41  5804.4  368.11  5848.8  368.91  5911.9  381.99  5970.1  387.09
#Mann= 5 ,-1 , 0
  4458.5     .16       0  4576.6     .12       0  5009.8     .07       0
  5015.8     .12       0  5223.2     .05       0
Bank Sta=4963.2,5021.6
XS Rating Curve= 0 ,0
Exp/Cntr=0.3,0.1

Type RM Length L Ch R = 1 ,185415  ,688,688,688
BEGIN DESCRIPTION:
CATFISH CREEK 156.0
END DESCRIPTION:
XS GIS Cut Line= 3
      3706549.65     10745360.16      3705849.61     10745860.19
       3705149.6     10746660.19
#Sta/Elev= 30
  4163.1  397.06  4191.4  396.59  4215.6  392.77  4235.7  389.13  4298.3  386.23
  4357.3  380.35  4372.1  376.76  4443.3  365.31  4449.5  365.63  4535.5  350.13
  4621.5  339.93    4844  330.38  4892.9  331.56  4986.5  332.21  5006.9  330.16
  5009.6  329.66  5012.9  330.16  5020.3  332.46  5157.7  330.19  5281.4  330.59
  5490.8  336.04  5658.6  343.69  5668.3  346.02  5697.7  346.44  5767.5  350.93
  5817.3  358.04  5923.6  367.45  5930.3  369.75  5993.9  377.85  6086.4  385.56
#Mann= 8 ,-1 , 0
  4163.1     .05       0  4215.6     .16       0  4892.9     .12       0
  5006.9     .07       0  5012.9     .12       0  5281.4     .16       0
  5658.6     .12       0  5697.7     .05       0
Bank Sta=4986.5,5020.3
XS Rating Curve= 0 ,0
Exp/Cntr=0.3,0.1

Type RM Length L Ch R = 1 ,184727  ,508,508,508
BEGIN DESCRIPTION:
CATFISH CREEK 155.0
END DESCRIPTION:
XS GIS Cut Line= 3
      3705899.63     10745310.18      3705499.61     10745460.19
      3704699.63     10745760.18
#Sta/Elev= 30
  4565.1  361.09  4605.2  357.64  4610.5  358.75  4660.4   351.8  4665.7  352.75
  4726.2  343.49    4814  335.91  4916.7  332.41    4922  330.75  4938.9  330.15
    4971  331.07  4989.7   329.9  5034.7  329.54  5037.5  329.04  5040.7  329.54
  5092.9  332.41  5109.8  331.79  5117.8   332.8  5409.7  337.93  5489.8  337.94
    5566  341.68  5573.2  342.28  5605.5  344.28  5675.8   353.7    5691  354.86
  5697.2  356.65  5761.3  365.26  5776.4   366.4  5782.6  368.25  5846.7  377.45
#Mann= 6 ,-1 , 0
  4565.1     .05       0    4814     .12       0  5034.7     .07       0
  5040.7     .12       0    5566     .16       0  5573.2     .05       0
Bank Sta=4916.7,5092.9
XS Rating Curve= 0 ,0
Exp/Cntr=0.3,0.1

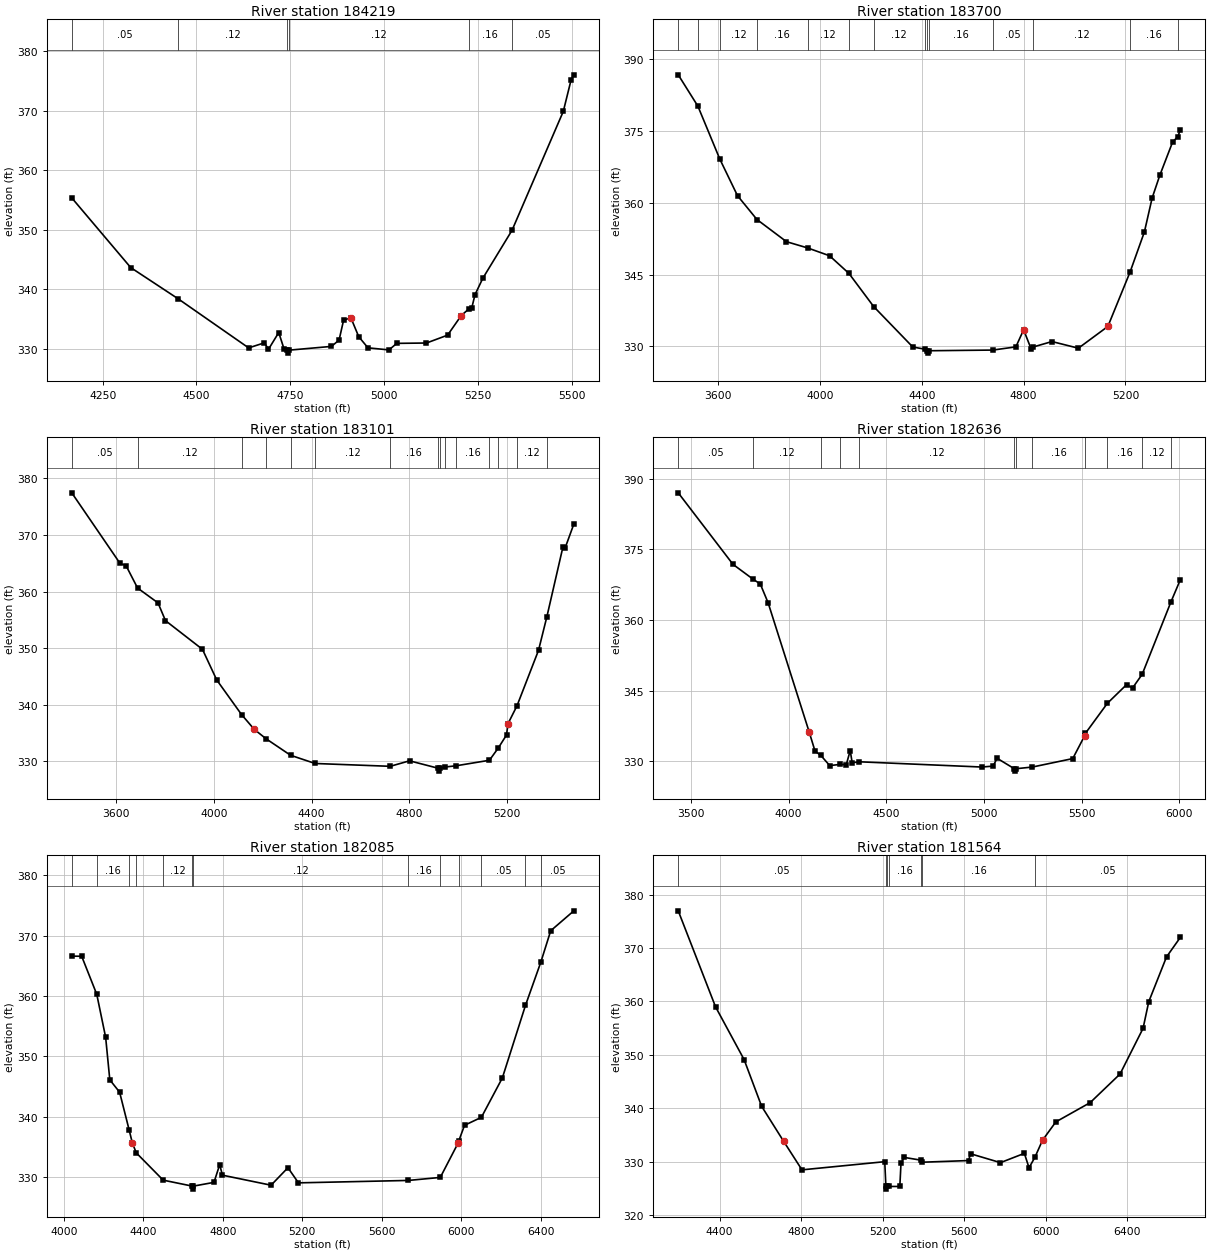
Type RM Length L Ch R = 1 ,184219  ,519,519,519
BEGIN DESCRIPTION:
CATFISH CREEK 154.0
END DESCRIPTION:
XS GIS Cut Line= 3
      3705849.56      10745010.2      3705049.61     10745260.19
      3704649.61     10745560.19
#Sta/Elev= 30
  4167.6  355.34  4324.7  343.63  4451.8  338.35    4639  330.13  4680.9  330.98
  4691.9   329.9  4719.2  332.71  4733.3  329.96  4740.8  329.75  4743.5  329.25
  4746.8  329.75  4859.6  330.38    4880  331.44    4892  334.78  4911.4   335.2
  4932.4  332.01    4957  330.14    5013  329.79  5033.8  330.89    5113  330.95
  5169.2  332.27  5205.7  335.57  5225.3  336.65  5233.8  336.89  5242.2  339.06
    5263  341.82    5341   349.9  5477.6  369.88  5498.4  375.18  5505.7  376.02
#Mann= 6 ,-1 , 0
  4167.6     .05       0  4451.8     .12       0  4740.8     .07       0
  4746.8     .12       0  5225.3     .16       0    5341     .05       0
Bank Sta=4911.4,5205.7
XS Rating Curve= 0 ,0
Exp/Cntr=0.3,0.1

Type RM Length L Ch R = 1 ,183700  ,599,599,599
BEGIN DESCRIPTION:
CATFISH CREEK 153.0
END DESCRIPTION:
XS GIS Cut Line= 3
      3706249.58     10744660.19      3704699.61     10744910.19
      3704299.63     10744960.19
#Sta/Elev= 30
  3442.6  386.79  3519.8  380.24    3606  369.17  3675.5  361.52  3751.9  356.54
    3868   351.9  3950.8   350.6  4037.2  348.96  4113.4  345.27  4210.6  338.34
  4364.3  329.88  4412.4  329.42  4422.1   329.1  4424.9   328.6  4428.1   329.1
  4679.1  329.24  4769.5  329.91  4799.9  333.48  4830.3  329.36  4837.9  329.89
  4911.3  331.02  5015.1  329.63    5131  334.18  5218.2  345.55  5274.6  353.95
  5304.9  361.02  5335.1  365.78  5385.5  372.75  5406.4  373.89  5415.7  375.34
#Mann= 14 ,-1 , 0
  3442.6     .05       0  3519.8     .16       0    3606     .12       0
  3751.9     .16       0  3950.8     .12       0  4113.4     .16       0
  4210.6     .12       0  4412.4     .16       0  4422.1     .07       0
  4428.1     .16       0  4679.1     .05       0  4837.9     .12       0
  5218.2     .16       0  5406.4     .05       0
Bank Sta=4799.9,5131
XS Rating Curve= 0 ,0
Exp/Cntr=0.3,0.1

Type RM Length L Ch R = 1 ,183101  ,465,465,465
BEGIN DESCRIPTION:
CATFISH CREEK 152.0
END DESCRIPTION:
XS GIS Cut Line= 3
      3706099.63     10744210.19      3704463.91     10744417.76
      3704249.61     10744760.19
#Sta/Elev= 30
  3419.5  377.43  3617.1  364.95  3641.3  364.58  3688.5  360.62  3772.1  357.99
  3802.6  354.86  3953.8  349.79  4012.2  344.38  4113.5  338.28  4165.5  335.66
  4213.8     334  4314.1  331.08  4414.4  329.63  4721.4  329.13  4800.5   330.1
  4918.5  328.78  4921.2  328.28  4924.5  328.78  4944.3     329  4990.5  329.22
  5127.2   330.2  5163.4  332.37    5197  334.66  5202.9  336.64  5240.1  339.84
  5327.9  349.62  5362.2  355.58  5428.1  367.95  5436.9  367.72  5472.3  371.92
#Mann= 15 ,-1 , 0
  3419.5     .05       0  3688.5     .12       0  4113.5     .05       0
  4213.8      .1       0  4314.1     .16       0  4414.4     .12       0
  4721.4     .16       0  4918.5     .07       0  4924.5     .16       0
  4944.3     .12       0  4990.5     .16       0  5127.2     .12       0
  5163.4     .16       0  5240.1     .12       0  5362.2     .05       0
Bank Sta=4165.5,5202.9
XS Rating Curve= 0 ,0
Exp/Cntr=0.3,0.1

Type RM Length L Ch R = 1 ,182636  ,551,551,551
BEGIN DESCRIPTION:
CATFISH CREEK 151.0
END DESCRIPTION:
XS GIS Cut Line= 3
      3706249.62     10744060.19      3704699.61     10744010.19
      3703699.63     10744210.18
#Sta/Elev= 30
  3434.7  386.97  3714.9   371.8  3815.5  368.72  3854.9  367.62    3895  363.63
  4105.1  336.24  4135.1  332.17  4164.5  331.28  4210.1  329.11  4263.4  329.35
  4295.2  329.31  4315.2   332.3  4325.2  329.72  4362.4  329.91  4988.1   328.8
  5046.7  328.99  5067.1  330.66  5155.9  328.43  5158.6  327.93  5161.9  328.43
  5248.3   328.8  5454.6  330.59  5515.8  335.45  5519.1  335.93  5631.9  342.32
    5730  346.27  5760.6  345.56  5810.1  348.47  5957.9  363.89  6005.3  368.53
#Mann= 12 ,-1 , 0
  3434.7     .05       0  3815.5     .12       0  4164.5     .16       0
  4263.4     .05       0  4362.4     .12       0  5155.9     .07       0
  5161.9     .12       0  5248.3     .16       0  5519.1     .05       0
  5631.9     .16       0  5810.1     .12       0  5957.9     .16       0
Bank Sta=4105.1,5515.8
XS Rating Curve= 0 ,0
Exp/Cntr=0.3,0.1

Type RM Length L Ch R = 1 ,182085  ,521,521,521
BEGIN DESCRIPTION:
CATFISH CREEK 150.0
END DESCRIPTION:
XS GIS Cut Line= 3
      3705699.62     10742960.18      3704949.61     10743610.19
      3703499.58      10744110.2
#Sta/Elev= 30
  4040.1  366.62    4090   366.6  4165.9  360.29  4210.6  353.16  4231.5  346.12
  4280.8  344.08  4328.3  337.88  4344.5  335.71  4364.4  334.03  4499.9   329.5
  4646.3  328.51  4649.1  328.01  4652.3  328.51  4755.7  329.13  4784.2  332.05
  4798.5  330.32  5042.9  328.66  5127.8  331.56  5180.7  329.05  5734.2  329.45
  5894.4  329.95  5984.6  335.68  5987.4     336  6016.3  338.59  6101.2  339.91
  6206.7  346.44    6323  358.46  6400.4  365.64    6450  370.83  6566.4  374.13
#Mann= 13 ,-1 , 0
  4040.1     .05       0  4165.9     .16       0  4328.3     .12       0
  4364.4     .05       0  4499.9     .12       0  4646.3     .07       0
  4652.3     .12       0  5734.2     .16       0  5894.4     .05       0
  5987.4     .16       0  6101.2     .05       0    6323     .16       0
  6400.4     .05       0
Bank Sta=4344.5,5984.6
XS Rating Curve= 0 ,0
Exp/Cntr=0.3,0.1

Type RM Length L Ch R = 1 ,181564  ,504,504,504
BEGIN DESCRIPTION:
CATFISH CREEK 149.0
END DESCRIPTION:
XS GIS Cut Line= 3
      3705649.64     10742810.18      3704899.61     10743110.19
      3703449.57     10743910.21
#Sta/Elev= 30
  4196.9  376.96    4380  358.98    4520  349.11  4606.2  340.35  4713.9  333.81
  4804.1  328.45  5210.3  329.98    5216  325.34  5218.8  324.84    5222  325.34
  5229.9  325.34  5284.3  325.34  5290.2  329.78  5306.1  330.78  5390.1  330.25
  5393.9  329.88  5621.4  330.19  5631.6  331.46  5778.3   329.8  5895.5  331.54
  5918.4  328.84  5947.2   330.8  5984.6     334  6049.9  337.43  6218.4  341.04
  6365.1   346.4    6478  354.95    6506  359.95  6593.1  368.33  6660.8  371.98
#Mann= 7 ,-1 , 0
  4196.9     .05       0    5216    .035       0    5222     .05       0
  5229.9     .16       0  5390.1     .05       0  5393.9     .16       0
  5947.2     .05       0
Bank Sta=4713.9,5984.6
XS Rating Curve= 0 ,0
Exp/Cntr=0.3,0.1

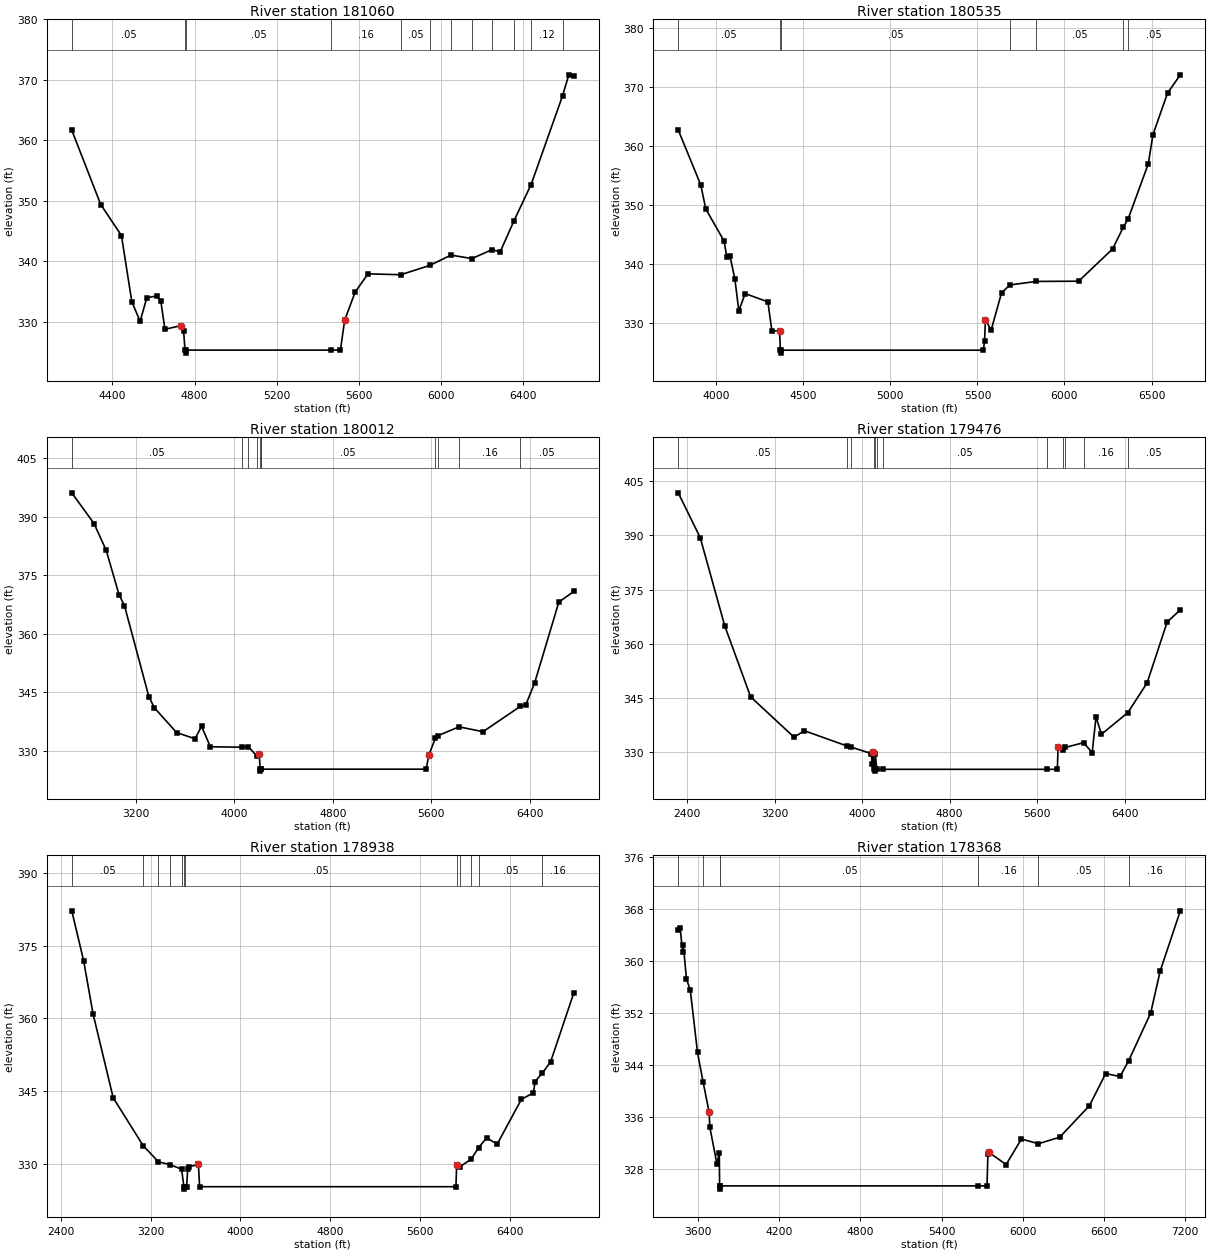
Type RM Length L Ch R = 1 ,181060  ,525,525,525
BEGIN DESCRIPTION:
CATFISH CREEK 148.0
END DESCRIPTION:
XS GIS Cut Line= 3
      3705499.62     10742760.19      3704699.61     10742660.19
      3703099.58      10743010.2
#Sta/Elev= 30
  4202.2  361.67  4343.3  349.38  4444.1  344.26  4494.5  333.34  4534.8  330.09
  4567.5  333.99  4615.4  334.28  4635.6  333.44  4655.7  328.78  4736.3   329.4
  4746.4   328.5  4753.5  325.34  4756.2  324.84  4759.5  325.34  5465.5  325.34
    5510  325.34  5530.5  330.26  5581.7  334.92  5644.2  337.94  5804.1  337.79
  5945.8  339.34    6048  341.03  6150.2  340.46  6246.5  341.91    6288  341.58
  6354.6  346.68  6437.9  352.66  6591.1  367.32  6621.8  370.81  6646.3  370.57
#Mann= 12 ,-1 , 0
  4202.2     .05       0  4753.5    .033       0  4759.5     .05       0
  5465.5     .16       0  5804.1     .05       0  5945.8     .16       0
    6048     .12       0  6150.2     .16       0  6246.5     .12       0
  6354.6     .16       0  6437.9     .12       0  6591.1     .05       0
Bank Sta=4736.3,5530.5
XS Rating Curve= 0 ,0
Exp/Cntr=0.3,0.1

Type RM Length L Ch R = 1 ,180535  ,523,523,523
BEGIN DESCRIPTION:
CATFISH CREEK 147.0
END DESCRIPTION:
XS GIS Cut Line= 3
      3705649.58     10742660.17      3704549.61     10742160.19
      3702949.59      10742660.2
#Sta/Elev= 30
  3780.9  362.72  3910.5  353.38    3939  349.32  4044.5  343.85  4059.9  341.13
  4077.4  341.41    4106  337.49  4129.1  332.02  4165.3  334.95    4296  333.54
  4319.1  328.56    4363  328.68  4367.7  325.34  4370.5  324.84  4373.7  325.34
    5534  325.34  5540.8  326.86    5546  330.53  5578.5  328.73  5638.2  335.05
    5686  336.41  5838.2  337.01  6081.4  337.05  6276.3  342.52  6337.4  346.18
  6366.5  347.68  6481.6  356.98  6508.3  361.92  6592.1  368.98  6665.5  372.08
#Mann= 7 ,-1 , 0
  3780.9     .05       0  4367.7    .033       0  4373.7     .05       0
    5686     .16       0  5838.2     .05       0  6337.4     .16       0
  6366.5     .05       0
Bank Sta=4363,5546
XS Rating Curve= 0 ,0
Exp/Cntr=0.3,0.1

Type RM Length L Ch R = 1 ,180012  ,536,536,536
BEGIN DESCRIPTION:
CATFISH CREEK 146.0
END DESCRIPTION:
XS GIS Cut Line= 3
      3706549.58     10742460.18      3704349.61     10741660.19
      3702899.61     10742610.19
#Sta/Elev= 30
  2682.3  396.16  2863.2  388.28  2962.2  381.39  3065.3   370.1  3109.9  367.25
  3308.1   343.9  3352.6  341.07  3533.5  334.71  3682.5  333.14  3735.7  336.32
  3806.8  331.08  4065.1  330.97  4114.1  331.13  4186.2  328.65  4203.9  329.17
  4210.9  325.34  4213.6  324.84  4216.9  325.34  4217.9  325.34  5558.4  325.34
  5579.4  328.93  5632.5  333.22  5652.9  333.92  5825.2  336.19  6019.6  334.94
  6323.6  341.46  6366.3  341.79  6438.6  347.46  6634.6  368.13  6756.7  370.91
#Mann= 11 ,-1 , 0
  2682.3     .05       0  4065.1     .16       0  4114.1     .05       0
  4186.2     .16       0  4210.9    .033       0  4216.9     .16       0
  4217.9     .05       0  5632.5     .16       0  5652.9     .05       0
  5825.2     .16       0  6323.6     .05       0
Bank Sta=4203.9,5579.4
XS Rating Curve= 0 ,0
Exp/Cntr=0.3,0.1

Type RM Length L Ch R = 1 ,179476  ,538,538,538
BEGIN DESCRIPTION:
CATFISH CREEK 145.0
END DESCRIPTION:
XS GIS Cut Line= 3
      3706599.58     10742360.17      3704199.61     10741160.19
      3702899.64     10742560.15
#Sta/Elev= 30
  2316.4  401.79  2517.6  389.39  2741.2  365.08  2978.8  345.37  3375.7  334.24
  3470.7     336  3863.6  331.76  3895.1  331.52  4082.9  329.69  4091.2  326.78
  4096.8  330.16  4110.6  325.34  4113.4  324.84  4116.6  325.34  4119.2  329.68
  4132.7  325.34  4189.3  325.34  5688.2  325.34  5785.1  325.34  5791.9   331.6
    5840  330.65  5858.3  331.39  6024.9  332.71  6103.7  329.96  6138.9  339.85
  6188.2  335.02  6430.4  341.04    6606  349.22  6789.7  366.06  6910.1  369.43
#Mann= 12 ,-1 , 0
  2316.4     .05       0  3863.6     .16       0  3895.1     .05       0
  4110.6    .033       0  4116.6     .05       0  4132.7     .16       0
  4189.3     .05       0  5688.2     .16       0    5840     .12       0
  5858.3     .05       0  6024.9     .16       0  6430.4     .05       0
Bank Sta=4096.8,5791.9
XS Rating Curve= 0 ,0
Exp/Cntr=0.3,0.1

Type RM Length L Ch R = 1 ,178938  ,570,570,570
BEGIN DESCRIPTION:
CATFISH CREEK 144.0
END DESCRIPTION:
XS GIS Cut Line= 3
      3706399.62     10739860.19      3703999.61     10740660.19
      3702399.59      10741760.2
#Sta/Elev= 30
  2498.8  382.17  2604.2  371.92  2688.5  360.93  2867.7  343.66  3133.9  333.82
  3270.7  330.46  3371.4   329.9  3477.1  328.95  3497.2  325.34  3499.9  324.84
  3503.2  325.34  3521.3  325.34  3531.8  329.02  3542.4  329.42  3626.7  329.96
  3637.2  325.34  5920.3  325.34  5926.6  329.85    5932  329.89  5957.6  329.48
  6055.4     331  6121.4  333.36  6193.6  335.41  6287.7  334.11  6502.8  343.32
  6610.4  344.69  6625.2  347.01  6690.1  348.77  6762.6  351.02  6970.3  365.28
#Mann= 12 ,-1 , 0
  2498.8     .05       0  3133.9     .12       0  3270.7     .05       0
  3371.4     .16       0  3477.1     .05       0  3497.2    .033       0
  3503.2     .05       0    5932     .12       0  5957.6     .16       0
  6055.4     .12       0  6121.4     .05       0  6690.1     .16       0
Bank Sta=3626.7,5926.6
XS Rating Curve= 0 ,0
Exp/Cntr=0.3,0.1

Type RM Length L Ch R = 1 ,178368  ,524,524,524
BEGIN DESCRIPTION:
CATFISH CREEK 143.0
END DESCRIPTION:
XS GIS Cut Line= 3
      3704449.59     10738710.22      3703799.61     10740160.19
       3702349.6      10741710.2
#Sta/Elev= 30
  3452.8  364.74  3467.1  365.13  3484.8   361.4  3490.3  362.51  3513.5  357.26
  3542.1   355.5  3595.2  345.92  3636.7  341.37  3681.2  336.67  3686.7  334.36
  3738.5  328.75  3756.2  330.44  3758.7  325.34  3761.5  324.84  3764.7  325.34
    5671  325.34  5735.2  325.34    5742  330.21  5749.4   330.5  5876.9  328.63
  5989.7  332.57  6115.6  331.84    6273  332.85  6492.4  337.71  6612.5  342.66
  6718.5  342.21  6781.3  344.59  6945.2     352  7015.5  358.47  7164.3  367.76
#Mann= 7 ,-1 , 0
  3452.8     .12       0  3636.7     .05       0  3758.7    .033       0
  3764.7     .05       0    5671     .16       0  6115.6     .05       0
  6781.3     .16       0
Bank Sta=3681.2,5749.4
XS Rating Curve= 0 ,0
Exp/Cntr=0.3,0.1

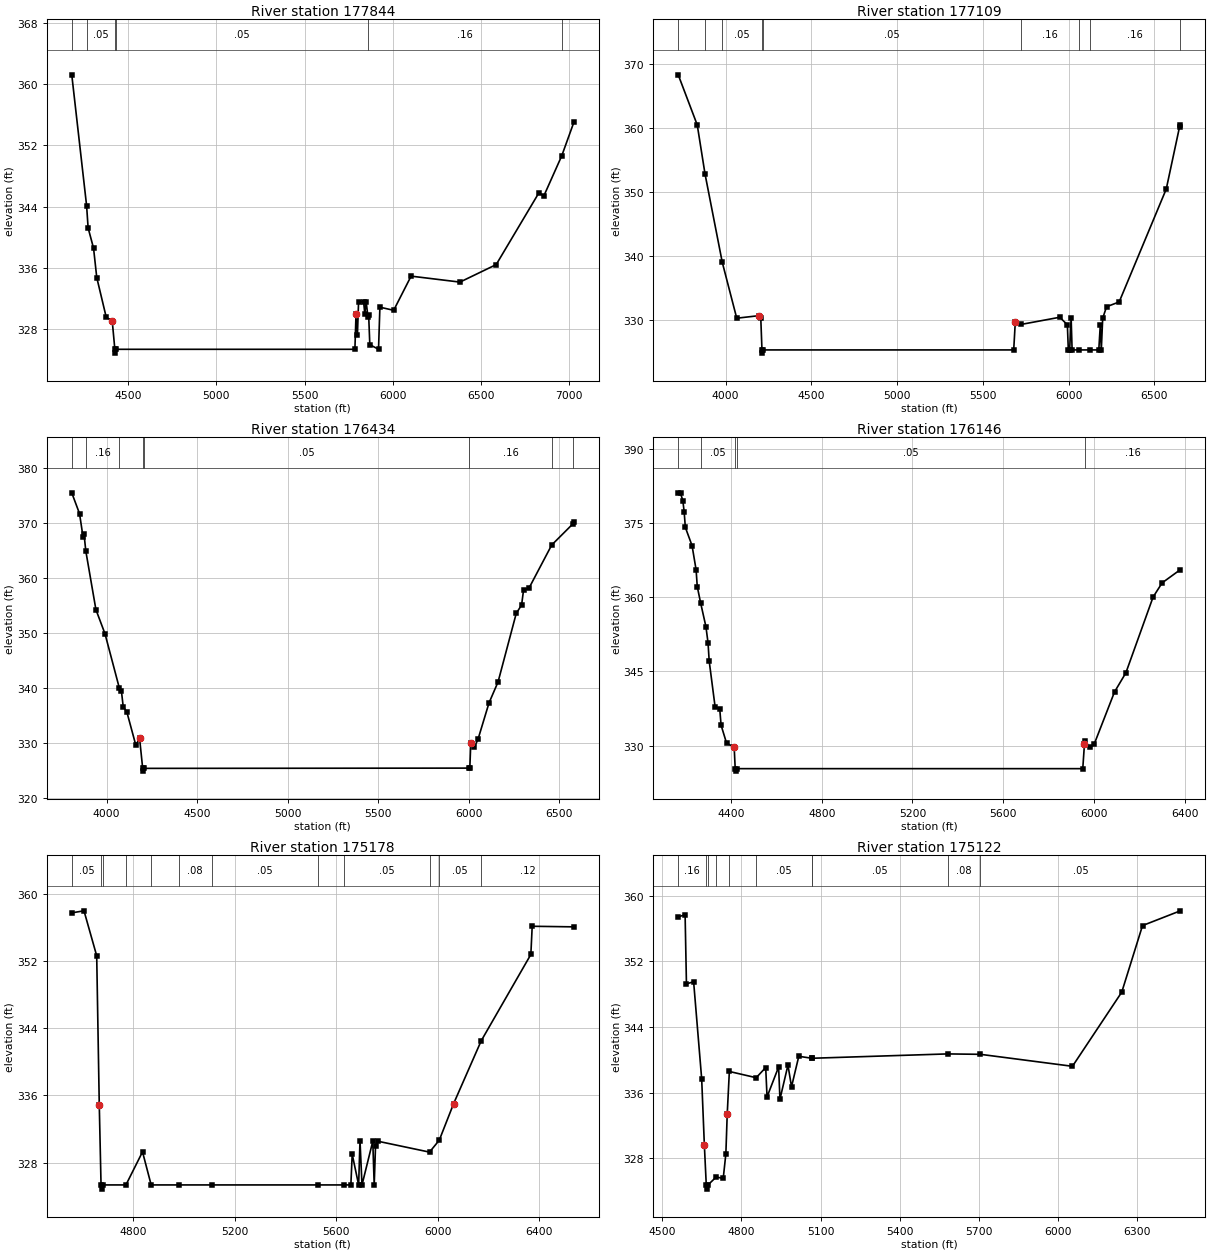
Type RM Length L Ch R = 1 ,177844  ,735,735,735
BEGIN DESCRIPTION:
CATFISH CREEK 142.0
END DESCRIPTION:
XS GIS Cut Line= 3
      3703399.62     10738860.24      3703599.61     10739660.19
      3702299.59     10741210.22
#Sta/Elev= 30
    4180  361.24  4264.1  344.13  4272.7  341.22  4303.6  338.56  4321.7  334.73
  4375.8   329.5  4409.3  329.09  4424.3  325.34  4427.1  324.84  4430.3  325.34
  5785.8  325.34  5792.3  330.02  5800.1   327.2  5806.6  331.55  5835.2  331.57
  5841.8  330.01  5849.5  331.58  5860.2  329.54  5863.8  329.88  5870.4  325.95
  5919.8  325.34  5927.6  330.85  6005.7  330.44  6104.5  334.91  6381.6  334.13
  6587.2  336.42  6829.2   345.8  6857.8  345.42    6959  350.65  7027.6  355.03
#Mann= 6 ,-1 , 0
    4180     .12       0  4264.1     .05       0  4424.3    .033       0
  4430.3     .05       0  5860.2     .16       0    6959     .05       0
Bank Sta=4409.3,5792.3
XS Rating Curve= 0 ,0
Exp/Cntr=0.3,0.1

Type RM Length L Ch R = 1 ,177109  ,675,675,675
BEGIN DESCRIPTION:
CATFISH CREEK 141.0
END DESCRIPTION:
XS GIS Cut Line= 3
      3702819.39     10738369.38      3702871.47     10739879.79
      3702207.39     10741129.84
#Sta/Elev= 30
  3724.2  368.28  3835.1  360.45  3880.3  352.81  3980.9  339.01  4065.2  330.29
  4195.3  330.69  4205.3  330.38  4212.3  325.34    4215  324.84  4218.3  325.34
  5679.8  325.34  5688.9  329.63  5725.1  329.33  5948.6  330.44  5992.6  329.26
  5998.2  325.34    6006  325.34  6014.5  330.39  6020.2  325.34    6059  325.34
    6126  325.34  6175.8  325.34  6184.7  329.29  6190.4  325.34  6198.5  330.28
  6221.1  332.08  6294.6  332.83  6569.1  350.46  6646.3  360.13    6651  360.45
#Mann= 9 ,-1 , 0
  3724.2     .05       0  3880.3     .16       0  3980.9     .05       0
  4212.3    .033       0  4218.3     .05       0  5725.1     .16       0
    6059     .05       0    6126     .16       0  6646.3     .05       0
Bank Sta=4195.3,5688.9
XS Rating Curve= 0 ,0
Exp/Cntr=0.3,0.1

Type RM Length L Ch R = 1 ,176434  ,288,288,288
BEGIN DESCRIPTION:
CATFISH CREEK 140.0
END DESCRIPTION:
XS GIS Cut Line= 2
      3702311.58      10738447.5      3702025.26     10741206.58
#Sta/Elev= 30
  3807.1   375.5    3850  371.71  3869.8  367.38  3874.9  367.95  3884.7   364.9
  3940.5  354.24  3990.8  349.83  4070.5  339.89  4081.3  339.46  4091.3  336.56
  4111.4  335.61  4160.9  329.57  4181.8   330.8  4198.9  325.34  4201.7  324.84
  4204.9  325.34  6004.3  325.39  6006.3  325.42  6011.6  329.96  6031.7  329.21
  6051.8  330.67  6112.1  337.24  6162.4  341.09  6262.9  353.57  6292.3  355.08
  6303.1   357.8  6333.3  358.16  6458.6     366  6574.8  369.82    6581  370.11
#Mann= 8 ,-1 , 0
  3807.1     .05       0  3884.7     .16       0  4070.5     .05       0
  4198.9    .033       0  4204.9     .05       0  6004.3     .16       0
  6458.6     .05       0  6574.8     .16       0
Bank Sta=4181.8,6011.6
XS Rating Curve= 0 ,0
Exp/Cntr=0.3,0.1

Type RM Length L Ch R = 1 ,176146  ,968,968,968
BEGIN DESCRIPTION:
CATFISH CREEK 139.0
END DESCRIPTION:
XS GIS Cut Line= 3
      3701749.62     10738810.24      3701899.61     10739610.19
      3701949.61      10741010.2
#Sta/Elev= 30
  4166.7  381.05  4176.8  380.94    4187  379.49  4192.9  377.19    4198  374.08
  4227.7  370.38  4245.5   365.5  4250.6  362.12  4265.2  358.87  4288.7  354.05
  4298.1  350.79  4303.2  347.09  4329.4  337.79  4349.8  337.41  4355.7  334.12
  4380.3  330.43  4413.4  329.76    4418  325.34  4420.8  324.84    4424  325.34
  5951.2  325.34  5958.7  330.33  5961.9  330.93  5981.2  329.64  6001.2  330.24
  6091.3  340.84  6141.3  344.69  6261.4     360  6301.4  362.87  6381.5  365.53
#Mann= 5 ,-1 , 0
  4166.7     .16       0  4265.2     .05       0    4418    .033       0
    4424     .05       0  5961.9     .16       0
Bank Sta=4413.4,5958.7
XS Rating Curve= 0 ,0
Exp/Cntr=0.3,0.1

Type RM Length L Ch R = 1 ,175178  ,56,56,56
BEGIN DESCRIPTION:
CATFISH CREEK 138.0
END DESCRIPTION:
XS GIS Cut Line= 5
      3701567.67     10739102.45       3701223.9     10739128.49
      3701083.28      10739196.2      3701010.36      10739321.2
      3700557.45     10740575.81
#Sta/Elev= 30
  4557.3  357.76  4605.5     358  4655.6  352.64  4665.7  334.91  4672.7  325.34
  4675.5  324.84  4678.7  325.34  4770.8  325.34  4836.2  329.28  4870.3  325.34
  4978.3  325.34  5108.7  325.34  5526.7  325.34  5629.5  325.34  5657.6  325.34
  5662.9  328.99  5688.3  325.34  5693.6  330.63  5701.5  325.34    5744  330.54
  5749.6  325.34  5754.9  330.03  5765.2  330.54  5967.7  329.25  6006.1  330.67
  6062.9  335.04  6171.4  342.51  6367.2   352.8  6372.5  356.16  6536.7  356.09
#Mann= 12 ,-1 , 0
  4557.3     .05       0  4672.7     .07       0  4678.7     .05       0
  4770.8     .08       0  4870.3     .05       0  4978.3     .08       0
  5108.7     .05       0  5526.7      .1       0  5629.5     .05       0
  5967.7      .1       0  6006.1     .05       0  6171.4     .12       0
Bank Sta=4665.7,6062.9
XS Rating Curve= 0 ,0
Exp/Cntr=0.3,0.1

Type RM Length L Ch R = 1 ,175122  ,108,108,108
BEGIN DESCRIPTION:
Mapping XS 0691a698
END DESCRIPTION:
XS GIS Cut Line= 6
      3701546.78     10739029.54      3701281.19     10739081.62
      3701067.65     10739128.49      3701005.15     10739206.62
      3700947.86     10739295.16      3700552.14     10740435.46
#Sta/Elev= 30
  4560.8   357.4  4586.8  357.69  4591.9  349.25  4619.1   349.5  4649.6  337.67
  4659.8  329.56    4667  324.73  4669.8  324.23    4673  324.73  4704.8  325.71
  4731.2  325.53  4741.2  328.54  4746.3  333.33  4754.4  338.57  4856.1  337.81
  4892.1  339.05  4897.2  335.47    4941  339.12  4946.1  335.19  4976.4  339.35
  4989.9   336.7  5017.4  340.42  5067.1  340.18  5067.2  340.18  5580.9  340.71
  5705.3  340.66    6054   339.2  6240.8  348.24  6319.4  356.35  6462.6  358.15
#Mann= 10 ,-1 , 0
  4560.8     .16       0    4667     .04       0    4673     .16       0
  4704.8     .05       0  4754.4     .08       0  4856.1     .05       0
  5067.1     .08       0  5067.2     .05       0  5580.9     .08       0
  5705.3     .05       0
Bank Sta=4659.8,4746.3
XS Rating Curve= 0 ,0
Exp/Cntr=0.3,0.1

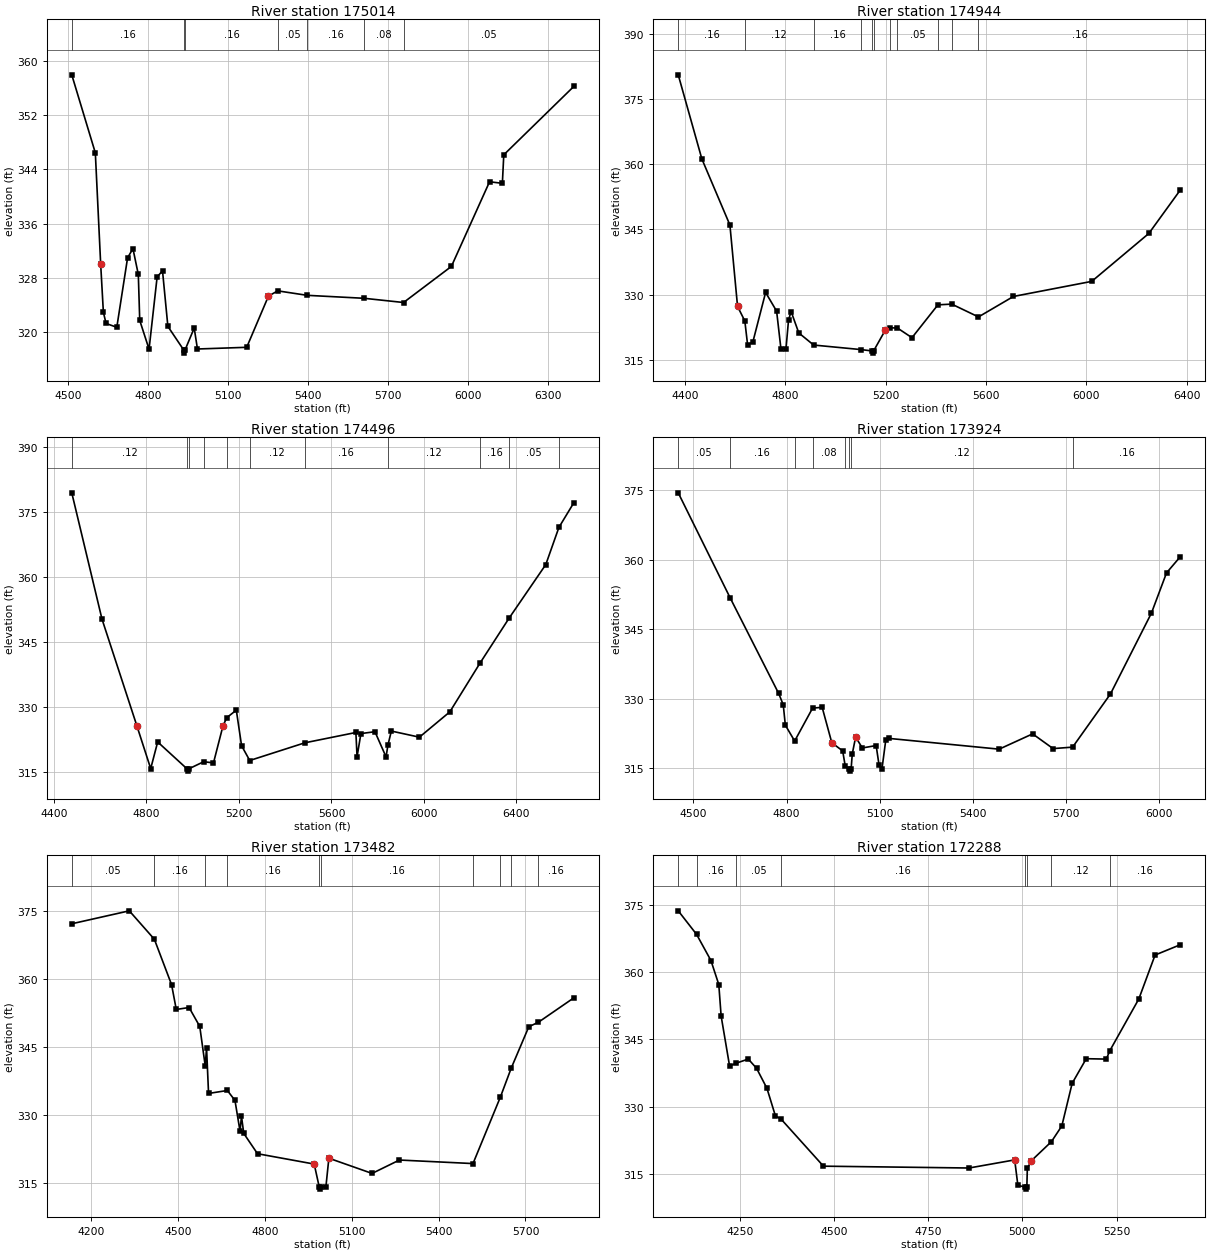
Type RM Length L Ch R = 1 ,175014  ,70,70,70
BEGIN DESCRIPTION:
Mapping XS 76f8aaa9
END DESCRIPTION:
XS GIS Cut Line= 6
      3701557.24     10738932.31      3701156.19     10738984.39
      3701025.98     10739041.69      3700927.03     10739130.23
      3700869.73     10739265.64      3700541.62     10740270.83
#Sta/Elev= 30
  4513.1  357.97  4601.5  346.44  4621.6  329.96  4631.7  322.88  4641.8  321.23
  4682.1  320.67  4722.5  330.93  4742.6  332.29  4762.8  328.47  4768.1  321.69
  4803.1  317.43  4833.4  328.11  4853.6  329.01  4873.7   320.8  4932.5  317.35
  4935.2  316.85  4938.5  317.35  4972.5  320.56  4984.7  317.46  5169.5  317.71
  5251.2  325.28    5286  326.05  5396.3  325.39  5610.7  324.95  5758.1  324.33
  5937.5  329.66  6080.7  342.17  6128.8  341.94  6134.1  346.15    6397  356.26
#Mann= 7 ,-1 , 0
  4513.1     .16       0  4932.5     .07       0  4938.5     .16       0
    5286     .05       0  5396.3     .16       0  5610.7     .08       0
  5758.1     .05       0
Bank Sta=4621.6,5251.2
XS Rating Curve= 0 ,0
Exp/Cntr=0.3,0.1

Type RM Length L Ch R = 1 ,174944  ,448,448,448
BEGIN DESCRIPTION:
CATFISH CREEK 137.0
END DESCRIPTION:
XS GIS Cut Line= 3
      3701682.27     10738833.78      3700935.71     10738972.67
      3700138.11     10739926.33
#Sta/Elev= 30
  4372.4  380.55  4466.6   361.2  4578.5  345.99    4609  327.25    4638  323.91
  4649.1   318.4  4670.1  319.09  4720.9  330.47  4764.8  326.17    4782  317.52
  4802.3  317.57  4812.4  324.17  4822.7  326.07  4853.2  321.16  4912.5  318.37
  5102.2  317.32  5145.6  317.01  5148.3  316.51  5151.6  317.01    5198  321.77
  5215.6  322.33  5246.4   322.3  5304.7  320.06  5408.2  327.62  5463.2  327.79
  5569.9  324.84  5709.4  329.55  6021.7  333.02  6249.5  344.05    6375  354.05
#Mann= 11 ,-1 , 0
  4372.4     .16       0    4638     .12       0  4912.5     .16       0
  5102.2      .1       0  5145.6     .07       0  5151.6      .1       0
  5215.6     .16       0  5246.4     .05       0  5408.2     .08       0
  5463.2     .05       0  5569.9     .16       0
Bank Sta=4609,5198
XS Rating Curve= 0 ,0
Exp/Cntr=0.3,0.1

Type RM Length L Ch R = 1 ,174496  ,572,572,572
BEGIN DESCRIPTION:
CATFISH CREEK 136.0
END DESCRIPTION:
XS GIS Cut Line= 3
      3701649.64     10738560.19      3701099.61     10738510.19
      3699499.62     10738260.19
#Sta/Elev= 30
  4476.8  379.44  4607.4  350.34    4758  325.77  4818.2  315.84  4848.4  321.99
  4975.9  315.76  4978.6  315.26  4981.9  315.76  5047.4  317.43  5089.8  317.16
  5130.8  325.68    5147  327.58  5188.5  329.32  5211.3  321.12  5246.6  317.71
  5484.8  321.79  5705.7  324.17  5710.8  318.59  5727.5  323.92  5788.2  324.35
  5836.3  318.53  5844.1  321.21  5859.1   324.5  5980.5  323.09  6112.1  328.93
  6242.4  340.15  6368.8  350.57  6527.1  362.89  6583.9  371.47  6648.5  377.16
#Mann= 11 ,-1 , 0
  4476.8     .12       0  4975.9     .07       0  4981.9     .12       0
  5047.4     .05       0    5147     .08       0  5246.6     .12       0
  5484.8     .16       0  5844.1     .12       0  6242.4     .16       0
  6368.8     .05       0  6583.9     .16       0
Bank Sta=4758,5130.8
XS Rating Curve= 0 ,0
Exp/Cntr=0.3,0.1

Type RM Length L Ch R = 1 ,173924  ,442,442,442
BEGIN DESCRIPTION:
CATFISH CREEK 135.0
END DESCRIPTION:
XS GIS Cut Line= 3
      3701599.58     10738210.17      3701099.61     10738010.19
      3700099.62     10737610.19
#Sta/Elev= 30
  4451.6  374.48  4618.3  351.86  4774.7  331.19  4789.5  328.74  4796.2  324.34
  4826.2  320.92  4883.9  328.02  4914.7  328.19  4945.7  320.55  4980.7  318.78
  4988.9  315.53  5001.9  314.92  5004.6  314.42  5007.9  314.92  5011.6  318.15
  5022.4  321.77  5043.9  319.42  5088.4  319.94  5097.8  315.71  5107.2  314.94
  5119.3  321.09  5130.1  321.48  5484.2  319.16  5591.9  322.46  5657.8  319.28
  5720.6   319.6  5842.3  331.07  5974.2  348.53  6022.7   357.2  6067.1   360.7
#Mann= 8 ,-1 , 0
  4451.6     .05       0  4618.3     .16       0  4826.2     .05       0
  4883.9     .08       0  4988.9     .12       0  5001.9     .07       0
  5007.9     .12       0  5720.6     .16       0
Bank Sta=4945.7,5022.4
XS Rating Curve= 0 ,0
Exp/Cntr=0.3,0.1

Type RM Length L Ch R = 1 ,173482  ,1194,1194,1194
BEGIN DESCRIPTION:
CATFISH CREEK 133.0
END DESCRIPTION:
XS GIS Cut Line= 3
      3701945.66     10737457.74      3700961.31      10737624.4
       3700346.7     10737218.13
#Sta/Elev= 30
    4132  372.21  4330.8  375.06  4417.4   368.8    4477  358.78  4493.1  353.33
  4537.4  353.76  4574.3   349.6  4593.2  340.91  4597.8  344.87  4604.7  334.83
  4669.7  335.48    4696  333.29  4713.5   326.5  4718.5   329.8  4726.4  326.02
  4773.9  321.55  4969.8  319.27  4987.1  314.25  4989.8  313.75  4993.1  314.25
  5010.3   314.3  5020.5  320.56  5169.8  317.21  5264.3  320.16  5518.6  319.38
  5613.4  334.06  5650.6  340.39  5711.5  349.53  5744.5  350.51  5867.1  355.89
#Mann= 10 ,-1 , 0
    4132     .05       0  4417.4     .16       0  4593.2     .05       0
  4669.7     .16       0  4987.1     .07       0  4993.1     .16       0
  5518.6     .12       0  5613.4     .16       0  5650.6     .12       0
  5744.5     .16       0
Bank Sta=4969.8,5020.5
XS Rating Curve= 0 ,0
Exp/Cntr=0.3,0.1

Type RM Length L Ch R = 1 ,172288  ,539,539,539
BEGIN DESCRIPTION:
CATFISH CREEK 132.0
END DESCRIPTION:
XS GIS Cut Line= 3
      3701749.62      10737310.2      3700999.61     10736760.19
      3700649.59     10736560.18
#Sta/Elev= 30
  4086.2  373.67  4134.9  368.42    4173  362.59  4193.9  357.23  4200.1  350.21
  4222.6  339.03  4239.3  339.67  4272.2  340.61  4294.2  338.55  4321.8  334.07
  4344.4  327.89  4358.6  327.28  4471.8  316.72  4858.4  316.31  4979.6  318.12
  4988.1  312.42  5005.9   312.1  5008.7   311.6  5011.9   312.1  5013.2  316.25
  5024.2  317.96  5077.2  322.19  5104.8   325.7  5132.2   335.2  5169.6  340.69
  5222.9   340.6  5232.2  342.47  5309.2  354.01  5352.4  363.81  5419.4  366.11
#Mann= 8 ,-1 , 0
  4086.2     .05       0  4134.9     .16       0  4239.3     .05       0
  4358.6     .16       0  5005.9     .07       0  5011.9     .16       0
  5077.2     .12       0  5232.2     .16       0
Bank Sta=4979.6,5024.2
XS Rating Curve= 0 ,0
Exp/Cntr=0.3,0.1