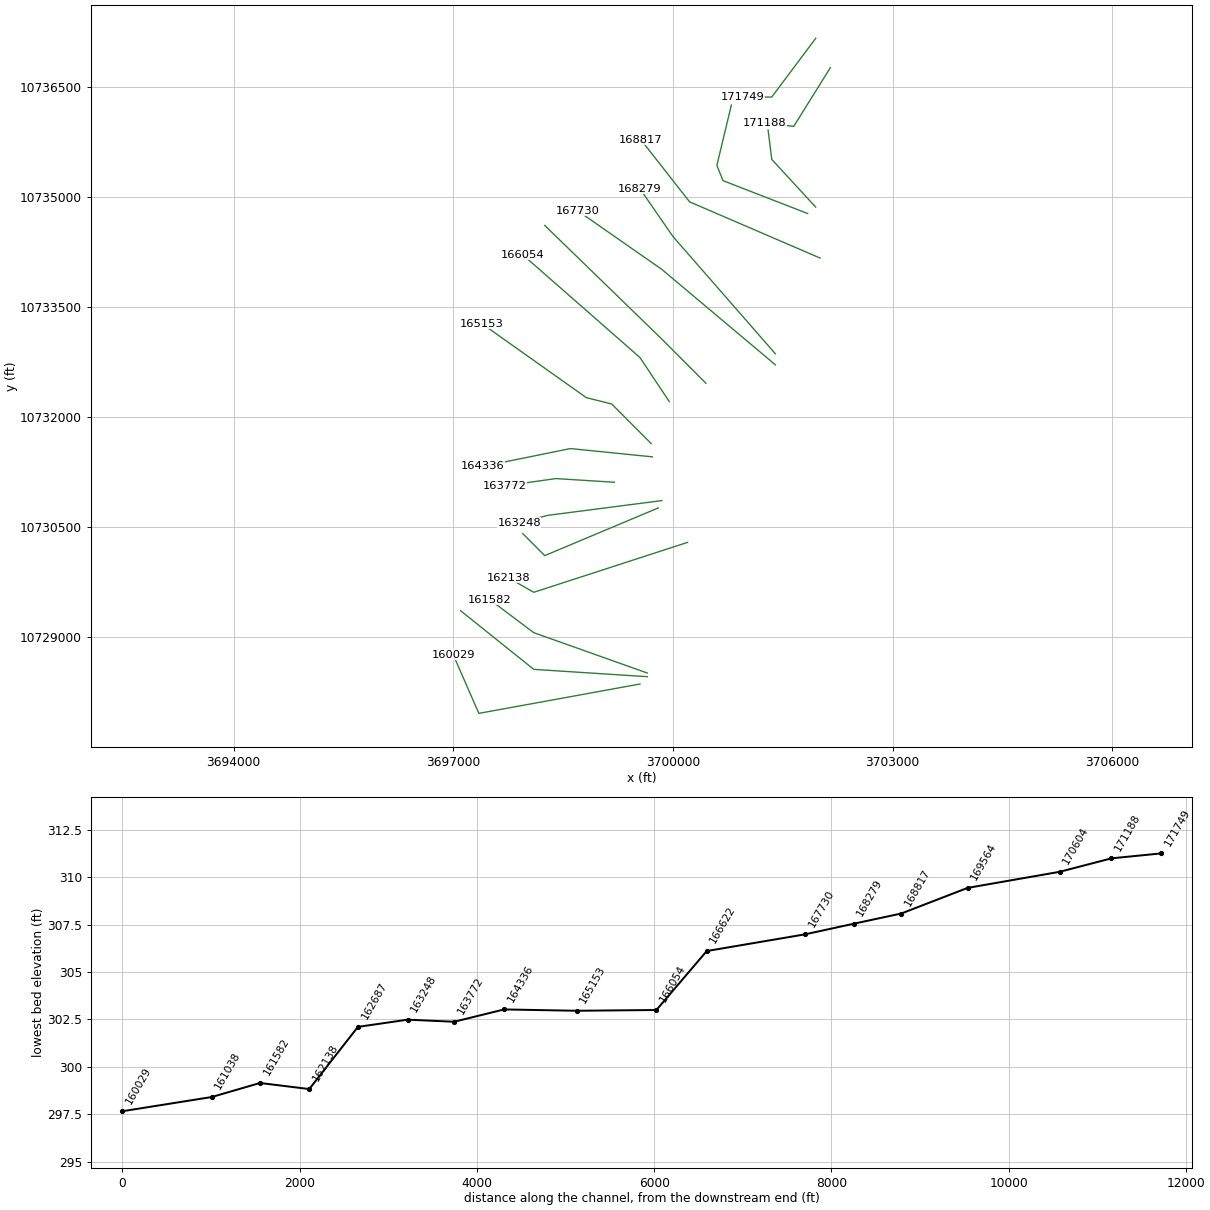
HEC-RAS study CATFISH CREEK.prj: CATFISH CREEK Base Level Engineering

--- CATFISH CREEK.g01 (geometry) --- (continued)

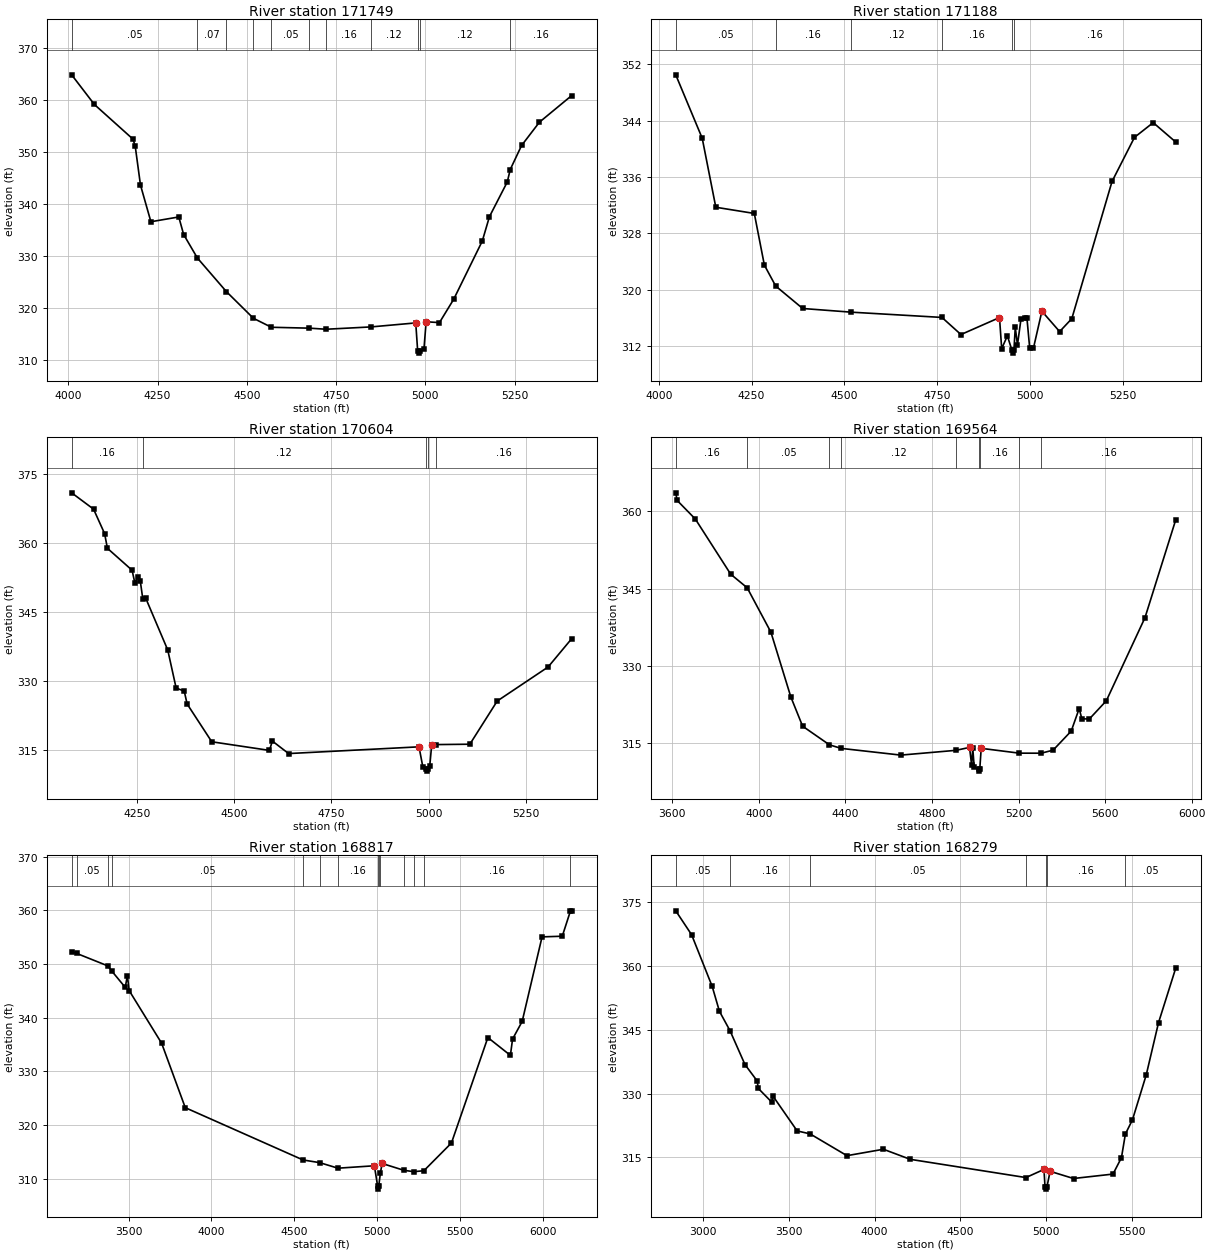
Type RM Length L Ch R = 1 ,171749  ,561,561,561
BEGIN DESCRIPTION:
CATFISH CREEK 131.0
END DESCRIPTION:
XS GIS Cut Line= 3
      3701949.62      10737160.2      3701349.61     10736360.19
      3700949.62     10736360.19
#Sta/Elev= 30
  4009.5  364.87  4073.1  359.16  4181.4  352.47  4187.6  351.07  4202.2  343.64
  4231.4  336.57  4309.5  337.49  4323.1  334.11  4361.6  329.58  4442.7  323.12
  4518.5  317.97  4568.9  316.24  4675.4  316.07  4721.9  315.86    4848  316.31
  4973.1  317.08  4978.4  311.76  4981.1  311.26  4984.4  311.76    4996  311.98
  5002.2   317.3  5039.5  317.14  5079.5  321.65  5159.5  332.86  5179.5  337.55
  5229.5  344.24  5237.7  346.63  5269.5  351.26  5319.5  355.75  5409.5  360.86
#Mann= 11 ,-1 , 0
  4009.5     .05       0  4361.6     .07       0  4442.7     .12       0
  4518.5     .16       0  4568.9     .05       0  4675.4     .12       0
  4721.9     .16       0    4848     .12       0  4978.4     .07       0
  4984.4     .12       0  5237.7     .16       0
Bank Sta=4973.1,5002.2
XS Rating Curve= 0 ,0
Exp/Cntr=0.3,0.1

Type RM Length L Ch R = 1 ,171188  ,584,584,584
BEGIN DESCRIPTION:
CATFISH CREEK 130.0
END DESCRIPTION:
XS GIS Cut Line= 3
      3702149.58     10736760.15      3701649.61     10735960.19
      3701249.57     10736010.19
#Sta/Elev= 30
  4045.8  350.53  4117.1  341.52  4153.7  331.72  4257.4  330.84  4284.5   323.5
    4315  320.53  4387.7  317.34  4517.9  316.82  4762.8  316.07    4814  313.64
  4917.8  316.05  4923.7  311.63    4939  313.45  4950.8   311.5  4953.5     311
  4956.8   311.5  4960.3  314.66  4966.2  312.17  4975.6  315.81  4986.2  315.99
  4991.7  315.99  4999.2  311.69  5009.3  311.72    5032  316.95  5079.8  314.06
  5112.6   315.9  5220.9  335.38  5281.4  341.65  5331.8  343.74  5392.3  340.99
#Mann= 6 ,-1 , 0
  4045.8     .05       0    4315     .16       0  4517.9     .12       0
  4762.8     .16       0  4950.8     .07       0  4956.8     .16       0
Bank Sta=4917.8,5032
XS Rating Curve= 0 ,0
Exp/Cntr=0.3,0.1

Type RM Length L Ch R = 1 ,170604  ,1040,1040,1040
BEGIN DESCRIPTION:
CATFISH CREEK 129.0
END DESCRIPTION:
XS GIS Cut Line= 3
      3701949.61     10734860.19      3701349.61     10735510.19
      3701299.61     10735910.19
#Sta/Elev= 30
  4080.8  370.99  4137.2  367.43  4165.6  362.11  4172.9  358.89  4236.4  354.11
  4243.8  351.25  4250.6  352.66  4257.7  351.67  4264.1  347.81  4271.6  348.01
  4328.3  336.71  4349.9  328.41  4370.8  327.74  4378.2  324.94  4441.7  316.69
  4590.3  314.81  4597.7  316.85  4639.6  314.12  4975.5  315.59  4985.5  311.16
  4992.6  310.79  4995.4  310.29  4998.6  310.79  5003.2  311.43  5008.2  316.01
  5019.5  316.08  5106.5  316.16    5177  325.58    5308     333  5368.5  339.15
#Mann= 5 ,-1 , 0
  4080.8     .16       0  4264.1     .12       0  4992.6     .07       0
  4998.6     .12       0  5019.5     .16       0
Bank Sta=4975.5,5008.2
XS Rating Curve= 0 ,0
Exp/Cntr=0.3,0.1

Type RM Length L Ch R = 1 ,169564  ,747,747,747
BEGIN DESCRIPTION:
CATFISH CREEK 128.0
END DESCRIPTION:
XS GIS Cut Line= 4
      3701839.78     10734772.73      3700683.54     10735220.64
       3700600.2     10735428.98      3700798.11     10736251.86
#Sta/Elev= 30
  3615.4  363.63  3621.6  362.16    3706  358.52  3869.5  347.78  3945.6  345.14
  4055.3  336.49  4147.3  323.89  4201.8  318.19  4325.8  314.56  4379.8  313.87
  4655.8  312.56  4910.8  313.49  4973.4  314.06  4982.9  310.62  4988.3  313.89
  4994.9  310.21  5014.9  309.94  5017.7  309.44  5020.9  309.94  5027.2  313.88
  5202.9  312.94  5304.2  312.93  5359.5  313.52  5443.4  317.24  5480.2  321.63
  5492.4  319.62  5527.3   319.6  5605.5  323.13  5784.2  339.31  5926.1  358.33
#Mann= 9 ,-1 , 0
  3615.4     .16       0  3945.6     .05       0  4325.8     .16       0
  4379.8     .12       0  4910.8     .16       0  5014.9     .07       0
  5020.9     .16       0  5202.9     .12       0  5304.2     .16       0
Bank Sta=4973.4,5027.2
XS Rating Curve= 0 ,0
Exp/Cntr=0.3,0.1

Type RM Length L Ch R = 1 ,168817  ,538,538,538
BEGIN DESCRIPTION:
CATFISH CREEK 127.0
END DESCRIPTION:
XS GIS Cut Line= 3
      3702008.71     10734166.05      3700227.49     10734931.66
      3699560.84     10735780.61
#Sta/Elev= 30
  3156.8  352.33  3186.1     352  3375.7  349.66  3398.3  348.73  3480.4  345.66
  3493.2  347.87  3503.9  345.07    3700  335.26  3842.7  323.26  4553.9  313.52
  4654.7  313.02  4764.3  311.99  4984.4  312.44  5004.4  308.59  5007.2  308.09
  5010.4  308.59  5020.5  311.03    5031  312.87  5162.1   311.6  5222.4  311.34
  5283.4  311.52  5449.7  316.68  5669.6  336.32  5805.7     333  5818.7  336.04
  5876.6  339.31  5996.8  355.07  6118.8  355.19  6167.5  359.83    6175  359.92
#Mann= 14 ,-1 , 0
  3156.8     .16       0  3186.1     .05       0  3375.7     .16       0
  3398.3     .05       0  4553.9     .16       0  4654.7     .12       0
  4764.3     .16       0  5004.4     .07       0  5010.4     .16       0
  5020.5     .12       0  5162.1     .16       0  5222.4     .12       0
  5283.4     .16       0  6167.5     .05       0
Bank Sta=4984.4,5031
XS Rating Curve= 0 ,0
Exp/Cntr=0.3,0.1

Type RM Length L Ch R = 1 ,168279  ,549,549,549
BEGIN DESCRIPTION:
CATFISH CREEK 126.0
END DESCRIPTION:
XS GIS Cut Line= 3
      3701399.58     10732860.22      3699999.61     10734460.19
      3699549.58     10735110.23
#Sta/Elev= 30
  2839.6  373.02  2932.1   367.4  3052.2  355.24  3094.4  349.39  3156.3  344.81
  3243.4  336.86  3314.6     333  3321.2  331.24  3399.1  328.04  3406.7  329.44
  3548.1  321.24  3623.3  320.55  3838.5  315.42  4051.1  316.93  4207.7  314.56
  4882.6  310.27  4987.9  312.19    4994  308.08  4999.1  308.05  5001.8  307.55
  5005.1  308.05  5023.7  311.74  5160.2  310.05  5390.6  311.09  5439.9  314.95
  5462.9  320.52  5504.1  323.85  5584.5  334.42  5656.2  346.71  5756.2  359.49
#Mann= 7 ,-1 , 0
  2839.6     .05       0  3156.3     .16       0  3623.3     .05       0
  4882.6     .16       0  4999.1     .07       0  5005.1     .16       0
  5462.9     .05       0
Bank Sta=4987.9,5023.7
XS Rating Curve= 0 ,0
Exp/Cntr=0.3,0.1

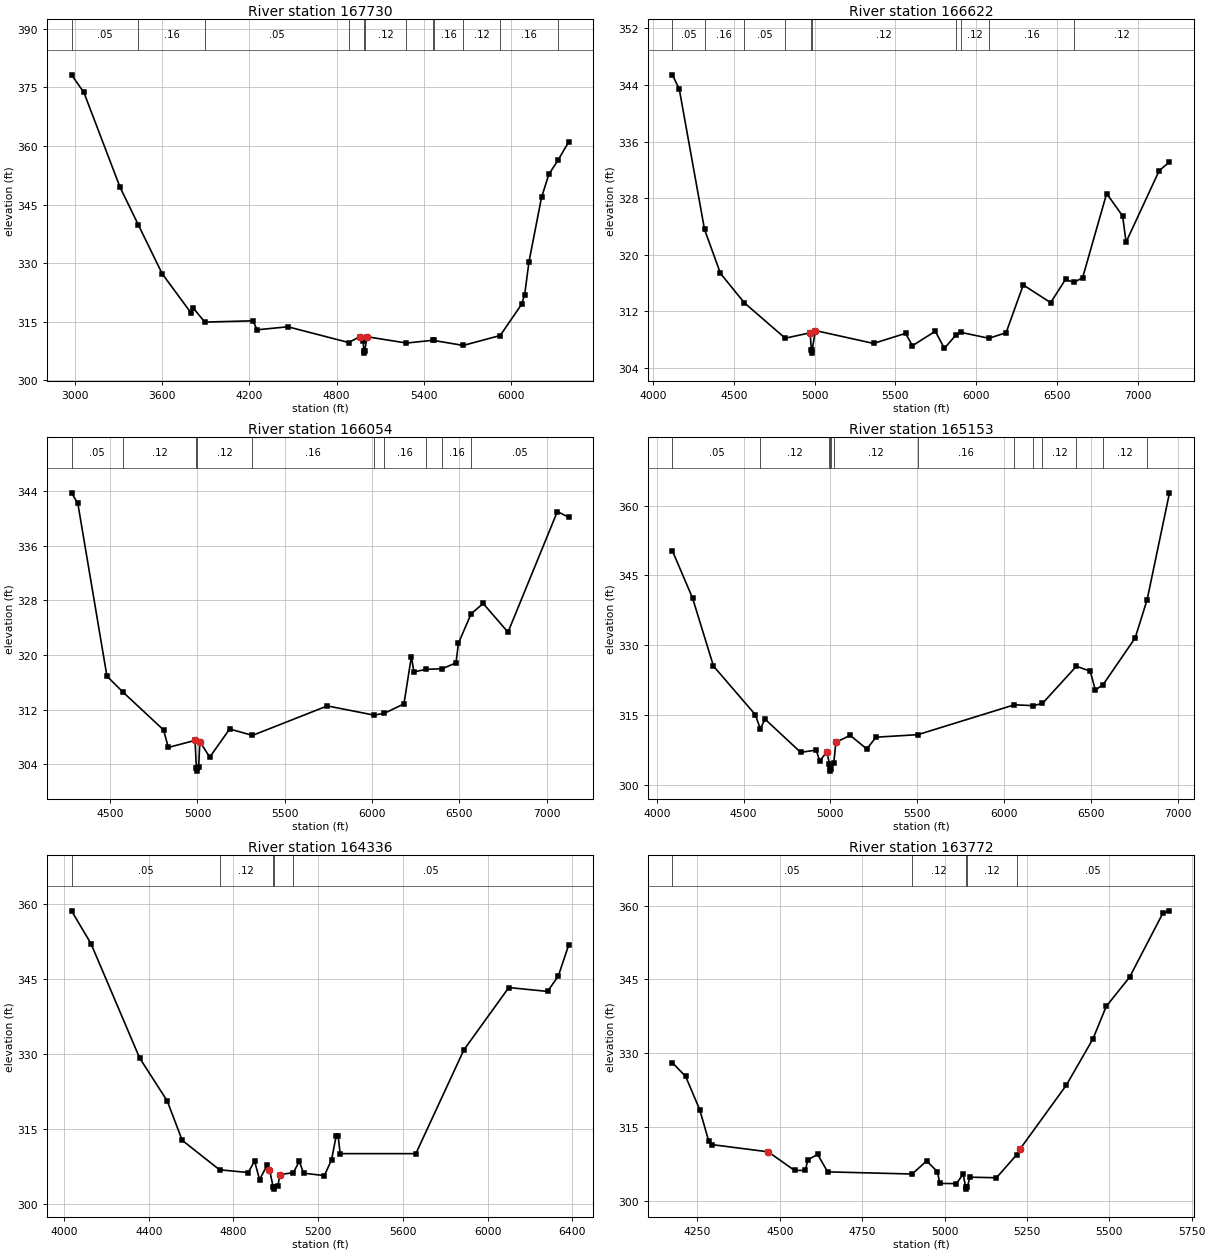
Type RM Length L Ch R = 1 ,167730  ,1108,1108,1108
BEGIN DESCRIPTION:
CATFISH CREEK 125.0
END DESCRIPTION:
XS GIS Cut Line= 3
      3701399.64     10732710.16      3699849.61     10734010.19
      3698699.63     10734810.18
#Sta/Elev= 30
    2974   378.2  3059.2  373.69  3307.7  349.49  3433.3  339.88  3599.1  327.27
  3796.9   317.3  3811.2   318.6    3892  314.93  4223.6  315.26  4252.2  312.96
  4464.3  313.73  4883.3   309.7  4961.3  311.22  4983.4  310.18  4986.9  307.49
  4989.6  306.99  4992.9  307.49  5010.5  311.18  5281.3  309.57  5465.4  310.28
  5467.7  310.24  5672.4  308.96  5927.1   311.5  6074.5  319.49  6095.5  321.91
  6125.2  330.36  6211.6  346.83  6262.2  352.75    6324  356.28  6397.9  360.96
#Mann= 12 ,-1 , 0
    2974     .05       0  3433.3     .16       0    3892     .05       0
  4883.3     .12       0  4986.9     .07       0  4992.9     .12       0
  5281.3     .16       0  5465.4     .12       0  5467.7     .16       0
  5672.4     .12       0  5927.1     .16       0    6324     .05       0
Bank Sta=4961.3,5010.5
XS Rating Curve= 0 ,0
Exp/Cntr=0.3,0.1

Type RM Length L Ch R = 1 ,166622  ,568,568,568
BEGIN DESCRIPTION:
CATFISH CREEK 123.0
END DESCRIPTION:
XS GIS Cut Line= 3
      3700449.64     10732460.16      3699849.61     10733060.19
      3698249.64     10734610.16
#Sta/Elev= 30
  4120.4  345.42  4162.9  343.37  4318.8  323.59  4417.4  317.38  4564.7  313.23
  4818.2  308.22  4972.5  308.98    4980  306.61  4982.8  306.11    4986  306.61
  5004.3   309.3    5365  307.48  5563.1   308.9  5605.5  307.16    5747  309.19
  5803.6  306.79  5876.9  308.72  5903.9  309.05  6079.2  308.21  6185.3  308.99
  6291.5  315.74  6461.1  313.24  6553.2  316.53  6605.1  316.09  6659.1  316.78
  6807.6  328.65  6906.6  325.48  6927.9  321.79    7133  331.89  7196.6   333.1
#Mann= 10 ,-1 , 0
  4120.4     .05       0  4318.8     .16       0  4564.7     .05       0
  4818.2     .12       0    4980     .07       0    4986     .12       0
  5876.9     .16       0  5903.9     .12       0  6079.2     .16       0
  6605.1     .12       0
Bank Sta=4972.5,5004.3
XS Rating Curve= 0 ,0
Exp/Cntr=0.3,0.1

Type RM Length L Ch R = 1 ,166054  ,901,901,901
BEGIN DESCRIPTION:
CATFISH CREEK 122.0
END DESCRIPTION:
XS GIS Cut Line= 3
      3699949.64     10732210.15      3699549.61     10732810.19
       3697949.6      10734210.2
#Sta/Elev= 30
  4278.5  343.76  4314.6  342.22  4481.4  316.91  4571.8  314.61  4805.9  309.03
  4832.9  306.47  4986.1   307.5  4993.7   303.5  4996.4     303  4999.7   303.5
  5006.8  303.54  5013.4  307.32  5070.4  305.05  5184.3  309.17  5314.9  308.23
  5743.8  312.55  6010.3  311.21  6068.9  311.45  6182.7  312.85  6225.4  319.78
  6239.7  317.54  6310.7  317.91  6401.6  317.99  6480.8  318.86    6495  321.74
  6567.2  326.02  6636.4  327.56  6778.8  323.35  7061.6  341.02  7125.7  340.19
#Mann= 10 ,-1 , 0
  4278.5     .05       0  4571.8     .12       0  4993.7     .07       0
  4999.7     .12       0  5314.9     .16       0  6010.3     .12       0
  6068.9     .16       0  6310.7     .05       0  6401.6     .16       0
  6567.2     .05       0
Bank Sta=4986.1,5013.4
XS Rating Curve= 0 ,0
Exp/Cntr=0.3,0.1

Type RM Length L Ch R = 1 ,165153  ,817,817,817
BEGIN DESCRIPTION:
CATFISH CREEK 121.0
END DESCRIPTION:
XS GIS Cut Line= 4
      3699702.06      10731638.6      3699163.86     10732176.79
      3698816.64      10732263.6      3697393.82     10733269.98
#Sta/Elev= 30
  4090.5  350.25  4206.5  340.11  4326.7  325.52  4567.1   315.1  4596.3  312.06
  4623.7  314.12  4828.8  306.99  4917.9  307.48  4938.5  305.14  4979.7  307.09
  4994.6   304.5  4997.3  303.46  5000.1  302.96  5003.3  303.46  5019.7  304.77
  5031.2  309.16  5113.7  310.64  5209.5  307.72  5262.6  310.25  5503.4  310.79
  6059.7  317.21  6166.9  317.02  6220.7  317.49  6416.2  325.49  6495.9  324.42
  6525.5  320.37  6570.3  321.55  6754.4  331.55  6823.3  339.74  6952.3  362.73
#Mann= 13 ,-1 , 0
  4090.5     .05       0  4596.3     .12       0  4994.6     .05       0
  4997.3     .03       0  5003.3     .05       0  5019.7     .12       0
  5503.4     .16       0  6059.7     .12       0  6166.9     .16       0
  6220.7     .12       0  6416.2     .16       0  6570.3     .12       0
  6823.3     .16       0
Bank Sta=4979.7,5031.2
XS Rating Curve= 0 ,0
Exp/Cntr=0.3,0.1

Type RM Length L Ch R = 1 ,164336  ,564,564,564
BEGIN DESCRIPTION:
CATFISH CREEK 120.0
END DESCRIPTION:
XS GIS Cut Line= 3
      3699719.38     10731456.31      3698599.62     10731569.16
      3697403.13     10731326.39
#Sta/Elev= 30
  4035.4  358.56  4127.3  352.01  4356.8  329.21  4487.5   320.6  4557.8  312.77
    4734  306.89  4869.4  306.34  4899.5  308.63  4923.2   304.9  4959.8  307.91
  4969.9  306.93    4987  303.53  4989.7  303.03    4993  303.53  5010.1  303.64
  5018.3  305.94  5082.6  306.31  5110.6  308.57  5130.7  306.21  5229.1  305.73
  5262.9  308.89  5284.9  313.69  5293.5  313.73  5303.7  310.11  5660.8  310.11
  5887.6  330.82  6099.6  343.25  6282.7  342.48  6333.3  345.56  6381.7  351.65
#Mann= 5 ,-1 , 0
  4035.4     .05       0    4734     .12       0    4987     .07       0
    4993     .12       0  5082.6     .05       0
Bank Sta=4969.9,5018.3
XS Rating Curve= 0 ,0
Exp/Cntr=0.3,0.1

Type RM Length L Ch R = 1 ,163772  ,524,524,524
BEGIN DESCRIPTION:
CATFISH CREEK 118.0
END DESCRIPTION:
XS GIS Cut Line= 3
      3699199.59     10731110.19      3698399.61     10731160.19
      3697699.65      10731060.2
#Sta/Elev= 30
  4174.1  328.05  4214.2  325.27  4256.7  318.55  4284.3  312.13  4294.3  311.42
  4464.6  309.96  4544.8  306.18  4577.4  306.18  4584.9  308.32  4614.9  309.44
    4645  305.89  4901.5  305.45  4945.6  308.11  4978.2  305.93  4985.7  303.54
  5036.2   303.5  5056.5  305.46  5063.6  302.88  5066.3  302.38  5069.6  302.88
  5076.7  304.81  5157.5  304.69  5219.5  309.41  5228.2  310.44  5369.6  323.51
  5450.4  332.91  5490.8  339.52  5561.5  345.44  5662.5  358.44  5682.7  358.93
#Mann= 5 ,-1 , 0
  4174.1     .05       0  4901.5     .12       0  5063.6     .07       0
  5069.6     .12       0  5219.5     .05       0
Bank Sta=4464.6,5228.2
XS Rating Curve= 0 ,0
Exp/Cntr=0.3,0.1

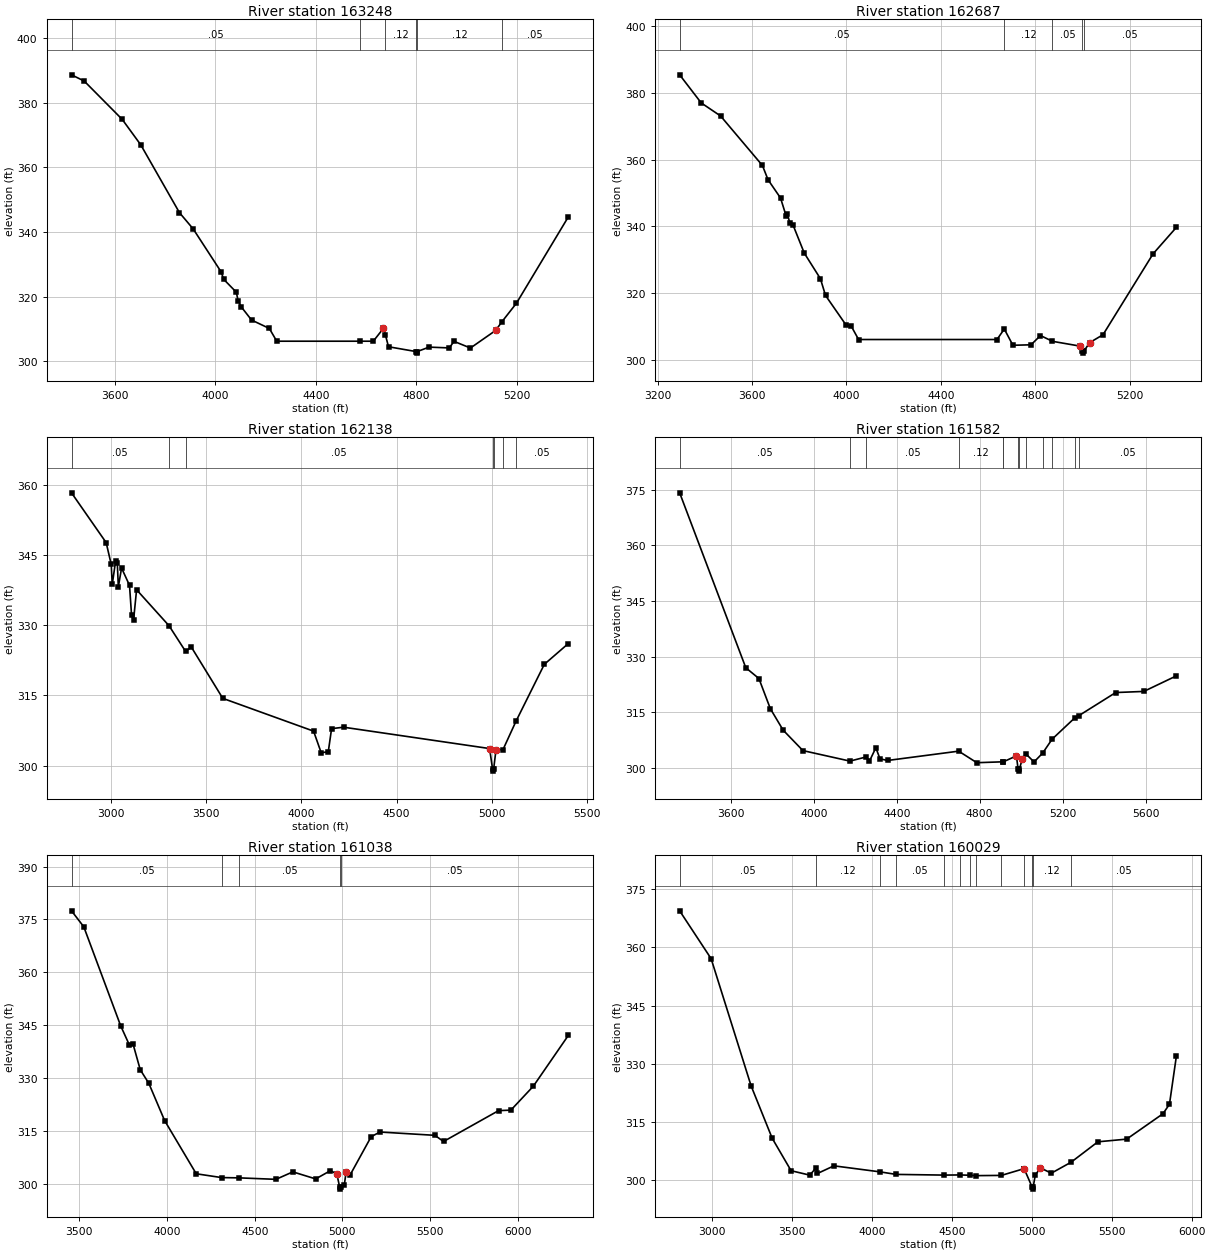
Type RM Length L Ch R = 1 ,163248  ,561,561,561
BEGIN DESCRIPTION:
CATFISH CREEK 117.0
END DESCRIPTION:
XS GIS Cut Line= 3
      3699849.63     10730860.19      3698299.61     10730660.19
      3697899.59     10730560.18
#Sta/Elev= 30
  3428.8  388.62  3479.2   386.7  3630.5  374.82  3704.2  366.95    3858  345.96
  3912.8  340.91  4023.7  327.63  4033.8  325.34  4084.2  321.34  4091.1  318.68
  4104.4  316.74  4144.7  312.73  4215.3  310.13  4244.9  306.18  4577.6  306.18
  4628.7  306.18    4669  310.16  4676.9   308.1  4689.2  304.46  4797.7  302.99
  4800.5  302.49  4803.7  302.99  4850.5  304.35  4931.2   304.1  4949.4  306.14
  5014.9  304.07  5115.4  309.52  5139.3  312.12  5197.8  317.93    5404  344.64
#Mann= 6 ,-1 , 0
  3428.8     .05       0  4577.6     .07       0  4676.9     .12       0
  4797.7     .07       0  4803.7     .12       0  5139.3     .05       0
Bank Sta=4669,5115.4
XS Rating Curve= 0 ,0
Exp/Cntr=0.3,0.1

Type RM Length L Ch R = 1 ,162687  ,549,549,549
BEGIN DESCRIPTION:
CATFISH CREEK 116.0
END DESCRIPTION:
XS GIS Cut Line= 3
      3699799.63      10730760.2      3698249.61     10730110.19
      3697949.58     10730410.22
#Sta/Elev= 30
  3293.3  385.35  3384.7  376.95  3466.8  373.04  3644.1  358.23  3667.8  353.97
  3720.8  348.51  3744.6  343.11    3750  343.73  3759.6  341.14  3773.8  340.42
  3821.3  332.04  3889.7  324.38  3911.4  319.36  3998.2  310.53  4019.9  310.24
  4051.5  306.18  4637.9  306.18  4668.9  309.32  4705.5  304.46  4782.2   304.6
  4822.3  307.37  4873.2  305.64  4988.2  304.23  4999.4  302.61  5002.1  302.11
  5005.4  302.61  5030.7  305.25  5087.2  307.61  5299.4  331.81  5398.4  339.75
#Mann= 5 ,-1 , 0
  3293.3     .05       0  4668.9     .12       0  4873.2     .05       0
  4999.4     .03       0  5005.4     .05       0
Bank Sta=4988.2,5030.7
XS Rating Curve= 0 ,0
Exp/Cntr=0.3,0.1

Type RM Length L Ch R = 1 ,162138  ,556,556,556
BEGIN DESCRIPTION:
CATFISH CREEK 115.0
END DESCRIPTION:
XS GIS Cut Line= 3
      3700199.86     10730290.65      3698099.61     10729610.19
      3697749.65     10729810.17
#Sta/Elev= 30
  2791.6  358.26  2973.7  347.63  3000.4  342.97  3005.7  338.69  3023.1  343.61
  3032.4  343.19  3037.7  338.19  3054.7   342.2  3096.4  338.51  3107.2  332.13
  3117.7  331.09  3133.6  337.56  3304.3  329.87  3390.9  324.41  3421.5  325.31
  3586.7  314.37  4063.8  307.37  4103.8  302.75  4141.1  302.98  4158.4   307.9
  4221.5  308.21  4988.8  303.65  5004.2  299.33    5007  298.83  5010.2  299.33
  5022.4  303.33  5059.3  303.43  5127.9  309.51  5276.5  321.64  5402.4  326.07
#Mann= 7 ,-1 , 0
  2791.6     .05       0  3304.3     .16       0  3390.9     .05       0
  5004.2     .03       0  5010.2     .05       0  5059.3     .16       0
  5127.9     .05       0
Bank Sta=4988.8,5022.4
XS Rating Curve= 0 ,0
Exp/Cntr=0.3,0.1

Type RM Length L Ch R = 1 ,161582  ,544,544,544
BEGIN DESCRIPTION:
CATFISH CREEK 114.0
END DESCRIPTION:
XS GIS Cut Line= 3
      3699649.59      10728510.2      3698099.61     10729060.19
      3697499.58     10729510.21
#Sta/Elev= 30
  3353.8  374.12  3672.6     327  3735.8   324.1  3790.8  315.99  3852.5   310.2
    3948  304.68  4174.8  301.85    4252  302.96  4268.7  301.84  4299.6  305.45
  4319.4  302.47    4356  302.02  4698.7  304.53  4786.3  301.42  4911.7  301.66
  4913.3  301.64  4977.2  303.26  4985.3  299.65  4988.1  299.15  4991.3  299.65
  5005.8  302.51    5022  303.84    5062  301.62  5103.7  304.01  5149.4  307.77
  5259.1  313.53  5276.9  314.05  5455.8  320.32  5591.2  320.62  5748.5  324.82
#Mann= 13 ,-1 , 0
  3353.8     .05       0  4174.8     .07       0    4252     .05       0
  4698.7     .12       0  4911.7     .07       0  4913.3     .12       0
  4985.3     .07       0  4991.3     .12       0    5022     .05       0
  5103.7     .12       0  5149.4     .05       0  5259.1     .16       0
  5276.9     .05       0
Bank Sta=4977.2,5005.8
XS Rating Curve= 0 ,0
Exp/Cntr=0.3,0.1

Type RM Length L Ch R = 1 ,161038  ,1009,1009,1009
BEGIN DESCRIPTION:
CATFISH CREEK 113.0
END DESCRIPTION:
XS GIS Cut Line= 3
      3699649.61     10728460.19      3698099.61     10728560.19
      3697099.57     10729360.22
#Sta/Elev= 30
  3454.9  377.45    3525  372.91  3735.5  344.78  3785.6  339.28  3805.6  339.68
    3847  332.32  3895.8  328.47    3986  317.89  4166.4  302.77  4311.1  301.69
  4410.5  301.61  4621.1  301.19  4717.5  303.31  4847.8  301.31  4931.7  303.65
    4968  302.77  4985.1  298.91  4987.8  298.41  4991.1  298.91  5011.3  299.71
  5021.7  303.35  5044.1  302.42  5164.2  313.29  5213.8  314.63  5527.6  313.69
  5577.2  311.94    5891   320.7  5961.4  320.85  6089.5  327.65  6288.8  342.05
#Mann= 5 ,-1 , 0
  3454.9     .05       0  4311.1     .07       0  4410.5     .05       0
  4985.1     .03       0  4991.1     .05       0
Bank Sta=4968,5021.7
XS Rating Curve= 0 ,0
Exp/Cntr=0.3,0.1

Type RM Length L Ch R = 1 ,160029  ,391,391,391
BEGIN DESCRIPTION:
CATFISH CREEK 112.0
END DESCRIPTION:
XS GIS Cut Line= 3
       3699549.6     10728360.19      3697349.61     10727960.19
       3696999.6     10728760.21
#Sta/Elev= 30
  2795.6  369.46  2992.5  357.12  3242.8   324.3  3374.9  310.77  3493.1  302.41
    3610  301.27  3650.8  303.22  3658.3   301.7  3761.2  303.67  4050.4  302.11
  4150.3  301.46    4450  301.28  4549.9  301.32  4612.1  301.24  4649.8  301.14
  4809.3   301.2  4949.5  302.92  4951.6  302.93    5002  298.16  5004.7  297.66
    5008  298.16  5021.5  301.29  5053.5  303.14  5121.7  301.77  5245.8  304.61
  5413.3  309.87  5593.4  310.56  5820.3   317.1  5861.2  319.55  5904.9  332.08
#Mann= 13 ,-1 , 0
  2795.6     .05       0  3650.8     .12       0  4050.4     .07       0
  4150.3     .05       0    4450     .12       0  4549.9     .05       0
  4612.1     .07       0  4649.8     .05       0  4809.3     .07       0
  4949.5     .12       0    5002     .07       0    5008     .12       0
  5245.8     .05       0
Bank Sta=4951.6,5053.5
XS Rating Curve= 0 ,0
Exp/Cntr=0.3,0.1