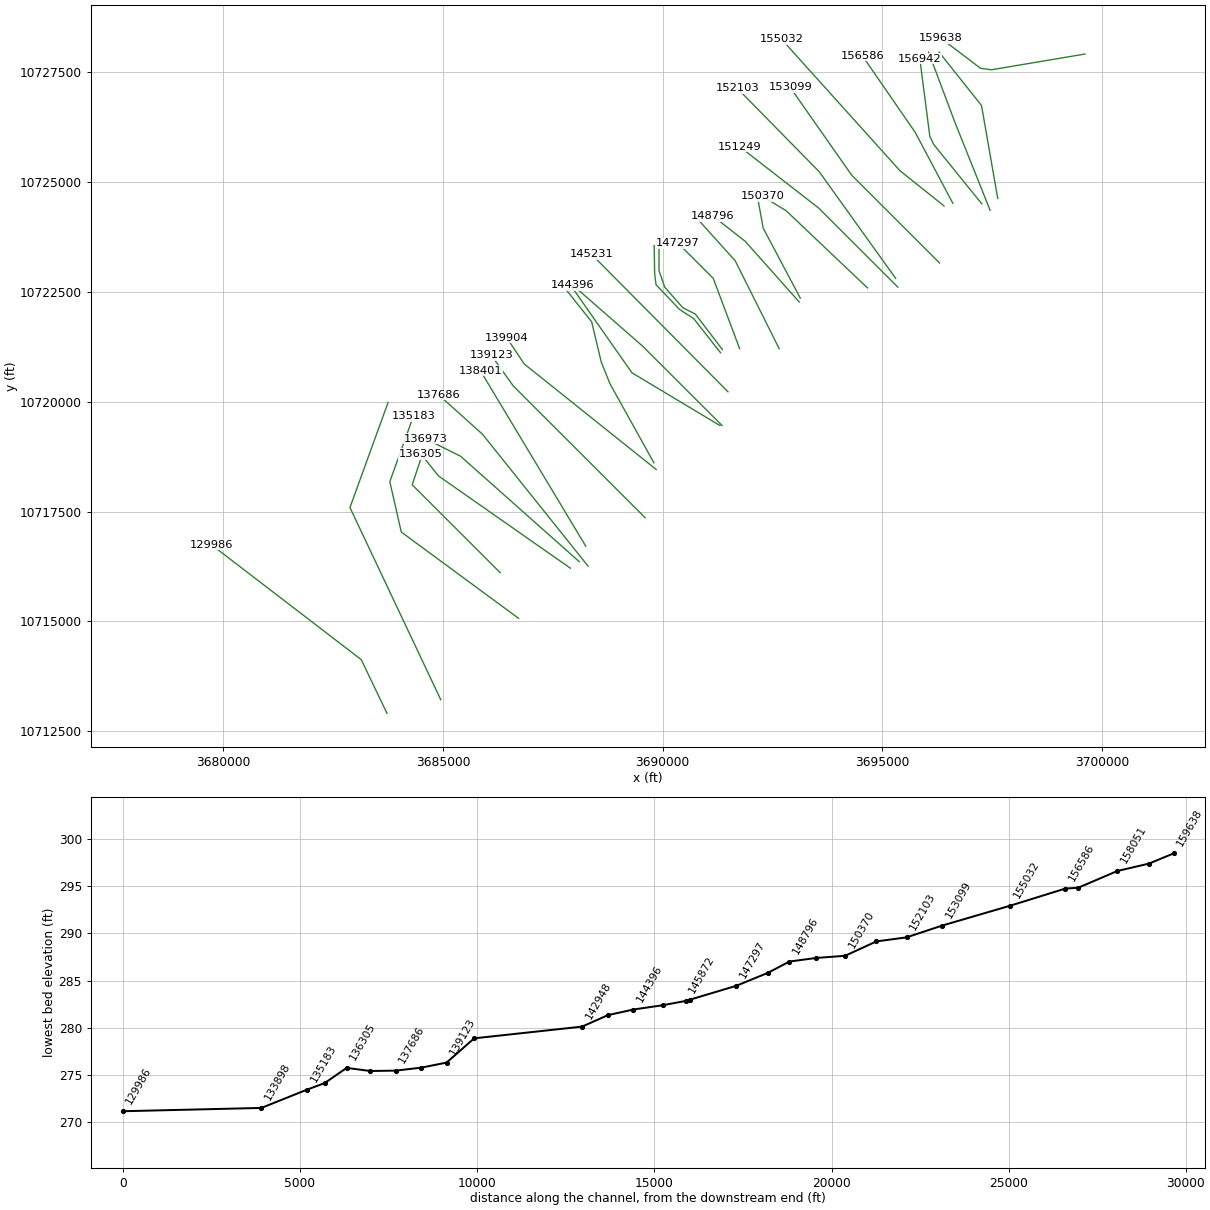
HEC-RAS study CATFISH CREEK.prj: CATFISH CREEK Base Level Engineering

--- CATFISH CREEK.g01 (geometry) --- (continued)

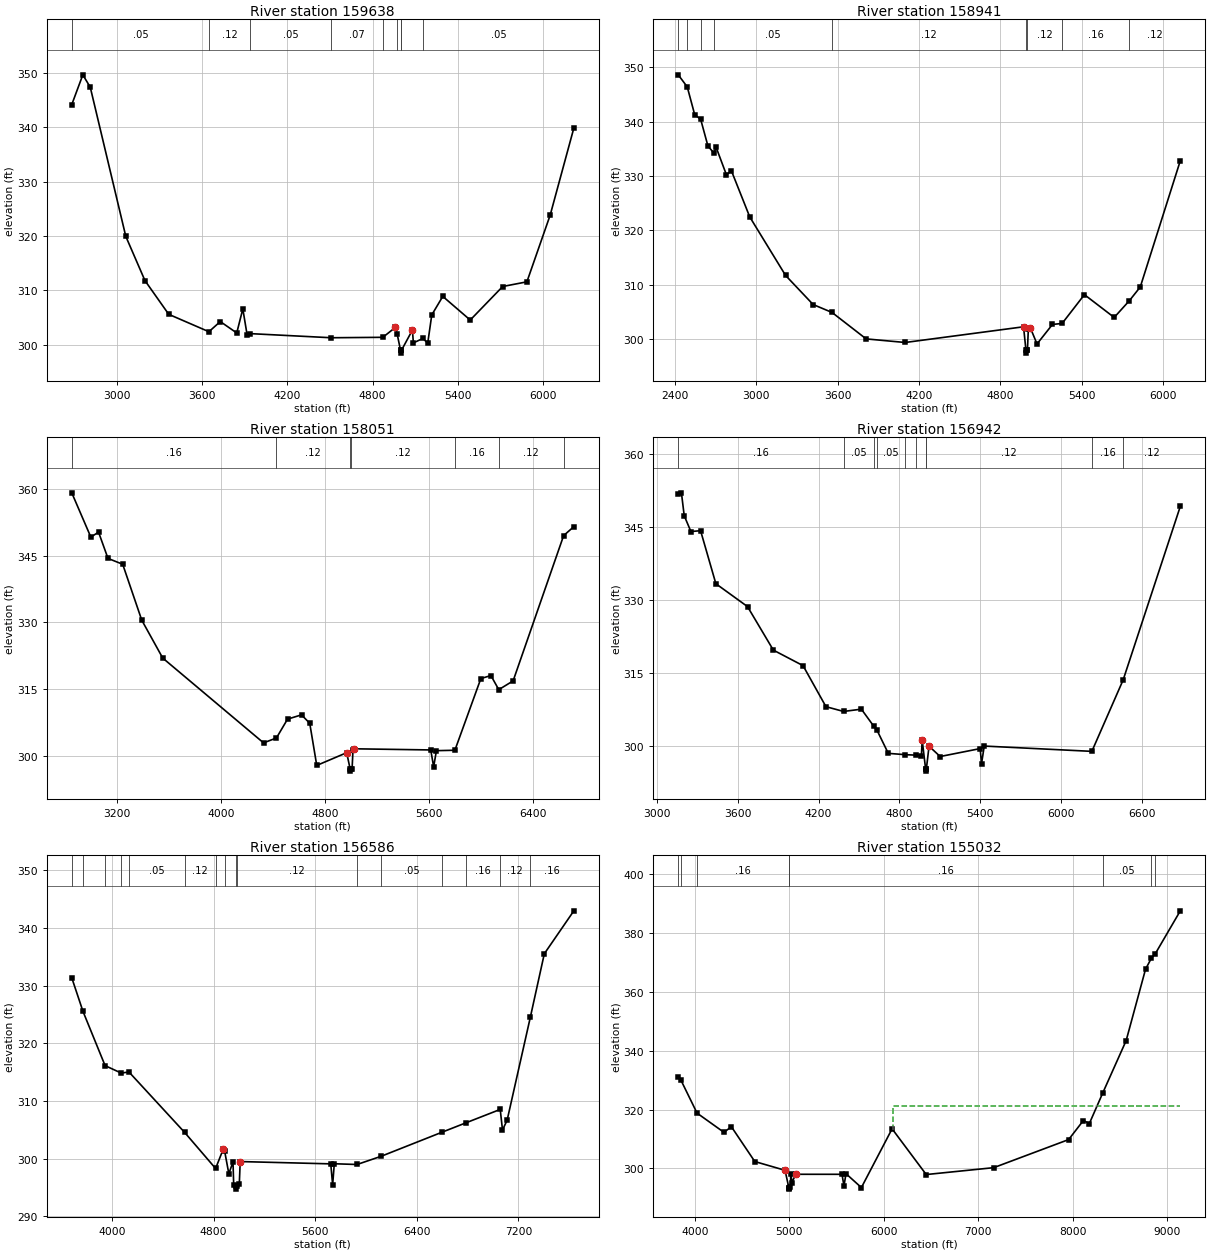
Type RM Length L Ch R = 1 ,159638  ,697,697,697
BEGIN DESCRIPTION:
CATFISH CREEK 111.0
END DESCRIPTION:
XS GIS Cut Line= 4
      3699608.06     10727918.68      3697481.37     10727560.62
       3697231.8     10727593.17       3696332.2       10728276.
#Sta/Elev= 30
  2680.7  344.19  2758.6  349.67    2811  347.39  3061.3  319.95  3196.3  311.81
    3364   305.6    3647   302.4  3727.2  304.27  3843.2  302.17  3885.9   306.6
  3916.3  301.81  3936.7  302.05  4508.8  301.29  4872.7  301.37  4960.1  303.18
    4973  302.03  4997.5  298.96  5000.2  298.46  5003.5  298.96  5081.1  302.72
  5087.6  300.34  5155.5  301.17  5188.7  300.26  5217.3  305.49  5294.9   308.9
  5488.3  304.55    5717  310.72  5887.6  311.58  6051.9  323.88  6218.4  339.88
#Mann= 9 ,-1 , 0
  2680.7     .05       0    3647     .12       0  3936.7     .05       0
  4508.8     .07       0  4872.7     .05       0    4973     .12       0
  4997.5     .07       0  5003.5     .12       0  5155.5     .05       0
Bank Sta=4960.1,5081.1
XS Rating Curve= 0 ,0
Exp/Cntr=0.3,0.1

Type RM Length L Ch R = 1 ,158941  ,890,890,890
BEGIN DESCRIPTION:
CATFISH CREEK 110.0
END DESCRIPTION:
XS GIS Cut Line= 3
      3697622.43     10724630.91       3697253.5     10726746.82
      3696287.78     10727962.11
#Sta/Elev= 30
  2425.8  348.63  2492.2  346.41  2546.9  341.31  2591.1  340.44  2644.6  335.53
  2689.9  334.18  2704.2  335.34  2780.3  330.26  2818.3  330.92  2952.9  322.46
  3216.8  311.69  3419.8  306.33  3559.3  304.87  3810.5     300  4098.2  299.34
  4970.6  302.23  4988.4  297.88  4991.2  297.38  4994.4  297.88  4999.4  297.97
  5005.8  301.78  5020.3  302.06  5069.9  299.07  5183.6  302.66    5255  302.85
  5419.2  308.15  5638.6  303.95  5750.9  307.05  5830.8  309.56  6125.9  332.82
#Mann= 9 ,-1 , 0
  2425.8     .16       0  2492.2     .05       0  2591.1     .16       0
  2689.9     .05       0  3559.3     .12       0  4988.4     .07       0
  4994.4     .12       0    5255     .16       0  5750.9     .12       0
Bank Sta=4970.6,5020.3
XS Rating Curve= 0 ,0
Exp/Cntr=0.3,0.1

Type RM Length L Ch R = 1 ,158051  ,1109,1109,1109
BEGIN DESCRIPTION:
CATFISH CREEK 109.0
END DESCRIPTION:
XS GIS Cut Line= 3
       3697449.6     10724360.21      3696649.61     10726360.19
      3696049.63     10727960.14
#Sta/Elev= 30
  2849.5  359.14  2996.2  349.19  3055.5  350.31  3128.2   344.4  3241.3  343.09
    3388  330.52  3549.6     322    4325  302.95  4424.1  304.05  4509.5  308.28
  4617.2  309.25  4680.4  307.35  4734.3  297.88  4964.5  300.74  4991.1   297.1
  4993.9   296.6  4997.1   297.1  5006.2  297.14  5013.3  301.45  5018.7  301.62
  5611.4  301.36  5633.7  297.57    5655   301.2  5797.1  301.29  5996.8   317.4
  6074.2  318.08  6134.7  314.91  6245.1  316.88  6633.8  349.53  6712.3  351.54
#Mann= 7 ,-1 , 0
  2849.5     .16       0  4424.1     .12       0  4991.1     .07       0
  4997.1     .12       0  5797.1     .16       0  6134.7     .12       0
  6633.8     .05       0
Bank Sta=4964.5,5018.7
XS Rating Curve= 0 ,0
Exp/Cntr=0.3,0.1

Type RM Length L Ch R = 1 ,156942  ,356,356,356
BEGIN DESCRIPTION:
CATFISH CREEK 108.0
END DESCRIPTION:
XS GIS Cut Line= 4
      3697259.91     10724507.27      3696164.02      10725861.4
      3696077.21     10726045.86      3695849.35     10727814.55
#Sta/Elev= 30
  3157.5  351.81  3181.2  351.99    3202  347.28  3251.6  344.04  3323.5  344.21
    3437  333.32    3672  328.62  3863.9  319.68  4084.5  316.49  4254.7  308.06
  4385.6  307.08  4517.8  307.55  4608.1  304.11  4631.8  303.34  4717.6  298.47
  4843.8   298.2    4926   298.1  4963.8  298.01  4969.3  301.21  4994.7  295.32
  4997.4  294.82  5000.7  295.32  5020.4  299.94    5103  297.82  5400.2  299.45
  5410.2  296.33  5430.4  299.97  6229.7  298.88  6462.3  313.57  6886.7  349.21
#Mann= 10 ,-1 , 0
  3157.5     .16       0  4385.6     .05       0  4608.1     .16       0
  4631.8     .05       0  4843.8     .16       0    4926     .12       0
  4994.7     .07       0  5000.7     .12       0  6229.7     .16       0
  6462.3     .12       0
Bank Sta=4969.3,5020.4
XS Rating Curve= 0 ,0
Exp/Cntr=0.3,0.1

Type RM Length L Ch R = 1 ,156586  ,1554,1554,1554
BEGIN DESCRIPTION:
Mapping XS cd90c643
END DESCRIPTION:
XS GIS Cut Line= 3
       3696601.6     10724518.81      3695744.38     10726135.58
      3694539.94     10727882.56
#Sta/Elev= 30
  3683.9  331.38  3771.7  325.58  3946.2  316.15  4073.3  314.86    4134  315.05
  4572.4  304.57    4816  298.32  4876.3  301.68  4886.3  301.43  4920.2  297.41
  4952.9  299.46  4958.6  295.37  4977.6  295.24  4980.3  294.74  4983.6  295.24
  5002.6  295.63  5009.7  299.52  5722.4  299.12  5737.3  295.47  5750.2  299.14
  5929.2  299.01  6119.9  300.44  6599.5  304.62  6788.1  306.25  7056.3  308.56
  7074.2     305  7110.6  306.68    7293  324.51  7403.4  335.55  7635.8  342.99
#Mann= 16 ,-1 , 0
  3683.9     .12       0  3771.7     .16       0  3946.2     .05       0
  4073.3      .1       0    4134     .05       0  4572.4     .12       0
    4816     .05       0  4886.3     .12       0  4977.6     .07       0
  4983.6     .12       0  5929.2     .16       0  6119.9     .05       0
  6599.5     .12       0  6788.1     .16       0  7056.3     .12       0
    7293     .16       0
Bank Sta=4876.3,5009.7
XS Rating Curve= 0 ,0
Exp/Cntr=0.3,0.1

Type RM Length L Ch R = 1 ,155032  ,1933,1933,1933
BEGIN DESCRIPTION:
CATFISH CREEK 107.0
END DESCRIPTION:
XS GIS Cut Line= 3
      3696399.62     10724460.18      3695399.61     10725260.19
      3692699.63     10728260.17
#Sta/Elev= 30
  3823.8  331.13  3851.6  330.04  4023.1  318.78  4308.1  312.24  4386.5  314.16
  4634.6  302.31  4954.8  299.33    4995  293.43  4997.7  292.93    5001  293.43
  5012.4  293.52  5018.8  297.91  5026.8  295.14  5068.4  297.98  5557.8  297.97
  5578.7  294.05  5600.4  298.18  5763.3  293.46  6088.4  313.44  6449.8  297.89
  7164.7  300.23  7957.7  309.78  8113.9  316.26  8177.5  315.25  8319.5  325.66
  8566.9  343.44  8772.4  367.74  8833.4  371.42  8876.8  373.06  9140.5  387.58
#Mann= 8 ,-1 , 0
  3823.8     .16       0  3851.6     .05       0  4023.1     .16       0
    4995     .07       0    5001     .16       0  8319.5     .05       0
  8833.4     .16       0  8876.8     .05       0
#XS Ineff= 2 , 0
                          6098.3           321.3
Permanent Ineff=
       F       F
Bank Sta=4954.8,5068.4
XS Rating Curve= 0 ,0
Exp/Cntr=0.3,0.1

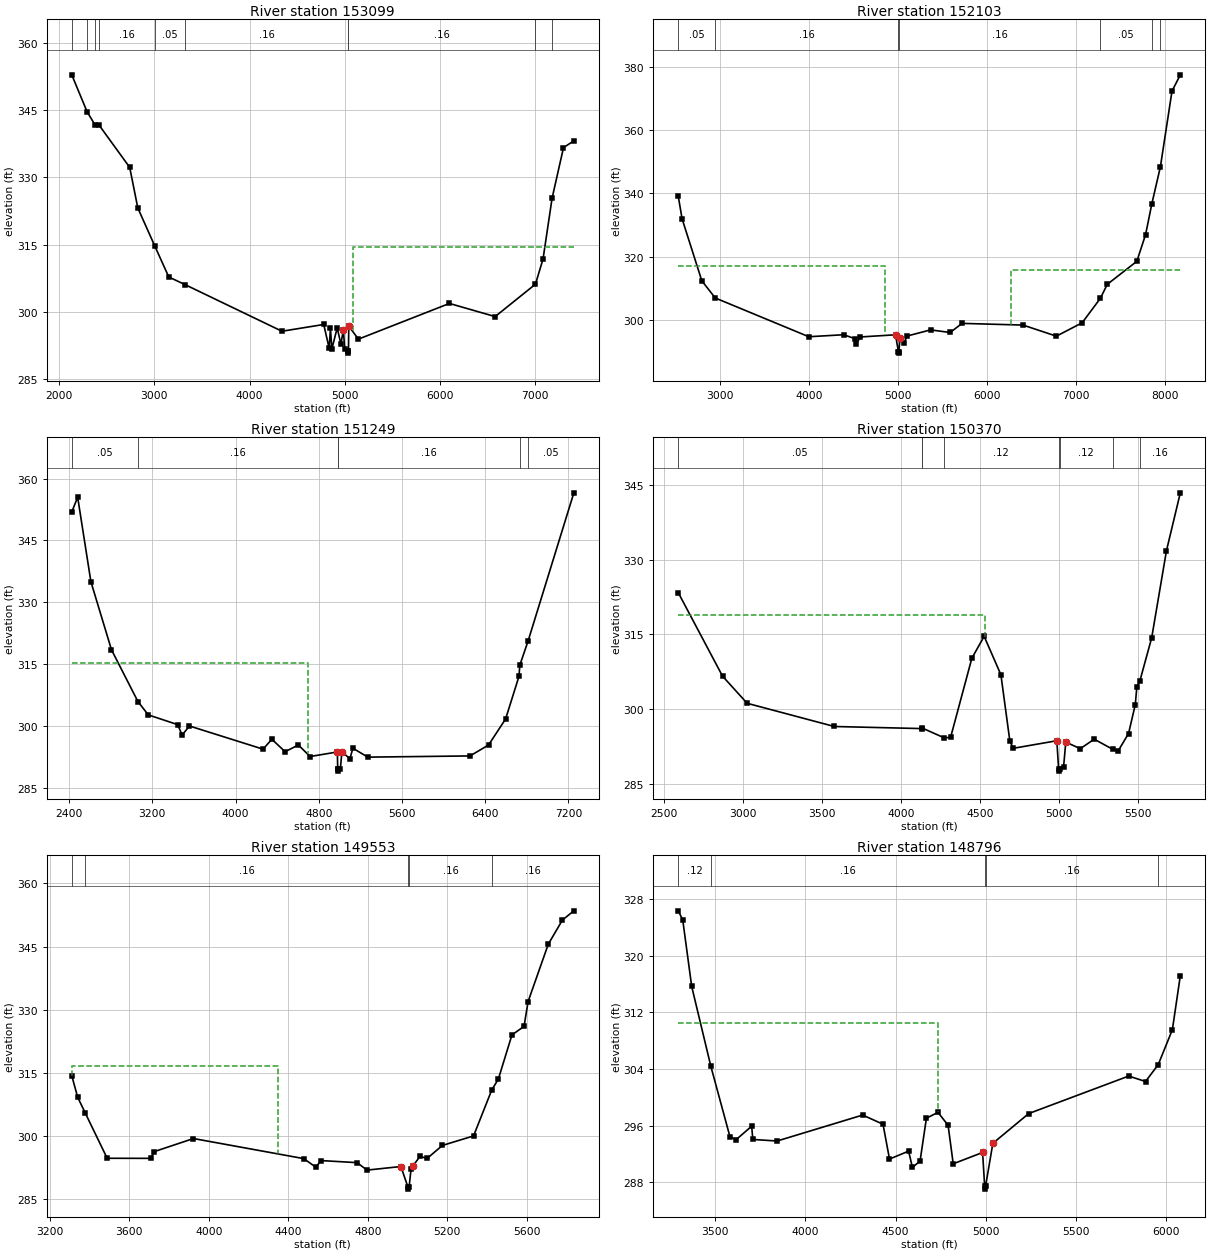
Type RM Length L Ch R = 1 ,153099  ,996,996,996
BEGIN DESCRIPTION:
CATFISH CREEK 105.0
END DESCRIPTION:
XS GIS Cut Line= 3
      3696299.63     10723160.17      3694299.61     10725160.19
      3692899.59     10727160.22
#Sta/Elev= 30
  2133.7  352.88  2294.8  344.63  2380.4  341.62    2421  341.64  2741.8  332.24
  2826.7  323.19  3003.4  314.78    3152  307.79  3321.7   306.1  4339.9  295.69
  4778.3   297.2  4834.9  291.93    4849  296.31  4863.2   291.7  4919.7  296.44
  4958.6  292.81  4984.4  295.98  4998.8  291.66    5032  291.31  5034.7  290.81
    5038  291.31  5041.1  296.83  5142.2  293.93  6097.4  301.89  6577.3  298.96
  7000.6  306.19  7080.4  311.83  7174.8  325.32  7294.9  336.65  7403.5  338.15
#Mann= 10 ,-1 , 0
  2133.7     .05       0  2294.8     .12       0  2380.4     .05       0
    2421     .16       0  3003.4     .05       0  3321.7     .16       0
    5032     .07       0    5038     .16       0  7000.6     .05       0
  7174.8     .16       0
#XS Ineff= 2 , 0
                         5081.82          314.44
Permanent Ineff=
       F       F
Bank Sta=4984.4,5041.1
XS Rating Curve= 0 ,0
Exp/Cntr=0.3,0.1

Type RM Length L Ch R = 1 ,152103  ,854,854,854
BEGIN DESCRIPTION:
CATFISH CREEK 104.0
END DESCRIPTION:
XS GIS Cut Line= 3
      3695299.62     10722810.17      3693561.75     10725237.36
      3691695.46     10727138.37
#Sta/Elev= 30
  2528.2  339.17  2571.2  332.04  2793.6  312.41  2944.7  306.99  3997.4  294.75
  4391.7  295.38  4520.7  294.07  4528.1  292.32  4578.5  294.68  4972.8  295.36
  5005.4  290.07  5008.2  289.57  5011.4  290.07  5023.1  294.36  5073.5   292.9
  5100.5  294.95  5367.1  296.91  5587.6  296.09    5722  298.97  6407.9  298.43
  6782.7  294.93  7072.7  299.15  7277.7  306.87  7355.4   311.3  7687.9  318.56
  7786.9  327.03  7857.4   336.8  7953.3  348.43  8083.8  372.33  8177.4  377.48
#Mann= 7 ,-1 , 0
  2528.2     .05       0  2944.7     .16       0  5005.4     .07       0
  5011.4     .16       0  7277.7     .05       0  7857.4     .16       0
  7953.3     .05       0
#XS Ineff= 2 , 0
         4855.68  317.05 6267.61          315.92
Permanent Ineff=
       F       F
Bank Sta=4972.8,5023.1
XS Rating Curve= 0 ,0
Exp/Cntr=0.3,0.1

Type RM Length L Ch R = 1 ,151249  ,879,879,879
BEGIN DESCRIPTION:
CATFISH CREEK 103.0
END DESCRIPTION:
XS GIS Cut Line= 3
      3695349.61     10722610.18      3693549.61     10724410.19
      3691749.64     10725810.16
#Sta/Elev= 30
  2425.8   351.9  2482.4  355.49  2609.7  335.01  2807.6  318.52  3062.2  305.97
  3161.2  302.76    3444   300.4  3486.5  297.88  3557.2  300.07  4264.3  294.46
  4349.1  296.86  4476.4  293.84  4603.7  295.47  4716.8  292.68  4978.6  293.78
    4982  289.64  4984.7  289.14    4988  289.64  5007.6  289.68  5022.1  293.85
    5099  292.13  5127.9  294.69  5270.9  292.53  6253.6  292.82  6431.9  295.47
  6595.7  301.77  6724.2  312.09  6732.3   314.8  6811.1  320.59  7251.7  356.54
#Mann= 6 ,-1 , 0
  2425.8     .05       0  3062.2     .16       0    4982     .07       0
    4988     .16       0  6732.3     .16       0  6811.1     .05       0
#XS Ineff= 2 , 0
         4693.18  315.24
Permanent Ineff=
       F       F
Bank Sta=4978.6,5022.1
XS Rating Curve= 0 ,0
Exp/Cntr=0.3,0.1

Type RM Length L Ch R = 1 ,150370  ,817,817,817
BEGIN DESCRIPTION:
CATFISH CREEK 102.0
END DESCRIPTION:
XS GIS Cut Line= 3
      3694658.61     10722593.04      3692804.44     10724353.46
      3692274.86     10724675.36
#Sta/Elev= 30
  2592.6  323.38  2872.8  306.65  3028.5  301.21  3580.2  296.56  4135.9  296.14
    4137  296.24  4273.8  294.31  4315.6  294.36  4450.3  310.24    4528  314.62
    4634  306.93  4690.6  293.66    4712  292.19  4987.9  293.71    4999  288.12
  5001.8  287.62    5005  288.12  5030.4  288.41  5044.5  293.43  5136.3  292.12
  5224.5  294.02  5340.3  292.01  5377.4  291.75  5441.6  295.15  5484.3  300.96
  5493.9  304.44  5513.7  305.74    5588  314.33  5681.6   331.8  5769.1  343.37
#Mann= 8 ,-1 , 0
  2592.6     .05       0  4135.9      .1       0    4137     .16       0
  4273.8     .12       0    4999     .07       0    5005     .12       0
  5340.3     .05       0  5513.7     .16       0
#XS Ineff= 2 , 0
          4530.4  318.81
Permanent Ineff=
       F       F
Bank Sta=4987.9,5044.5
XS Rating Curve= 0 ,0
Exp/Cntr=0.3,0.1

Type RM Length L Ch R = 1 ,149553  ,757,757,757
BEGIN DESCRIPTION:
CATFISH CREEK 101.0
END DESCRIPTION:
XS GIS Cut Line= 3
      3693129.64     10722361.05       3692285.9     10723954.77
      3692155.98     10724666.73
#Sta/Elev= 30
  3310.5  314.33  3340.2  309.22  3377.4  305.57  3488.6  294.72  3708.6   294.7
  3724.9  296.29  3922.9  299.41    4478  294.64  4538.3  292.62    4566  294.17
  4746.5  293.68  4796.7  291.91    4967  292.76  5002.4  287.89  5005.1  287.39
  5008.4  287.89  5018.1   292.2  5027.4   292.9  5063.3  295.16  5099.1  294.69
  5175.9  297.77  5332.8  300.03  5424.2  310.93  5457.5  313.53  5525.9  324.02
  5586.9  326.06  5607.2  331.95  5708.9  345.58    5780  351.31  5837.5   353.5
#Mann= 5 ,-1 , 0
  3310.5     .12       0  3377.4     .16       0  5002.4     .07       0
  5008.4     .16       0  5424.2     .16       0
#XS Ineff= 2 , 0
            4350  316.65
Permanent Ineff=
       F       F
Bank Sta=4967,5027.4
XS Rating Curve= 0 ,0
Exp/Cntr=0.3,0.1

Type RM Length L Ch R = 1 ,148796  ,607,607,607
BEGIN DESCRIPTION:
CATFISH CREEK 100.0
END DESCRIPTION:
XS GIS Cut Line= 3
      3693106.24     10722271.58      3691877.05     10723654.43
      3691139.21     10724231.68
#Sta/Elev= 30
  3293.7  326.34  3318.6  325.07  3368.4  315.65  3474.6  304.38  3580.8  294.41
  3615.9  294.02  3701.2   295.9  3707.9  294.03  3842.6  293.81  4317.5  297.48
  4430.4  296.18  4466.4  291.26  4572.6  292.38  4593.5  290.07  4636.1  290.98
  4671.3  297.03  4735.6  297.86  4791.7  296.03  4820.1  290.59  4983.2  292.19
  4994.4  287.51  4997.1  287.01  5000.4  287.51    5040  293.48  5239.2  297.69
  5794.4  302.99  5887.5  302.22  5958.1   304.6  6036.7  309.55  6080.7  317.17
#Mann= 5 ,-1 , 0
  3293.7     .12       0  3474.6     .16       0  4994.4     .07       0
  5000.4     .16       0  5958.1     .05       0
#XS Ineff= 2 , 0
         4734.09  310.54
Permanent Ineff=
       F       F
Bank Sta=4983.2,5040
XS Rating Curve= 0 ,0
Exp/Cntr=0.3,0.1

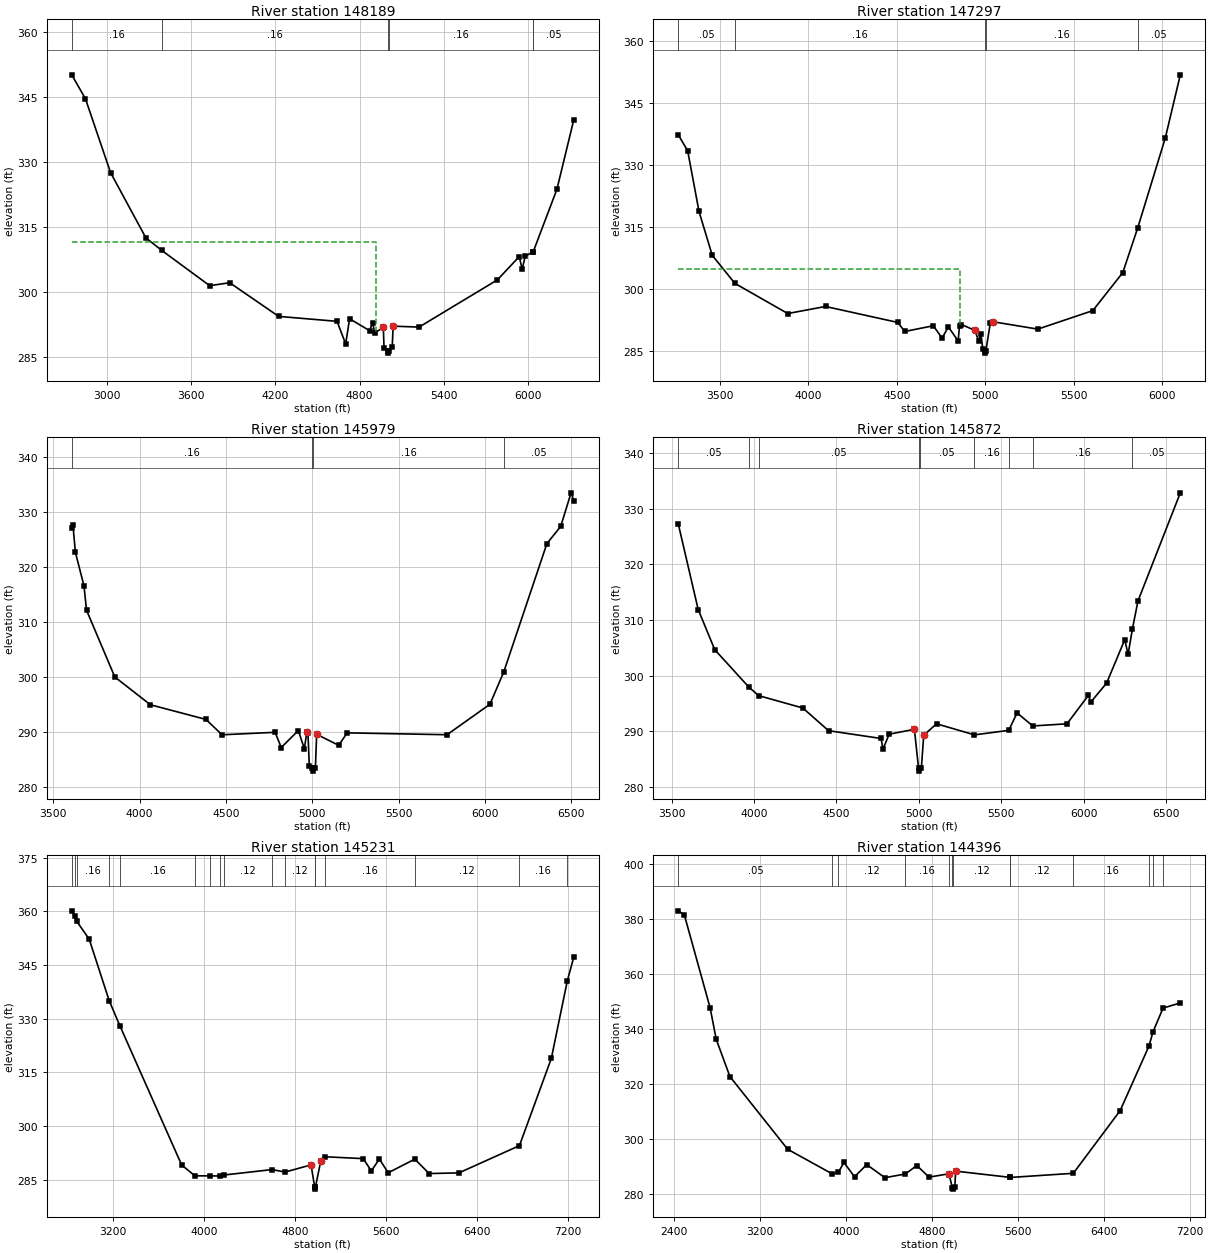
Type RM Length L Ch R = 1 ,148189  ,892,892,892
BEGIN DESCRIPTION:
CATFISH CREEK 99.0
END DESCRIPTION:
XS GIS Cut Line= 3
       3692649.6      10721210.2      3691649.61     10723210.19
      3690749.62     10724210.18
#Sta/Elev= 30
  2747.4  350.07  2845.2  344.52  3024.1  327.49  3275.7  312.44  3387.5  309.57
  3731.3  301.38  3873.8  302.07  4223.2  294.29  4639.7  293.15  4701.1  287.93
  4729.1  293.75  4871.6     291    4894  292.85    4908  290.43  4969.5  291.77
  4975.1  286.94  5001.8  286.31  5004.5  285.81  5007.8  286.31  5033.2  287.32
  5039.9  292.04  5224.5  291.82  5783.6  302.73    5939  308.09  5960.7  305.21
  5981.6  308.17  6038.4  309.21  6039.1  309.22  6208.1  323.65  6328.8  339.75
#Mann= 6 ,-1 , 0
  2747.4     .16       0  3387.5     .16       0  5001.8     .07       0
  5007.8     .16       0  6038.4     .12       0  6039.1     .05       0
#XS Ineff= 2 , 0
         4915.91  311.44
Permanent Ineff=
       F       F
Bank Sta=4969.5,5039.9
XS Rating Curve= 0 ,0
Exp/Cntr=0.3,0.1

Type RM Length L Ch R = 1 ,147297  ,1318,1318,1318
BEGIN DESCRIPTION:
CATFISH CREEK 98.0
END DESCRIPTION:
XS GIS Cut Line= 3
      3691749.62     10721210.16      3691149.61     10722810.19
      3690349.61     10723610.19
#Sta/Elev= 30
  3263.2  337.28  3316.6  333.41  3380.7  318.72  3455.5  308.12  3583.6  301.32
  3882.7  294.02  4096.3  295.73  4504.8  291.87  4544.8  289.68  4705.9  291.06
  4755.8   288.1  4791.4  290.78  4846.5  287.39  4854.6  291.04  4865.2  291.36
  4942.3  289.93  4962.2  287.38  4975.6  289.04  4986.2  285.37  4997.3  284.94
  5000.1  284.44  5003.3  284.94  5028.6  291.75  5042.7  292.04  5297.3  290.25
  5608.4  294.73  5778.1  303.94    5863  314.82  6018.5  336.52  6103.4  351.79
#Mann= 5 ,-1 , 0
  3263.2     .05       0  3583.6     .16       0  4997.3     .07       0
  5003.3     .16       0    5863     .05       0
#XS Ineff= 2 , 0
         4857.39  304.83
Permanent Ineff=
       F       F
Bank Sta=4942.3,5042.7
XS Rating Curve= 0 ,0
Exp/Cntr=0.3,0.1

Type RM Length L Ch R = 1 ,145979  ,107,107,107
BEGIN DESCRIPTION:
CATFISH CREEK 97.0
END DESCRIPTION:
XS GIS Cut Line= 6
      3691357.73     10721188.94      3690743.15     10721996.22
      3690456.69     10722142.06      3690045.23     10722610.81
      3689915.03     10722985.81      3689915.03     10723526.32
#Sta/Elev= 30
  3607.2   327.1  3613.7  327.72  3628.2   322.7  3678.1  316.57  3692.6  312.19
  3856.6  300.05  4062.7  295.01  4384.1  292.35  4477.9  289.56  4784.9  290.01
  4820.4  287.25  4919.5  290.33  4954.2  287.02  4968.6  290.03  4975.1  289.84
    4983  283.93  5000.8  283.46  5003.5  282.96  5006.8  283.46  5018.2  283.51
  5025.5  289.65  5153.1  287.65  5202.4  289.91  5780.5  289.57    6029   295.1
    6109  300.96    6359  324.28    6439   327.4    6499   333.5  6515.1   332.1
#Mann= 4 ,-1 , 0
  3607.2     .16       0  5000.8     .04       0  5006.8     .16       0
    6109     .05       0
Bank Sta=4968.6,5025.5
XS Rating Curve= 0 ,0
Exp/Cntr=0.3,0.1

Type RM Length L Ch R = 1 ,145872  ,641,641,641
BEGIN DESCRIPTION:
CATFISH CREEK 96.0
END DESCRIPTION:
XS GIS Cut Line= 6
      3691316.06     10721116.03      3690706.69     10721892.06
      3690378.57      10722105.6      3689847.32      10722668.1
      3689816.07     10722923.31      3689805.68     10723556.95
#Sta/Elev= 30
  3540.7  327.32  3661.6   311.9  3762.1  304.68  3969.4  297.93  4028.9  296.41
  4296.1  294.19  4452.4  290.11  4770.6  288.71  4782.5   286.8  4819.8  289.48
  4972.9  290.36  4998.2  283.34  5000.9  282.84  5004.2  283.34  5015.3  283.47
  5029.5  289.29  5107.1  291.35  5337.3  289.36    5545  290.17  5595.5  293.31
  5690.9  290.96  5898.3  291.35  6028.7  296.49  6042.2  295.23  6138.7  298.68
  6248.7  306.49  6268.7  303.82  6295.5  308.48  6328.7  313.43  6585.5  332.88
#Mann= 9 ,-1 , 0
  3540.7     .05       0  3969.4     .16       0  4028.9     .05       0
  4998.2     .04       0  5004.2     .05       0  5337.3     .16       0
    5545     .05       0  5690.9     .16       0  6295.5     .05       0
Bank Sta=4972.9,5029.5
XS Rating Curve= 0 ,0
Exp/Cntr=0.3,0.1

Type RM Length L Ch R = 1 ,145231  ,835,835,835
BEGIN DESCRIPTION:
CATFISH CREEK 95.0
END DESCRIPTION:
XS GIS Cut Line= 2
      3691484.46     10720228.01      3688373.99      10723364.5
#Sta/Elev= 30
  2837.1  360.14  2865.3  358.63  2880.3  357.23  2990.6  352.21  3166.9  334.99
  3260.9  327.99  3803.7  289.15  3920.5   286.1  4055.1   286.1  4138.5  286.05
  4175.1  286.33  4599.1  287.85  4713.8  287.16  4942.2  289.16  4974.6  282.89
  4977.3  282.39  4980.6  282.89    5027  290.14  5065.5  291.43  5401.8  290.91
  5472.6  287.47  5543.3  290.81    5621  286.96  5855.3  290.77  5981.6  286.74
  6243.3  286.93  6775.7  294.54  7056.5  318.93  7196.6  340.55  7254.4  347.27
#Mann= 17 ,-1 , 0
  2837.1     .16       0  2865.3     .12       0  2880.3     .16       0
  3166.9     .12       0  3260.9     .16       0  3920.5     .12       0
  4055.1     .07       0  4138.5     .05       0  4175.1     .12       0
  4599.1     .16       0  4713.8     .12       0  4974.6     .07       0
  4980.6     .12       0  5065.5     .16       0  5855.3     .12       0
  6775.7     .16       0  7196.6     .05       0
Bank Sta=4942.2,5027
XS Rating Curve= 0 ,0
Exp/Cntr=0.3,0.1

Type RM Length L Ch R = 1 ,144396  ,717,717,717
BEGIN DESCRIPTION:
CATFISH CREEK 94.0
END DESCRIPTION:
XS GIS Cut Line= 3
      3691349.59     10719460.21      3689549.61     10721260.19
       3687949.6      10722660.2
#Sta/Elev= 30
  2440.7     383  2497.2  381.55  2737.7  347.72  2794.2  336.33  2921.5  322.81
  3458.9  296.41  3875.7  287.42  3930.9  288.02  3982.2  291.61  4081.2  286.42
  4194.3  290.83    4364  286.09  4553.7  287.42    4661   290.5  4774.1  286.29
    4958  287.49  4963.7  286.96  4990.4  282.43  4993.1  281.93  4996.4  282.43
  5014.3   282.7  5021.9  288.47  5530.2  286.19  5530.6  286.17  6116.9  287.68
  6552.8  310.46  6820.6  333.88  6858.3  339.04  6951.3  347.68  7112.3  349.55
#Mann= 13 ,-1 , 0
  2440.7     .05       0  3875.7     .16       0  3930.9     .12       0
  4553.7     .16       0  4963.7     .12       0  4990.4     .07       0
  4996.4     .12       0  5530.2     .16       0  5530.6     .12       0
  6116.9     .16       0  6820.6     .05       0  6858.3     .16       0
  6951.3     .05       0
Bank Sta=4958,5021.9
XS Rating Curve= 0 ,0
Exp/Cntr=0.3,0.1

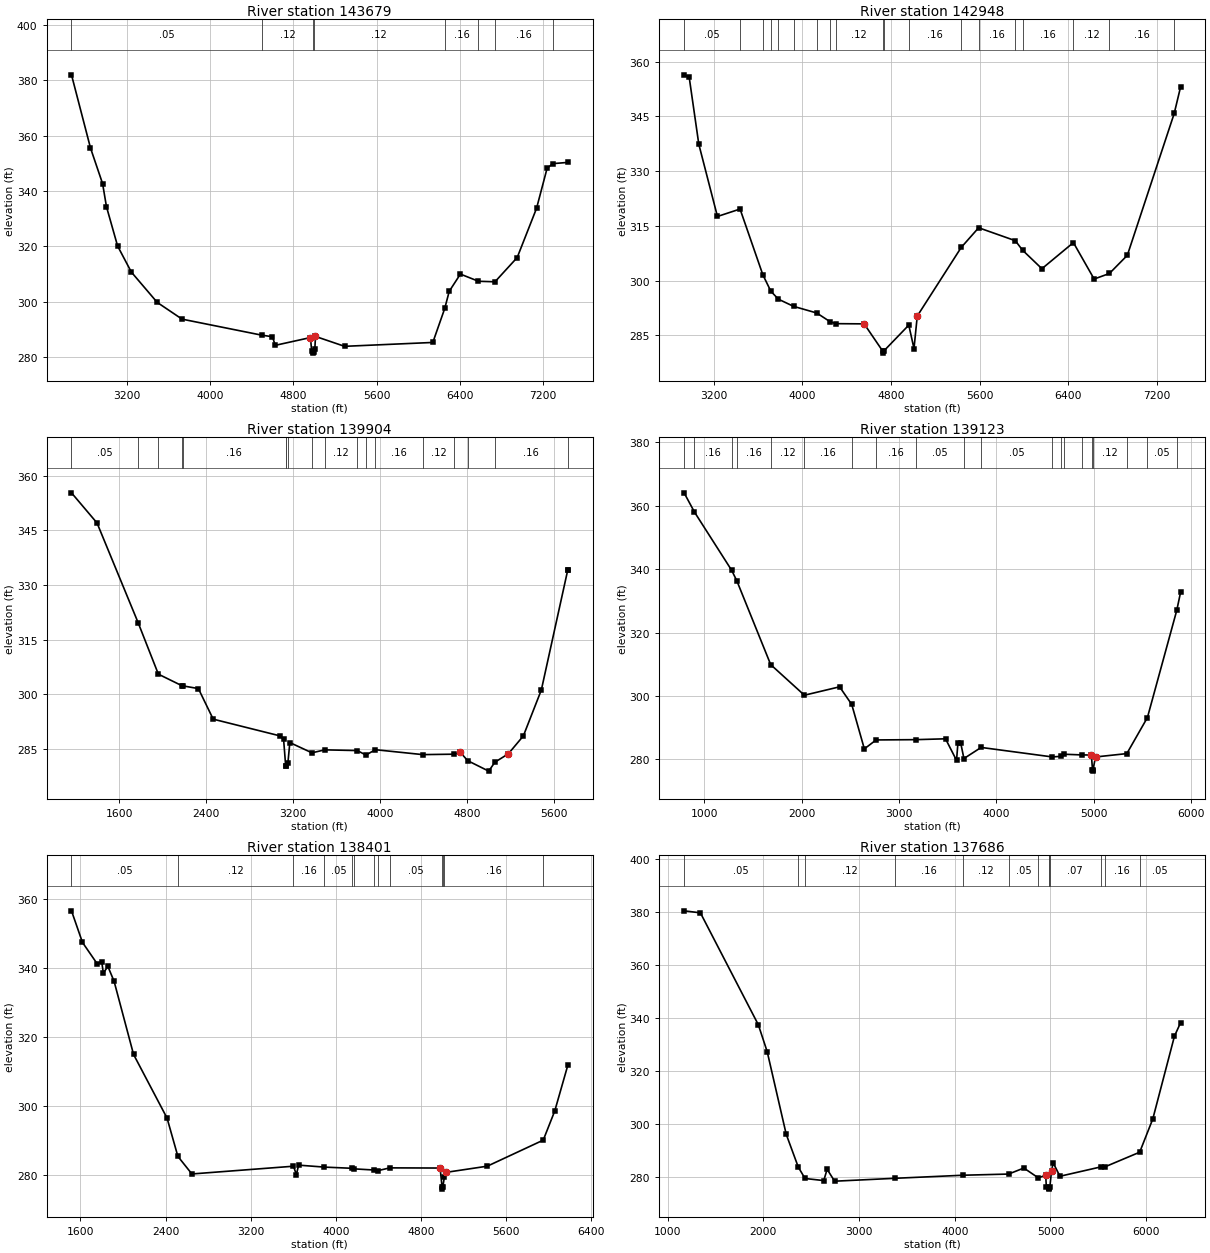
Type RM Length L Ch R = 1 ,143679  ,731,731,731
BEGIN DESCRIPTION:
CATFISH CREEK 93.0
END DESCRIPTION:
XS GIS Cut Line= 3
      3691299.58      10719460.2      3689299.61     10720660.19
      3687899.59     10722660.22
#Sta/Elev= 30
  2666.7  381.99  2849.4  355.53    2966   342.6  3002.9  334.31  3109.8   320.1
    3242  310.66  3490.8  299.69  3729.8  293.63  4496.7  287.83  4598.7  287.27
  4625.9  284.16  4964.1  286.97  4975.7  282.26  4988.3  281.84    4991  281.34
  4994.3  281.84  5006.5  282.88  5012.6  287.38  5292.4   283.8  6140.8   285.2
  6255.3  297.49  6298.6   303.7  6405.9  309.93  6579.4  307.33  6738.5  307.14
  6952.1  315.92  7138.2  333.72  7239.4  348.17  7293.9  349.87  7440.4  350.32
#Mann= 8 ,-1 , 0
  2666.7     .05       0  4496.7     .12       0  4988.3     .07       0
  4994.3     .12       0  6255.3     .16       0  6579.4     .12       0
  6738.5     .16       0  7293.9     .05       0
Bank Sta=4964.1,5012.6
XS Rating Curve= 0 ,0
Exp/Cntr=0.3,0.1

Type RM Length L Ch R = 1 ,142948  ,3044,3044,3044
BEGIN DESCRIPTION:
CATFISH CREEK 92.0
END DESCRIPTION:
XS GIS Cut Line= 5
      3689799.59     10718610.22      3688799.61     10720410.19
      3688599.61     10720910.19      3688383.66     10721821.09
      3687795.14     10722560.64
#Sta/Elev= 30
  2932.8  356.41  2978.5  355.82  3065.5  337.39  3233.6  317.58  3437.6  319.62
  3642.9  301.62  3715.2   297.1  3783.4  294.91  3920.6  292.94  4129.6  291.12
    4250  288.73  4300.1   288.2  4557.2  288.14  4725.8  280.62  4728.5  280.12
  4731.8  280.62  4959.8   287.8  5006.7  281.36  5036.3  290.29  5432.9   309.1
    5590  314.49  5920.8  310.94    5986  308.34  6160.7  303.26  6444.8  310.42
  6631.8  300.43  6769.4  301.95  6931.3  306.94  7354.2  345.83  7411.7  353.11
#Mann= 19 ,-1 , 0
  2932.8     .05       0  3437.6     .16       0  3642.9     .12       0
  3715.2     .16       0  3783.4     .12       0  3920.6     .16       0
  4129.6     .12       0    4250     .16       0  4300.1     .12       0
  4725.8     .07       0  4731.8     .12       0  4959.8     .16       0
  5432.9     .12       0    5590     .16       0  5920.8     .12       0
    5986     .16       0  6444.8     .12       0  6769.4     .16       0
  7354.2     .05       0
Bank Sta=4557.2,5036.3
XS Rating Curve= 0 ,0
Exp/Cntr=0.3,0.1

Type RM Length L Ch R = 1 ,139904  ,781,781,781
BEGIN DESCRIPTION:
CATFISH CREEK 91.0
END DESCRIPTION:
XS GIS Cut Line= 3
      3689849.65     10718460.16      3686849.61     10720860.19
      3686449.63     10721460.16
#Sta/Elev= 30
  1162.7  355.25  1397.3  346.98    1776  319.55  1961.1  305.49  2180.4  302.28
  2187.9  302.27  2328.9  301.53    2465  293.14  3076.5  288.57  3111.7  287.72
  3131.1  280.34  3137.1  280.34    3152  281.24  3169.3  286.72  3372.6   283.9
    3490  284.72  3789.3  284.52  3868.8  283.29    3955  284.76  4391.3  283.41
  4677.9  283.53  4734.9   284.1  4803.2  281.76 4997.18  278.88  5053.9  281.33
  5177.4  283.63  5315.6  288.55  5480.9  301.16  5722.7  333.97  5725.7  333.97
#Mann= 18 ,-1 , 0
  1162.7     .05       0    1776     .12       0  1961.1     .16       0
  2180.4     .12       0  2187.9     .16       0  3131.1     .07       0
  3137.1     .16       0    3152     .12       0  3372.6     .16       0
    3490     .12       0  3789.3     .16       0  3868.8     .12       0
    3955     .16       0  4391.3     .12       0  4677.9     .16       0
  4803.2     .12       0  5053.9     .16       0  5722.7     .05       0
Bank Sta=4734.9,5177.4
XS Rating Curve= 0 ,0
Exp/Cntr=0.3,0.1

Type RM Length L Ch R = 1 ,139123  ,722,722,722
BEGIN DESCRIPTION:
CATFISH CREEK 90.0
END DESCRIPTION:
XS GIS Cut Line= 3
       3689599.6      10717360.2      3686599.61     10720360.19
      3686099.59     10721060.22
#Sta/Elev= 30
     791  364.12   897.6  358.05  1280.8  339.63  1334.4  336.26  1681.2  309.91
  2027.5  300.26  2389.1  302.91    2514  297.35  2643.6  283.33  2764.6  286.15
  3171.9  286.24    3478  286.51  3591.1   279.7  3605.3  285.16  3633.6  285.23
  3667.2  280.28  3843.9  283.79    4575  280.79  4661.9  280.97  4694.8  281.64
  4884.4  281.42  4977.1   281.4  4988.2  276.81    4991  276.31  4994.2  276.81
  5019.5  280.78  5341.3  281.84    5553  293.22  5854.4  327.02  5893.9  332.76
#Mann= 20 ,-1 , 0
     791     .05       0   897.6     .16       0  1280.8     .12       0
  1334.4     .16       0  1681.2     .12       0  2027.5     .16       0
    2514     .12       0  2764.6     .16       0  3171.9     .05       0
  3667.2     .16       0  3843.9     .05       0    4575     .16       0
  4661.9     .12       0  4694.8     .16       0  4884.4     .12       0
  4988.2     .07       0  4994.2     .12       0  5341.3     .16       0
    5553     .05       0  5854.4     .16       0
Bank Sta=4977.1,5019.5
XS Rating Curve= 0 ,0
Exp/Cntr=0.3,0.1

Type RM Length L Ch R = 1 ,138401  ,715,715,715
BEGIN DESCRIPTION:
CATFISH CREEK 89.0
END DESCRIPTION:
XS GIS Cut Line= 3
      3688249.58     10716710.23      3686449.61     10719710.19
      3685849.62     10720710.18
#Sta/Elev= 30
    1516  356.54    1619  347.38    1757  341.19  1799.7  341.79  1815.3  338.48
    1858   340.4  1916.3  336.08    2099  314.87  2413.9  296.38  2515.4  285.28
  2647.2  280.17  3601.8  282.42  3628.7  279.99  3650.1  282.73    3893  282.16
  4155.9  281.81  4171.4  281.65  4361.6  281.31  4394.8  281.13  4506.5  281.94
  4979.5  281.89  4997.9  276.27  5000.7  275.77  5003.9  276.27  5019.3  279.23
  5037.8  280.65  5422.7  282.43  5948.2  289.99  6056.3  298.45  6180.7   311.9
#Mann= 13 ,-1 , 0
    1516     .05       0  2515.4     .12       0  3601.8     .16       0
    3893     .05       0  4155.9      .1       0  4171.4     .16       0
  4361.6     .05       0  4394.8     .16       0  4506.5     .05       0
  4997.9     .03       0  5003.9     .05       0  5019.3     .16       0
  5948.2     .05       0
Bank Sta=4979.5,5037.8
XS Rating Curve= 0 ,0
Exp/Cntr=0.3,0.1

Type RM Length L Ch R = 1 ,137686  ,713,713,713
BEGIN DESCRIPTION:
CATFISH CREEK 88.0
END DESCRIPTION:
XS GIS Cut Line= 3
      3688299.59     10716260.22      3685899.61     10719260.19
      3684899.61     10720160.19
#Sta/Elev= 30
  1172.2  380.38  1342.6  379.62  1947.7  337.44  2040.6  327.26  2239.1  296.14
  2365.4  283.75  2435.8  279.47  2631.3  278.68  2666.5  282.93  2744.9  278.45
    3380  279.55  4086.9   280.7  4562.1  281.14  4721.9  283.41  4871.1  279.75
    4950  280.61  4957.2  276.13    4983  275.96  4985.8  275.46    4989  275.96
  4992.9   276.1  5010.8  282.25  5027.9  285.39  5098.9  280.31    5524  283.82
  5569.7  283.87    5932  289.38    6069  301.92  6295.5  333.15  6359.4  338.21
#Mann= 13 ,-1 , 0
  1172.2     .05       0  2365.4     .16       0  2435.8     .12       0
    3380     .16       0  4086.9     .12       0  4562.1     .05       0
  4871.1     .16       0    4983     .07       0    4989     .16       0
  4992.9     .07       0    5524     .12       0  5569.7     .16       0
    5932     .05       0
Bank Sta=4950,5010.8
XS Rating Curve= 0 ,0
Exp/Cntr=0.3,0.1

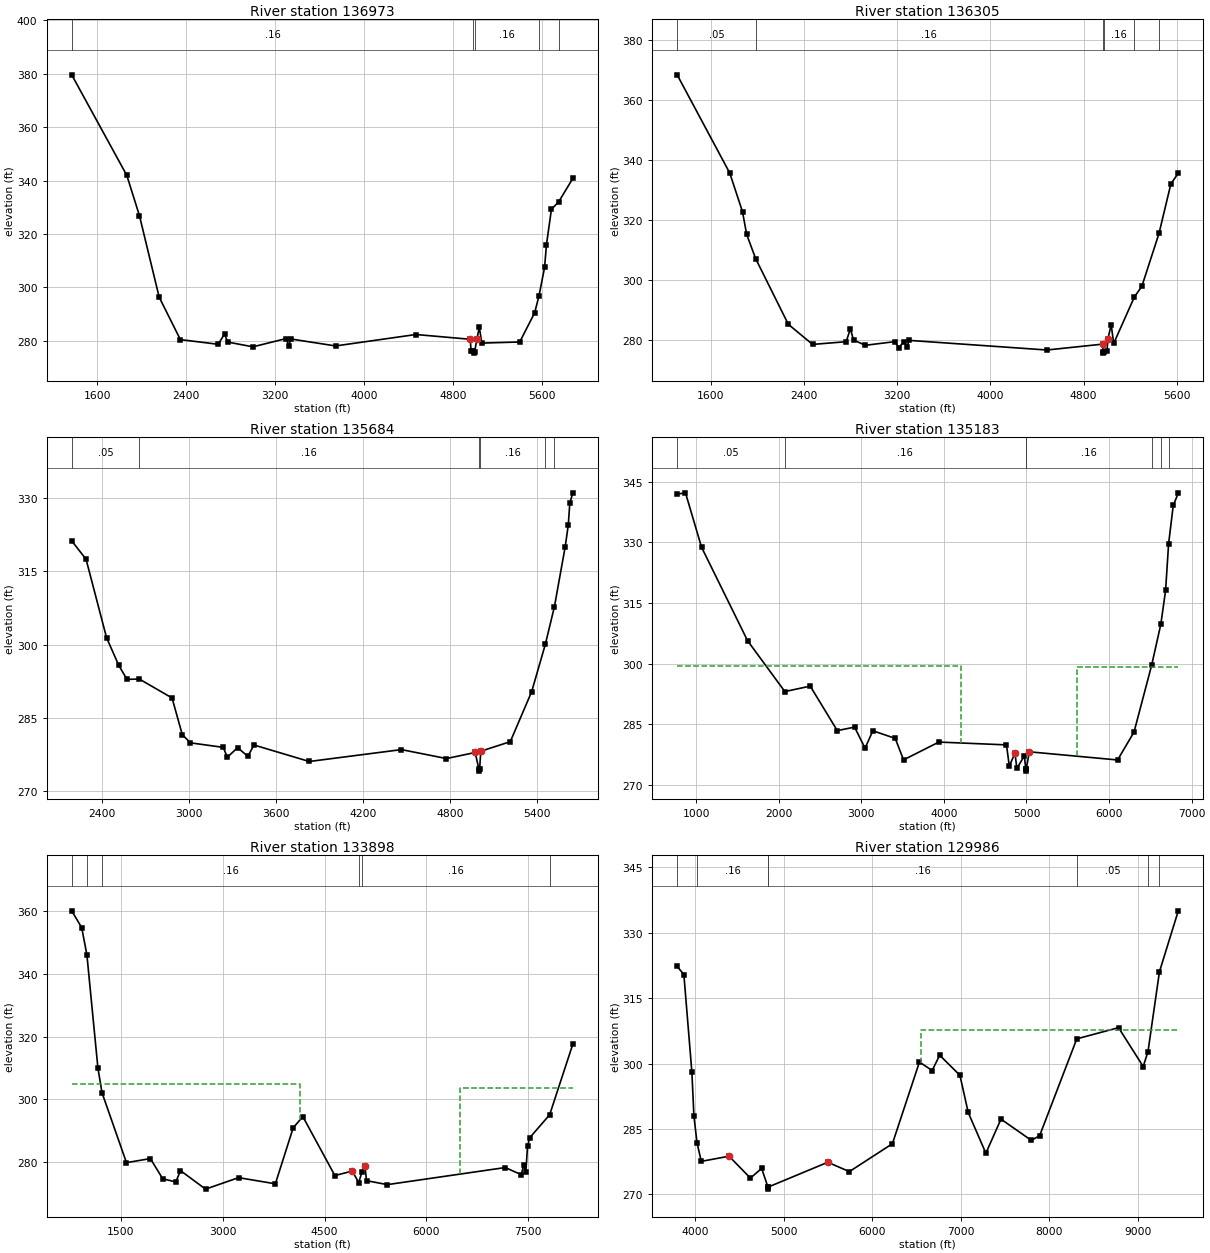
Type RM Length L Ch R = 1 ,136973  ,668,668,668
BEGIN DESCRIPTION:
CATFISH CREEK 87.0
END DESCRIPTION:
XS GIS Cut Line= 3
       3688099.6      10716360.2      3685399.61     10718760.19
       3684599.6     10719160.19
#Sta/Elev= 30
  1371.9  379.61  1867.3  341.97  1981.1  326.86  2158.3  296.38    2349  280.48
  2689.3  278.73  2746.2  282.61  2774.6  279.56  3001.3  277.78  3298.5  280.85
  3326.5  278.25  3340.8  280.73  3744.7  278.11  4467.2  282.39  4956.3   280.6
    4963  276.21  4984.4  276.07  4992.5  275.42  4995.7  275.92  5015.1  280.55
  5037.5  285.11  5059.8  279.18  5400.8  279.59    5535   290.5  5574.1  296.86
  5624.4   307.5  5641.2  315.98  5685.9  329.23  5751.5  332.09  5878.8  340.85
#Mann= 5 ,-1 , 0
  1371.9     .16       0  4984.4     .07       0  4995.7     .16       0
  5574.1     .05       0  5751.5     .16       0
Bank Sta=4956.3,5015.1
XS Rating Curve= 0 ,0
Exp/Cntr=0.3,0.1

Type RM Length L Ch R = 1 ,136305  ,621,621,621
BEGIN DESCRIPTION:
CATFISH CREEK 86.0
END DESCRIPTION:
XS GIS Cut Line= 3
      3687899.61     10716210.18      3684899.61     10718310.19
       3684499.6      10718810.2
#Sta/Elev= 30
  1310.6  368.45  1762.2  335.73  1871.7  322.82  1907.4  315.27    1985  307.18
  2264.9  285.35  2473.3  278.65  2761.9  279.56  2797.6  283.88  2824.7  280.12
  2925.8  278.36  3178.2  279.57  3214.4  277.62  3256.2  279.51  3285.9  277.73
  3300.3     280  4484.3  276.79  4965.2  278.75  4966.5  276.25  4969.3  275.75
  4972.5  276.25  5000.6  276.45  5008.6  280.39  5036.6  285.25  5058.2  278.97
  5235.9  294.47  5299.9     298  5447.1   315.6  5548.9  332.09  5612.9  335.72
#Mann= 6 ,-1 , 0
  1310.6     .05       0    1985     .16       0  4966.5     .07       0
  4972.5     .16       0  5235.9     .05       0  5447.1     .16       0
Bank Sta=4965.2,5008.6
XS Rating Curve= 0 ,0
Exp/Cntr=0.3,0.1

Type RM Length L Ch R = 1 ,135684  ,501,501,501
BEGIN DESCRIPTION:
CATFISH CREEK 85.0
END DESCRIPTION:
XS GIS Cut Line= 3
      3686299.59     10716110.21      3684299.61     10718110.19
      3684499.62     10718710.24
#Sta/Elev= 30
    2189  321.22    2288  317.46  2429.4  301.44  2514.2  295.74  2570.8   292.9
  2655.7  292.97  2881.9   289.1  2952.6  281.59  3009.2  279.92  3235.5     279
  3263.8  276.97  3334.5  278.95  3405.2  277.17  3447.6  279.48  3829.5  276.11
  4465.9  278.54    4777  276.71    4975  277.95  5000.3  274.64    5003  274.14
  5006.3  274.64  5013.9  278.21  5217.7  280.16  5365.2  290.37  5460.1   300.1
  5522.7  307.79  5597.1  320.03  5618.2  324.45  5628.8  328.96  5649.9  331.04
#Mann= 6 ,-1 , 0
    2189     .05       0  2655.7     .16       0  5000.3     .07       0
  5006.3     .16       0  5460.1     .05       0  5522.7     .16       0
Bank Sta=4975,5013.9
XS Rating Curve= 0 ,0
Exp/Cntr=0.3,0.1

Type RM Length L Ch R = 1 ,135183  ,1285,1285,1285
BEGIN DESCRIPTION:
CATFISH CREEK 84.0
END DESCRIPTION:
XS GIS Cut Line= 4
      3686720.23     10715068.61      3684050.93     10717034.78
      3683790.51     10718180.61      3684324.38     10719665.02
#Sta/Elev= 30
   770.7  341.96   871.6  342.28  1065.9  328.83  1623.5  305.69  2074.7  293.12
  2381.7  294.47  2709.6  283.46  2918.6  284.33  3045.9  279.11  3139.9  283.43
  3411.5  281.53  3511.7  276.22  3939.8  280.63  4758.1  279.93  4792.6  274.67
  4860.6   277.9  4883.9  274.14  4975.2  277.22  4990.9  273.94  4993.7  273.44
  4996.9  273.94    5035  278.22  6102.9   276.2    6302  283.08    6517  299.73
  6627.1   309.8  6684.6  318.12    6721  329.65  6777.5   339.2  6838.5   342.2
#Mann= 7 ,-1 , 0
   770.7     .05       0  2074.7     .16       0  4990.9     .03       0
  4996.9     .16       0    6517     .05       0  6627.1     .16       0
    6721     .05       0
#XS Ineff= 2 , 0
         4211.93  299.44 5615.91          299.14
Permanent Ineff=
       F       F
Bank Sta=4860.6,5035
XS Rating Curve= 0 ,0
Exp/Cntr=0.3,0.1

Type RM Length L Ch R = 1 ,133898  ,3912,3912,3912
BEGIN DESCRIPTION:
CATFISH CREEK 83.0
END DESCRIPTION:
XS GIS Cut Line= 3
      3684949.36     10713216.43       3682883.4     10717591.42
      3683751.08     10719986.22
#Sta/Elev= 30
     774  359.95     921  354.61   997.6  345.98  1159.8  310.03  1220.5  302.14
  1580.7  279.92  1933.2  281.22  2115.4  274.77  2308.6  273.81  2376.9  277.39
  2746.4  271.51  3233.2  275.16  3775.1   273.2  4037.7  290.99  4179.8  294.57
  4651.8  275.82  4907.8  277.25  5004.4  273.57  5049.9  276.96  5095.4  278.84
  5118.2   274.2  5425.2  272.94  7163.8  278.37  7397.8  276.11  7435.5  279.18
  7466.1  276.81  7491.4   285.1    7522   287.8  7817.7  295.15  8159.4  317.63
#Mann= 6 ,-1 , 0
     774     .05       0   997.6     .12       0  1220.5     .16       0
  5004.4     .07       0  5049.9     .16       0  7817.7     .05       0
#XS Ineff= 2 , 0
         4136.93  305.06 6499.43           303.8
Permanent Ineff=
       F       F
Bank Sta=4907.8,5095.4
XS Rating Curve= 0 ,0
Exp/Cntr=0.3,0.1

Type RM Length L Ch R = 1 ,129986  ,3688,3688,3688
BEGIN DESCRIPTION:
CATFISH CREEK 82.0
END DESCRIPTION:
XS GIS Cut Line= 3
      3683726.27      10712904.8      3683140.34     10714128.75
      3679729.36     10716745.56
#Sta/Elev= 30
  3797.9  322.28  3873.6  320.43  3964.3  297.94  3986.9  287.94  4022.3  281.77
    4070  277.53  4383.3  278.72  4624.3   273.7  4751.5  275.91  4822.1  271.66
  4824.8  271.16  4828.1  271.66  5498.2  277.33  5741.2  275.18  6227.1  281.58
  6532.5  300.34  6675.7  298.39  6760.9   301.9  6989.4  297.29  7082.8  288.76
  7282.2   279.4  7452.5  287.23  7795.2  282.36  7888.6  283.41  8308.2  305.66
  8779.6  308.23  9057.9   299.3    9112  302.75  9241.3  321.07    9454  335.05
#Mann= 7 ,-1 , 0
  3797.9     .16       0  4022.3     .16       0  4822.1     .07       0
  4828.1     .16       0  8308.2     .05       0    9112     .16       0
  9241.3     .05       0
#XS Ineff= 2 , 0
                          6551.7          307.58
Permanent Ineff=
       F       F
Bank Sta=4383.3,5498.2
XS Rating Curve= 0 ,0
Exp/Cntr=0.3,0.1