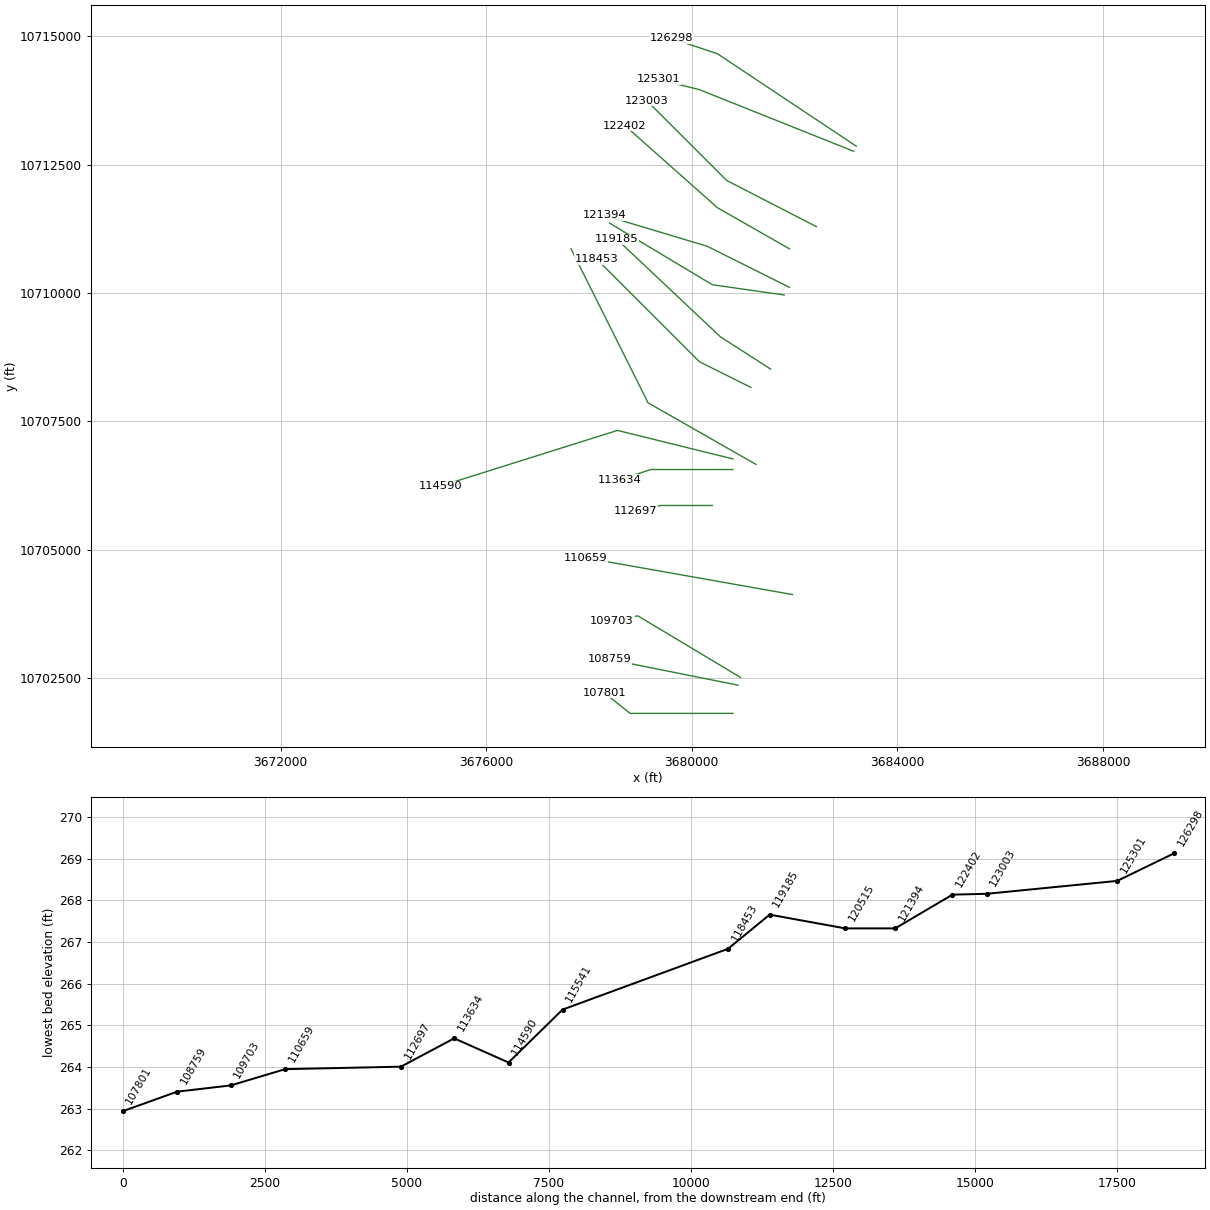
HEC-RAS study CATFISH CREEK.prj: CATFISH CREEK Base Level Engineering

--- CATFISH CREEK.g01 (geometry) --- (continued)

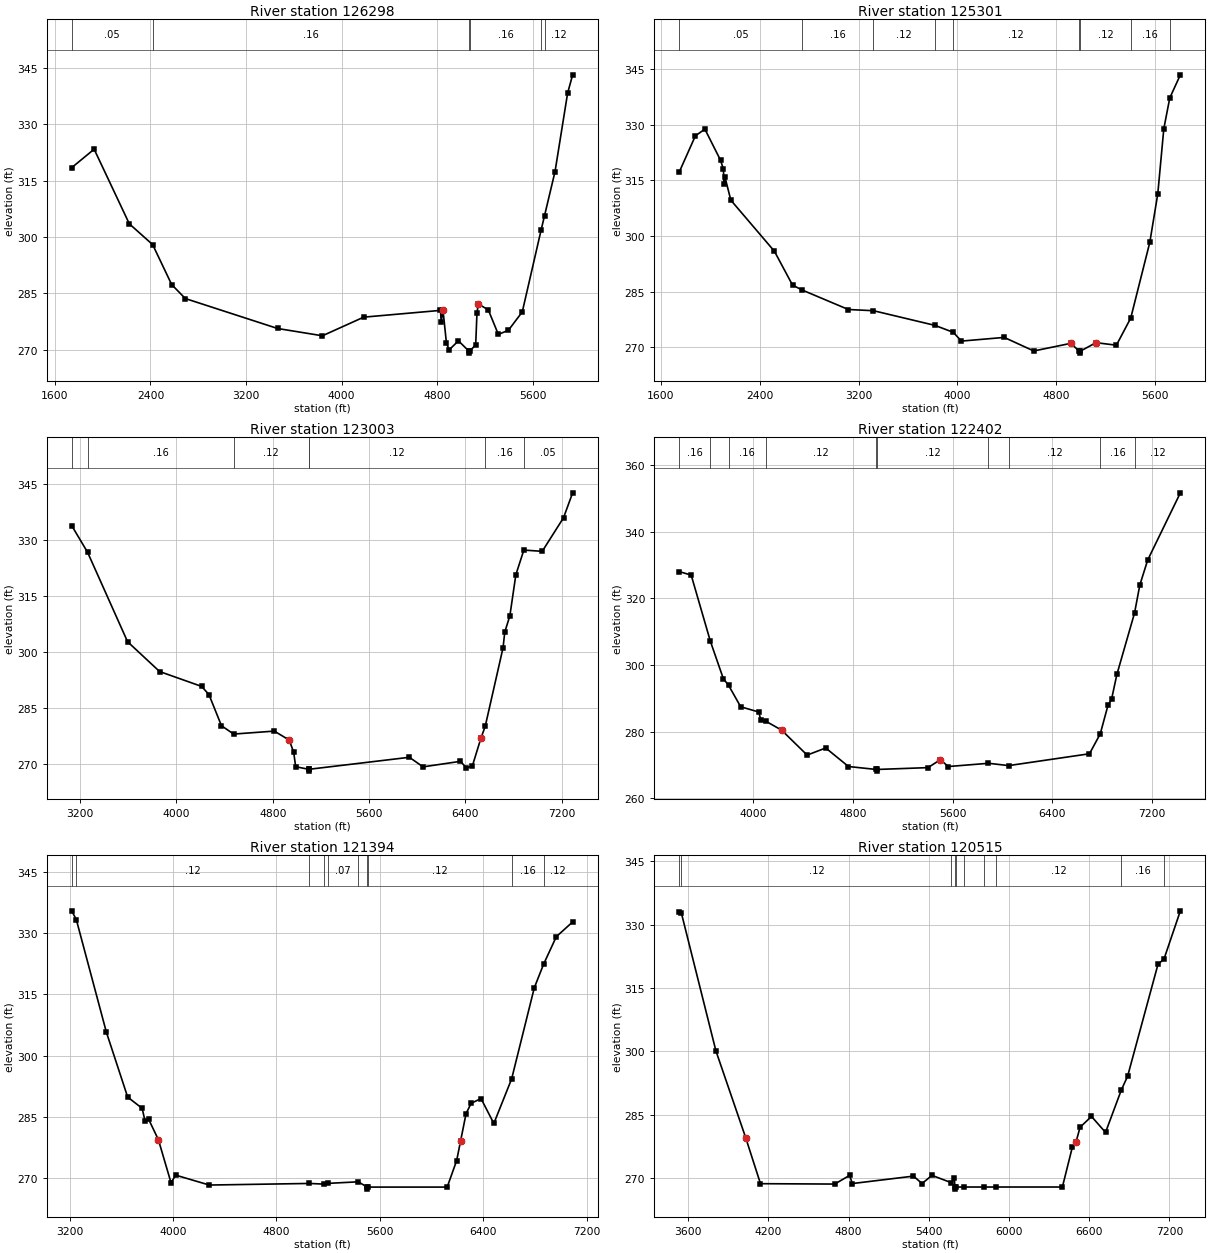
Type RM Length L Ch R = 1 ,126298  ,997,997,997
BEGIN DESCRIPTION:
CATFISH CREEK 80.0
END DESCRIPTION:
XS GIS Cut Line= 3
      3683199.65     10712860.16      3680499.61     10714660.19
      3679599.63     10714960.18
#Sta/Elev= 30
  1740.8  318.43  1928.6  323.33  2223.1   303.5  2418.4  297.97  2577.6  287.36
  2691.8  283.64    3464  275.68  3839.6  273.74  4185.1  278.69  4828.1  280.49
  4834.1  277.51  4849.1  280.53  4877.7  271.91  4900.2  269.98  4978.3   272.4
  5067.2  269.63  5069.9  269.13  5073.2  269.63  5122.9  271.37  5133.4   279.7
    5144  282.21  5228.3  280.63  5312.6   274.1  5396.9  275.21  5512.9  280.09
    5671  301.91  5699.5   305.7    5787  317.37  5892.4  338.23  5934.5   343.1
#Mann= 6 ,-1 , 0
  1740.8     .05       0  2418.4     .16       0  5067.2     .07       0
  5073.2     .16       0    5671     .16       0  5699.5     .12       0
Bank Sta=4849.1,5144
XS Rating Curve= 0 ,0
Exp/Cntr=0.3,0.1

Type RM Length L Ch R = 1 ,125301  ,2298,2298,2298
BEGIN DESCRIPTION:
CATFISH CREEK 79.0
END DESCRIPTION:
XS GIS Cut Line= 3
      3683149.58      10712760.2      3680149.61     10713960.19
       3679349.6     10714160.19
#Sta/Elev= 30
  1749.8  317.34    1879  326.97  1955.7  328.77  2082.3  320.41  2105.2  318.06
  2111.9  314.08  2117.3  315.99  2165.8  309.65  2518.5   295.9  2665.2   286.8
  2738.2  285.53  3117.6  280.21  3320.7  279.89  3818.4  275.94  3966.3  274.08
  4033.1  271.71  4379.1   272.7  4618.7  269.05  4917.6   271.1  4988.2  268.97
  4990.9  268.47  4994.2  268.97  5122.6  271.29  5287.5   270.6  5403.7  277.91
  5558.1  298.31  5622.5  311.33  5671.5  328.89  5719.7  337.17  5805.5  343.39
#Mann= 9 ,-1 , 0
  1749.8     .05       0  2738.2     .16       0  3320.7     .12       0
  3818.4     .16       0  3966.3     .12       0  4988.2     .07       0
  4994.2     .12       0  5403.7     .16       0  5719.7     .05       0
Bank Sta=4917.6,5122.6
XS Rating Curve= 0 ,0
Exp/Cntr=0.3,0.1

Type RM Length L Ch R = 1 ,123003  ,601,601,601
BEGIN DESCRIPTION:
CATFISH CREEK 78.0
END DESCRIPTION:
XS GIS Cut Line= 3
      3682424.96     10711291.63      3680677.96     10712192.26
      3679126.27     10713743.94
#Sta/Elev= 30
  3130.6   333.8  3262.4  326.67  3594.5  302.76  3860.4  294.79  4209.4  290.81
  4270.2  288.63  4374.2   280.3  4475.5  278.07    4813  278.86  4936.7  276.47
  4973.8  273.24  4990.4  269.34  5097.5  268.66  5100.3  268.16  5103.5  268.66
  5934.9  271.86  6048.1   269.3  6359.2  270.78  6408.7  268.99  6458.2  269.58
  6528.9  276.98  6564.4  280.12  6712.7  301.16  6726.9  305.35  6769.3   309.7
  6818.8  320.65  6885.2  327.26    7038  326.93  7214.8  335.91  7290.5  342.57
#Mann= 7 ,-1 , 0
  3130.6     .05       0  3262.4     .16       0  4475.5     .12       0
  5097.5     .07       0  5103.5     .12       0  6564.4     .16       0
  6885.2     .05       0
Bank Sta=4936.7,6528.9
XS Rating Curve= 0 ,0
Exp/Cntr=0.3,0.1

Type RM Length L Ch R = 1 ,122402  ,1008,1008,1008
BEGIN DESCRIPTION:
CATFISH CREEK 77.0
END DESCRIPTION:
XS GIS Cut Line= 3
      3681899.61     10710860.19      3680499.61     10711660.19
      3678699.59     10713260.21
#Sta/Elev= 30
  3407.2  328.01  3501.5  326.96  3655.2  307.14  3759.2  295.92  3802.2  293.85
  3898.9  287.45  4044.3  285.88  4060.1  283.44  4102.2  283.08  4227.1  280.45
  4432.3  272.95  4581.3  275.09  4764.1  269.52  4987.1  268.64  4989.9  268.14
  4993.1  268.64  5402.2  269.19  5501.3  271.56  5565.3  269.52  5887.8  270.49
    6050   269.8  6698.4  273.35  6784.9  279.32  6847.2  287.93  6875.6   289.7
  6918.3  297.14  7060.4  315.63  7102.3  323.96  7165.8   331.5    7428  351.66
#Mann= 10 ,-1 , 0
  3407.2     .16       0  3655.2     .12       0  3802.2     .16       0
  4102.2     .12       0  4987.1     .07       0  4993.1     .12       0
  5887.8     .07       0    6050     .12       0  6784.9     .16       0
  7060.4     .12       0
Bank Sta=4227.1,5501.3
XS Rating Curve= 0 ,0
Exp/Cntr=0.3,0.1

Type RM Length L Ch R = 1 ,121394  ,879,879,879
BEGIN DESCRIPTION:
CATFISH CREEK 76.0
END DESCRIPTION:
XS GIS Cut Line= 3
      3681899.61     10710110.19      3680299.61     10710910.19
      3678299.63     10711510.18
#Sta/Elev= 30
  3215.8  335.44  3251.5  333.28  3484.1  305.73    3649  289.85  3760.8  287.11
  3783.2  284.01  3811.2  284.42  3886.6  279.43  3984.4  268.89  4020.8  270.75
  4280.7  268.33  5055.5  268.72  5166.7  268.56    5199  268.74  5434.1  269.12
  5501.9  267.83  5504.7  267.33  5507.9  267.83  6121.8  267.83  6194.9   274.3
  6226.2  279.22  6267.9  285.82  6307.1  288.33  6383.6   289.5  6482.8   283.4
  6620.7  294.32    6796  316.61  6868.4  322.41  6966.6  329.12  7092.7  332.72
#Mann= 10 ,-1 , 0
  3215.8     .16       0  3251.5     .12       0  5055.5     .07       0
  5166.7     .12       0    5199     .07       0  5434.1     .12       0
  5501.9     .07       0  5507.9     .12       0  6620.7     .16       0
  6868.4     .12       0
Bank Sta=3886.6,6226.2
XS Rating Curve= 0 ,0
Exp/Cntr=0.3,0.1

Type RM Length L Ch R = 1 ,120515  ,1330,1330,1330
BEGIN DESCRIPTION:
CATFISH CREEK 75.0
END DESCRIPTION:
XS GIS Cut Line= 3
      3681799.63     10709960.19      3680399.61     10710160.19
      3678399.62     10711360.18
#Sta/Elev= 30
  3535.2  333.02    3550   332.7    3808  300.08  4030.2  279.56  4141.3  268.62
  4696.9  268.53    4808  270.59  4828.2  268.65  5285.7  270.41  5349.8  268.65
  5423.7  270.59  5568.9  268.85  5590.8  269.98  5595.6  267.83  5598.4  267.33
  5601.6  267.83  5660.1  267.83  5812.4  267.83  5903.5  267.83  6399.4  267.83
  6473.3  277.21  6500.5  278.39  6531.6     282  6617.1  284.55    6722  280.77
  6840.4  290.84  6887.2  294.08  7114.7  320.63    7159  321.82  7281.8  333.27
#Mann= 10 ,-1 , 0
  3535.2     .16       0    3550     .12       0  5568.9     .07       0
  5595.6     .07       0  5601.6     .07       0  5660.1     .12       0
  5812.4     .07       0  5903.5     .12       0  6840.4     .16       0
    7159     .12       0
Bank Sta=4030.2,6500.5
XS Rating Curve= 0 ,0
Exp/Cntr=0.3,0.1

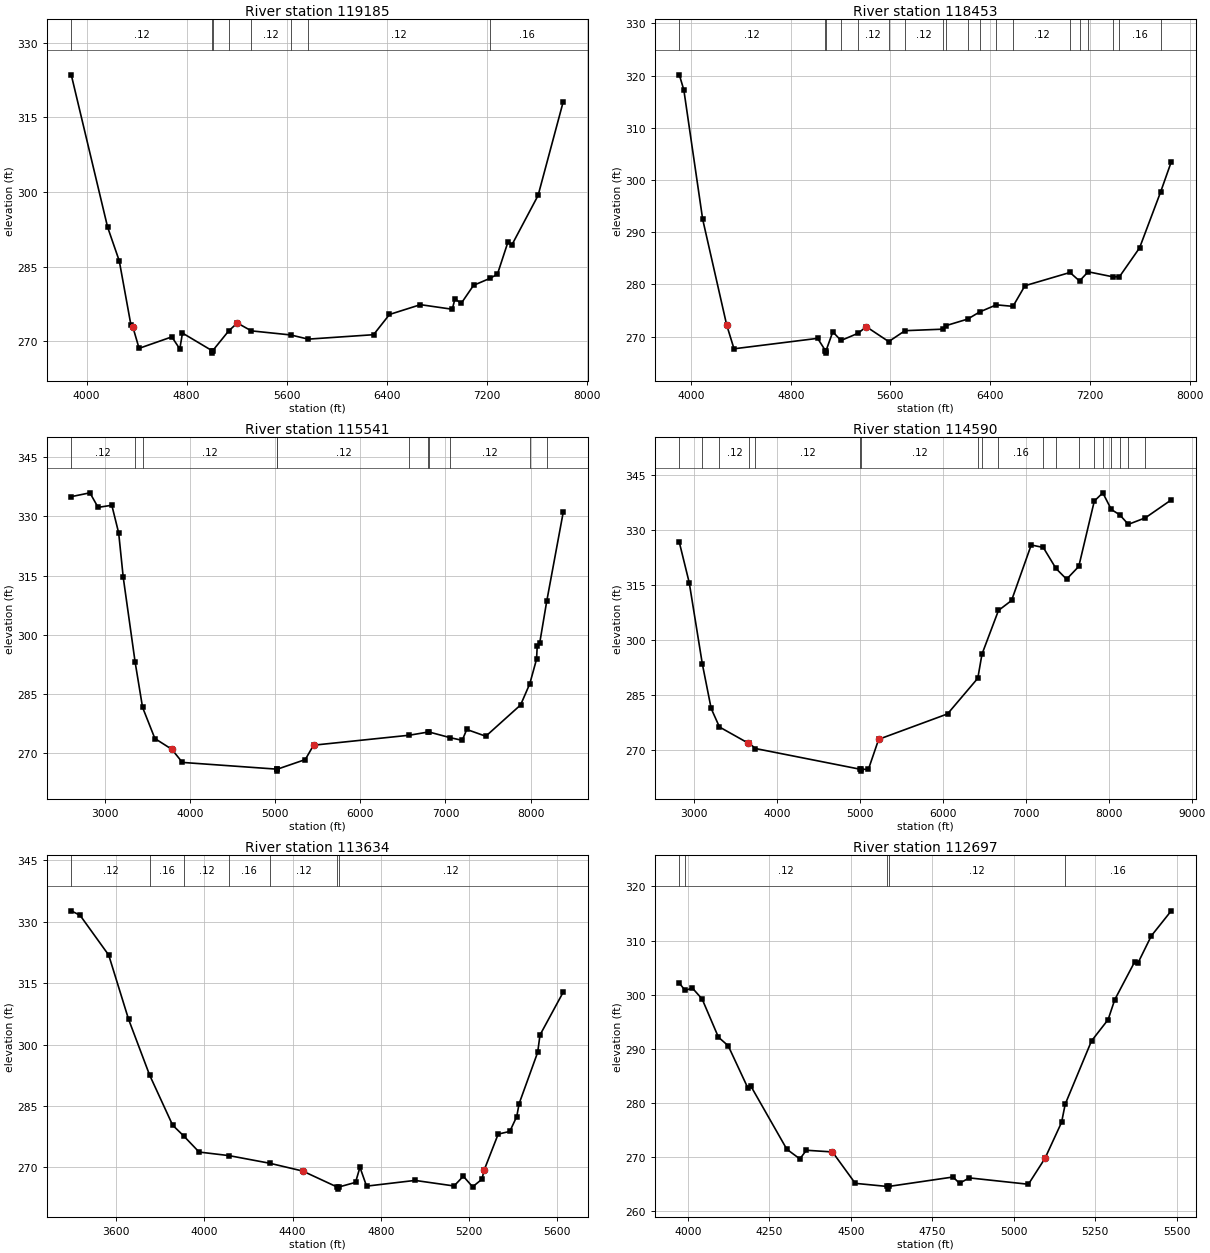
Type RM Length L Ch R = 1 ,119185  ,732,732,732
BEGIN DESCRIPTION:
CATFISH CREEK 74.0
END DESCRIPTION:
XS GIS Cut Line= 3
      3681535.66     10708516.23      3680556.49     10709146.44
      3678542.05     10711046.37
#Sta/Elev= 30
  3878.1  323.54  4168.3  292.99    4262  286.17  4355.8  273.22    4371  272.87
  4420.4  268.62  4682.1  270.92    4746   268.5  4767.2  271.69  5003.2  268.16
  5005.9  267.66  5009.2  268.16  5136.2   272.1  5205.6  273.71    5318  272.13
  5632.6  271.31  5772.6  270.47  6295.1  271.36  6422.5  275.42  6670.1  277.39
  6924.6  276.47    6946  278.58  6995.4  277.63  7094.5  281.27  7223.6  282.65
  7285.5   283.5  7370.4  290.02  7398.8  289.28  7610.7  299.32  7811.6  318.13
#Mann= 8 ,-1 , 0
  3878.1     .12       0  5003.2     .07       0  5009.2     .12       0
  5136.2     .16       0    5318     .12       0  5632.6     .16       0
  5772.6     .12       0  7223.6     .16       0
Bank Sta=4371,5205.6
XS Rating Curve= 0 ,0
Exp/Cntr=0.3,0.1

Type RM Length L Ch R = 1 ,118453  ,2912,2912,2912
BEGIN DESCRIPTION:
CATFISH CREEK 73.0
END DESCRIPTION:
XS GIS Cut Line= 3
       3681149.6     10708160.19      3680149.61     10708660.19
      3678149.64     10710660.16
#Sta/Elev= 30
  3906.4  320.15  3942.7  317.26  4093.7  292.49  4286.5  272.22  4345.2  267.67
    5016  269.67    5078  267.34  5080.7  266.84    5084  267.34  5137.6  270.92
  5203.3  269.26    5340  270.64  5406.3   271.9  5586.2  269.05  5716.8  271.14
    6021  271.43  6049.1  272.13  6219.4  273.36  6316.1  274.73  6449.5  276.09
    6583   275.8    6679  279.75  7040.3  282.29  7116.8  280.66  7185.9  282.42
  7383.8  281.46    7437  281.47  7598.3  286.99  7768.3  297.77  7852.8  303.48
#Mann= 19 ,-1 , 0
  3906.4     .12       0    5078     .07       0    5084     .12       0
  5203.3     .05       0    5340     .12       0  5586.2     .16       0
  5716.8     .12       0    6021     .16       0  6049.1     .12       0
  6219.4     .16       0  6316.1     .12       0  6449.5     .05       0
    6583     .12       0  7040.3     .16       0  7116.8     .12       0
  7185.9     .16       0  7383.8     .12       0    7437     .16       0
  7768.3     .05       0
Bank Sta=4286.5,5406.3
XS Rating Curve= 0 ,0
Exp/Cntr=0.3,0.1

Type RM Length L Ch R = 1 ,115541  ,951,951,951
BEGIN DESCRIPTION:
CATFISH CREEK 72.0
END DESCRIPTION:
XS GIS Cut Line= 3
      3681249.64     10706660.17      3679149.61     10707860.19
      3677649.62     10710860.18
#Sta/Elev= 30
  2608.8     335  2827.7  335.97  2923.4  332.28  3084.7  332.82  3165.3  325.77
  3218.5  314.56  3358.1  293.04  3445.3  281.57    3590  273.65  3788.7  270.92
  3912.5  267.59  5021.6  265.88  5024.4  265.38  5027.6  265.88  5354.5  268.31
  5452.4  271.96  6576.4  274.49  6798.6   275.3  6804.2  275.32  7054.4  273.87
  7196.5  273.19  7249.6  275.95  7473.2  274.23  7881.3  282.16  7989.4  287.55
  8068.6  293.76  8076.9  297.23  8104.9  297.77  8187.8  308.43  8381.6  331.03
#Mann= 11 ,-1 , 0
  2608.8     .12       0  3358.1     .16       0  3445.3     .12       0
  5021.6     .07       0  5027.6     .12       0  6576.4     .16       0
  6798.6     .12       0  6804.2     .16       0  7054.4     .12       0
  7989.4     .05       0  8187.8     .12       0
Bank Sta=3788.7,5452.4
XS Rating Curve= 0 ,0
Exp/Cntr=0.3,0.1

Type RM Length L Ch R = 1 ,114590  ,956,956,956
BEGIN DESCRIPTION:
CATFISH CREEK 71.0
END DESCRIPTION:
XS GIS Cut Line= 3
      3680802.21     10706766.85      3678553.92     10707322.41
      3675107.72     10706237.34
#Sta/Elev= 30
  2824.5  326.66  2944.1  315.62  3102.1  293.39  3208.3  281.25    3308  276.18
  3648.7  271.84  3669.8  271.68  3741.6  270.29  5007.9  264.61  5010.7  264.11
  5013.9  264.61  5103.6  264.61  5227.3  272.81    6057  279.75  6421.9   289.5
  6472.2  296.08    6671  308.03  6828.5  310.75  7065.6  325.92  7210.8  325.25
  7364.1   319.5  7491.7  316.57  7638.7  320.06  7825.8  337.92  7928.3  340.18
  8030.8  335.63  8133.3  334.15  8235.8  331.56  8440.8  333.34  8753.4  338.25
#Mann= 19 ,-1 , 0
  2824.5     .12       0  3102.1     .16       0    3308     .12       0
  3669.8     .16       0  3741.6     .12       0  5007.9     .07       0
  5013.9     .12       0  6421.9     .16       0  6472.2     .12       0
    6671     .16       0  7210.8     .12       0  7364.1     .16       0
  7638.7     .12       0  7825.8      .1       0  7928.3     .12       0
  8030.8     .16       0  8133.3     .05       0  8235.8     .16       0
  8440.8     .05       0
Bank Sta=3648.7,5227.3
XS Rating Curve= 0 ,0
Exp/Cntr=0.3,0.1

Type RM Length L Ch R = 1 ,113634  ,937,937,937
BEGIN DESCRIPTION:
CATFISH CREEK 70.0
END DESCRIPTION:
XS GIS Cut Line= 3
      3680799.56     10706560.19      3679199.61     10706560.19
      3678599.62     10706360.19
#Sta/Elev= 30
  3395.4  332.68  3435.4  331.58  3565.4  321.86  3655.4  306.19  3750.6   292.6
  3855.4  280.32  3906.3  277.65  3975.4  273.75  4110.9  272.88  4296.3  271.01
  4445.4  269.11  4602.4  265.19  4605.1  264.69  4608.4  265.19  4685.4  266.34
  4705.4  270.04  4735.4  265.42  4955.4  266.82  5132.4  265.46  5174.5  267.84
  5216.7  265.25  5258.9  267.11  5269.4  269.39  5332.7  278.13  5385.4  278.79
    5417  282.43  5427.5  285.54  5511.9  298.11  5522.4  302.34  5627.8  312.81
#Mann= 7 ,-1 , 0
  3395.4     .12       0  3750.6     .16       0  3906.3     .12       0
  4110.9     .16       0  4296.3     .12       0  4602.4     .07       0
  4608.4     .12       0
Bank Sta=4445.4,5269.4
XS Rating Curve= 0 ,0
Exp/Cntr=0.3,0.1

Type RM Length L Ch R = 1 ,112697  ,2038,2038,2038
BEGIN DESCRIPTION:
CATFISH CREEK 69.0
END DESCRIPTION:
XS GIS Cut Line= 3
      3680399.59     10705860.19      3679399.61     10705860.19
      3678899.59     10705760.18
#Sta/Elev= 30
  3973.2  302.12  3991.1  300.76  4013.2  301.21  4043.2  299.18  4093.2  292.12
  4123.2  290.53  4183.2  282.77  4193.2  283.02  4303.2  271.39  4343.2   269.6
  4363.2   271.2  4443.2  270.89  4513.2  265.08  4610.2  264.51  4612.9  264.01
  4616.2  264.51  4813.2  266.25  4833.2  265.09  4863.2  266.09  5044.6  264.91
  5095.6  269.71  5146.5  276.37  5157.5  279.71  5238.3  291.42  5289.3  295.37
  5309.7  299.06  5370.9  306.06  5381.1  305.86  5421.9  310.86  5483.1  315.49
#Mann= 5 ,-1 , 0
  3973.2     .16       0  3991.1     .12       0  4610.2     .07       0
  4616.2     .12       0  5157.5     .16       0
Bank Sta=4443.2,5095.6
XS Rating Curve= 0 ,0
Exp/Cntr=0.3,0.1

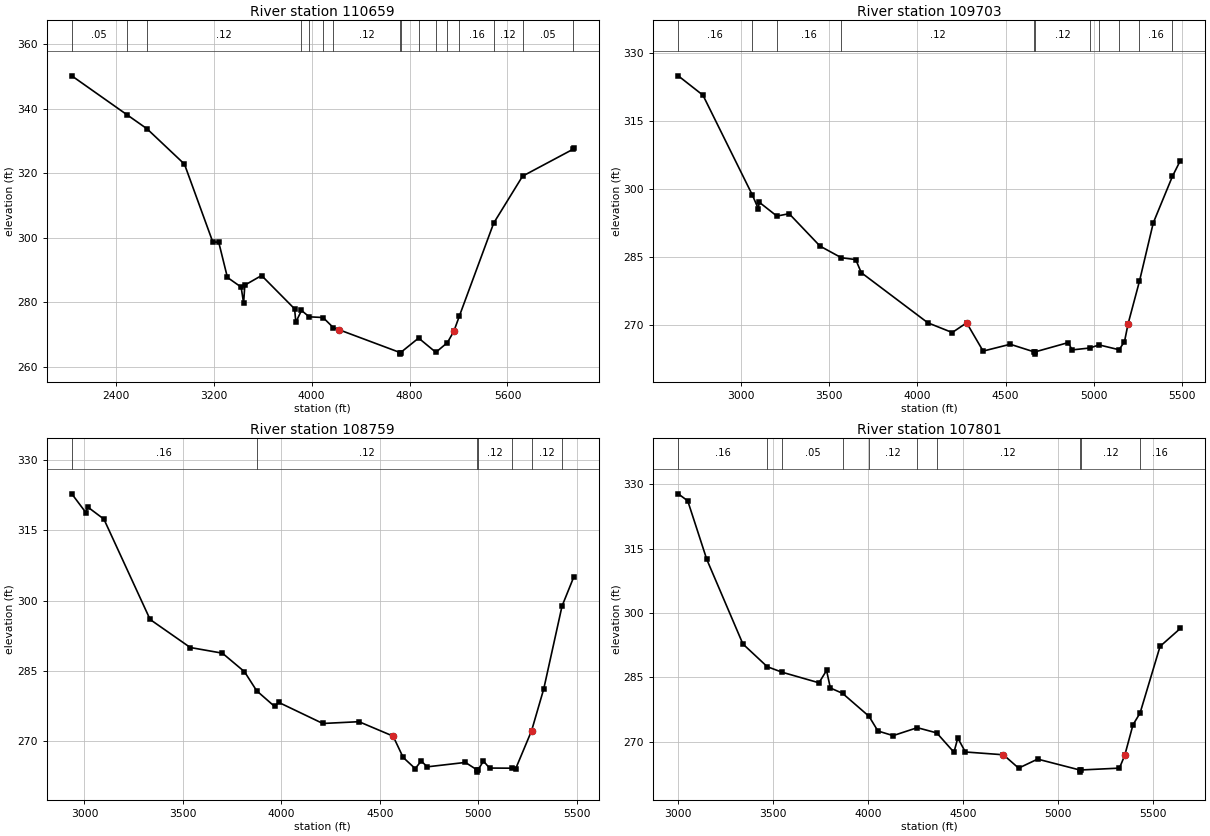
Type RM Length L Ch R = 1 ,110659  ,956,956,956
BEGIN DESCRIPTION:
CATFISH CREEK 67.0
END DESCRIPTION:
XS GIS Cut Line= 2
        3681961.      10704124.5      3677924.63     10704840.63
#Sta/Elev= 30
  2042.4  350.21    2492  338.18  2656.4   333.8  2962.6  322.83  3193.9   298.7
  3242.2  298.65  3313.3  287.72  3425.1  284.74  3445.4  279.78  3455.5  285.34
  3592.3  288.31  3861.8  277.98  3871.9  273.84    3918  277.49  3981.1  275.51
  4094.1   275.3  4178.5  272.14  4227.4  271.47    4722  264.45  4724.8  263.95
    4728  264.45  4874.3  268.93    5015  264.51  5109.1  267.51  5161.8  271.01
  5206.7  275.71  5487.3  304.56  5723.4  319.12  6137.5   327.5  6141.8  327.97
#Mann= 16 ,-1 , 0
  2042.4     .05       0    2492     .16       0  2656.4     .12       0
    3918     .16       0  3981.1     .12       0  4094.1     .16       0
  4178.5     .12       0    4722     .07       0    4728     .12       0
  4874.3     .07       0    5015     .12       0  5109.1     .07       0
  5206.7     .16       0  5487.3     .12       0  5723.4     .05       0
  6137.5     .16       0
Bank Sta=4227.4,5161.8
XS Rating Curve= 0 ,0
Exp/Cntr=0.3,0.1

Type RM Length L Ch R = 1 ,109703  ,944,944,944
BEGIN DESCRIPTION:
CATFISH CREEK 66.0
END DESCRIPTION:
XS GIS Cut Line= 3
      3680949.62     10702510.18      3678949.61     10703710.19
       3678449.6     10703610.19
#Sta/Elev= 30
  2647.2  325.03  2787.2  320.75  3066.7  298.71  3100.1   295.7  3105.9  297.11
  3205.6  294.05    3275  294.58  3449.9  287.42  3570.6  284.85  3652.1  284.44
  3683.2  281.56  4060.2  270.48  4198.2  268.33  4279.9  270.47  4373.2  264.23
  4526.7  265.74  4661.7  264.06  4664.5  263.56  4667.7  264.06  4855.2  266.11
  4876.6  264.49  4978.3  264.92  5029.3   265.6  5142.7  264.53  5173.4   266.3
  5193.8  270.25    5258  279.63  5336.5  292.56  5444.9  302.83  5489.5   306.3
#Mann= 11 ,-1 , 0
  2647.2     .16       0  3066.7      .1       0  3205.6     .16       0
  3570.6     .12       0  4661.7     .07       0  4667.7     .12       0
  4978.3     .07       0  5029.3     .12       0  5142.7     .07       0
    5258     .16       0  5444.9     .05       0
Bank Sta=4279.9,5193.8
XS Rating Curve= 0 ,0
Exp/Cntr=0.3,0.1

Type RM Length L Ch R = 1 ,108759  ,958,958,958
BEGIN DESCRIPTION:
CATFISH CREEK 65.0
END DESCRIPTION:
XS GIS Cut Line= 3
      3680899.64     10702360.18      3678899.61     10702760.19
      3678399.65     10702860.18
#Sta/Elev= 30
  2935.7  322.79  3007.1   318.8  3017.3  319.96  3098.9  317.39  3333.5  295.98
  3537.4     290  3700.6  288.79  3812.8  284.83  3874.8  280.76  3965.7  277.42
  3986.1   278.3  4210.5  273.79  4394.1  274.17  4567.4  271.09  4618.4  266.55
  4679.6  264.16  4710.2  265.78  4740.8  264.54  4934.5  265.48  4992.7  263.91
  4995.5  263.41  4998.7  263.91  5026.3  265.76  5056.9  264.28  5168.9  264.25
  5189.5   264.1  5270.6  272.24  5332.3  281.16  5425.2  298.83  5485.2  305.09
#Mann= 7 ,-1 , 0
  2935.7     .16       0  3874.8     .12       0  4992.7     .07       0
  4998.7     .12       0  5168.9     .07       0  5270.6     .12       0
  5425.2     .05       0
Bank Sta=4567.4,5270.6
XS Rating Curve= 0 ,0
Exp/Cntr=0.3,0.1

Type RM Length L Ch R = 1 ,107801  ,956,956,956
BEGIN DESCRIPTION:
CATFISH CREEK 64.0
END DESCRIPTION:
XS GIS Cut Line= 3
      3680799.57     10701810.19      3678799.61     10701810.19
      3678299.59      10702210.2
#Sta/Elev= 30
  3002.5  327.74  3052.5   326.1  3152.5  312.48  3342.5  292.78  3470.5  287.49
  3548.9   286.2  3742.5  283.74  3782.5  286.61  3802.5  282.53  3866.4  281.29
  4005.7  275.94  4052.5  272.52  4132.5  271.44  4259.7  273.29    4362  272.07
  4452.5  267.56  4472.5  270.88  4512.5  267.63  4712.5  266.98  4792.5  263.87
  4892.5  265.97  5113.9  263.44  5116.7  262.94  5119.9  263.44  5322.6  263.87
  5350.6  266.85  5393.9  273.96  5431.2   276.7  5536.3  292.22  5642.8  296.39
#Mann= 10 ,-1 , 0
  3002.5     .16       0  3470.5     .12       0  3548.9     .05       0
  3866.4     .16       0  4005.7     .12       0  4259.7     .16       0
    4362     .12       0  5113.9     .07       0  5119.9     .12       0
  5431.2     .16       0
Bank Sta=4712.5,5350.6
XS Rating Curve= 0 ,0
Exp/Cntr=0.3,0.1