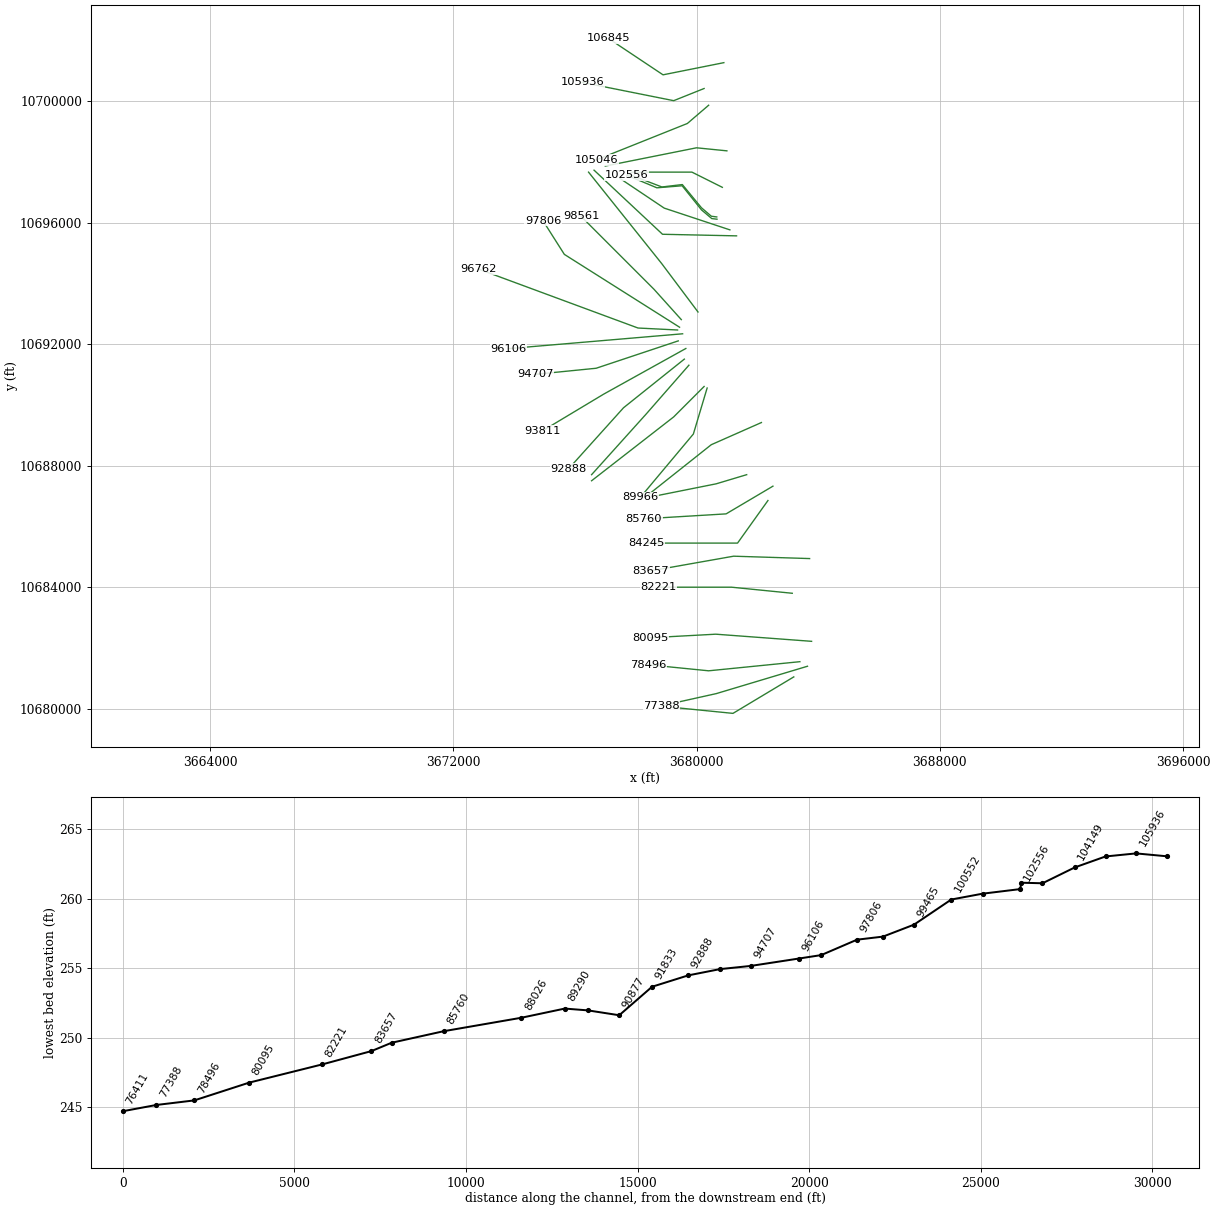
HEC-RAS study CATFISH CREEK.prj: CATFISH CREEK Base Level Engineering

--- CATFISH CREEK.g01 (geometry) --- (continued)

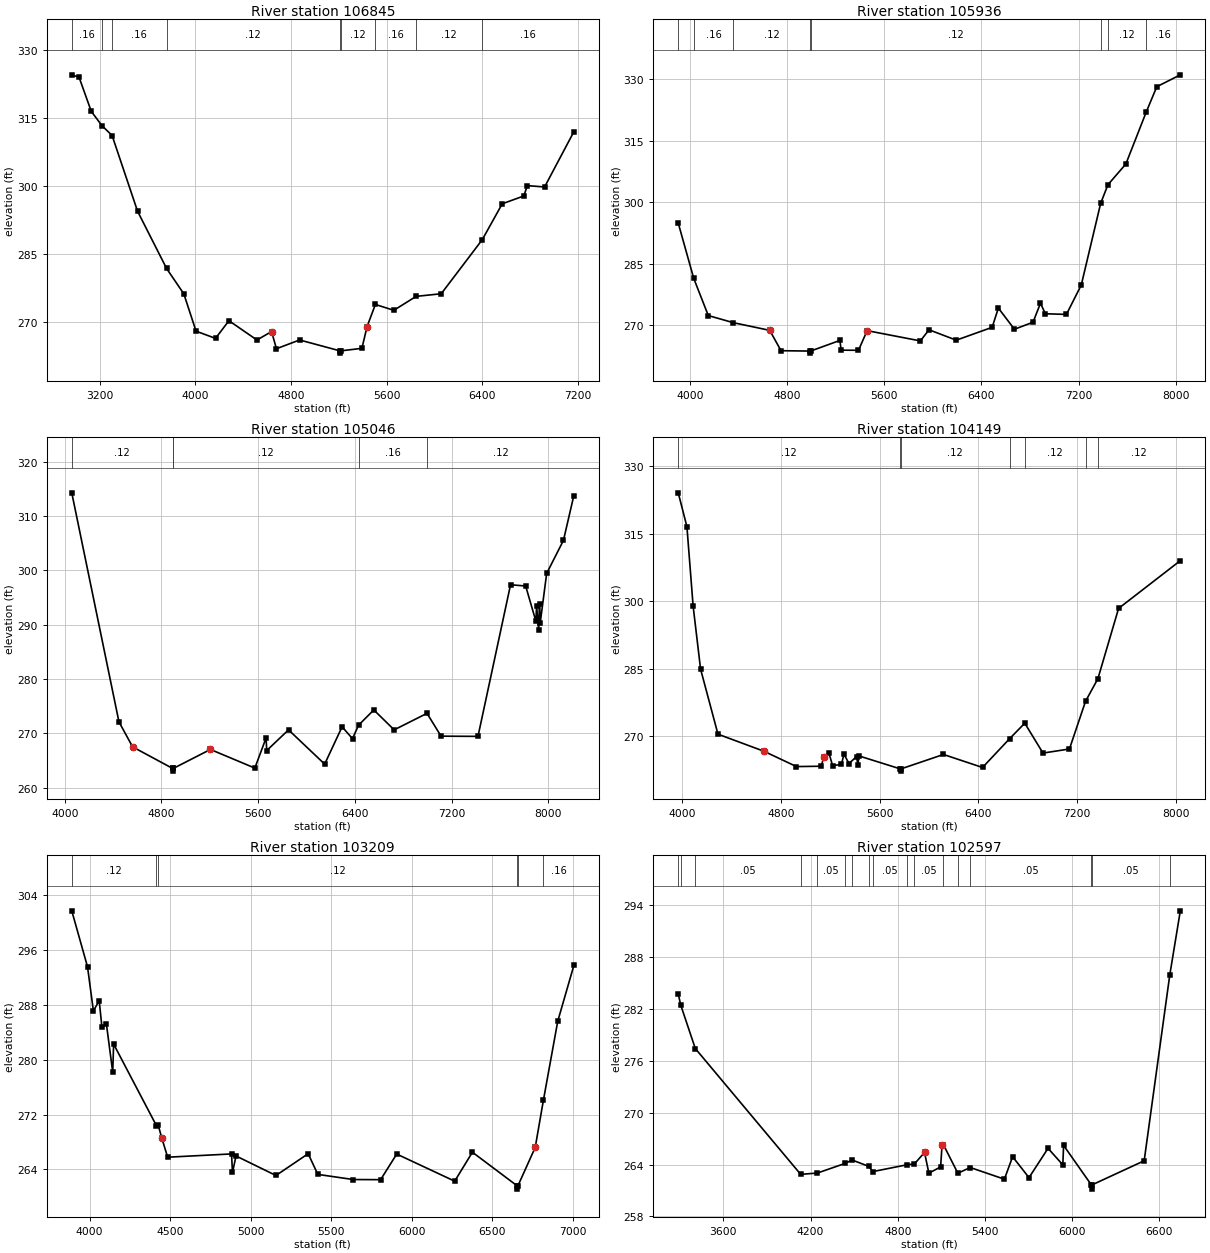
Type RM Length L Ch R = 1 ,106845  ,909,909,909
BEGIN DESCRIPTION:
CATFISH CREEK 63.0
END DESCRIPTION:
XS GIS Cut Line= 3
      3680899.63     10701260.19      3678899.61     10700860.19
      3677099.58     10702060.21
#Sta/Elev= 30
  2965.3   324.6  3026.5  324.06  3128.5  316.52  3218.1  313.36  3302.9  311.18
    3516  294.44    3759  281.78  3903.5  276.16  4005.5  267.92  4168.7  266.32
  4280.9  270.23  4515.4  265.96  4637.8  267.83  4678.6  264.03  4872.4  265.97
  5210.8  263.56  5213.5  263.06  5216.8  263.56    5394  264.12  5437.6  268.94
  5506.8  273.82  5661.4  272.53  5848.1  275.61  6058.1  276.19  6401.5  288.14
  6568.8  296.08  6749.1  297.81  6779.2   300.1  6923.4   299.8  7168.3  312.01
#Mann= 9 ,-1 , 0
  2965.3     .16       0  3218.1     .12       0  3302.9     .16       0
    3759     .12       0  5210.8     .07       0  5216.8     .12       0
  5506.8     .16       0  5848.1     .12       0  6401.5     .16       0
Bank Sta=4637.8,5437.6
XS Rating Curve= 0 ,0
Exp/Cntr=0.3,0.1

Type RM Length L Ch R = 1 ,105936  ,890,890,890
BEGIN DESCRIPTION:
CATFISH CREEK 62.0
END DESCRIPTION:
XS GIS Cut Line= 3
       3680249.6     10700410.18      3679249.61     10700010.19
      3676249.64     10700610.18
#Sta/Elev= 30
  3901.9  294.92    4029   281.5  4149.6  272.41  4355.3  270.68  4655.8  268.81
  4748.7  263.86  4986.1  263.77  4988.9  263.27  4992.1  263.77  5233.9  266.36
  5244.1  263.99  5386.8  263.96  5458.2  268.74  5896.7  266.24  5968.1  268.95
  6192.5  266.42  6488.2  269.55  6539.2  274.23  6671.8  269.08  6824.8  270.79
    6886   275.4  6926.7  272.85  7100.1  272.69  7222.5  279.86    7382   299.7
  7441.9  304.24  7589.6  309.28  7757.8  321.95  7844.6  328.09  8038.3  330.98
#Mann= 8 ,-1 , 0
  3901.9     .12       0    4029     .16       0  4355.3     .12       0
  4986.1     .07       0  4992.1     .12       0    7382     .16       0
  7441.9     .12       0  7757.8     .16       0
Bank Sta=4655.8,5458.2
XS Rating Curve= 0 ,0
Exp/Cntr=0.3,0.1

Type RM Length L Ch R = 1 ,105046  ,897,897,897
BEGIN DESCRIPTION:
CATFISH CREEK 61.0
END DESCRIPTION:
XS GIS Cut Line= 3
      3680399.59     10699860.17      3679699.61     10699260.19
      3676699.64      10698060.2
#Sta/Elev= 30
  4058.2   314.3  4448.4  272.13  4561.4  267.52  4892.1  263.55  4894.8  263.05
  4898.1  263.55    5205  267.04  5572.5  263.61  5665.4  269.16  5670.8  266.84
  5851.2  270.65  6150.1  264.34  6294.1  271.21  6380.3  269.03  6430.4  271.51
  6556.6  274.32  6724.9  270.65  6996.6  273.69  7112.7  269.49  7418.3  269.45
  7687.5  297.37  7812.7  297.14  7897.5  290.64  7902.9  293.54  7920.4     289
  7927.2  293.74  7932.5  290.26  7986.4  299.46  8125.1  305.54  8211.2   313.8
#Mann= 5 ,-1 , 0
  4058.2     .12       0  4892.1     .07       0  4898.1     .12       0
  6430.4     .16       0  6996.6     .12       0
Bank Sta=4561.4,5205
XS Rating Curve= 0 ,0
Exp/Cntr=0.3,0.1

Type RM Length L Ch R = 1 ,104149  ,940,940,940
BEGIN DESCRIPTION:
CATFISH CREEK 60.0
END DESCRIPTION:
XS GIS Cut Line= 3
      3680999.59     10698360.19      3679999.61     10698460.19
      3676999.59     10697860.18
#Sta/Elev= 30
  3969.5  324.09  4039.8  316.57  4090.1   298.9  4150.4  284.92  4291.1  270.47
  4662.9  266.68  4926.7  263.27  5127.4  263.35  5147.8  265.42  5188.6  266.36
  5219.2  263.47  5290.6  263.76    5311  266.02  5351.8  263.95    5413   265.5
  5423.2  263.73  5433.4  265.63  5766.9  262.76  5769.7  262.26  5772.9  262.76
  6116.6  265.96  6432.8  263.07  6652.1  269.47  6774.7  272.91  6922.3  266.27
  7136.4  267.18  7266.7  277.78  7366.7  282.79  7534.2  298.41  8033.9  309.02
#Mann= 7 ,-1 , 0
  3969.5     .12       0  5766.9     .07       0  5772.9     .12       0
  6652.1     .16       0  6774.7     .12       0  7266.7     .16       0
  7366.7     .12       0
Bank Sta=4662.9,5147.8
XS Rating Curve= 0 ,0
Exp/Cntr=0.3,0.1

Type RM Length L Ch R = 1 ,103209  ,612,612,612
BEGIN DESCRIPTION:
CATFISH CREEK 59.0
END DESCRIPTION:
XS GIS Cut Line= 3
      3680849.61     10697160.19      3679849.61     10697660.19
      3677849.65     10697660.19
#Sta/Elev= 30
  3889.7  301.75  3987.5  293.58  4023.9  287.16  4060.2  288.61    4077  284.76
  4104.9  285.21  4144.1  278.18  4149.6   282.3  4415.4  270.39  4426.6  270.46
  4448.7  268.58  4485.1  265.78    4882  266.26  4887.6  263.55  4909.9  265.96
  5157.7  263.11  5357.7  266.29  5417.7  263.27  5637.7  262.52  5807.7   262.5
  5907.7  266.24  6267.7  262.28  6377.7  266.51  6654.7  261.62  6657.5  261.12
  6660.7  261.62  6767.7   267.2  6818.4  274.06  6907.7  285.63  7007.7  293.77
#Mann= 6 ,-1 , 0
  3889.7     .12       0  4415.4     .16       0  4426.6     .12       0
  6654.7     .07       0  6660.7     .12       0  6818.4     .16       0
Bank Sta=4448.7,6767.7
XS Rating Curve= 0 ,0
Exp/Cntr=0.3,0.1

Type RM Length L Ch R = 1 ,102597  ,41,41,41
BEGIN DESCRIPTION:
Mapping XS 16253d9f
END DESCRIPTION:
XS GIS Cut Line= 6
      3680665.79     10696186.58      3680488.02     10696210.16
      3680161.47     10696489.54      3679533.76      10697251.5
      3678862.52     10697171.67      3677777.68     10697588.92
#Sta/Elev= 30
  3289.1  283.74  3306.4  282.45  3406.4  277.43  4131.6  262.87  4246.4  263.02
  4438.2  264.14  4485.2  264.53  4599.4   263.8  4628.5  263.19  4860.9  263.97
  4914.4  264.08  4983.8   265.4  5013.8  263.01  5094.6  263.73  5104.7  266.31
  5113.9   266.3  5213.2     263  5298.3  263.66  5533.5  262.31  5589.9  264.91
  5702.8  262.49  5833.8  265.88  5935.5  263.97  5940.9  266.22  6131.4  261.66
  6134.2  261.16  6137.4  261.66  6495.3  264.44  6671.5  285.94    6744  293.36
#Mann= 17 ,-1 , 0
  3289.1     .05       0  3306.4     .08       0  3406.4     .05       0
  4131.6     .08       0  4246.4     .05       0  4438.2     .08       0
  4485.2     .05       0  4599.4     .16       0  4628.5     .05       0
  4860.9     .12       0  4914.4     .05       0  5113.9     .08       0
  5213.2     .12       0  5298.3     .05       0  6131.4     .04       0
  6137.4     .05       0  6671.5     .16       0
Bank Sta=4983.8,5104.7
XS Rating Curve= 0 ,0
Exp/Cntr=0.3,0.1

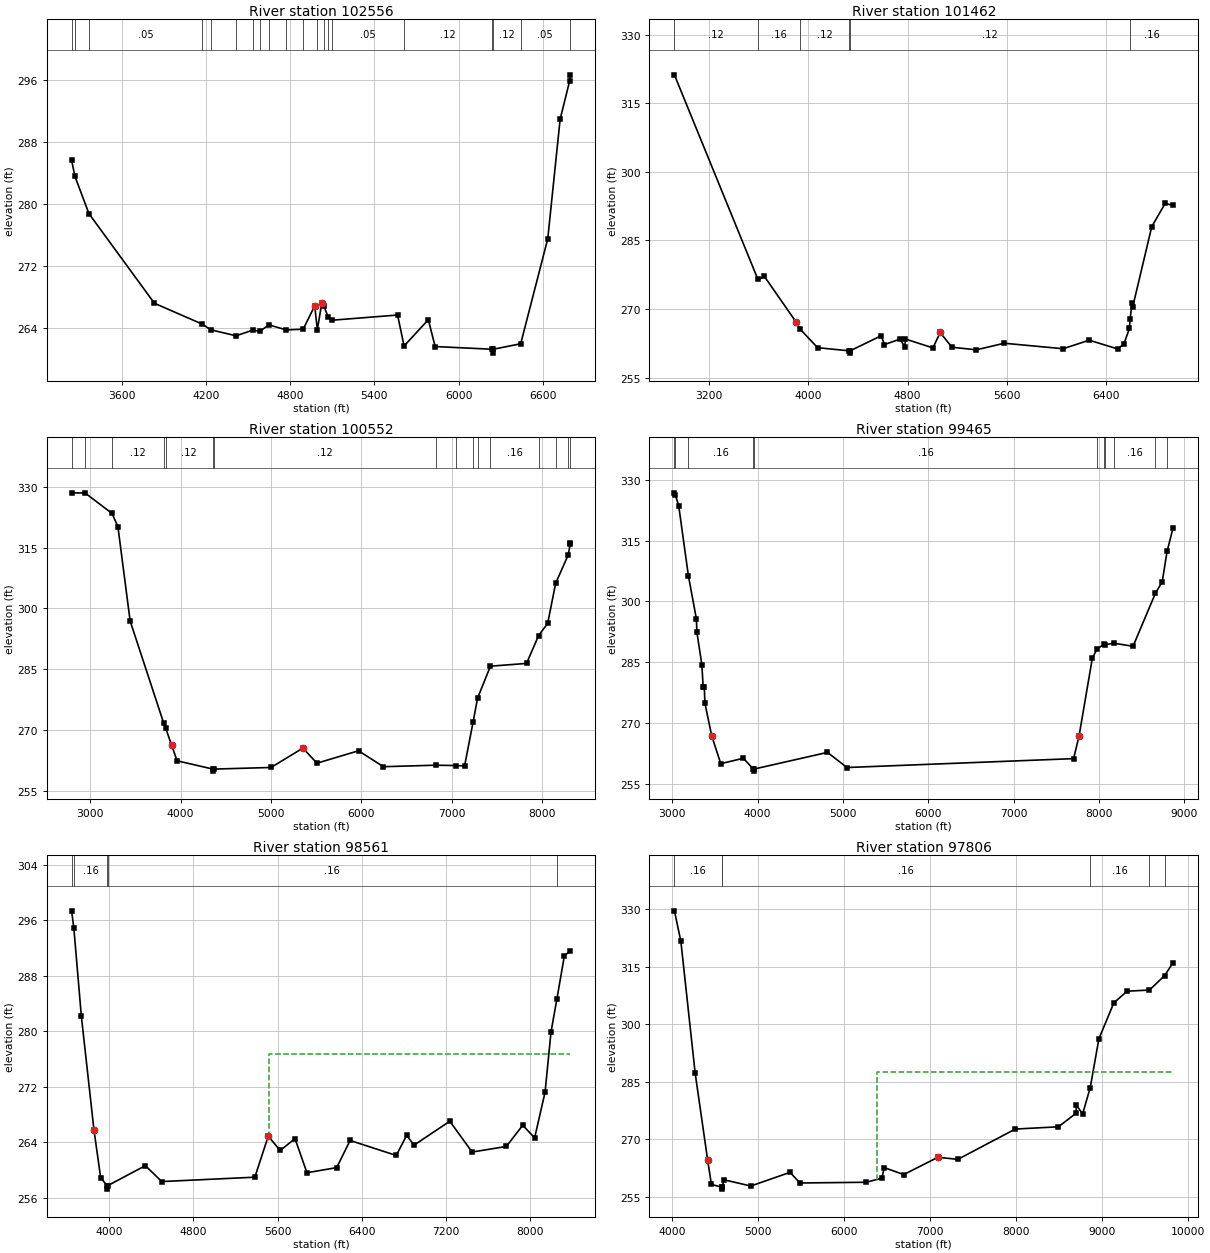
Type RM Length L Ch R = 1 ,102556  ,1094,1094,1094
BEGIN DESCRIPTION:
Mapping XS 55b6a093
END DESCRIPTION:
XS GIS Cut Line= 6
      3680674.88     10696112.19      3680502.53     10696132.15
       3680165.1     10696416.98      3679528.32     10697211.59
      3678697.43     10697144.46      3677711.74     10697555.75
#Sta/Elev= 30
  3244.4  285.62  3267.9  283.54  3367.8  278.72  3834.1  267.14  4176.1  264.44
  4234.2  263.72  4415.3  262.94  4533.3  263.66  4585.4  263.52  4649.7  264.35
  4773.4   263.7  4893.7  263.79  4975.8  266.81  4994.7  263.72  5025.8  267.12
  5040.4  266.82  5071.9  265.35  5097.7  264.95  5566.1  265.62  5612.4  261.62
  5785.1  265.02  5833.6  261.55  6241.2   261.2    6244   260.7  6247.2   261.2
    6443  261.91  6635.6  275.47  6723.8  290.91  6791.9  295.88  6796.6  296.65
#Mann= 20 ,-1 , 0
  3244.4     .05       0  3267.9     .08       0  3367.8     .05       0
  4176.1     .08       0  4234.2     .05       0  4415.3     .08       0
  4533.3     .05       0  4585.4     .08       0  4649.7     .05       0
  4773.4     .05       0  4893.7     .08       0  4994.7     .12       0
  5040.4     .05       0  5071.9     .12       0  5097.7     .05       0
  5612.4     .12       0  6241.2     .07       0  6247.2     .12       0
    6443     .05       0  6791.9     .16       0
Bank Sta=4975.8,5025.8
XS Rating Curve= 0 ,0
Exp/Cntr=0.3,0.1

Type RM Length L Ch R = 1 ,101462  ,910,910,910
BEGIN DESCRIPTION:
CATFISH CREEK 57.0
END DESCRIPTION:
XS GIS Cut Line= 3
      3681098.46     10695761.28      3678938.73     10696476.56
      3677487.36     10697448.77
#Sta/Elev= 30
  2920.2  321.19    3594  276.47  3645.8  277.14  3898.7  267.27  3935.7  265.56
  4075.1  261.56    4331  260.87  4333.7  260.37    4337  260.87  4587.6  264.17
  4614.1  262.24  4740.9  263.45  4777.9   261.7  4783.5  263.45  5005.1  261.51
  5063.2  264.88  5158.3  261.66  5355.6  261.09  5579.4  262.53  6055.1  261.33
  6265.2   263.2  6494.1  261.29  6544.4  262.34  6589.4  265.76  6594.7  267.74
  6610.4  271.25  6616.4  270.52  6769.5     288  6877.6  293.09  6942.2  292.65
#Mann= 6 ,-1 , 0
  2920.2     .12       0    3594     .16       0  3935.7     .12       0
    4331     .07       0    4337     .12       0  6594.7     .16       0
Bank Sta=3898.7,5063.2
XS Rating Curve= 0 ,0
Exp/Cntr=0.3,0.1

Type RM Length L Ch R = 1 ,100552  ,1087,1087,1087
BEGIN DESCRIPTION:
CATFISH CREEK 56.0
END DESCRIPTION:
XS GIS Cut Line= 3
       3681317.2     10695564.23      3678882.31     10695616.31
        3676630.     10697725.42
#Sta/Elev= 30
  2793.2  328.47  2943.1  328.42  3240.3  323.41  3305.7  320.16  3440.9  296.94
  3813.1  271.74  3833.3  270.62    3901  266.29  3961.1  262.49  4358.2  260.45
  4360.9  259.95  4364.2  260.45  5001.3  260.85  5353.7  265.62  5509.1   261.9
  5969.2  264.96  6245.2  261.04  6821.8  261.41    7048  261.32  7143.5  261.23
  7236.8  271.94    7287   277.9  7429.7  285.79  7829.8  286.47  7962.7  293.34
  8063.3  296.33  8151.9  306.21  8289.6  313.12  8313.8  315.91  8314.3  316.06
#Mann= 16 ,-1 , 0
  2793.2     .12       0  2943.1     .16       0  3240.3     .12       0
  3813.1     .16       0  3833.3     .12       0  4358.2     .07       0
  4364.2     .12       0  6821.8     .07       0    7048     .12       0
  7236.8     .16       0    7287     .12       0  7429.7     .16       0
  7962.7     .05       0  8151.9     .16       0  8289.6     .12       0
  8313.8     .16       0
Bank Sta=3901,5353.7
XS Rating Curve= 0 ,0
Exp/Cntr=0.3,0.1

Type RM Length L Ch R = 1 ,99465   ,904,904,904
BEGIN DESCRIPTION:
CATFISH CREEK 55.0
END DESCRIPTION:
XS GIS Cut Line= 3
      3680049.59     10693060.21      3678849.61     10694660.19
      3676449.64     10697660.15
#Sta/Elev= 30
  3026.4  326.76  3037.3  326.24  3076.4  323.63    3190  306.34  3283.7  295.69
  3289.9  292.37  3348.2  284.33  3362.8     279  3376.4  278.84  3383.7   274.9
  3462.8  266.88  3569.1  259.98  3833.7  261.31  3951.5  258.64  3954.2  258.14
  3957.5  258.64  4819.1  262.76    5048  259.03  7702.1  261.22  7766.1  266.81
  7921.4  285.97    7979  288.34  8060.5  289.38  8066.3  289.28  8171.1  289.69
  8398.4  288.92  8661.1  302.03  8740.2  304.84    8797  312.32  8868.2   318.2
#Mann= 11 ,-1 , 0
  3026.4     .12       0  3037.3     .16       0    3190     .16       0
  3951.5     .07       0  3957.5     .16       0    7979     .12       0
  8060.5     .16       0  8066.3     .12       0  8171.1     .16       0
  8661.1     .05       0    8797     .16       0
Bank Sta=3462.8,7766.1
XS Rating Curve= 0 ,0
Exp/Cntr=0.3,0.1

Type RM Length L Ch R = 1 ,98561   ,755,755,755
BEGIN DESCRIPTION:
CATFISH CREEK 54.0
END DESCRIPTION:
XS GIS Cut Line= 3
      3679499.63     10692810.17      3678599.61     10693810.19
      3676199.61     10696210.19
#Sta/Elev= 30
  3642.8  297.37  3664.1  294.88  3735.1  282.23  3855.5  265.77    3919  258.94
  3979.5  257.78  3982.3  257.28  3985.5  257.78  4343.5  260.66  4499.8  258.37
  5384.2     259  5511.5  264.91  5624.6  262.85    5766  264.55  5879.1  259.64
    6162  260.38  6289.3  264.29  6727.7  262.13  6826.7  265.02  6897.4  263.62
  7236.8  267.06  7448.9  262.62  7774.2  263.43  7929.8  266.48  8042.9  264.67
  8141.9  271.23  8198.5  279.92    8255  284.71  8325.7  290.91  8382.3  291.59
#Mann= 5 ,-1 , 0
  3642.8     .12       0  3664.1     .16       0  3979.5     .07       0
  3985.5     .16       0    8255     .16       0
#XS Ineff= 2 , 0
                         5515.91          276.72
Permanent Ineff=
       F       F
Bank Sta=3855.5,5511.5
XS Rating Curve= 0 ,0
Exp/Cntr=0.3,0.1

Type RM Length L Ch R = 1 ,97806   ,1044,1044,1044
BEGIN DESCRIPTION:
Mapping XS 3abc5acb
END DESCRIPTION:
XS GIS Cut Line= 3
      3679442.87     10692559.45       3675653.8     10694955.29
      3674950.68     10696062.05
#Sta/Elev= 30
  4030.9  329.57  4105.7  321.65  4271.7  287.35  4417.6  264.53  4460.7  258.29
  4581.6  257.56  4584.3  257.06  4587.6  257.56  4605.8   259.5  4918.6  257.87
  5373.9  261.43    5490  258.66  6259.1  258.85  6439.6   259.9  6470.1  262.66
  6694.8  260.85  7092.4  265.36  7323.9  264.82  7991.1  272.71  8492.1   273.3
  8695.2  276.79  8701.1  278.91  8773.9  276.67    8862  283.53  8961.9  296.18
  9135.8  305.59  9289.7  308.63  9550.1  308.93  9725.6  312.68  9825.1  316.09
#Mann= 6 ,-1 , 0
  4030.9     .16       0  4581.6     .07       0  4587.6     .16       0
    8862     .16       0  9550.1     .05       0  9725.6     .16       0
#XS Ineff= 2 , 0
                         6379.55          287.52
Permanent Ineff=
       F       F
Bank Sta=4417.6,7092.4
XS Rating Curve= 0 ,0
Exp/Cntr=0.3,0.1

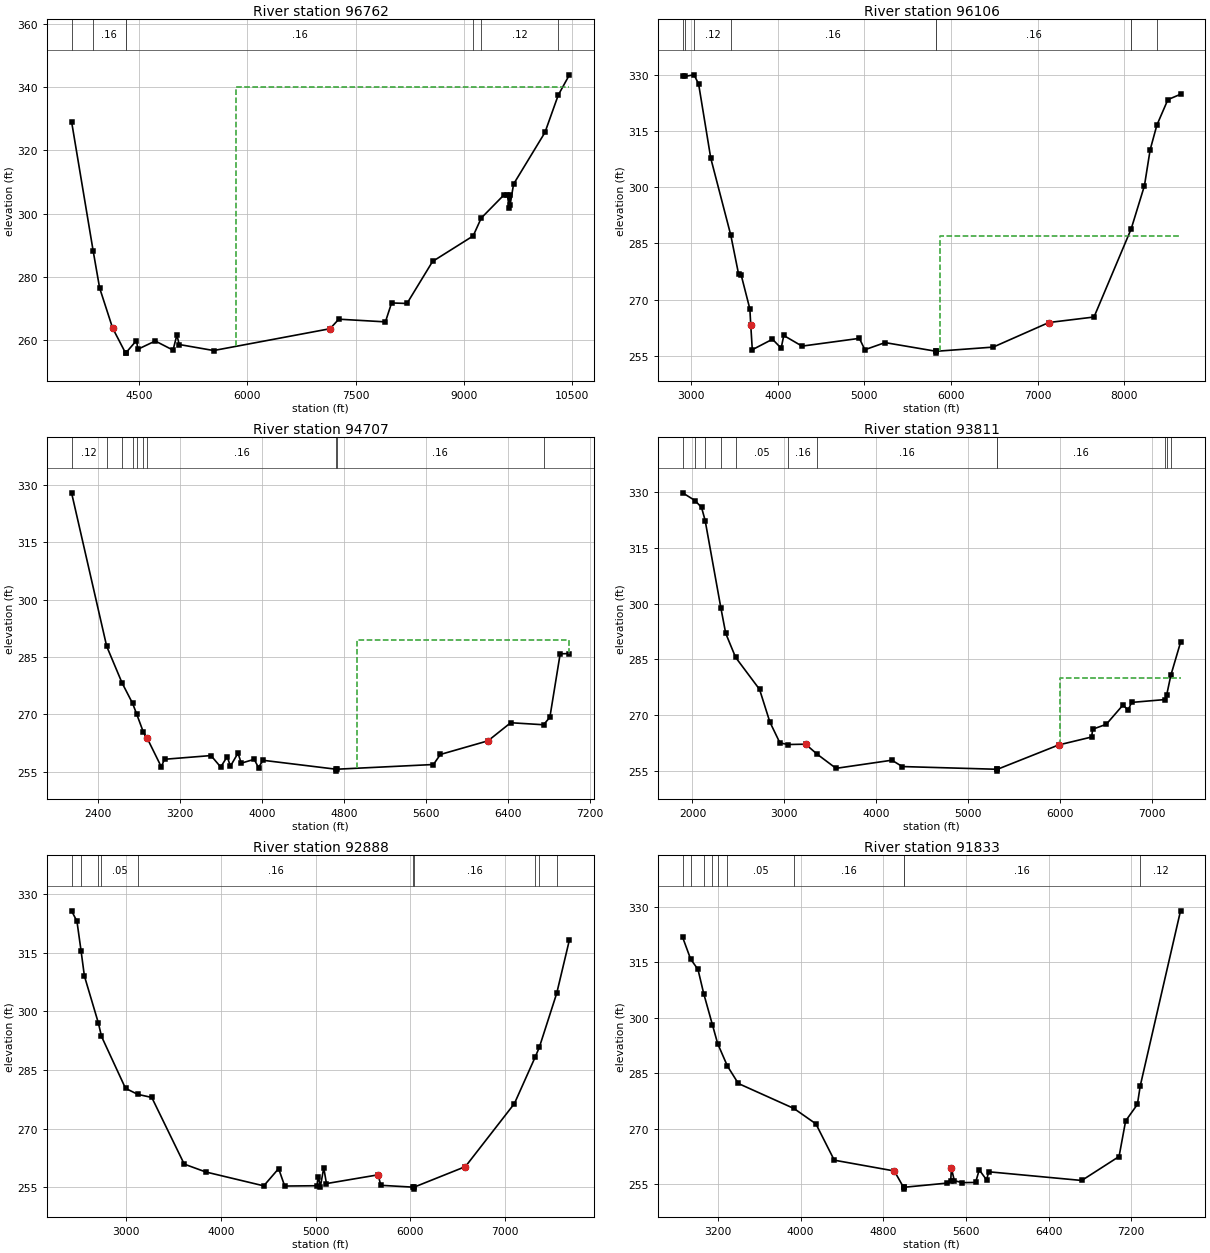
Type RM Length L Ch R = 1 ,96762   ,656,656,656
BEGIN DESCRIPTION:
Mapping XS bff50019
END DESCRIPTION:
XS GIS Cut Line= 3
      3679377.76     10692468.31      3678075.67     10692533.42
      3672828.26     10694473.53
#Sta/Elev= 30
  3565.4  329.09  3863.9  288.33    3954  276.55  4134.3  263.86  4314.2  255.95
  4314.7  255.95  4464.7  259.93  4484.7  257.18    4725  259.78  4971.5   256.9
  5024.8  261.67  5056.8  258.67  5534.4  256.77  7146.5  263.66  7268.4  266.67
  7914.1  265.82  7999.4   271.8  8212.7  271.63  8567.6  284.91  9129.6  292.96
  9241.8  298.61    9556  305.91  9603.7   305.9  9628.8  301.92  9634.1   305.8
  9641.3   302.7  9689.6  309.33 10124.4  325.64 10308.9  337.45 10463.7  343.84
#Mann= 7 ,-1 , 0
  3565.4     .12       0  3863.9     .16       0  4314.2     .05       0
  4314.7     .16       0  9129.6     .16       0  9241.8     .12       0
 10308.9     .16       0
#XS Ineff= 2 , 0
                         5845.45          339.92
Permanent Ineff=
       F       F
Bank Sta=4134.3,7146.5
XS Rating Curve= 0 ,0
Exp/Cntr=0.3,0.1

Type RM Length L Ch R = 1 ,96106   ,1399,1399,1399
BEGIN DESCRIPTION:
CATFISH CREEK 53.0
END DESCRIPTION:
XS GIS Cut Line= 2
      3679543.16     10692343.75      3673814.23     10691855.49
#Sta/Elev= 30
  2900.6  329.58  2932.8   329.6  3031.8  329.99  3084.8  327.58  3225.3  307.74
  3456.2  287.22  3546.5  276.81  3576.6  276.55    3677  267.47    3687  263.22
    3705  256.61  3937.9  259.41  4038.3  257.02  4068.4  260.41  4279.1  257.57
  4941.5  259.64    5005  256.61  5238.2  258.51  5825.7   256.2  5828.4   255.7
  5831.7   256.2  6487.1  257.31  7129.4  263.87  7651.3  265.34  8080.4  288.86
  8233.4  300.37  8299.6  309.98  8377.3  316.57  8504.4  323.37  8650.3   324.8
#Mann= 9 ,-1 , 0
  2900.6     .05       0  2932.8     .16       0  3031.8     .12       0
  3456.2     .16       0  5825.7     .07       0  5831.7     .16       0
  8080.4     .05       0  8080.4     .16       0  8377.3     .05       0
#XS Ineff= 2 , 0
                         5869.89          286.96
Permanent Ineff=
       F       F
Bank Sta=3687,7129.4
XS Rating Curve= 0 ,0
Exp/Cntr=0.3,0.1

Type RM Length L Ch R = 1 ,94707   ,896,896,896
BEGIN DESCRIPTION:
CATFISH CREEK 52.0
END DESCRIPTION:
XS GIS Cut Line= 3
      3679399.59     10692110.18      3676699.61     10691210.19
      3674699.61     10691010.19
#Sta/Elev= 30
  2144.7  327.97  2487.2  287.83  2637.2  278.25  2740.2  272.88  2779.4  270.13
    2845  265.37  2882.3  263.78  2882.5  263.77  3019.6  256.31  3051.2  258.27
  3504.5  259.24  3599.3  256.24  3662.6  258.94  3694.2  256.47    3768  259.88
  3799.6  257.25  3926.1  258.26  3968.3  256.07  4010.4  258.01  4724.2  255.67
    4727  255.17  4730.2  255.67  5674.1   256.9    5742  259.53  6206.8   263.1
  6427.9  267.83  6747.8   267.3  6809.8  269.25  6910.3  285.86  7000.7  285.92
#Mann= 10 ,-1 , 0
  2144.7     .12       0  2487.2     .16       0  2637.2     .05       0
  2740.2     .16       0  2779.4     .05       0    2845     .16       0
  2882.3     .16       0  4724.2     .07       0  4730.2     .16       0
  6747.8     .16       0
#XS Ineff= 2 , 0
                         4928.41          289.44
Permanent Ineff=
       F       F
Bank Sta=2882.5,6206.8
XS Rating Curve= 0 ,0
Exp/Cntr=0.3,0.1

Type RM Length L Ch R = 1 ,93811   ,923,923,923
BEGIN DESCRIPTION:
CATFISH CREEK 51.0
END DESCRIPTION:
XS GIS Cut Line= 3
      3679649.62     10691860.19      3676949.61     10690360.19
      3674949.59     10689160.18
#Sta/Elev= 30
  1893.2  329.83  2027.4  327.76  2099.1   325.9  2138.3  322.37  2309.3  298.88
  2362.2  292.01    2470  285.55  2730.6  276.94  2842.7  268.17  2952.5  262.53
  3040.4   262.1  3231.6  262.19  3360.4  259.45  3563.4  255.69    4172  257.88
  4284.1  256.17  5315.1  255.44  5317.9  254.94  5321.1  255.44  5986.8  261.98
  6346.3  264.12    6358  266.22  6505.7  267.54  6686.5  272.69  6744.8  271.41
  6781.7  273.43  7147.1   274.2    7163  275.36  7208.6   280.7  7314.3  289.58
#Mann= 12 ,-1 , 0
  1893.2     .05       0  2027.4     .16       0  2138.3     .12       0
  2309.3     .16       0    2470     .05       0  3040.4     .16       0
  3360.4     .16       0  5315.1     .07       0  5321.1     .16       0
  7147.1     .12       0    7163     .16       0  7208.6     .05       0
#XS Ineff= 2 , 0
                         6003.41          279.92
Permanent Ineff=
       F       F
Bank Sta=3231.6,5986.8
XS Rating Curve= 0 ,0
Exp/Cntr=0.3,0.1

Type RM Length L Ch R = 1 ,92888   ,1055,1055,1055
BEGIN DESCRIPTION:
CATFISH CREEK 50.0
END DESCRIPTION:
XS GIS Cut Line= 3
      3679599.64     10691510.21      3677599.61     10689910.19
      3675799.62      10687910.2
#Sta/Elev= 30
    2425  325.71  2481.9  323.03  2525.7  315.39  2560.3  309.05  2707.9  296.99
  2740.8  293.58  2994.1  280.29  3122.2  278.75  3271.1  277.95  3613.6  260.89
  3840.9  258.88  4452.4  255.33  4609.3  259.74  4673.3  255.28  5014.3  255.36
  5028.5  257.72  5050.2  255.16  5085.3  259.96  5113.7  255.91    5659  258.15
    5687  255.47  6031.5  254.99  6034.3  254.49  6037.5  254.99  6579.4  260.25
  7096.6  276.39  7315.6  288.28  7359.1  290.76    7543  304.63    7677  318.29
#Mann= 10 ,-1 , 0
    2425     .12       0  2525.7     .16       0  2707.9     .12       0
  2740.8     .05       0  3122.2     .16       0  6031.5     .07       0
  6037.5     .16       0  7315.6     .12       0  7359.1     .16       0
    7543     .05       0
Bank Sta=5659,6579.4
XS Rating Curve= 0 ,0
Exp/Cntr=0.3,0.1

Type RM Length L Ch R = 1 ,91833   ,956,956,956
BEGIN DESCRIPTION:
CATFISH CREEK 49.0
END DESCRIPTION:
XS GIS Cut Line= 3
      3679749.58     10691310.15      3678349.61     10689710.19
      3676549.61     10687710.19
#Sta/Elev= 30
  2859.5  321.76  2936.9  315.87    3008  313.08  3063.2  306.56  3148.2  298.06
    3198  293.05  3292.1  286.98  3398.1  282.24  3936.2  275.48  4148.8  271.32
  4326.3   261.5  4907.2  258.58  4996.3  254.17  4999.1  253.67  5002.3  254.17
  5417.1   255.3    5453  255.91  5459.7  259.29  5488.1  255.95  5565.9  255.43
  5693.7  255.48  5728.8  258.88  5799.8  256.17  5820.7  258.36  6720.6  256.01
  7081.6  262.49  7145.2  272.12  7258.8  276.58  7286.4  281.57  7676.2  328.93
#Mann= 10 ,-1 , 0
  2859.5     .16       0  2936.9     .12       0  3063.2     .16       0
  3148.2     .12       0    3198     .16       0  3292.1     .05       0
  3936.2     .16       0  4996.3     .07       0  5002.3     .16       0
  7286.4     .12       0
Bank Sta=4907.2,5459.7
XS Rating Curve= 0 ,0
Exp/Cntr=0.3,0.1

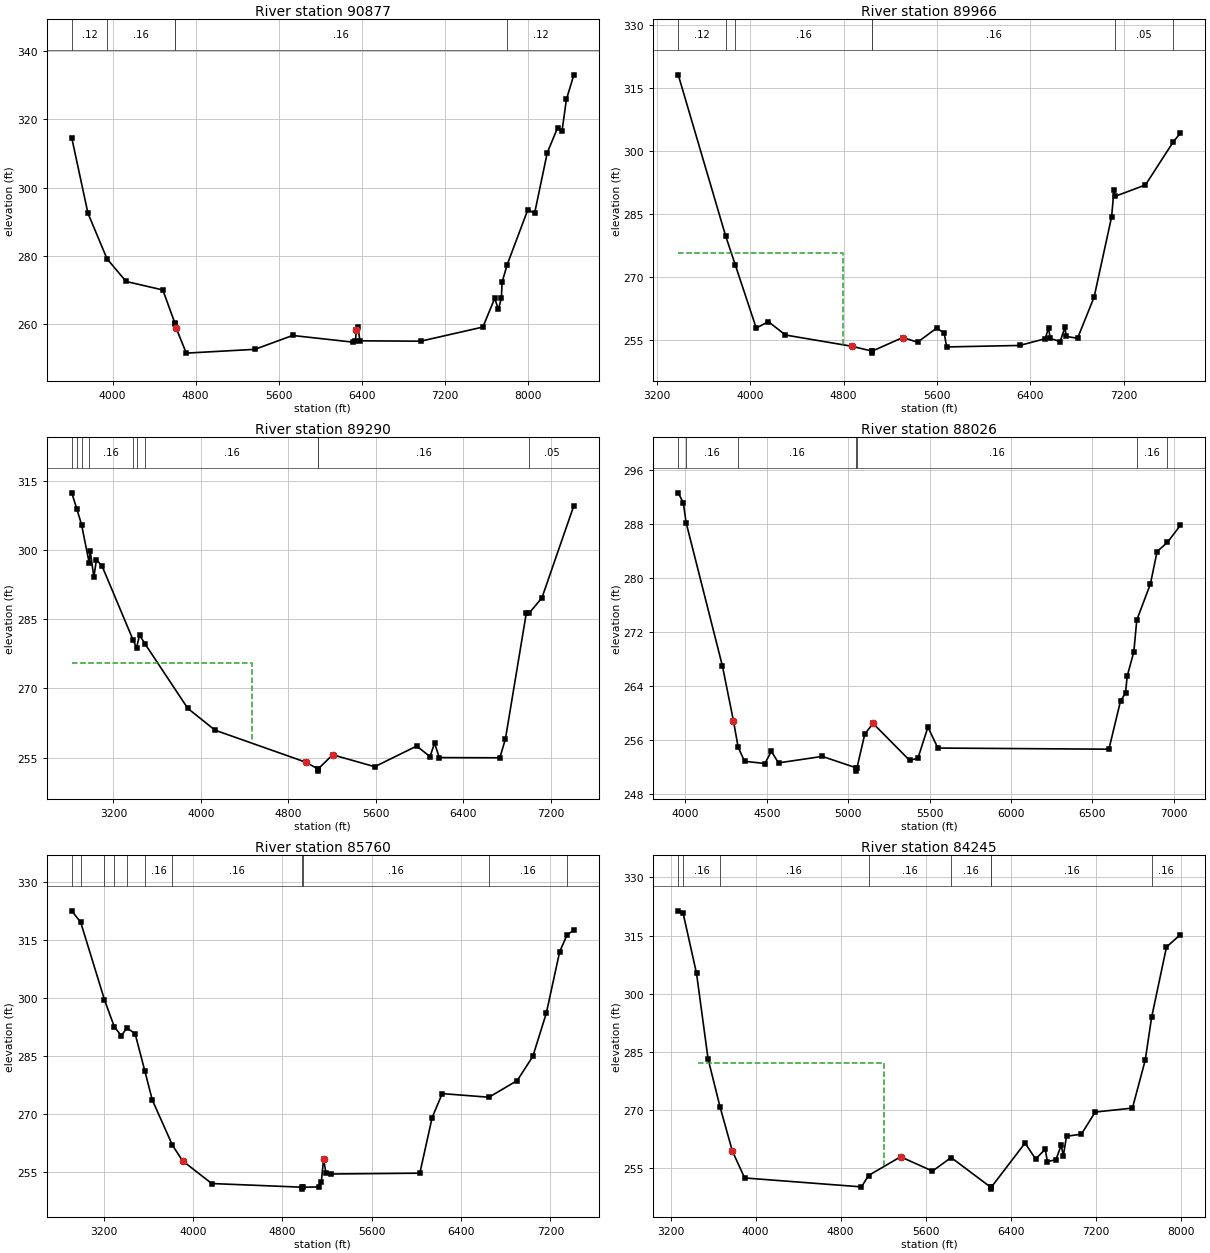
Type RM Length L Ch R = 1 ,90877   ,911,911,911
BEGIN DESCRIPTION:
CATFISH CREEK 48.0
END DESCRIPTION:
XS GIS Cut Line= 3
      3680249.61     10690610.19      3679249.61     10689610.19
      3676549.64     10687510.22
#Sta/Elev= 30
  3607.2  314.52  3762.8  292.52  3946.6  279.18  4130.5  272.56    4484  270.08
  4600.5  260.35  4601.9  260.18  4611.3  259.01    4710  251.62  5370.7  252.73
  5733.6  256.78  6318.1  254.82    6339  255.11  6347.1  258.37  6361.6  259.37
  6382.4  255.22    6967  255.11    7566  259.24    7680  267.65  7715.3  264.38
  7744.3  267.73  7750.6  272.34  7800.4  277.51  7999.4  293.59  8063.7  292.46
  8185.9  310.18  8285.4  317.48  8327.9   316.5  8370.5  325.78  8441.9  332.96
#Mann= 5 ,-1 , 0
  3607.2     .12       0  3946.6     .16       0  4600.5     .07       0
  4601.9     .16       0  7800.4     .12       0
Bank Sta=4611.3,6347.1
XS Rating Curve= 0 ,0
Exp/Cntr=0.3,0.1

Type RM Length L Ch R = 1 ,89966   ,676,676,676
BEGIN DESCRIPTION:
CATFISH CREEK 47.0
END DESCRIPTION:
XS GIS Cut Line= 3
      3680349.62     10690560.22      3679896.77      10689046.9
      3678149.61     10686960.18
#Sta/Elev= 30
  3382.8  318.08  3788.7  279.82  3871.4  272.94  4050.9  257.93  4155.3  259.44
  4301.4  256.27  4867.8  253.61  5040.3  252.47    5043  251.97  5046.3  252.47
  5306.1  255.67  5433.6  254.57  5597.2  257.93  5661.3  256.72  5682.2  253.44
  6306.7  253.79  6526.6  255.39  6555.2  257.97  6569.6  255.45  6654.1  254.73
  6697.1  258.18  6704.9  255.94  6803.8   255.5  6945.6   265.3  7095.2  284.32
    7116  290.72  7125.7  289.22  7385.4  291.92  7625.2  302.23    7684  304.17
#Mann= 7 ,-1 , 0
  3382.8     .12       0  3788.7     .16       0  3871.4     .16       0
  5040.3     .07       0  5046.3     .16       0  7125.7     .05       0
  7625.2     .12       0
#XS Ineff= 2 , 0
          4798.3  275.84
Permanent Ineff=
       F       F
Bank Sta=4867.8,5306.1
XS Rating Curve= 0 ,0
Exp/Cntr=0.3,0.1

Type RM Length L Ch R = 1 ,89290   ,1264,1264,1264
BEGIN DESCRIPTION:
CATFISH CREEK 46.0
END DESCRIPTION:
XS GIS Cut Line= 3
      3682134.55     10689424.86      3680485.25     10688695.69
      3678299.59     10686960.17
#Sta/Elev= 30
  2818.9  312.38  2864.9   308.9  2908.6  305.48  2978.3  297.21    2987  299.86
  3021.2  294.11  3044.5  297.92  3097.6  296.44  3378.7  280.58  3411.6  278.82
  3439.2  281.55  3491.3  279.59  3880.5  265.69  4129.8  260.97  4964.2     254
  5068.6   252.6  5071.4   252.1  5074.6   252.6  5206.2  255.64  5590.7  253.06
  5975.2  257.53    6097  255.25  6138.6  258.16  6181.9  255.03  6736.3  254.99
  6787.4  259.12  6978.9  286.45  7002.3  286.28  7120.7  289.62  7413.1   309.6
#Mann= 10 ,-1 , 0
  2818.9     .05       0  2864.9     .16       0  2908.6     .05       0
  2978.3     .16       0  3378.7     .05       0  3411.6     .16       0
  3491.3     .16       0  5068.6     .07       0  5074.6     .16       0
  7002.3     .05       0
#XS Ineff= 2 , 0
         4464.77  275.49
Permanent Ineff=
       F       F
Bank Sta=4964.2,5206.2
XS Rating Curve= 0 ,0
Exp/Cntr=0.3,0.1

Type RM Length L Ch R = 1 ,88026   ,2266,2266,2266
BEGIN DESCRIPTION:
CATFISH CREEK 45.0
END DESCRIPTION:
XS GIS Cut Line= 3
      3681649.63     10687710.19      3680649.61     10687410.19
      3678649.57     10687010.18
#Sta/Elev= 30
  3956.3  292.68  3987.6  291.19  4004.6  288.27  4227.8     267  4295.6  258.87
  4324.2  254.99  4363.5   252.9  4488.8  252.57  4527.9  254.38  4572.3  252.66
  4841.1  253.62  5048.3  251.94  5051.1  251.44  5054.3  251.94  5102.3  256.96
  5153.3   258.5  5377.7  253.03  5428.7  253.37  5489.9  257.96    5551  254.86
  6601.4  254.69  6672.8  261.84  6703.4  262.99  6713.6  265.51  6754.4  269.09
  6772.6  273.83  6856.4  279.18  6897.2  283.97  6960.4  285.33    7040  287.84
#Mann= 7 ,-1 , 0
  3956.3     .05       0  4004.6     .16       0  4324.2     .16       0
  5048.3     .07       0  5054.3     .16       0  6772.6     .16       0
  6960.4     .05       0
Bank Sta=4295.6,5153.3
XS Rating Curve= 0 ,0
Exp/Cntr=0.3,0.1

Type RM Length L Ch R = 1 ,85760   ,1515,1515,1515
BEGIN DESCRIPTION:
CATFISH CREEK 44.0
END DESCRIPTION:
XS GIS Cut Line= 3
      3682514.22     10687332.64      3680973.45      10686421.2
      3678273.11     10686258.53
#Sta/Elev= 30
  2914.8  322.58  2994.7  319.61  3207.8  299.51  3295.6  292.54  3358.7  290.21
  3407.7  292.23  3481.5  290.78  3568.2  281.18  3635.6  273.57  3816.4  261.84
  3906.7  257.81    4168  251.92  4976.3  250.97  4979.1  250.47  4982.3  250.97
  5129.6  251.03  5149.6   252.4  5169.6  258.36  5189.7  254.72  5239.8  254.39
  6031.2   254.6  6141.4  269.01  6231.6  275.22  6649.6  274.28  6902.8  278.59
    7043  284.87  7163.3  296.02  7283.5  312.01  7350.6  316.41  7410.2  317.54
#Mann= 11 ,-1 , 0
  2914.8     .05       0  2994.7     .16       0  3207.8     .12       0
  3295.6     .16       0  3407.7     .12       0  3568.2     .16       0
  3816.4     .16       0  4976.3     .07       0  4982.3     .16       0
  6649.6     .16       0  7350.6     .12       0
Bank Sta=3906.7,5169.6
XS Rating Curve= 0 ,0
Exp/Cntr=0.3,0.1

Type RM Length L Ch R = 1 ,84245   ,588,588,588
BEGIN DESCRIPTION:
CATFISH CREEK 43.0
END DESCRIPTION:
XS GIS Cut Line= 3
      3682349.62     10686860.21      3681349.61     10685460.19
       3678349.6     10685460.19
#Sta/Elev= 30
  3272.7  321.38  3317.8  320.86  3444.8  305.23  3552.9  283.26  3665.2  270.89
  3781.5  259.45    3897  252.52  4995.7  250.22    5062  253.15  5363.2  257.98
  5663.2  254.29  5838.5  257.78  6210.2  250.14  6212.9  249.64  6216.2  250.14
  6533.2  261.51  6633.2   257.4  6723.2  259.93  6743.2  256.76  6823.2  257.21
  6873.2  260.92  6893.2  258.22  6923.2  263.26  7063.2  263.81  7193.2  269.51
  7543.2  270.53  7663.2  282.88  7723.2  293.89  7863.2  312.04  7993.2  315.24
#Mann= 8 ,-1 , 0
  3272.7     .05       0  3317.8     .16       0  3665.2     .16       0
    5062     .16       0  5838.5     .16       0  6210.2     .07       0
  6216.2     .16       0  7723.2     .16       0
#XS Ineff= 1 ,-1
 3460.23 5204.55  282.24
Permanent Ineff=
       F
Bank Sta=3781.5,5363.2
XS Rating Curve= 0 ,0
Exp/Cntr=0.3,0.1

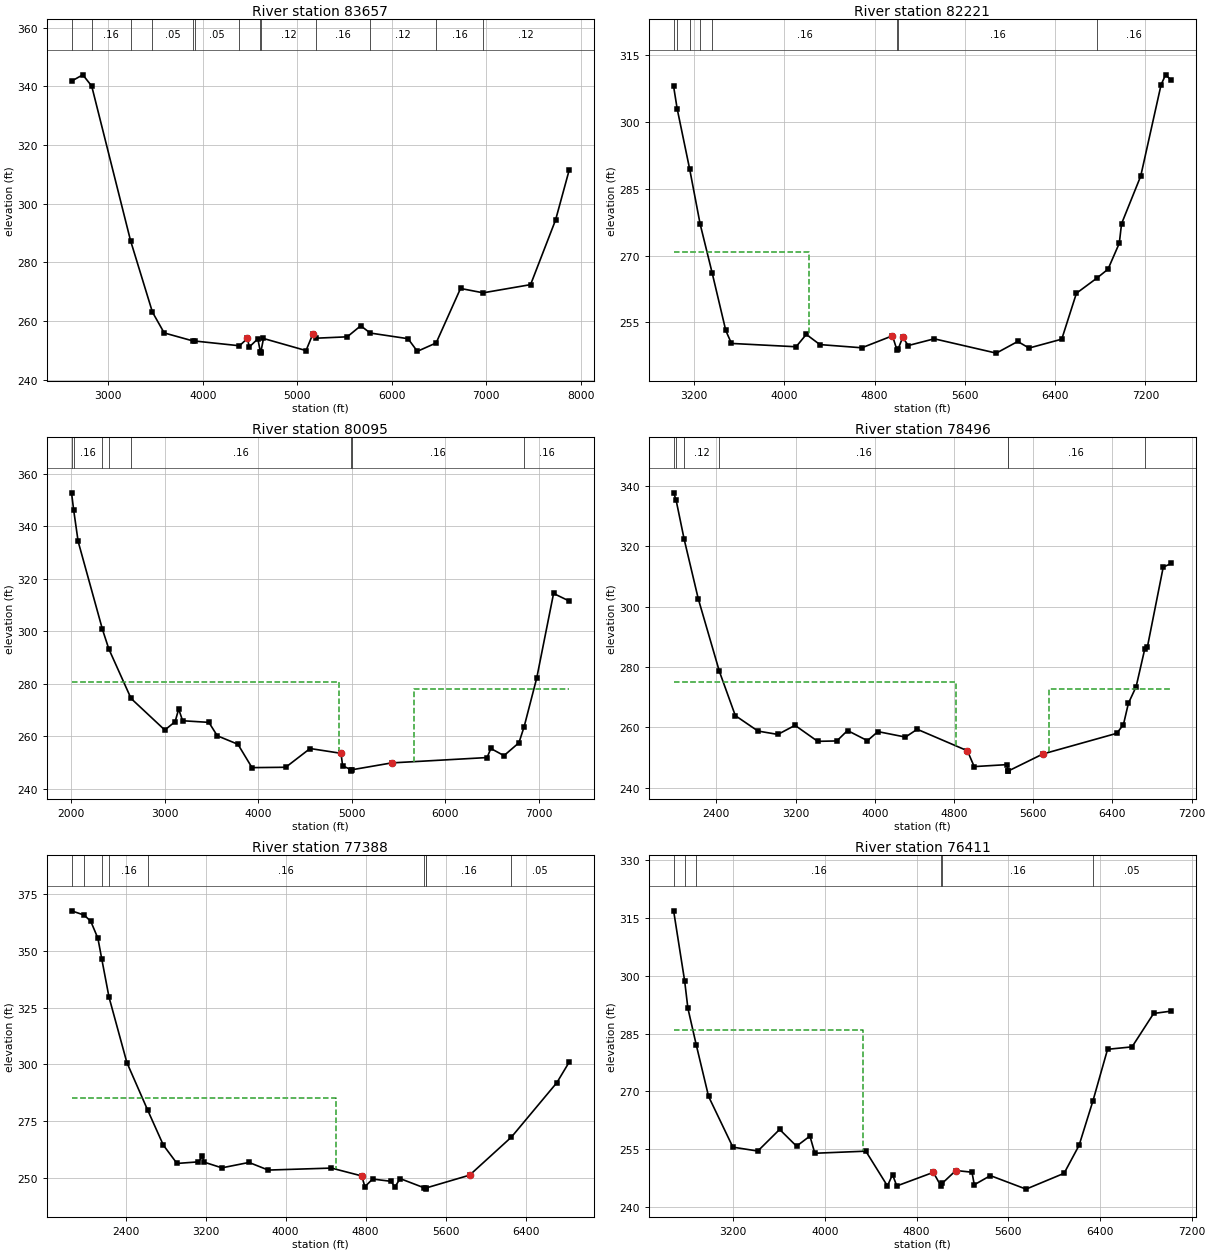
Type RM Length L Ch R = 1 ,83657   ,1436,1436,1436
BEGIN DESCRIPTION:
CATFISH CREEK 42.0
END DESCRIPTION:
XS GIS Cut Line= 3
      3683719.52     10684951.32      3681219.54     10685029.45
      3678498.16     10684547.67
#Sta/Elev= 30
  2611.9  341.74  2731.3  343.88  2825.2  340.05  3236.1  287.39  3467.6  263.03
  3592.3  255.92  3891.9  253.24  3918.3  253.16  4388.9  251.55  4472.7  254.03
  4492.7  251.14  4582.8  253.89  4609.8  249.54  4612.5  249.04  4615.8  249.54
  4642.8  254.03    5093  249.91  5163.8  255.45  5202.1  254.13  5529.4   254.6
  5671.6  258.36    5773  255.88  6172.2  253.96  6270.8  249.65  6469.8  252.51
  6727.8  271.08  6966.7  269.59  7469.1  272.38  7733.2  294.39  7876.8  311.33
#Mann= 13 ,-1 , 0
  2611.9     .05       0  2825.2     .16       0  3236.1     .12       0
  3467.6     .05       0  3891.9     .08       0  3918.3     .05       0
  4388.9     .12       0  4609.8     .07       0  4615.8     .12       0
  5202.1     .16       0    5773     .12       0  6469.8     .16       0
  6966.7     .12       0
Bank Sta=4472.7,5163.8
XS Rating Curve= 0 ,0
Exp/Cntr=0.3,0.1

Type RM Length L Ch R = 1 ,82221   ,2126,2126,2126
BEGIN DESCRIPTION:
CATFISH CREEK 41.0
END DESCRIPTION:
XS GIS Cut Line= 3
      3683149.56     10683810.19      3681149.61     10684010.19
      3678749.64     10684010.19
#Sta/Elev= 30
  3018.6  308.03  3050.1  303.01    3161  289.43  3253.4  277.13  3360.7  266.05
  3480.8  253.17  3531.1  250.26  4103.9  249.51  4194.4  252.29    4315     250
  4686.8  249.28  4958.2  251.98  4998.4  248.73  5008.4  248.98  5048.5  251.62
  5098.5  249.79  5328.5   251.3  5878.3  248.08  6068.5   250.7  6168.5  249.22
  6458.5  251.22  6588.5  261.54    6770  264.95  6868.5  266.95  6968.5  272.79
  6988.5  277.17  7158.5  287.89  7338.5  308.39  7378.5  310.65  7428.5  309.46
#Mann= 8 ,-1 , 0
  3018.6     .16       0  3050.1     .05       0    3161      .1       0
  3253.4     .05       0  3360.7     .16       0  4998.4     .07       0
  5008.4     .16       0    6770     .16       0
#XS Ineff= 2 , 0
         4215.91  270.74
Permanent Ineff=
       F       F
Bank Sta=4958.2,5048.5
XS Rating Curve= 0 ,0
Exp/Cntr=0.3,0.1

Type RM Length L Ch R = 1 ,80095   ,1599,1599,1599
BEGIN DESCRIPTION:
CATFISH CREEK 38.0
END DESCRIPTION:
XS GIS Cut Line= 3
      3683784.65     10682229.97       3680633.6     10682464.34
      3678473.42     10682347.22
#Sta/Elev= 30
  2001.6  352.77    2024   346.3  2071.9   334.3  2332.5  300.72  2400.3  293.31
  2638.4  274.44  2999.4  262.42  3109.7  265.61  3147.6  270.42  3189.9  265.96
  3470.7  265.34  3560.9  260.23  3781.5     257    3932   248.1    4293  248.24
  4553.7  255.38  4884.6  253.55  4901.4  248.83  4991.9  247.27  4994.6  246.77
  4997.9  247.27  5425.7   249.9  6447.2  251.94  6487.3  255.39    6628  252.67
  6787.7  257.57  6843.8  263.74    6978  282.21  7158.3  314.44  7324.7  311.58
#Mann= 8 ,-1 , 0
  2001.6     .12       0    2024     .16       0  2332.5     .12       0
  2400.3     .16       0  2638.4     .16       0  4991.9     .07       0
  4997.9     .16       0  6843.8     .16       0
#XS Ineff= 2 , 0
         4860.23  280.55 5668.18          278.15
Permanent Ineff=
       F       F
Bank Sta=4884.6,5425.7
XS Rating Curve= 0 ,0
Exp/Cntr=0.3,0.1

Type RM Length L Ch R = 1 ,78496   ,1108,1108,1108
BEGIN DESCRIPTION:
CATFISH CREEK 37.0
END DESCRIPTION:
XS GIS Cut Line= 3
       3683399.6     10681560.19      3680399.61     10681260.19
      3678399.64     10681460.19
#Sta/Elev= 30
  1967.9  337.69  1991.9  335.44  2074.7  322.26  2216.6  302.61  2430.2  278.51
    2591  263.88  2819.6  258.77  3020.6  257.65    3194  260.66  3422.6  255.36
  3616.1  255.49  3724.1  258.94  3925.1  255.58  4030.6  258.58  4309.5  256.77
  4427.6  259.36  4935.1  252.23    5003  246.99  5337.1  247.65  5344.4  245.49
  5344.9  245.49  5696.4  251.16  6442.6  258.01  6510.4  260.89  6560.7  267.98
  6638.6  273.46    6725  285.83  6751.6  286.49  6912.4  313.09  6992.8  314.28
#Mann= 7 ,-1 , 0
  1967.9     .12       0  1991.9     .16       0  2074.7     .12       0
  2430.2     .16       0  5344.4     .07       0  5344.9     .16       0
    6725     .16       0
#XS Ineff= 2 , 0
         4821.59  275.17  5762.5          272.54
Permanent Ineff=
       F       F
Bank Sta=4935.1,5696.4
XS Rating Curve= 0 ,0
Exp/Cntr=0.3,0.1

Type RM Length L Ch R = 1 ,77388   ,977,977,977
BEGIN DESCRIPTION:
CATFISH CREEK 36.0
END DESCRIPTION:
XS GIS Cut Line= 3
      3683649.61     10681410.19      3680649.61     10680510.19
      3678849.61     10680110.19
#Sta/Elev= 30
  1859.2  367.51  1985.9  365.63  2051.5  362.89  2122.8  355.44  2161.3  346.37
  2233.8  329.58  2412.5  300.81  2621.3  279.82  2777.1  264.52  2913.7  256.45
  3128.6  257.15  3166.8  259.56  3185.1  257.02  3362.6  254.52  3634.1  256.89
  3826.3  253.54  4458.8  254.41  4760.7  250.97  4792.9  246.24  4870.4  249.59
  5052.8   248.6  5093.7  246.14    5145  249.79  5379.3  245.84  5400.8  245.16
    5404  245.66  5840.3  251.31  6257.7  268.02  6712.3  291.95  6835.2  300.96
#Mann= 9 ,-1 , 0
  1859.2     .05       0  1985.9     .16       0  2161.3     .12       0
  2233.8     .16       0  2621.3     .16       0  5379.3     .07       0
    5404     .07       0    5404     .16       0  6257.7     .05       0
#XS Ineff= 2 , 0
         4507.95  285.03
Permanent Ineff=
       F       F
Bank Sta=4760.7,5840.3
XS Rating Curve= 0 ,0
Exp/Cntr=0.3,0.1

Type RM Length L Ch R = 1 ,76411   ,1376,1376,1376
BEGIN DESCRIPTION:
CATFISH CREEK 35.0
END DESCRIPTION:
XS GIS Cut Line= 3
      3683199.64     10681060.21      3681199.61     10679860.19
      3679199.61     10680060.19
#Sta/Elev= 30
    2679  316.78  2775.5  298.57  2803.4  291.58  2877.3  281.96  2984.2   268.7
  3196.1  255.58  3413.7  254.57  3604.2  260.17  3751.9  255.83  3868.6  258.45
  3911.3     254  4356.4  254.54  4544.9  245.54  4589.6  248.47  4626.6  245.53
  4945.3  249.05  5011.4  245.57  5021.5  246.17  5142.1  249.53  5282.8  249.09
  5302.9  245.84  5443.6  248.21  5754.9  244.71  6086.8  248.81  6217.4  256.04
    6338  267.52  6466.1  280.92  6679.7  281.55  6868.1   290.2  7021.4  290.81
#Mann= 6 ,-1 , 0
    2679      .1       0  2775.5     .05       0  2877.3     .16       0
  5011.4     .07       0  5021.5     .16       0    6338     .05       0
#XS Ineff= 2 , 0
         4335.23  285.86
Permanent Ineff=
       F       F
Bank Sta=4945.3,5142.1
XS Rating Curve= 0 ,0
Exp/Cntr=0.3,0.1