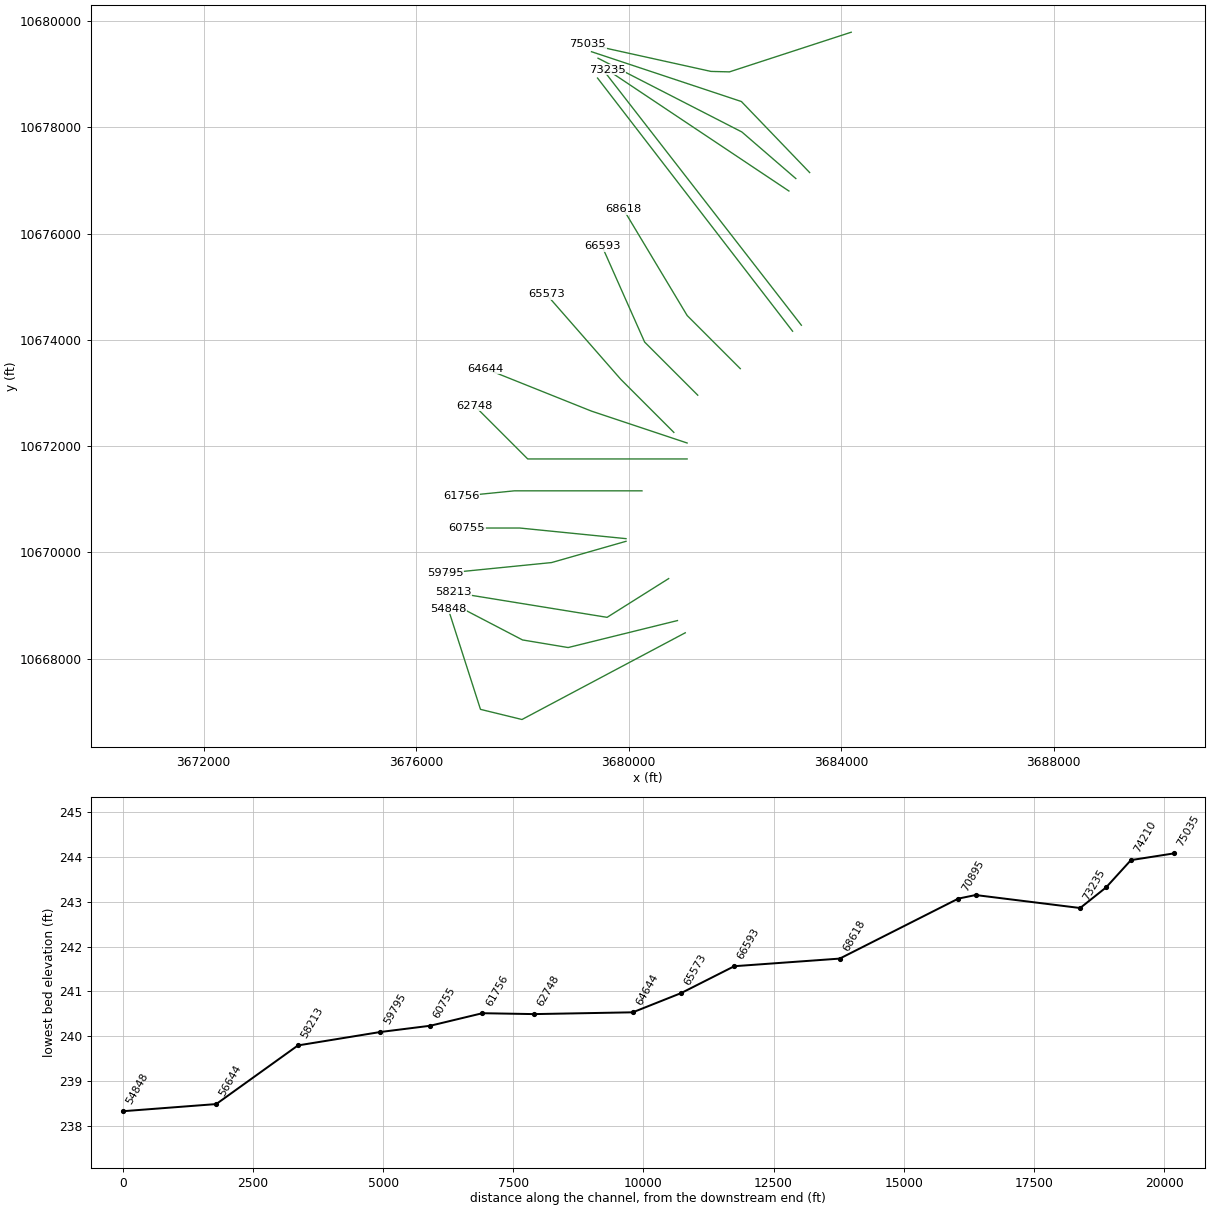
HEC-RAS study CATFISH CREEK.prj: CATFISH CREEK Base Level Engineering

--- CATFISH CREEK.g01 (geometry) --- (continued)

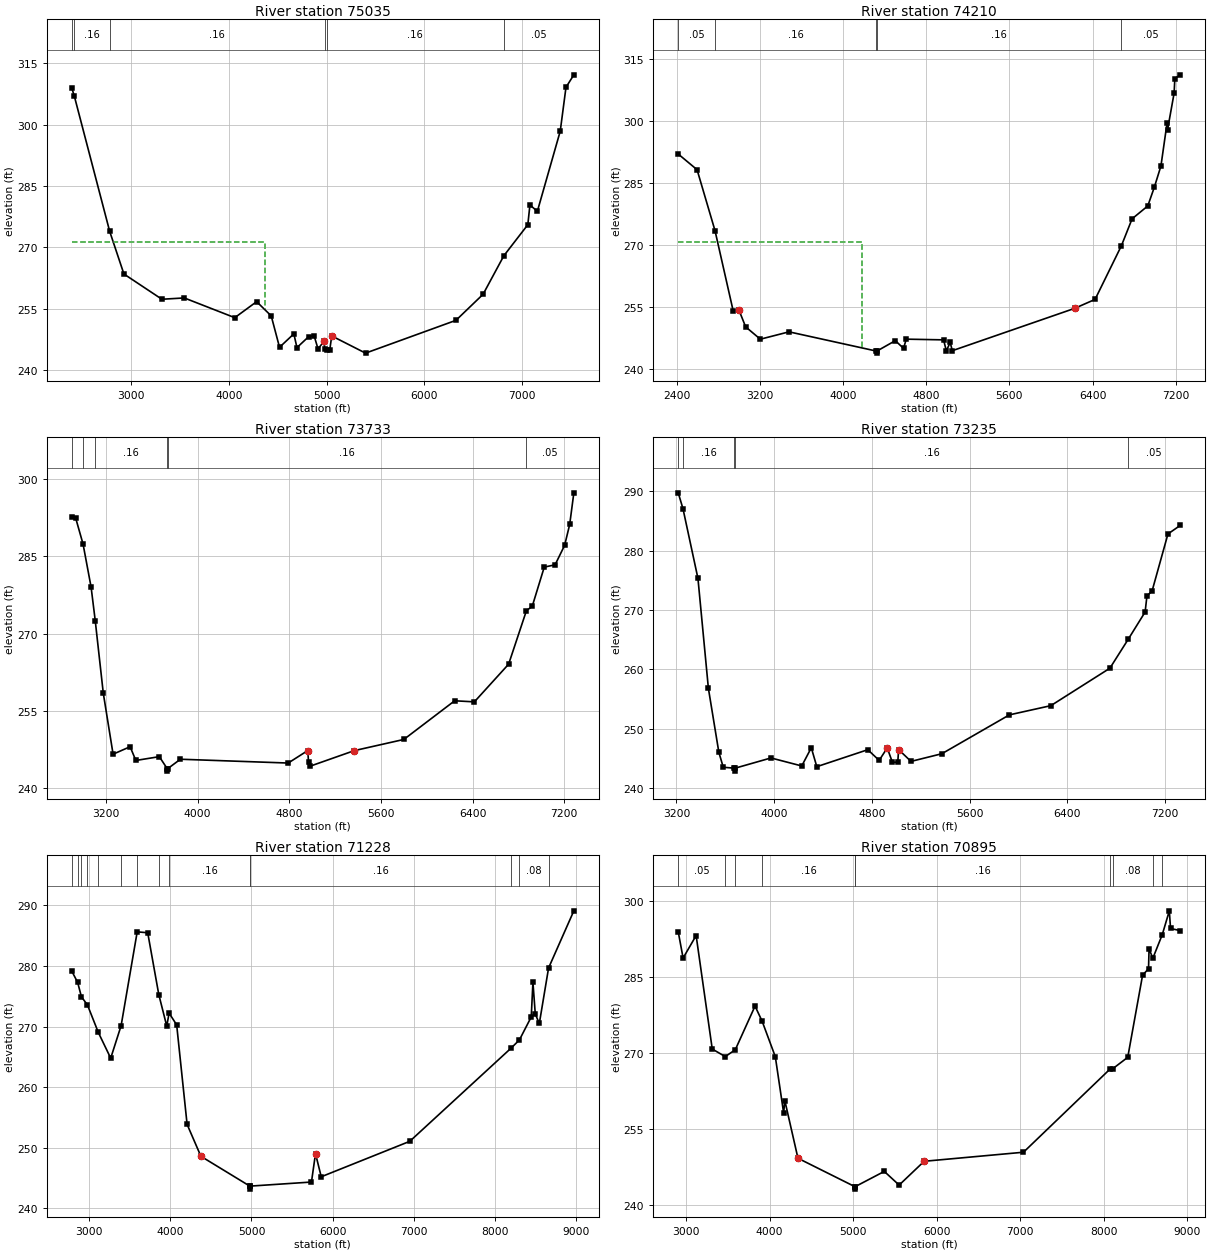
Type RM Length L Ch R = 1 ,75035   ,825,825,825
BEGIN DESCRIPTION:
CATFISH CREEK 34.0
END DESCRIPTION:
XS GIS Cut Line= 4
      3684187.71     10679791.44      3681896.05     10679044.92
      3681548.83      10679053.6      3679231.15     10679565.74
#Sta/Elev= 30
  2395.2  308.99  2421.5  306.98  2782.3  273.92  2928.1  263.45  3316.4  257.27
  3545.1  257.59  4061.1  252.76  4284.5  256.68  4433.5   253.2  4518.4  245.51
  4664.9   248.8  4696.5  245.43  4816.5  248.12  4871.8  248.33  4911.9  245.12
  4971.9  246.94  4981.9     245  5001.9  244.93  5031.9  244.87  5051.9  248.29
  5397.5  244.08  6321.6  252.11  6598.9  258.49    6811  267.92    7056  275.52
  7077.3  280.35  7153.5   278.8  7387.2  298.42    7446  309.16  7526.3  312.21
#Mann= 6 ,-1 , 0
  2395.2     .12       0  2421.5     .16       0  2782.3     .16       0
  4981.9     .07       0  5001.9     .16       0    6811     .05       0
#XS Ineff= 2 , 0
         4365.91  271.34
Permanent Ineff=
       F       F
Bank Sta=4971.9,5051.9
XS Rating Curve= 0 ,0
Exp/Cntr=0.3,0.1

Type RM Length L Ch R = 1 ,74210   ,477,477,477
BEGIN DESCRIPTION:
CATFISH CREEK 33.0
END DESCRIPTION:
XS GIS Cut Line= 3
      3683405.64     10677150.16      3682120.91     10678486.98
      3679299.69     10679424.49
#Sta/Elev= 30
    2416  292.09    2597   288.3  2769.4  273.57  2943.5  254.23  3000.1  254.32
  3063.9  250.29  3205.4   247.3  3481.2  249.08  4320.4  244.43  4323.1  243.93
  4326.4  244.43  4503.3  246.95  4581.9  245.08  4608.3  247.31  4967.1  247.14
  4993.5  244.48  5030.5  246.52  5051.2  244.52  6228.3  254.77  6423.6  256.93
  6676.9  269.92  6779.4  276.42  6930.2  279.53  6993.5  284.08  7056.8  289.21
  7114.9  299.48  7120.1  297.94  7183.5  306.84  7190.4  310.36    7243  311.25
#Mann= 5 ,-1 , 0
    2416     .05       0  2769.4     .16       0  4320.4     .07       0
  4326.4     .16       0  6676.9     .05       0
#XS Ineff= 2 , 0
         4185.23  270.74
Permanent Ineff=
       F       F
Bank Sta=3000.1,6228.3
XS Rating Curve= 0 ,0
Exp/Cntr=0.3,0.1

Type RM Length L Ch R = 1 ,73733   ,498,498,498
BEGIN DESCRIPTION:
CATFISH CREEK 32.0
END DESCRIPTION:
XS GIS Cut Line= 3
       3683145.2     10677037.34      3682129.59     10677914.06
      3679422.92     10679302.09
#Sta/Elev= 30
  2901.3  292.69  2935.2  292.48    3000  287.39  3070.1  279.05  3106.2  272.53
  3176.5  258.45    3262  246.61  3410.7  248.06  3460.6  245.39  3665.7  246.13
    3734  243.82  3736.8  243.32    3740  243.82    3850  245.63  4790.7  244.89
  4962.2  247.32  4968.2  245.07  4984.7   244.3  5367.8   247.3  5800.4  249.47
  6244.3  256.98  6416.3  256.77  6715.4  264.09  6871.1   274.5  6921.2   275.3
  7026.5  282.94  7120.9  283.38  7204.1  287.15  7248.5  291.21  7284.8  297.36
#Mann= 6 ,-1 , 0
  2901.3     .16       0    3000     .12       0  3106.2     .16       0
    3734     .07       0    3740     .16       0  6871.1     .05       0
Bank Sta=4962.2,5367.8
XS Rating Curve= 0 ,0
Exp/Cntr=0.3,0.1

Type RM Length L Ch R = 1 ,73235   ,2007,2007,2007
BEGIN DESCRIPTION:
CATFISH CREEK 31.0
END DESCRIPTION:
XS GIS Cut Line= 2
      3683014.97     10676802.97      3679595.41     10679085.57
#Sta/Elev= 30
  3214.8  289.75  3254.1  287.03  3376.2  275.33  3461.7  256.81  3547.4  246.03
  3583.5  243.51  3675.1  243.36  3677.9  242.86  3681.1  243.36    3974  245.08
  4226.3  243.73  4304.4   246.8  4349.5  243.61    4767  246.47  4860.1  244.67
  4926.2  246.77  4968.3  244.36  5012.7  244.35  5019.3  246.49  5120.9   244.5
  5373.4  245.79  5926.5  252.34    6266  253.89  6749.6   260.2  6900.3   265.1
    7038  269.67    7053  272.38    7095  273.21    7225  282.82  7326.2  284.27
#Mann= 5 ,-1 , 0
  3214.8     .05       0  3254.1     .16       0  3675.1     .07       0
  3681.1     .16       0  6900.3     .05       0
Bank Sta=4926.2,5019.3
XS Rating Curve= 0 ,0
Exp/Cntr=0.3,0.1

Type RM Length L Ch R = 1 ,71228   ,333,333,333
BEGIN DESCRIPTION:
CATFISH CREEK 30.0
END DESCRIPTION:
XS GIS Cut Line= 2
      3683249.35     10674276.94      3679455.96     10679164.08
#Sta/Elev= 30
  2785.9  279.15  2858.4  277.28    2905   274.9  2978.9  273.57    3113  269.02
  3265.7  264.77  3393.9  270.14  3592.1  285.63  3721.8  285.48  3858.2  275.27
  3956.3  270.07  3985.2  272.21  4078.5  270.27    4207  253.84  4377.2  248.57
  4979.7  243.65  4982.4  243.15  4985.7  243.65  5739.4  244.32  5789.2  249.01
  5859.8  245.19  6950.4  251.04  8196.8   266.4  8301.6  267.78  8447.5  271.58
  8468.3  277.31  8497.3  272.06  8547.1   270.5    8661  279.66  8972.5   289.1
#Mann= 14 ,-1 , 0
  2785.9     .05       0  2858.4     .12       0    2905     .08       0
  2978.9     .12       0    3113     .08       0  3393.9     .05       0
  3592.1     .08       0  3858.2     .05       0  3985.2     .16       0
  4979.7     .07       0  4985.7     .16       0  8196.8     .05       0
  8301.6     .08       0    8661     .05       0
Bank Sta=4377.2,5789.2
XS Rating Curve= 0 ,0
Exp/Cntr=0.3,0.1

Type RM Length L Ch R = 1 ,70895   ,2277,2277,2277
BEGIN DESCRIPTION:
CATFISH CREEK 29.0
END DESCRIPTION:
XS GIS Cut Line= 2
      3683084.45     10674164.06      3679413.57     10678928.39
#Sta/Elev= 30
  2905.2  293.91  2963.4  288.72  3119.6  293.17  3312.6  270.75  3468.6  269.25
  3588.8  270.61  3825.3  279.23  3910.5  276.23  4068.1  269.23  4167.8  258.13
  4182.3  260.54  4339.4  249.17    5020  243.57  5022.7  243.07    5026  243.57
  5373.6  246.57  5551.4  243.87  5851.1  248.57    7041  250.36  8076.1  266.76
  8109.3  266.84  8289.9  269.11  8467.5  285.32    8539  286.62  8545.4  290.54
  8590.6  288.68  8703.8  293.36  8788.2  298.05  8802.7  294.56  8919.7  294.14
#Mann= 10 ,-1 , 0
  2905.2     .05       0  3468.6     .05       0  3588.8     .12       0
  3910.5     .16       0    5020     .07       0    5026     .16       0
  8076.1     .16       0  8109.3     .08       0  8590.6     .05       0
  8703.8     .08       0
Bank Sta=4339.4,5851.1
XS Rating Curve= 0 ,0
Exp/Cntr=0.3,0.1

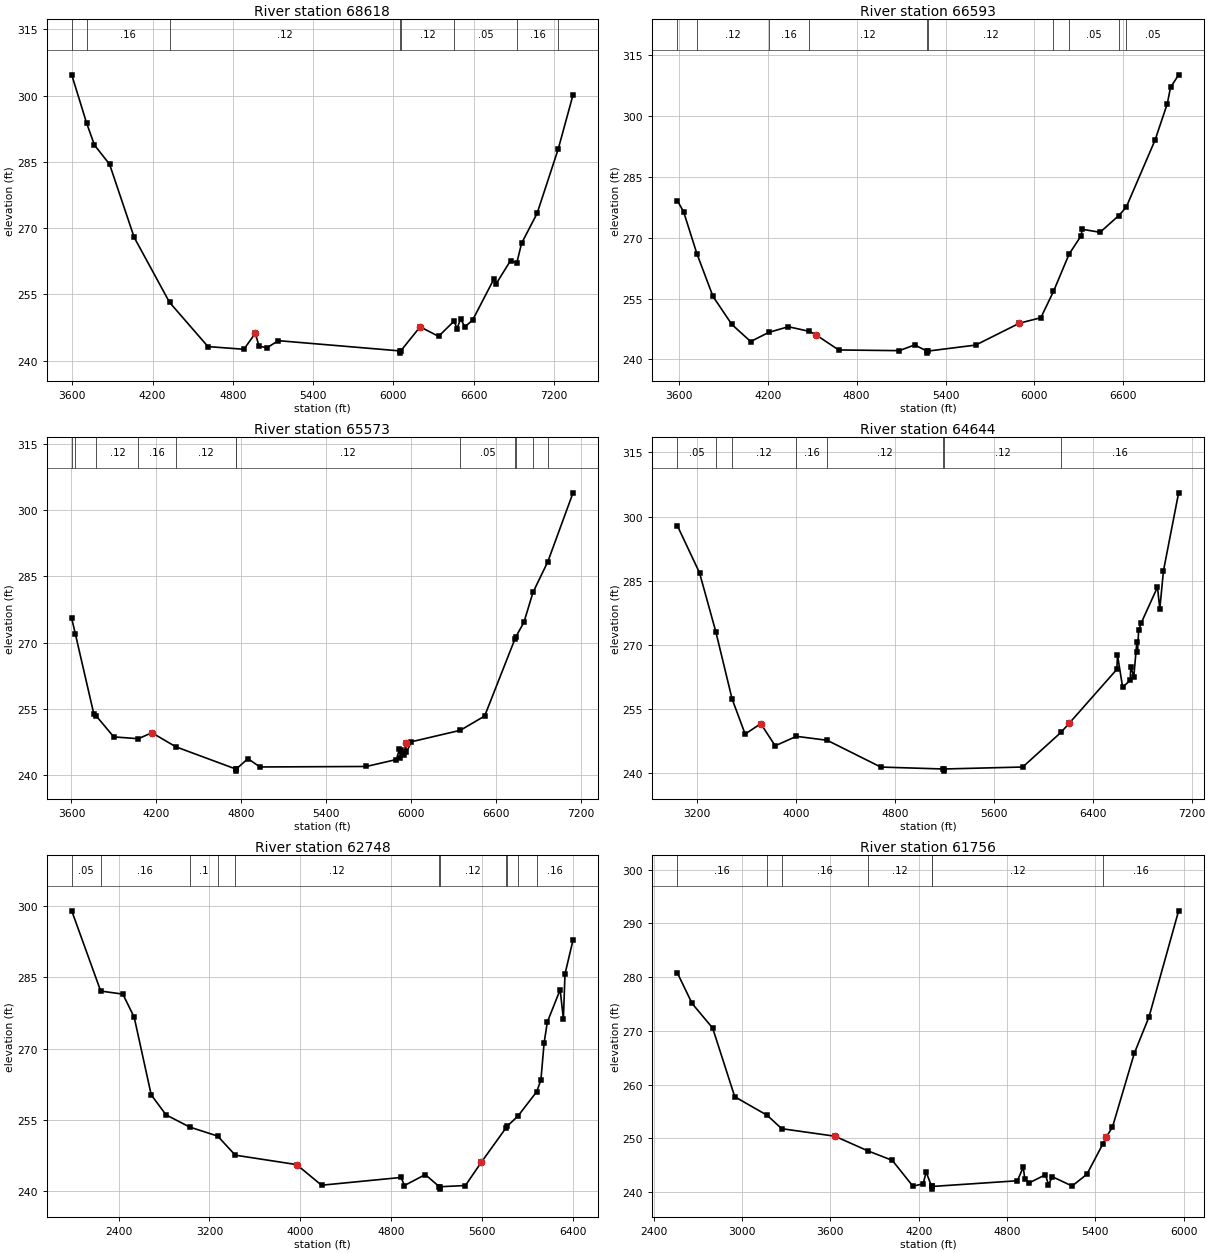
Type RM Length L Ch R = 1 ,68618   ,2025,2025,2025
BEGIN DESCRIPTION:
CATFISH CREEK 28.0
END DESCRIPTION:
XS GIS Cut Line= 3
      3682099.59     10673460.21      3681099.61     10674460.19
      3679899.59     10676460.22
#Sta/Elev= 30
  3596.3  304.72  3707.2  293.83    3766  288.83  3879.1  284.48    4063  267.93
  4327.4  253.22  4614.5  243.21  4883.2   242.6  4968.1  246.23  4996.3  243.32
  5055.2  242.94  5140.7  244.55  6049.3  242.23    6052  241.73  6055.3  242.23
    6200  247.68    6338  245.53  6454.1  248.98    6476  247.29  6503.2   249.5
  6534.3  247.65  6592.6  249.21    6752  258.53  6767.5  257.38  6876.4  262.69
  6922.5  262.11    6958  266.56  7074.6  273.38  7232.7  287.97  7342.9  300.18
#Mann= 8 ,-1 , 0
  3596.3     .05       0  3707.2     .16       0  4327.4     .12       0
  6049.3     .07       0  6055.3     .12       0  6454.1     .05       0
  6922.5     .16       0  7232.7     .05       0
Bank Sta=4968.1,6200
XS Rating Curve= 0 ,0
Exp/Cntr=0.3,0.1

Type RM Length L Ch R = 1 ,66593   ,1020,1020,1020
BEGIN DESCRIPTION:
CATFISH CREEK 27.0
END DESCRIPTION:
XS GIS Cut Line= 3
      3681299.61     10672960.19      3680299.61     10673960.19
       3679499.6     10675760.21
#Sta/Elev= 30
  3589.5   279.1  3631.9  276.34  3721.3  266.06  3829.9  255.54  3957.2  248.63
  4084.5  244.41  4206.2  246.66    4339  248.06  4481.2  246.91  4522.9  246.12
  4678.4  242.34  5087.8  242.17  5191.8  243.58  5274.3  242.06    5277  241.56
  5280.3  242.06  5603.5  243.54    5899  248.93  6043.3  250.27  6128.7  256.75
  6234.1  265.92  6316.2   270.5  6321.7  272.04  6443.4   271.3  6568.9  275.39
  6619.6  277.46  6814.1  293.96  6896.9  302.94  6918.8  306.94  6973.5  310.05
#Mann= 10 ,-1 , 0
  3589.5     .16       0  3721.3     .12       0  4206.2     .16       0
  4481.2     .12       0  5274.3     .07       0  5280.3     .12       0
  6128.7     .16       0  6234.1     .05       0  6568.9     .16       0
  6619.6     .05       0
Bank Sta=4522.9,5899
XS Rating Curve= 0 ,0
Exp/Cntr=0.3,0.1

Type RM Length L Ch R = 1 ,65573   ,929,929,929
BEGIN DESCRIPTION:
CATFISH CREEK 26.0
END DESCRIPTION:
XS GIS Cut Line= 3
      3680849.64     10672260.16      3679849.61     10673260.19
       3678449.6      10674860.2
#Sta/Elev= 30
  3601.7  275.48  3627.8  271.92  3757.3  253.94  3776.6  253.36  3898.7   248.7
  4072.4  248.29  4167.4  249.64  4337.8  246.45  4758.4  241.46  4761.1  240.96
  4764.4  241.46  4846.2  243.77  4931.1   241.9  5681.8  242.01  5894.4  243.58
  5916.2  245.93  5922.8  243.84  5930.4  245.84  5951.3  244.68  5958.9  247.23
  5965.5  245.26  6000.7   247.6    6346  250.19  6517.9  253.42    6733  270.94
  6736.9  271.26  6795.1   274.6    6859  281.36  6964.4  288.35    7142  303.89
#Mann= 12 ,-1 , 0
  3601.7     .05       0  3627.8     .16       0  3776.6     .12       0
  4072.4     .16       0  4337.8     .12       0  4758.4     .07       0
  4764.4     .12       0    6346     .05       0    6733     .16       0
  6736.9     .05       0    6859     .12       0  6964.4     .16       0
Bank Sta=4167.4,5958.9
XS Rating Curve= 0 ,0
Exp/Cntr=0.3,0.1

Type RM Length L Ch R = 1 ,64644   ,1896,1896,1896
BEGIN DESCRIPTION:
CATFISH CREEK 25.0
END DESCRIPTION:
XS GIS Cut Line= 3
       3681099.6     10672060.19      3679299.61     10672660.19
      3677299.63     10673460.18
#Sta/Elev= 30
    3043   297.9  3222.2  286.89  3354.5  273.05  3485.2  257.42  3591.1  249.19
  3717.6  251.62  3833.6  246.45  4005.4  248.66  4253.9  247.74  4687.4  241.48
  5191.8  241.03  5194.6  240.53  5197.8  241.03  5834.3  241.49  6143.4  249.58
  6211.3  251.75    6595  264.31  6600.3  267.67  6642.1   260.1  6702.7  261.77
    6708  264.96  6732.3  262.63  6756.5  270.61  6761.9  268.42  6771.3   273.4
  6792.9  275.21  6923.4  283.53  6942.3  278.45  6971.9  287.36  7094.4  305.57
#Mann= 8 ,-1 , 0
    3043     .05       0  3354.5     .16       0  3485.2     .12       0
  4005.4     .16       0  4253.9     .12       0  5191.8     .07       0
  5197.8     .12       0  6143.4     .16       0
Bank Sta=3717.6,6211.3
XS Rating Curve= 0 ,0
Exp/Cntr=0.3,0.1

Type RM Length L Ch R = 1 ,62748   ,992,992,992
BEGIN DESCRIPTION:
CATFISH CREEK 24.0
END DESCRIPTION:
XS GIS Cut Line= 3
      3681099.65     10671760.19      3678099.61     10671760.19
      3677099.57     10672760.22
#Sta/Elev= 30
    1988   298.9    2243  282.06    2438  281.42    2538  276.57    2688  260.27
    2818  256.09  3025.3  253.53  3273.4  251.62  3427.9  247.62    3968  245.64
    4188  241.31    4888  242.94    4918  241.25  5101.2  243.54  5225.5  240.99
  5228.2  240.49  5231.5  240.99  5454.7  241.25  5596.1  246.17  5813.7   253.4
  5823.5  253.72  5916.6   255.8  6081.9  260.92  6119.4  263.37  6147.7  271.17
    6176  275.55  6289.1  282.35  6317.4  276.17  6331.5  285.63  6402.3  292.78
#Mann= 11 ,-1 , 0
    1988     .05       0    2243     .16       0  3025.3      .1       0
  3273.4     .16       0  3427.9     .12       0  5225.5     .07       0
  5231.5     .12       0  5813.7      .1       0  5823.5     .16       0
  5916.6      .1       0  6081.9     .16       0
Bank Sta=3968,5596.1
XS Rating Curve= 0 ,0
Exp/Cntr=0.3,0.1

Type RM Length L Ch R = 1 ,61756   ,1001,1001,1001
BEGIN DESCRIPTION:
CATFISH CREEK 23.0
END DESCRIPTION:
XS GIS Cut Line= 3
       3680249.6     10671160.19      3677849.61     10671160.19
      3676849.59     10671060.19
#Sta/Elev= 30
  2560.2   280.8  2660.2  275.11  2800.2  270.51  2950.2  257.72  3170.2  254.27
  3269.1  251.77  3630.2  250.37  3855.3  247.63  4020.2  245.87  4160.2  241.06
  4230.2   241.5  4250.2   243.7  4287.2  241.01  4289.9  240.51  4293.2  241.01
  4870.2  242.07  4910.2  244.62  4920.2  242.36  4950.2  241.68  5060.7  243.19
  5080.8  241.36  5108.4  242.81  5241.6  241.09  5342.1  243.28  5450.3  248.91
  5472.7  250.16  5515.5  252.04  5663.7  265.78  5764.2  272.61  5965.2  292.36
#Mann= 7 ,-1 , 0
  2560.2     .16       0  3170.2     .12       0  3269.1     .16       0
  3855.3     .12       0  4287.2     .07       0  4293.2     .12       0
  5450.3     .16       0
Bank Sta=3630.2,5472.7
XS Rating Curve= 0 ,0
Exp/Cntr=0.3,0.1

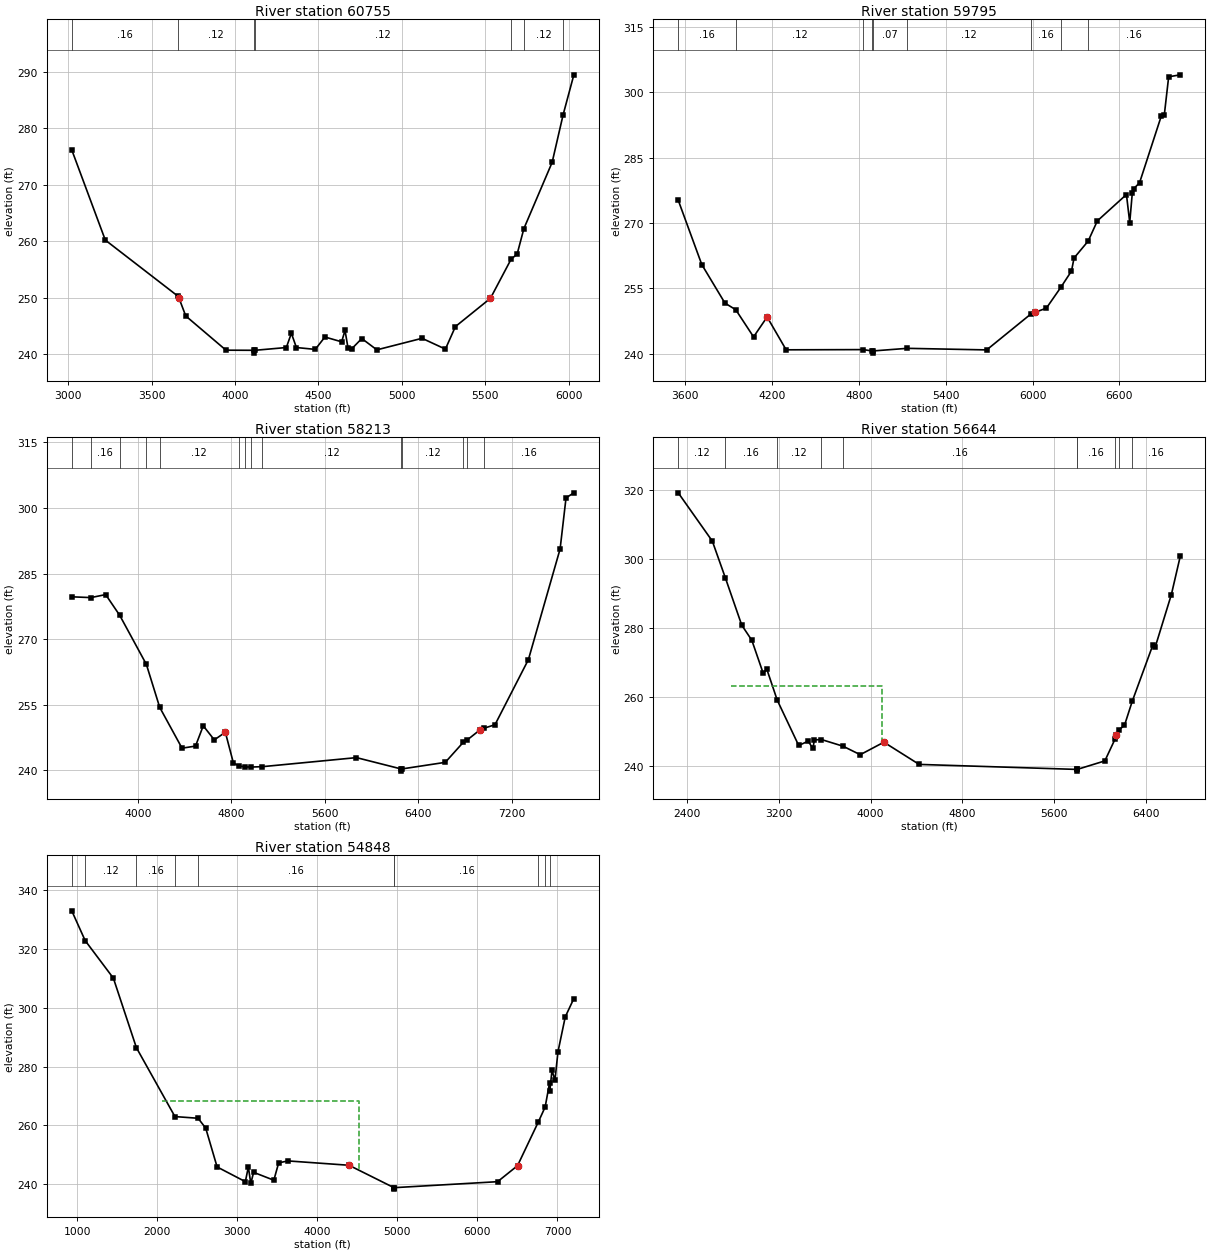
Type RM Length L Ch R = 1 ,60755   ,960,960,960
BEGIN DESCRIPTION:
CATFISH CREEK 22.0
END DESCRIPTION:
XS GIS Cut Line= 3
      3679949.56     10670260.19      3677949.61     10670460.19
      3676949.64     10670460.19
#Sta/Elev= 30
  3021.9  276.15  3222.9  260.21  3658.6  250.29    3665  249.93  3705.2   246.8
  3946.4  240.75  4114.3  240.73    4117  240.23  4120.3  240.73  4308.2  241.22
  4338.4  243.74  4368.5  241.22  4481.6  240.89  4539.4  243.08  4639.9  242.23
    4660  244.26  4677.6  241.19  4700.2  240.99  4760.5  242.81  4850.9  240.81
  5121.8  242.85  5261.8  240.94  5321.8  244.92  5531.8  249.92  5655.8  256.84
  5691.8  257.73  5732.3  262.24  5901.8  273.96  5967.5  282.36  6031.8  289.42
#Mann= 7 ,-1 , 0
  3021.9     .16       0  3658.6     .12       0  4114.3     .07       0
  4120.3     .12       0  5655.8     .16       0  5732.3     .12       0
  5967.5     .16       0
Bank Sta=3665,5531.8
XS Rating Curve= 0 ,0
Exp/Cntr=0.3,0.1

Type RM Length L Ch R = 1 ,59795   ,1582,1582,1582
BEGIN DESCRIPTION:
CATFISH CREEK 21.0
END DESCRIPTION:
XS GIS Cut Line= 3
      3679949.61     10670210.19      3678549.61     10669810.19
      3676549.61     10669610.19
#Sta/Elev= 30
    3554   275.2  3716.5  260.43  3876.4  251.58  3951.2  250.05    4074  243.82
  4167.6  248.39  4298.9  240.85  4830.8   240.9  4892.6  240.59  4895.4  240.09
  4898.6  240.59  5134.5  241.19  5683.4  240.83  5986.4  249.02    6015  249.43
  6095.4  250.42  6195.7  255.22  6268.8  258.94  6286.4  261.93  6383.8  265.81
  6447.2  270.45  6648.2  276.51  6670.8  270.08  6688.4   276.8  6698.4  277.85
  6738.6   279.2  6889.4  294.61  6909.5  294.78  6939.6  303.54    7020  303.99
#Mann= 9 ,-1 , 0
    3554     .16       0  3951.2     .12       0  4830.8     .07       0
  4892.6     .07       0  4898.6     .07       0  5134.5     .12       0
  5986.4     .16       0  6195.7     .12       0  6383.8     .16       0
Bank Sta=4167.6,6015
XS Rating Curve= 0 ,0
Exp/Cntr=0.3,0.1

Type RM Length L Ch R = 1 ,58213   ,1569,1569,1569
BEGIN DESCRIPTION:
CATFISH CREEK 20.0
END DESCRIPTION:
XS GIS Cut Line= 3
      3680751.92     10669508.44       3679593.1     10668779.29
      3676703.58     10669247.86
#Sta/Elev= 30
  3433.6  279.67  3597.2  279.49  3723.6  280.18  3843.7  275.44    4072  264.21
  4186.1  254.38  4377.1  245.04  4492.5  245.52  4558.7  250.16  4653.3  246.94
  4747.8  248.68  4816.4  241.68  4862.9  240.98  4914.1  240.77  4963.8  240.72
  5064.7  240.81    5870  242.88  6251.9  240.29  6254.7  239.79  6257.9  240.29
  6629.8   241.8  6783.4  246.37  6815.6  246.88  6923.6  249.16    6960  249.59
  7055.3  250.41  7341.2  265.31  7612.5  290.63  7663.1  302.31    7730  303.46
#Mann= 14 ,-1 , 0
  3433.6     .12       0  3597.2     .16       0  3843.7     .05       0
    4072     .16       0  4186.1     .12       0  4862.9     .07       0
  4914.1     .05       0  4963.8     .07       0  5064.7     .12       0
  6251.9     .07       0  6257.9     .12       0  6783.4     .16       0
  6815.6     .12       0    6960     .16       0
Bank Sta=4747.8,6923.6
XS Rating Curve= 0 ,0
Exp/Cntr=0.3,0.1

Type RM Length L Ch R = 1 ,56644   ,1796,1796,1796
BEGIN DESCRIPTION:
Mapping XS 1ea8d9fd
END DESCRIPTION:
XS GIS Cut Line= 4
      3680917.72     10668718.52      3678860.46     10668210.72
      3678001.09     10668353.95      3676777.13     10668991.97
#Sta/Elev= 30
  2325.6  319.27  2622.4  305.25  2736.4  294.53  2878.3  280.87  2966.4  276.45
  3065.3  266.87  3096.2  268.12  3187.2   259.1  3374.3  245.92  3456.7  247.18
  3497.9  245.07  3510.6  247.54  3572.4  247.65  3759.8  245.72  3909.9  243.25
  4115.9  246.88  4422.8  240.43  5792.6  238.98  5795.4  238.48  5798.6  238.98
  6039.2  241.45  6128.5  247.82  6137.8  249.03  6158.6  250.41  6209.8  251.74
  6277.2  258.71  6456.5  275.04    6479  274.65  6618.3  289.75  6696.1  300.92
#Mann= 10 ,-1 , 0
  2325.6     .12       0  2736.4     .16       0  3187.2     .12       0
  3572.4     .16       0  3759.8     .16       0  5792.6     .07       0
  5798.6     .16       0  6128.5     .16       0  6158.6     .12       0
  6277.2     .16       0
#XS Ineff= 1 ,-1
 2784.09 4096.59  263.05
Permanent Ineff=
       F
Bank Sta=4115.9,6137.8
XS Rating Curve= 0 ,0
Exp/Cntr=0.3,0.1

Type RM Length L Ch R = 1 ,54848   ,2808,2808,2808
BEGIN DESCRIPTION:
CATFISH CREEK 19.0
END DESCRIPTION:
XS GIS Cut Line= 4
      3681064.49     10668488.51      3677991.54     10666856.55
      3677210.29     10667047.52      3676602.65     10668939.89
#Sta/Elev= 30
   933.2  332.92  1100.5   322.8  1452.9  310.03  1740.4   286.4  2221.7  262.98
    2511  262.41  2606.1  259.06  2748.6  245.86  3101.4  240.86  3138.6  245.85
  3169.3  240.28  3204.6  244.03  3457.1  241.35  3517.4  247.25  3633.5  247.91
    4396  246.43  4957.2  238.82    4960  238.32  4963.2  238.82  6251.8  240.85
    6501  246.29  6762.3  261.24    6846  266.23  6900.9  274.41  6904.5  271.69
  6931.3   278.7  6968.7  275.38  7006.1     285  7097.1  296.87  7204.4  303.11
#Mann= 10 ,-1 , 0
   933.2     .16       0  1100.5     .12       0  1740.4     .16       0
  2221.7     .16       0    2511     .16       0  4957.2     .07       0
  4963.2     .16       0  6762.3     .16       0    6846     .12       0
  6900.9     .16       0
#XS Ineff= 1 ,-1
 2054.55 4522.73268.3604
Permanent Ineff=
       F
Bank Sta=4396,6501
XS Rating Curve= 0 ,0
Exp/Cntr=0.3,0.1