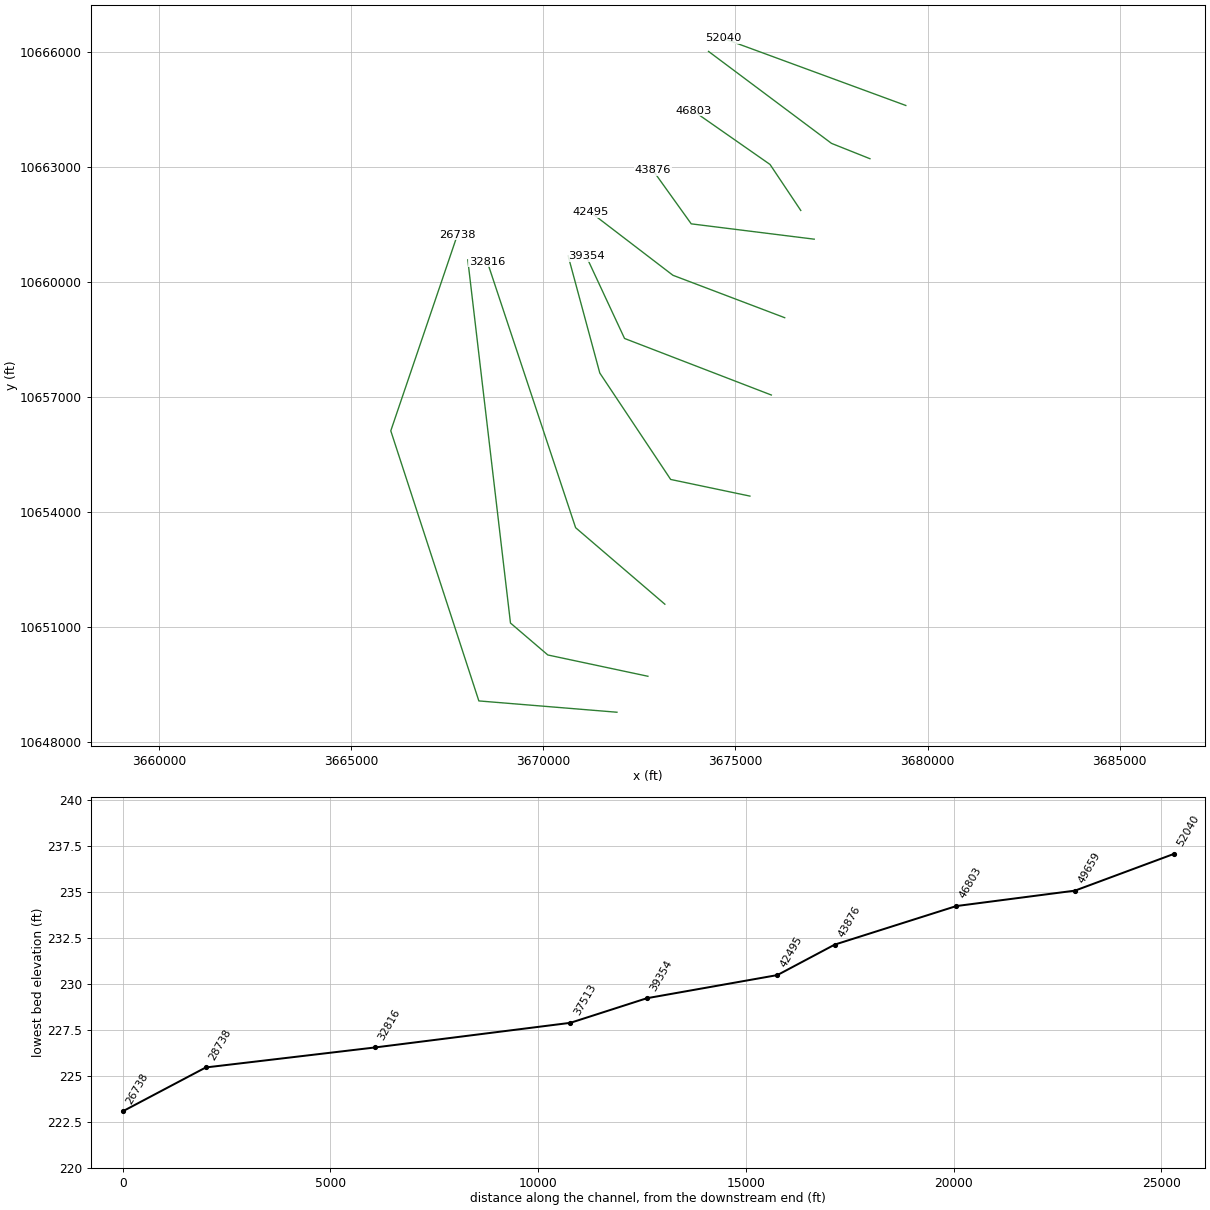
HEC-RAS study CATFISH CREEK.prj: CATFISH CREEK Base Level Engineering

--- CATFISH CREEK.g01 (geometry) --- (continued)

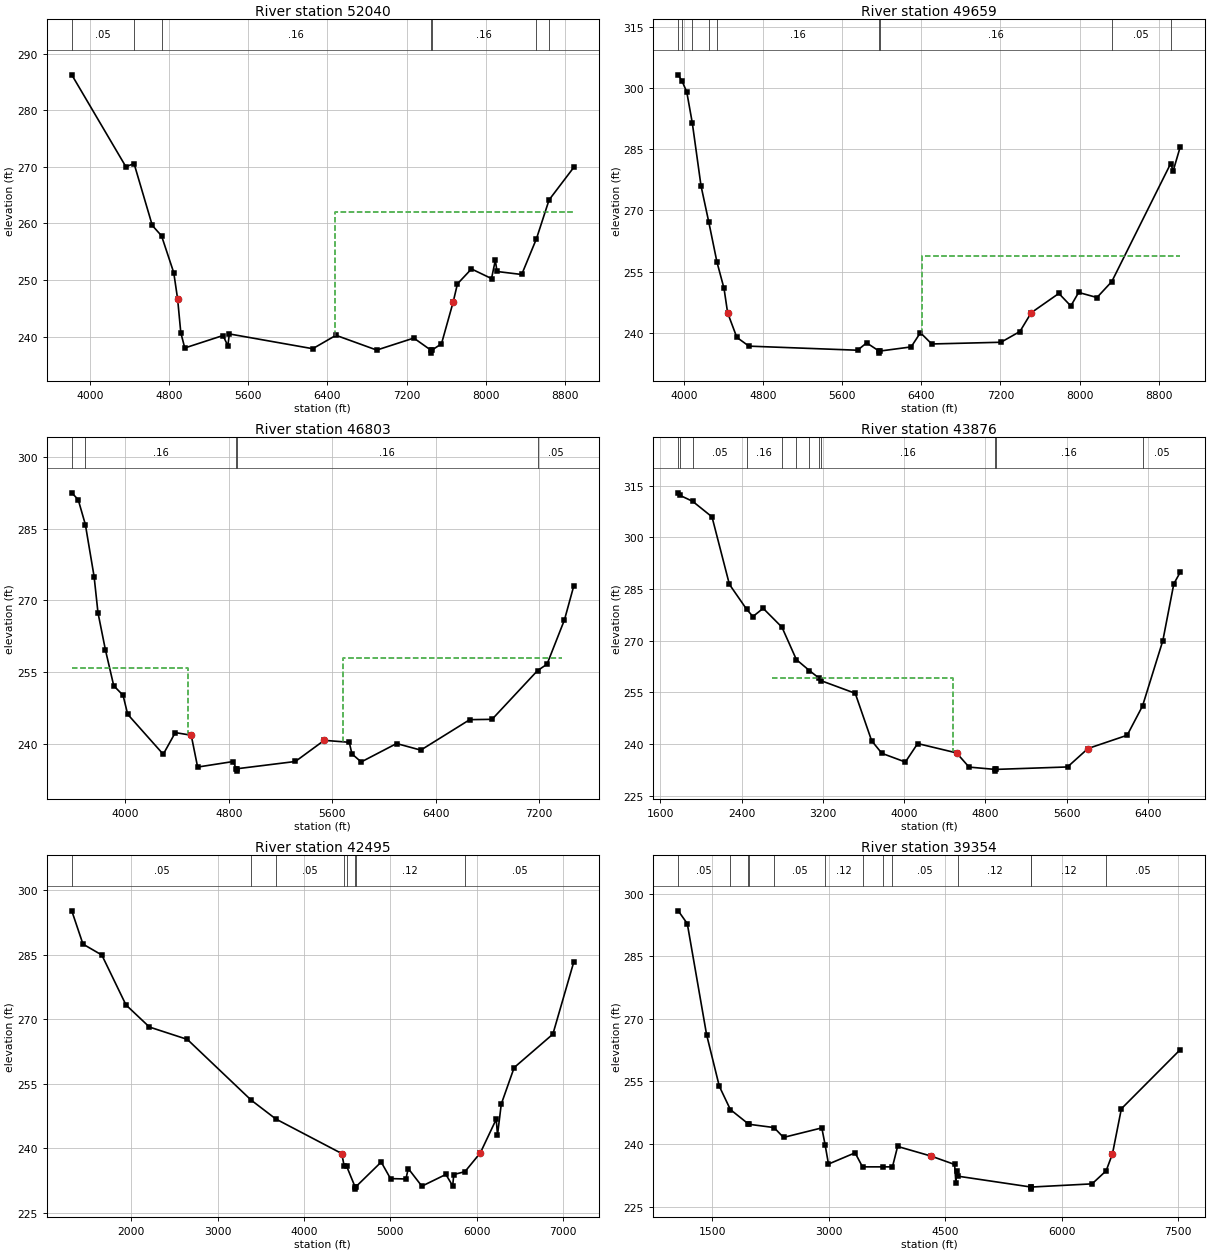
Type RM Length L Ch R = 1 ,52040   ,2381,2381,2381
BEGIN DESCRIPTION:
CATFISH CREEK 18.0
END DESCRIPTION:
XS GIS Cut Line= 2
       3679432.5     10664599.61      3674675.58     10666353.07
#Sta/Elev= 30
  3818.1  286.25  4364.7  270.01    4447  270.58  4631.2  259.64  4724.5  257.81
  4847.9   251.3    4887  246.65  4918.9  240.72    4959     238  5345.2   240.2
  5394.4  238.38  5409.2  240.48  6251.1  237.87  6485.6  240.24  6897.5  237.63
  7271.9  239.75  7446.3  237.59    7449  237.09  7452.3  237.59  7551.4  238.74
  7668.6  246.07  7712.6  249.33  7854.1  251.96  8056.6  250.26  8094.9  253.49
  8112.1  251.51  8361.4  250.98  8510.6  257.31  8637.9  264.16  8887.9  269.92
#Mann= 7 ,-1 , 0
  3818.1     .05       0    4447     .16       0  4724.5     .16       0
  7446.3     .07       0  7452.3     .16       0  8510.6     .16       0
  8637.9     .12       0
#XS Ineff= 2 , 0
                         6473.36          262.04
Permanent Ineff=
       F       F
Bank Sta=4887,7668.6
XS Rating Curve= 0 ,0
Exp/Cntr=0.3,0.1

Type RM Length L Ch R = 1 ,49659   ,2856,2856,2856
BEGIN DESCRIPTION:
CATFISH CREEK 17.0
END DESCRIPTION:
XS GIS Cut Line= 3
      3678499.56     10663210.21      3677499.61     10663610.19
       3674299.6      10666010.2
#Sta/Elev= 30
  3942.2   303.2  3981.4  301.62  4028.3  299.02  4084.2  291.46  4172.4  276.05
    4252  267.06  4333.9  257.36  4405.3  250.91  4441.6  244.96  4534.5  238.95
    4657   236.8  5755.6   235.8  5847.3   237.6  5973.5  235.59  5976.2  235.09
  5979.5  235.59  6297.3  236.61  6391.1  240.09  6505.6  237.33  7205.6  237.75
  7397.3  240.38  7511.9  244.98  7791.1   249.7  7911.9  246.63  7991.1  249.94
  8176.5   248.7  8326.5  252.61  8921.5  281.47  8947.3  279.71  9019.2  285.64
#Mann= 9 ,-1 , 0
  3942.2     .05       0  3981.4     .16       0  4084.2     .12       0
    4252     .16       0  4333.9     .16       0  5973.5     .07       0
  5979.5     .16       0  8326.5     .05       0  8921.5     .08       0
#XS Ineff= 2 , 0
                         6408.52          258.84
Permanent Ineff=
       F       F
Bank Sta=4441.6,7511.9
XS Rating Curve= 0 ,0
Exp/Cntr=0.3,0.1

Type RM Length L Ch R = 1 ,46803   ,2927,2927,2927
BEGIN DESCRIPTION:
CATFISH CREEK 15.0
END DESCRIPTION:
XS GIS Cut Line= 3
       3676699.6     10661860.21      3675899.61     10663060.19
      3673899.61     10664460.18
#Sta/Elev= 30
    3586  292.54  3635.6  291.12  3691.1   285.9  3758.7  275.01  3788.8  267.42
  3845.9  259.69  3910.5  252.14  3982.6  250.14  4018.6  246.15  4293.6  237.78
  4386.7  242.32  4509.9  241.77  4559.5   235.1  4834.4  236.26  4858.4  234.75
  4861.2  234.25  4864.4  234.75  5315.5  236.27  5538.7   240.7  5732.3  240.29
  5753.2  237.86  5824.7  236.17  6098.4  240.03  6285.5  238.65  6664.3  245.03
  6836.9   245.1  7188.8  255.31    7262  256.64  7396.7  265.92  7469.5  273.09
#Mann= 5 ,-1 , 0
    3586     .16       0  3691.1     .16       0  4858.4     .07       0
  4864.4     .16       0  7188.8     .05       0
#XS Ineff= 2 ,-1
 3536.93 4488.64  255.76 5681.25 7377.31257.9597
Permanent Ineff=
       F       F
Bank Sta=4509.9,5538.7
XS Rating Curve= 0 ,0
Exp/Cntr=0.3,0.1

Type RM Length L Ch R = 1 ,43876   ,1381,1381,1381
BEGIN DESCRIPTION:
CATFISH CREEK 13.0
END DESCRIPTION:
XS GIS Cut Line= 3
      3677049.66     10661110.18      3673849.61     10661510.19
      3672849.62     10662910.17
#Sta/Elev= 30
  1775.2  312.91  1794.7  312.14    1917  310.45  2107.8  305.93  2279.1  286.35
  2449.1  279.11  2510.9  277.01  2611.7  279.39  2796.8  273.92    2939  264.51
  3066.3  261.35  3166.5  259.03  3183.6  258.38  3518.7  254.73    3680  240.98
  3780.7  237.32  4012.5  234.79  4133.5  240.15  4516.4  237.44  4639.9  233.32
  4896.4  232.65  4899.1  232.15  4902.4  232.65  5609.7  233.36  5811.2  238.71
  6197.1  242.56  6348.3  251.04  6548.6  270.03  6656.7  286.51  6720.6  289.91
#Mann= 12 ,-1 , 0
  1775.2     .05       0  1794.7     .16       0    1917     .05       0
  2449.1     .16       0  2796.8     .12       0    2939     .16       0
  3066.3     .12       0  3166.5     .16       0  3183.6     .16       0
  4896.4     .07       0  4902.4     .16       0  6348.3     .05       0
#XS Ineff= 1 ,-1
 2697.73 4480.68   259.3
Permanent Ineff=
       F
Bank Sta=4516.4,5811.2
XS Rating Curve= 0 ,0
Exp/Cntr=0.3,0.1

Type RM Length L Ch R = 1 ,42495   ,3141,3141,3141
BEGIN DESCRIPTION:
CATFISH CREEK 11.0
END DESCRIPTION:
XS GIS Cut Line= 3
      3676280.77     10659061.48       3673372.8     10660168.24
      3671226.01     10661816.29
#Sta/Elev= 30
  1309.1  295.26  1438.7  287.52  1657.5  284.97  1937.2  273.36  2209.1  268.21
  2647.8  265.34  3388.1   251.2  3674.1  246.81  4437.7  238.77  4466.2  235.78
  4493.6  235.84  4592.5  230.99  4595.2  230.49  4598.5  230.99  4894.6  236.79
  5002.5  232.94    5181  232.85  5208.2  235.28  5365.9  231.18  5644.2  233.91
  5723.1  231.24  5735.7  233.89  5864.8  234.55    6043  238.91  6227.8  246.76
  6242.3  243.08  6285.9  250.27  6435.4  258.78    6884  266.56    7127  283.41
#Mann= 8 ,-1 , 0
  1309.1     .05       0  3388.1     .08       0  3674.1     .05       0
  4466.2     .07       0  4493.6     .12       0  4592.5     .07       0
  4598.5     .12       0  5864.8     .05       0
Bank Sta=4437.7,6043
XS Rating Curve= 0 ,0
Exp/Cntr=0.3,0.1

Type RM Length L Ch R = 1 ,39354   ,1841,1841,1841
BEGIN DESCRIPTION:
CATFISH CREEK 10.0
END DESCRIPTION:
XS GIS Cut Line= 3
      3675933.58     10657043.23      3672114.12     10658518.93
      3671116.35     10660666.32
#Sta/Elev= 30
  1062.2  295.86  1178.8  292.79    1427  266.23  1590.6  253.87  1733.1  248.28
  1966.4  244.82  1971.5  244.76  2294.9  243.97  2417.2  241.61  2910.4  243.89
    2952   239.9  2996.1  235.23  3338.4  237.92  3434.2  234.56  3697.5  234.56
  3819.5  234.56  3885.9  239.45  4317.1  237.14  4619.8  235.13  4636.4  230.67
  4644.4  233.68  4661.9  232.33  5602.7  229.73  5605.4  229.23  5608.7  229.73
  6388.7  230.49  6569.9  233.61  6651.5  237.69    6766  248.47  7524.7  262.64
#Mann= 13 ,-1 , 0
  1062.2     .05       0  1733.1     .12       0  1966.4     .05       0
  1971.5     .12       0  2294.9     .05       0    2952     .12       0
  3434.2     .07       0  3697.5     .12       0  3819.5     .05       0
  4661.9     .12       0  5602.7     .07       0  5608.7     .12       0
  6569.9     .05       0
Bank Sta=4317.1,6651.5
XS Rating Curve= 0 ,0
Exp/Cntr=0.3,0.1

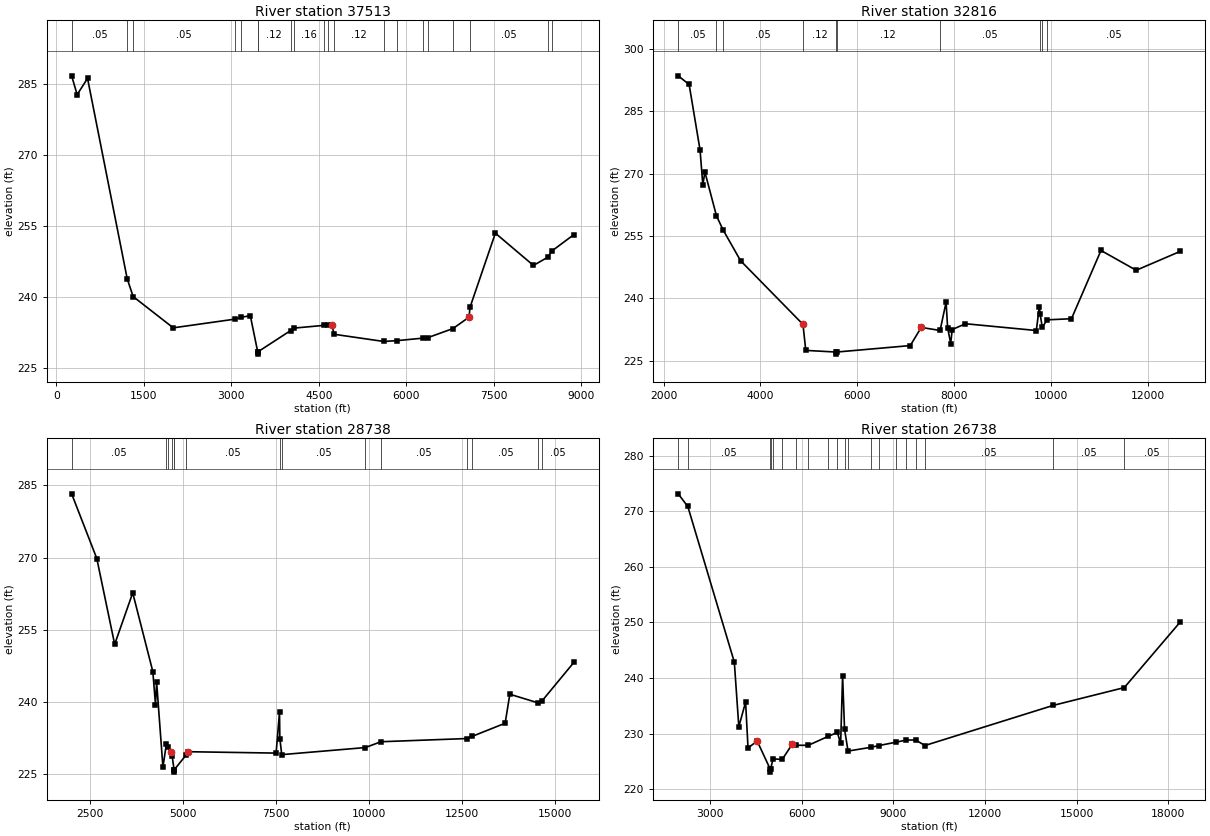
Type RM Length L Ch R = 1 ,37513   ,4697,4697,4697
BEGIN DESCRIPTION:
Mapping XS 1c516730
END DESCRIPTION:
XS GIS Cut Line= 4
      3675376.24     10654405.64      3673314.58     10654839.67
      3671469.96     10657617.45      3670645.59     10660676.29
#Sta/Elev= 30
   262.4  286.75   356.7  282.77   534.9  286.21  1214.9  243.83  1316.9  240.06
  2004.5  233.45  3067.7   235.3  3161.4  235.65  3325.7  236.03    3452  228.39
  3454.8  227.89    3458  228.39  4017.5  232.88  4079.4   233.4  4587.3  233.97
  4653.2  234.03  4717.9  234.01  4767.9  232.08  5611.4  230.57  5838.3  230.74
  6293.7  231.28  6363.8  231.35  6800.5   233.3  7074.1  235.69  7094.4  237.86
  7527.3  253.47  8180.2  246.65  8423.7  248.37  8502.1  249.76  8871.7  253.15
#Mann= 20 ,-1 , 0
   262.4     .05       0  1214.9     .08       0  1316.9     .05       0
  3067.7     .08       0  3161.4     .05       0    3452     .07       0
    3458     .12       0  4017.5     .05       0  4079.4     .16       0
  4587.3     .05       0  4653.2     .16       0  4767.9     .12       0
  5611.4     .07       0  5838.3     .12       0  6293.7     .07       0
  6363.8     .12       0  6800.5     .07       0  7094.4     .05       0
  8423.7     .08       0  8502.1     .05       0
Bank Sta=4717.9,7074.1
XS Rating Curve= 0 ,0
Exp/Cntr=0.3,0.1

Type RM Length L Ch R = 1 ,32816   ,4078,4078,4078
BEGIN DESCRIPTION:
Mapping XS 260692d6
END DESCRIPTION:
XS GIS Cut Line= 3
      3673162.65     10651584.48      3670840.62     10653580.99
      3668540.32     10660525.29
#Sta/Elev= 30
  2299.2  293.59  2525.6  291.51  2751.6   275.7  2808.7  267.29  2851.5  270.42
  3090.8  259.85  3225.8  256.51  3588.9  249.05  4878.2  233.72  4936.4  227.45
  5565.8  227.05  5568.5  226.55  5571.8  227.05  7095.8  228.61    7323  232.98
  7712.5  232.25  7836.3  239.07  7867.9   232.9  7931.1  229.11  7962.7  232.47
  8236.6  233.87  9700.6  232.24    9764  237.97  9779.9  236.13  9824.3  233.05
  9926.3  234.81 10427.7  235.08 11037.4  251.52 11765.6  246.75 12676.9  251.31
#Mann= 10 ,-1 , 0
  2299.2     .05       0  3090.8     .08       0  3225.8     .05       0
  4878.2     .12       0  5565.8     .07       0  5571.8     .12       0
  7712.5     .05       0  9779.9     .08       0  9824.3      .1       0
  9926.3     .05       0
Bank Sta=4878.2,7323
XS Rating Curve= 0 ,0
Exp/Cntr=0.3,0.1

Type RM Length L Ch R = 1 ,28738   ,2000,2000,2000
BEGIN DESCRIPTION:
CATFISH CREEK 9.0
END DESCRIPTION:
XS GIS Cut Line= 4
      3672722.21     10649703.54      3670118.03      10650259.1
       3669145.8     10651092.43       3668034.7     10660571.56
#Sta/Elev= 30
  2015.5  283.23  2691.2   269.8  3171.1  251.99  3656.1  262.67  4196.1  246.33
  4267.7  239.46  4298.3   244.1  4467.4  226.49  4558.5  231.22  4614.2  230.66
  4685.2  229.68    4716  228.71  4766.7  225.96  4769.5  225.46  4772.7  225.96
  5097.5  229.09  5131.9   229.7  7507.1  229.41  7598.8  237.94  7607.7  232.44
  7658.5  229.09  9904.3  230.56 10322.3  231.77 12625.4  232.43 12779.7   232.9
 13658.9  235.61 13785.2  241.63   14555  239.81 14653.3  240.27 15502.8  248.22
#Mann= 15 ,-1 , 0
  2015.5     .05       0  4558.5     .07       0  4614.2     .05       0
    4716     .07       0  4766.7     .07       0  4772.7     .07       0
  5097.5     .05       0  7598.8     .07       0  7658.5     .05       0
  9904.3     .12       0 10322.3     .05       0 12625.4     .07       0
 12779.7     .05       0   14555     .08       0 14653.3     .05       0
Bank Sta=4685.2,5131.9
XS Rating Curve= 0 ,0
Exp/Cntr=0.3,0.1

Type RM Length L Ch R = 1 ,26738   ,0,0,0
BEGIN DESCRIPTION:
Mapping XS 3cdc0504
END DESCRIPTION:
XS GIS Cut Line= 4
      3671916.62     10648764.99      3668322.87     10649060.13
       3666031.2     10656108.74      3667767.31     10661230.24
#Sta/Elev= 30
  1963.1  273.15  2278.2  270.87  3799.7  242.87  3946.8  231.24  4168.6  235.68
  4247.8  227.43  4548.8  228.65  4977.2  223.57    4980  223.07  4983.2  223.57
  5066.7  225.46  5365.5  225.35  5696.6  228.11  5832.6   227.9    6221   227.9
  6872.2  229.51  7169.6  230.21  7277.6  228.24  7341.5  240.42  7404.5  230.83
  7518.7  226.86  8270.3  227.54  8516.1  227.83  9090.1  228.46  9424.7  228.84
  9730.2  228.85 10035.6  227.86 14237.9  235.09 16555.9  238.28 18388.5   250.1
#Mann= 20 ,-1 , 0
  1963.1     .08       0  2278.2     .05       0  4977.2     .03       0
  4983.2     .05       0  5066.7     .07       0  5365.5     .05       0
  5832.6     .12       0    6221     .07       0  6872.2     .07       0
  7169.6     .05       0  7404.5     .07       0  7518.7     .05       0
  8270.3     .05       0  8516.1     .07       0  9090.1     .05       0
  9424.7     .08       0  9730.2     .05       0 10035.6     .05       0
 14237.9     .05       0 16555.9     .05       0
Bank Sta=4548.8,5696.6
XS Rating Curve= 0 ,0
Exp/Cntr=0.3,0.1

Chan Stop Cuts=-1
Use User Specified Reach Order=0
Composite Channel Slope=5