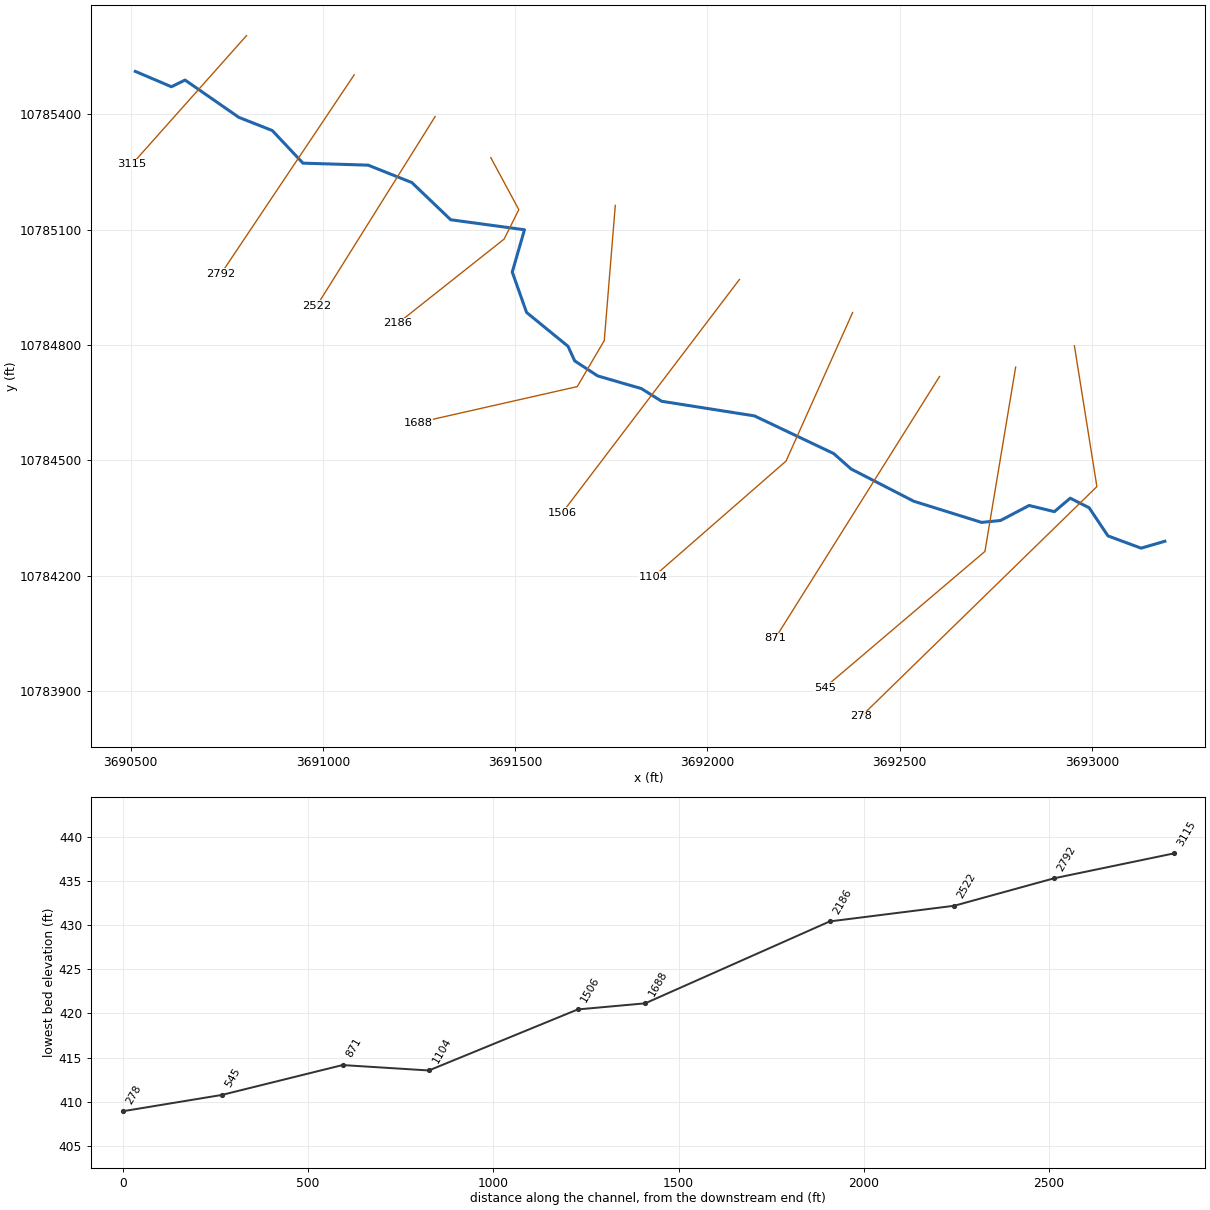
--- COON CREEK NORTH TRIBUTARY.prj (project) ---

Proj Title=COON CREEK NORTH TRIBUTARY Base Level Engineering
Current Plan=p01
Default Exp/Contr=0.3,0.1
English Units
Geom File=g01
Flow File=f01
Plan File=p01
Y Axis Title=Elevation
X Axis Title(PF)=Main Channel Distance
X Axis Title(XS)=Station
BEGIN DESCRIPTION:
COON CREEK NORTH TRIBUTARY
END DESCRIPTION:
DSS Export Rating Curves= 0
DSS Export Rating Curve Sorted= 0
DSS Export Volume Flow Curves= 0
DXF OffsetX= 0
DXF OffsetY= 0
DXF ScaleX= 1
DXF ScaleY= 10

--- COON CREEK NORTH TRIBUTARY.p01 (plan) ---

Plan Title=Multiple Run
Short Identifier=Multiple
Geom File=g01
Flow File=f01
Subcritical Flow
K Sum by GR= 0
Std Step Tol= 0.01
Critical Tol= 0.01
Num of Std Step Trials= 20
Max Error Tol= 0.3
Flow Tol Ratio= 0.001
Split Flow NTrial= 30
Split Flow Tol= 0.02
Split Flow Ratio= 0.02
Log Output Level= 0
Friction Slope Method= 1
Unsteady Friction Slope Method= 2
Unsteady Bridges Friction Slope Method= 1
Parabolic Critical Depth
Global Vel Dist=  1 , 1 , 1
Global Log Level= 0
CheckData=True
Encroach Param= -1, 0, 0, 0
BEGIN DESCRIPTION:
Multiple Run
END DESCRIPTION:

--- COON CREEK NORTH TRIBUTARY.f01 (steady flow) ---

Flow Title=Multiple
Number of Profiles=7
Profile Names=10-year,25-year,50-year,1pct_min,100-year,1pct_plu,500-year
River Rch & RM= COON CREEK NORTH,Reach-1,3115
     367     482     574     503     680     919     952
Boundary for River Rch & Prof#=COON CREEK NORTH,Reach-1,1
Up Type=0
Dn Type=3
Dn Slope=0.005
Boundary for River Rch & Prof#=COON CREEK NORTH,Reach-1,2
Up Type=0
Dn Type=3
Dn Slope=0.005
Boundary for River Rch & Prof#=COON CREEK NORTH,Reach-1,3
Up Type=0
Dn Type=3
Dn Slope=0.005
Boundary for River Rch & Prof#=COON CREEK NORTH,Reach-1,4
Up Type=0
Dn Type=3
Dn Slope=0.005
Boundary for River Rch & Prof#=COON CREEK NORTH,Reach-1,5
Up Type=0
Dn Type=3
Dn Slope=0.005
Boundary for River Rch & Prof#=COON CREEK NORTH,Reach-1,6
Up Type=0
Dn Type=3
Dn Slope=0.005
Boundary for River Rch & Prof#=COON CREEK NORTH,Reach-1,7
Up Type=0
Dn Type=3
Dn Slope=0.005

--- COON CREEK NORTH TRIBUTARY.g01 (geometry) ---

Geom Title=Existing Conditions
Program Version=4.10

River Reach=COON CREEK NORTH,Reach-1
Reach XY= 30
      3690512.35     10785511.84       3690606.1     10785471.91
      3690641.69     10785489.28      3690781.52     10785392.28
       3690868.5       10785358.      3690948.29      10785273.2
      3691117.75       10785268.      3691231.31     10785222.81
       3691332.5       10785126.      3691524.25       10785100.
       3691492.5       10784990.      3691529.75       10784885.
       3691637.5       10784797.      3691654.89     10784759.01
       3691714.5       10784720.      3691828.25       10784687.
        3691881.       10784654.      3692122.25       10784616.
       3692328.5       10784518.       3692373.5       10784478.
      3692536.75       10784394.        3692713.       10784339.
      3692762.25       10784344.       3692836.5       10784383.
      3692902.25       10784367.       3692943.5       10784402.
      3692992.75       10784377.       3693041.5       10784304.
      3693127.75       10784272.       3693189.5       10784290.

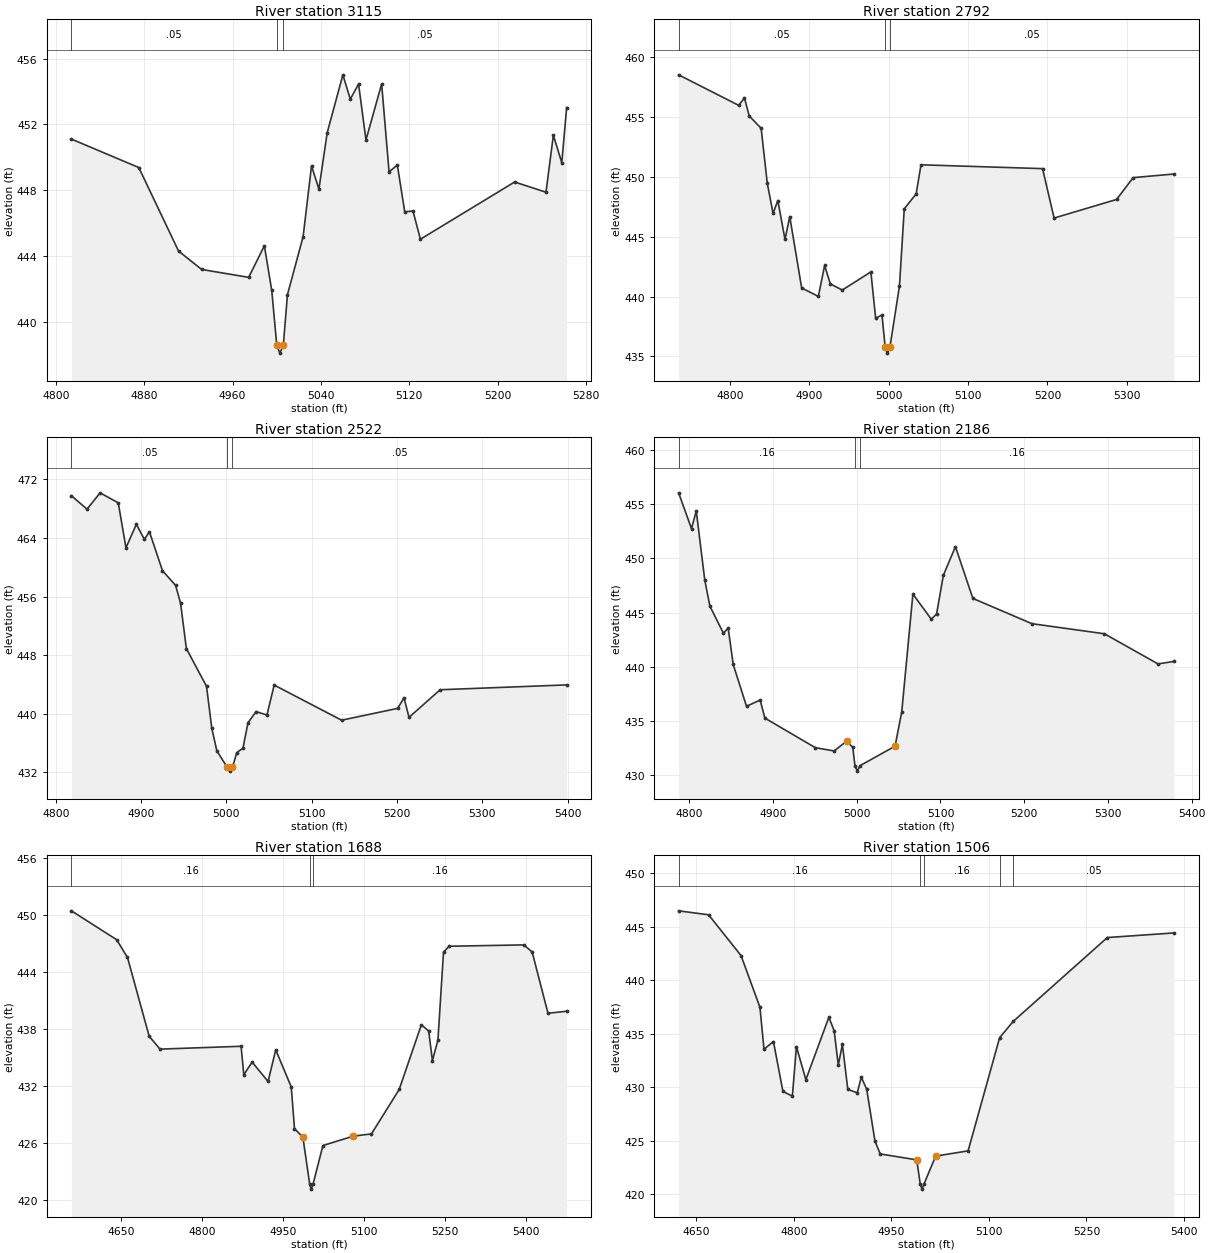
Type RM Length L Ch R = 1 ,3115    ,323,323,323
BEGIN DESCRIPTION:
COON CREEK NORTH TRIBUTARY 6.0
END DESCRIPTION:
XS GIS Cut Line= 2
      3690801.52     10785604.87      3690503.35     10785269.97
#Sta/Elev= 30
  4814.1  451.11  4875.1  449.38  4911.1   444.3    4932  443.18  4974.6   442.7
  4988.8  444.62  4995.5   441.9    5000  438.59  5002.8  438.09    5006  438.59
  5009.7  441.64  5023.9  445.18  5031.5  449.48  5038.2  448.07  5045.7   451.5
  5059.9  455.02  5066.6  453.54  5074.1  454.46  5080.8  451.06    5095  454.46
  5101.7  449.12  5109.2  449.53  5115.9  446.69  5123.4  446.73  5130.1  445.02
  5215.4   448.5  5243.8  447.88  5250.5  451.35  5258.1  449.67  5262.5  453.03
#Mann= 3 ,-1 , 0
  4814.1     .05       0    5000     .03       0    5006     .05       0
Bank Sta=5000,5006
XS Rating Curve= 0 ,0
Exp/Cntr=0.3,0.1

Type RM Length L Ch R = 1 ,2792    ,270,270,270
BEGIN DESCRIPTION:
Mapping XS 11404398
END DESCRIPTION:
XS GIS Cut Line= 2
      3691081.49     10785502.89      3690734.75     10784984.94
#Sta/Elev= 30
  4735.7  458.48  4811.2  455.94  4818.6  456.54  4824.6  455.05  4839.6  454.02
  4847.3  449.44  4854.6  446.93  4860.6     448  4869.6  444.76  4875.6  446.66
  4890.6  440.71  4911.6  440.01  4919.5  442.59  4926.7  441.05  4941.7  440.54
  4977.7  442.05  4983.7  438.19  4991.7  438.46  4995.7  435.78  4998.5  435.28
  5001.7  435.78  5013.7  440.88  5019.7   447.3  5034.7  448.56  5040.8  450.98
  5193.8  450.66  5208.3  446.54  5286.9  448.09  5307.9  449.91    5359  450.21
#Mann= 3 ,-1 , 0
  4735.7     .05       0  4995.7    .035       0  5001.7     .05       0
Bank Sta=4995.7,5001.7
XS Rating Curve= 0 ,0
Exp/Cntr=0.3,0.1

Type RM Length L Ch R = 1 ,2522    ,336,336,336
BEGIN DESCRIPTION:
Mapping XS 8f5cb6d2
END DESCRIPTION:
XS GIS Cut Line= 2
        3691292.      10785394.4      3690984.25     10784902.43
#Sta/Elev= 30
  4818.4  469.76  4836.7  467.93    4852  470.16  4873.3  468.79  4882.3  462.66
  4894.5  465.87  4903.9   463.8  4909.8  464.85  4925.1  459.53  4940.5  457.52
  4946.3  455.09  4953.1   448.9  4976.7  443.75  4982.9  438.01  4988.8  434.94
  5001.1  432.67  5003.9  432.17  5007.1  432.67  5012.1  434.69  5019.4   435.3
  5025.3  438.77  5034.8  440.29  5047.5  439.83    5056  443.92    5135  439.12
  5200.8  440.74  5208.1  442.19    5214  439.51  5250.5  443.28  5398.7  443.94
#Mann= 3 ,-1 , 0
  4818.4     .05       0  5001.1     .03       0  5007.1     .05       0
Bank Sta=5001.1,5007.1
XS Rating Curve= 0 ,0
Exp/Cntr=0.3,0.1

Type RM Length L Ch R = 1 ,2186    ,498,498,498
BEGIN DESCRIPTION:
COON CREEK NORTH TRIBUTARY 5.0
END DESCRIPTION:
XS GIS Cut Line= 4
      3691436.69     10785287.62       3691509.6     10785152.21
       3691471.4     10785075.82      3691195.37     10784857.08
#Sta/Elev= 30
  4787.3  456.05  4802.7  452.75  4808.4  454.38  4818.5  448.04  4824.6  445.62
  4840.8  443.11  4846.5  443.59  4852.5  440.23  4868.4  436.38  4884.7  436.95
  4890.3  435.29  4950.6  432.56    4973  432.26  4988.1  433.17  4995.3  432.58
  4997.9   430.9  5000.7   430.4  5003.9   430.9  5045.8   432.7  5053.8  435.87
  5067.1  446.72  5089.1   444.4  5095.4  444.89  5103.5  448.45  5117.9  451.09
  5138.7  446.32  5209.2  443.99  5295.8  443.06  5359.9  440.28  5378.7  440.51
#Mann= 3 ,-1 , 0
  4787.3     .16       0  4997.9     .03       0  5003.9     .16       0
Bank Sta=4988.1,5045.8
XS Rating Curve= 0 ,0
Exp/Cntr=0.3,0.1

Type RM Length L Ch R = 1 ,1688    ,182,182,182
BEGIN DESCRIPTION:
COON CREEK NORTH TRIBUTARY 4.0
END DESCRIPTION:
XS GIS Cut Line= 4
      3691760.47     10785163.51      3691731.82     10784811.93
      3691661.51     10784692.14      3691247.43     10784598.39
#Sta/Elev= 30
  4558.3  450.46  4641.9  447.42    4662  445.55  4702.1  437.25  4722.2  435.89
  4872.2  436.19  4877.2   433.2  4892.7  434.52  4922.1  432.48  4936.3  435.81
    4965  431.91    4971  427.51  4986.5  426.62  4999.2  421.64  5001.9  421.14
  5005.2  421.64  5023.6  425.73  5079.5  426.72  5113.4  426.96  5164.7  431.64
  5205.7  438.45  5219.2  437.81  5226.2  434.68  5236.4  436.84  5246.7  446.11
    5257  446.73  5395.4  446.87  5410.7  446.12    5440  439.67  5474.5  439.88
#Mann= 3 ,-1 , 0
  4558.3     .16       0  4999.2     .03       0  5005.2     .16       0
Bank Sta=4986.5,5079.5
XS Rating Curve= 0 ,0
Exp/Cntr=0.3,0.1

Type RM Length L Ch R = 1 ,1506    ,402,402,402
BEGIN DESCRIPTION:
Mapping XS 50fbdb3a
END DESCRIPTION:
XS GIS Cut Line= 2
      3692083.35     10784970.75      3691622.47     10784364.05
#Sta/Elev= 30
  4622.6  446.49  4668.7  446.12  4718.6  442.31  4747.7  437.47    4754  433.54
  4768.5  434.26  4783.1  429.59  4797.6  429.15  4803.9  433.78  4818.4  430.69
  4853.8  436.53  4861.9  435.27  4868.3  432.06  4874.6  433.99  4882.9  429.79
  4897.4  429.46  4903.7  430.92    4912   429.8  4924.7  424.95  4932.8  423.74
    4989  423.19  4994.3  420.95    4997  420.45  5000.3  420.95  5018.1  423.54
    5068  424.03  5116.5  434.62  5137.5  436.15  5282.2  443.99  5384.5  444.42
#Mann= 5 ,-1 , 0
  4622.6     .16       0  4994.3     .03       0  5000.3     .16       0
  5116.5     .16       0  5137.5     .05       0
Bank Sta=4989,5018.1
XS Rating Curve= 0 ,0
Exp/Cntr=0.3,0.1

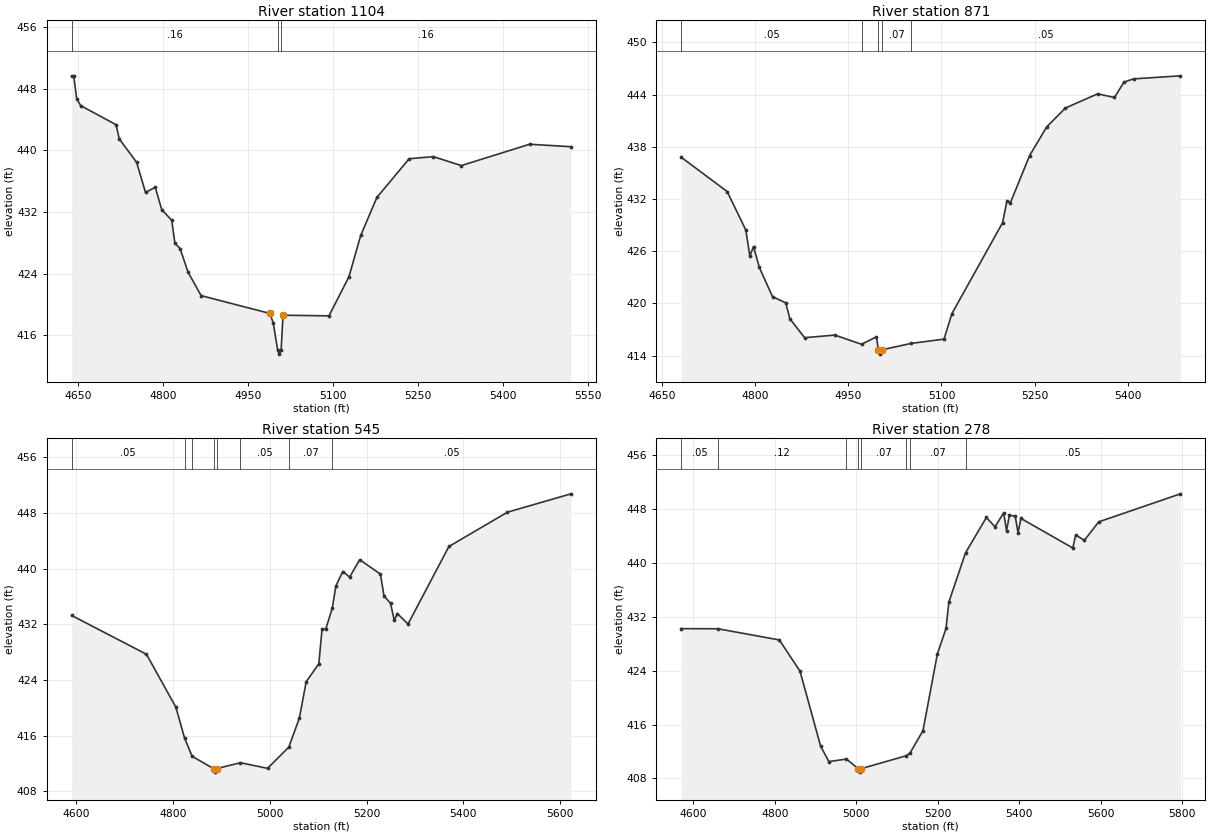
Type RM Length L Ch R = 1 ,1104    ,233,233,233
BEGIN DESCRIPTION:
Mapping XS 3df792fa
END DESCRIPTION:
XS GIS Cut Line= 3
      3692377.64     10784884.81      3692204.39     10784498.39
      3691859.44     10784197.37
#Sta/Elev= 30
  4638.3  449.67    4642  449.67  4647.3  446.69  4654.3   445.8  4716.8  443.32
  4722.3  441.49    4753  438.44  4768.7  434.53  4785.8  435.21  4797.3  432.31
    4815  430.92  4820.5  427.94  4829.7  427.25  4843.7   424.2  4866.9  421.14
  4988.2  418.83  4994.1  417.61    5002  414.05  5004.8  413.55    5008  414.05
  5011.4   418.6  5092.5  418.52  5127.7  423.58  5148.5  428.95    5177  433.88
    5234  438.91  5276.7  439.18  5326.1  438.02  5446.6  440.79  5519.6  440.47
#Mann= 3 ,-1 , 0
  4638.3     .16       0    5002     .03       0    5008     .16       0
Bank Sta=4988.2,5011.4
XS Rating Curve= 0 ,0
Exp/Cntr=0.3,0.1

Type RM Length L Ch R = 1 ,871     ,326,326,326
BEGIN DESCRIPTION:
COON CREEK NORTH TRIBUTARY 3.0
END DESCRIPTION:
XS GIS Cut Line= 2
      3692603.64     10784718.48      3692176.54     10784037.89
#Sta/Elev= 30
    4681   436.8  4755.1  432.85  4785.2  428.41  4791.6  425.42  4797.5  426.53
  4806.9  424.12  4828.1  420.76  4849.3  420.06  4856.1  418.22  4879.7  416.05
  4928.3  416.35  4971.3  415.29  4995.4  416.15  4998.3  414.66  5001.1  414.16
  5004.3  414.66  5051.6   415.4    5104  415.88  5116.8  418.82  5198.4  429.28
  5205.1  431.71    5211  431.58  5241.7  436.97  5269.3  440.28  5299.4  442.45
  5351.2  444.08  5378.3  443.66  5393.7  445.43    5409   445.8  5484.5  446.15
#Mann= 5 ,-1 , 0
    4681     .05       0  4971.3     .07       0  4998.3     .07       0
  5004.3     .07       0  5051.6     .05       0
Bank Sta=4998.3,5004.3
XS Rating Curve= 0 ,0
Exp/Cntr=0.3,0.1

Type RM Length L Ch R = 1 ,545     ,267,267,267
BEGIN DESCRIPTION:
COON CREEK NORTH TRIBUTARY 2.0
END DESCRIPTION:
XS GIS Cut Line= 3
      3692801.55     10784742.76      3692721.69     10784263.61
      3692305.03     10783909.45
#Sta/Elev= 30
    4590  433.27  4744.7   427.7  4805.5  420.11  4823.7  415.64  4839.2  413.05
  4883.6  411.28  4886.4  410.78  4889.6  411.28  4939.2  412.13  4995.1  411.32
  5039.2  414.38    5061  418.55    5075  423.74  5101.2  426.34  5107.8  431.27
  5115.5  431.33  5129.1  434.32  5136.3  437.47  5150.6  439.58  5164.9  438.78
  5185.7  441.27  5228.6  439.21    5236  436.06  5249.4  435.02  5257.1   432.6
  5263.7  433.52  5285.7  432.05  5370.2  443.17  5491.1  448.09  5622.6  450.73
#Mann= 8 ,-1 , 0
    4590     .05       0  4823.7     .07       0  4839.2     .12       0
  4883.6     .03       0  4889.6     .12       0  4939.2     .05       0
  5039.2     .07       0  5129.1     .05       0
Bank Sta=4883.6,4889.6
XS Rating Curve= 0 ,0
Exp/Cntr=0.3,0.1

Type RM Length L Ch R = 1 ,278     ,0,0,0
BEGIN DESCRIPTION:
COON CREEK NORTH TRIBUTARY 1.0
END DESCRIPTION:
XS GIS Cut Line= 3
      3692954.33     10784798.36      3693012.78     10784432.11
      3692400.79     10783835.31
#Sta/Elev= 30
  4570.3  430.23  4660.7  430.21  4811.5  428.55  4862.1  423.92  4912.8  412.79
    4933   410.5  4976.1  410.88  5005.4  409.44  5008.2  408.94  5011.4  409.44
  5122.3  411.36  5131.7  411.72    5164  415.09  5199.3  426.46  5220.6  430.26
  5227.6  434.18  5268.5  441.48  5319.6  446.72  5340.8  445.34  5362.1   447.4
  5369.1  444.77  5376.2  447.03  5390.4  446.93  5397.3  444.48  5404.5  446.58
  5531.8  442.19  5538.8  444.13  5560.1  443.33  5595.4  446.07    5796  450.23
#Mann= 8 ,-1 , 0
  4570.3     .05       0  4660.7     .12       0  4976.1     .07       0
  5005.4     .07       0  5011.4     .07       0  5122.3     .05       0
  5131.7     .07       0  5268.5     .05       0
Bank Sta=5005.4,5011.4
XS Rating Curve= 0 ,0
Exp/Cntr=0.3,0.1

Chan Stop Cuts=-1
Use User Specified Reach Order=0
Composite Channel Slope=5