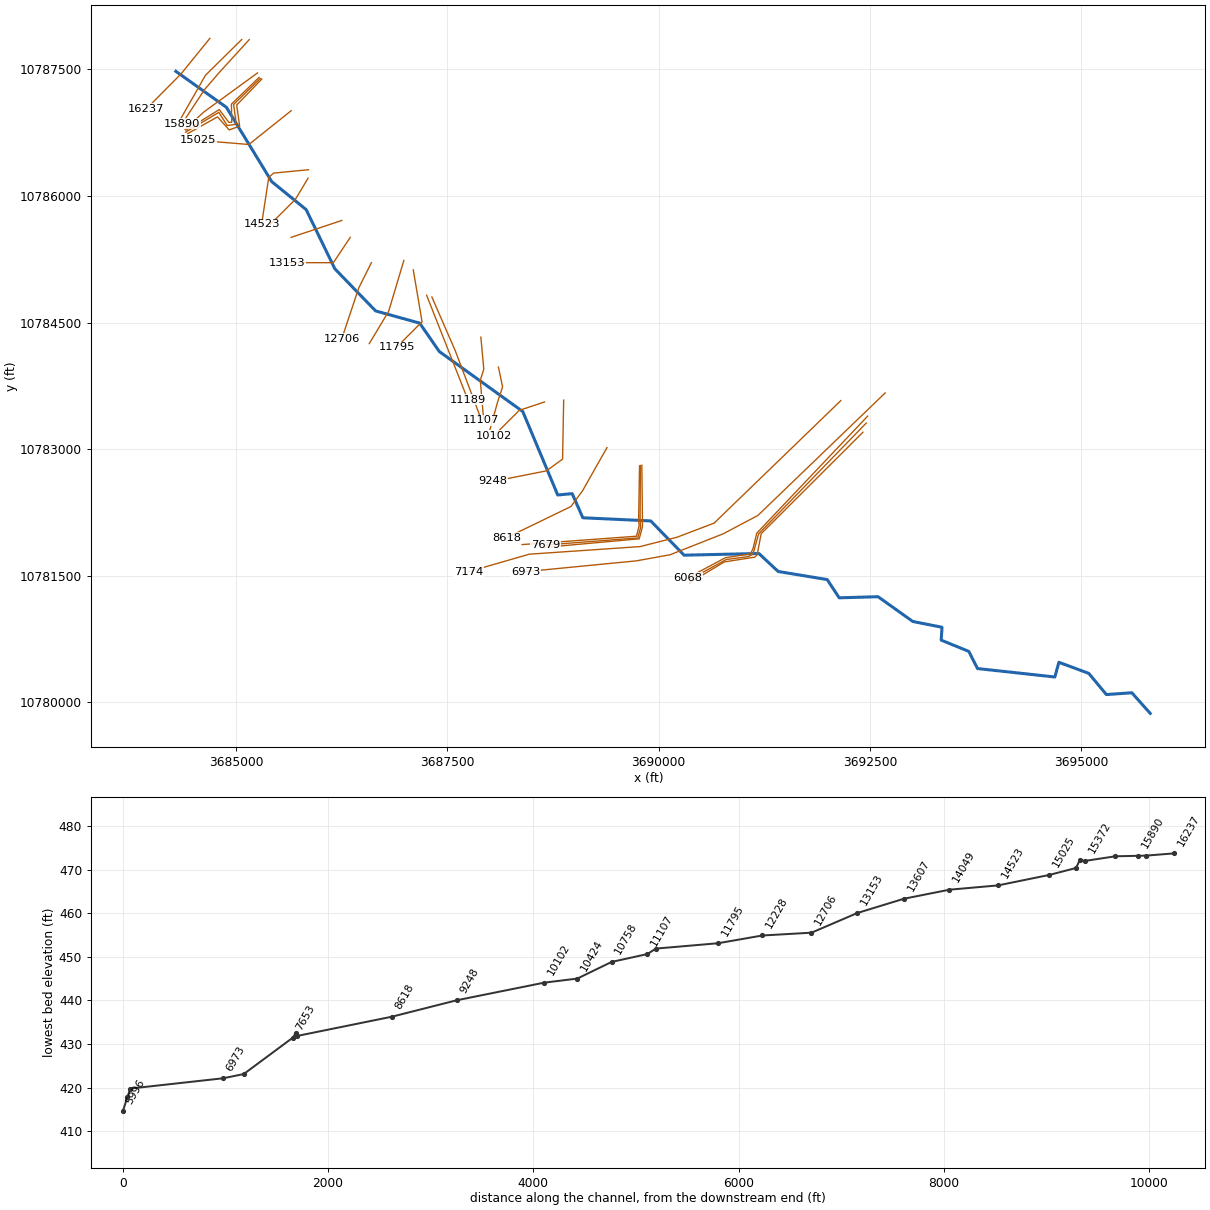
--- COON CREEK SOUTH TRIBUTARY.prj (project) ---

Proj Title=COON CREEK SOUTH TRIBUTARY Base Level Engineering
Current Plan=p01
Default Exp/Contr=0.3,0.1
English Units
Geom File=g01
Flow File=f01
Plan File=p01
Y Axis Title=Elevation
X Axis Title(PF)=Main Channel Distance
X Axis Title(XS)=Station
BEGIN DESCRIPTION:
COON CREEK SOUTH TRIBUTARY
END DESCRIPTION:
DSS Export Rating Curves= 0
DSS Export Rating Curve Sorted= 0
DSS Export Volume Flow Curves= 0
DXF OffsetX= 0
DXF OffsetY= 0
DXF ScaleX= 1
DXF ScaleY= 10

--- COON CREEK SOUTH TRIBUTARY.p01 (plan) ---

Plan Title=Multiple Run
Short Identifier=Multiple
Geom File=g01
Flow File=f01
Subcritical Flow
K Sum by GR= 0
Std Step Tol= 0.01
Critical Tol= 0.01
Num of Std Step Trials= 20
Max Error Tol= 0.3
Flow Tol Ratio= 0.001
Split Flow NTrial= 30
Split Flow Tol= 0.02
Split Flow Ratio= 0.02
Log Output Level= 0
Friction Slope Method= 1
Unsteady Friction Slope Method= 2
Unsteady Bridges Friction Slope Method= 1
Parabolic Critical Depth
Global Vel Dist=  1 , 1 , 1
Global Log Level= 0
CheckData=True
Encroach Param= -1, 0, 0, 0
BEGIN DESCRIPTION:
Multiple Run
END DESCRIPTION:

--- COON CREEK SOUTH TRIBUTARY.f01 (steady flow) ---

Flow Title=Multiple
Program Version=4.10
Number of Profiles= 7
Profile Names=10-year,25-year,50-year,1pct_min,100-year,1pct_plu,500-year
River Rch & RM=COON CREEK SOUTH,Reach-1         ,16237
     476     633     759     669     904    1223    1285
River Rch & RM=COON CREEK SOUTH,Reach-1         ,11107
     638     863    1047     932    1260    1704    1828
River Rch & RM=COON CREEK SOUTH,Reach-1         ,7696
     720     981    1196    1069    1446    1955    2118
River Rch & RM=COON CREEK SOUTH,Reach-1         ,6973
     966    1338    1649    1489    2013    2723    3010
River Rch & RM=COON CREEK SOUTH,Reach-1         ,3703
    1055    1465    1809    1635    2211    2989    3312
Boundary for River Rch & Prof#=COON CREEK SOUTH,Reach-1         , 1
Up Type= 0
Dn Type= 3
Dn Slope=0.00634
Boundary for River Rch & Prof#=COON CREEK SOUTH,Reach-1         , 2
Up Type= 0
Dn Type= 3
Dn Slope=0.00634
Boundary for River Rch & Prof#=COON CREEK SOUTH,Reach-1         , 3
Up Type= 0
Dn Type= 3
Dn Slope=0.00634
Boundary for River Rch & Prof#=COON CREEK SOUTH,Reach-1         , 4
Up Type= 0
Dn Type= 3
Dn Slope=0.00634
Boundary for River Rch & Prof#=COON CREEK SOUTH,Reach-1         , 5
Up Type= 0
Dn Type= 3
Dn Slope=0.00634
Boundary for River Rch & Prof#=COON CREEK SOUTH,Reach-1         , 6
Up Type= 0
Dn Type= 3
Dn Slope=0.00634
Boundary for River Rch & Prof#=COON CREEK SOUTH,Reach-1         , 7
Up Type= 0
Dn Type= 3
Dn Slope=0.00634
DSS Import GetInterval= 0
DSS Import GetPeak= 0
DSS Import FillOption= 0

--- COON CREEK SOUTH TRIBUTARY.g01 (geometry) ---

Geom Title=Existing Conditions
Program Version=4.10

River Reach=COON CREEK SOUTH,Reach-1
Reach XY= 30
      3684284.36     10787477.38        3684883.       10787051.
      3685420.25       10786170.      3685827.25       10785839.
      3686166.75       10785138.      3686649.25       10784639.
       3687171.5       10784494.      3687403.25       10784158.
      3688391.75       10783447.      3688805.75       10782458.
       3688976.5       10782474.      3689102.75       10782188.
        3689906.       10782151.       3690301.5       10781745.
        3691187.       10781765.      3691415.25       10781552.
      3691995.75       10781456.      3692137.75       10781240.
      3692597.75       10781253.       3693008.5       10780960.
      3693354.75       10780891.        3693345.       10780739.
        3693672.       10780605.        3693775.       10780402.
       3694690.5       10780302.      3694738.75       10780476.
        3695092.       10780345.      3695300.75       10780094.
      3695602.25       10780115.      3695819.75       10779871.

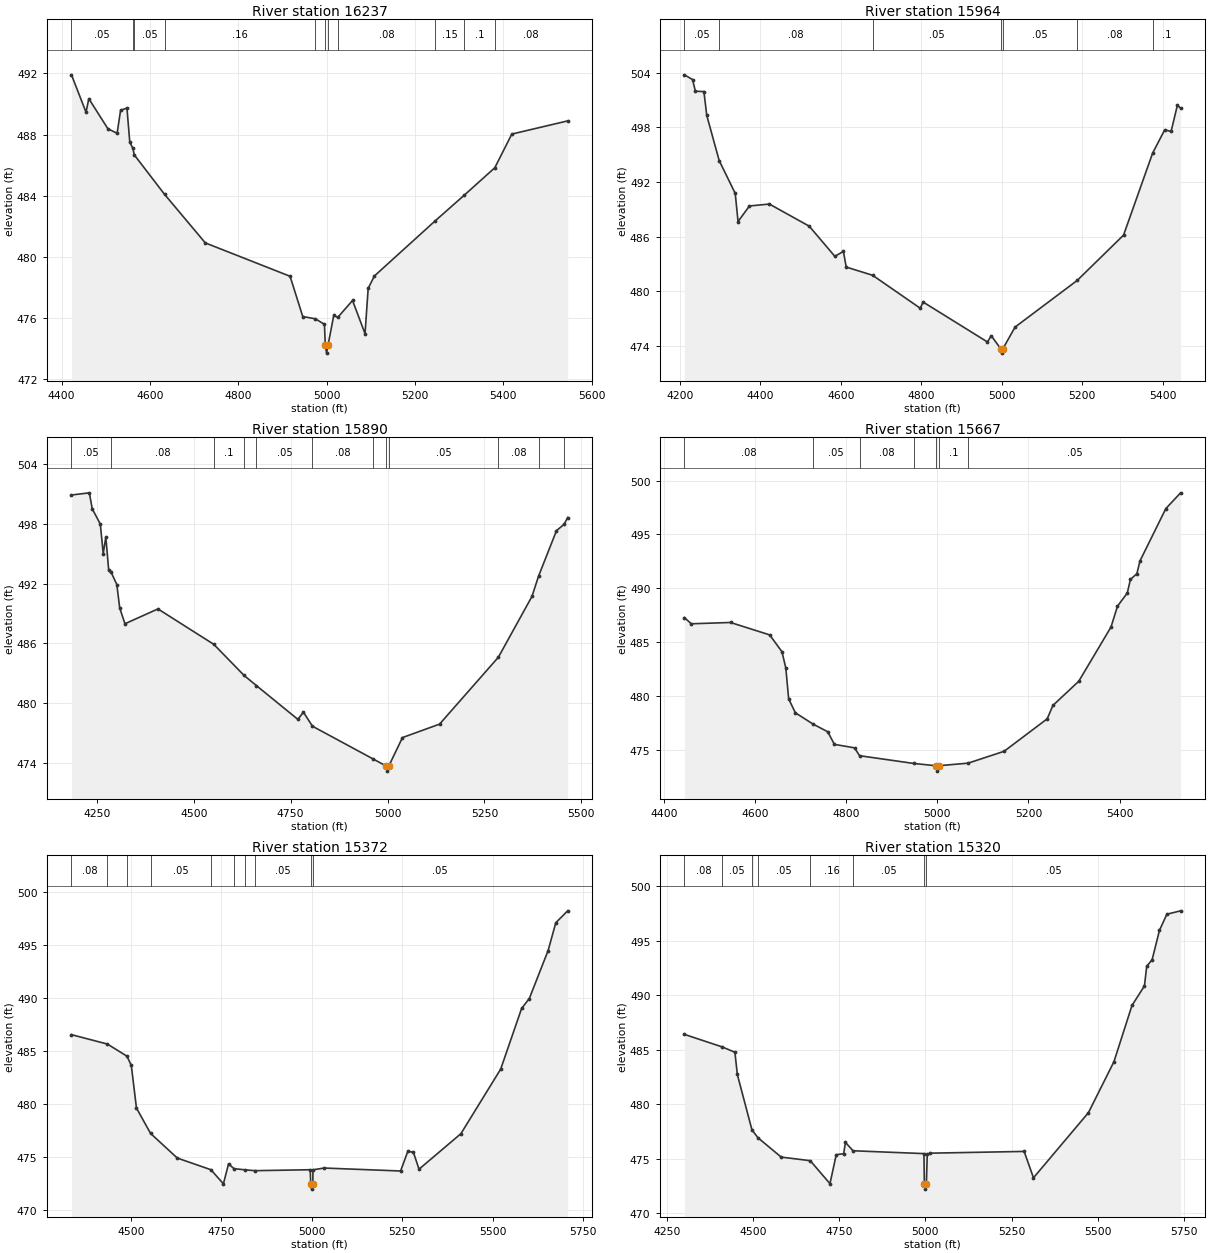
Type RM Length L Ch R = 1 ,16237   ,273,273,273
BEGIN DESCRIPTION:
COON CREEK SOUTH TRIBUTARY 29.0
END DESCRIPTION:
XS GIS Cut Line= 3
      3684687.65     10787867.84      3684347.34     10787447.66
      3683937.11     10787033.97
#Sta/Elev= 30
  4422.3   491.9  4455.2  489.46  4461.6  490.34  4504.7  488.38  4525.6  488.08
  4533.5  489.58  4547.9  489.73  4554.3   487.5  4561.3   487.1  4564.5  486.67
  4633.1  484.09  4725.3  480.92  4917.2  478.74  4945.9  476.11  4974.7  475.96
    4995   475.6    4997  474.22  4999.8  473.72    5003  474.22  5016.1  476.19
    5025  476.05  5058.6  477.16  5086.9  474.99    5094  477.95  5108.1  478.76
  5245.3  482.35    5312  484.05  5380.7  485.83  5419.2  488.03  5545.6  488.89
#Mann= 11 ,-1 , 0
  4422.3     .05       0  4561.3     .08       0  4564.5     .05       0
  4633.1     .16       0  4974.7     .05       0    4997     .04       0
    5003     .05       0    5025     .08       0  5245.3     .15       0
    5312      .1       0  5380.7     .08       0
Bank Sta=4997,5003
XS Rating Curve= 0 ,0
Exp/Cntr=0.3,0.1

Type RM Length L Ch R = 1 ,15964   ,74,74,74
BEGIN DESCRIPTION:
Mapping XS adcf36a9
END DESCRIPTION:
XS GIS Cut Line= 3
      3685064.35      10787853.9      3684635.54      10787430.3
      3684323.84     10786883.11
#Sta/Elev= 30
  4211.7  503.77  4231.9  503.25  4238.9  501.97  4260.1  501.93  4267.2  499.31
    4298  494.36  4337.9  490.75  4344.9  487.66  4373.2  489.37  4422.7  489.58
  4521.7  487.15  4585.3  483.84  4606.6  484.38  4613.6  482.66  4679.1  481.76
  4797.5  478.14  4804.6  478.82  4964.2  474.44    4974  475.11    4997  473.71
  4999.8  473.21    5003  473.71    5033  476.07  5187.3  481.19  5302.5  486.17
  5374.6  495.16  5404.8  497.74  5420.6  497.55  5436.1  500.42  5444.2  500.11
#Mann= 7 ,-1 , 0
  4211.7     .05       0    4298     .08       0  4679.1     .05       0
    4997     .04       0    5003     .05       0  5187.3     .08       0
  5374.6      .1       0
Bank Sta=4997,5003
XS Rating Curve= 0 ,0
Exp/Cntr=0.3,0.1

Type RM Length L Ch R = 1 ,15890   ,223,223,223
BEGIN DESCRIPTION:
Mapping XS 6efbb32c
END DESCRIPTION:
XS GIS Cut Line= 4
      3685152.92      10787852.2      3684800.47     10787465.02
      3684626.86     10787263.64      3684356.47     10786854.59
#Sta/Elev= 30
  4184.7   500.9  4230.8  501.12  4238.2  499.52  4259.1  497.98  4266.6  495.02
  4273.3  496.68  4280.7  493.36  4286.9  493.15  4301.7  491.91  4309.1  489.56
  4322.6  487.97  4407.8  489.46  4551.9   485.9  4629.9  482.78  4661.7  481.76
  4768.6  478.37  4782.9  479.09  4806.3  477.68  4961.4  474.42    4997  473.67
  4999.8  473.17    5003  473.67  5038.4  476.54  5134.1  477.89  5285.8  484.61
  5372.5  490.72  5389.4  492.75  5435.7  497.32  5455.4  497.96  5464.5  498.64
#Mann= 12 ,-1 , 0
  4184.7     .05       0  4286.9     .08       0  4551.9      .1       0
  4629.9     .08       0  4661.7     .05       0  4806.3     .08       0
  4961.4     .05       0    4997     .04       0    5003     .05       0
  5285.8     .08       0  5389.4     .05       0  5455.4      .1       0
Bank Sta=4997,5003
XS Rating Curve= 0 ,0
Exp/Cntr=0.3,0.1

Type RM Length L Ch R = 1 ,15667   ,295,295,295
BEGIN DESCRIPTION:
Mapping XS 61a0d187
END DESCRIPTION:
XS GIS Cut Line= 3
      3685251.85     10787458.07      3684612.97      10786992.8
      3684393.54     10786790.65
#Sta/Elev= 30
  4445.2  487.29  4460.3  486.72  4546.4  486.84  4632.2  485.69  4659.2  484.13
  4667.7  482.61  4673.9  479.76  4688.6  478.47  4727.1  477.43  4759.6  476.71
  4774.3  475.54  4818.4  475.22  4829.5  474.49  4948.6  473.77    4997  473.56
  4999.8  473.06    5003  473.56  5067.7   473.8  5146.7   474.9  5241.2  477.91
  5253.7  479.15  5310.4  481.39  5381.2  486.42  5395.4  488.35  5416.9  489.57
  5423.8  490.83    5438  491.37  5444.8  492.55  5501.5   497.4  5533.9  498.86
#Mann= 7 ,-1 , 0
  4445.2     .08       0  4727.1     .05       0  4829.5     .08       0
  4948.6      .1       0    4997     .07       0    5003      .1       0
  5067.7     .05       0
Bank Sta=4997,5003
XS Rating Curve= 0 ,0
Exp/Cntr=0.3,0.1

Type RM Length L Ch R = 1 ,15372   ,52,52,52
BEGIN DESCRIPTION:
Mapping XS e69d19b2
END DESCRIPTION:
XS GIS Cut Line= 6
      3685269.19     10787404.23      3684942.83     10787088.29
       3684946.3     10786873.01      3684911.58     10786873.01
      3684798.73     10787024.05      3684404.65     10786779.27
#Sta/Elev= 30
  4336.2  486.57  4435.7  485.68  4489.4  484.54  4501.5  483.67  4515.7  479.65
  4554.8  477.25  4628.6  474.93  4721.4  473.83  4755.9   472.5  4770.1  474.38
  4785.2  473.93  4815.8  473.82  4842.9  473.74  4995.9  473.83    4997   472.5
  4999.8     472    5003   472.5  5003.2  473.82  5034.3  473.99  5245.4  473.71
  5265.6  475.59  5280.9  475.46  5296.3  473.88    5412  477.23  5521.9  483.32
  5579.7  489.04    5601  489.98  5652.9   494.5  5674.2  497.13  5706.9  498.25
#Mann= 10 ,-1 , 0
  4336.2     .08       0  4435.7     .05       0  4489.4     .08       0
  4554.8     .05       0  4721.4     .16       0  4785.2     .08       0
  4815.8     .16       0  4842.9     .05       0    4997     .03       0
    5003     .05       0
Bank Sta=4997,5003
XS Rating Curve= 0 ,0
Exp/Cntr=0.3,0.1

Type RM Length L Ch R = 1 ,15320   ,36,36,36
BEGIN DESCRIPTION:
Mapping XS aa61b5c4
END DESCRIPTION:
XS GIS Cut Line= 6
      3685284.81     10787392.08      3684968.87     10787084.82
      3685000.12     10786850.44      3684892.48     10786834.82
      3684793.52     10786991.07      3684399.65     10786755.09
#Sta/Elev= 30
  4300.9  486.41  4410.6  485.26  4447.4  484.77  4454.4  482.73  4496.9  477.64
  4514.4  476.92  4581.7  475.15    4666  474.82  4723.2  472.71  4741.4  475.37
  4762.9  475.46  4768.1   476.5  4790.2  475.73  4995.9  475.47    4997  472.71
  4999.8  472.21    5003  472.71  5005.5  475.41  5013.9  475.51  5286.6  475.67
  5313.7  473.25  5473.2  479.23  5547.1   483.9  5599.6  489.07  5635.7  490.86
  5642.3  492.67  5657.9  493.26  5679.3  495.96  5700.7  497.44  5740.6  497.75
#Mann= 8 ,-1 , 0
  4300.9     .08       0  4410.6     .05       0  4496.9     .08       0
  4514.4     .05       0    4666     .16       0  4790.2     .05       0
    4997     .03       0    5003     .05       0
Bank Sta=4997,5003
XS Rating Curve= 0 ,0
Exp/Cntr=0.3,0.1

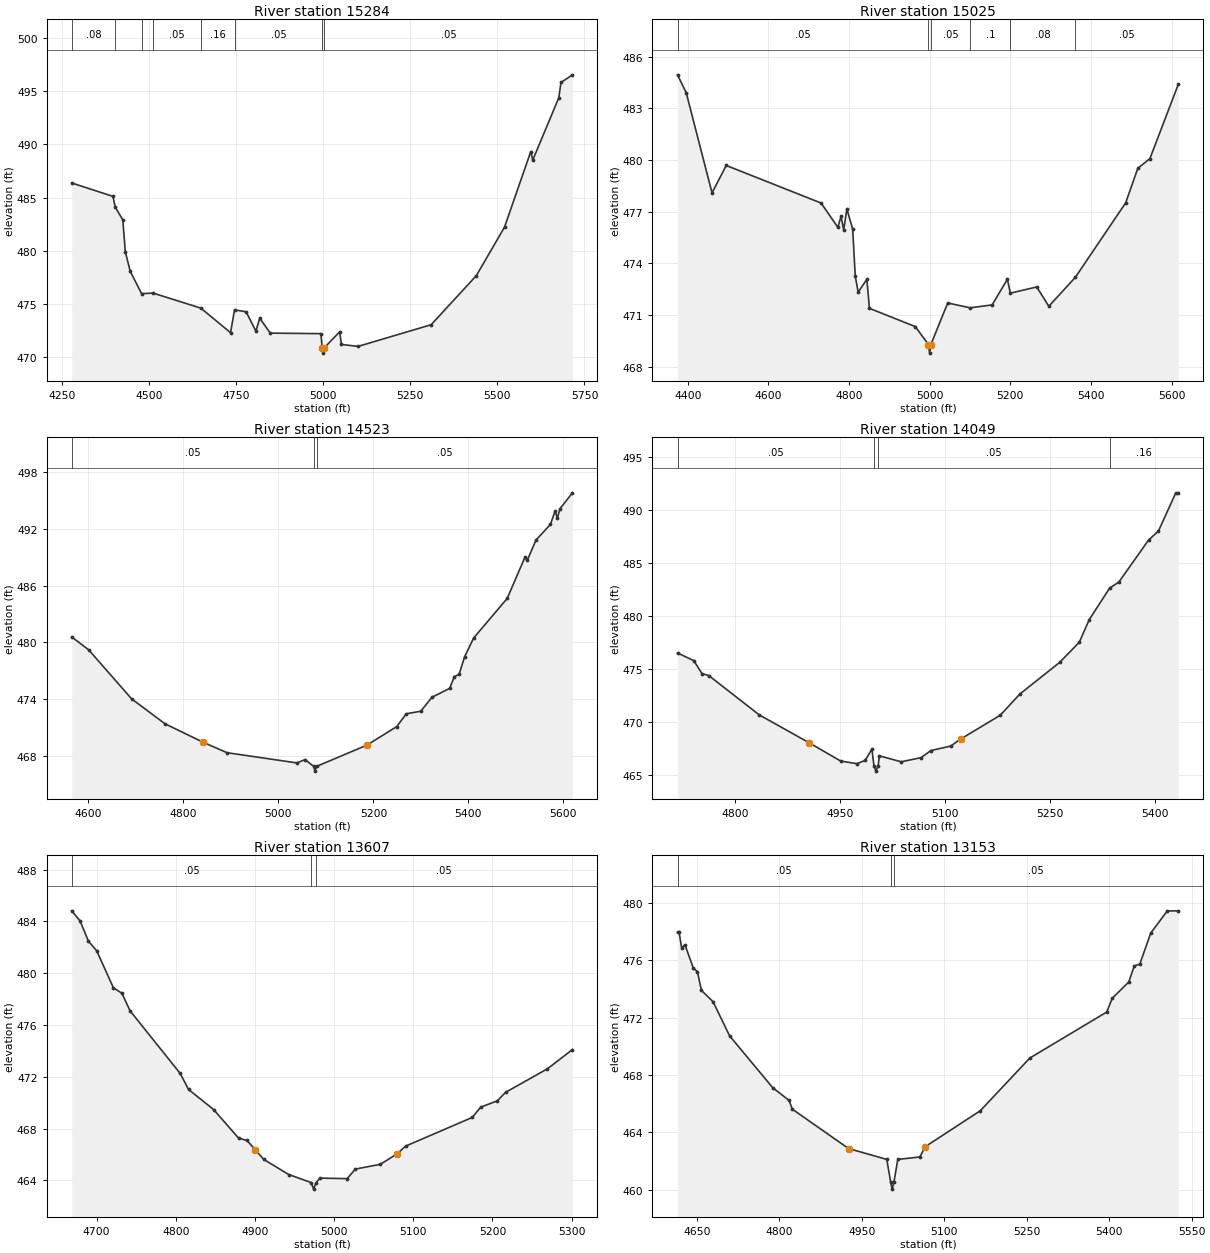
Type RM Length L Ch R = 1 ,15284   ,259,259,259
BEGIN DESCRIPTION:
Mapping XS abed90de
END DESCRIPTION:
XS GIS Cut Line= 6
      3685302.19     10787385.15      3685005.33     10787077.87
      3685040.05     10786827.87      3684916.79     10786782.73
       3684777.9     10786937.25      3684425.43     10786739.31
#Sta/Elev= 30
    4278  486.37  4396.4  485.11  4403.2  484.08  4424.7   482.9  4431.9   479.9
    4446  478.07  4478.5  475.97  4511.7  476.02  4648.7  474.61    4734   472.3
  4745.4  474.44  4778.6  474.27  4806.7  472.45  4817.8  473.66    4848  472.26
  4993.4  472.21    4997  470.88  4999.8  470.38    5003  470.88  5047.1  472.38
  5052.3   471.2  5099.8  471.01  5309.9  473.05  5439.5  477.66  5520.5  482.22
  5595.7  489.31  5601.5  488.52  5676.2  494.37  5682.5  495.81  5715.4  496.53
#Mann= 8 ,-1 , 0
    4278     .08       0  4403.2     .05       0  4478.5     .08       0
  4511.7     .05       0  4648.7     .16       0  4745.4     .05       0
    4997     .03       0    5003     .05       0
Bank Sta=4997,5003
XS Rating Curve= 0 ,0
Exp/Cntr=0.3,0.1

Type RM Length L Ch R = 1 ,15025   ,502,502,502
BEGIN DESCRIPTION:
COON CREEK SOUTH TRIBUTARY 28.0
END DESCRIPTION:
XS GIS Cut Line= 3
      3685649.61     10787010.19      3685149.61     10786610.19
       3684549.6     10786660.19
#Sta/Elev= 30
  4374.3  484.94  4395.9   483.9  4459.9  478.09  4495.2  479.68  4730.5   477.5
  4772.1  476.09  4780.1  476.73  4786.5  475.94  4794.5  477.15  4808.9  475.99
  4815.3  473.26  4822.5  472.33  4844.1  473.07  4850.5  471.39  4964.2  470.33
    4997  469.29  4999.8  468.79    5003  469.29  5044.7   471.7  5100.5  471.42
  5155.1  471.59  5192.7  473.08  5200.2  472.27  5265.5  472.63  5295.6  471.51
  5361.4  473.19  5486.2  477.51  5516.3  479.51  5546.4  480.08  5616.7  484.38
#Mann= 6 ,-1 , 0
  4374.3     .05       0    4997     .07       0    5003     .05       0
  5100.5      .1       0  5200.2     .08       0  5361.4     .05       0
Bank Sta=4997,5003
XS Rating Curve= 0 ,0
Exp/Cntr=0.3,0.1

Type RM Length L Ch R = 1 ,14523   ,474,474,474
BEGIN DESCRIPTION:
COON CREEK SOUTH TRIBUTARY 27.0
END DESCRIPTION:
XS GIS Cut Line= 4
      3685855.15     10786311.34        3685442.     10786271.41
      3685384.71     10786221.07      3685299.74     10785664.46
#Sta/Elev= 30
  4564.7  480.58  4600.4  479.22  4690.8  474.03  4761.2  471.39  4841.6  469.43
  4891.8  468.33  5038.8  467.25  5056.1   467.6  5074.2  466.88  5076.9  466.38
  5080.2  466.88  5186.3  469.13  5249.1  471.09  5269.4  472.45  5299.7  472.72
  5323.4   474.2  5360.4  475.13  5370.5  476.37  5380.6  476.64  5391.9  478.46
    5411  480.46  5481.8  484.66  5518.9  488.99    5524  488.69  5542.5  490.84
  5572.8  492.49  5582.4  493.89  5587.4  493.18  5593.1  494.16  5619.1  495.83
#Mann= 3 ,-1 , 0
  4564.7     .05       0  5074.2     .03       0  5080.2     .05       0
Bank Sta=4841.6,5186.3
XS Rating Curve= 0 ,0
Exp/Cntr=0.3,0.1

Type RM Length L Ch R = 1 ,14049   ,442,442,442
BEGIN DESCRIPTION:
COON CREEK SOUTH TRIBUTARY 26.0
END DESCRIPTION:
XS GIS Cut Line= 3
       3685849.6     10786210.18      3685699.61     10785960.19
      3685399.61     10785660.19
#Sta/Elev= 30
  4717.5  476.53  4740.8   475.8  4752.5  474.58  4762.2   474.4  4834.1   470.7
    4906  468.05  4950.7  466.34  4974.1  466.09  4985.7   466.4  4995.4  467.47
  4998.3  465.89    5001  465.39  5004.3  465.89  5006.1  466.83  5037.3  466.27
  5065.6  466.66  5079.7  467.33    5108  467.75  5122.2  468.41  5178.7  470.65
    5207  472.66  5263.6  475.63  5291.9  477.54    5306  479.66  5335.2  482.64
  5348.4  483.21  5390.9  487.17    5405  488.02  5429.8  491.62  5433.3  491.62
#Mann= 4 ,-1 , 0
  4717.5     .05       0  4998.3     .03       0  5004.3     .05       0
  5335.2     .16       0
Bank Sta=4906,5122.2
XS Rating Curve= 0 ,0
Exp/Cntr=0.3,0.1

Type RM Length L Ch R = 1 ,13607   ,454,454,454
BEGIN DESCRIPTION:
COON CREEK SOUTH TRIBUTARY 25.0
END DESCRIPTION:
XS GIS Cut Line= 3
      3686249.62     10785710.19      3685949.61     10785610.19
      3685649.58     10785510.18
#Sta/Elev= 30
  4668.5  484.82  4679.1  484.04  4689.6  482.48  4700.1  481.73  4721.2  478.87
  4731.8  478.46  4742.3  477.09  4805.5  472.26  4816.1  471.02  4847.7  469.47
  4879.3  467.26  4889.9  467.08  4900.4  466.36    4911  465.62  4942.6  464.45
  4971.2  463.82    4974  463.32  4977.2  463.82  4982.1  464.17  5016.4  464.13
  5026.9  464.87  5058.5  465.24  5079.6  466.05  5090.2  466.64  5174.5  468.86
    5185  469.65  5206.1  470.14  5216.6   470.8  5269.3  472.61    5301   474.1
#Mann= 3 ,-1 , 0
  4668.5     .05       0  4971.2     .03       0  4977.2     .05       0
Bank Sta=4900.4,5079.6
XS Rating Curve= 0 ,0
Exp/Cntr=0.3,0.1

Type RM Length L Ch R = 1 ,13153   ,447,447,447
BEGIN DESCRIPTION:
COON CREEK SOUTH TRIBUTARY 24.0
END DESCRIPTION:
XS GIS Cut Line= 3
      3686349.62      10785510.2      3686149.61     10785210.19
      3685599.58     10785210.19
#Sta/Elev= 30
  4615.1  477.93  4618.1  477.93  4622.6  476.85  4628.6  477.08  4643.7  475.46
  4651.2   475.2  4658.7  473.89  4679.7  473.11  4709.8  470.73  4787.9  467.13
  4817.9  466.23  4823.9  465.62  4926.1  462.88  4995.7  462.12  5002.7  460.55
  5005.4  460.05  5008.7  460.55  5015.7  462.12  5055.7  462.29  5065.7  463.01
  5165.7  465.51  5255.7  469.18  5395.7  472.39  5405.7  473.35  5435.7  474.48
  5445.7   475.6  5455.7  475.72  5475.7  477.89  5505.7  479.43  5525.7  479.44
#Mann= 3 ,-1 , 0
  4615.1     .05       0  5002.7     .03       0  5008.7     .05       0
Bank Sta=4926.1,5065.7
XS Rating Curve= 0 ,0
Exp/Cntr=0.3,0.1

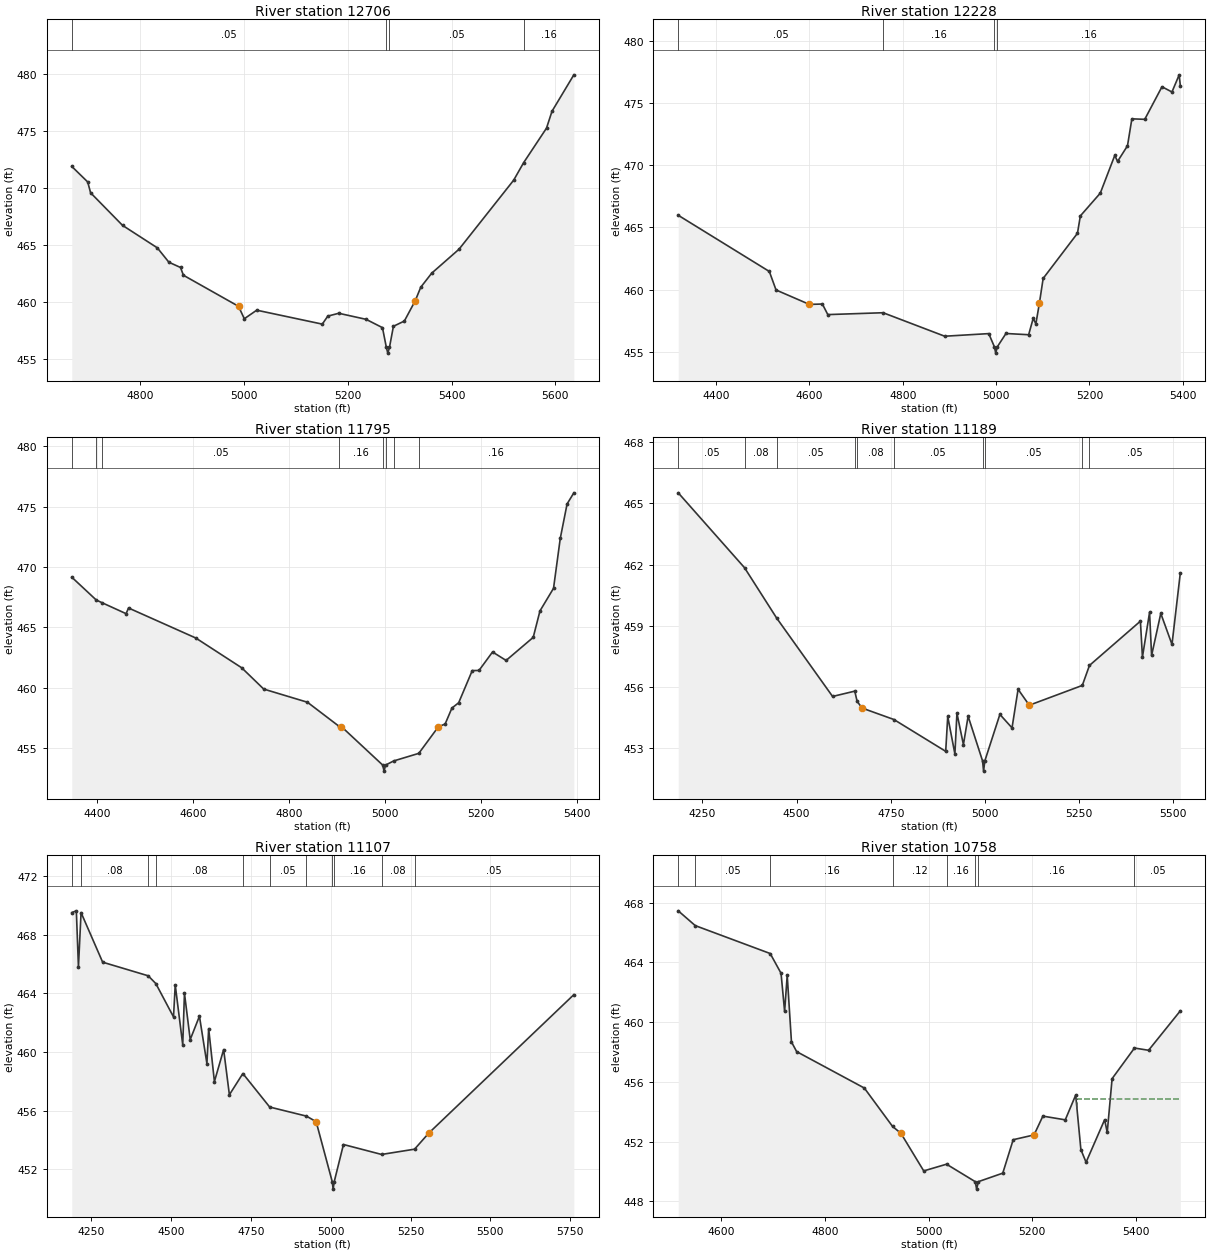
Type RM Length L Ch R = 1 ,12706   ,478,478,478
BEGIN DESCRIPTION:
COON CREEK SOUTH TRIBUTARY 23.0
END DESCRIPTION:
XS GIS Cut Line= 3
      3686599.59     10785210.15      3686449.61     10784910.19
      3686249.62     10784310.21
#Sta/Elev= 30
  4667.9  471.88  4698.6  470.52  4704.2  469.57  4765.7  466.72  4832.8  464.75
  4855.1  463.49  4877.5  463.03  4883.1  462.35  4989.3  459.63  5000.5  458.54
  5024.4  459.29  5150.8  458.07  5161.4  458.77  5182.5  459.02  5235.2  458.49
  5266.8  457.76  5274.3  456.03  5277.1  455.53  5280.3  456.03  5287.9  457.88
    5309  458.34    5330  460.12  5340.6   461.3  5361.7  462.53  5414.4  464.63
  5519.8  470.68  5538.8   472.2    5583  475.23  5593.6  476.71  5635.7   479.9
#Mann= 4 ,-1 , 0
  4667.9     .05       0  5274.3     .03       0  5280.3     .05       0
  5538.8     .16       0
Bank Sta=4989.3,5330
XS Rating Curve= 0 ,0
Exp/Cntr=0.3,0.1

Type RM Length L Ch R = 1 ,12228   ,433,433,433
BEGIN DESCRIPTION:
COON CREEK SOUTH TRIBUTARY 22.0
END DESCRIPTION:
XS GIS Cut Line= 3
      3686984.24     10785237.25      3686803.69      10784633.1
      3686574.56     10784251.22
#Sta/Elev= 30
  4318.8  465.98    4514  461.46  4528.4  459.97  4599.8  458.81  4627.7  458.84
  4639.3  457.99  4757.8  458.14  4889.8  456.25  4984.2  456.46  4996.4  455.39
  4999.1  454.89  5002.4  455.39  5021.1  456.47  5069.7  456.37  5079.4  457.68
  5085.2  457.25  5092.7   458.9  5100.8   460.9  5174.3  464.53  5180.5  465.93
  5223.2  467.76  5254.3   470.8  5260.2  470.31  5281.5  471.57  5290.9  473.74
  5318.5   473.7  5355.4  476.32  5376.8   475.9  5392.3  477.28  5394.7  476.41
#Mann= 4 ,-1 , 0
  4318.8     .05       0  4757.8     .16       0  4996.4     .07       0
  5002.4     .16       0
Bank Sta=4599.8,5092.7
XS Rating Curve= 0 ,0
Exp/Cntr=0.3,0.1

Type RM Length L Ch R = 1 ,11795   ,606,606,606
BEGIN DESCRIPTION:
COON CREEK SOUTH TRIBUTARY 21.0
END DESCRIPTION:
XS GIS Cut Line= 3
      3687095.36     10785125.26      3687199.61     10784510.19
      3686899.62      10784210.2
#Sta/Elev= 30
  4346.3  469.16  4397.4  467.27  4410.4  467.03  4459.7  466.14  4464.8  466.61
    4605  464.13  4701.1  461.66    4747   459.9  4838.3  458.81  4904.2  456.82
  4909.3  456.79  4995.4  453.61  4998.2  453.11  5001.4  453.61  5018.1  453.95
  5070.7  454.58  5111.6  456.78  5125.7  457.01  5139.9  458.33    5154  458.77
  5182.3  461.43  5196.4  461.44  5224.7  462.97    5253  462.27  5309.6  464.18
  5323.7  466.37    5352  468.24  5366.1  472.38  5380.3  475.22  5394.4  476.14
#Mann= 8 ,-1 , 0
  4346.3     .05       0  4397.4     .08       0  4410.4     .05       0
  4904.2     .16       0  4995.4     .07       0  5001.4     .16       0
  5018.1     .12       0  5070.7     .16       0
Bank Sta=4909.3,5111.6
XS Rating Curve= 0 ,0
Exp/Cntr=0.3,0.1

Type RM Length L Ch R = 1 ,11189   ,82,82,82
BEGIN DESCRIPTION:
COON CREEK SOUTH TRIBUTARY 19.0
END DESCRIPTION:
XS GIS Cut Line= 2
      3687253.34     10784824.08      3687742.79     10783584.83
#Sta/Elev= 30
  4186.1  465.52    4362  461.85    4447  459.39  4595.7  455.54  4654.6   455.8
  4660.8   455.3  4674.1  454.97  4758.4  454.41  4895.9  452.85  4901.3  454.56
  4920.3  452.72  4925.7  454.72  4942.9  453.18  4955.4  454.57  4993.7  452.38
  4996.4  451.88  4999.7  452.38  5039.7  454.66  5071.9     454    5088  455.89
  5117.7  455.11  5258.4  456.08  5277.4  457.06  5412.6  459.23    5418  457.47
  5436.9  459.66  5442.3  457.55  5466.7  459.61  5496.4  458.09  5518.5  461.59
#Mann= 10 ,-1 , 0
  4186.1     .05       0    4362     .08       0    4447     .05       0
  4654.6     .12       0  4660.8     .08       0  4758.4     .05       0
  4993.7     .04       0  4999.7     .05       0  5258.4     .08       0
  5277.4     .05       0
Bank Sta=4674.1,5117.7
XS Rating Curve= 0 ,0
Exp/Cntr=0.3,0.1

Type RM Length L Ch R = 1 ,11107   ,349,349,349
BEGIN DESCRIPTION:
COON CREEK SOUTH TRIBUTARY 18.0
END DESCRIPTION:
XS GIS Cut Line= 4
      3687315.82     10784803.28      3687593.62     10784164.35
      3687798.48     10783622.69      3687902.58     10783345.08
#Sta/Elev= 30
  4189.2  469.53  4203.5  469.65  4210.1  465.82  4218.3  469.53  4285.9  466.14
  4428.5  465.21  4452.4  464.68  4507.8   462.4  4513.2  464.59  4536.7  460.49
  4542.1  464.02  4560.1  460.85    4589  462.45  4612.4  459.21  4617.9   461.6
  4635.9  457.98  4664.8  460.17  4682.8  457.08    4725  458.53    4809  456.24
    4924  455.62  4954.5  455.24    5005  451.13  5007.7  450.63    5011  451.13
    5040  453.68  5159.4     453  5262.7  453.36  5307.3  454.46  5761.5  463.92
#Mann= 11 ,-1 , 0
  4189.2     .05       0  4218.3     .08       0  4428.5     .05       0
  4452.4     .08       0    4725     .16       0    4809     .05       0
    4924     .16       0    5005     .07       0    5011     .16       0
  5159.4     .08       0  5262.7     .05       0
Bank Sta=4954.5,5307.3
XS Rating Curve= 0 ,0
Exp/Cntr=0.3,0.1

Type RM Length L Ch R = 1 ,10758   ,334,334,334
BEGIN DESCRIPTION:
Mapping XS b34db8c0
END DESCRIPTION:
XS GIS Cut Line= 4
       3687895.7     10784327.53      3687930.42     10783949.07
      3687888.76     10783817.13      3687926.96     10783369.17
#Sta/Elev= 30
  4517.3  467.46  4550.1  466.47  4694.6   464.6  4715.5  463.28  4722.4  460.72
  4727.4  463.14  4735.6  458.68  4745.6  458.03  4876.1  455.59  4930.5  453.02
  4946.6  452.56  4990.6  450.04  5034.6  450.49  5089.9  449.32  5092.6  448.82
  5095.9  449.32    5143  449.89  5163.1  452.13  5203.3  452.45  5220.3  453.71
  5263.5  453.46  5283.6  455.12  5293.6  451.47  5303.6  450.62  5339.4  453.47
  5344.4  452.62  5353.8  456.22  5396.9  458.27  5424.1  458.12  5485.3  460.76
#Mann= 8 ,-1 , 0
  4517.3     .16       0  4550.1     .05       0  4694.6     .16       0
  4930.5     .12       0  5034.6     .16       0  5089.9     .07       0
  5095.9     .16       0  5396.9     .05       0
#XS Ineff= 2 , 0
                         5285.91          454.88
Permanent Ineff=
       F       F
Bank Sta=4946.6,5203.3
XS Rating Curve= 0 ,0
Exp/Cntr=0.3,0.1

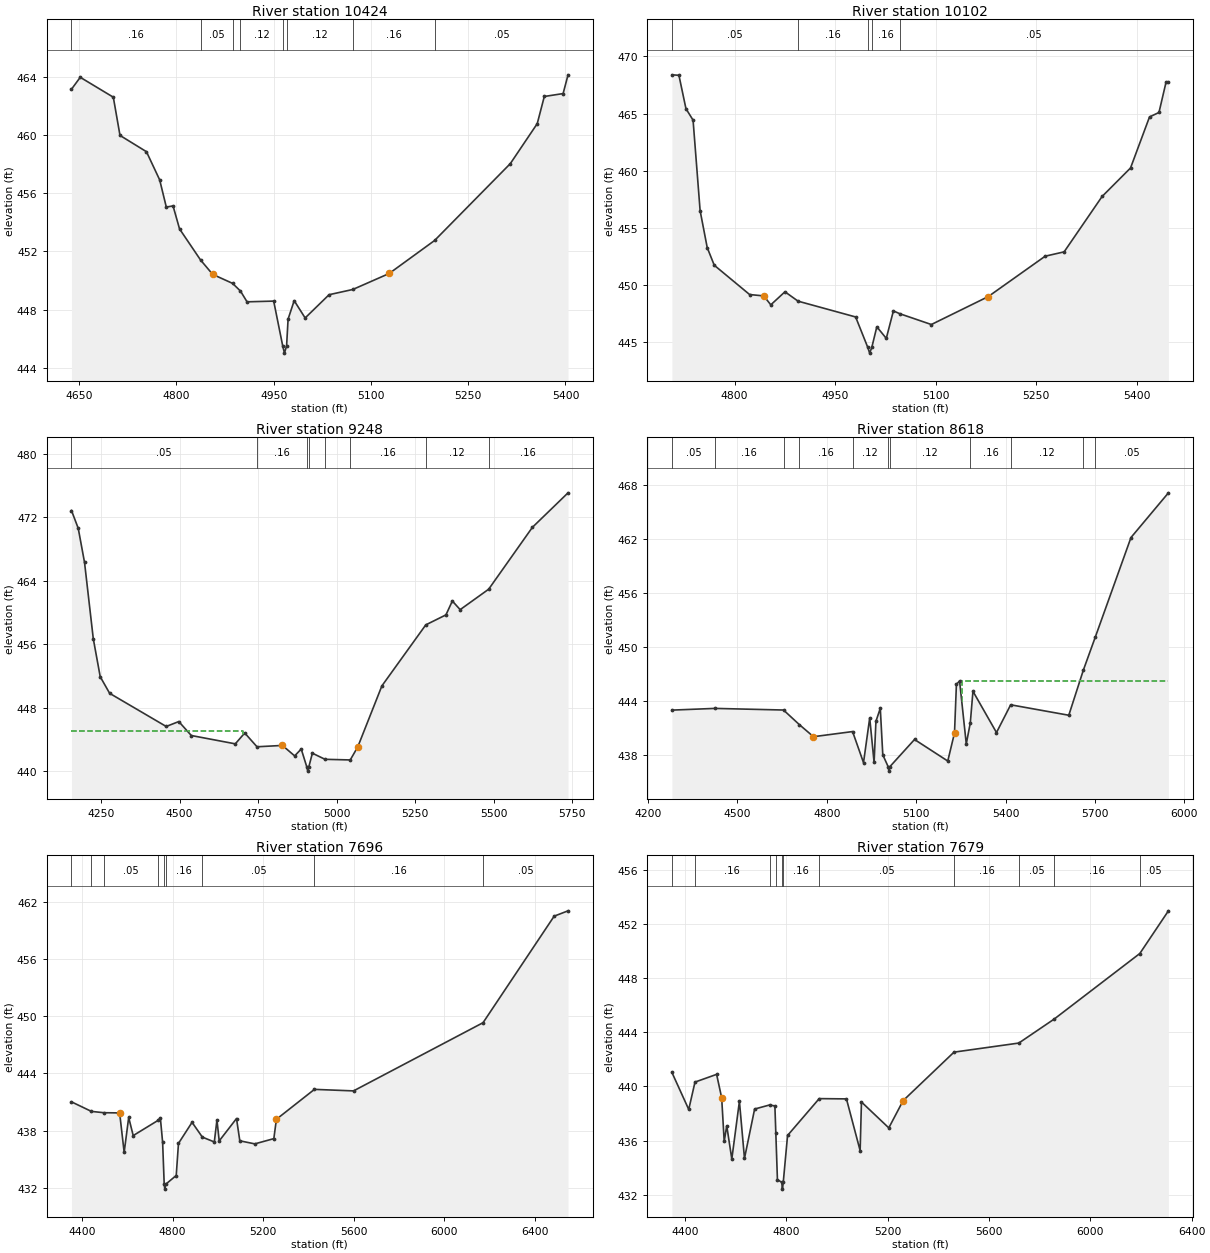
Type RM Length L Ch R = 1 ,10424   ,322,322,322
BEGIN DESCRIPTION:
Mapping XS dcf60202
END DESCRIPTION:
XS GIS Cut Line= 4
      3688104.03     10783973.41      3688152.65     10783737.27
      3688097.09      10783570.6      3688003.53     10783234.46
#Sta/Elev= 30
  4638.3  463.16  4651.8  463.98  4702.8  462.61  4713.1  459.98  4753.9  458.86
  4774.3  456.92  4784.5  455.05  4794.9  455.13  4804.9  453.55  4837.3  451.41
    4856  450.42  4886.7   449.8  4898.9  449.27    4909  448.53  4950.1  448.58
    4964   445.5  4966.7     445    4970   445.5  4972.3  447.34  4981.7  448.61
  4998.6  447.42  5035.5  449.02  5072.1  449.38  5128.2  450.48  5198.2  452.75
    5315  458.04  5356.5  460.79  5367.4  462.66  5396.4  462.86    5404  464.15
#Mann= 8 ,-1 , 0
  4638.3     .16       0  4837.3     .05       0  4886.7     .16       0
  4898.9     .12       0    4964     .07       0    4970     .12       0
  5072.1     .16       0  5198.2     .05       0
Bank Sta=4856,5128.2
XS Rating Curve= 0 ,0
Exp/Cntr=0.3,0.1

Type RM Length L Ch R = 1 ,10102   ,854,854,854
BEGIN DESCRIPTION:
COON CREEK SOUTH TRIBUTARY 17.0
END DESCRIPTION:
XS GIS Cut Line= 3
      3688649.57     10783560.18      3688349.61     10783460.19
      3688049.64     10783160.22
#Sta/Elev= 30
  4706.6  468.39  4717.1  468.35  4727.6  465.43  4738.2  464.43  4748.7  456.52
  4759.3  453.29  4769.8  451.75  4822.5  449.19  4843.6  449.07  4854.1  448.29
  4875.2  449.43  4894.8  448.61  4980.6  447.23  4998.7  444.57  5001.5  444.07
  5004.7  444.57  5012.2  446.37  5026.3  445.36  5036.9  447.76  5046.6  447.51
  5093.5  446.57  5178.3  449.01  5263.2  452.54  5291.5  452.92  5348.1  457.76
  5390.5  460.25  5418.8  464.71  5432.9   465.1  5443.5  467.76    5447  467.76
#Mann= 5 ,-1 , 0
  4706.6     .05       0  4894.8     .16       0  4998.7     .07       0
  5004.7     .16       0  5046.6     .05       0
Bank Sta=4843.6,5178.3
XS Rating Curve= 0 ,0
Exp/Cntr=0.3,0.1

Type RM Length L Ch R = 1 ,9248    ,630,630,630
BEGIN DESCRIPTION:
Mapping XS 5c33fd69
END DESCRIPTION:
XS GIS Cut Line= 4
      3688875.95     10783581.69      3688862.93     10782882.89
      3688671.96       10782744.      3688038.31     10782618.13
#Sta/Elev= 30
    4156  472.88  4177.5  470.63  4197.5  466.34  4225.4  456.71  4247.5  451.92
  4277.5  449.83  4457.6  445.65  4497.6  446.27  4537.6  444.51  4677.6  443.46
  4707.6  444.83  4746.7  443.09  4827.6  443.26  4866.6  441.94  4887.5  442.81
  4905.5  440.52  4908.3  440.02  4911.5  440.52    4923  442.28  4963.3  441.51
  5043.6  441.43  5067.6  443.08  5144.4  450.77  5284.1  458.46  5348.3  459.72
  5368.7  461.47  5393.6  460.38  5484.4  462.96  5623.6  470.76  5737.1  475.11
#Mann= 8 ,-1 , 0
    4156     .05       0  4746.7     .16       0  4905.5     .07       0
  4911.5     .16       0  4963.3     .12       0  5043.6     .16       0
  5284.1     .12       0  5484.4     .16       0
#XS Ineff= 2 , 0
         4702.87  445.14
Permanent Ineff=
       F       F
Bank Sta=4827.6,5067.6
XS Rating Curve= 0 ,0
Exp/Cntr=0.3,0.1

Type RM Length L Ch R = 1 ,8618    ,922,922,922
BEGIN DESCRIPTION:
Mapping XS e001c83d
END DESCRIPTION:
XS GIS Cut Line= 4
      3689388.62     10783019.11      3689098.67     10782506.92
      3688961.51     10782321.16      3688199.37     10781951.37
#Sta/Elev= 30
  4279.9  443.03  4424.3  443.22  4654.6  443.04  4707.4  441.43  4755.2  440.08
  4886.4  440.65  4923.1   437.2  4943.9  442.16  4958.6  437.22  4964.8  441.79
  4979.4  443.23  4987.8  438.07  5005.7  436.76  5008.4  436.26  5011.7  436.76
  5094.3  439.77  5205.9  437.38  5228.5   440.5  5234.9  445.88  5245.5  446.27
    5268  439.28  5281.5  441.61  5290.4  445.12  5369.4  440.54    5417  443.62
  5612.1  442.46    5661  447.47  5700.9  451.12  5820.8  462.18  5946.5  467.14
#Mann= 11 ,-1 , 0
  4279.9     .05       0  4424.3     .16       0  4654.6     .05       0
  4707.4     .16       0  4886.4     .12       0  5005.7     .07       0
  5011.7     .12       0  5281.5     .16       0    5417     .12       0
    5661     .16       0  5700.9     .05       0
#XS Ineff= 2 , 0
                          5253.2          446.29
Permanent Ineff=
       F       F
Bank Sta=4755.2,5228.5
XS Rating Curve= 0 ,0
Exp/Cntr=0.3,0.1

Type RM Length L Ch R = 1 ,7696    ,17,17,17
BEGIN DESCRIPTION:
COON CREEK SOUTH TRIBUTARY 15.0
END DESCRIPTION:
XS GIS Cut Line= 5
      3689773.98     10782802.97      3689763.56     10782188.35
      3689768.77     10782089.39      3689737.52      10781969.6
      3688383.94     10781870.68
#Sta/Elev= 30
  4353.1  441.01    4441  440.01    4496  439.87  4565.9  439.85  4585.9  435.71
  4605.9  439.37  4625.9  437.47  4735.3  439.06  4745.9  439.32  4755.9  436.77
  4762.9  432.35  4765.7  431.85  4768.9  432.35    4816  433.28    4826  436.65
    4886  438.86  4931.5  437.31  4984.4   436.8    4996  439.11    5006  436.91
  5082.5  439.26  5097.1  436.92  5163.4   436.6  5247.5  437.15  5258.8  439.18
  5426.9  442.32  5599.7  442.16  6172.3  449.32  6486.6   460.5  6547.9  461.06
#Mann= 9 ,-1 , 0
  4353.1     .05       0    4441     .16       0    4496     .05       0
  4735.3     .16       0  4762.9    .033       0  4768.9     .16       0
  4931.5     .05       0  5426.9     .16       0  6172.3     .05       0
Bank Sta=4565.9,5258.8
XS Rating Curve= 0 ,0
Exp/Cntr=0.3,0.1

Type RM Length L Ch R = 1 ,7679    ,26,26,26
BEGIN DESCRIPTION:
Mapping XS e42430f0
END DESCRIPTION:
XS GIS Cut Line= 6
      3689784.05      10782806.7      3689780.58     10782185.22
      3689784.05     10782129.67      3689787.52     10782074.11
       3689752.8     10781949.11      3688659.02     10781865.78
#Sta/Elev= 30
  4348.8  441.04  4415.3   438.3    4440  440.32  4525.3  440.89  4545.3  439.16
  4555.3  435.94  4565.3   437.1  4585.3  434.64  4615.3   438.9  4635.3  434.69
  4675.3  438.33  4734.1  438.63  4755.3  438.56    4759  436.55  4765.3  433.13
  4782.3  432.92  4785.1  432.42  4788.3  432.92  4805.3  436.38  4930.2   439.1
  5037.7  439.08  5091.7  435.26  5096.9  438.85  5204.8  436.94  5261.3  438.95
  5462.1  442.53  5717.8   443.2  5858.1  444.98  6195.4  449.81  6308.3  452.96
#Mann= 11 ,-1 , 0
  4348.8     .05       0    4440     .16       0  4734.1     .05       0
    4759     .16       0  4782.3    .033       0  4788.3     .16       0
  4930.2     .05       0  5462.1     .16       0  5717.8     .05       0
  5858.1     .16       0  6195.4     .05       0
Bank Sta=4545.3,5261.3
XS Rating Curve= 0 ,0
Exp/Cntr=0.3,0.1

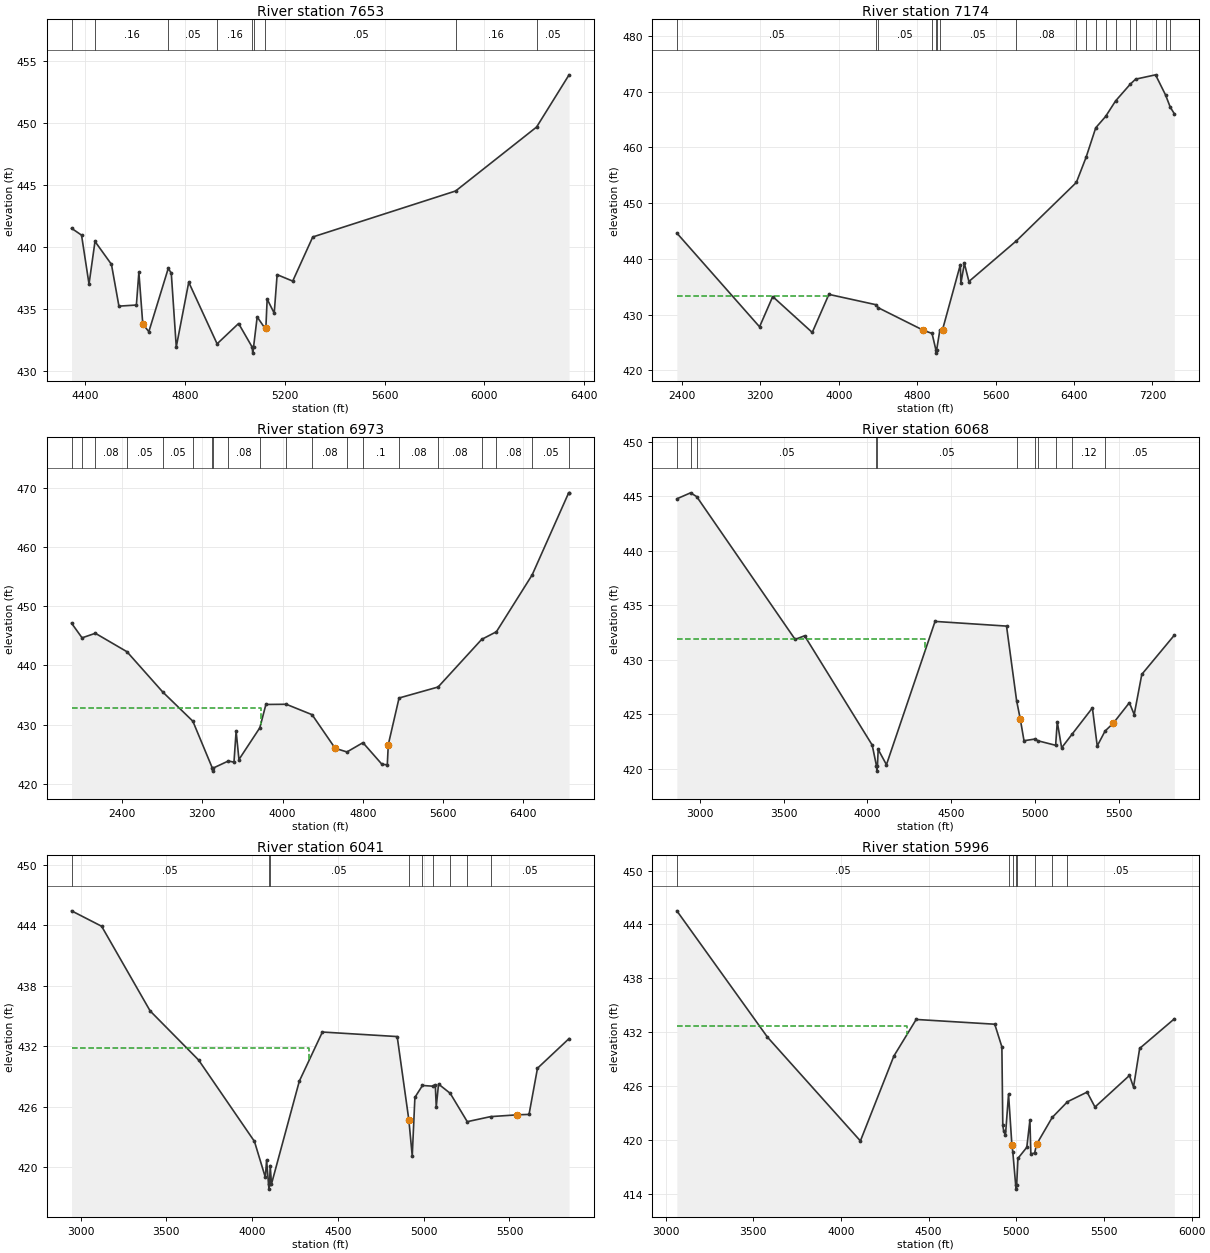
Type RM Length L Ch R = 1 ,7653    ,479,479,479
BEGIN DESCRIPTION:
Mapping XS ccf6839f
END DESCRIPTION:
XS GIS Cut Line= 5
      3689801.41     10782810.27      3689808.35      10782188.7
      3689808.35     10782081.06      3689770.16      10781938.7
      3688655.55       10781838.
#Sta/Elev= 30
  4344.3  441.53  4384.4  440.98  4414.4  437.03  4438.4  440.47  4504.4  438.62
  4534.4  435.25  4604.4  435.34  4614.4  437.98  4630.1   433.8  4654.4  433.19
  4732.3   438.3  4744.4  437.91  4764.4  431.96  4814.4  437.18  4928.2  432.21
  5014.4  433.85  5068.5  431.96  5071.2  431.46  5074.5  431.96    5089  434.38
  5122.1  433.41  5123.8  433.48    5129  435.82  5157.3  434.68    5169  437.79
  5231.5  437.27  5311.9  440.83  5885.1  444.54  6209.9   449.7  6340.1  453.91
#Mann= 9 ,-1 , 0
  4344.3     .05       0  4438.4     .16       0  4732.3     .05       0
  4928.2     .16       0  5068.5     .07       0  5074.5     .16       0
  5122.1     .05       0  5885.1     .16       0  6209.9     .05       0
Bank Sta=4630.1,5123.8
XS Rating Curve= 0 ,0
Exp/Cntr=0.3,0.1

Type RM Length L Ch R = 1 ,7174    ,201,201,201
BEGIN DESCRIPTION:
COON CREEK SOUTH TRIBUTARY 14.0
END DESCRIPTION:
XS GIS Cut Line= 6
      3692156.76     10783576.19      3690656.74     10782124.78
      3690219.24     10781958.12      3689781.74     10781847.01
      3688469.24     10781756.73      3687746.99     10781548.39
#Sta/Elev= 30
  2348.8  444.64  3192.5  427.82  3326.8  433.25  3729.9  426.81  3899.6  433.64
  4378.9  431.79  4402.5  431.25    4862  427.21  4952.1  426.63  4992.1   423.6
  4994.9   423.1  4998.1   423.6  5031.1  427.17  5059.3  427.33  5240.8  438.98
    5246  435.62  5281.8   439.2  5327.9  435.95  5813.2  443.26  6423.8  453.72
  6522.8  458.22  6621.7  463.53  6722.2  465.56  6824.1  468.35  6973.1  471.34
  7027.9  472.25  7231.7  473.03  7333.6  469.42  7381.6  467.23  7423.6  466.04
#Mann= 18 ,-1 , 0
  2348.8     .05       0  4378.9     .08       0  4402.5     .05       0
  4952.1      .1       0  4992.1     .07       0  4998.1      .1       0
  5031.1     .05       0  5813.2     .08       0  6423.8     .05       0
  6522.8     .08       0  6621.7     .05       0  6722.2     .08       0
  6824.1     .05       0  6973.1     .08       0  7027.9      .1       0
  7231.7     .08       0  7333.6     .05       0  7381.6      .1       0
#XS Ineff= 2 , 0
         3877.97  433.41
Permanent Ineff=
       F       F
Bank Sta=4862,5059.3
XS Rating Curve= 0 ,0
Exp/Cntr=0.3,0.1

Type RM Length L Ch R = 1 ,6973    ,905,905,905
BEGIN DESCRIPTION:
COON CREEK SOUTH TRIBUTARY 13.0
END DESCRIPTION:
XS GIS Cut Line= 6
      3692682.08     10783667.08      3691175.16     10782215.71
      3690763.84     10781998.07      3690135.37     10781749.81
      3689734.25     10781677.47      3688424.53     10781549.89
#Sta/Elev= 30
  1897.2  447.14    2002  444.66  2134.5  445.43  2449.7  442.31    2806  435.51
  3106.3  430.57    3301  422.63  3303.8  422.13    3307  422.63  3459.7  423.84
  3516.3  423.65  3537.6  428.89  3565.9  424.09    3774  429.46  3834.5   433.4
  4037.6  433.43  4294.9  431.67  4524.9  425.99  4642.2  425.37  4801.9  426.94
  4991.9  423.27  5044.6  423.21  5054.4  426.61  5161.8  434.49    5551  436.35
  5985.4   444.4  6132.2  445.69  6488.5   455.3  6852.4  469.17  6856.3  469.09
#Mann= 20 ,-1 , 0
  1897.2     .08       0    2002     .08       0  2134.5     .08       0
  2449.7     .05       0    2806     .05       0  3106.3     .08       0
    3301     .07       0    3307     .05       0  3459.7     .08       0
    3774     .05       0  4037.6     .08       0  4294.9     .08       0
  4642.2     .08       0  4801.9      .1       0  5161.8     .08       0
    5551     .08       0  5985.4      .1       0  6132.2     .08       0
  6488.5     .05       0  6852.4     .08       0
#XS Ineff= 2 , 0
         3782.18  432.78
Permanent Ineff=
       F       F
Bank Sta=4524.9,5054.4
XS Rating Curve= 0 ,0
Exp/Cntr=0.3,0.1

Type RM Length L Ch R = 1 ,6068    ,27,27,27
BEGIN DESCRIPTION:
Mapping XS 2d1eef0d
END DESCRIPTION:
XS GIS Cut Line= 6
      3692475.02     10783392.63      3691162.05     10782005.88
      3691116.48     10781819.25       3691086.1     10781760.66
      3690790.96     10781715.08      3690348.24     10781478.53
#Sta/Elev= 30
  2862.9  444.76  2944.8  445.31  2981.4  444.96  3568.6  431.86  3625.2  432.19
  4028.5  422.16  4053.8  420.27  4056.6  419.77  4059.8  420.27  4064.1  421.76
  4113.5  420.36  4403.5  433.51  4829.9  433.08  4890.1  426.23  4912.3  424.52
  4934.2  422.56  5001.8  422.72  5015.9  422.56  5122.9  422.14  5132.7  424.29
  5158.7  421.91  5222.5  423.19  5342.2  425.57  5371.1  422.08  5417.9  423.45
  5466.9  424.17  5562.9  426.05  5591.7  424.96    5637  428.65  5831.3  432.25
#Mann= 11 ,-1 , 0
  2862.9     .05       0  2944.8     .08       0  2981.4     .05       0
  4053.8     .07       0  4059.8     .05       0  4890.1     .16       0
  5001.8     .07       0  5015.9     .12       0  5122.9     .16       0
  5222.5     .12       0  5417.9     .05       0
#XS Ineff= 2 , 0
         4342.89  431.86
Permanent Ineff=
       F       F
Bank Sta=4912.3,5466.9
XS Rating Curve= 0 ,0
Exp/Cntr=0.3,0.1

Type RM Length L Ch R = 1 ,6041    ,45,45,45
BEGIN DESCRIPTION:
Mapping XS 3b02e151
END DESCRIPTION:
XS GIS Cut Line= 6
      3692457.63     10783310.14      3691183.75      10781997.2
      3691116.48     10781756.32      3691062.23      10781728.1
      3690799.64     10781693.38      3690366.11     10781454.94
#Sta/Elev= 30
  2946.9  445.42  3122.3  443.89  3405.2  435.49  3687.9  430.62  4013.3  422.55
  4076.9  418.98  4084.1  420.72  4095.2  418.32    4098  417.82  4101.2  418.32
  4105.2  420.16  4112.4  418.32  4274.9  428.53  4409.4   433.4  4845.5  432.95
  4913.4  424.69  4933.2   421.1  4948.7  426.92  4992.8   428.1    5052  428.03
  5067.6  428.17  5073.2  425.97  5086.5  428.24  5154.6  427.32    5254  424.51
  5389.9  425.01  5546.8  425.19  5614.1  425.23  5663.4  429.81  5847.5  432.75
#Mann= 9 ,-1 , 0
  2946.9     .05       0  4095.2     .07       0  4101.2     .05       0
  4913.4     .16       0  4992.8     .07       0    5052     .12       0
  5154.6     .16       0    5254     .12       0  5389.9     .05       0
#XS Ineff= 2 , 0
         4332.21  431.77
Permanent Ineff=
       F       F
Bank Sta=4913.4,5546.8
XS Rating Curve= 0 ,0
Exp/Cntr=0.3,0.1

Type RM Length L Ch R = 1 ,5996    ,62,62,62
BEGIN DESCRIPTION:
Mapping XS 8af6c230
END DESCRIPTION:
XS GIS Cut Line= 6
      3692418.58     10783201.65      3691214.14     10781999.37
      3691166.39      10781749.8      3691138.18     10781721.59
      3690777.94     10781665.17      3690369.98     10781419.96
#Sta/Elev= 30
  3064.1  445.52  3580.6  431.48  4110.9  419.93  4301.8  429.37  4429.1  433.44
  4877.1  432.91  4917.8  430.39    4923  421.66  4928.1  421.04  4938.2  420.56
  4955.8  425.13    4975  419.46  4979.9  418.75  4996.3  415.07    4999  414.57
  5002.3  415.07  5009.4  417.99  5059.9  419.22  5077.7  422.24    5083  418.49
  5104.6  418.58  5115.5  419.55  5204.8  422.54    5292  424.29  5403.7  425.36
  5448.8   423.7  5645.3  427.21  5668.6  425.92  5703.6  430.22  5901.5  433.51
#Mann= 8 ,-1 , 0
  3064.1     .05       0  4955.8     .16       0  4979.9     .07       0
  4996.3     .07       0  5002.3     .07       0  5104.6     .12       0
  5204.8     .16       0    5292     .05       0
#XS Ineff= 2 , 0
         4376.45  432.68
Permanent Ineff=
       F       F
Bank Sta=4975,5115.5
XS Rating Curve= 0 ,0
Exp/Cntr=0.3,0.1