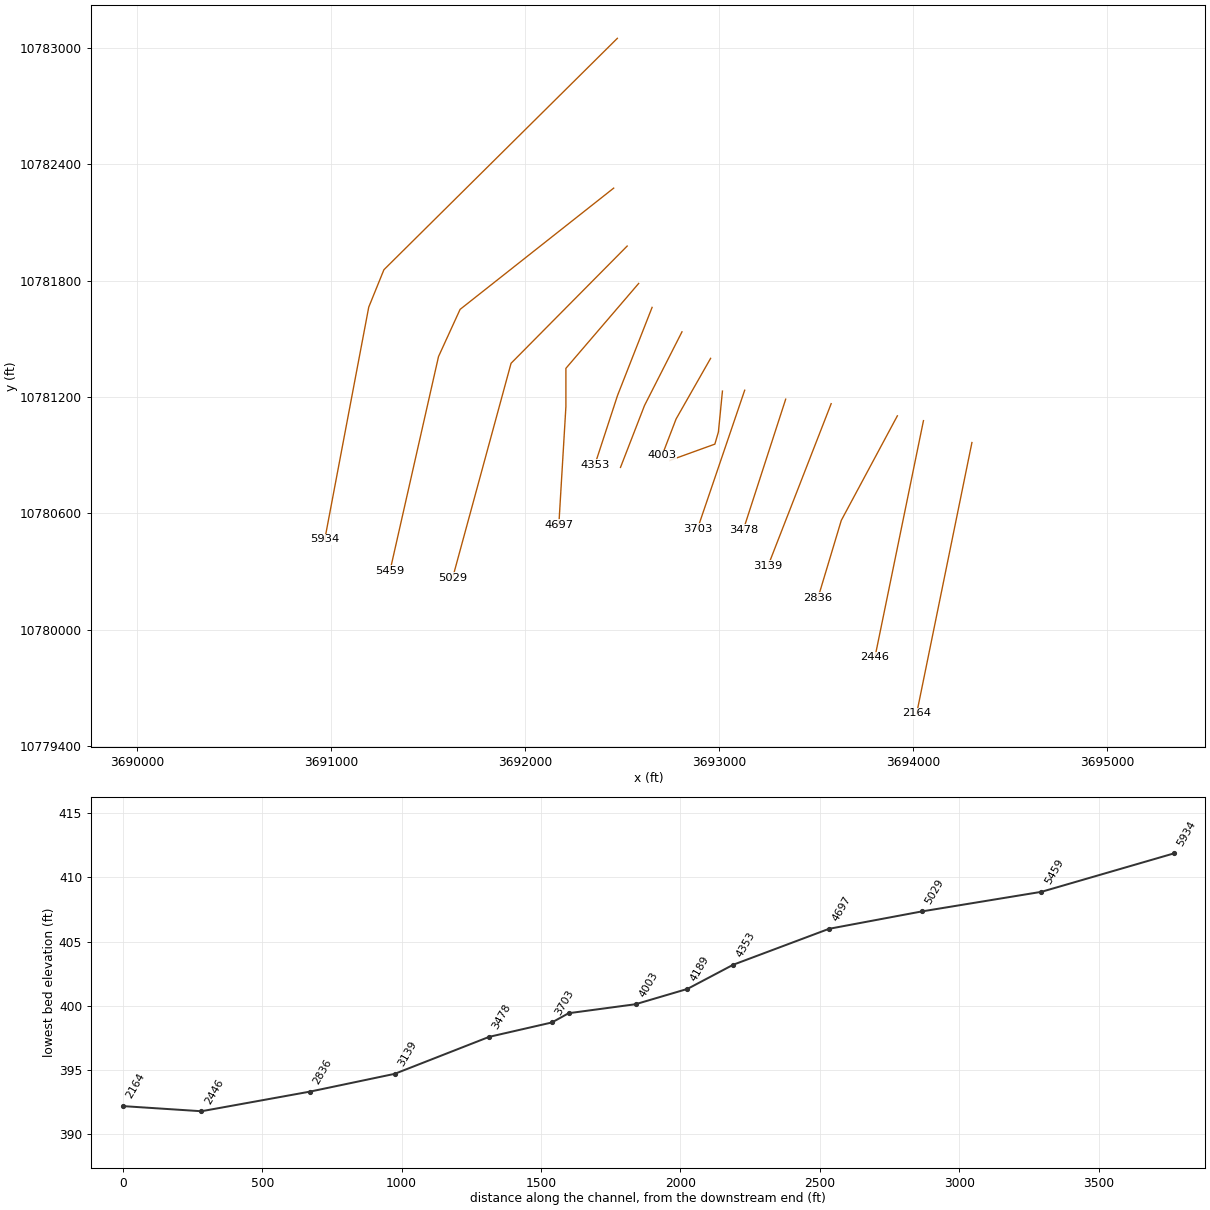
HEC-RAS study COON CREEK SOUTH TRIBUTARY.prj: COON CREEK SOUTH TRIBUTARY Base Level Engineering

--- COON CREEK SOUTH TRIBUTARY.g01 (geometry) --- (continued)

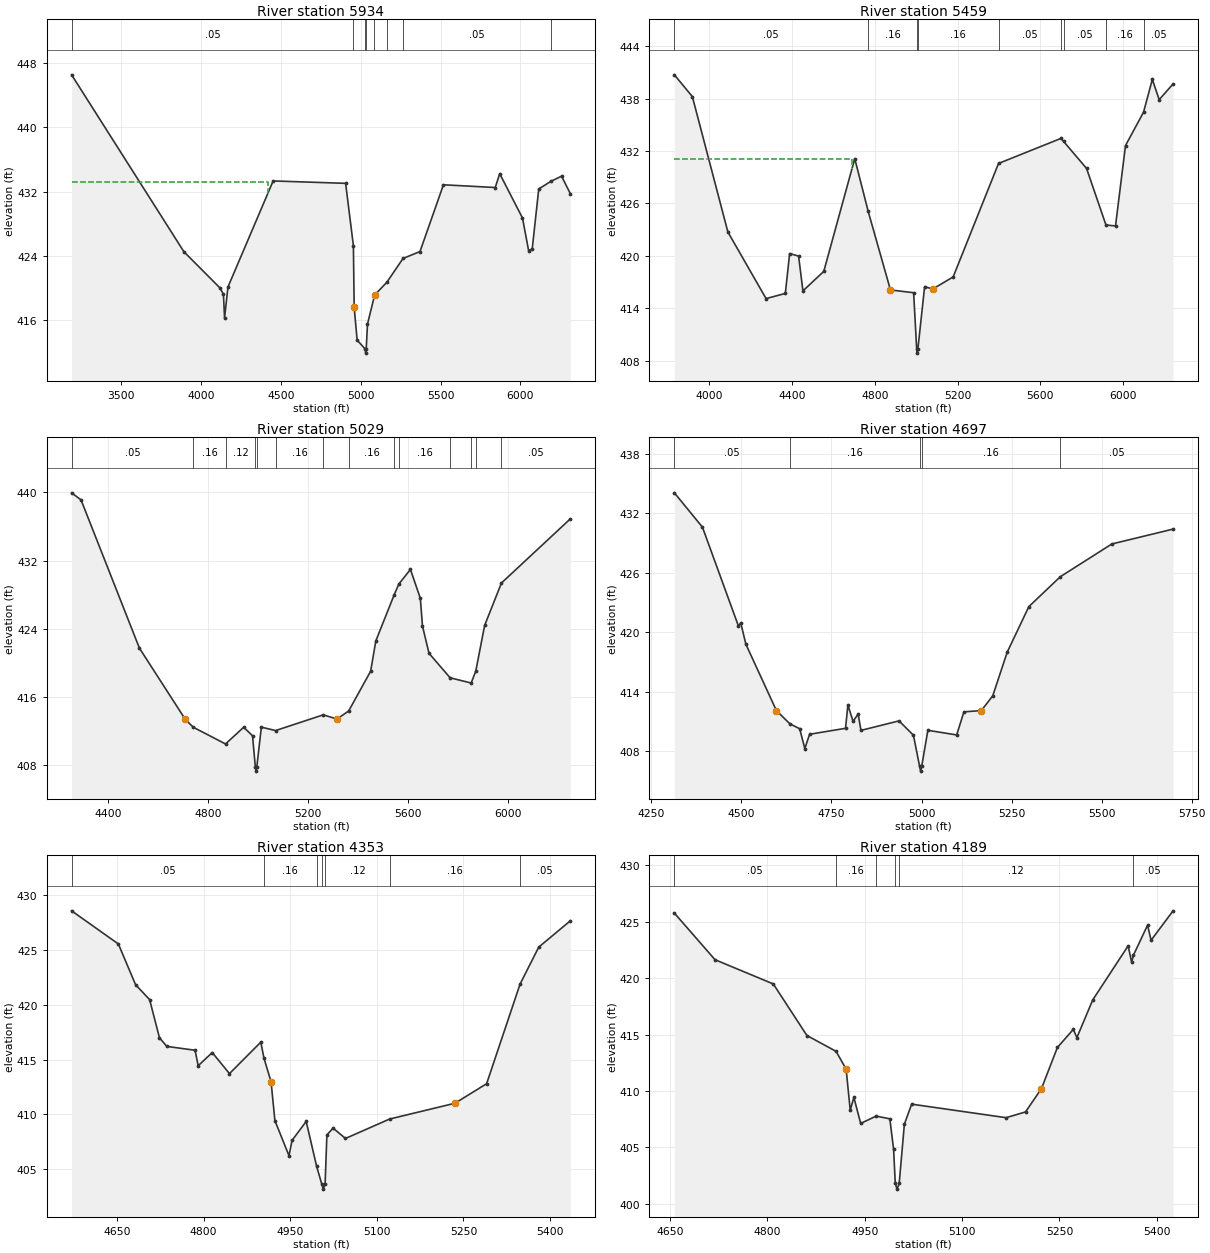
Type RM Length L Ch R = 1 ,5934    ,475,475,475
BEGIN DESCRIPTION:
COON CREEK SOUTH TRIBUTARY 11.0
END DESCRIPTION:
XS GIS Cut Line= 4
      3692474.61     10783048.58      3691271.47     10781855.86
      3691193.34     10781663.15      3690966.79     10780466.19
#Sta/Elev= 30
  3191.6  446.56    3894  424.51  4120.3  419.98  4141.6  419.19  4148.6  416.25
  4169.8   420.1  4452.6  433.33    4906  433.03  4954.7  425.26  4959.6  417.57
  4978.2  413.48  5028.9  412.36  5031.7  411.86  5034.9  412.36  5042.9  415.48
  5086.7  419.03  5090.9  419.17  5164.6  420.71  5265.1  423.66  5371.5  424.53
  5518.1  432.85  5842.2  432.51  5870.2  434.23  6012.7  428.71  6051.5   424.6
  6073.7  424.88  6114.5  432.33    6192   433.3  6256.9  433.92  6311.9  431.76
#Mann= 8 ,-1 , 0
  3191.6     .05       0  4954.7     .16       0  5028.9     .07       0
  5034.9     .16       0  5086.7     .07       0  5164.6     .16       0
  5265.1     .05       0    6192     .16       0
#XS Ineff= 2 , 0
         4417.94  433.24
Permanent Ineff=
       F       F
Bank Sta=4959.6,5090.9
XS Rating Curve= 0 ,0
Exp/Cntr=0.3,0.1

Type RM Length L Ch R = 1 ,5459    ,430,430,430
BEGIN DESCRIPTION:
COON CREEK SOUTH TRIBUTARY 10.0
END DESCRIPTION:
XS GIS Cut Line= 4
      3692455.75     10782276.56       3691664.1     10781651.58
      3691552.99     10781408.53       3691303.1     10780304.82
#Sta/Elev= 30
  3832.8  440.71  3919.6  438.22  4091.1  422.73  4275.5  415.11  4368.5   415.7
  4389.3  420.26  4432.6  419.97  4453.4  415.99  4554.1  418.22  4703.6  431.12
  4768.6  425.08  4875.9   416.1  4987.9  415.78  5002.5  409.37  5005.2  408.87
  5008.5  409.37  5040.9  416.48    5080   416.2  5178.7  417.59  5397.7  430.57
  5699.5  433.44  5711.5   433.1  5822.7     430  5916.3  423.53  5962.4  423.42
  6010.7  432.62  6097.8  436.44  6140.1  440.18  6173.3  437.87  6240.3  439.67
#Mann= 9 ,-1 , 0
  3832.8     .05       0  4768.6     .16       0  5002.5     .07       0
  5008.5     .16       0  5397.7     .05       0  5699.5     .16       0
  5711.5     .05       0  5916.3     .16       0  6097.8     .05       0
#XS Ineff= 2 , 0
         4689.75  431.03
Permanent Ineff=
       F       F
Bank Sta=4875.9,5080
XS Rating Curve= 0 ,0
Exp/Cntr=0.3,0.1

Type RM Length L Ch R = 1 ,5029    ,332,332,332
BEGIN DESCRIPTION:
COON CREEK SOUTH TRIBUTARY 9.0
END DESCRIPTION:
XS GIS Cut Line= 3
      3692525.22     10781977.98      3691926.84     10781373.81
      3691626.15     10780269.66
#Sta/Elev= 30
  4254.6  439.93  4292.4   439.1  4525.7  421.75  4709.6  413.39  4741.2  412.48
  4870.2  410.52  4942.9  412.48  4978.3  411.48  4989.4  407.84  4992.2  407.34
  4995.4  407.84  5013.6  412.49  5070.4  412.09  5261.2  413.93    5316  413.44
  5362.7  414.38  5450.7  419.04  5471.4  422.59  5545.3  428.02  5563.3  429.24
  5609.8  430.96  5649.5  427.57    5658  424.33  5684.1  421.14  5768.6  418.27
  5852.7  417.66  5871.2  419.05  5906.7  424.41  5973.9  429.37  6249.3  436.88
#Mann= 14 ,-1 , 0
  4254.6     .05       0  4741.2     .16       0  4870.2     .12       0
  4989.4     .07       0  4995.4     .12       0  5070.4     .16       0
  5261.2     .12       0  5362.7     .16       0  5545.3     .12       0
  5563.3     .16       0  5768.6     .12       0  5852.7     .16       0
  5871.2     .12       0  5973.9     .05       0
Bank Sta=4709.6,5316
XS Rating Curve= 0 ,0
Exp/Cntr=0.3,0.1

Type RM Length L Ch R = 1 ,4697    ,344,344,344
BEGIN DESCRIPTION:
Mapping XS 677bd320
END DESCRIPTION:
XS GIS Cut Line= 4
      3692584.49     10781785.28      3692209.48     10781347.77
      3692209.48     10781149.85      3692173.02      10780540.5
#Sta/Elev= 30
  4313.8  434.07  4391.7  430.61  4491.6  420.64  4498.2  420.93  4512.4  418.79
  4597.1   412.1  4634.6  410.76  4661.7  410.27    4676  408.27  4689.3  409.71
    4789  410.31  4795.6  412.66  4809.9  411.01  4824.1  411.75  4831.8   410.1
  4937.6  411.06  4977.6  409.61  4994.6  406.49  4997.4  405.99  5000.6  406.49
  5017.6  410.11  5097.6  409.64  5117.7  411.97  5166.1   412.1  5197.8  413.59
  5237.9  417.99    5298  422.59  5385.5  425.61  5528.4  428.91  5698.4  430.41
#Mann= 5 ,-1 , 0
  4313.8     .05       0  4634.6     .16       0  4994.6     .07       0
  5000.6     .16       0  5385.5     .05       0
Bank Sta=4597.1,5166.1
XS Rating Curve= 0 ,0
Exp/Cntr=0.3,0.1

Type RM Length L Ch R = 1 ,4353    ,164,164,164
BEGIN DESCRIPTION:
Mapping XS 24d8c245
END DESCRIPTION:
XS GIS Cut Line= 3
      3692653.68     10781661.91      3692475.72     10781208.33
      3692358.53     10780850.26
#Sta/Elev= 30
  4571.2  428.56  4652.2  425.54    4682  421.83  4706.4  420.46  4723.4  416.99
  4736.2   416.2  4785.1  415.85  4790.5  414.44  4814.9  415.64  4844.7  413.72
    4899  416.59  4904.4  415.14  4916.8  412.97  4923.4  409.44  4947.8  406.24
  4953.2  407.64  4977.6  409.36  4995.7  405.27  5004.4  403.69  5007.2  403.19
  5010.4  403.69  5013.5  408.13  5024.2  408.75  5045.7  407.81  5122.2  409.58
  5235.4  411.02  5290.2   412.8  5348.3   421.9  5380.5  425.25  5435.2  427.65
#Mann= 7 ,-1 , 0
  4571.2     .05       0  4904.4     .16       0  4995.7     .12       0
  5004.4     .07       0  5010.4     .12       0  5122.2     .16       0
  5348.3     .05       0
Bank Sta=4916.8,5235.4
XS Rating Curve= 0 ,0
Exp/Cntr=0.3,0.1

Type RM Length L Ch R = 1 ,4189    ,186,186,186
BEGIN DESCRIPTION:
Mapping XS 593093e1
END DESCRIPTION:
XS GIS Cut Line= 3
      3692807.75     10781536.01      3692614.61     10781156.25
      3692490.91     10780837.24
#Sta/Elev= 30
  4656.8  425.77  4719.4  421.64  4809.2  419.49    4861  414.92  4905.9  413.52
  4921.4  411.94  4927.7   408.3  4933.3  409.44  4943.8  407.13  4967.6  407.78
  4988.7  407.54  4994.5  404.85  4997.1  401.81  4999.8  401.31  5003.1  401.81
  5011.1  407.06  5022.3  408.84  5167.8  407.64  5197.7  408.15  5222.3  410.22
  5246.8  413.86  5271.4  415.47  5276.8  414.73  5301.3  418.08  5355.8  422.87
  5361.2  421.41  5363.8  422.02  5385.7   424.7  5391.1  423.36    5425  425.97
#Mann= 6 ,-1 , 0
  4656.8     .05       0  4905.9     .16       0  4967.6     .12       0
  4997.1     .07       0  5003.1     .12       0  5363.8     .05       0
Bank Sta=4921.4,5222.3
XS Rating Curve= 0 ,0
Exp/Cntr=0.3,0.1

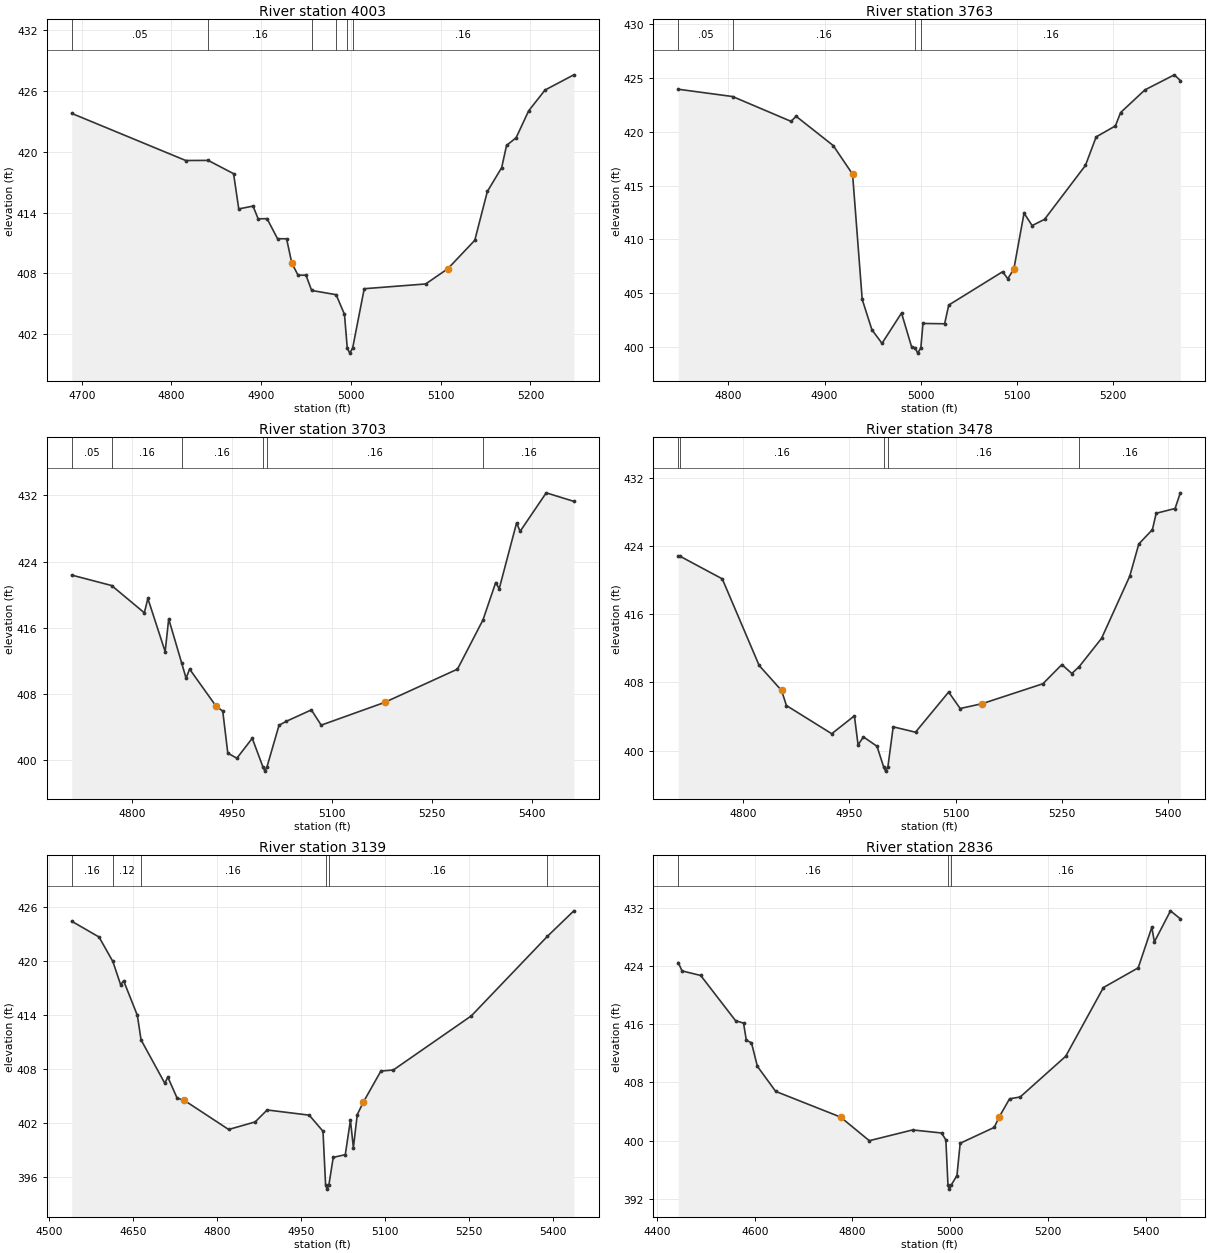
Type RM Length L Ch R = 1 ,4003    ,240,240,240
BEGIN DESCRIPTION:
COON CREEK SOUTH TRIBUTARY 8.0
END DESCRIPTION:
XS GIS Cut Line= 3
      3692955.32     10781399.31      3692777.37     10781086.81
      3692705.76     10780900.19
#Sta/Elev= 30
  4688.9  423.79  4815.9  419.14  4840.9  419.15  4869.2  417.84    4875  414.36
  4890.9  414.64  4896.6  413.38  4906.5   413.4  4918.2  411.42  4928.3  411.41
  4934.1  409.01  4941.1  407.81  4949.9  407.82  4956.2  406.31  4983.5  405.89
  4992.8  403.95  4995.9  400.62  4998.7  400.12  5001.9  400.62  5014.8  406.48
  5083.3  406.95  5107.9  408.45    5138  411.26    5152  416.08    5168  418.44
  5173.4  420.63  5184.1  421.39    5198  424.04  5216.3   426.1  5248.4   427.6
#Mann= 6 ,-1 , 0
  4688.9     .05       0  4840.9     .16       0  4956.2     .12       0
  4983.5     .16       0  4995.9     .07       0  5001.9     .16       0
Bank Sta=4934.1,5107.9
XS Rating Curve= 0 ,0
Exp/Cntr=0.3,0.1

Type RM Length L Ch R = 1 ,3763    ,60,60,60
BEGIN DESCRIPTION:
COON CREEK SOUTH TRIBUTARY 7.0
END DESCRIPTION:
XS GIS Cut Line= 4
       3693016.3     10781230.58      3692995.47     10781019.66
      3692977.24     10780957.16      3692746.79     10780873.83
#Sta/Elev= 30
  4747.9  423.96  4804.5  423.28  4865.3  420.97  4870.4  421.45  4909.1  418.72
  4929.2  416.06  4939.2  404.42  4949.3  401.59  4959.8  400.33  4980.1  403.15
  4990.5  400.02  4994.2  399.92  4996.9  399.42  5000.2  399.92  5002.4  402.18
  5024.9  402.15  5029.2  403.89  5085.2  406.99  5090.6  406.34  5096.9  407.24
  5107.5  412.44  5115.9  411.28  5128.8  411.86  5171.3  416.87  5182.5  419.53
  5202.5  420.55  5207.9  421.79  5233.2   423.9  5263.8   425.3    5270  424.77
#Mann= 4 ,-1 , 0
  4747.9     .05       0  4804.5     .16       0  4994.2     .07       0
  5000.2     .16       0
Bank Sta=4929.2,5096.9
XS Rating Curve= 0 ,0
Exp/Cntr=0.3,0.1

Type RM Length L Ch R = 1 ,3703    ,225,225,225
BEGIN DESCRIPTION:
COON CREEK SOUTH TRIBUTARY 6.0
END DESCRIPTION:
XS GIS Cut Line= 2
       3693130.9     10781234.91      3692887.85     10780520.95
#Sta/Elev= 30
  4708.8  422.36  4768.7   421.1  4817.8  417.81  4823.1  419.54  4849.1  413.12
  4854.4  417.08  4873.7   411.8  4880.5  409.92  4885.8  411.02  4925.1  406.59
  4935.6  405.94  4943.2  400.87  4956.8  400.26  4979.9  402.66    4996   399.2
  4998.8   398.7    5002   399.2  5020.1  404.23  5030.7   404.7  5068.7  406.09
  5083.5  404.25  5178.6  406.99  5288.2  411.01  5326.5  416.95  5345.6  421.46
  5350.9  420.72    5377  428.66  5382.3  427.64  5421.5  432.29    5463  431.26
#Mann= 6 ,-1 , 0
  4708.8     .05       0  4768.7     .16       0  4873.7     .16       0
    4996     .07       0    5002     .16       0  5326.5     .16       0
Bank Sta=4925.1,5178.6
XS Rating Curve= 0 ,0
Exp/Cntr=0.3,0.1

Type RM Length L Ch R = 1 ,3478    ,339,339,339
BEGIN DESCRIPTION:
Mapping XS 88c9ee66
END DESCRIPTION:
XS GIS Cut Line= 2
      3693342.28     10781188.94      3693123.52     10780514.43
#Sta/Elev= 30
  4708.2  422.85  4710.2  422.83  4770.4  420.15  4822.5  409.98  4854.1  407.05
    4861  405.28    4925  401.97    4957  404.07  4962.2  400.65  4969.7   401.6
  4988.9   400.5  4998.3  398.08    5001  397.58  5004.3  398.08  5011.8  402.78
  5043.3  402.15  5090.1  406.86  5106.4  404.93  5137.9  405.51  5223.3  407.84
    5250  410.09  5264.1  409.04  5274.6  409.86  5306.1  413.17  5345.9  420.47
  5358.7  424.25  5377.9  425.93  5383.2  427.85  5409.9  428.41  5417.3  430.25
#Mann= 5 ,-1 , 0
  4708.2     .16       0  4710.2     .16       0  4998.3     .07       0
  5004.3     .16       0  5274.6     .16       0
Bank Sta=4854.1,5137.9
XS Rating Curve= 0 ,0
Exp/Cntr=0.3,0.1

Type RM Length L Ch R = 1 ,3139    ,303,303,303
BEGIN DESCRIPTION:
Mapping XS 05d40a1d
END DESCRIPTION:
XS GIS Cut Line= 2
      3693576.67     10781165.53      3693251.14     10780329.58
#Sta/Elev= 30
  4540.9  424.47  4589.6  422.72  4614.3     420  4628.2  417.42  4633.6  417.85
  4658.1  414.01  4664.7  411.29  4707.1  406.47  4712.5  407.15  4729.1  404.82
  4742.3  404.55  4821.2  401.33  4868.6  402.17    4890   403.5  4965.2  402.92
  4989.8  401.13  4994.4   395.2  4997.1   394.7  5000.4   395.2  5008.1  398.23
  5029.6  398.53  5038.8  402.36  5044.1  399.31    5051  402.98  5061.7  404.35
  5093.2  407.82  5115.4  407.94  5254.9  413.96  5390.8   422.8    5438  425.63
#Mann= 6 ,-1 , 0
  4540.9     .16       0  4614.3     .12       0  4664.7     .16       0
  4994.4     .07       0  5000.4     .16       0  5390.8     .12       0
Bank Sta=4742.3,5061.7
XS Rating Curve= 0 ,0
Exp/Cntr=0.3,0.1

Type RM Length L Ch R = 1 ,2836    ,390,390,390
BEGIN DESCRIPTION:
Mapping XS 8caa57fd
END DESCRIPTION:
XS GIS Cut Line= 3
       3693917.8     10781102.99      3693628.74     10780563.93
      3693508.95     10780165.51
#Sta/Elev= 30
  4443.5  424.48  4451.3  423.33  4489.5   422.7  4560.9  416.48  4577.2  416.15
  4582.9  413.78  4593.4  413.45  4605.5  410.21    4643  406.76  4775.7  403.23
  4834.6  399.98  4923.2  401.46  4982.5  401.04  4991.3  400.09  4995.7  393.82
  4998.5  393.32  5001.7  393.82    5014  395.19  5020.6  399.63  5090.4  401.81
  5099.9  403.18  5121.7  405.74  5143.4  405.99  5236.6  411.59  5313.8  421.04
    5385  423.75  5412.9  429.33  5418.1  427.32  5451.1  431.59  5471.2  430.49
#Mann= 3 ,-1 , 0
  4443.5     .16       0  4995.7     .07       0  5001.7     .16       0
Bank Sta=4775.7,5099.9
XS Rating Curve= 0 ,0
Exp/Cntr=0.3,0.1

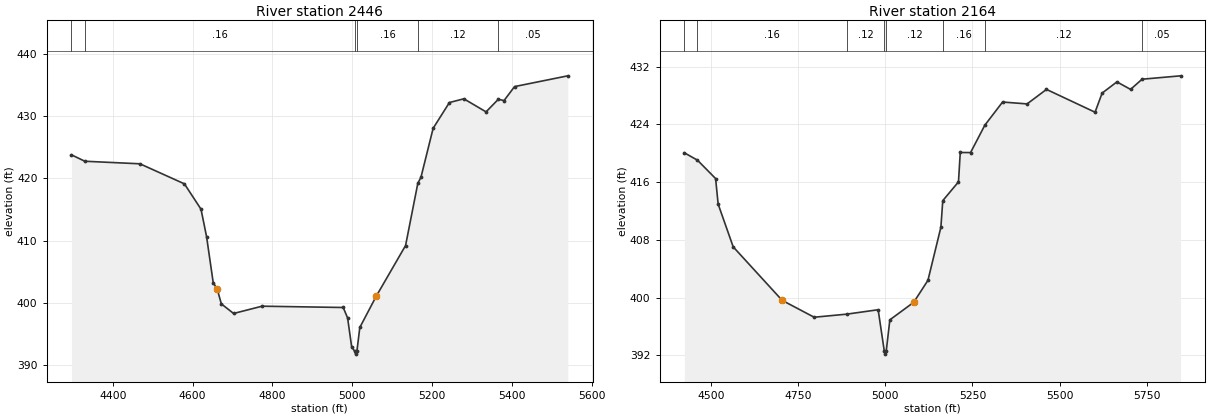
Type RM Length L Ch R = 1 ,2446    ,282,282,282
BEGIN DESCRIPTION:
COON CREEK SOUTH TRIBUTARY 5.0
END DESCRIPTION:
XS GIS Cut Line= 2
      3694052.35     10781078.27      3693802.36     10779859.55
#Sta/Elev= 30
  4296.2   423.8  4329.7  422.77  4467.8  422.36  4579.3  419.14  4620.9  415.07
  4634.8  410.68  4651.5  403.28  4661.7  402.19  4671.9  399.86  4702.6  398.32
    4774  399.49  4977.4  399.28  4988.4   397.6  4998.6  392.95  5005.8  392.29
  5008.6  391.79  5011.8  392.29    5019  396.07  5059.9  401.06  5133.7  409.23
  5164.5  419.25  5172.2  420.17  5202.8  428.06  5243.6   432.2  5279.8   432.8
  5335.5   430.7  5366.2  432.72  5380.6  432.52  5406.9  434.76  5540.3  436.49
#Mann= 6 ,-1 , 0
  4296.2     .05       0  4329.7     .16       0  5005.8     .07       0
  5011.8     .16       0  5164.5     .12       0  5366.2     .05       0
Bank Sta=4661.7,5059.9
XS Rating Curve= 0 ,0
Exp/Cntr=0.3,0.1

Type RM Length L Ch R = 1 ,2164    ,420,420,420
BEGIN DESCRIPTION:
COON CREEK SOUTH TRIBUTARY 4.0
END DESCRIPTION:
XS GIS Cut Line= 2
      3694302.09     10780965.36      3694017.37      10779569.5
#Sta/Elev= 30
    4423  420.08  4460.6  419.06  4512.8  416.51  4520.1  412.97  4563.3  407.05
  4703.8  399.64  4795.7   397.3  4889.7  397.73  4979.4  398.34  4996.8  392.69
  4999.6  392.19  5002.8  392.69    5013  396.94  5081.5  399.37  5122.3  402.41
  5159.5  409.77  5164.9  413.45    5210  416.05  5215.1  420.12  5244.7  420.11
  5285.6   423.9  5336.6  427.11    5407  426.85  5462.6  428.86    5602   425.7
  5622.4  428.35  5664.8   429.9    5704  428.86  5736.9  430.27  5847.6  430.74
#Mann= 8 ,-1 , 0
    4423     .05       0  4460.6     .16       0  4889.7     .12       0
  4996.8     .07       0  5002.8     .12       0  5164.9     .16       0
  5285.6     .12       0  5736.9     .05       0
Bank Sta=4703.8,5081.5
XS Rating Curve= 0 ,0
Exp/Cntr=0.3,0.1