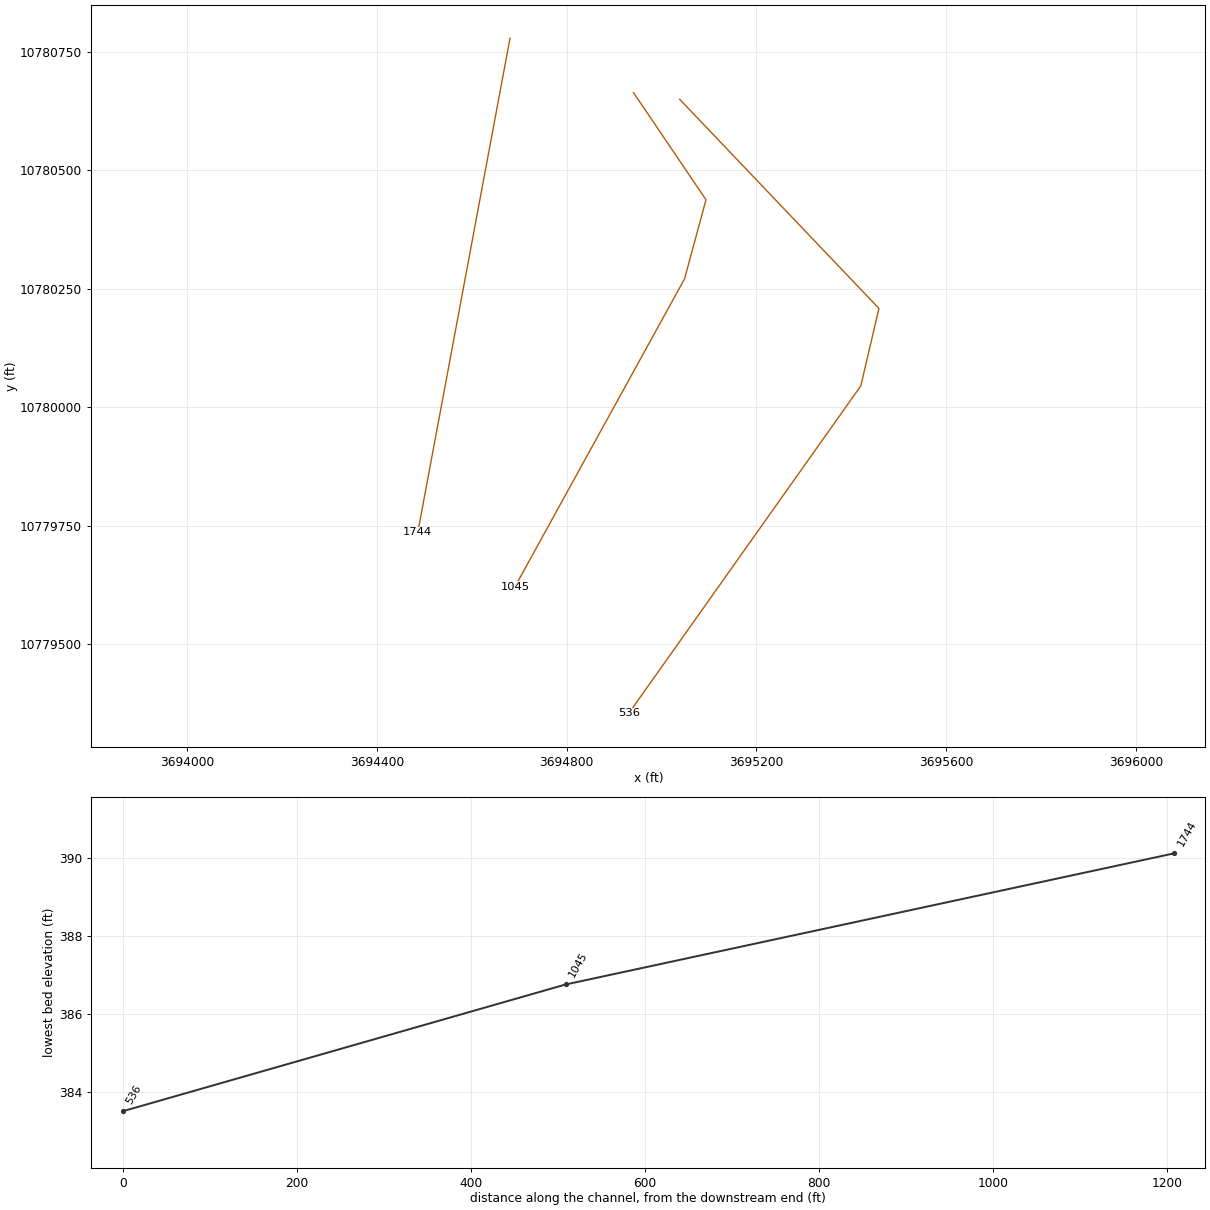
HEC-RAS study COON CREEK SOUTH TRIBUTARY.prj: COON CREEK SOUTH TRIBUTARY Base Level Engineering

--- COON CREEK SOUTH TRIBUTARY.g01 (geometry) --- (continued)

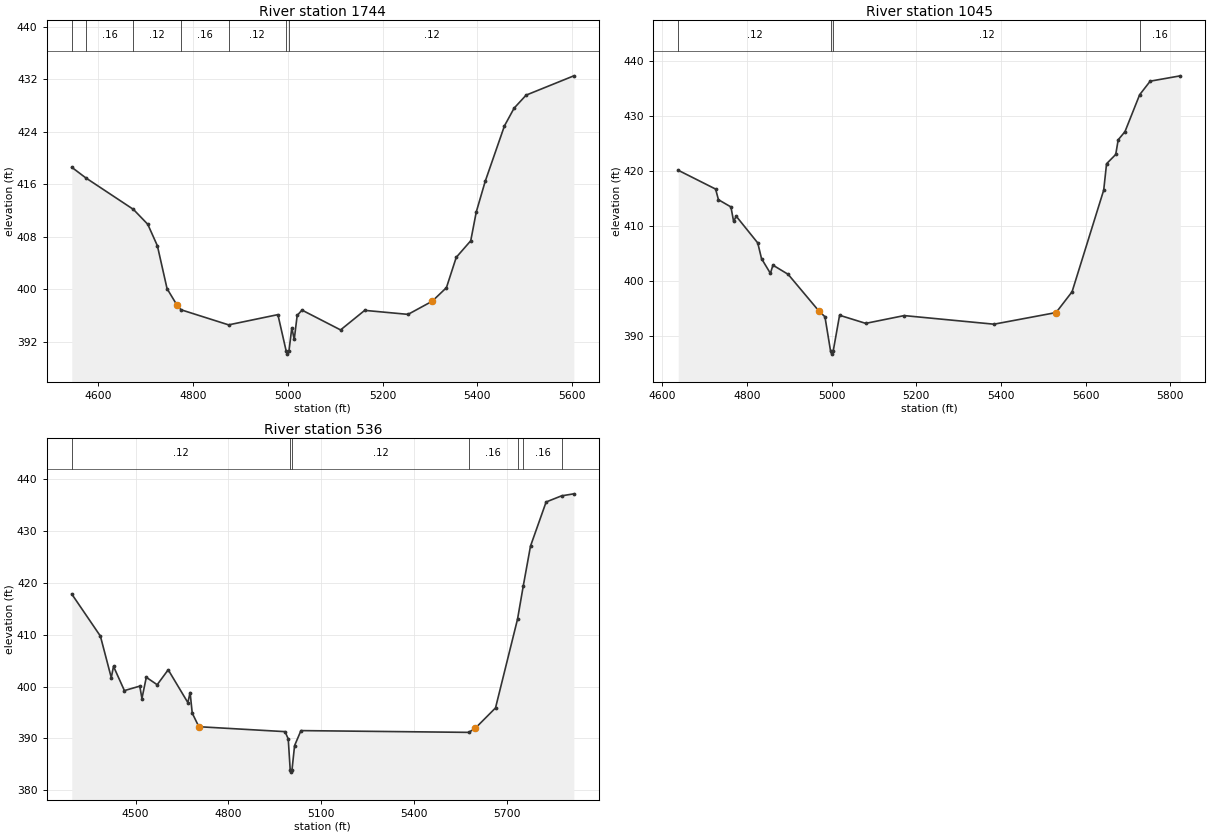
Type RM Length L Ch R = 1 ,1744    ,699,699,699
BEGIN DESCRIPTION:
COON CREEK SOUTH TRIBUTARY 3.0
END DESCRIPTION:
XS GIS Cut Line= 2
      3694680.56     10780777.85      3694486.13     10779736.24
#Sta/Elev= 30
  4544.2   418.6  4573.9  416.98  4674.3  412.18  4704.6  409.91  4724.9  406.63
  4745.3   400.1  4765.6  397.67  4774.8  396.88  4875.2  394.58  4979.2  396.14
  4996.6  390.62  4999.3  390.12  5002.6  390.62  5008.6  394.14  5013.7  392.36
  5019.9  396.02  5030.1  396.83  5111.5  393.81  5162.4  396.79  5253.9  396.18
  5304.8  398.18  5334.9  400.25  5355.6  404.87  5386.2   407.4  5397.8  411.77
  5416.7  416.45  5457.4  424.92  5477.7  427.61  5503.1   429.6  5603.8  432.54
#Mann= 7 ,-1 , 0
  4544.2     .05       0  4573.9     .16       0  4674.3     .12       0
  4774.8     .16       0  4875.2     .12       0  4996.6     .07       0
  5002.6     .12       0
Bank Sta=4765.6,5304.8
XS Rating Curve= 0 ,0
Exp/Cntr=0.3,0.1

Type RM Length L Ch R = 1 ,1045    ,509,509,509
BEGIN DESCRIPTION:
COON CREEK SOUTH TRIBUTARY 2.0
END DESCRIPTION:
XS GIS Cut Line= 4
      3694940.99     10780663.27      3695093.76     10780437.59
      3695048.62     10780270.93      3694690.98      10779621.6
#Sta/Elev= 30
  4637.5  420.11  4725.8   416.7  4732.5  414.77    4762  413.46  4768.4  410.83
  4774.5  411.78  4825.4  406.93  4834.3  404.09  4855.3  401.41  4861.3   402.9
  4897.3  401.23  4969.5  394.62  4984.2  393.54  4997.6  387.26  5000.3  386.76
  5003.6  387.26  5018.8  393.81  5080.5  392.34  5171.5  393.75  5383.6  392.19
  5530.4   394.3  5568.2  398.07    5643  416.52  5649.7  421.29  5671.4  422.98
  5677.2  425.64  5693.2  427.11  5727.9  433.81  5752.8  436.27    5824  437.24
#Mann= 4 ,-1 , 0
  4637.5     .12       0  4997.6     .07       0  5003.6     .12       0
  5727.9     .16       0
Bank Sta=4969.5,5530.4
XS Rating Curve= 0 ,0
Exp/Cntr=0.3,0.1

Type RM Length L Ch R = 1 ,536     ,0,0,0
BEGIN DESCRIPTION:
COON CREEK SOUTH TRIBUTARY 1.0
END DESCRIPTION:
XS GIS Cut Line= 4
      3695038.21     10780649.39      3695458.35     10780208.43
      3695420.15     10780045.23      3694930.92     10779354.76
#Sta/Elev= 30
  4293.4  417.82  4385.9  409.72  4421.1  401.71  4428.3  403.89  4463.5  399.22
  4513.3  400.08  4520.2  397.69  4534.3  401.78  4569.5  400.35  4605.1  403.23
  4668.6  396.91  4675.9  398.84  4682.8  394.88  4704.2  392.26  4982.8  391.31
  4993.1  389.91  4999.4  384.01  5002.2  383.51  5005.4  384.01  5013.6  388.62
  5034.2  391.51  5576.6  391.17  5597.8  391.97  5663.1  395.88  5734.3  412.99
  5752.9  419.41  5776.2  427.06  5826.7  435.56  5876.5  436.74  5916.3  437.13
#Mann= 7 ,-1 , 0
  4293.4     .12       0  4999.4     .07       0  5005.4     .12       0
  5576.6     .16       0  5734.3     .12       0  5752.9     .16       0
  5876.5     .05       0
Bank Sta=4704.2,5597.8
XS Rating Curve= 0 ,0
Exp/Cntr=0.3,0.1

Chan Stop Cuts=-1
Use User Specified Reach Order=0
Composite Channel Slope=5