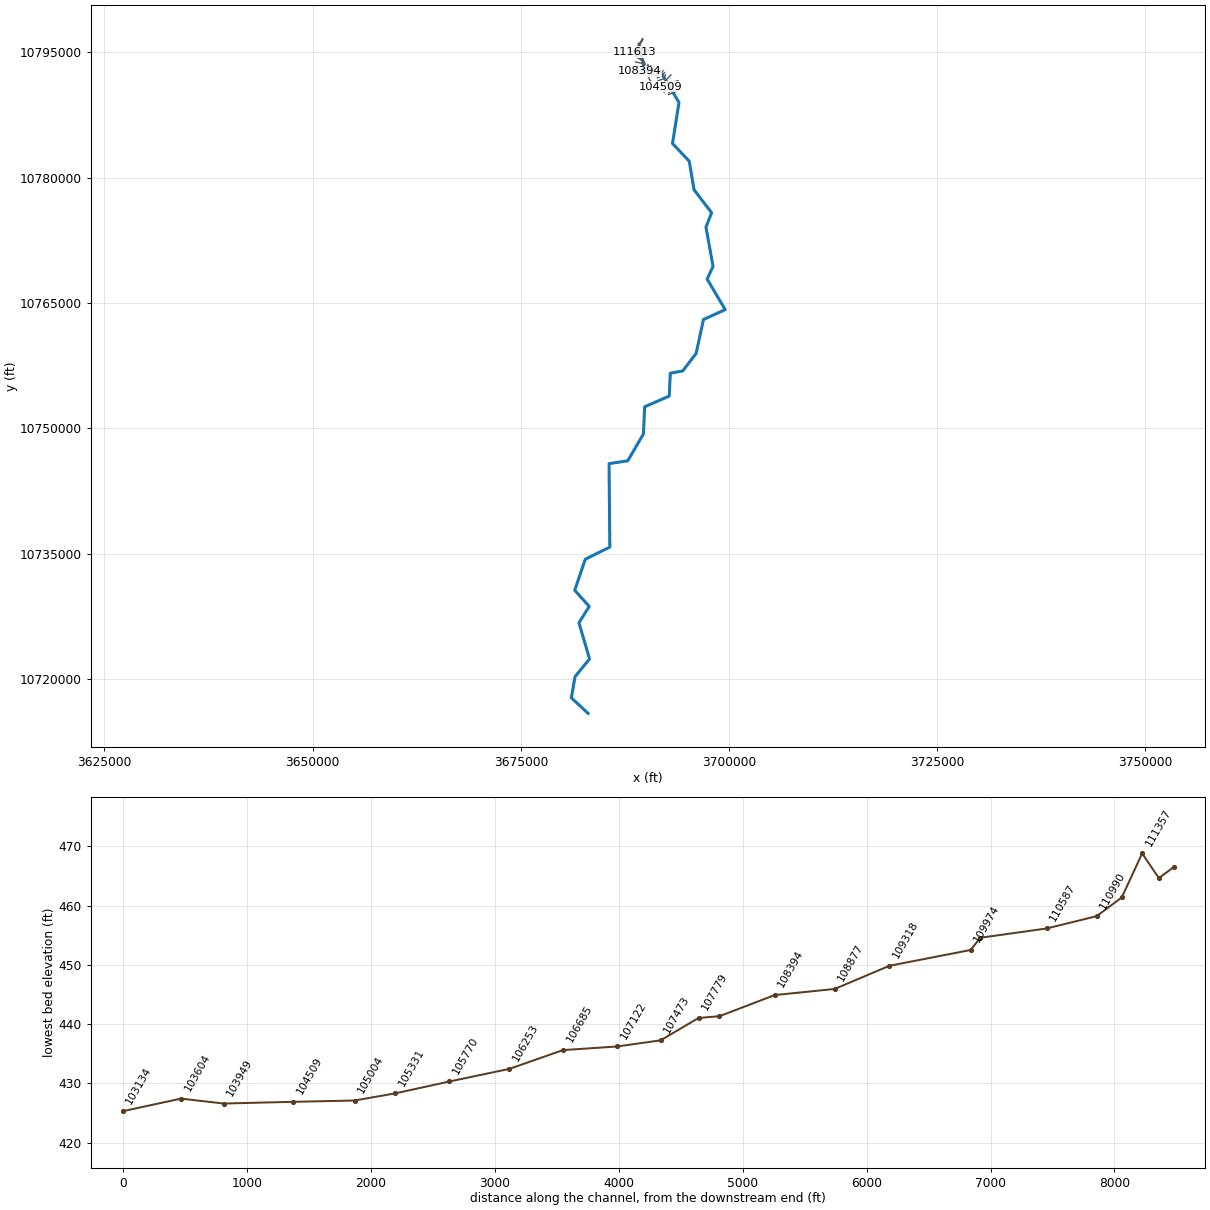
--- COON CREEK.prj (project) ---

Proj Title=COON CREEK Base Level Engineering
Current Plan=p01
Default Exp/Contr=0.3,0.1
English Units
Geom File=g01
Geom File=g02
Flow File=f01
Plan File=p01
Y Axis Title=Elevation
X Axis Title(PF)=Main Channel Distance
X Axis Title(XS)=Station
BEGIN DESCRIPTION:
COON CREEK
END DESCRIPTION:
DSS Export Rating Curves= 0
DSS Export Rating Curve Sorted= 0
DSS Export Volume Flow Curves= 0
DXF OffsetX= 0
DXF OffsetY= 0
DXF ScaleX= 1
DXF ScaleY= 10

--- COON CREEK.p01 (plan) ---

Plan Title=Multiple Run
Program Version=4.10
Short Identifier=Multiple
Geom File=g01
Flow File=f01
Subcritical Flow
K Sum by GR= 0
Std Step Tol= 0.01
Critical Tol= 0.01
Num of Std Step Trials= 20
Max Error Tol= 0.3
Flow Tol Ratio= 0.001
Split Flow NTrial= 30
Split Flow Tol= 0.02
Split Flow Ratio= 0.02
Log Output Level= 0
Friction Slope Method= 1
Unsteady Friction Slope Method= 2
Unsteady Bridges Friction Slope Method= 1
Parabolic Critical Depth
Global Vel Dist= 1 , 1 , 1
Global Log Level= 0
CheckData=True
Encroach Param=-1 ,0,0, 0
BEGIN DESCRIPTION:
Multiple Run
END DESCRIPTION:
Computation Interval=1HOUR
Output Interval=1HOUR
Run HTab= 0
Run UNet= 0
Run PostProcess= 0
Run WQNet= 0
UNET Theta= 1
UNET Theta Warmup= 1
UNET ZTol= 0.02
UNET ZSATol= 0.05
UNET MxIter= 20
UNET MaxInSteps= 0
UNET DtIC= 0
UNET DtMin= 0
UNET MaxCRTS= 20
UNET WFStab= 2
UNET SFStab= 1
UNET WFX= 1
UNET SFX= 1
UNET DSS MLevel= 4
UNET DZMax Abort= 100
UNET Convert EG Bridges= 0
UNET Use Existing IB Tables=-1
UNET Froude Reduction=False
UNET Froude Limit= 1
UNET Froude Power= 10
UNET Time Slicing=0,0, 5
UNET Junction Losses=0
Instantaneous Interval=1HOUR
Write IC File= 0
Write IC File at Sim End=0
Echo Input=False
Echo Parameters=False
Echo Output=False
Write Detailed= 0
WQ AD Non Conservative
WQ ULTIMATE=-1
WQ Max Comp Step=1HOUR
WQ Output Interval=15MIN
WQ Output Selected Increments= 0
WQ Output face flow=0
WQ Output face velocity=0
WQ Output face area=0
WQ Output face dispersion=0
WQ Output cell volume=0
WQ Output cell surface area=0
WQ Output cell continuity=0
WQ Output cumulative cell continuity=0
WQ Output face conc=0
WQ Output face dconc_dx=0
WQ Output face courant=0
WQ Output face peclet=0
WQ Output face adv mass=0
WQ Output face disp mass=0
WQ Output cell mass=0
WQ Output cell source sink temp=0
WQ Output cell source sink nsm=0
WQ Output MaxMinRange=-1
WQ Daily Max Min Mean=-1
WQ Daily Range=0
WQ Daily Time=0
WQ Create Restart=0
WQ Fixed Restart=0
WQ System Summary=0
WQ Use Fixed Temperature=0
Sorting and Armoring Iterations= 10
XS Update Threshold= 0.02
Hydraulics Update Threshold= 0.02
Energy Slope Method= 1
Volume Change Method= 0
XS Weighting Method= 0
Number of US Weighted Cross Sections= 1
Number of DS Weighted Cross Sections= 1
Upstream XS Weight=0.25
Main XS Weight=0.5
Downstream XS Weight=0.25
Number of DS XS's Weighted with US Boundary= 1
Upstream Boundary Weight= 1
Weight of XSs Associated with US Boundary= 0
Number of US XS's Weighted with DS Boundary= 1
Downstream Boundary Weight= 0.5
Weight of XSs Associated with DS Boundary= 0.5
Sediment Output Level= 4
Mass or Volume Output= 0
Output Increment Type= 1
Profile and TS Output Increment= 10
XS Output Flag= 0
XS Output Increment= 10
Disregard all LS=0
Disregard all Conn=0
Disregard all Breaches=0
Disregard all Pumps=0

--- COON CREEK.f01 (steady flow) ---

Flow Title=Multiple
Program Version=4.10
Number of Profiles= 7
Profile Names=10-year,25-year,50-year,1pct_min,100-year,1pct_plu,500-year
River Rch & RM=COON CREEK,Reach-1         ,111613
     579     784     952     849    1149    1553    1673
River Rch & RM=COON CREEK,Reach-1         ,107779
     959    1333    1648    1492    2018    2729    3035
River Rch & RM=COON CREEK,Reach-1         ,104509
    1285    1808    2254    2055    2779    3759    4240
River Rch & RM=COON CREEK,Reach-1         ,101776
    1706    2428    3048    2797    3783    5116    5845
River Rch & RM=COON CREEK,Reach-1         ,101128
    1706    2428    3048    2797    3783    5116    5845
River Rch & RM=COON CREEK,Reach-1         ,96543
    1851    2645    3329    3062    4141    5600    6429
River Rch & RM=COON CREEK,Reach-1         ,96171
    1851    2645    3329    3062    4141    5600    6429
River Rch & RM=COON CREEK,Reach-1         ,95699
    1928    2754    3465    3185    4308    5826    6680
River Rch & RM=COON CREEK,Reach-1         ,92433
    2017    2885    3635    3345    4523    6117    7028
River Rch & RM=COON CREEK,Reach-1         ,91952
    2017    2885    3635    3345    4523    6117    7028
River Rch & RM=COON CREEK,Reach-1         ,90857
    2572    3710    4699    4344    5875    7945    9213
River Rch & RM=COON CREEK,Reach-1         ,89904
    2572    3710    4699    4344    5875    7945    9213
River Rch & RM=COON CREEK,Reach-1         ,86027
    3357    4881    6217    5775    7810   10562   12364
River Rch & RM=COON CREEK,Reach-1         ,80532
    3834    5590    7134    6635    8974   12136   14246
River Rch & RM=COON CREEK,Reach-1         ,75220
    4299    6288    8040    7493   10133   13704   16144
River Rch & RM=COON CREEK,Reach-1         ,70298
    4493    6571    8401    7826   10583   14313   16849
River Rch & RM=COON CREEK,Reach-1         ,65930
    4640    6792    8691    8102   10957   14818   17468
River Rch & RM=COON CREEK,Reach-1         ,63057
    4564    6662    8508    7915   10705   14477   16996
River Rch & RM=COON CREEK,Reach-1         ,56584
    5101    7459    9537    8879   12008   16240   19095
River Rch & RM=COON CREEK,Reach-1         ,49803
    5121    7479    9553    8886   12017   16251   19070
River Rch & RM=COON CREEK,Reach-1         ,46632
    6905   10170   13068   12223   16530   22355   26513
River Rch & RM=COON CREEK,Reach-1         ,45833
    6905   10170   13068   12223   16530   22355   26513
River Rch & RM=COON CREEK,Reach-1         ,45447
    8924   13201   17019   15961   21586   29192   34802
River Rch & RM=COON CREEK,Reach-1         ,38729
    8901   13161   16960   15900   21503   29080   34641
River Rch & RM=COON CREEK,Reach-1         ,37321
    8832   13022   16750   15672   21194   28663   34008
River Rch & RM=COON CREEK,Reach-1         ,31233
    8858   13045   16764   15671   21193   28661   33939
River Rch & RM=COON CREEK,Reach-1         ,27825
    8783   12915   16580   15482   20938   28316   33460
River Rch & RM=COON CREEK,Reach-1         ,25044
    9786   14410   18521   17311   23411   31660   37476
River Rch & RM=COON CREEK,Reach-1         ,24396
    9786   14410   18521   17311   23411   31660   37476
River Rch & RM=COON CREEK,Reach-1         ,14626
    9833   14464   18576   17348   23461   31728   37493
River Rch & RM=COON CREEK,Reach-1         ,12271
    9833   14464   18576   17348   23461   31728   37493
River Rch & RM=COON CREEK,Reach-1         ,10799
    9942   14619   18770   17523   23698   32049   37849
River Rch & RM=COON CREEK,Reach-1         ,4486
   10311   15148   19438   18137   24528   33171   39125
Boundary for River Rch & Prof#=COON CREEK,Reach-1         , 1
Up Type= 0
Dn Type= 3
Dn Slope=0.0005
Boundary for River Rch & Prof#=COON CREEK,Reach-1         , 2
Up Type= 0
Dn Type= 3
Dn Slope=0.0005
Boundary for River Rch & Prof#=COON CREEK,Reach-1         , 3
Up Type= 0
Dn Type= 3
Dn Slope=0.0005
Boundary for River Rch & Prof#=COON CREEK,Reach-1         , 4
Up Type= 0
Dn Type= 3
Dn Slope=0.0005
Boundary for River Rch & Prof#=COON CREEK,Reach-1         , 5
Up Type= 0
Dn Type= 3
Dn Slope=0.0005
Boundary for River Rch & Prof#=COON CREEK,Reach-1         , 6
Up Type= 0
Dn Type= 3
Dn Slope=0.0005
Boundary for River Rch & Prof#=COON CREEK,Reach-1         , 7
Up Type= 0
Dn Type= 3
Dn Slope=0.0005
DSS Import GetInterval= 0
DSS Import GetPeak= 0
DSS Import FillOption= 0

--- COON CREEK.g01 (geometry) ---

Geom Title=Existing Conditions
Program Version=4.10

River Reach=COON CREEK      ,Reach-1
Reach XY= 30
       3689200.8      10796008.9      3689866.25       10792827.
      3691695.25       10792809.      3693991.75       10789017.
      3693209.75       10784101.        3695216.       10781979.
       3695802.5       10778552.      3697906.25       10775810.
      3697229.75       10774075.       3698079.5       10769380.
      3697369.25       10767865.      3699540.25       10764210.
       3696925.5       10763023.      3696046.75       10758961.
        3694438.       10756868.       3692948.5       10756601.
      3692817.25       10753858.       3689864.5       10752573.
      3689723.25       10749329.        3687839.       10746111.
      3685593.25       10745772.      3685686.25       10735777.
       3682735.5       10734324.      3681470.25       10730610.
       3683212.5       10728671.        3681979.       10726720.
        3683249.       10722395.        3681506.       10720260.
        3681067.       10717736.        3683077.       10715872.

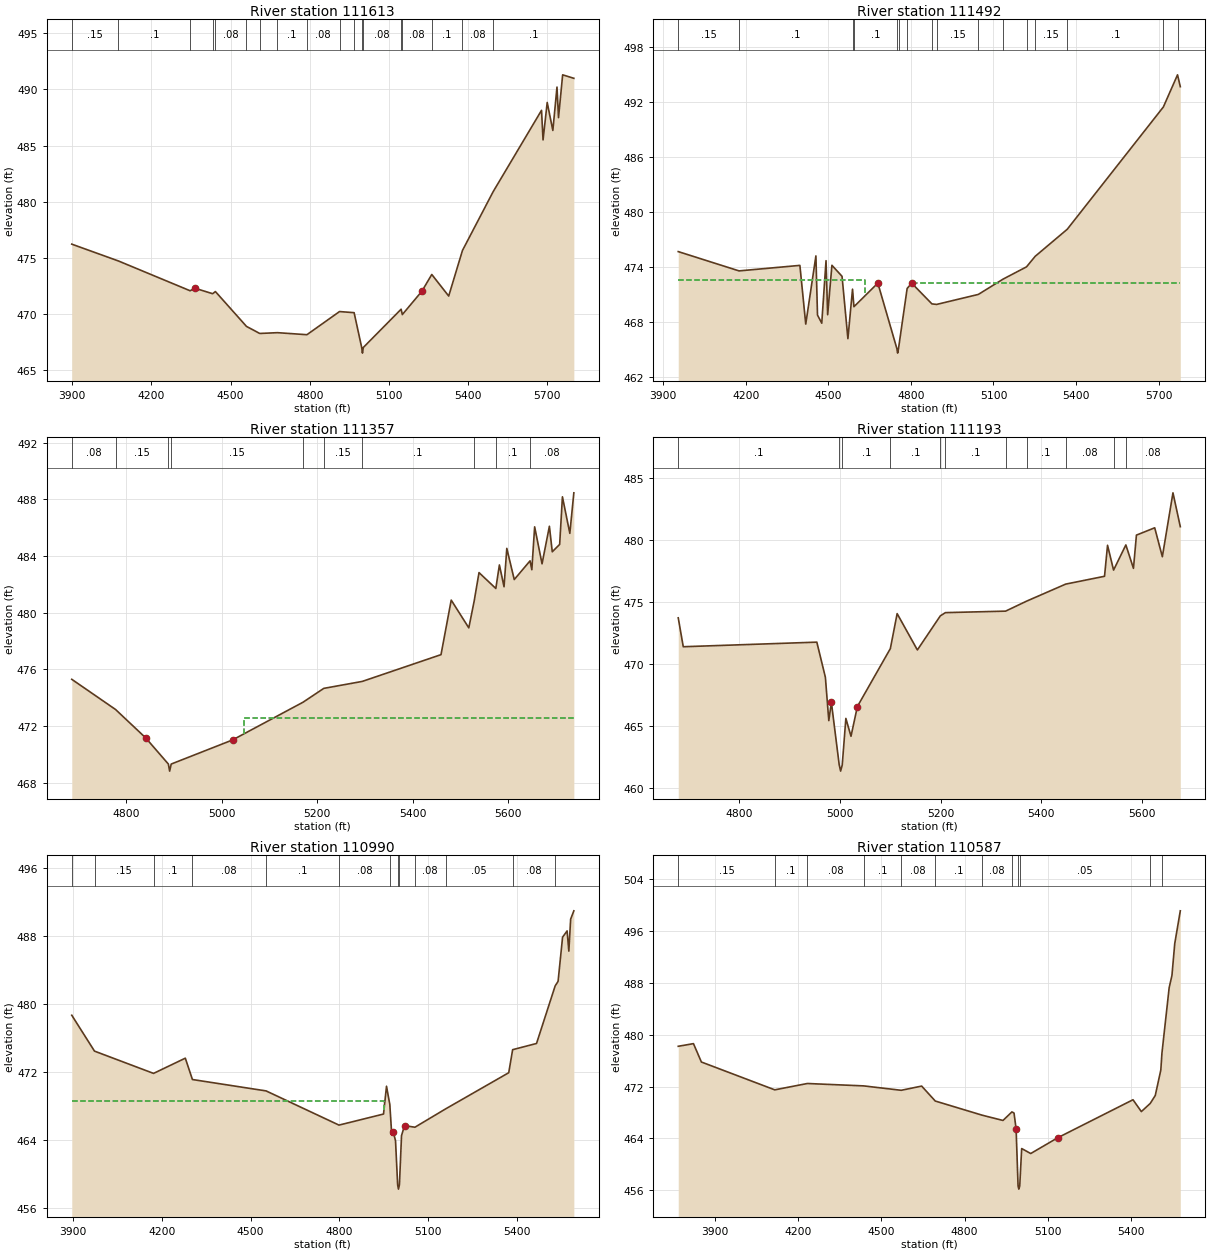
Type RM Length L Ch R = 1 ,111613  ,121,121,121
BEGIN DESCRIPTION:
Mapping XS 255b001d
END DESCRIPTION:
XS GIS Cut Line= 4
      3689624.07     10796687.83      3689284.19     10796132.49
      3689048.53     10795745.97      3688644.31     10795056.63
#Sta/Elev= 30
  3898.1  476.23  4075.2  474.73  4346.8  472.08  4364.3  472.31    4432  471.82
  4442.5  472.01  4560.2  468.91  4610.5  468.28  4677.8  468.35  4789.4  468.17
  4912.9  470.23  4968.2  470.13    4997  467.03  4999.8  466.53    5003  467.03
  5146.4  470.44  5150.9  469.96  5225.1  472.04  5262.6  473.53  5326.7  471.61
  5378.9  475.67  5495.2   480.9  5678.5  488.14  5684.3  485.51    5700  488.84
  5721.4  486.35  5737.1  490.21  5742.9  487.49  5758.6   491.3    5801  490.99
#Mann= 18 ,-1 , 0
  3898.1     .15       0  4075.2      .1       0  4346.8     .15       0
    4432      .1       0  4442.5     .08       0  4560.2      .1       0
  4610.5     .08       0  4677.8      .1       0  4789.4     .08       0
  4912.9      .1       0  4968.2     .08       0    4997     .07       0
    5003     .08       0  5146.4      .1       0  5150.9     .08       0
  5262.6      .1       0  5378.9     .08       0  5495.2      .1       0
Bank Sta=4364.3,5225.1
XS Rating Curve= 0 ,0
Exp/Cntr=0.3,0.1

Type RM Length L Ch R = 1 ,111492  ,135,135,135
BEGIN DESCRIPTION:
Mapping XS 3166093e
END DESCRIPTION:
XS GIS Cut Line= 4
      3689654.01     10796522.72      3689318.05     10795967.99
      3689021.17     10795522.68      3688695.67     10794970.62
#Sta/Elev= 30
  3954.4   475.7  4175.4   473.6  4396.5   474.2  4417.8  467.81  4454.7  475.23
  4460.5  468.79    4476  467.91  4491.5  474.71  4497.4  468.83  4512.9  474.21
  4549.7  473.01    4571  466.22  4587.8  471.61  4592.9   469.7  4679.8  472.27
  4748.9  465.15  4751.7  464.65  4754.9  465.15  4786.3  471.69    4803  472.26
  4876.3  470.01  4893.3  469.95    5045  471.04  5135.2  472.71  5220.1  474.04
  5251.7  475.19  5368.1  478.13  5717.4  491.44  5768.9  494.94    5779  493.65
#Mann= 16 ,-1 , 0
  3954.4     .15       0  4175.4      .1       0  4587.8     .15       0
  4592.9      .1       0  4748.9     .07       0  4754.9      .1       0
  4786.3     .15       0  4876.3      .1       0  4893.3     .15       0
    5045      .1       0  5135.2     .15       0  5220.1      .1       0
  5251.7     .15       0  5368.1      .1       0  5717.4     .08       0
  5768.9      .1       0
#XS Ineff= 2 , 0
         4633.31  472.63 4810.25          472.23
Permanent Ineff=
       F       F
Bank Sta=4679.8,4803
XS Rating Curve= 0 ,0
Exp/Cntr=0.3,0.1

Type RM Length L Ch R = 1 ,111357  ,164,164,164
BEGIN DESCRIPTION:
Mapping XS ab7f491f
END DESCRIPTION:
XS GIS Cut Line= 4
      3689462.66     10795559.67      3689113.91     10795508.18
      3688992.19     10795412.21      3688711.29     10794946.38
#Sta/Elev= 30
  4686.1   475.3  4777.8  473.17  4840.8  471.17  4888.4  469.32  4891.1  468.82
  4894.4  469.32  5022.8  471.02  5170.3  473.68  5213.9  474.66  5294.4  475.15
  5459.4  477.04  5480.8  480.89  5517.6  478.93  5528.8  480.81    5539  482.83
  5574.2  481.71  5581.7  483.37  5591.4  481.83  5597.2  484.54  5612.8  482.34
  5645.9  483.66  5649.6  483.03  5655.5  486.06    5671  483.45  5686.4   486.1
  5692.4   484.3  5707.9  484.82  5713.7  488.18  5729.2   485.6  5737.6  488.46
#Mann= 10 ,-1 , 0
  4686.1     .08       0  4777.8     .15       0  4888.4     .07       0
  4894.4     .15       0  5170.3      .1       0  5213.9     .15       0
  5294.4      .1       0  5528.8     .08       0  5574.2      .1       0
  5645.9     .08       0
#XS Ineff= 2 , 0
                         5045.88          472.54
Permanent Ineff=
       F       F
Bank Sta=4840.8,5022.8
XS Rating Curve= 0 ,0
Exp/Cntr=0.3,0.1

Type RM Length L Ch R = 1 ,111193  ,203,203,203
BEGIN DESCRIPTION:
Mapping XS a3164259
END DESCRIPTION:
XS GIS Cut Line= 5
      3689493.15     10795437.96      3689226.27     10795370.07
      3689057.73      10795337.3      3688982.83     10795334.96
      3688725.48      10794934.9
#Sta/Elev= 30
  4678.8  473.75  4688.8  471.42  4954.2  471.79  4971.2  468.96    4978  465.46
  4983.1  466.94  4998.7  461.89  5001.5  461.39  5004.7  461.89  5011.9  465.64
  5022.1   464.2  5034.8   466.6  5100.3  471.27  5113.8  474.09    5154  471.16
  5199.6  473.91  5209.8  474.17  5329.3  474.29  5371.3   475.1  5448.8  476.47
  5525.9   477.1  5531.9   479.6  5543.9   477.6  5568.3  479.63  5583.4  477.74
  5589.3  480.42  5625.6  481.01  5640.8  478.68  5661.9  483.83  5676.5   481.1
#Mann= 11 ,-1 , 0
  4678.8      .1       0  4998.7     .07       0  5004.7      .1       0
  5100.3      .1       0  5199.6     .15       0  5209.8      .1       0
  5329.3     .05       0  5371.3      .1       0  5448.8     .08       0
  5543.9      .1       0  5568.3     .08       0
Bank Sta=4983.1,5034.8
XS Rating Curve= 0 ,0
Exp/Cntr=0.3,0.1

Type RM Length L Ch R = 1 ,110990  ,403,403,403
BEGIN DESCRIPTION:
Mapping XS b48b5f19
END DESCRIPTION:
XS GIS Cut Line= 3
      3690247.63     10795355.57      3689098.35     10795150.71
      3688650.47     10794866.02
#Sta/Elev= 30
  3895.1  478.68    3972  474.46  4171.7  471.84  4279.1  473.63  4303.2  471.12
  4552.4  469.78  4798.9  465.76  4949.5  467.06  4959.6  470.33  4970.8  468.18
  4977.4  464.56  4982.5  464.95  4990.1  463.92  4997.3  458.73    5000  458.23
  5003.3  458.73  5010.4  464.53  5020.6   465.7  5055.7  465.51  5159.2  467.66
    5373  471.92  5386.2  474.63    5467  475.36  5529.9  482.12  5539.9  482.67
  5555.1  487.86  5570.4   488.6  5576.3  486.22  5582.4  489.98  5593.2  490.96
#Mann= 13 ,-1 , 0
  3895.1      .1       0    3972     .15       0  4171.7      .1       0
  4303.2     .08       0  4552.4      .1       0  4798.9     .08       0
  4970.8     .05       0  4997.3     .04       0  5003.3     .05       0
  5055.7     .08       0  5159.2     .05       0  5386.2     .08       0
  5529.9      .1       0
#XS Ineff= 2 , 0
         4950.95  468.63
Permanent Ineff=
       F       F
Bank Sta=4982.5,5020.6
XS Rating Curve= 0 ,0
Exp/Cntr=0.3,0.1

Type RM Length L Ch R = 1 ,110587  ,536,536,536
BEGIN DESCRIPTION:
COON CREEK 176.0
END DESCRIPTION:
XS GIS Cut Line= 3
      3690299.61     10795260.19      3689199.61     10794760.19
      3688599.59     10794810.19
#Sta/Elev= 30
  3767.2  478.22  3822.1  478.63  3850.7  475.79  4115.3  471.49  4232.7  472.47
    4436   472.1  4571.2  471.42  4644.9  472.07  4694.1  469.76  4863.5  467.57
  4938.2  466.76  4970.4  468.08    4978  467.91  4985.5  465.46  4992.6  456.65
  4995.3  456.15  4998.6  456.65  5005.6  462.42  5038.2  461.65  5136.1   464.1
    5407  469.96  5437.1  468.13  5469.1  469.39  5487.3  470.62  5507.3  474.55
  5511.3  477.13  5537.4  487.27  5547.5  489.18  5557.5  494.08  5577.6  499.15
#Mann= 12 ,-1 , 0
  3767.2     .15       0  4115.3      .1       0  4232.7     .08       0
    4436      .1       0  4571.2     .08       0  4694.1      .1       0
  4863.5     .08       0  4970.4     .05       0  4992.6     .04       0
  4998.6     .05       0  5469.1     .08       0  5511.3      .1       0
Bank Sta=4985.5,5136.1
XS Rating Curve= 0 ,0
Exp/Cntr=0.3,0.1

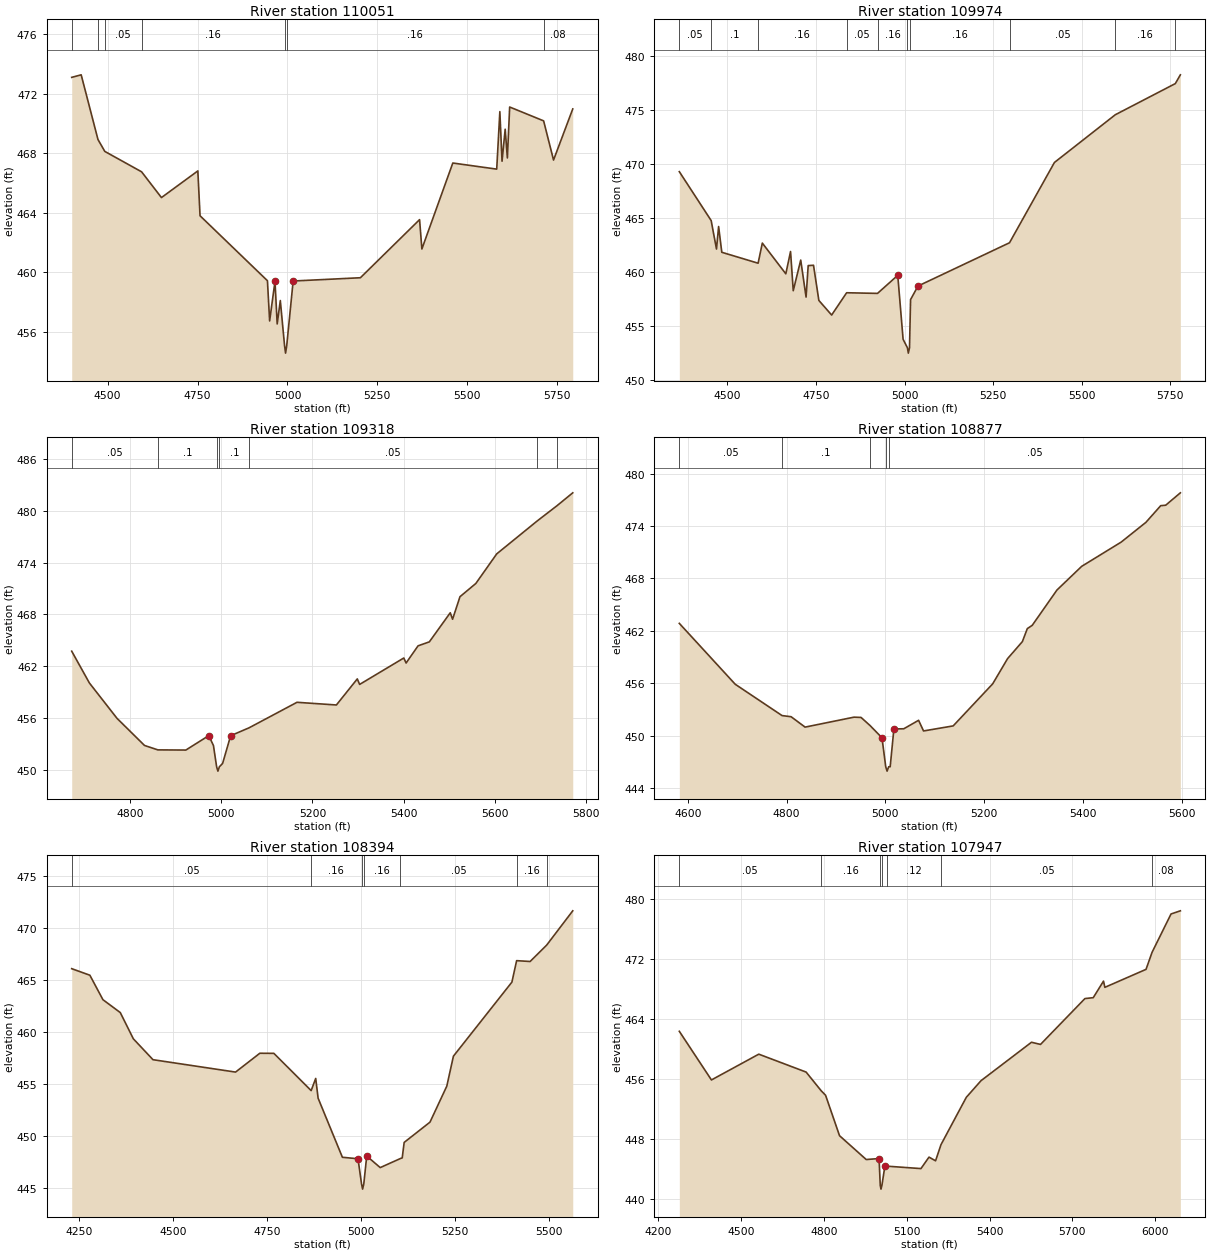
Type RM Length L Ch R = 1 ,110051  ,77,77,77
BEGIN DESCRIPTION:
COON CREEK 175.0
END DESCRIPTION:
XS GIS Cut Line= 2
      3689787.36     10793930.97      3688645.89     10794729.57
#Sta/Elev= 30
  4400.2  473.09  4426.5  473.26  4473.2  468.92  4492.2  468.12  4594.5  466.75
  4649.7  465.02  4750.9  466.81    4757   463.8  4944.4  459.44  4950.5  456.74
  4965.4   459.4  4971.5  456.54  4980.2  458.11    4992  455.08  4994.8  454.58
    4998  455.08  5015.9  459.42  5202.9  459.64  5367.4  463.54  5373.8  461.57
  5459.8  467.34  5581.9  466.93  5590.6  470.79  5596.7  467.46  5605.4  469.61
  5611.5  467.68  5617.9   471.1  5712.3  470.17  5739.9  467.54  5793.3  470.97
#Mann= 7 ,-1 , 0
  4400.2     .05       0  4473.2      .1       0  4492.2     .05       0
  4594.5     .16       0    4992     .07       0    4998     .16       0
  5712.3     .08       0
Bank Sta=4965.4,5015.9
XS Rating Curve= 0 ,0
Exp/Cntr=0.3,0.1

Type RM Length L Ch R = 1 ,109974  ,656,656,656
BEGIN DESCRIPTION:
COON CREEK 174.0
END DESCRIPTION:
XS GIS Cut Line= 3
      3689791.73     10793857.17      3689153.69     10794278.19
      3688603.74     10794624.61
#Sta/Elev= 30
  4364.1  469.29    4454  464.77    4469  462.14    4475  464.22    4484  461.84
  4586.5  460.83  4598.4  462.69  4664.7  459.85  4678.1  461.91  4685.7  458.29
  4706.8  461.12  4721.9   457.7  4727.9  460.61  4742.9  460.64    4758  457.39
  4794.1  456.04  4836.4   458.1  4923.6  458.04  4980.7  459.71  4995.8   453.8
  5007.9  453.02  5010.6  452.52  5013.9  453.02  5016.9  457.47  5037.9  458.72
  5296.2  462.72    5423  470.14  5594.8  474.55  5764.3  477.43  5778.5  478.24
#Mann= 10 ,-1 , 0
  4364.1     .05       0    4454      .1       0  4586.5     .16       0
  4836.4     .05       0  4923.6     .16       0  5007.9     .07       0
  5013.9     .16       0  5296.2     .05       0  5594.8     .16       0
  5764.3     .05       0
Bank Sta=4980.7,5037.9
XS Rating Curve= 0 ,0
Exp/Cntr=0.3,0.1

Type RM Length L Ch R = 1 ,109318  ,441,441,441
BEGIN DESCRIPTION:
COON CREEK 173.0
END DESCRIPTION:
XS GIS Cut Line= 3
       3689848.1     10793748.67      3689499.61     10793710.19
      3688767.43     10793857.18
#Sta/Elev= 30
  4672.9  463.74  4711.6  460.06    4772  455.97  4832.4  452.82  4861.6  452.31
  4922.9  452.29  4973.1  453.96  4983.3  452.82  4990.3  450.35  4993.1  449.85
  4996.3  450.35  5003.4  450.74    5021  453.95  5061.5  454.87  5166.3  457.82
  5252.6  457.51  5298.4  460.53  5303.5  459.89  5400.2  462.95  5405.3  462.37
  5431.5  464.36  5456.2  464.82    5502  468.19  5507.1  467.44  5523.3  470.05
    5558  471.58  5603.8  475.01  5692.4  478.82  5736.1   480.6  5770.3  482.08
#Mann= 7 ,-1 , 0
  4672.9     .05       0  4861.6      .1       0  4990.3     .07       0
  4996.3      .1       0  5061.5     .05       0  5692.4     .08       0
  5736.1     .05       0
Bank Sta=4973.1,5021
XS Rating Curve= 0 ,0
Exp/Cntr=0.3,0.1

Type RM Length L Ch R = 1 ,108877  ,483,483,483
BEGIN DESCRIPTION:
COON CREEK 172.0
END DESCRIPTION:
XS GIS Cut Line= 3
      3689949.59     10793610.16      3689649.61     10793310.19
      3689059.95     10793312.91
#Sta/Elev= 30
    4583  462.86  4696.1  455.89  4790.9   452.3  4809.2  452.17  4837.5  450.98
  4936.5  452.12  4950.7  452.09  4968.6  451.18  4993.1  449.76  5000.7  446.44
  5003.4  445.94  5006.7  446.44  5009.7  446.44  5017.2  450.77  5037.2  450.79
  5067.2  451.76  5077.2  450.54  5137.2  451.12  5217.2  455.94  5247.2  458.82
  5277.2  460.77  5287.2  462.26  5297.2  462.64  5347.2  466.68  5397.2  469.39
  5477.2  472.17  5527.2  474.43  5557.2  476.34  5567.2  476.39  5596.9  477.81
#Mann= 5 ,-1 , 0
    4583     .05       0  4790.9      .1       0  4968.6     .05       0
  5000.7     .03       0  5006.7     .05       0
Bank Sta=4993.1,5017.2
XS Rating Curve= 0 ,0
Exp/Cntr=0.3,0.1

Type RM Length L Ch R = 1 ,108394  ,447,447,447
BEGIN DESCRIPTION:
COON CREEK 171.0
END DESCRIPTION:
XS GIS Cut Line= 4
      3690262.96     10793542.04      3689906.17     10792924.83
      3689783.77     10792875.35      3689313.62     10792745.47
#Sta/Elev= 30
  4230.6   466.1  4278.9  465.47  4313.6  463.12  4359.8  461.88  4394.5  459.36
  4446.8  457.35  4666.4  456.16    4731  457.97  4768.3  457.96  4867.5  454.38
  4879.6  455.55    4886  453.65  4950.6  447.97  4992.1  447.83  5001.5  445.41
  5004.3  444.91  5007.5  445.41  5015.3  448.09  5051.2  446.98  5104.9  447.85
  5109.7  447.91  5114.9   449.4  5183.6  451.35  5228.3  454.81  5245.9  457.69
  5401.5  464.81    5414  466.87  5449.9  466.79  5493.8  468.36  5563.3  471.66
#Mann= 7 ,-1 , 0
  4230.6     .05       0  4867.5     .16       0  5001.5     .07       0
  5007.5     .16       0  5104.9     .05       0    5414     .16       0
  5493.8     .05       0
Bank Sta=4992.1,5015.3
XS Rating Curve= 0 ,0
Exp/Cntr=0.3,0.1

Type RM Length L Ch R = 1 ,107947  ,168,168,168
BEGIN DESCRIPTION:
Mapping XS b6db7351
END DESCRIPTION:
XS GIS Cut Line= 5
      3690312.34     10793395.49      3690220.32     10792723.61
       3690166.5     10792647.23      3689814.07     10792499.66
      3689156.06     10792423.26
#Sta/Elev= 30
  4275.5   462.4  4391.9  455.91  4563.5  459.35  4735.1  456.96  4789.4  454.48
  4805.7  453.86  4856.2  448.47  4952.9  445.29  4999.5  445.42  5003.8  441.84
  5006.5  441.34  5009.8  441.84  5020.4  444.37  5029.5   444.4  5151.3  444.08
  5180.5  445.61  5204.3  445.12    5224  447.28  5315.7  453.59    5369  455.81
    5552  460.94  5584.7  460.65  5745.7  466.77  5775.9  466.89    5813   469.1
    5818  468.27  5967.2  470.67    5989  472.94  6057.8  478.06  6091.6  478.48
#Mann= 7 ,-1 , 0
  4275.5     .05       0  4789.4     .16       0  5003.8     .07       0
  5009.8     .16       0  5029.5     .12       0    5224     .05       0
    5989     .08       0
Bank Sta=4999.5,5020.4
XS Rating Curve= 0 ,0
Exp/Cntr=0.3,0.1

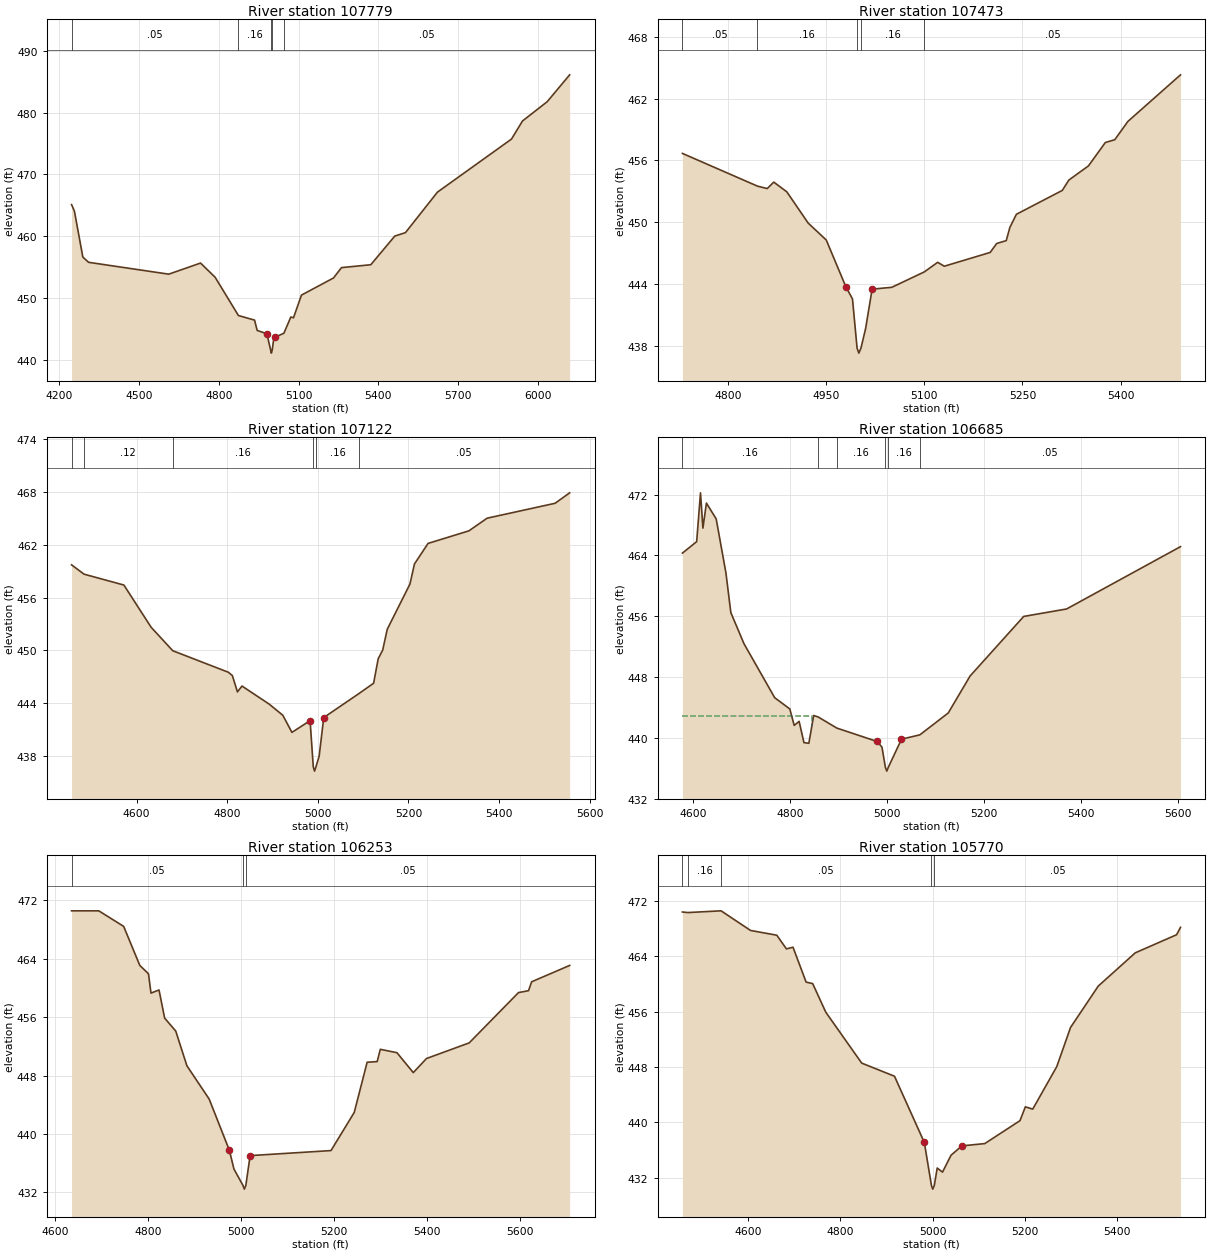
Type RM Length L Ch R = 1 ,107779  ,306,306,306
BEGIN DESCRIPTION:
Mapping XS b382e535
END DESCRIPTION:
XS GIS Cut Line= 4
      3690604.01     10793390.28      3690341.85      10792631.6
      3690395.67     10791824.31      3690558.84     10791621.22
#Sta/Elev= 30
  4246.7   465.1  4257.4  464.04  4289.1   456.6  4310.8  455.75    4612  453.83
  4731.5  455.63  4786.4  453.33  4873.9  447.13  4934.5  446.39  4944.4  444.72
  4980.9  444.17    4995  441.54  4997.7  441.04    5001  441.54  5006.8  443.42
  5012.1  443.64  5044.7  444.25  5070.9  446.89  5080.9  446.77  5110.9  450.44
  5231.2  453.21  5261.3  454.89  5371.5  455.36  5461.7     460  5501.8  460.56
  5622.1  467.12  5900.3  475.71  5941.9  478.65  6034.7  481.77    6119  486.12
#Mann= 5 ,-1 , 0
  4246.7     .05       0  4873.9     .16       0    4995     .07       0
    5001     .16       0  5044.7     .05       0
Bank Sta=4980.9,5012.1
XS Rating Curve= 0 ,0
Exp/Cntr=0.3,0.1

Type RM Length L Ch R = 1 ,107473  ,351,351,351
BEGIN DESCRIPTION:
Mapping XS 82fac23b
END DESCRIPTION:
XS GIS Cut Line= 2
      3690642.19     10792919.49       3690692.1     10792159.93
#Sta/Elev= 30
  4730.3  456.69  4844.9  453.51  4859.9  453.27  4869.9   453.9  4889.9  452.95
  4922.4  449.92  4950.1  448.27  4980.1  443.72  4990.2  442.54  4997.2  437.77
  4999.9  437.27  5003.2  437.77  5010.2  439.64  5020.2  443.49  5050.3  443.67
    5100  445.17  5120.4   446.1  5130.5  445.72  5200.6  447.06  5210.6  447.93
  5225.2  448.21  5230.7  449.49  5240.7  450.77  5310.8  453.09  5320.9   454.1
  5350.9  455.48  5376.6  457.75    5391  458.02  5411.1   459.8  5491.5  464.33
#Mann= 5 ,-1 , 0
  4730.3     .05       0  4844.9     .16       0  4997.2     .07       0
  5003.2     .16       0    5100     .05       0
Bank Sta=4980.1,5020.2
XS Rating Curve= 0 ,0
Exp/Cntr=0.3,0.1

Type RM Length L Ch R = 1 ,107122  ,437,437,437
BEGIN DESCRIPTION:
COON CREEK 168.0
END DESCRIPTION:
XS GIS Cut Line= 3
      3690958.71      10793275.4      3690999.61     10792710.19
      3690969.13     10792178.15
#Sta/Elev= 30
  4456.4  459.72  4483.8  458.66  4571.9  457.42  4632.1  452.61  4679.8  449.94
  4802.5  447.49  4811.4  447.11  4822.6  445.25  4832.6  445.92  4892.7  443.86
  4922.8  442.59  4942.9  440.64    4983  441.98    4990  436.73  4992.8  436.23
    4996  436.73    5003  437.94  5013.1  442.33  5090.5  445.05  5123.2  446.24
  5133.3  449.02  5143.3  450.02  5153.3  452.38  5203.4  457.53  5213.4  459.82
  5243.4  462.16  5333.6  463.59  5373.7  465.03  5523.9  466.73    5556  467.92
#Mann= 6 ,-1 , 0
  4456.4     .16       0  4483.8     .12       0  4679.8     .16       0
    4990     .07       0    4996     .16       0  5090.5     .05       0
Bank Sta=4983,5013.1
XS Rating Curve= 0 ,0
Exp/Cntr=0.3,0.1

Type RM Length L Ch R = 1 ,106685  ,432,432,432
BEGIN DESCRIPTION:
COON CREEK 167.0
END DESCRIPTION:
XS GIS Cut Line= 3
      3691469.13     10793209.41      3691413.58     10792719.81
      3691167.33     10792244.67
#Sta/Elev= 30
  4577.9   464.3  4607.3  465.81  4615.2  472.23  4620.2  467.59  4627.4  470.88
  4647.6   468.8  4667.7  461.69  4677.8  456.48  4704.8   452.4  4768.3  445.28
  4799.5   443.8  4808.6  441.63  4818.7  442.17  4828.7  439.37  4838.8  439.28
  4848.8  442.94  4858.2  442.74  4896.6  441.28  4979.7  439.52  4989.7  438.78
  4996.8  436.12  4999.6  435.62  5002.8  436.12    5030  439.82  5067.8  440.39
  5126.5  443.27  5171.5  448.13  5282.2  455.97  5370.7  456.95  5605.8  465.15
#Mann= 6 ,-1 , 0
  4577.9     .16       0  4858.2     .05       0  4896.6     .16       0
  4996.8     .07       0  5002.8     .16       0  5067.8     .05       0
#XS Ineff= 2 , 0
         4845.03  442.88
Permanent Ineff=
       F       F
Bank Sta=4979.7,5030
XS Rating Curve= 0 ,0
Exp/Cntr=0.3,0.1

Type RM Length L Ch R = 1 ,106253  ,483,483,483
BEGIN DESCRIPTION:
COON CREEK 166.0
END DESCRIPTION:
XS GIS Cut Line= 3
      3692083.74     10792799.68      3691694.83     10792639.95
       3691257.3     10792157.28
#Sta/Elev= 30
  4635.8  470.57  4694.3  470.57  4747.9  468.44  4782.7  463.09  4801.3  461.95
  4806.7   459.3    4824  459.73  4836.1  455.88    4860   454.1    4884  449.35
    4932  444.78  4975.4  437.77  4985.3  435.19  5004.8  432.95  5007.6  432.45
  5010.8  432.95  5020.1  437.04  5194.1  437.73  5244.1  442.95  5271.9  449.83
  5293.5  449.92  5300.2   451.6    5336  451.14  5371.2  448.41  5399.6  450.34
  5491.5  452.48  5597.6  459.37  5619.2  459.63  5625.9  460.85  5707.7  463.09
#Mann= 3 ,-1 , 0
  4635.8     .05       0  5004.8     .03       0  5010.8     .05       0
Bank Sta=4975.4,5020.1
XS Rating Curve= 0 ,0
Exp/Cntr=0.3,0.1

Type RM Length L Ch R = 1 ,105770  ,439,439,439
BEGIN DESCRIPTION:
COON CREEK 165.0
END DESCRIPTION:
XS GIS Cut Line= 4
       3692250.6     10792587.97      3691917.28     10792210.38
      3691839.16     10792186.94      3691403.12     10791953.35
#Sta/Elev= 30
  4457.6  470.43  4469.6  470.35  4541.4   470.6  4605.3  467.76  4662.2  467.07
  4683.1  465.09  4697.4  465.33  4725.8  460.28    4740  460.07  4768.5  455.92
  4846.3  448.56  4917.4  446.66  4982.1  437.07  4997.6  430.82  5000.3  430.32
  5003.6  430.82    5010  433.37  5021.5  432.78    5040  435.23  5063.5  436.58
  5113.1  436.91  5189.5  440.23  5201.1  442.23  5217.1   441.9  5269.2  448.05
  5299.1  453.72  5359.2  459.71  5439.4  464.52    5529  467.14  5537.5  468.21
#Mann= 5 ,-1 , 0
  4457.6     .05       0  4469.6     .16       0  4541.4     .05       0
  4997.6     .03       0  5003.6     .05       0
Bank Sta=4982.1,5063.5
XS Rating Curve= 0 ,0
Exp/Cntr=0.3,0.1

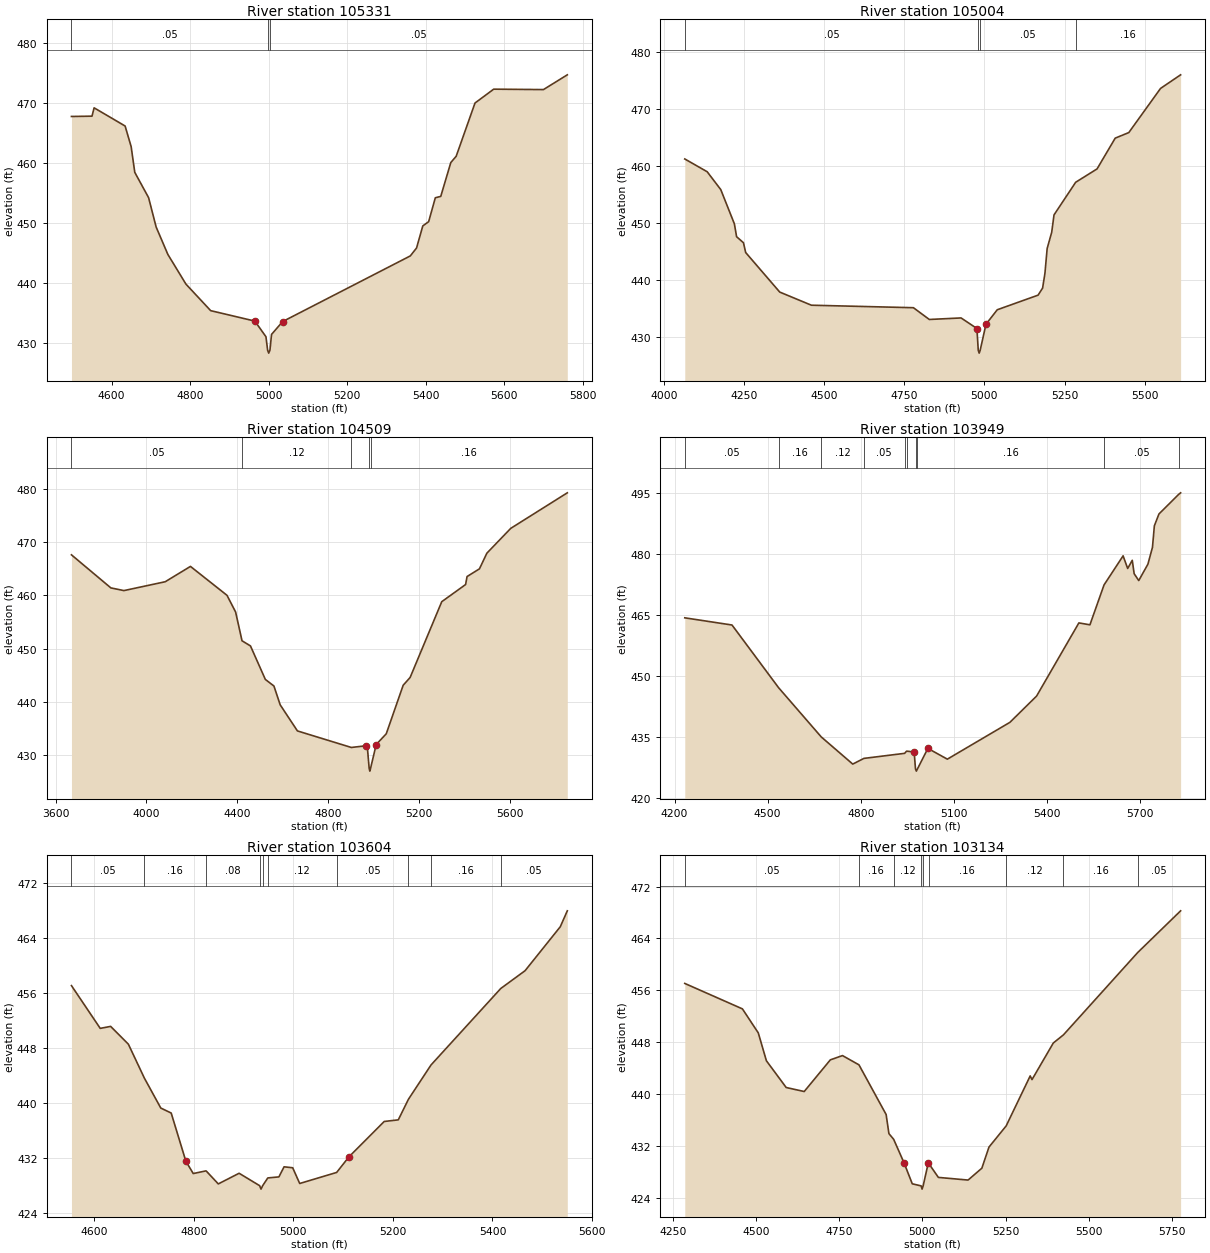
Type RM Length L Ch R = 1 ,105331  ,327,327,327
BEGIN DESCRIPTION:
COON CREEK 164.0
END DESCRIPTION:
XS GIS Cut Line= 4
      3692364.33      10792331.9      3692201.13     10791911.77
      3692114.33     10791828.43       3691463.1     10791596.35
#Sta/Elev= 30
  4497.9  467.75  4550.2   467.8  4555.6  469.19  4634.5  466.16  4649.9  462.72
  4659.1  458.44  4694.3  454.22  4713.5  449.33  4743.4  444.75  4789.4  439.81
  4852.3  435.39  4964.8  433.65  4993.1  431.04  4997.3  428.81  5000.1  428.31
  5003.3  428.81  5007.3  431.43  5035.6  433.57  5360.6  444.51  5376.5  445.83
  5392.4  449.51  5407.3  450.22  5424.3   454.2  5438.1  454.43  5463.7  460.07
  5477.4  461.12  5525.3  469.99  5572.9   472.3  5699.6  472.23  5760.3  474.69
#Mann= 3 ,-1 , 0
  4497.9     .05       0  4997.3     .03       0  5003.3     .05       0
Bank Sta=4964.8,5035.6
XS Rating Curve= 0 ,0
Exp/Cntr=0.3,0.1

Type RM Length L Ch R = 1 ,105004  ,495,495,495
BEGIN DESCRIPTION:
COON CREEK 163.0
END DESCRIPTION:
XS GIS Cut Line= 2
      3693024.03     10792314.52      3691954.64     10791196.52
#Sta/Elev= 30
  4065.2  461.27  4135.1  459.02  4177.5  455.88    4220  449.85  4226.9  447.59
  4248.3  446.53  4255.2  444.81  4361.5  437.85  4460.3  435.54  4778.6   435.1
  4828.2  433.03  4927.3   433.3  4976.7  431.44  4980.9  427.61  4983.7  427.11
  4986.9  427.61    5005  432.19  5040.2  434.74  5167.6  437.31  5181.7  438.56
    5189  441.17  5195.9  445.52  5210.1  448.38  5217.3  451.43  5284.9  457.17
  5351.6  459.52  5408.2  464.93  5450.6  465.91  5549.7  473.68  5612.3  476.07
#Mann= 4 ,-1 , 0
  4065.2     .05       0  4980.9     .03       0  4986.9     .05       0
  5284.9     .16       0
Bank Sta=4976.7,5005
XS Rating Curve= 0 ,0
Exp/Cntr=0.3,0.1

Type RM Length L Ch R = 1 ,104509  ,560,560,560
BEGIN DESCRIPTION:
COON CREEK 162.0
END DESCRIPTION:
XS GIS Cut Line= 4
      3693880.31     10791626.21      3692695.39     10791261.62
      3692543.48      10791183.5      3691834.53     10790877.07
#Sta/Elev= 30
  3669.8  467.66  3843.2  461.43  3900.7  460.92  4082.6  462.59  4193.7  465.48
  4354.6  460.03  4392.5  456.88  4420.7  451.46  4457.9  450.49  4523.3  444.18
  4561.2  442.93  4588.7  439.39  4664.6  434.47  4901.9  431.35    4967  431.67
  4972.6  431.31  4980.5  427.39  4983.3  426.89  4986.5  427.39  5011.3   431.9
  5055.7  433.93  5130.1  443.07  5160.8  444.55    5300  458.83  5404.9  462.06
  5411.4  463.57  5465.9  465.02  5498.6  467.97  5603.7  472.65  5852.7  479.35
#Mann= 5 ,-1 , 0
  3669.8     .05       0  4420.7     .12       0  4901.9     .16       0
  4980.5     .07       0  4986.5     .16       0
Bank Sta=4967,5011.3
XS Rating Curve= 0 ,0
Exp/Cntr=0.3,0.1

Type RM Length L Ch R = 1 ,103949  ,345,345,345
BEGIN DESCRIPTION:
COON CREEK 161.0
END DESCRIPTION:
XS GIS Cut Line= 3
      3693417.81     10791287.22      3692909.97     10790757.69
      3692207.57     10790254.73
#Sta/Elev= 30
    4233  464.29  4385.2  462.52  4535.2  447.12  4672.7  435.01  4774.2  428.33
  4810.2  429.73  4941.3  430.97  4947.7  431.51  4972.1   431.3  4976.4   427.1
  4979.2   426.6  4982.4   427.1  5016.3  432.19    5079  429.54  5280.5  438.59
  5366.5  445.05  5502.8  463.04  5538.4  462.57  5583.8  472.37  5645.3  479.53
    5660  476.42  5674.8  478.43  5680.9  475.13  5695.7  473.45  5725.2  477.48
  5739.9  481.63    5746  486.91  5760.8  489.82  5824.5  494.65  5830.6  495.02
#Mann= 10 ,-1 , 0
    4233     .05       0  4535.2     .16       0  4672.7     .12       0
  4810.2     .05       0  4941.3     .12       0  4947.7     .16       0
  4976.4     .07       0  4982.4     .16       0  5583.8     .05       0
  5824.5     .08       0
Bank Sta=4972.1,5016.3
XS Rating Curve= 0 ,0
Exp/Cntr=0.3,0.1

Type RM Length L Ch R = 1 ,103604  ,470,470,470
BEGIN DESCRIPTION:
COON CREEK 160.0
END DESCRIPTION:
XS GIS Cut Line= 3
      3693399.61     10790910.19      3693149.61     10790560.19
      3692749.61     10790160.19
#Sta/Elev= 30
  4554.5  457.07  4612.3  450.84  4633.2  451.13  4668.8  448.54    4701  443.59
  4733.9  439.24  4754.8  438.51  4784.3  431.49  4799.1   429.7  4824.9  430.09
  4849.4  428.19  4891.2  429.74  4932.5  427.93  4935.2  427.43  4938.5  427.93
  4948.8  429.06  4971.1  429.21  4981.5  430.68  4998.8  430.54  5012.9  428.25
  5087.1  429.86  5111.9  432.14  5182.6  437.28  5210.9  437.52  5231.2  440.51
  5276.6  445.51  5416.7  456.65  5465.5  459.24  5536.2  465.64  5550.3  467.96
#Mann= 10 ,-1 , 0
  4554.5     .05       0    4701     .16       0  4824.9     .08       0
  4932.5     .07       0  4938.5     .08       0  4948.8     .12       0
  5087.1     .05       0  5231.2     .12       0  5276.6     .16       0
  5416.7     .05       0
Bank Sta=4784.3,5111.9
XS Rating Curve= 0 ,0
Exp/Cntr=0.3,0.1

Type RM Length L Ch R = 1 ,103134  ,924,924,924
BEGIN DESCRIPTION:
COON CREEK 159.0
END DESCRIPTION:
XS GIS Cut Line= 2
      3694120.94     10790505.96      3692733.33     10789959.59
#Sta/Elev= 30
  4285.4  457.06  4458.8  453.13  4506.5  449.42  4530.9  445.12  4590.4  440.99
  4644.6  440.37  4723.2  445.26  4759.7  445.92  4809.3  444.49    4891  436.82
  4899.4  433.87  4913.7  432.99  4945.2  429.32  4969.6  426.12  4996.3   425.8
  4999.1   425.3  5002.3   425.8  5017.6  429.31  5018.5  429.31  5048.1  427.11
  5137.4   426.7  5178.9  428.53  5200.3  431.79    5252  435.06  5324.3  442.78
  5329.7  442.21  5393.8  447.86  5424.3  449.12  5647.4  461.82  5776.7  468.27
#Mann= 9 ,-1 , 0
  4285.4     .05       0  4809.3     .16       0  4913.7     .12       0
  4996.3     .07       0  5002.3     .12       0  5018.5     .16       0
    5252     .12       0  5424.3     .16       0  5647.4     .05       0
Bank Sta=4945.2,5017.6
XS Rating Curve= 0 ,0
Exp/Cntr=0.3,0.1