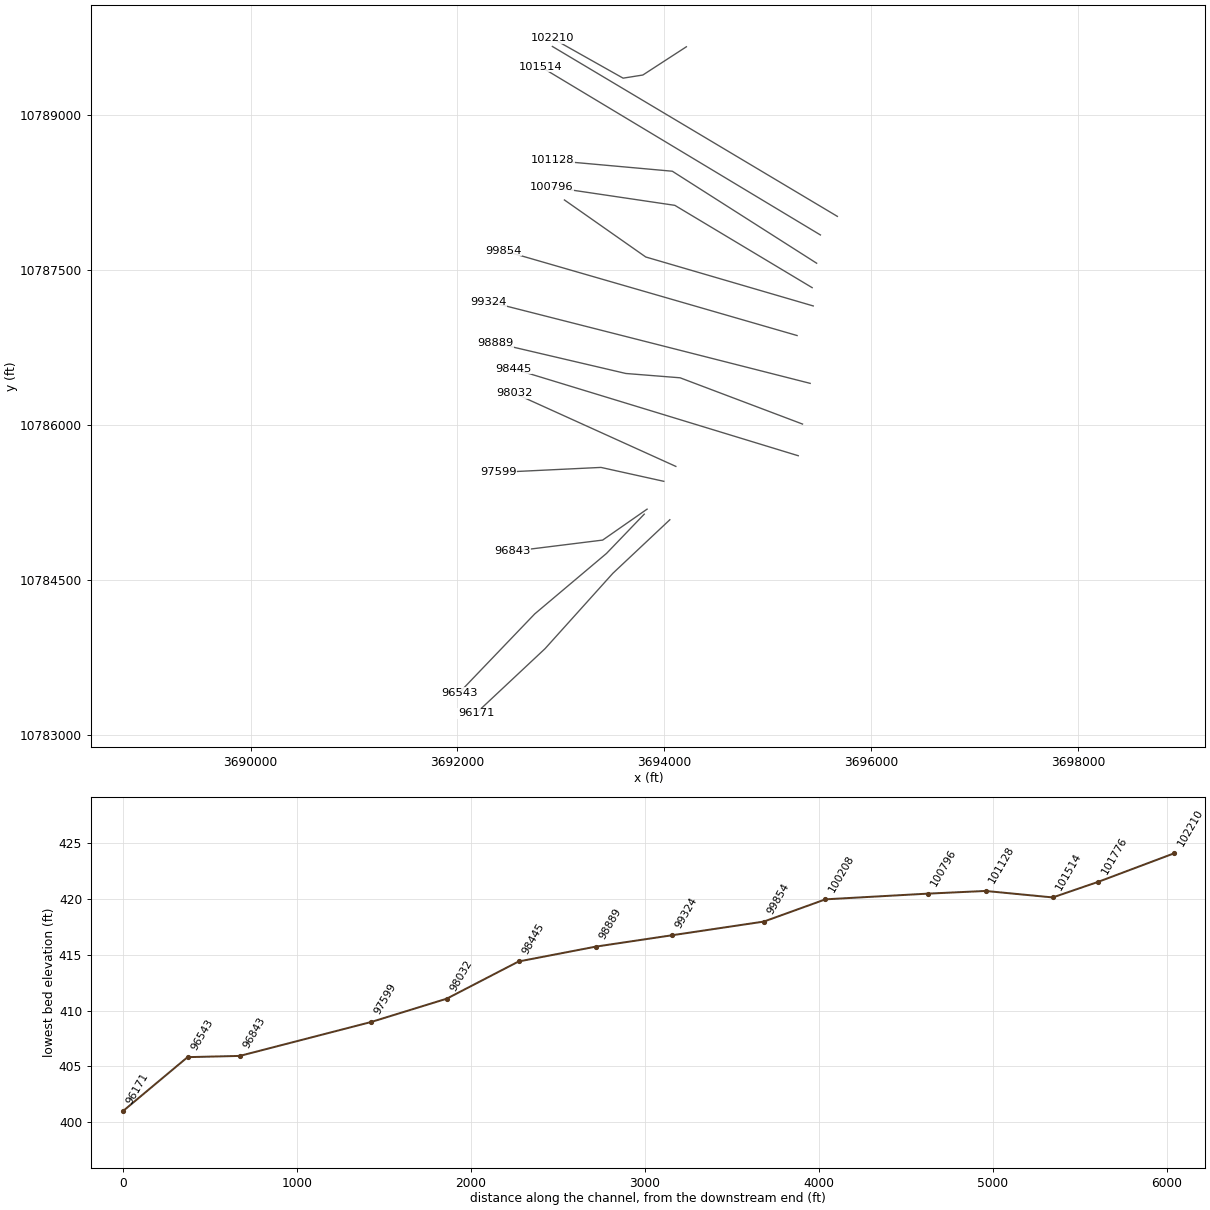
HEC-RAS study COON CREEK.prj: COON CREEK Base Level Engineering

--- COON CREEK.g01 (geometry) --- (continued)

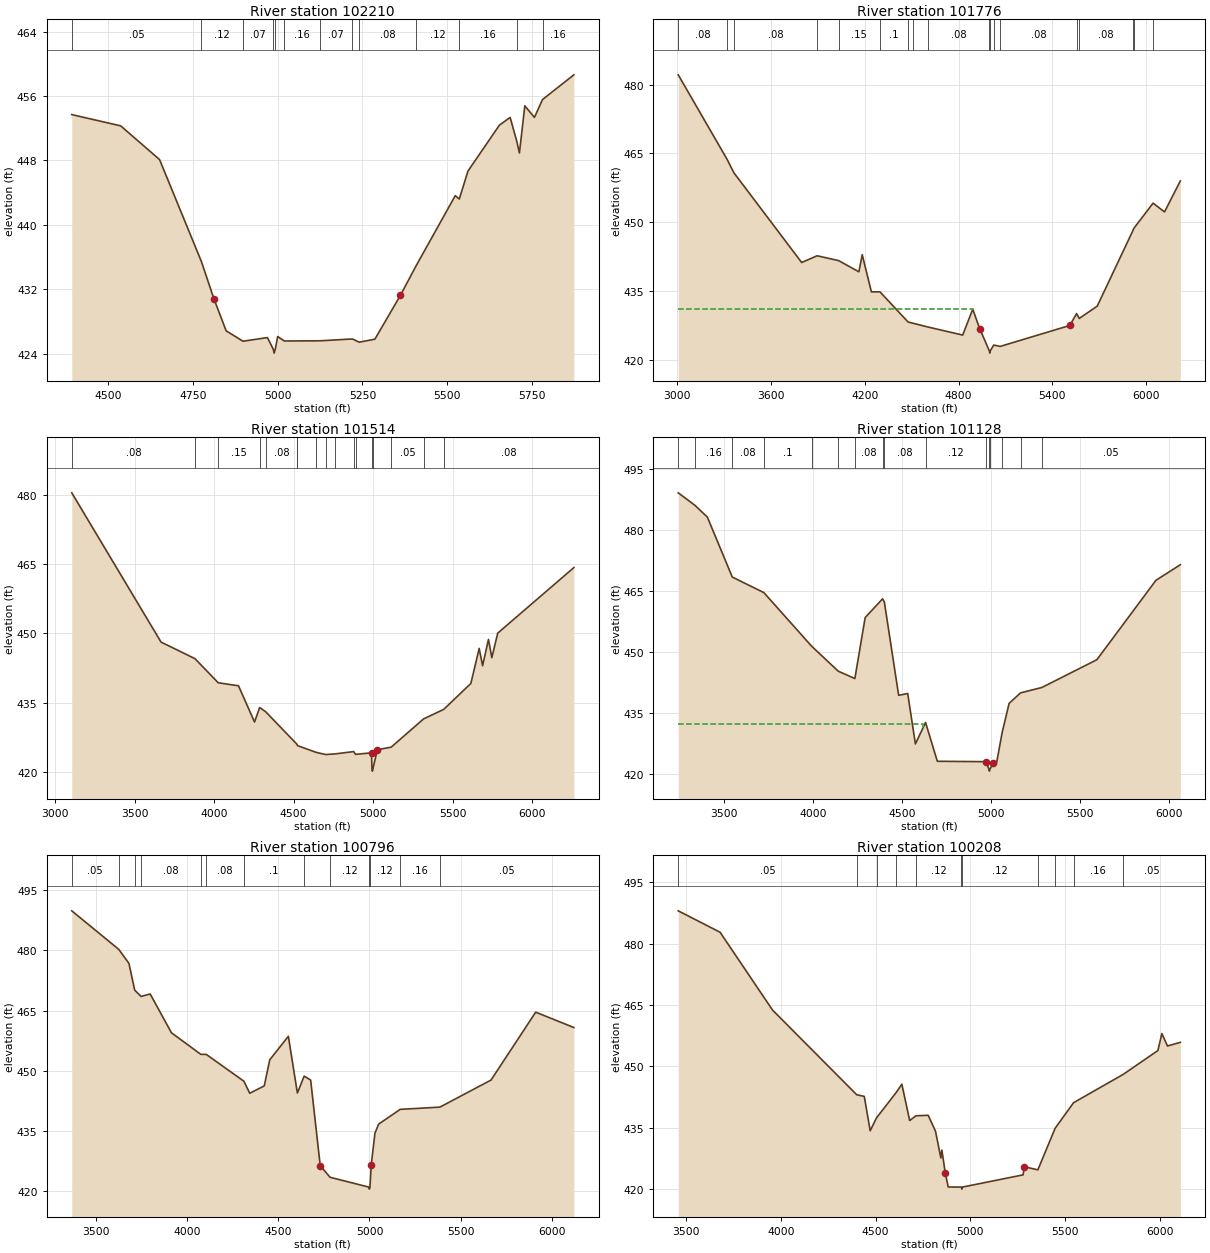
Type RM Length L Ch R = 1 ,102210  ,434,434,434
BEGIN DESCRIPTION:
COON CREEK 158.0
END DESCRIPTION:
XS GIS Cut Line= 4
      3694214.64     10789664.38      3693793.62     10789390.93
      3693602.65     10789360.55      3692918.34     10789746.01
#Sta/Elev= 30
  4392.7  453.69    4537  452.29  4651.7   448.1  4775.1  435.43  4811.8  430.83
    4848  426.83  4897.7  425.54  4969.7  425.99  4986.9  424.56  4989.6  424.06
  4992.9  424.56    5000  426.12  5019.6  425.57  5124.4  425.59  5220.5  425.82
  5240.6  425.42  5286.7  425.79  5361.9  431.23  5407.4  434.84  5523.7  443.62
  5535.6   443.2  5561.3  446.68    5654  452.38  5685.6  453.34  5705.2  450.38
    5713  448.92  5728.9  454.78  5757.3  453.34  5781.1  455.56  5873.5  458.63
#Mann= 13 ,-1 , 0
  4392.7     .05       0  4775.1     .12       0  4897.7     .07       0
  4986.9     .07       0  4992.9     .07       0  5019.6     .16       0
  5124.4     .07       0  5220.5     .16       0  5240.6     .08       0
  5407.4     .12       0  5535.6     .16       0  5705.2     .08       0
  5781.1     .16       0
Bank Sta=4811.8,5361.9
XS Rating Curve= 0 ,0
Exp/Cntr=0.3,0.1

Type RM Length L Ch R = 1 ,101776  ,262,262,262
BEGIN DESCRIPTION:
COON CREEK 157.0
END DESCRIPTION:
XS GIS Cut Line= 2
      3695674.81     10788022.37      3692918.78     10789667.31
#Sta/Elev= 30
  3008.2  482.12  3320.7  463.71  3363.9   460.8  3797.3  441.25  3896.1  442.72
  4034.1  441.66  4163.1  439.23  4184.5  442.95  4242.9  434.86  4297.8  434.87
  4477.4   428.3  4509.3  428.03  4601.9  427.23  4826.7  425.45  4890.9  431.09
  4935.8  426.81    4997  422.02  4999.8  421.52    5003  422.02  5025.2  423.28
  5066.3  422.98  5511.7  427.55  5554.9  430.13  5571.6  429.07  5686.9  431.76
    5914  448.15  5922.1  448.75  6043.7  454.18    6117  452.27  6217.8  459.01
#Mann= 18 ,-1 , 0
  3008.2     .08       0  3320.7      .1       0  3363.9     .08       0
  3896.1      .1       0  4034.1     .15       0  4297.8      .1       0
  4477.4     .08       0  4509.3      .1       0  4601.9     .08       0
    4997     .07       0    5003     .08       0  5025.2     .05       0
  5066.3     .08       0  5554.9     .07       0  5571.6     .08       0
    5914     .12       0  5922.1     .16       0  6043.7     .08       0
#XS Ineff= 2 , 0
         4892.01  431.15
Permanent Ineff=
       F       F
Bank Sta=4935.8,5511.7
XS Rating Curve= 0 ,0
Exp/Cntr=0.3,0.1

Type RM Length L Ch R = 1 ,101514  ,386,386,386
BEGIN DESCRIPTION:
COON CREEK 156.0
END DESCRIPTION:
XS GIS Cut Line= 2
      3695510.95     10787842.47      3692803.66     10789472.06
#Sta/Elev= 30
  3103.4  480.52  3665.2  448.13  3878.8  444.53    4025   439.3  4152.7  438.64
  4253.7  430.78  4285.8  433.92  4322.9  433.04  4522.4  425.89  4523.3  425.67
  4640.7   424.2  4701.8  423.72    4759  423.85  4877.4  424.36  4889.7  423.76
  4989.8  424.09  4992.8  420.62  4995.5  420.12  4998.8  420.62  5026.7  424.75
    5114  425.33  5317.6  431.45  5444.8  433.53  5615.2  439.15  5667.6  446.76
    5689  442.99  5725.9  448.71  5747.2  444.73  5784.1  450.06  6263.3  464.29
#Mann= 17 ,-1 , 0
  3103.4     .08       0  3878.8      .1       0    4025     .15       0
  4285.8      .1       0  4322.9     .08       0  4522.4     .12       0
  4523.3     .08       0  4640.7     .05       0  4701.8     .08       0
    4759     .05       0  4877.4     .16       0  4889.7     .08       0
  4992.8     .07       0  4998.8     .08       0    5114     .05       0
  5317.6     .16       0  5444.8     .08       0
Bank Sta=4989.8,5026.7
XS Rating Curve= 0 ,0
Exp/Cntr=0.3,0.1

Type RM Length L Ch R = 1 ,101128  ,332,332,332
BEGIN DESCRIPTION:
COON CREEK 155.0
END DESCRIPTION:
XS GIS Cut Line= 3
      3695474.47     10787568.88      3694078.63     10788459.51
      3692923.48     10788563.58
#Sta/Elev= 30
  3245.6  489.05  3339.2  485.98  3408.8   483.1  3548.8  468.36    3726  464.54
  3993.1  451.41  4142.8  445.25  4236.2  443.44  4293.9  458.41  4391.7  463.02
  4401.5  462.24  4481.7  439.32  4532.5  439.76  4575.6  427.38  4632.6  432.64
  4698.6  423.12  4970.7  423.02  4971.2     423  4987.8   421.2  4990.5   420.7
  4993.8   421.2  5010.8  422.67  5030.9  422.75  5062.3  430.22  5101.2  437.34
  5165.3  439.92  5284.7  441.24  5593.2  448.06  5924.5  467.56  6061.2  471.39
#Mann= 16 ,-1 , 0
  3245.6     .05       0  3339.2     .16       0  3548.8     .08       0
    3726      .1       0  3993.1     .08       0  4142.8      .1       0
  4236.2     .08       0  4391.7      .1       0  4401.5     .08       0
  4632.6     .12       0  4971.2     .16       0  4987.8     .07       0
  4993.8     .16       0  5062.3     .12       0  5165.3     .16       0
  5284.7     .05       0
#XS Ineff= 2 , 0
         4616.53  432.22
Permanent Ineff=
       F       F
Bank Sta=4970.7,5010.8
XS Rating Curve= 0 ,0
Exp/Cntr=0.3,0.1

Type RM Length L Ch R = 1 ,100796  ,588,588,588
BEGIN DESCRIPTION:
COON CREEK 154.0
END DESCRIPTION:
XS GIS Cut Line= 3
      3695431.09     10787332.32      3694102.94     10788129.22
       3692910.2      10788306.3
#Sta/Elev= 30
  3366.7  489.86  3624.4  480.26  3680.4  476.76    3712  470.08    3747  468.51
    3797  469.12  3913.6  459.45  4074.5  454.08  4104.9  454.05  4310.9  447.38
  4343.1  444.37  4422.8   446.2    4453  452.71    4555  458.57  4604.6  444.44
  4641.8  448.64  4677.5  447.64  4729.9  426.31  4783.7  423.42  4996.8  420.96
  4999.6  420.46  5002.8  420.96  5009.9  426.59  5030.2  434.43  5050.4  436.67
  5168.7  440.35  5386.5  440.91  5667.1  447.66  5912.1  464.59  6121.4  460.76
#Mann= 13 ,-1 , 0
  3366.7     .05       0  3624.4     .16       0    3712     .05       0
    3747     .08       0  4074.5     .05       0  4104.9     .08       0
  4310.9      .1       0  4641.8     .08       0  4783.7     .12       0
  4996.8     .07       0  5002.8     .12       0  5168.7     .16       0
  5386.5     .05       0
Bank Sta=4729.9,5009.9
XS Rating Curve= 0 ,0
Exp/Cntr=0.3,0.1

Type RM Length L Ch R = 1 ,100208  ,354,354,354
BEGIN DESCRIPTION:
COON CREEK 153.0
END DESCRIPTION:
XS GIS Cut Line= 3
      3695441.51     10787155.25      3693821.69     10787629.22
      3693035.26     10788181.28
#Sta/Elev= 30
  3458.9  488.02  3679.7  482.78  3956.5  463.74  4400.4  443.04  4440.3  442.63
  4471.6  434.23  4504.8  437.38  4609.1  443.61  4638.6  445.61  4679.9  436.73
  4713.5  437.89  4777.6  438.01  4816.2   434.1  4844.4  427.58  4849.6   429.5
  4867.5  423.94  4883.1  420.47  4952.2  420.45  4954.9  419.95  4958.2  420.45
  5278.2  423.44  5284.3  425.44    5356  424.66  5447.3  434.85  5544.4  441.09
    5806  448.01  5989.3  453.85  6010.2     458  6039.8  454.96  6107.5  455.85
#Mann= 11 ,-1 , 0
  3458.9     .05       0  4400.4      .1       0  4504.8     .15       0
  4609.1     .08       0  4713.5     .12       0  4952.2     .07       0
  4958.2     .12       0    5356     .05       0  5447.3     .12       0
  5544.4     .16       0    5806     .05       0
Bank Sta=4867.5,5284.3
XS Rating Curve= 0 ,0
Exp/Cntr=0.3,0.1

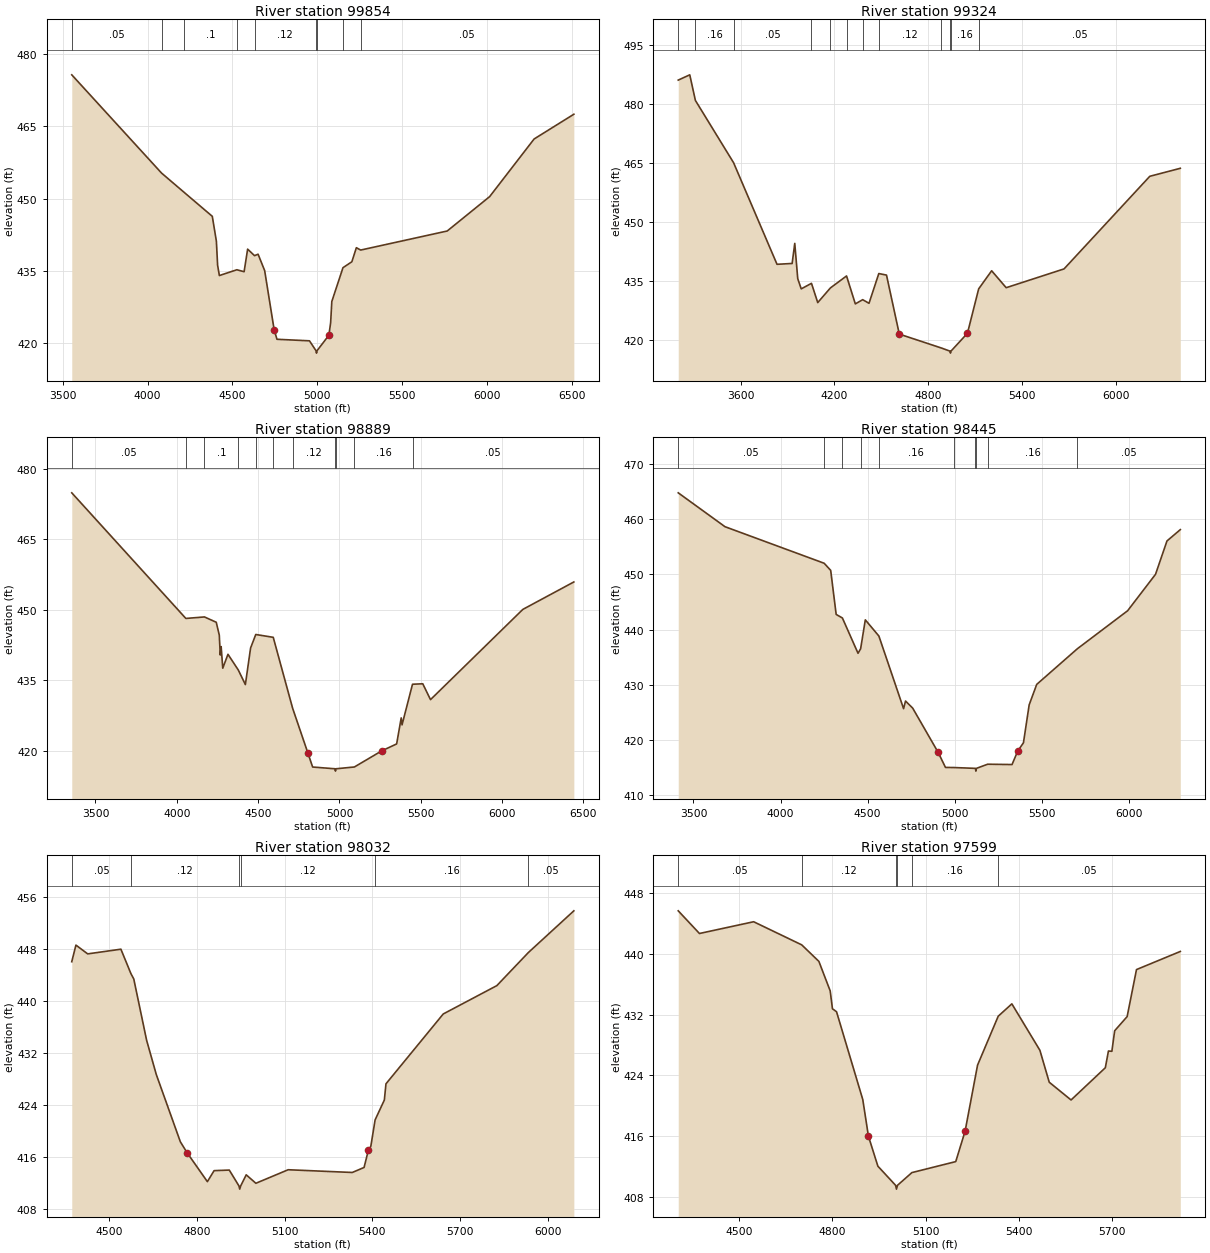
Type RM Length L Ch R = 1 ,99854   ,530,530,530
BEGIN DESCRIPTION:
COON CREEK 152.0
END DESCRIPTION:
XS GIS Cut Line= 2
      3695285.21      10786868.8      3692443.02     10787691.27
#Sta/Elev= 30
  3553.1  475.64  4081.9  455.29  4213.3  451.34  4381.3  446.31  4405.4  441.14
  4412.6  436.16    4423  434.04    4526  435.24  4568.7  434.83  4589.5  439.51
  4630.2  438.16  4651.1  438.46  4689.9  435.06  4745.7  422.82  4762.3  420.83
  4953.9  420.51  4992.5  418.46  4995.3  417.96  4998.5  418.46  5068.4  421.67
  5078.8  424.32  5085.5  428.65  5151.4  435.67  5203.8   436.9  5230.3  439.81
  5255.6  439.32  5765.6  443.27  6015.8   450.4  6277.7  462.34  6511.9  467.47
#Mann= 9 ,-1 , 0
  3553.1     .05       0  4081.9     .08       0  4213.3      .1       0
    4526     .08       0  4630.2     .12       0  4992.5     .07       0
  4998.5     .12       0  5151.4     .16       0  5255.6     .05       0
Bank Sta=4745.7,5068.4
XS Rating Curve= 0 ,0
Exp/Cntr=0.3,0.1

Type RM Length L Ch R = 1 ,99324   ,435,435,435
BEGIN DESCRIPTION:
COON CREEK 151.0
END DESCRIPTION:
XS GIS Cut Line= 2
      3695411.73     10786405.91      3692300.58     10787197.59
#Sta/Elev= 30
  3201.4  486.04  3275.1  487.38  3311.1  480.88  3555.3  465.07    3833  439.28
  3929.7  439.49  3946.5  444.59  3965.5  435.64  3987.8  433.04  4053.4  434.45
  4093.4  429.56  4174.4  433.28  4277.6  436.32  4333.7  429.23  4380.8   430.3
  4421.2  429.38  4483.9  436.93  4533.1  436.54  4614.9  421.56  4884.7  418.02
  4939.2  417.23    4942  416.73  4945.2  417.23  5050.6  421.77  5122.4  433.04
  5205.4  437.64  5298.3  433.34  5668.3  438.11  6216.6  461.62  6411.7  463.65
#Mann= 12 ,-1 , 0
  3201.4     .05       0  3311.1     .16       0  3555.3     .05       0
  4053.4     .08       0  4174.4      .1       0  4277.6     .08       0
  4380.8     .16       0  4483.9     .12       0  4884.7     .16       0
  4939.2     .07       0  4945.2     .16       0  5122.4     .05       0
Bank Sta=4614.9,5050.6
XS Rating Curve= 0 ,0
Exp/Cntr=0.3,0.1

Type RM Length L Ch R = 1 ,98889   ,444,444,444
BEGIN DESCRIPTION:
COON CREEK 150.0
END DESCRIPTION:
XS GIS Cut Line= 4
      3695337.74     10786011.87       3694153.7     10786459.79
      3693629.39     10786501.46      3692368.97      10786796.6
#Sta/Elev= 30
  3354.5  474.85  4055.9  448.16  4170.2  448.48  4242.6  447.35  4261.3  444.62
  4267.5  440.39  4272.8  442.18  4282.7  437.59  4314.7  440.54  4378.2  437.21
  4421.7  434.11  4453.7  441.87  4485.6  444.75    4593  444.15  4712.3  429.07
  4805.1  419.66  4835.2  416.59  4972.6  416.22  4975.4  415.72  4978.6  416.22
  5091.9   416.6  5259.1  420.01  5351.6   421.5  5379.7  427.03  5384.8  425.55
  5449.1  434.18  5512.2  434.28  5559.8  430.91  6127.3  450.08  6440.9  455.91
#Mann= 11 ,-1 , 0
  3354.5     .05       0  4055.9     .08       0  4170.2      .1       0
  4378.2     .08       0  4485.6     .05       0    4593     .16       0
  4712.3     .12       0  4972.6     .07       0  4978.6     .12       0
  5091.9     .16       0  5449.1     .05       0
Bank Sta=4805.1,5259.1
XS Rating Curve= 0 ,0
Exp/Cntr=0.3,0.1

Type RM Length L Ch R = 1 ,98445   ,413,413,413
BEGIN DESCRIPTION:
COON CREEK 149.0
END DESCRIPTION:
XS GIS Cut Line= 2
      3695296.55     10785705.29      3692540.51     10786547.29
#Sta/Elev= 30
  3412.8  464.74  3681.3  458.61  4250.2     452  4287.9  450.71  4319.3  442.74
    4355   442.1  4444.8  435.71  4459.7  436.53  4486.6  441.76  4564.5  438.83
  4706.2  425.69  4717.4  427.07  4758.5  425.79  4904.9  417.77  4946.7  415.06
  4993.3  415.04  5118.5  414.89  5121.2  414.39  5124.5  414.89  5188.6  415.64
  5328.7  415.58  5361.5  418.02  5394.3  419.52  5427.1  426.38  5470.4  430.08
  5703.3  436.52  5992.3  443.41  6152.4     450    6218  456.03  6294.6  458.08
#Mann= 10 ,-1 , 0
  3412.8     .05       0  4250.2     .08       0    4355      .1       0
  4459.7     .05       0  4564.5     .16       0  4993.3     .12       0
  5118.5     .07       0  5124.5     .12       0  5188.6     .16       0
  5703.3     .05       0
Bank Sta=4904.9,5361.5
XS Rating Curve= 0 ,0
Exp/Cntr=0.3,0.1

Type RM Length L Ch R = 1 ,98032   ,433,433,433
BEGIN DESCRIPTION:
COON CREEK 148.0
END DESCRIPTION:
XS GIS Cut Line= 2
      3694112.56     10785601.98      3692550.02     10786310.33
#Sta/Elev= 30
    4373  446.03  4387.2  448.58  4427.4  447.23  4540.9  447.95  4575.1   444.2
  4584.9  443.37  4628.8  433.94  4661.7   428.7  4744.1  418.33  4767.2  416.65
  4836.4  412.21  4859.3   413.9  4911.2  413.99  4944.2  411.56  4946.9  411.06
  4950.2  411.56  4969.1  413.26  5002.1  411.96  5112.4  414.04  5331.5  413.62
  5371.8  414.39  5386.4  417.03  5394.9  417.65  5409.5   421.7  5441.1  424.76
  5446.6  427.25  5642.3  437.99  5825.5  442.35  5933.3  447.44  6088.6  453.85
#Mann= 6 ,-1 , 0
    4373     .05       0  4575.1     .12       0  4944.2     .07       0
  4950.2     .12       0  5409.5     .16       0  5933.3     .05       0
Bank Sta=4767.2,5386.4
XS Rating Curve= 0 ,0
Exp/Cntr=0.3,0.1

Type RM Length L Ch R = 1 ,97599   ,756,756,756
BEGIN DESCRIPTION:
COON CREEK 147.0
END DESCRIPTION:
XS GIS Cut Line= 3
      3693996.23     10785457.59      3693388.59     10785592.14
        3692399.      10785544.4
#Sta/Elev= 30
  4305.2  445.69  4373.4   442.7  4547.5  444.25    4702   441.2  4757.1  439.02
  4793.4  435.13  4800.7  432.77  4813.8  432.38  4898.1   420.8  4916.3  415.96
  4946.6  412.01  5003.6  409.48  5006.4  408.98  5009.6  409.48  5055.9  411.16
  5196.8  412.61  5226.9  416.63  5266.9  425.34  5333.3  431.79  5377.1  433.42
  5467.2  427.29  5497.2  423.08  5567.3  420.74  5677.4  424.99  5687.4   427.2
  5698.4  427.16  5707.4  429.87  5747.5  431.74  5777.5  437.94  5918.3  440.33
#Mann= 6 ,-1 , 0
  4305.2     .05       0    4702     .12       0  5003.6     .07       0
  5009.6     .12       0  5055.9     .16       0  5333.3     .05       0
Bank Sta=4916.3,5226.9
XS Rating Curve= 0 ,0
Exp/Cntr=0.3,0.1

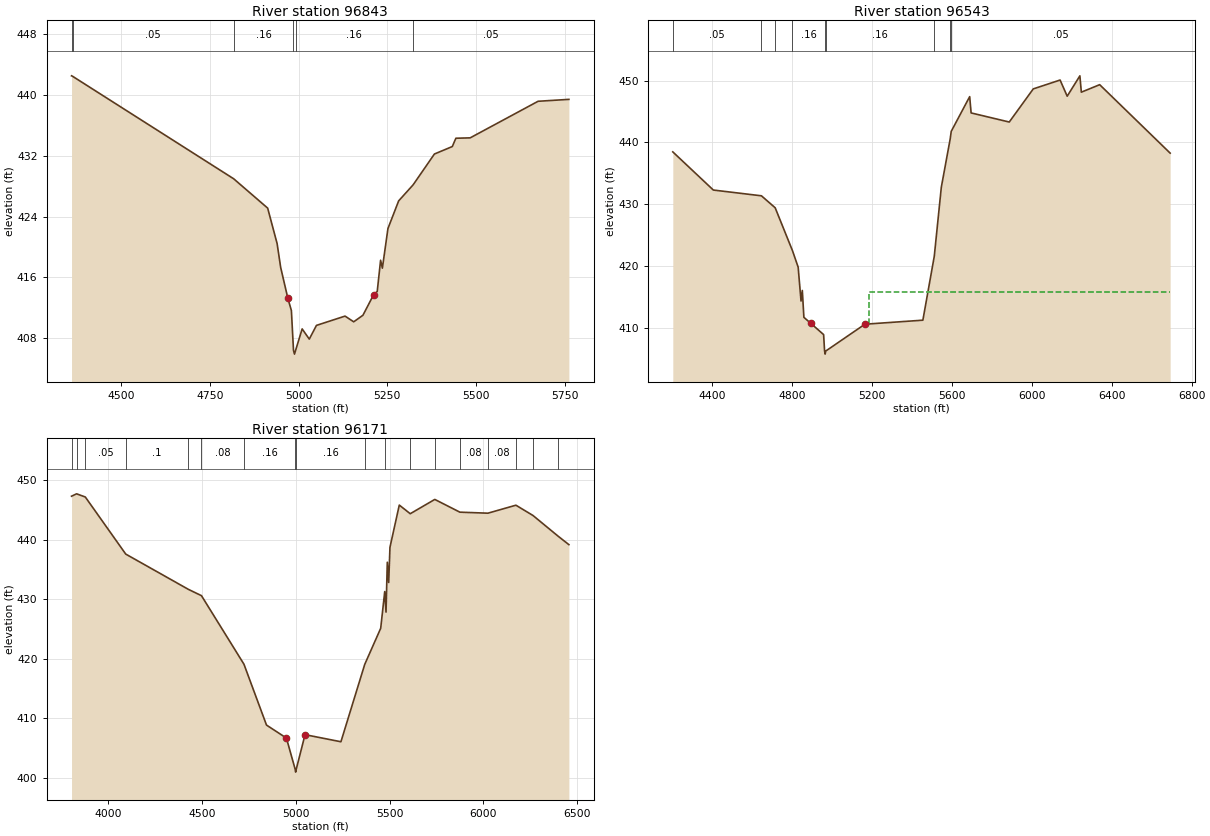
Type RM Length L Ch R = 1 ,96843   ,300,300,300
BEGIN DESCRIPTION:
COON CREEK 146.0
END DESCRIPTION:
XS GIS Cut Line= 3
      3693834.53     10785188.08      3693404.85     10784888.61
      3692533.51     10784780.24
#Sta/Elev= 30
  4360.2  442.46  4363.1   442.4  4817.2  428.95    4913   425.1  4939.6  420.45
  4949.7  417.31  4969.8  413.29  4979.9  411.65  4985.8  406.44  4988.6  405.94
  4991.8  406.44  5010.2  409.25  5030.3  407.91  5050.5  409.71  5131.1  410.93
  5155.5  410.18  5181.5  411.04  5211.7  413.74  5221.8  414.16  5231.3  418.26
  5236.3  417.22    5252  422.42  5282.2  426.05  5322.9  428.15    5383   432.2
  5433.4  433.18  5443.5  434.27  5483.8  434.32  5675.2  439.12    5762  439.37
#Mann= 6 ,-1 , 0
  4360.2     .08       0  4363.1     .05       0  4817.2     .16       0
  4985.8     .07       0  4991.8     .16       0  5322.9     .05       0
Bank Sta=4969.8,5211.7
XS Rating Curve= 0 ,0
Exp/Cntr=0.3,0.1

Type RM Length L Ch R = 1 ,96543   ,372,372,372
BEGIN DESCRIPTION:
COON CREEK 145.0
END DESCRIPTION:
XS GIS Cut Line= 4
      3693807.06     10785139.58      3693442.47      10784759.8
      3692747.97     10784173.87      3692018.89     10783412.18
#Sta/Elev= 30
  4202.9  438.48  4405.8  432.32  4646.5  431.39  4715.3  429.46  4801.8  422.54
  4830.4  419.87  4844.7   414.4  4851.2  416.11    4859  411.77  4894.1  410.79
  4957.8  408.98  4962.6  406.33  4965.3  405.83  4968.6  406.33  5164.5  410.66
  5454.6  411.31  5511.7  421.63  5546.9  432.77  5591.6  440.62  5596.6   441.8
  5688.9   447.4  5696.1  444.77    5887   443.3  6007.2  448.65  6141.5  450.08
    6177  447.47  6240.5  450.76  6247.8  448.12  6339.6  449.33  6692.4  438.28
#Mann= 9 ,-1 , 0
  4202.9     .05       0  4646.5     .08       0  4715.3     .05       0
  4801.8     .16       0  4962.6     .07       0  4968.6     .16       0
  5511.7     .07       0  5591.6     .08       0  5596.6     .05       0
#XS Ineff= 2 , 0
                         5182.95          415.82
Permanent Ineff=
       F       F
Bank Sta=4894.1,5164.5
XS Rating Curve= 0 ,0
Exp/Cntr=0.3,0.1

Type RM Length L Ch R = 1 ,96171   ,472,472,472
BEGIN DESCRIPTION:
COON CREEK 144.0
END DESCRIPTION:
XS GIS Cut Line= 4
      3694054.47     10785085.34      3693503.24     10784566.66
      3692847.85     10783837.49      3692179.71     10783211.03
#Sta/Elev= 30
  3803.1  447.32  3830.1  447.72  3876.5  447.19  4092.3   437.6  4426.4  431.68
  4496.2  430.62  4722.9  419.11  4843.2  408.89  4949.4  406.71    4996  401.49
  4998.7  400.99    5002  401.49  5048.8  407.28  5240.2  406.09  5367.2  419.08
  5452.4  425.14  5473.9  431.31  5480.8  427.86  5487.6  436.24    5495  432.83
  5501.8  438.75  5551.6  445.83    5610  444.38    5741  446.78  5874.8  444.64
  6024.3  444.47  6173.7  445.81  6264.9  444.08  6400.7  440.56  6456.3  439.19
#Mann= 18 ,-1 , 0
  3803.1     .05       0  3830.1     .08       0  3876.5     .05       0
  4092.3      .1       0  4426.4     .05       0  4496.2     .08       0
  4722.9     .16       0    4996     .07       0    5002     .16       0
  5367.2      .1       0  5473.9     .08       0    5610     .08       0
    5741     .08       0  5874.8     .08       0  6024.3     .08       0
  6173.7     .08       0  6264.9      .1       0  6400.7     .05       0
Bank Sta=4949.4,5048.8
XS Rating Curve= 0 ,0
Exp/Cntr=0.3,0.1