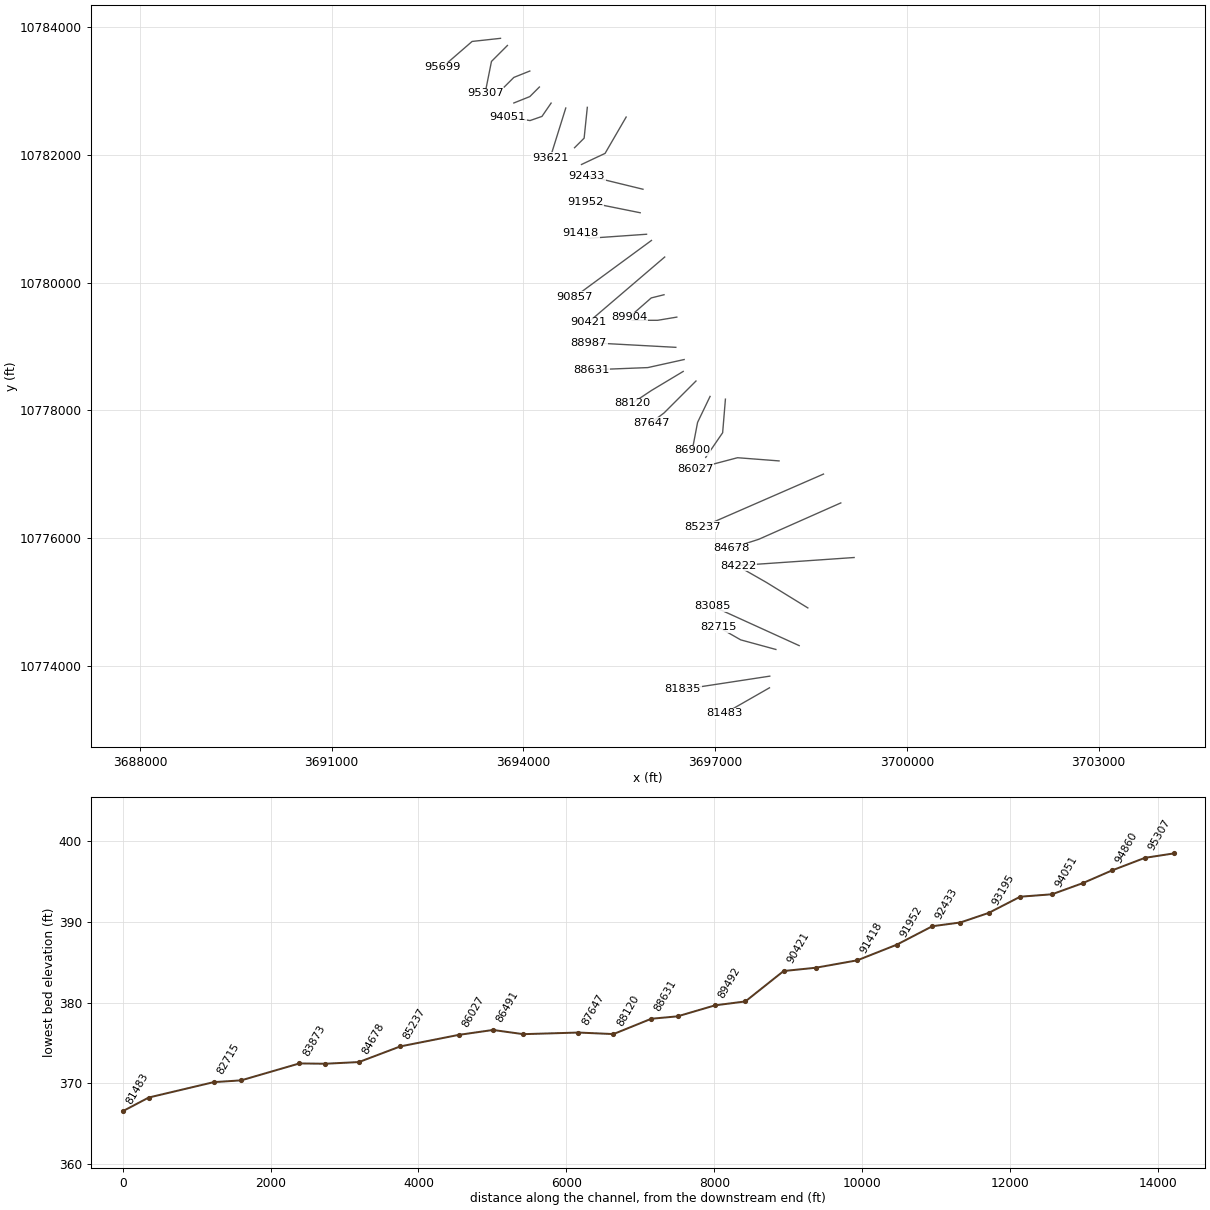
HEC-RAS study COON CREEK.prj: COON CREEK Base Level Engineering

--- COON CREEK.g01 (geometry) --- (continued)

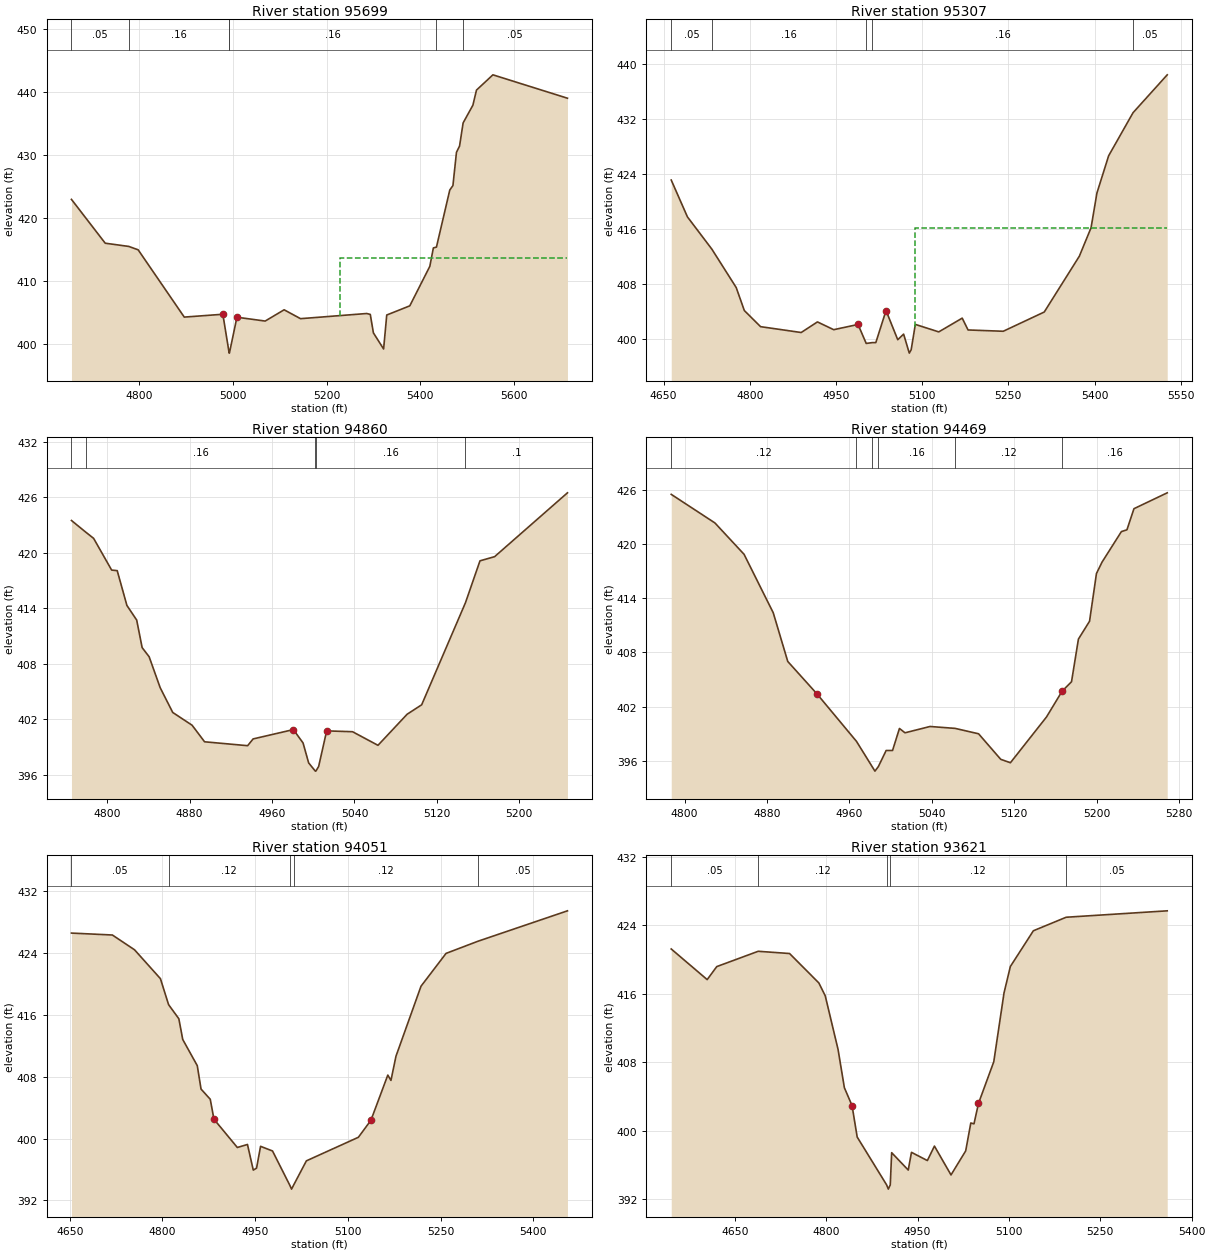
Type RM Length L Ch R = 1 ,95699   ,392,392,392
BEGIN DESCRIPTION:
COON CREEK 143.0
END DESCRIPTION:
XS GIS Cut Line= 3
      3693641.35     10783821.75      3693196.93     10783773.14
      3692733.14     10783371.65
#Sta/Elev= 30
  4654.7  422.97  4726.9     416  4777.2  415.49  4797.3  414.95  4895.9  404.25
  4978.4   404.7  4991.9  398.52  4992.4  398.52  5008.5  404.23  5068.9  403.62
  5109.4  405.41  5144.5     404    5286  404.82  5293.6  404.68  5300.3  401.74
  5322.1  399.18  5328.8  404.58  5378.1  406.04  5420.9  412.32  5428.5  415.25
  5435.1  415.39  5463.6  424.46  5470.3  425.16  5477.9  430.46  5484.5  431.45
  5492.1  435.13    5513  437.95  5520.7  440.35  5555.8  442.78  5715.2  439.06
#Mann= 6 ,-1 , 0
  4654.7     .05       0  4777.2     .16       0  4991.9     .07       0
  4992.4     .16       0  5435.1     .07       0  5492.1     .05       0
#XS Ineff= 2 , 0
                         5228.64          413.65
Permanent Ineff=
       F       F
Bank Sta=4978.4,5008.5
XS Rating Curve= 0 ,0
Exp/Cntr=0.3,0.1

Type RM Length L Ch R = 1 ,95307   ,447,447,447
BEGIN DESCRIPTION:
COON CREEK 142.0
END DESCRIPTION:
XS GIS Cut Line= 3
      3693749.58     10783710.16      3693499.61     10783460.19
      3693399.61      10782960.2
#Sta/Elev= 30
  4663.2  423.15  4691.4  417.79  4733.9   413.1  4776.3  407.51  4790.4  404.17
  4818.7  401.82  4889.4  400.97  4917.7  402.51    4946  401.38  4988.4  402.14
  5002.6  399.38  5013.2   399.5  5019.3   399.5  5037.1  404.16  5057.5  399.92
  5067.7  400.74  5077.6  397.97  5080.9  398.47  5088.1  402.15  5128.9  401.06
  5169.7  403.06  5179.9  401.34  5241.1  401.15  5312.5  403.95  5373.6  412.07
    5394  416.21  5404.2  421.26  5424.6  426.68  5467.1  432.95  5526.6  438.46
#Mann= 5 ,-1 , 0
  4663.2     .05       0  4733.9     .16       0  5002.6     .07       0
  5013.2     .16       0  5467.1     .05       0
#XS Ineff= 2 , 0
                          5087.5          416.17
Permanent Ineff=
       F       F
Bank Sta=4988.4,5037.1
XS Rating Curve= 0 ,0
Exp/Cntr=0.3,0.1

Type RM Length L Ch R = 1 ,94860   ,391,391,391
BEGIN DESCRIPTION:
COON CREEK 141.0
END DESCRIPTION:
XS GIS Cut Line= 3
      3694099.59     10783310.18      3693849.61     10783210.19
      3693699.59     10783060.17
#Sta/Elev= 30
  4765.3  423.49  4779.4  422.21  4786.8  421.56  4804.3  418.13  4809.7  418.07
  4819.1  414.31  4828.6  412.73  4833.9  409.75  4840.7  408.76  4851.4  405.42
  4863.6  402.74  4882.4  401.36  4894.5  399.57  4936.3  399.15  4941.6  399.88
  4980.7  400.89  4990.1  399.44  4995.5  397.29    5002   396.4  5002.5   396.4
  5005.2   396.9    5013  400.75  5038.1  400.66  5062.8  399.19  5091.1  402.55
  5105.2  403.57  5147.7   414.6  5161.8  419.13    5176  419.58  5246.7  426.48
#Mann= 5 ,-1 , 0
  4765.3     .05       0  4779.4     .16       0    5002     .07       0
  5002.5     .16       0  5147.7      .1       0
Bank Sta=4980.7,5013
XS Rating Curve= 0 ,0
Exp/Cntr=0.3,0.1

Type RM Length L Ch R = 1 ,94469   ,418,418,418
BEGIN DESCRIPTION:
COON CREEK 140.0
END DESCRIPTION:
XS GIS Cut Line= 3
      3694249.59     10783060.17      3694099.61     10782910.19
      3693849.58     10782810.18
#Sta/Elev= 30
  4787.1  425.53  4829.5  422.36  4857.8  418.88  4886.1   412.4  4900.2     407
  4928.5  403.41  4966.9  398.14  4982.1  395.34  4984.8  394.84  4988.1  395.34
  4995.7  397.13  5001.9  397.13  5008.6  399.57    5014  399.09  5038.3  399.79
  5062.6  399.58  5085.4  398.98  5106.9  396.15  5116.3  395.77  5151.3  400.84
  5166.5  403.71  5175.6  404.75  5182.3  409.48  5193.1  411.46  5199.8  416.75
  5205.2  418.01    5224   421.4  5229.4   421.6  5236.2  423.94  5268.5   425.7
#Mann= 6 ,-1 , 0
  4787.1     .12       0  4966.9     .16       0  4982.1     .07       0
  4988.1     .16       0  5062.6     .12       0  5166.5     .16       0
Bank Sta=4928.5,5166.5
XS Rating Curve= 0 ,0
Exp/Cntr=0.3,0.1

Type RM Length L Ch R = 1 ,94051   ,430,430,430
BEGIN DESCRIPTION:
COON CREEK 139.0
END DESCRIPTION:
XS GIS Cut Line= 4
      3694432.92     10782808.49      3694289.68     10782600.15
      3694103.05     10782535.04       3693755.8     10782591.47
#Sta/Elev= 30
  4652.8  426.59    4719  426.34  4754.8  424.43  4796.7  420.69  4809.9  417.33
  4826.5   415.5  4832.8  412.82  4856.3  409.43  4862.4   406.4  4877.3  405.08
  4883.3   402.5  4921.1  398.84  4937.5  399.23  4946.9  395.91  4952.2  396.17
  4958.7  398.99    4978  398.39    5006  393.95  5008.8  393.45    5012  393.95
  5032.8  397.11  5116.9  400.16  5137.2  402.36  5164.5  408.21  5169.6  407.52
  5177.7  410.65  5218.2  419.71  5258.7  423.96  5310.2  425.53  5455.1  429.47
#Mann= 5 ,-1 , 0
  4652.8     .05       0  4809.9     .12       0    5006     .07       0
    5012     .12       0  5310.2     .05       0
Bank Sta=4883.3,5137.2
XS Rating Curve= 0 ,0
Exp/Cntr=0.3,0.1

Type RM Length L Ch R = 1 ,93621   ,426,426,426
BEGIN DESCRIPTION:
COON CREEK 138.0
END DESCRIPTION:
XS GIS Cut Line= 2
      3694662.21     10782731.49      3694419.39     10781954.45
#Sta/Elev= 30
  4545.8  421.22  4604.8  417.64  4620.5  419.16  4688.5  420.95    4740  420.69
  4788.1  417.25  4798.6  415.74  4819.6  409.48    4830     405  4842.6  402.91
    4851  399.24  4899.3  393.65  4902.1  393.15  4905.3  393.65  4907.6  397.41
  4934.8  395.38  4940.1  397.45  4966.2  396.49  4977.8  398.18    5005  394.81
  5029.1  397.62  5037.5  400.88  5042.7  400.78  5050.1  403.17  5075.2  408.04
    5092  416.08  5102.4  419.17  5140.2  423.35    5194  424.93  5359.9  425.68
#Mann= 5 ,-1 , 0
  4545.8     .05       0  4688.5     .12       0  4899.3     .07       0
  4905.3     .12       0    5194     .05       0
Bank Sta=4842.6,5050.1
XS Rating Curve= 0 ,0
Exp/Cntr=0.3,0.1

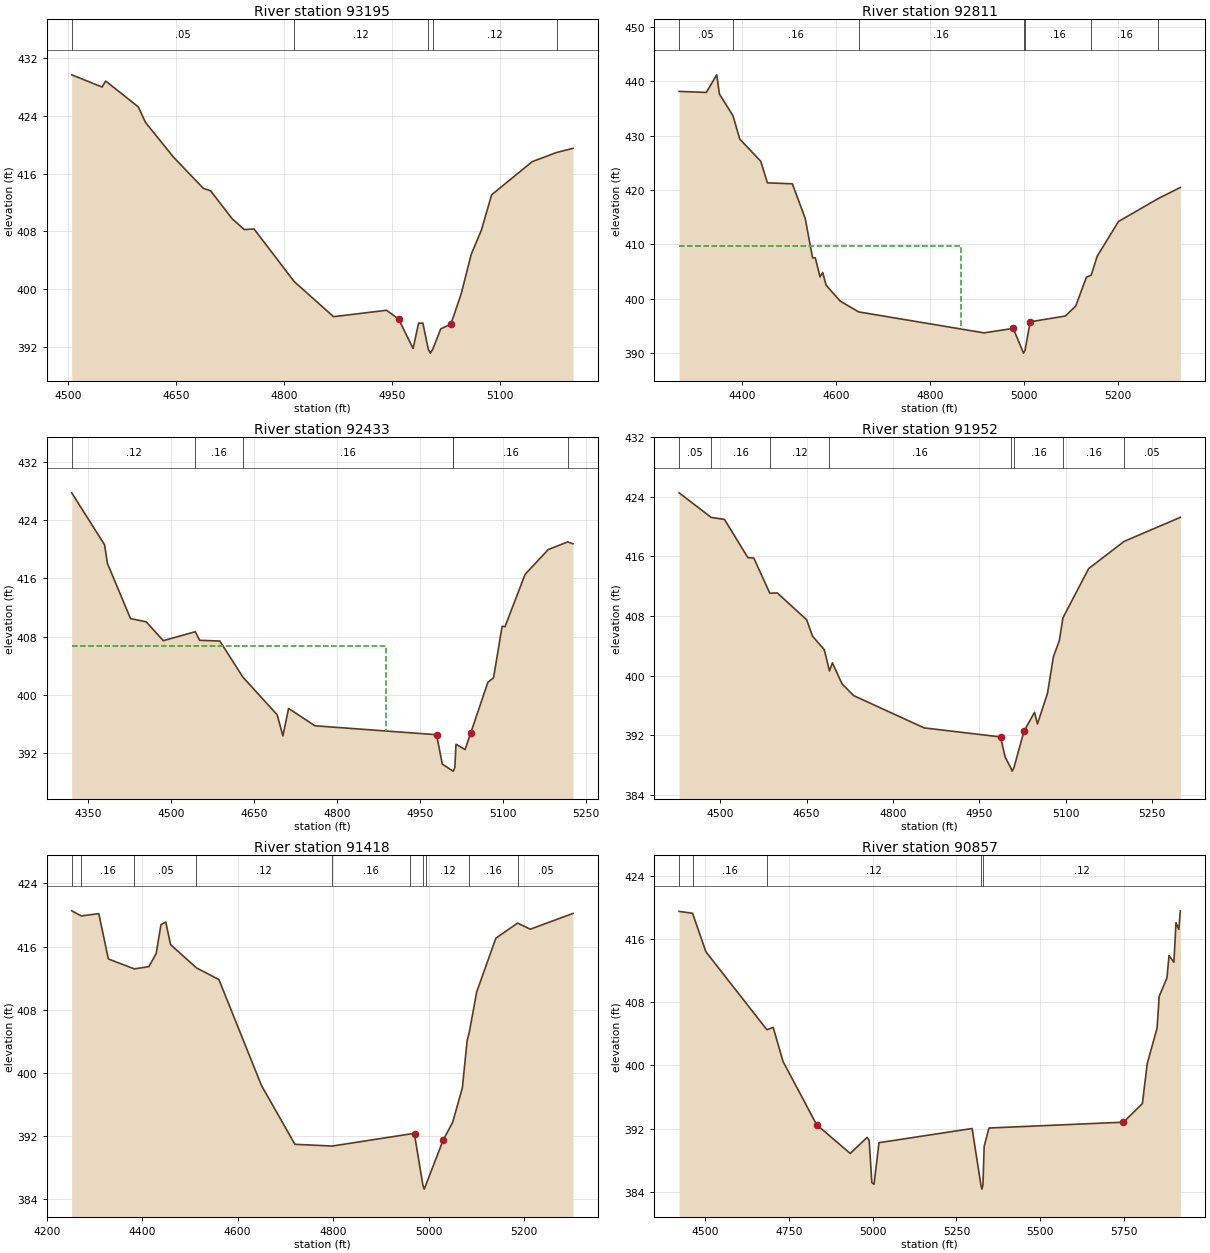
Type RM Length L Ch R = 1 ,93195   ,384,384,384
BEGIN DESCRIPTION:
COON CREEK 137.0
END DESCRIPTION:
XS GIS Cut Line= 3
      3694999.46      10782742.2      3694949.61     10782260.19
      3694799.62      10782110.2
#Sta/Elev= 30
  4504.6  429.71  4546.8  428.02  4551.8  428.85  4597.1  425.27  4607.2  423.11
  4645.7  418.34  4687.6  413.97  4697.6  413.64  4727.8  409.74  4744.5  408.26
    4758  408.35  4813.6  401.08  4868.5  396.19  4942.3  397.08    4959  395.85
  4979.1  391.78  4986.7  395.29  4992.7  395.29  5000.3  391.64  5003.1  391.14
  5006.3  391.64  5017.5   394.5  5031.6  395.16  5045.8  399.32  5059.9  404.84
    5074  408.18  5088.2  413.08  5144.7  417.68  5178.6  418.95  5201.3  419.52
#Mann= 5 ,-1 , 0
  4504.6     .05       0  4813.6     .12       0  5000.3     .07       0
  5006.3     .12       0  5178.6     .05       0
Bank Sta=4959,5031.6
XS Rating Curve= 0 ,0
Exp/Cntr=0.3,0.1

Type RM Length L Ch R = 1 ,92811   ,378,378,378
BEGIN DESCRIPTION:
COON CREEK 136.0
END DESCRIPTION:
XS GIS Cut Line= 3
      3695607.08     10782590.27      3695277.24     10782021.73
      3694908.34     10781848.13
#Sta/Elev= 30
  4266.7  438.15  4324.6  437.96  4346.6   441.2  4352.4  437.66  4381.2  433.66
  4395.5  429.38  4440.2  425.28  4454.3  421.31  4507.3  421.13  4534.6  414.78
  4550.3   407.5  4556.1  407.51  4566.1  403.99  4571.9   404.8  4578.9  402.47
  4609.1  399.52  4648.3  397.54  4914.7  393.68  4976.6  394.51  4998.5  389.95
  5001.7  390.45  5012.6  395.72  5087.2  396.78  5109.3  398.61  5132.1  403.92
  5142.4  404.32  5154.9  407.78  5200.4   414.2    5285  418.43  5331.7  420.46
#Mann= 7 ,-1 , 0
  4266.7     .05       0  4381.2     .16       0  4648.3     .16       0
  4998.5     .07       0  5001.7     .16       0  5142.4     .16       0
    5285     .05       0
#XS Ineff= 2 , 0
         4865.45  409.63
Permanent Ineff=
       F       F
Bank Sta=4976.6,5012.6
XS Rating Curve= 0 ,0
Exp/Cntr=0.3,0.1

Type RM Length L Ch R = 1 ,92433   ,481,481,481
BEGIN DESCRIPTION:
Mapping XS f09daa53
END DESCRIPTION:
XS GIS Cut Line= 2
      3695870.51     10781460.65      3694990.06     10781675.56
#Sta/Elev= 30
  4319.9  427.78  4379.3  420.63  4384.5  418.06  4426.2  410.48  4454.6  410.03
  4485.5  407.44  4543.3  408.67  4551.2  407.49  4587.7  407.39  4629.4  402.42
  4691.4  397.24  4701.7  394.34    4712  398.12  4759.5  395.73  4979.6   394.5
  4989.9  390.46  5009.3  389.49  5009.8  389.49  5012.6  389.99  5014.7  393.19
  5031.1  392.46  5041.4  394.75  5072.3  401.71  5082.6  402.34  5098.1  409.43
  5103.2  409.35  5139.7  416.57  5181.4  419.97  5216.7  421.03  5226.2  420.77
#Mann= 6 ,-1 , 0
  4319.9     .12       0  4543.3     .16       0  4629.4     .16       0
  5009.3     .07       0  5009.8     .16       0  5216.7     .05       0
#XS Ineff= 2 , 0
         4888.64  406.74
Permanent Ineff=
       F       F
Bank Sta=4979.6,5041.4
XS Rating Curve= 0 ,0
Exp/Cntr=0.3,0.1

Type RM Length L Ch R = 1 ,91952   ,534,534,534
BEGIN DESCRIPTION:
COON CREEK 135.0
END DESCRIPTION:
XS GIS Cut Line= 2
      3695826.76     10781092.91      3694973.56     10781264.59
#Sta/Elev= 30
  4428.8  424.54  4484.5  421.24  4507.5  420.98  4548.3  415.84  4558.5  415.79
  4586.3  411.07  4599.3  411.11  4650.3   407.5  4660.5   405.3  4680.9  403.49
  4689.9  400.64    4695  401.73  4711.5  398.93  4731.9  397.33  4854.3     393
  4986.9  391.79    4995  389.07  5004.3   387.7  5007.1   387.2  5010.3   387.7
  5027.7  392.57  5045.9  395.09    5051  393.53  5068.5  397.66  5078.7  402.55
  5088.9  404.69  5095.2  407.76  5139.9  414.37  5201.4  418.02  5299.1  421.25
#Mann= 8 ,-1 , 0
  4428.8     .05       0  4484.5     .16       0  4586.3     .12       0
  4689.9     .16       0  5004.3     .07       0  5010.3     .16       0
  5095.2     .16       0  5201.4     .05       0
Bank Sta=4986.9,5027.7
XS Rating Curve= 0 ,0
Exp/Cntr=0.3,0.1

Type RM Length L Ch R = 1 ,91418   ,561,561,561
BEGIN DESCRIPTION:
COON CREEK 134.0
END DESCRIPTION:
XS GIS Cut Line= 3
       3695926.2     10780756.45      3695032.99     10780693.96
      3694897.61     10780769.45
#Sta/Elev= 30
  4252.3  420.53  4272.4  419.88    4309  420.18  4329.1  414.43  4383.6  413.17
    4414  413.46  4429.3  415.12  4439.3  418.78  4449.4  419.12  4459.4  416.25
  4513.7   413.3  4560.8  411.81  4649.9   398.4    4720  390.94  4798.2  390.72
  4961.6  392.25  4970.6   392.2  4988.2  385.76    4991  385.26  4994.2  385.76
  5030.8  391.49  5050.8  393.76  5070.9  398.11  5080.9  404.07  5085.7  405.23
    5101  410.27  5141.1  417.06  5186.8  418.98  5213.2   418.2  5302.7   420.2
#Mann= 10 ,-1 , 0
  4252.3     .05       0  4272.4     .16       0  4383.6     .05       0
  4513.7     .12       0  4798.2     .16       0  4961.6     .12       0
  4988.2     .07       0  4994.2     .12       0  5085.7     .16       0
  5186.8     .05       0
Bank Sta=4970.6,5030.8
XS Rating Curve= 0 ,0
Exp/Cntr=0.3,0.1

Type RM Length L Ch R = 1 ,90857   ,436,436,436
BEGIN DESCRIPTION:
COON CREEK 133.0
END DESCRIPTION:
XS GIS Cut Line= 2
      3696003.01     10780659.65      3694797.94     10779774.71
#Sta/Elev= 30
  4422.8  419.52  4462.9  419.28  4502.8   414.4  4684.7  404.53  4703.4  404.83
  4732.7  400.52    4833   392.5  4933.3  388.86  4983.5  390.89  4989.7  390.53
  4997.7  385.17  5004.3  384.96    5019  390.22  5296.8  392.02  5323.1  384.84
  5325.9  384.34  5329.1  384.84  5332.7  389.76    5347  392.08  5748.2  392.82
  5804.6  395.17  5819.2  400.25  5848.5  404.74  5854.8  408.76  5877.9  411.08
  5884.1  413.91  5898.7  413.08  5904.9  418.08  5913.4  417.24  5917.9  419.59
#Mann= 5 ,-1 , 0
  4422.8     .05       0  4462.9     .16       0  4684.7     .12       0
  5323.1     .07       0  5329.1     .12       0
Bank Sta=4833,5748.2
XS Rating Curve= 0 ,0
Exp/Cntr=0.3,0.1

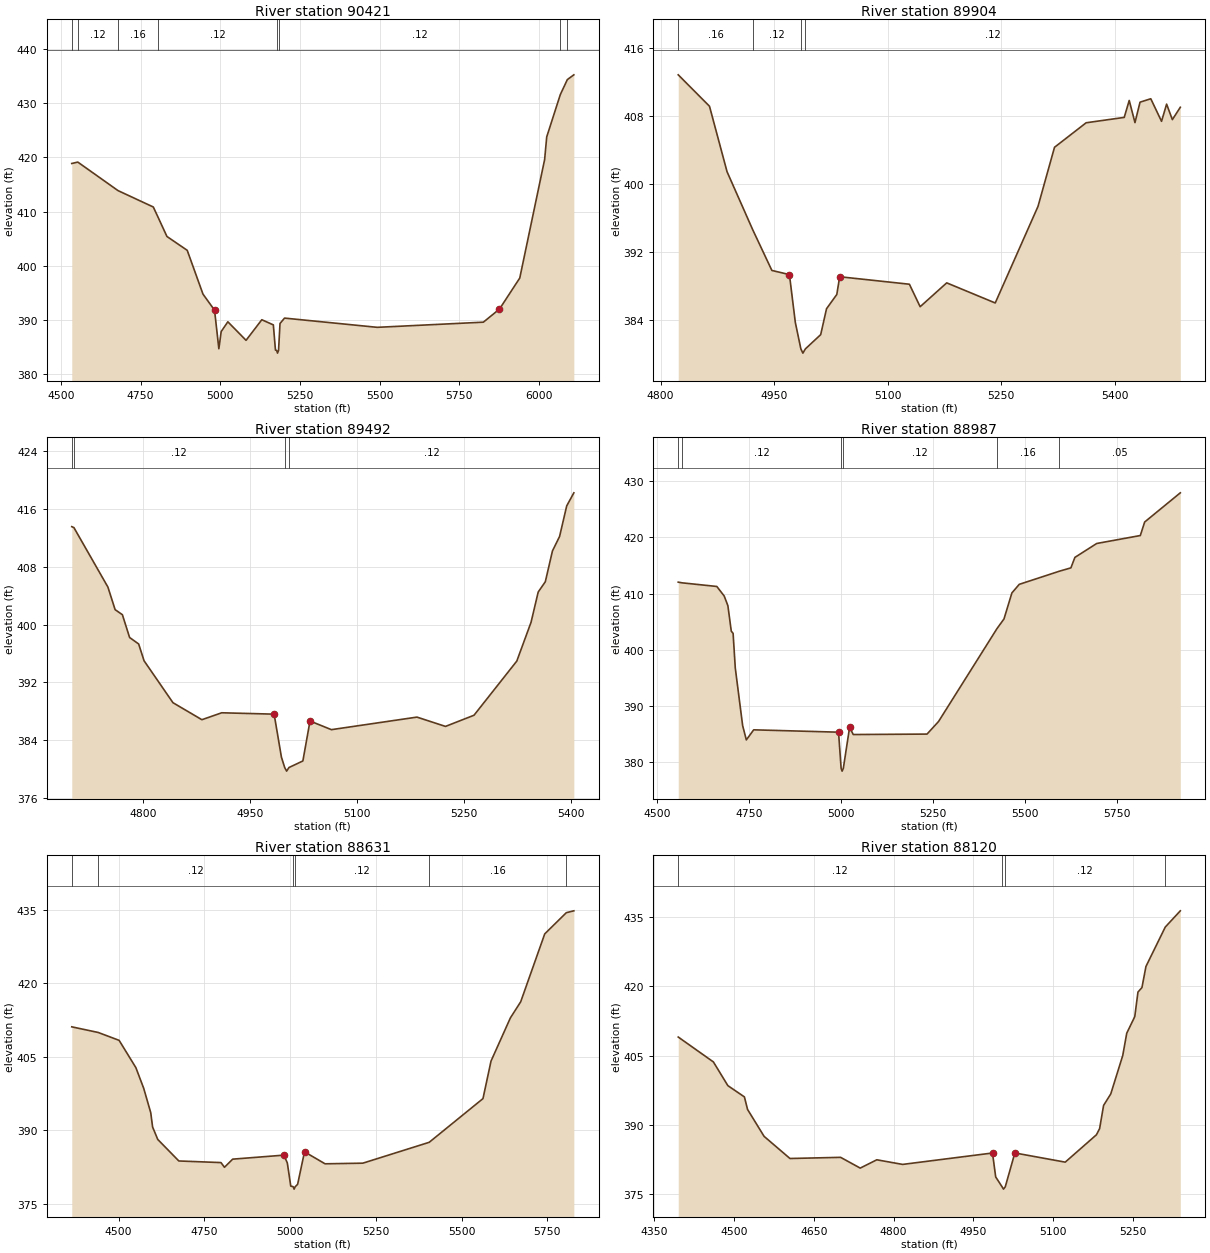
Type RM Length L Ch R = 1 ,90421   ,517,517,517
BEGIN DESCRIPTION:
COON CREEK 132.0
END DESCRIPTION:
XS GIS Cut Line= 2
      3696210.24      10780400.2       3695013.5     10779376.89
#Sta/Elev= 30
  4534.4  418.85  4553.3  419.11  4679.4  413.86  4790.1  410.84  4805.5   408.9
  4832.9  405.41  4896.5  402.86  4945.9   394.8  4982.2  391.84  4995.7  384.74
    5003   387.9  5023.9   389.7    5081  386.29  5130.4  390.08  5166.6  389.13
  5173.2  384.49  5176.9  384.43  5179.7  383.93  5182.9  384.43  5187.5  389.39
  5201.7  390.38  5492.6  388.68  5825.2  389.63  5875.8  392.04  5939.4  397.76
  6017.4  419.58  6023.9  423.74  6066.5  431.53  6088.6   434.3    6109  435.18
#Mann= 8 ,-1 , 0
  4534.4     .16       0  4553.3     .12       0  4679.4     .16       0
  4805.5     .12       0  5176.9     .07       0  5182.9     .12       0
  6066.5     .16       0  6088.6     .05       0
Bank Sta=4982.2,5875.8
XS Rating Curve= 0 ,0
Exp/Cntr=0.3,0.1

Type RM Length L Ch R = 1 ,89904   ,412,412,412
BEGIN DESCRIPTION:
COON CREEK 131.0
END DESCRIPTION:
XS GIS Cut Line= 3
      3696199.65      10779810.2      3695999.61     10779760.19
      3695655.56     10779459.23
#Sta/Elev= 30
  4823.3  412.84  4864.6  409.15  4887.8  401.46  4921.6  394.67    4947  389.87
  4970.2  389.38    4978  383.76  4985.3  380.66    4988  380.16  4991.3  380.66
  5011.5  382.33  5019.2  385.37  5032.8  387.05  5036.6  389.13  5128.7  388.25
  5142.9  385.61    5178  388.41  5242.1  386.05  5298.6  397.39  5320.4  404.33
  5362.2  407.21  5412.5  407.84  5419.1  409.83  5426.7  407.23  5433.4  409.63
  5447.6  410.03  5461.8  407.38  5468.5   409.4  5476.1  407.58  5486.6  409.03
#Mann= 4 ,-1 , 0
  4823.3     .16       0  4921.6     .12       0  4985.3     .07       0
  4991.3     .12       0
Bank Sta=4970.2,5036.6
XS Rating Curve= 0 ,0
Exp/Cntr=0.3,0.1

Type RM Length L Ch R = 1 ,89492   ,505,505,505
BEGIN DESCRIPTION:
COON CREEK 130.0
END DESCRIPTION:
XS GIS Cut Line= 3
       3696399.6     10779460.19      3696099.61     10779410.19
      3695699.63     10779410.19
#Sta/Elev= 30
  4700.2  413.57  4703.2  413.44  4750.9  405.19    4761  402.06  4771.2  401.36
  4781.3   398.2    4794   397.3  4801.6  394.97  4842.1  389.16  4882.7   386.8
  4910.5  387.76    4984  387.57  4994.2  381.62  4998.8  380.17  5001.5  379.67
  5004.8  380.17  5024.3  381.08  5034.3  386.62  5064.3  385.42  5184.3  387.16
  5224.3  385.87  5264.3  387.42  5324.3  394.93  5344.3  400.31  5354.3   404.5
  5364.3  405.93  5374.3   410.2  5384.3  412.21  5394.3  416.45  5404.3  418.26
#Mann= 4 ,-1 , 0
  4700.2     .16       0  4703.2     .12       0  4998.8     .07       0
  5004.8     .12       0
Bank Sta=4984,5034.3
XS Rating Curve= 0 ,0
Exp/Cntr=0.3,0.1

Type RM Length L Ch R = 1 ,88987   ,356,356,356
BEGIN DESCRIPTION:
COON CREEK 129.0
END DESCRIPTION:
XS GIS Cut Line= 2
      3696384.25     10778987.18      3695022.95     10779060.88
#Sta/Elev= 30
  4558.4  412.03  4568.7  411.91  4663.2  411.26  4683.2  409.56  4693.2  407.84
  4702.4   403.3  4707.4  402.88  4713.3  396.71  4733.3  386.43  4743.3  383.88
  4763.3  385.68  4993.7  385.26  5000.7  378.81  5003.4  378.31  5006.7  378.81
  5023.7  386.12  5033.7  384.84    5234  384.92  5265.3  387.17  5424.1  403.76
  5442.9  405.46  5464.4  410.11  5484.4  411.64  5593.2  413.98  5624.6  414.58
  5635.5  416.45  5694.7  418.93  5813.1  420.35  5824.9  422.76  5921.7  427.97
#Mann= 6 ,-1 , 0
  4558.4     .05       0  4568.7     .12       0  5000.7     .07       0
  5006.7     .12       0  5424.1     .16       0  5593.2     .05       0
Bank Sta=4993.7,5023.7
XS Rating Curve= 0 ,0
Exp/Cntr=0.3,0.1

Type RM Length L Ch R = 1 ,88631   ,511,511,511
BEGIN DESCRIPTION:
COON CREEK 128.0
END DESCRIPTION:
XS GIS Cut Line= 3
      3696514.42     10778796.21      3695945.84     10778670.34
      3695064.77     10778635.62
#Sta/Elev= 30
  4363.4  411.15  4440.4     410  4501.5  408.39  4550.4  402.81  4573.2  398.59
  4593.7  393.62  4599.1   390.7  4614.1  388.16  4675.6  383.76  4798.5  383.43
  4808.7  382.47  4832.6  384.13    4982  384.95    4992  383.35    5002  378.63
    5009  378.51  5011.8  378.01    5015  378.51    5022  378.99  5042.1  385.63
  5102.1  383.18  5212.2  383.31  5405.7  387.57  5562.5  396.49    5586  404.16
  5642.5  412.98  5672.5  416.26  5742.6  430.13  5805.6  434.46  5827.5  434.84
#Mann= 6 ,-1 , 0
  4363.4     .05       0  4440.4     .12       0    5009     .07       0
    5015     .12       0  5405.7     .16       0  5805.6     .05       0
Bank Sta=4982,5042.1
XS Rating Curve= 0 ,0
Exp/Cntr=0.3,0.1

Type RM Length L Ch R = 1 ,88120   ,473,473,473
BEGIN DESCRIPTION:
COON CREEK 127.0
END DESCRIPTION:
XS GIS Cut Line= 3
      3696499.65     10778610.21      3695999.61     10778310.19
      3695699.61     10778110.19
#Sta/Elev= 30
  4395.3  409.03  4461.4  403.64  4488.6  398.51  4519.7  396.07  4525.6  393.36
  4556.7  387.53  4605.3  382.74  4700.5  382.99  4737.4  380.66  4768.5  382.46
  4817.1  381.46    4986  383.93    4992  378.75    5004  376.61  5006.7  376.11
    5010  376.61    5028  383.94  5122.7  381.95  5181.3  387.87  5187.3   389.2
  5194.8  394.23  5208.3  396.72  5230.8  405.03  5238.3  409.85  5253.4  413.45
  5259.4  418.76  5266.9  419.74  5274.4   424.3  5310.7  432.83    5339  436.35
#Mann= 4 ,-1 , 0
  4395.3     .12       0    5004     .07       0    5010     .12       0
  5310.7     .16       0
Bank Sta=4986,5028
XS Rating Curve= 0 ,0
Exp/Cntr=0.3,0.1

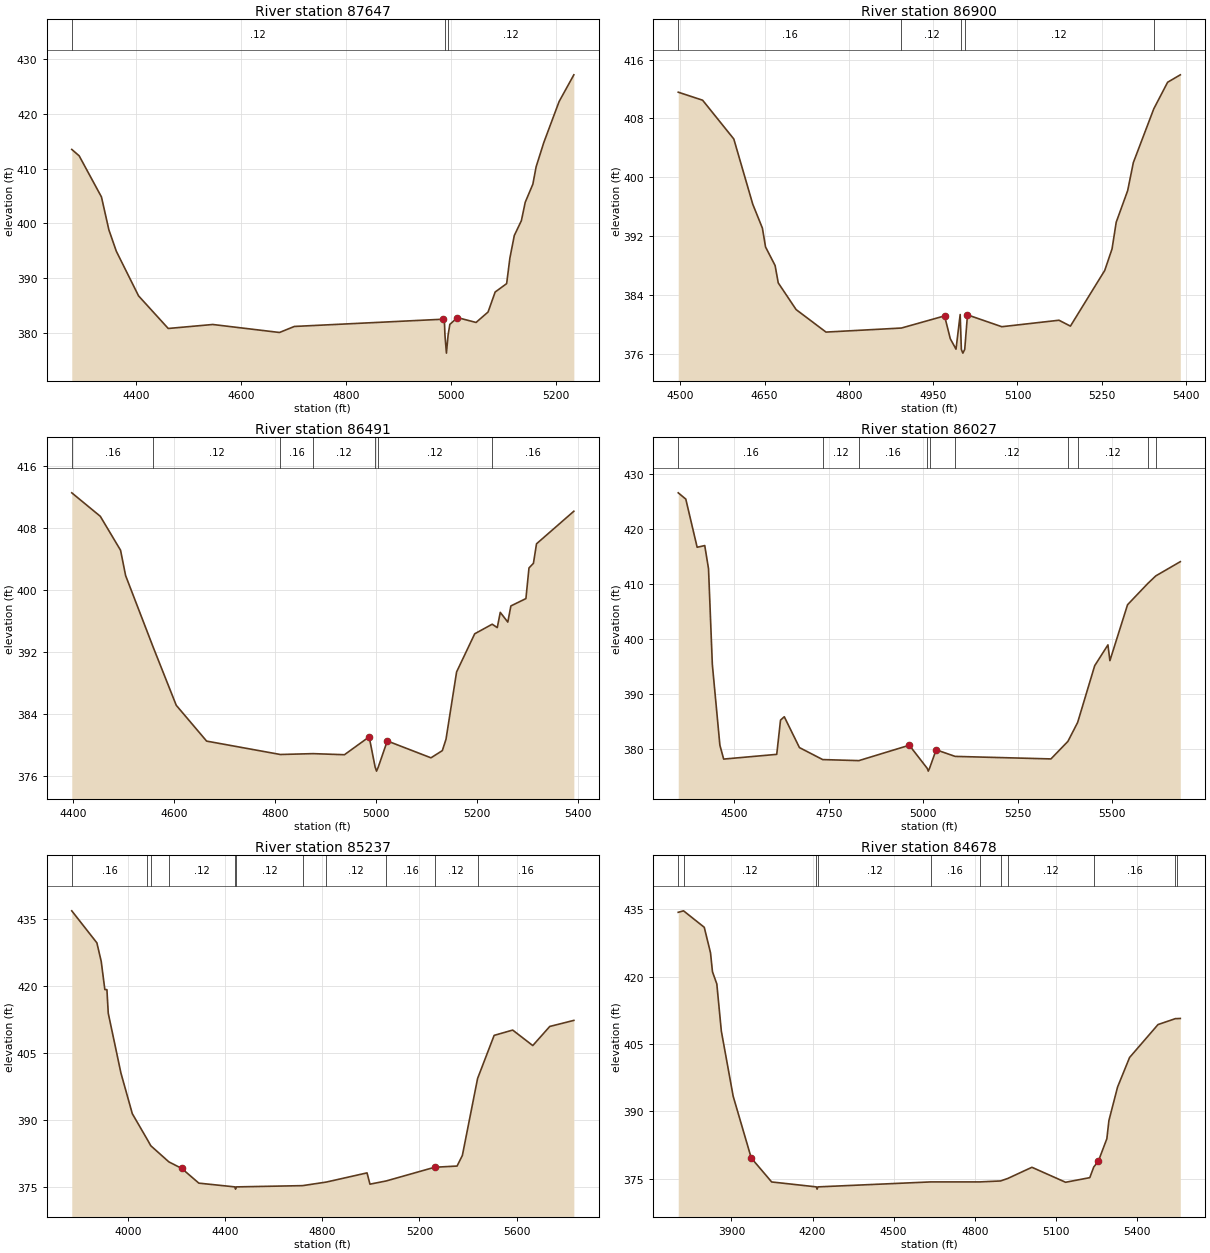
Type RM Length L Ch R = 1 ,87647   ,747,747,747
BEGIN DESCRIPTION:
COON CREEK 126.0
END DESCRIPTION:
XS GIS Cut Line= 3
      3696699.61     10778460.19      3696199.61     10777960.19
      3695999.62      10777810.2
#Sta/Elev= 30
  4277.8   413.5  4291.9  412.33  4334.4  404.82  4348.5  398.83  4362.7  394.91
  4405.1  386.76  4461.7   380.8  4546.5  381.53  4673.8  380.07  4702.1  381.17
  4984.9  382.49    4988  382.49  4989.2   379.6    4992   376.3  4995.2   379.6
  4998.5  381.55    5013  382.79  5048.5   381.9  5071.4  383.81  5084.9  387.46
  5106.8  388.99    5113  393.67  5121.4  397.78  5134.9  400.49  5142.2  403.84
  5156.8  407.16    5163  410.33  5177.6  414.75  5206.8  422.24  5234.9  427.12
#Mann= 3 ,-1 , 0
  4277.8     .12       0  4989.2     .07       0  4995.2     .12       0
Bank Sta=4984.9,5013
XS Rating Curve= 0 ,0
Exp/Cntr=0.3,0.1

Type RM Length L Ch R = 1 ,86900   ,409,409,409
BEGIN DESCRIPTION:
COON CREEK 125.0
END DESCRIPTION:
XS GIS Cut Line= 3
      3696919.96     10778219.29      3696724.63     10777812.99
       3696641.3     10777378.12
#Sta/Elev= 30
  4496.2  411.57  4539.6  410.48  4595.1  405.21  4628.9  396.33    4646  393.09
  4651.6  390.53  4668.6  388.01  4674.2  385.65    4706  382.02  4759.2  378.96
  4893.4  379.51  4970.2  381.16  4980.4  378.06  4990.6  376.64    4998  381.35
  5000.1   376.6  5002.8   376.1  5006.1   376.6    5011   381.3  5072.1  379.69
  5173.9  380.57  5194.2  379.77  5255.3  387.34  5268.3  390.27  5275.7  393.89
  5296.1  398.19  5306.2     402  5342.6  409.31  5367.2  412.92  5389.8  413.93
#Mann= 5 ,-1 , 0
  4496.2     .16       0  4893.4     .12       0  5000.1     .07       0
  5006.1     .12       0  5342.6     .16       0
Bank Sta=4970.2,5011
XS Rating Curve= 0 ,0
Exp/Cntr=0.3,0.1

Type RM Length L Ch R = 1 ,86491   ,464,464,464
BEGIN DESCRIPTION:
COON CREEK 124.0
END DESCRIPTION:
XS GIS Cut Line= 3
      3697160.18     10778176.54      3697116.77     10777651.32
      3696852.08     10777265.13
#Sta/Elev= 30
  4396.9  412.59  4453.4  409.56  4493.6  405.17  4503.6   401.9  4558.4  392.62
    4604  385.13  4664.2   380.5  4810.3  378.77  4875.4  378.88  4937.4  378.74
  4986.4  381.05  4998.3  377.12    5001  376.62  5004.3  377.12  5022.3  380.52
  5108.9  378.34  5131.4  379.27  5138.7  380.74  5159.7  389.44  5195.6  394.37
  5230.3  395.61  5240.3  395.17  5246.3  397.14  5261.2  395.88  5267.3  397.97
  5297.1  398.92  5303.2  402.88    5312  403.48  5318.1     406  5392.1  410.21
#Mann= 7 ,-1 , 0
  4396.9     .16       0  4558.4     .12       0  4810.3     .16       0
  4875.4     .12       0  4998.3     .07       0  5004.3     .12       0
  5230.3     .16       0
Bank Sta=4986.4,5022.3
XS Rating Curve= 0 ,0
Exp/Cntr=0.3,0.1

Type RM Length L Ch R = 1 ,86027   ,790,790,790
BEGIN DESCRIPTION:
COON CREEK 123.0
END DESCRIPTION:
XS GIS Cut Line= 3
       3697999.6     10777210.19      3697349.61     10777260.19
      3696694.56     10777087.64
#Sta/Elev= 30
  4351.4  426.62  4371.4  425.48  4401.5  416.72  4421.6  417.03  4431.6  412.81
  4441.7   395.4  4461.7  380.72  4471.7   378.2  4612.2  379.06  4622.2  385.28
  4632.2   385.9  4672.3  380.29  4733.9  378.11  4829.6  377.92  4963.2  380.72
  5010.7  376.51  5013.4  376.01  5016.7  376.51  5034.3  379.89  5084.5  378.69
  5338.2  378.23  5383.1  381.42  5408.8  384.85    5454  395.18  5489.1  398.97
  5494.3   396.1    5541  406.27    5595  410.16  5615.9  411.52  5680.7   414.1
#Mann= 10 ,-1 , 0
  4351.4     .16       0  4733.9     .12       0  4829.6     .16       0
  5010.7     .07       0  5016.7     .16       0  5084.5     .12       0
  5383.1     .16       0  5408.8     .12       0    5595     .16       0
  5615.9     .12       0
Bank Sta=4963.2,5034.3
XS Rating Curve= 0 ,0
Exp/Cntr=0.3,0.1

Type RM Length L Ch R = 1 ,85237   ,559,559,559
BEGIN DESCRIPTION:
COON CREEK 122.0
END DESCRIPTION:
XS GIS Cut Line= 2
       3698694.5     10777004.29      3696798.68      10776177.9
#Sta/Elev= 30
  3767.8  436.94  3871.3  429.76  3889.2  425.59    3904   419.3  3912.6  419.28
  3918.1     414  3970.3  400.59  4017.2  391.48  4077.6  385.82  4093.5  384.29
  4167.7  380.69  4220.9  379.21  4291.2  375.92  4439.6  375.08  4442.4  374.58
  4445.6  375.08  4718.6  375.36    4817  376.17    4984  378.22  4996.1  375.69
  5062.9  376.41  5262.4  379.48  5354.9  379.75  5376.7  382.12  5439.4  399.37
  5507.6  409.03    5584  410.22  5666.7  406.75  5736.7  411.03  5835.9  412.39
#Mann= 11 ,-1 , 0
  3767.8     .16       0  4077.6     .12       0  4093.5     .16       0
  4167.7     .12       0  4439.6     .07       0  4445.6     .12       0
  4718.6     .16       0    4817     .12       0  5062.9     .16       0
  5262.4     .12       0  5439.4     .16       0
Bank Sta=4220.9,5262.4
XS Rating Curve= 0 ,0
Exp/Cntr=0.3,0.1

Type RM Length L Ch R = 1 ,84678   ,456,456,456
BEGIN DESCRIPTION:
COON CREEK 121.0
END DESCRIPTION:
XS GIS Cut Line= 3
      3698965.34      10776552.9      3697680.66     10775983.47
      3697251.08      10775844.9
#Sta/Elev= 30
  3703.3  434.36  3722.9  434.69  3799.5  431.02  3822.7  425.32  3829.9  421.11
    3846  418.38  3862.7  407.87  3906.5  393.34  3973.3  379.59  4048.7  374.24
    4214  373.14  4216.8  372.64    4220  373.14  4637.4  374.25  4818.7  374.25
  4895.2  374.46  4922.3  375.03  5011.2  377.51  5135.7  374.17  5225.2   375.2
  5239.8  377.57  5256.7  378.84  5288.3  383.89  5295.9  387.94    5328  395.42
  5372.3  401.99  5477.4  409.33  5542.1  410.66    5548  410.66  5559.9  410.69
#Mann= 11 ,-1 , 0
  3703.3     .16       0  3722.9     .12       0    4214     .07       0
    4220     .12       0  4637.4     .16       0  4818.7     .12       0
  4895.2     .16       0  4922.3     .12       0  5239.8     .16       0
  5542.1     .05       0    5548      .1       0
Bank Sta=3973.3,5256.7
XS Rating Curve= 0 ,0
Exp/Cntr=0.3,0.1

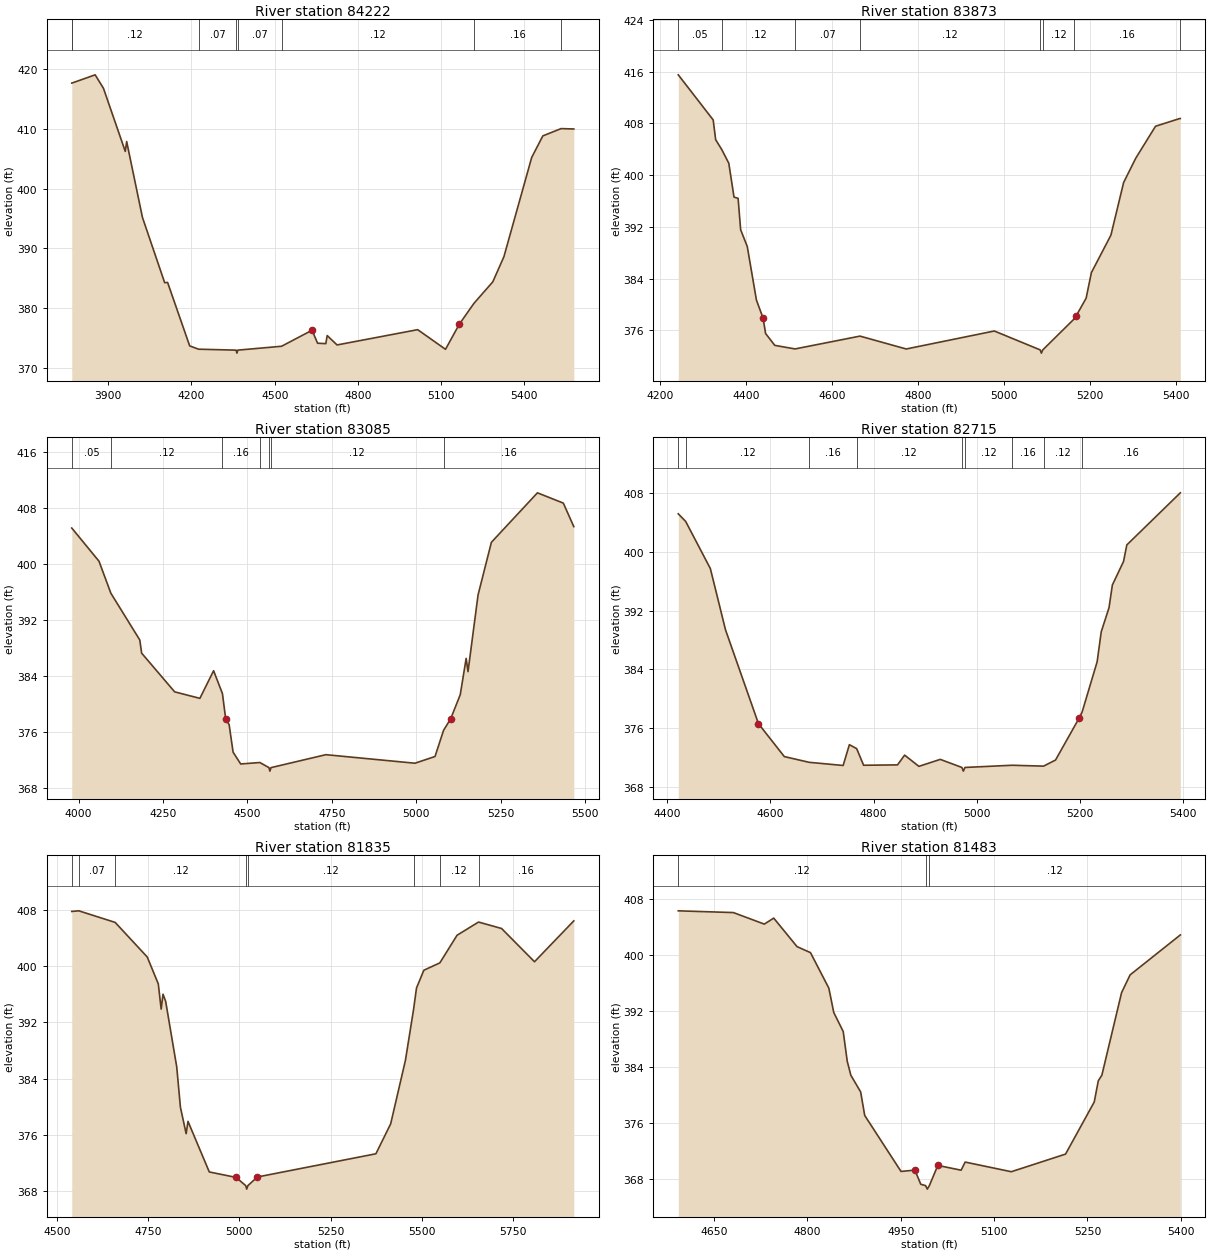
Type RM Length L Ch R = 1 ,84222   ,349,349,349
BEGIN DESCRIPTION:
COON CREEK 120.0
END DESCRIPTION:
XS GIS Cut Line= 2
      3699173.68     10775698.75       3697368.2     10775573.75
#Sta/Elev= 30
  3768.5  417.67  3769.2  417.67  3852.8  419.05  3882.8  416.79  3961.4  406.22
  3966.4  407.88  4023.2  395.18  4103.4  384.23    4114  384.27  4193.6  373.64
  4225.6  373.09    4361  372.93  4363.7  372.43    4367  372.93  4524.8  373.58
  4634.6  376.26  4654.7  374.09  4684.3  374.02  4689.3  375.37  4724.9   373.8
  5015.5  376.36  5115.8  373.07  5165.9   377.3  5218.5  380.78  5286.2  384.37
  5326.3  388.58  5426.5  405.21  5466.6  408.82  5532.4  410.04  5578.3  409.98
#Mann= 8 ,-1 , 0
  3768.5     .16       0  3769.2     .12       0  4225.6     .07       0
    4361     .07       0    4367     .07       0  4524.8     .12       0
  5218.5     .16       0  5532.4      .1       0
Bank Sta=4634.6,5165.9
XS Rating Curve= 0 ,0
Exp/Cntr=0.3,0.1

Type RM Length L Ch R = 1 ,83873   ,788,788,788
BEGIN DESCRIPTION:
COON CREEK 119.0
END DESCRIPTION:
XS GIS Cut Line= 3
      3698449.59      10774910.2      3697799.61     10775310.19
      3697449.62     10775510.18
#Sta/Elev= 30
  4242.8  415.49  4323.9  408.52  4329.7  405.46  4343.9  403.93  4360.2  401.82
  4372.3  396.59  4381.8   396.4  4387.7  391.55  4403.1  388.95  4424.4  380.67
  4439.8  377.89  4445.7   375.5    4467  373.67  4514.2  373.12    4665   375.1
  4772.3  373.11    4977  375.89  5083.6  372.97  5086.4  372.47  5089.6  372.97
  5162.7  377.77  5167.2  378.23  5190.3  380.96  5202.5  384.91  5247.9  390.71
  5277.4  398.84  5305.5  402.59  5351.5  407.54  5408.1  408.74  5409.1  408.74
#Mann= 8 ,-1 , 0
  4242.8     .05       0  4343.9     .12       0  4514.2     .07       0
    4665     .12       0  5083.6     .07       0  5089.6     .12       0
  5162.7     .16       0  5408.1      .1       0
Bank Sta=4439.8,5167.2
XS Rating Curve= 0 ,0
Exp/Cntr=0.3,0.1

Type RM Length L Ch R = 1 ,83085   ,370,370,370
BEGIN DESCRIPTION:
COON CREEK 118.0
END DESCRIPTION:
XS GIS Cut Line= 2
      3698314.32     10774320.11      3696961.54      10774935.8
#Sta/Elev= 30
    3980  405.11  4060.6  400.37  4095.8  395.79  4181.4  389.11  4186.9  387.23
  4284.6   381.7  4359.3  380.77  4399.9  384.72  4426.1  381.44  4435.6  377.88
    4446  376.99  4457.6  373.08  4480.1  371.39  4536.8   371.6  4563.8  370.87
  4566.6  370.37  4569.8  370.87  4732.3  372.72    4996   371.5  5055.4  372.46
  5080.8  376.21  5101.5  377.82  5130.1  381.29  5147.6  386.48  5153.1  384.59
  5182.8  395.54  5222.3  403.07  5358.6  410.14  5435.3  408.67  5466.3  405.31
#Mann= 7 ,-1 , 0
    3980     .05       0  4095.8     .12       0  4426.1     .16       0
  4536.8     .12       0  4563.8     .07       0  4569.8     .12       0
  5080.8     .16       0
Bank Sta=4435.6,5101.5
XS Rating Curve= 0 ,0
Exp/Cntr=0.3,0.1

Type RM Length L Ch R = 1 ,82715   ,880,880,880
BEGIN DESCRIPTION:
COON CREEK 117.0
END DESCRIPTION:
XS GIS Cut Line= 3
      3697949.61     10774260.19      3697399.61     10774410.19
      3697049.61     10774610.19
#Sta/Elev= 30
  4421.4  405.21  4435.8  404.17  4483.6  397.75    4513   389.4  4576.9  376.61
    4627  372.13  4675.2  371.35    4741  370.92  4753.1  373.75  4767.2  373.22
  4780.7  370.95  4846.4     371  4860.2  372.33  4887.8   370.8  4929.3  371.75
  4971.2  370.65    4974  370.15  4977.2  370.65  5068.5  370.95  5129.5  370.83
  5152.7  371.66  5198.1  377.33  5204.2  378.19  5233.4  385.06  5241.3  389.13
  5256.4  392.42  5262.9  395.51  5284.5  398.71  5290.9  400.97  5394.6  408.07
#Mann= 9 ,-1 , 0
  4421.4     .05       0  4435.8     .12       0  4675.2     .16       0
  4767.2     .12       0  4971.2     .07       0  4977.2     .12       0
  5068.5     .16       0  5129.5     .12       0  5204.2     .16       0
Bank Sta=4576.9,5198.1
XS Rating Curve= 0 ,0
Exp/Cntr=0.3,0.1

Type RM Length L Ch R = 1 ,81835   ,352,352,352
BEGIN DESCRIPTION:
COON CREEK 116.0
END DESCRIPTION:
XS GIS Cut Line= 2
      3697854.23     10773842.67      3696493.04     10773634.59
#Sta/Elev= 30
  4540.2  407.83  4559.6  407.92  4659.2  406.27  4747.2  401.34  4777.5  397.51
  4785.4  393.91  4790.5  396.03  4797.8     395  4828.1  385.67  4838.2  379.92
  4853.9  376.15    4859   377.9  4917.4  370.69  4990.9  369.91  5017.3  368.74
  5020.1  368.24  5023.3  368.74  5049.3  369.97  5374.4  373.28  5414.9  377.55
  5455.3  386.59  5477.6  393.83  5485.7  396.91  5505.9  399.45  5549.8   400.5
    5597  404.44  5655.9  406.32  5719.1   405.4  5809.4  400.66  5917.2  406.49
#Mann= 8 ,-1 , 0
  4540.2     .05       0  4559.6     .07       0  4659.2     .12       0
  5017.3     .07       0  5023.3     .12       0  5477.6     .16       0
  5549.8     .12       0  5655.9     .16       0
Bank Sta=4990.9,5049.3
XS Rating Curve= 0 ,0
Exp/Cntr=0.3,0.1

Type RM Length L Ch R = 1 ,81483   ,520,520,520
BEGIN DESCRIPTION:
COON CREEK 115.0
END DESCRIPTION:
XS GIS Cut Line= 3
      3697849.57     10773660.17      3697499.61     10773460.19
       3697149.6     10773260.18
#Sta/Elev= 30
  4592.9  406.35  4681.4   406.1  4731.1  404.45  4746.2  405.31  4783.6  401.23
  4805.2  400.37  4834.7  395.29  4842.6  391.81  4857.8  389.08  4864.2  384.85
    4870  382.84  4885.8  380.44  4892.3  377.08  4950.6  369.07  4972.9  369.26
  4982.3  367.24  4990.1  367.04  4992.8  366.54  4996.1  367.04  5009.7  369.93
  5047.1  369.25  5053.6  370.41  5127.7  369.03  5214.8  371.55  5260.9  379.01
  5267.4  382.04  5273.1  382.83  5304.8  394.65  5318.5  397.19  5399.1   402.9
#Mann= 3 ,-1 , 0
  4592.9     .12       0  4990.1     .07       0  4996.1     .12       0
Bank Sta=4972.9,5009.7
XS Rating Curve= 0 ,0
Exp/Cntr=0.3,0.1