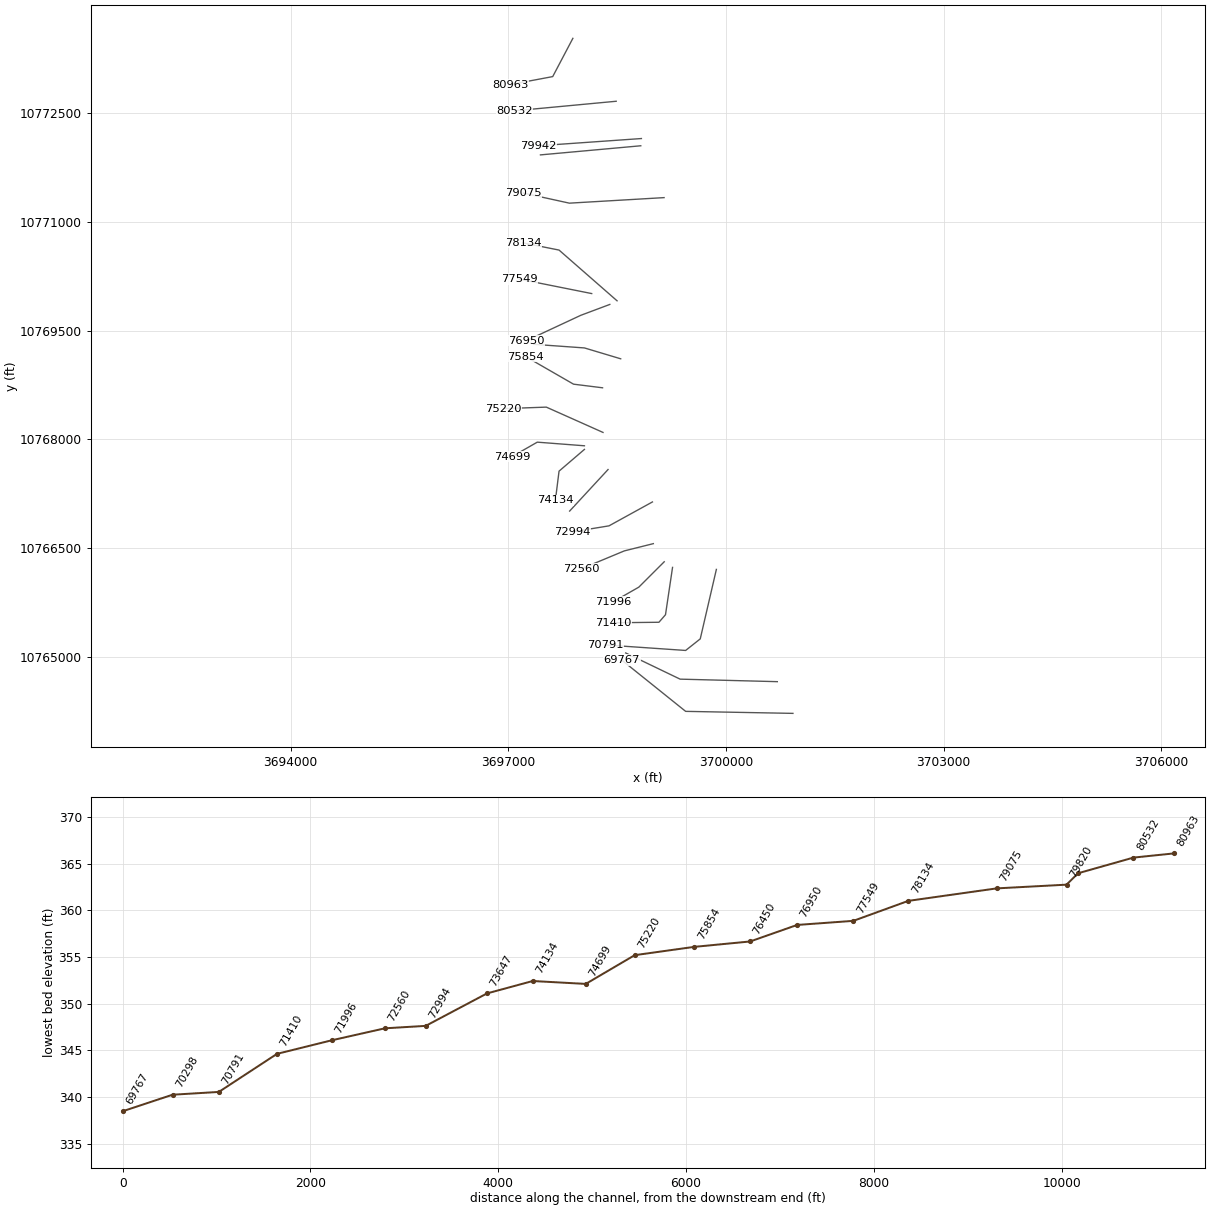
HEC-RAS study COON CREEK.prj: COON CREEK Base Level Engineering

--- COON CREEK.g01 (geometry) --- (continued)

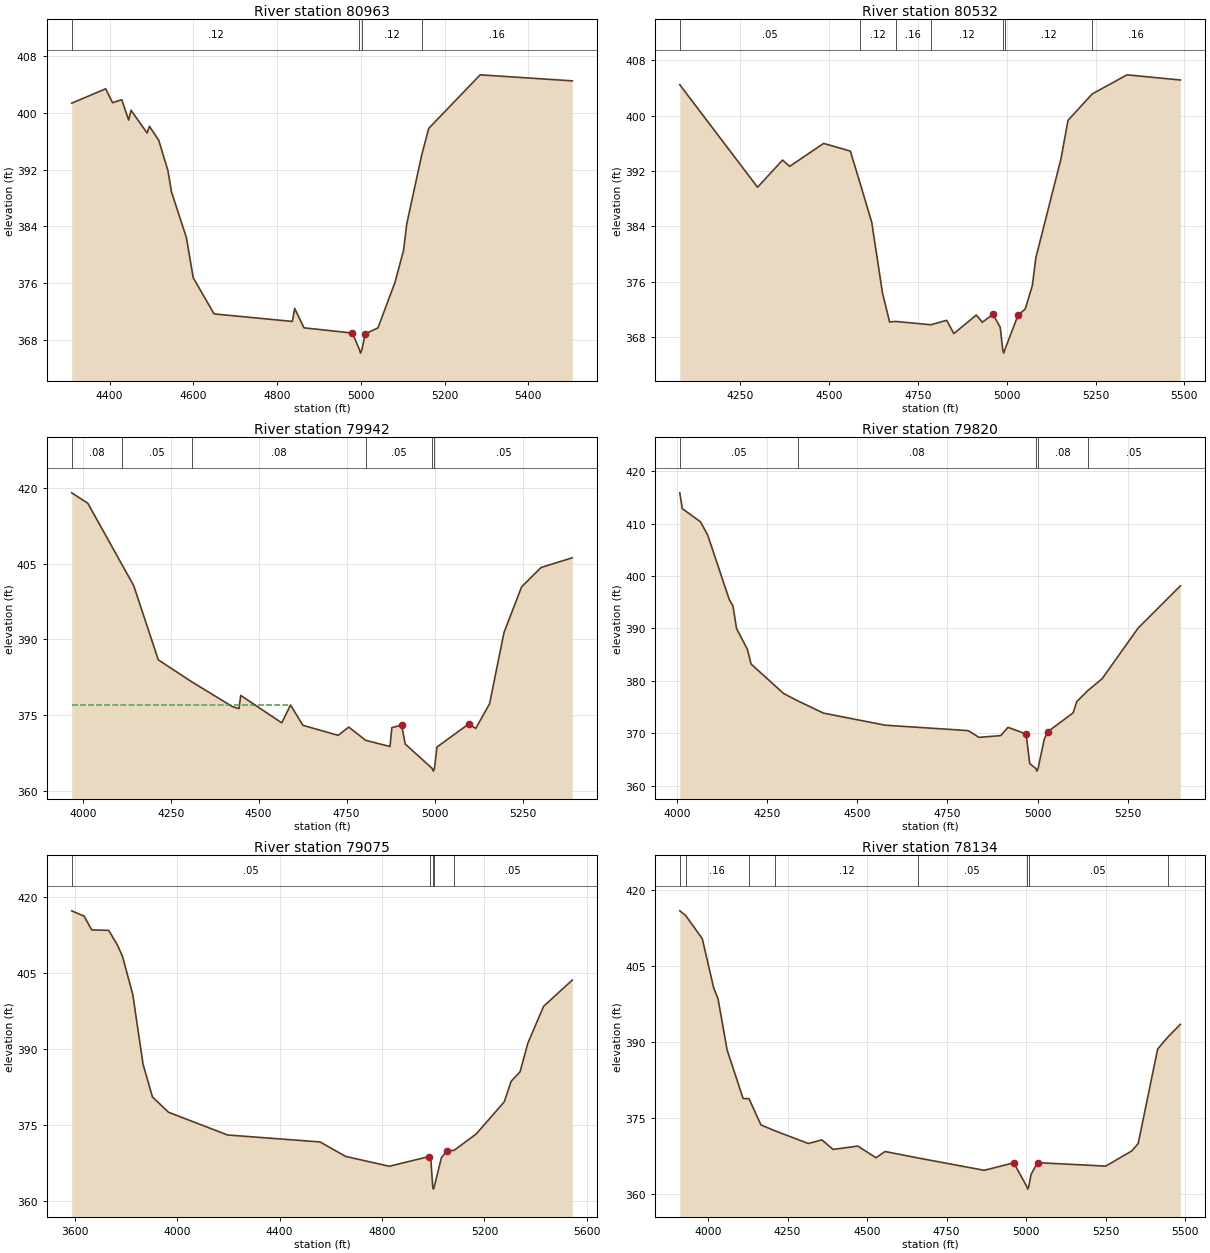
Type RM Length L Ch R = 1 ,80963   ,431,431,431
BEGIN DESCRIPTION:
COON CREEK 114.0
END DESCRIPTION:
XS GIS Cut Line= 3
      3697890.27     10773531.15      3697612.51     10773003.41
      3697023.43     10772892.52
#Sta/Elev= 30
  4309.4  401.36  4390.6  403.39    4407  401.43    4429  401.85  4445.4  398.98
  4451.1  400.37  4489.5  397.16  4495.1   398.1  4517.2  396.15  4539.2  391.88
  4547.8  388.85  4583.3  382.43  4599.7  376.75  4649.5  371.65  4836.4  370.59
  4842.1  372.42  4864.2  369.69    4980  368.95  4996.7  366.62  4999.5  366.12
  5002.7  366.62  5010.5  368.83    5041  369.68  5081.7   376.1  5102.1   380.6
  5109.8  384.34  5145.4  394.03  5162.2   397.8  5285.2  405.36  5505.2  404.51
#Mann= 4 ,-1 , 0
  4309.4     .12       0  4996.7     .07       0  5002.7     .12       0
  5145.4     .16       0
Bank Sta=4980,5010.5
XS Rating Curve= 0 ,0
Exp/Cntr=0.3,0.1

Type RM Length L Ch R = 1 ,80532   ,590,590,590
BEGIN DESCRIPTION:
COON CREEK 113.0
END DESCRIPTION:
XS GIS Cut Line= 2
      3698487.51     10772663.13       3697084.7     10772531.18
#Sta/Elev= 30
  4079.7  404.46  4298.6  389.64  4368.9  393.57    4389  392.66  4484.6  395.98
  4559.7  394.87  4588.1  390.07    4620  384.57  4650.1   374.4  4670.2  370.17
  4687.2  370.25  4786.2  369.77  4830.9  370.41    4851  368.49  4914.1  371.17
  4931.3  370.14  4961.5  371.28  4981.6  369.39  4988.6  366.17  4991.4  365.67
  4994.6  366.17  5031.8  371.16  5051.9  372.04    5072  375.43    5082  379.47
  5152.3  393.68  5172.4  399.31  5240.6  403.13  5338.6  405.89  5488.7  405.14
#Mann= 7 ,-1 , 0
  4079.7     .05       0  4588.1     .12       0  4687.2     .16       0
  4786.2     .12       0  4988.6     .07       0  4994.6     .12       0
  5240.6     .16       0
Bank Sta=4961.5,5031.8
XS Rating Curve= 0 ,0
Exp/Cntr=0.3,0.1

Type RM Length L Ch R = 1 ,79942   ,122,122,122
BEGIN DESCRIPTION:
COON CREEK 112.0
END DESCRIPTION:
XS GIS Cut Line= 2
      3698835.16     10772148.82      3697415.86     10772048.99
#Sta/Elev= 30
  3968.6  418.98  4014.3  416.94  4111.3  404.82  4144.6  400.69  4214.8  385.98
  4309.3  381.66  4425.3  376.74  4444.1  376.34  4449.1  378.95  4565.6  373.53
  4590.6  377.05  4625.8  373.04    4726  371.06  4756.1  372.69  4804.1  370.08
  4873.4  368.85  4878.5  372.59  4906.5  373.07  4916.5  369.35  4993.7  364.49
  4996.4  363.99  4999.7  364.49  5006.7  368.75  5096.9   373.3    5117  372.42
  5156.3   377.3  5197.2  391.35  5247.3  400.39  5302.8  404.23  5391.4  406.14
#Mann= 6 ,-1 , 0
  3968.6     .08       0  4111.3     .05       0  4309.3     .08       0
  4804.1     .05       0  4993.7     .03       0  4999.7     .05       0
#XS Ineff= 2 , 0
         4585.85  377.09
Permanent Ineff=
       F       F
Bank Sta=4906.5,5096.9
XS Rating Curve= 0 ,0
Exp/Cntr=0.3,0.1

Type RM Length L Ch R = 1 ,79820   ,745,745,745
BEGIN DESCRIPTION:
COON CREEK 111.0
END DESCRIPTION:
XS GIS Cut Line= 2
      3698826.49       10772049.      3697443.29     10771923.25
#Sta/Elev= 30
  4007.3  415.87  4014.2  412.86  4064.4  410.36  4084.5  407.85  4144.7  395.49
  4154.8  394.28  4164.8  389.98    4195  385.99    4205  383.21  4295.4  377.58
  4335.7  376.14  4405.8  373.84  4576.5  371.54  4807.5   370.5  4837.6  369.21
  4897.8  369.55  4917.9  371.13  4968.1  369.86  4978.2  364.22  4995.3  363.27
    4998  362.77  5001.3  363.27  5018.3   368.8  5028.4   370.3  5098.7  373.89
  5108.7  376.04  5139.4  378.14    5179   380.4  5279.4   390.1  5396.2  398.13
#Mann= 5 ,-1 , 0
  4007.3     .05       0  4335.7     .08       0  4995.3     .07       0
  5001.3     .08       0  5139.4     .05       0
Bank Sta=4968.1,5028.4
XS Rating Curve= 0 ,0
Exp/Cntr=0.3,0.1

Type RM Length L Ch R = 1 ,79075   ,941,941,941
BEGIN DESCRIPTION:
COON CREEK 110.0
END DESCRIPTION:
XS GIS Cut Line= 3
      3699147.71     10771333.72      3697842.12     10771257.33
      3697210.22     10771396.21
#Sta/Elev= 30
  3588.5  417.28  3636.7  416.25  3666.7  413.52  3733.2  413.42  3766.9  410.54
  3786.9  408.29    3827  400.79  3867.1  387.03  3903.9  380.55  3967.2  377.52
  4197.6  373.05  4558.3  371.68  4658.4  368.82  4828.7  366.88  4982.7  368.78
  4988.8  368.32    4991  368.16  4998.3  362.87    5001  362.37  5004.3  362.87
    5032  368.52  5052.5   369.9  5081.9  370.03    5168  373.25  5277.7   379.6
  5304.5  383.64  5339.2   385.5  5369.9  391.18  5431.3  398.44  5543.3  403.62
#Mann= 5 ,-1 , 0
  3588.5     .05       0  4988.8     .16       0  4998.3     .07       0
  5004.3     .16       0  5081.9     .05       0
Bank Sta=4982.7,5052.5
XS Rating Curve= 0 ,0
Exp/Cntr=0.3,0.1

Type RM Length L Ch R = 1 ,78134   ,585,585,585
BEGIN DESCRIPTION:
COON CREEK 109.0
END DESCRIPTION:
XS GIS Cut Line= 3
      3698499.64     10769910.17      3697699.61     10770610.19
      3697199.56      10770710.2
#Sta/Elev= 30
  3911.5  415.92  3929.6  415.03  3982.2  410.42  4017.8  400.78  4031.6  398.59
  4060.1  388.52  4110.4   378.9    4129  378.87  4166.4   373.7  4211.4  372.51
  4315.4  370.03  4358.1  370.74  4393.2  368.86    4471  369.52    4528  367.22
  4556.5  368.45  4658.9  367.19  4868.2  364.74  4960.8  366.22  5002.1  361.53
  5004.9  361.03  5008.1  361.53  5015.3  363.94  5035.7  366.25  5249.9  365.57
  5331.5  368.55  5351.9  370.02  5413.1  388.66  5444.2  390.96  5484.5  393.53
#Mann= 8 ,-1 , 0
  3911.5     .05       0  3929.6     .16       0    4129     .05       0
  4211.4     .12       0  4658.9     .05       0  5002.1     .03       0
  5008.1     .05       0  5444.2     .16       0
Bank Sta=4960.8,5035.7
XS Rating Curve= 0 ,0
Exp/Cntr=0.3,0.1

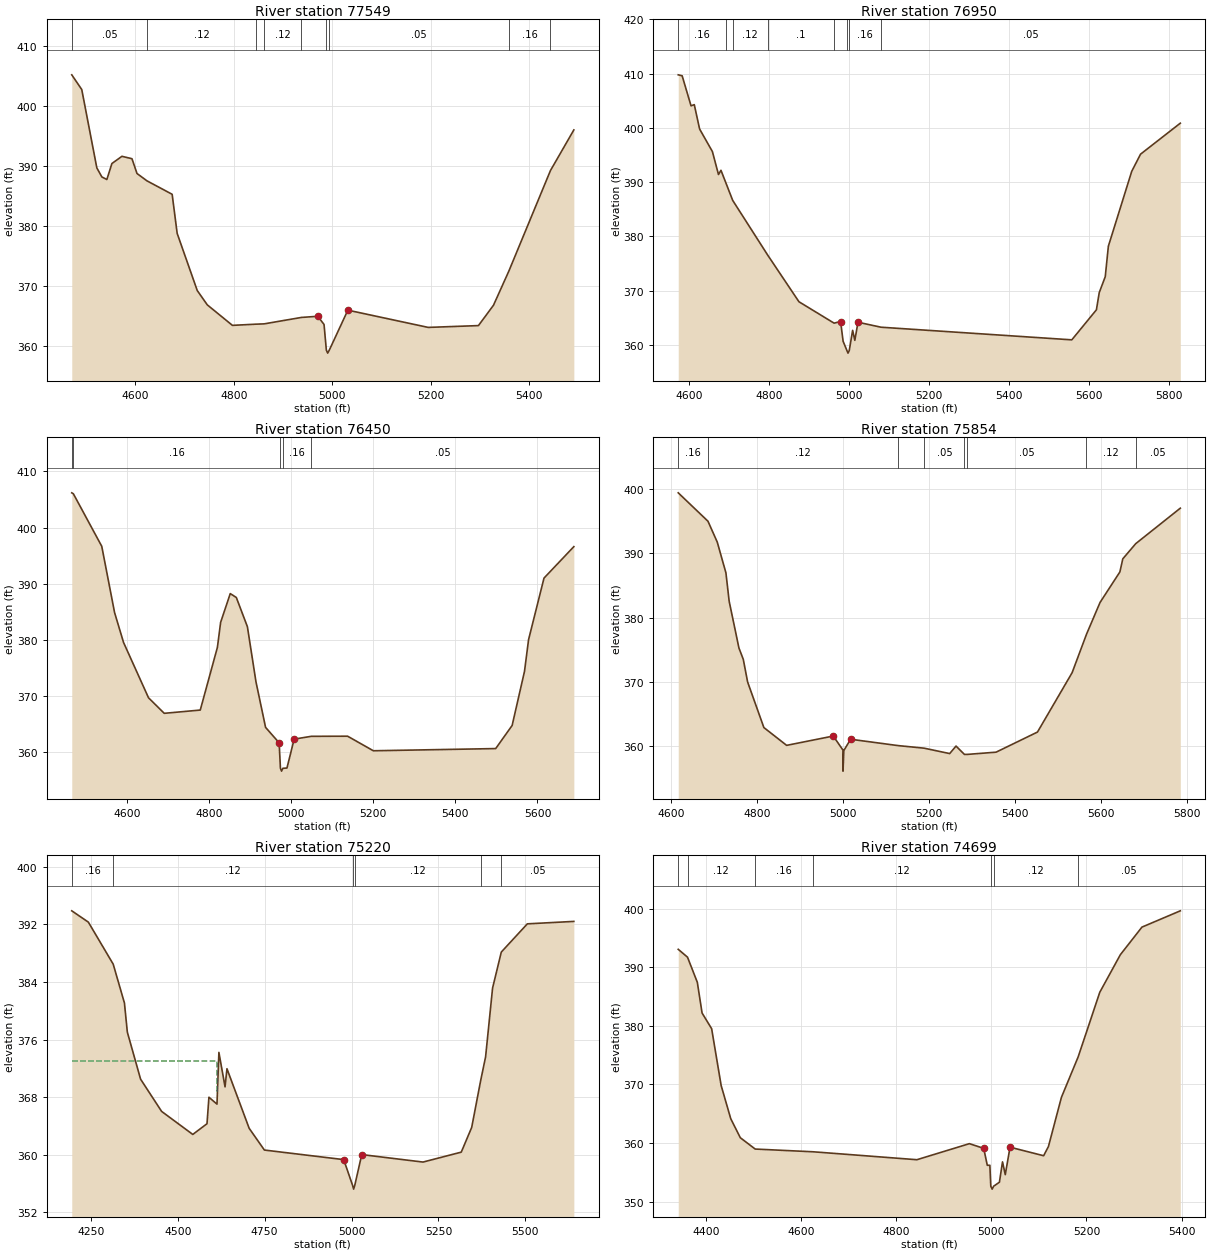
Type RM Length L Ch R = 1 ,77549   ,599,599,599
BEGIN DESCRIPTION:
COON CREEK 108.0
END DESCRIPTION:
XS GIS Cut Line= 3
      3698149.56      10770010.2      3697649.61     10770110.19
      3697149.57      10770210.2
#Sta/Elev= 30
  4470.9   405.2  4491.2  402.75  4521.8  389.72    4532  388.21  4542.2  387.78
  4552.4  390.44  4572.8  391.64  4593.2  391.24  4603.4  388.78  4623.6  387.56
  4674.8  385.32    4685  378.81  4725.8   369.3  4746.2  366.92  4797.2  363.51
  4845.5  363.71  4861.7  363.76  4937.4  364.83  4970.6  365.02  4983.3  363.66
    4988  359.39  4990.7  358.89    4994  359.39  5031.7  366.04  5194.9  363.17
  5296.9  363.47  5327.5  366.86  5358.8  372.56  5443.2  389.27  5490.7  396.03
#Mann= 9 ,-1 , 0
  4470.9     .05       0  4623.6     .12       0  4845.5     .16       0
  4861.7     .12       0  4937.4     .05       0    4988     .03       0
    4994     .05       0  5358.8     .16       0  5443.2     .05       0
Bank Sta=4970.6,5031.7
XS Rating Curve= 0 ,0
Exp/Cntr=0.3,0.1

Type RM Length L Ch R = 1 ,76950   ,500,500,500
BEGIN DESCRIPTION:
COON CREEK 107.0
END DESCRIPTION:
XS GIS Cut Line= 3
      3698399.61     10769860.19      3697999.61     10769710.19
      3697249.56     10769360.17
#Sta/Elev= 30
  4572.5  409.79  4582.3  409.61  4604.5  404.07  4612.6  404.29  4625.9   399.8
  4657.9  395.63  4673.1   391.4  4679.3  392.18  4692.2  389.74  4708.7  386.62
  4796.5  376.49  4874.2  367.93    4962  363.98  4978.3  364.28  4984.6  360.64
    4994  358.95  4996.8  358.45    5000  358.95  5008.4  362.65  5013.9  360.81
  5021.8  364.15  5079.4  363.23  5556.2   360.9  5617.7  366.44  5624.8  369.62
  5639.8  372.55  5647.6  378.18    5706  391.99    5728  395.15  5827.4  400.87
#Mann= 8 ,-1 , 0
  4572.5     .16       0  4692.2     .07       0  4708.7     .12       0
  4796.5      .1       0    4962     .16       0    4994     .07       0
    5000     .16       0  5079.4     .05       0
Bank Sta=4978.3,5021.8
XS Rating Curve= 0 ,0
Exp/Cntr=0.3,0.1

Type RM Length L Ch R = 1 ,76450   ,596,596,596
BEGIN DESCRIPTION:
COON CREEK 106.0
END DESCRIPTION:
XS GIS Cut Line= 3
      3698549.63     10769110.18      3698049.61     10769260.19
      3697349.63     10769310.19
#Sta/Elev= 30
  4464.9  406.17  4468.8     406    4538  396.66  4569.3  384.86  4591.1  379.56
    4652  369.72  4690.3  366.96  4778.1  367.54  4819.9  378.69  4827.7  383.12
  4851.2  388.25    4866  387.56    4893  382.36  4913.9  372.56  4937.3  364.46
  4970.4  361.71  4973.5  357.18  4976.2  356.68  4979.5  357.18  4989.4  357.23
    5007  362.37  5048.8  362.87  5137.3  362.89    5200   360.3  5498.2  360.69
  5538.3   364.8  5568.4  374.41  5578.4  380.08    5616  391.01  5688.7   396.6
#Mann= 5 ,-1 , 0
  4464.9     .05       0  4468.8     .16       0  4973.5     .07       0
  4979.5     .16       0  5048.8     .05       0
#XS Ineff= 2 , 0
          4798.9  373.04
Permanent Ineff=
       F       F
Bank Sta=4970.4,5007
XS Rating Curve= 0 ,0
Exp/Cntr=0.3,0.1

Type RM Length L Ch R = 1 ,75854   ,634,634,634
BEGIN DESCRIPTION:
COON CREEK 105.0
END DESCRIPTION:
XS GIS Cut Line= 3
       3698299.6     10768710.19      3697899.61     10768760.19
      3697237.99     10769141.42
#Sta/Elev= 30
  4617.2  399.41  4686.3  394.99  4707.9  391.74    4728  386.96  4735.6  382.52
  4758.3  375.25  4768.4  373.49  4778.4  369.98  4816.2  362.88  4869.1  360.11
  4977.5  361.56  5000.1  359.36 5000.11   356.1    5002   359.3  5017.8  361.06
  5128.4  360.07  5188.8  359.67    5248  358.83  5262.7     360  5282.3   358.7
  5288.3   358.7  5355.8  359.05    5452  362.18  5532.5  371.42  5565.9   377.4
  5597.4  382.35  5643.5   387.1  5650.3  389.14  5680.3   391.5  5783.9  397.02
#Mann= 8 ,-1 , 0
  4617.2     .16       0  4686.3     .12       0  5128.4     .16       0
  5188.8     .05       0  5282.3     .07       0  5288.3     .05       0
  5565.9     .12       0  5680.3     .05       0
Bank Sta=4977.5,5017.8
XS Rating Curve= 0 ,0
Exp/Cntr=0.3,0.1

Type RM Length L Ch R = 1 ,75220   ,521,521,521
BEGIN DESCRIPTION:
COON CREEK 104.0
END DESCRIPTION:
XS GIS Cut Line= 3
      3698305.65     10768094.57      3697524.41     10768443.53
      3696935.91      10768422.7
#Sta/Elev= 30
    4195  393.88  4242.7  392.31  4314.2  386.47  4346.5  381.08  4354.9  377.02
    4393  370.49  4453.5  366.01  4543.2  362.81  4584.1   364.3  4589.6  367.98
  4612.8  367.02  4618.3  374.21    4636  369.42  4641.5  371.94  4705.4  363.66
  4749.2  360.64  4977.4  359.31  5003.1  355.71  5005.9  355.21  5009.1  355.71
  5029.3  360.01  5205.5  358.97  5315.6  360.35  5345.6  363.78  5371.5  370.31
  5385.6  373.59  5405.7  383.15  5430.8  388.15  5505.7  392.07  5639.5  392.41
#Mann= 6 ,-1 , 0
    4195     .16       0  4314.2     .12       0  5003.1     .07       0
  5009.1     .12       0  5371.5     .16       0  5430.8     .05       0
#XS Ineff= 2 , 0
         4613.91  372.97
Permanent Ineff=
       F       F
Bank Sta=4977.4,5029.3
XS Rating Curve= 0 ,0
Exp/Cntr=0.3,0.1

Type RM Length L Ch R = 1 ,74699   ,565,565,565
BEGIN DESCRIPTION:
COON CREEK 103.0
END DESCRIPTION:
XS GIS Cut Line= 3
      3698049.59     10767910.19      3697399.61     10767960.19
      3697049.62     10767760.19
#Sta/Elev= 30
  4342.2  393.06  4361.7  391.72  4382.3  387.43  4392.3  382.19  4412.4  379.51
  4432.4  369.81  4452.5  364.16  4472.6  360.91  4503.9  358.97  4626.2   358.5
  4843.7  357.15    4954  359.89  4984.1  359.09  4991.6   356.2    4997   356.2
    4999  352.63  5001.8  352.13    5005  352.63  5017.1  353.31  5023.6  356.78
  5029.4   354.6  5039.4  359.29    5110  357.83  5120.1   359.4  5147.4   367.8
  5182.7  374.73    5228  385.73  5271.2  392.14  5316.6  396.85  5397.2  399.63
#Mann= 7 ,-1 , 0
  4342.2     .16       0  4361.7     .12       0  4503.9     .16       0
  4626.2     .12       0    4999     .07       0    5005     .12       0
  5182.7     .05       0
Bank Sta=4984.1,5039.4
XS Rating Curve= 0 ,0
Exp/Cntr=0.3,0.1

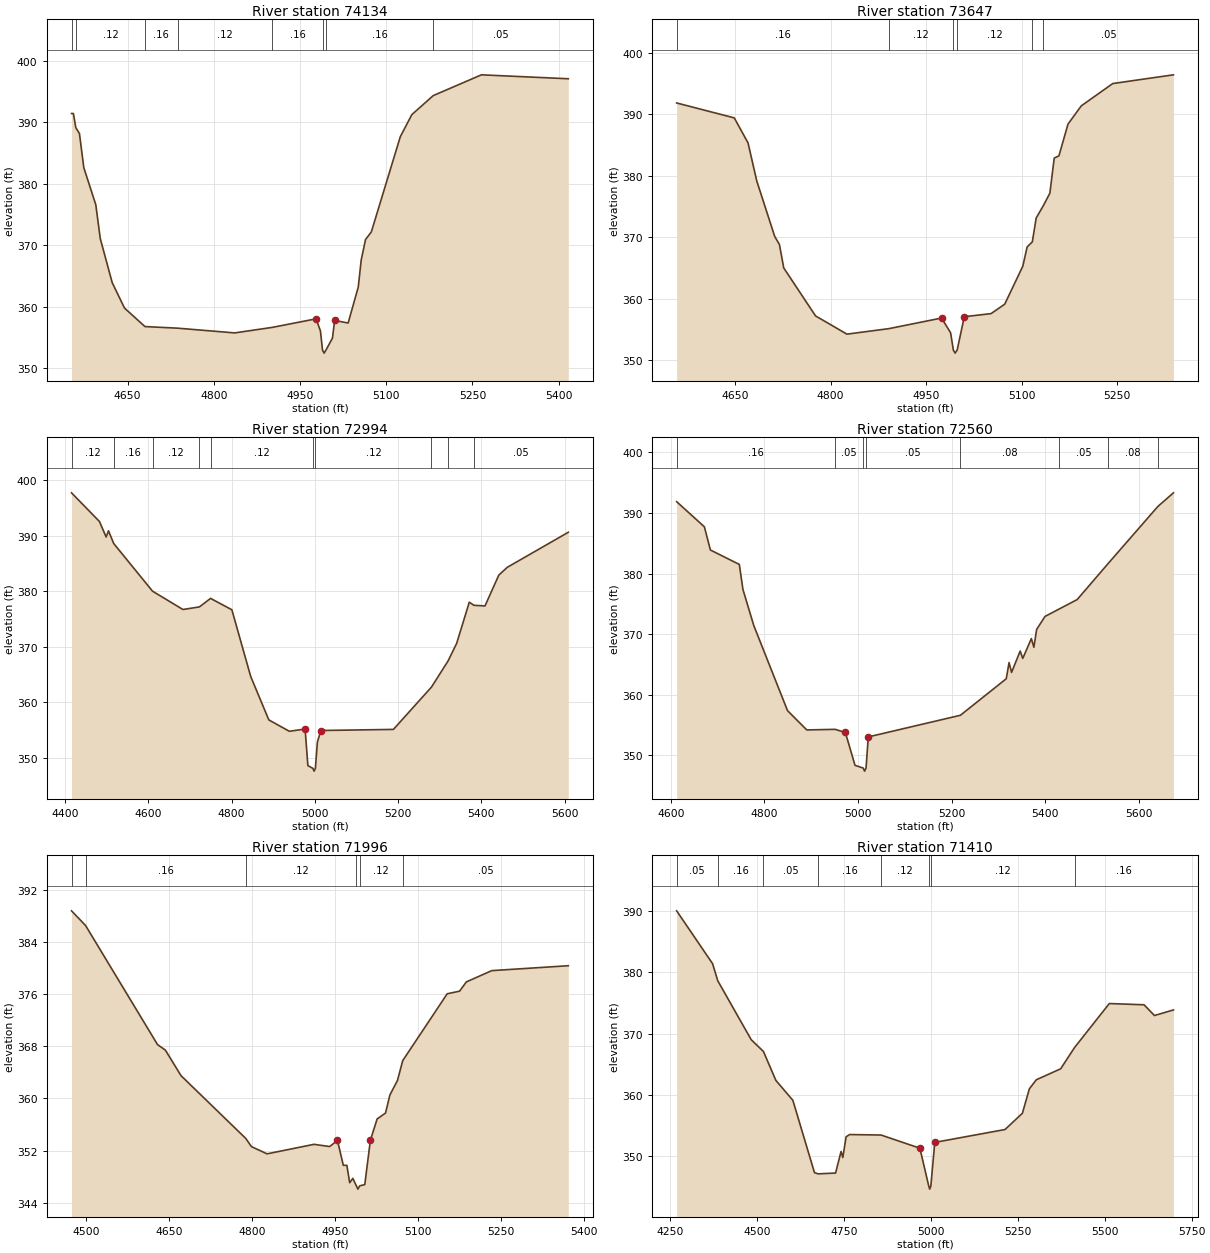
Type RM Length L Ch R = 1 ,74134   ,487,487,487
BEGIN DESCRIPTION:
COON CREEK 102.0
END DESCRIPTION:
XS GIS Cut Line= 3
      3698049.64     10767860.22      3697699.61     10767560.19
      3697649.61     10767160.22
#Sta/Elev= 30
  4552.6  391.43  4555.9  391.43  4560.1  389.12  4566.4  388.18    4574  382.62
  4594.9  376.57  4602.6  371.09  4623.4  363.91  4644.8  359.77  4680.4  356.76
  4737.3   356.5  4836.4  355.73  4901.9  356.63    4978  358.02  4985.6  356.04
  4989.2  352.94    4992  352.44  4995.2  352.94  5006.5  354.88  5010.3  357.76
  5033.8  357.34  5051.4   363.2  5056.5  367.59    5064  370.92  5074.1  372.16
  5124.5  387.65  5144.6  391.25  5181.8  394.34  5265.6  397.72  5416.7  397.08
#Mann= 8 ,-1 , 0
  4552.6     .16       0  4560.1     .12       0  4680.4     .16       0
  4737.3     .12       0  4901.9     .16       0  4989.2     .07       0
  4995.2     .16       0  5181.8     .05       0
Bank Sta=4978,5010.3
XS Rating Curve= 0 ,0
Exp/Cntr=0.3,0.1

Type RM Length L Ch R = 1 ,73647   ,653,653,653
BEGIN DESCRIPTION:
COON CREEK 101.0
END DESCRIPTION:
XS GIS Cut Line= 2
      3698375.24     10767582.57      3697845.75     10767009.68
#Sta/Elev= 30
  4558.3  391.83  4648.8   389.4  4670.4  385.33  4684.1  379.14  4712.3   370.1
  4719.7  368.79  4726.5  364.97  4776.4  357.17  4825.7   354.2  4891.3  355.09
  4974.3  356.82  4988.5  354.42  4992.8  351.61  4995.6  351.11  4998.8  351.61
    5010  357.04    5052  357.54  5073.5  359.08  5101.9  365.27  5108.7   368.4
  5116.8  369.22  5122.9  373.11  5134.1  375.11  5144.4  377.15  5151.2  382.86
  5158.6  383.22  5172.8  388.38  5193.7  391.36  5243.1  394.99  5338.4  396.41
#Mann= 6 ,-1 , 0
  4558.3     .16       0  4891.3     .12       0  4992.8     .07       0
  4998.8     .12       0  5116.8     .16       0  5134.1     .05       0
Bank Sta=4974.3,5010
XS Rating Curve= 0 ,0
Exp/Cntr=0.3,0.1

Type RM Length L Ch R = 1 ,72994   ,434,434,434
BEGIN DESCRIPTION:
COON CREEK 100.0
END DESCRIPTION:
XS GIS Cut Line= 3
       3698987.2     10767135.51      3698388.27     10766805.67
      3697884.82     10766723.21
#Sta/Elev= 30
  4415.2  397.72  4482.4  392.56  4498.4  389.77  4504.1  390.88  4516.7  388.59
  4609.9  380.02    4683  376.72  4722.7  377.19  4749.4  378.72  4800.6  376.67
  4845.9  364.66  4889.4  356.85  4938.7   354.8  4976.6  355.21  4983.3  348.62
  4995.3  348.13  4998.1  347.63  5001.3  348.13  5006.1  352.85  5014.4  354.94
  5188.8  355.14  5280.3  362.76  5320.1  367.45  5340.8  370.62  5371.2  378.04
  5382.2  377.48  5408.9  377.36  5442.1  382.91  5462.4  384.31  5609.1  390.62
#Mann= 10 ,-1 , 0
  4415.2     .12       0  4516.7     .16       0  4609.9     .12       0
  4722.7     .05       0  4749.4     .12       0  4995.3     .07       0
  5001.3     .12       0  5280.3     .05       0  5320.1     .16       0
  5382.2     .05       0
Bank Sta=4976.6,5014.4
XS Rating Curve= 0 ,0
Exp/Cntr=0.3,0.1

Type RM Length L Ch R = 1 ,72560   ,564,564,564
BEGIN DESCRIPTION:
COON CREEK 99.0
END DESCRIPTION:
XS GIS Cut Line= 3
      3698999.65      10766560.2      3698599.61     10766460.19
      3697999.65     10766210.21
#Sta/Elev= 30
  4612.2  391.86  4671.5  387.71  4684.4  383.88  4746.2   381.5    4754  377.35
  4777.2   371.4  4849.3  357.36  4890.5  354.17    4951  354.27    4973  353.75
  4993.6  348.33  5011.2  347.87    5014  347.37  5017.2  347.87    5022  353.02
  5218.9  356.59    5317  362.62    5323  365.29  5328.4  363.67  5346.8   367.2
  5352.3  365.98  5370.7  369.26  5376.1  367.81    5382  370.77  5399.9  372.91
    5430  374.13  5468.7   375.7  5535.6  381.71  5641.1  391.06  5674.5  393.32
#Mann= 8 ,-1 , 0
  4612.2     .16       0    4951     .05       0  5011.2     .04       0
  5017.2     .05       0  5218.9     .08       0    5430     .05       0
  5535.6     .08       0  5641.1     .05       0
Bank Sta=4973,5022
XS Rating Curve= 0 ,0
Exp/Cntr=0.3,0.1

Type RM Length L Ch R = 1 ,71996   ,586,586,586
BEGIN DESCRIPTION:
COON CREEK 98.0
END DESCRIPTION:
XS GIS Cut Line= 3
       3699149.6     10766310.18      3698799.61     10765960.19
      3698449.58     10765760.17
#Sta/Elev= 30
  4473.8  388.77  4499.2  386.52  4629.3  368.26  4643.5  367.41  4671.8  363.49
    4789  353.85  4799.1  352.61  4827.3   351.5  4912.2  352.96  4940.5  352.62
  4954.6  353.55  4965.2  349.74  4971.6  349.74  4976.7  347.07  4982.4  347.74
  4988.8  346.59  4991.5  346.09  4994.8  346.59    5004  346.79  5014.1  353.58
  5026.3  356.85  5041.5  357.76  5049.4  360.53  5063.1  362.76  5072.6   365.8
    5153  376.05  5175.4  376.45  5187.6  377.87  5233.7   379.6  5371.9  380.35
#Mann= 6 ,-1 , 0
  4473.8     .05       0  4499.2     .16       0    4789     .12       0
  4988.8     .07       0  4994.8     .12       0  5072.6     .05       0
Bank Sta=4954.6,5014.1
XS Rating Curve= 0 ,0
Exp/Cntr=0.3,0.1

Type RM Length L Ch R = 1 ,71410   ,619,619,619
BEGIN DESCRIPTION:
COON CREEK 97.0
END DESCRIPTION:
XS GIS Cut Line= 4
      3699264.41     10766232.58      3699167.19      10765579.8
      3699076.91     10765475.63      3698444.98     10765468.69
#Sta/Elev= 30
  4267.8  390.01  4371.3  381.39  4386.2   378.6  4482.5  368.99  4517.6  367.08
  4553.3  362.37  4602.3  359.11  4664.5  347.32    4675  347.12  4725.2  347.25
    4741  350.77  4746.1  349.78  4755.5  353.16  4765.6  353.53  4856.2  353.45
  4967.9   351.3  4993.4  345.13  4996.2  344.63  4999.4  345.13  5010.7  352.25
  5212.9  354.35  5262.9     357  5282.9  360.98  5302.9  362.46    5373  364.25
  5413.3  367.74    5513  374.89    5613  374.69    5643  372.94  5697.6  373.85
#Mann= 8 ,-1 , 0
  4267.8     .05       0  4386.2     .16       0  4517.6     .05       0
    4675     .16       0  4856.2     .12       0  4993.4     .07       0
  4999.4     .12       0  5413.3     .16       0
Bank Sta=4967.9,5010.7
XS Rating Curve= 0 ,0
Exp/Cntr=0.3,0.1

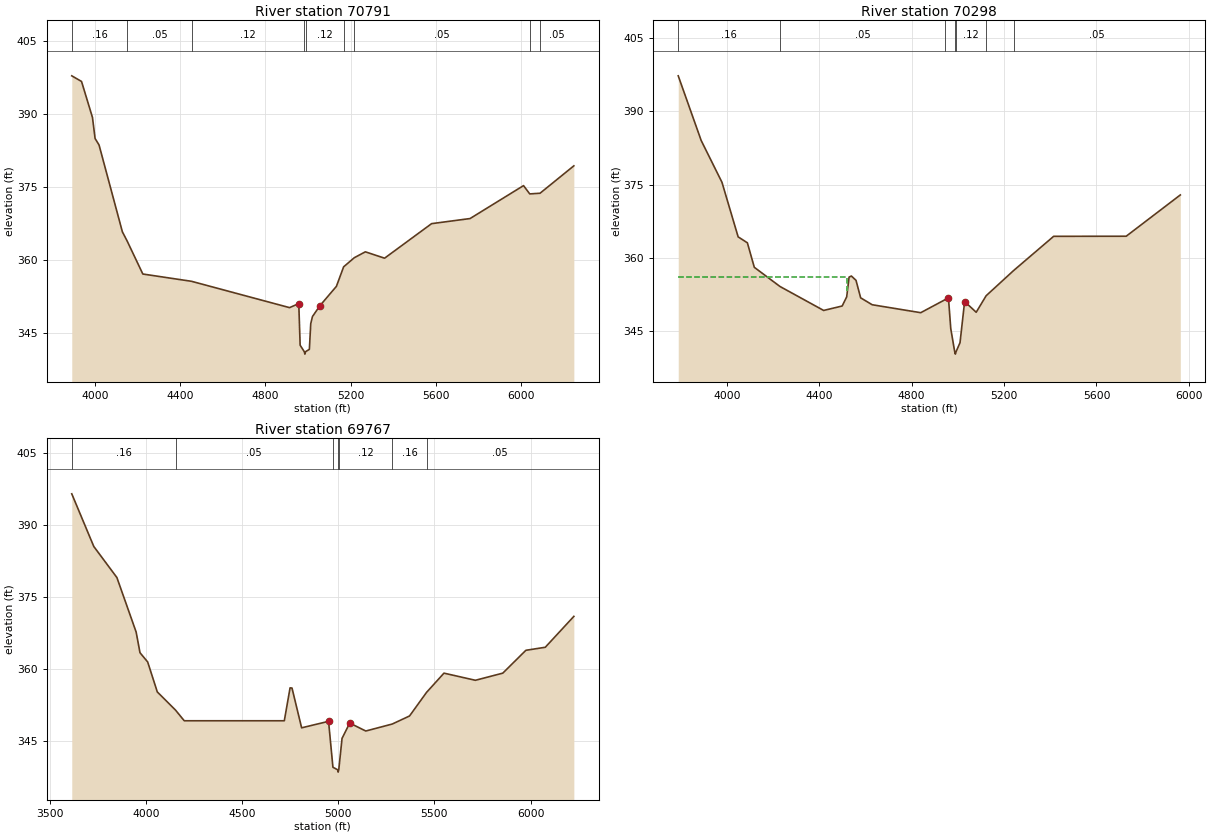
Type RM Length L Ch R = 1 ,70791   ,493,493,493
BEGIN DESCRIPTION:
COON CREEK 96.0
END DESCRIPTION:
XS GIS Cut Line= 4
      3699868.57     10766204.78      3699646.36     10765246.46
      3699444.97     10765086.74      3698334.27      10765163.1
#Sta/Elev= 30
  3892.5  397.84  3938.3  396.68  3989.6  389.27  4001.8  384.94  4020.4  383.61
  4129.8  365.73  4152.8  363.78  4225.7  357.04    4454  355.54  4913.6  350.12
  4956.9  350.95  4963.3  342.38  4982.8  341.05  4985.5  340.55  4988.8  341.05
  5006.6  341.54    5013  346.82    5021  348.28  5056.2  350.53  5133.3   354.5
  5167.2  358.52  5217.3   360.4    5269  361.61  5359.2   360.3  5579.7  367.41
  5760.1  368.46  6010.7  375.24  6039.9  373.53  6088.2  373.67  6246.6  379.31
#Mann= 9 ,-1 , 0
  3892.5     .16       0  4152.8     .05       0    4454     .12       0
  4982.8     .07       0  4988.8     .12       0  5167.2     .16       0
  5217.3     .05       0  6039.9     .12       0  6088.2     .05       0
Bank Sta=4956.9,5056.2
XS Rating Curve= 0 ,0
Exp/Cntr=0.3,0.1

Type RM Length L Ch R = 1 ,70298   ,531,531,531
BEGIN DESCRIPTION:
COON CREEK 95.0
END DESCRIPTION:
XS GIS Cut Line= 3
      3700708.84     10764656.19      3699368.58     10764690.91
       3698618.6     10765052.01
#Sta/Elev= 30
  3789.8  397.28  3889.1  384.03  3979.1  375.46  4049.1  364.28  4089.1  363.06
  4119.1  358.04  4230.3  354.11  4419.2   349.2  4499.3  350.11  4518.9  351.98
  4529.3  356.04  4539.3  356.25  4559.3  355.37  4579.3  351.79  4629.3  350.37
  4839.4  348.74  4946.4  351.45  4959.4  351.74  4969.4  345.47  4986.4  340.75
  4989.2  340.25  4992.4  340.75  5009.4  342.59  5029.4  351.02  5079.5  348.83
  5122.4  352.21  5241.7  357.39  5414.7  364.39  5728.7  364.41  5962.9  372.87
#Mann= 7 ,-1 , 0
  3789.8     .16       0  4230.3     .05       0  4946.4     .12       0
  4986.4     .07       0  4992.4     .12       0  5122.4     .16       0
  5241.7     .05       0
#XS Ineff= 2 , 0
         4521.96  356.09
Permanent Ineff=
       F       F
Bank Sta=4959.4,5029.4
XS Rating Curve= 0 ,0
Exp/Cntr=0.3,0.1

Type RM Length L Ch R = 1 ,69767   ,538,538,538
BEGIN DESCRIPTION:
COON CREEK 94.0
END DESCRIPTION:
XS GIS Cut Line= 3
      3700924.12     10764218.69      3699444.97     10764246.46
      3698563.79     10764954.18
#Sta/Elev= 30
  3615.6  396.57  3730.1  385.58  3850.1   379.1  3950.2  367.72  3970.2  363.41
  4010.2  361.47  4060.2  355.22  4155.3  351.41  4200.2   349.2  4720.3   349.2
  4750.3  356.07  4760.3  356.03  4810.3  347.73  4950.3  349.08    4973  339.49
  4997.4  338.98  5000.1  338.48  5003.4  338.98  5020.4  345.53  5060.4  348.72
  5143.8  347.06  5281.5  348.52  5371.2   350.2  5459.7  355.13  5550.2  359.14
  5713.5  357.65  5855.9  359.14  5975.9  363.91  6076.7  364.54  6225.2  370.99
#Mann= 7 ,-1 , 0
  3615.6     .16       0  4155.3     .05       0    4973     .12       0
  4997.4     .07       0  5003.4     .12       0  5281.5     .16       0
  5459.7     .05       0
Bank Sta=4950.3,5060.4
XS Rating Curve= 0 ,0
Exp/Cntr=0.3,0.1