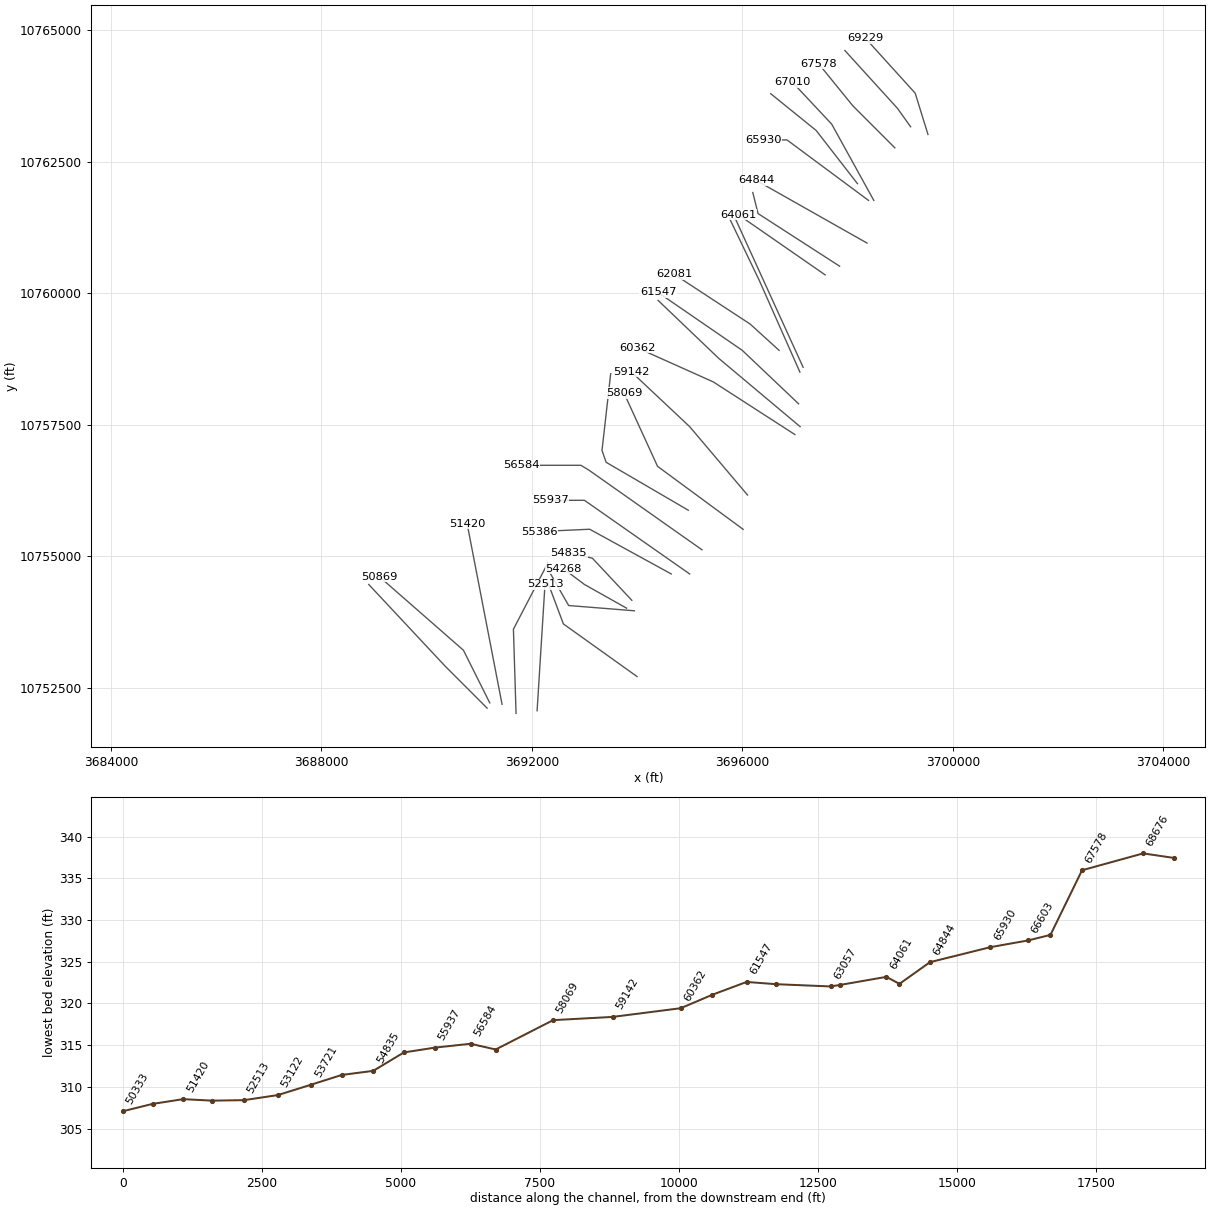
HEC-RAS study COON CREEK.prj: COON CREEK Base Level Engineering

--- COON CREEK.g01 (geometry) --- (continued)

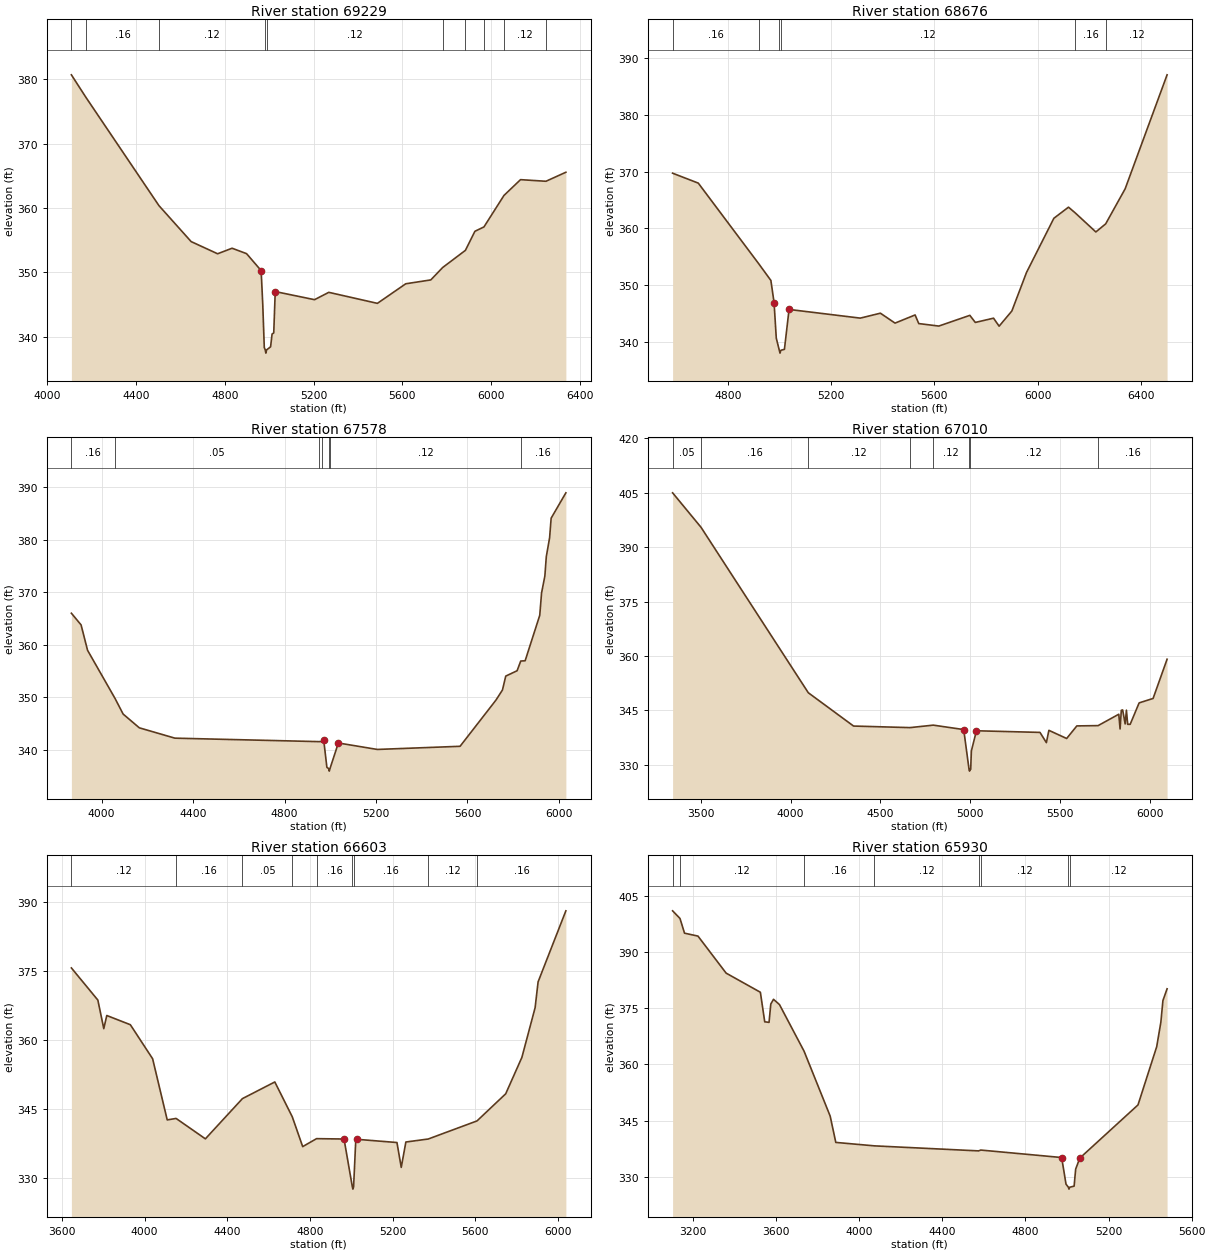
Type RM Length L Ch R = 1 ,69229   ,553,553,553
BEGIN DESCRIPTION:
COON CREEK 93.0
END DESCRIPTION:
XS GIS Cut Line= 3
      3699529.12      10763014.8      3699286.06     10763799.52
       3698341.6     10764841.21
#Sta/Elev= 30
  4109.1  380.67    4175  377.15  4503.7  360.35  4648.6  354.77  4767.8  352.88
    4833  353.74  4898.2   352.9  4963.9  350.27  4971.3  344.95  4978.1  338.31
  4982.5  337.95  4985.2  337.45  4988.5  337.95  5006.5  338.43  5013.2  340.43
  5020.7  340.58  5027.4  347.01  5204.5  345.75  5268.7  346.89  5487.6  345.18
  5615.4  348.22  5728.2  348.82  5781.5  350.74  5884.1  353.41  5926.9  356.37
  5967.7  357.05  6057.9  361.94  6132.4  364.39    6247  364.14  6336.7  365.54
#Mann= 10 ,-1 , 0
  4109.1     .12       0    4175     .16       0  4503.7     .12       0
  4982.5     .07       0  4988.5     .12       0  5781.5     .16       0
  5884.1     .12       0  5967.7     .16       0  6057.9     .12       0
    6247     .16       0
Bank Sta=4963.9,5027.4
XS Rating Curve= 0 ,0
Exp/Cntr=0.3,0.1

Type RM Length L Ch R = 1 ,68676   ,1098,1098,1098
BEGIN DESCRIPTION:
COON CREEK 92.0
END DESCRIPTION:
XS GIS Cut Line= 3
      3699199.62     10763160.17      3698949.61     10763510.19
      3697949.58     10764610.23
#Sta/Elev= 30
  4585.2  369.71  4684.8  367.96  4919.5  353.72  4966.2   350.8  4978.5   346.9
  4987.1  340.63  4998.8  338.49  5001.6  337.99  5004.8  338.49  5018.7  338.66
  5036.6  345.69  5312.7  344.16  5390.7  345.03  5447.5  343.28  5525.2  344.72
  5539.4   343.2  5617.1  342.76  5737.4  344.65  5758.6   343.4  5829.3  344.15
  5850.9  342.74  5900.2  345.41    5957   352.2  6063.1  361.76  6119.8  363.72
  6145.7  362.72  6225.9  359.35    6264  360.78  6339.4  366.95    6502  387.05
#Mann= 6 ,-1 , 0
  4585.2     .16       0  4919.5     .12       0  4998.8     .07       0
  5004.8     .12       0  6145.7     .16       0    6264     .12       0
Bank Sta=4978.5,5036.6
XS Rating Curve= 0 ,0
Exp/Cntr=0.3,0.1

Type RM Length L Ch R = 1 ,67578   ,568,568,568
BEGIN DESCRIPTION:
COON CREEK 90.0
END DESCRIPTION:
XS GIS Cut Line= 3
      3698899.59     10762760.21      3698099.61     10763560.19
      3697449.62     10764360.17
#Sta/Elev= 30
  3868.1  366.05  3910.5  363.82  3938.8  358.99  4059.4  349.78  4094.3  346.84
  4165.1  344.22  4320.6  342.25  4949.7  341.59    4962  341.61  4971.2  341.94
  4985.3  336.68  4992.9  336.47  4995.7  335.97  4998.9  336.47  5035.4  341.33
  5205.6   340.1  5567.6   340.7  5724.2  349.48    5753  351.43  5767.3  354.07
  5816.9  355.09  5832.9  356.94  5852.1  356.99    5916  365.65  5923.9   369.9
  5938.3  373.12  5944.7  376.84  5959.1  380.42  5965.8  384.15  6030.2  388.98
#Mann= 7 ,-1 , 0
  3868.1     .16       0  4059.4     .05       0  4949.7     .16       0
    4962     .12       0  4992.9     .07       0  4998.9     .12       0
  5832.9     .16       0
Bank Sta=4971.2,5035.4
XS Rating Curve= 0 ,0
Exp/Cntr=0.3,0.1

Type RM Length L Ch R = 1 ,67010   ,407,407,407
BEGIN DESCRIPTION:
COON CREEK 89.0
END DESCRIPTION:
XS GIS Cut Line= 3
      3698499.63     10761760.15      3697699.61     10763210.19
      3696949.59     10764010.21
#Sta/Elev= 30
    3343  404.97    3501  395.48  4098.3  349.84  4350.4  340.65  4664.5  340.22
  4794.3   340.9  4963.6  339.68  4993.2  328.72    4996  328.22  4999.2  328.72
  5002.5  328.72  5006.2   333.8  5034.5  339.35  5388.2   338.9  5423.8  336.08
  5437.7  339.47  5536.6  337.22  5593.3  340.69  5711.6  340.77  5826.8  343.91
  5834.1  339.85  5840.9  344.99  5848.3   345.1  5862.4  341.24  5869.3  345.03
  5876.4  341.13  5890.3  341.13  5940.1  347.04  6017.8  348.26  6095.7  359.08
#Mann= 8 ,-1 , 0
    3343     .05       0    3501     .16       0  4098.3     .12       0
  4664.5     .16       0  4794.3     .12       0  4993.2     .07       0
  4999.2     .12       0  5711.6     .16       0
Bank Sta=4963.6,5034.5
XS Rating Curve= 0 ,0
Exp/Cntr=0.3,0.1

Type RM Length L Ch R = 1 ,66603   ,673,673,673
BEGIN DESCRIPTION:
COON CREEK 88.0
END DESCRIPTION:
XS GIS Cut Line= 3
      3698188.86     10762079.07      3697403.27     10763090.36
      3696539.53     10763789.17
#Sta/Elev= 30
    3646  375.58    3774   368.6  3802.7   362.4  3817.2  365.25  3931.2  363.25
  4038.9  355.86  4109.5  342.58  4152.4   342.9  4294.1  338.47  4473.2   347.2
  4629.9  350.82  4714.2  343.27  4764.7  336.78  4831.7  338.51  4964.7  338.43
  5004.9  328.05  5007.6  327.55  5010.9  328.05  5021.3  338.06  5028.7  338.36
  5220.6  337.67  5241.4  332.27  5263.7  337.78  5371.8  338.43  5607.8  342.36
  5746.6  348.25  5824.9  356.16  5888.9  366.96  5903.3  372.56  6037.6  387.98
#Mann= 9 ,-1 , 0
    3646     .12       0  4152.4     .16       0  4473.2     .05       0
  4714.2     .12       0  4831.7     .16       0  5004.9     .07       0
  5010.9     .16       0  5371.8     .12       0  5607.8     .16       0
Bank Sta=4964.7,5028.7
XS Rating Curve= 0 ,0
Exp/Cntr=0.3,0.1

Type RM Length L Ch R = 1 ,65930   ,1086,1086,1086
BEGIN DESCRIPTION:
COON CREEK 87.0
END DESCRIPTION:
XS GIS Cut Line= 3
      3698399.58     10761760.21      3696849.61     10762910.19
       3696399.6     10762910.19
#Sta/Elev= 30
  3101.7  400.98  3137.2  398.95  3159.1  395.02  3223.8  394.24  3359.4  384.36
  3524.2  379.26  3545.1  371.38  3565.9  371.23  3574.3  376.11  3587.3  377.38
    3616  375.98  3734.5  363.54  3860.1  346.23  3887.2  339.21  4073.1  338.29
  4574.3  336.95  4584.9  337.17  4974.3  335.18  4995.2  328.08  5006.8  327.25
  5009.5  326.75  5012.8  327.25  5034.2  327.55  5041.7  332.09  5061.7  335.03
  5341.7  349.21  5431.7  364.73  5451.7  371.26  5461.7  377.05  5481.7  380.18
#Mann= 8 ,-1 , 0
  3101.7     .05       0  3137.2     .12       0  3734.5     .16       0
  4073.1     .12       0  4574.3     .16       0  4584.9     .12       0
  5006.8     .07       0  5012.8     .12       0
Bank Sta=4974.3,5061.7
XS Rating Curve= 0 ,0
Exp/Cntr=0.3,0.1

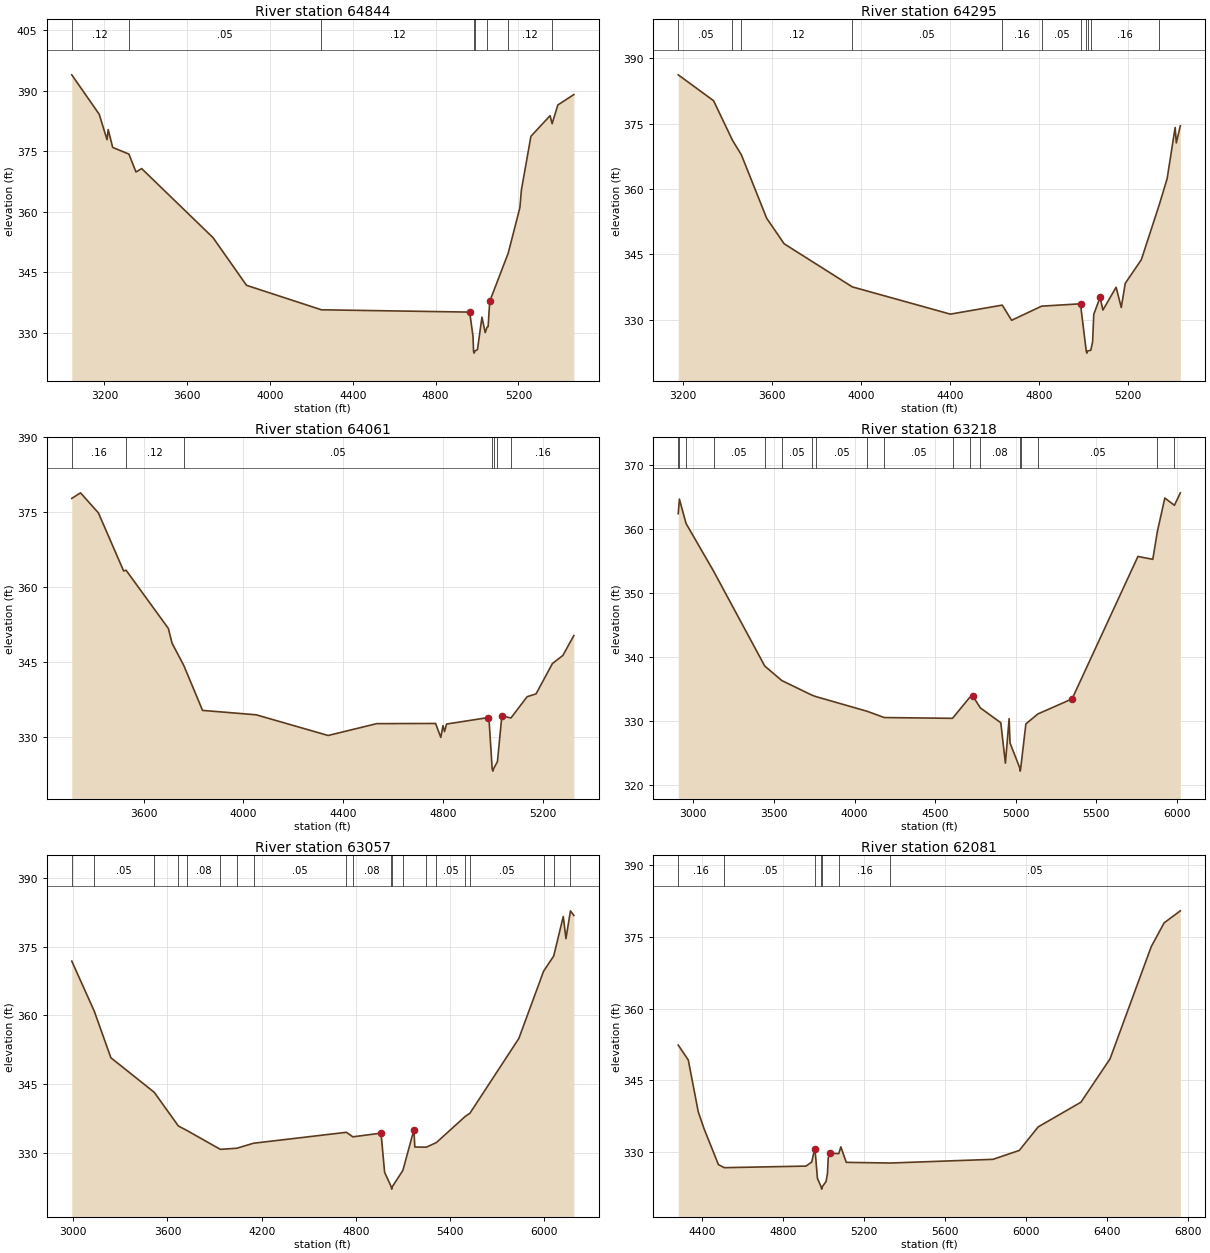
Type RM Length L Ch R = 1 ,64844   ,549,549,549
BEGIN DESCRIPTION:
COON CREEK 85.0
END DESCRIPTION:
XS GIS Cut Line= 2
      3698370.26     10760949.89      3696259.14     10762144.34
#Sta/Elev= 30
  3042.2  393.99  3174.9   384.2  3212.5   377.9  3218.2  380.41  3239.9  375.98
  3318.2  374.33  3352.5  369.89  3379.9  370.73  3724.8  353.59  3886.5  341.77
  4248.5   335.7  4964.6  335.13  4980.5  329.17  4983.3  325.45    4986  324.95
  4989.3  325.45  5002.2  325.83  5023.8  333.87  5039.7  330.04  5048.8  331.43
  5053.6   331.5  5061.4  337.79  5150.7  349.75  5207.1  361.03  5214.5  365.45
  5260.4  378.73  5352.9  383.86    5363  381.87  5390.4  386.51  5467.8  389.09
#Mann= 8 ,-1 , 0
  3042.2     .12       0  3318.2     .05       0  4248.5     .12       0
  4983.3     .07       0  4989.3     .12       0  5048.8     .16       0
  5150.7     .12       0    5363     .05       0
Bank Sta=4964.6,5061.4
XS Rating Curve= 0 ,0
Exp/Cntr=0.3,0.1

Type RM Length L Ch R = 1 ,64295   ,234,234,234
BEGIN DESCRIPTION:
COON CREEK 84.0
END DESCRIPTION:
XS GIS Cut Line= 3
      3697849.64     10760510.17      3696299.61     10761510.19
      3696199.62     10761910.16
#Sta/Elev= 30
  3177.9  386.16  3336.7  380.23  3421.8  371.15  3461.6  367.84  3575.6  353.26
  3654.1  347.42  3960.4  337.54  4401.2  331.29  4634.4  333.36  4676.4  329.88
  4811.4  333.12  4986.8  333.66  4990.2  331.88  5011.9  322.85  5014.7  322.35
  5017.9  322.85  5032.3     323  5040.6  324.91  5045.7  331.24  5074.1  335.15
  5086.9  332.22  5146.2  337.46  5169.4  332.82  5187.4  338.36  5259.6  343.77
  5340.5  356.43  5375.6  362.36  5411.6   374.1  5416.8  370.55  5434.8  374.45
#Mann= 11 ,-1 , 0
  3177.9     .05       0  3421.8     .16       0  3461.6     .12       0
  3960.4     .05       0  4634.4     .16       0  4811.4     .05       0
  4990.2     .12       0  5011.9     .07       0  5017.9     .12       0
  5032.3     .16       0  5340.5     .12       0
Bank Sta=4986.8,5074.1
XS Rating Curve= 0 ,0
Exp/Cntr=0.3,0.1

Type RM Length L Ch R = 1 ,64061   ,843,843,843
BEGIN DESCRIPTION:
COON CREEK 83.0
END DESCRIPTION:
XS GIS Cut Line= 2
      3697574.04     10760345.76      3695920.42     10761491.57
#Sta/Elev= 30
  3312.3  377.76  3347.3  378.87  3418.9  374.87  3520.2  363.23  3529.8  363.39
  3699.2  351.75  3714.1   348.8  3761.7  344.27  3836.4  335.34  4051.2  334.46
  4339.6  330.32  4534.3  332.69  4770.1  332.73    4791  329.94  4799.8   332.3
  4805.9  331.09  4814.1  332.61  4978.8  333.89  4984.9  333.04  4996.8  323.69
  4999.5  323.19  5002.8  323.69  5017.9  325.09  5035.6  334.22  5072.1  333.83
  5136.9  338.08  5172.7  338.65  5238.3  344.72  5280.1  346.33  5324.1  350.32
#Mann= 7 ,-1 , 0
  3312.3     .16       0  3529.8     .12       0  3761.7     .05       0
  4996.8     .03       0  5002.8     .05       0  5017.9     .12       0
  5072.1     .16       0
Bank Sta=4978.8,5035.6
XS Rating Curve= 0 ,0
Exp/Cntr=0.3,0.1

Type RM Length L Ch R = 1 ,63218   ,161,161,161
BEGIN DESCRIPTION:
COON CREEK 82.0
END DESCRIPTION:
XS GIS Cut Line= 2
      3697156.08      10758588.6      3695864.29     10761421.47
#Sta/Elev= 30
  2906.7  362.43  2913.9  364.71  2955.2   360.9  3125.6  353.47  3443.2  338.63
    3549  336.36  3737.4  334.06  3760.8  333.85  4078.3  331.56  4184.2  330.58
  4607.6  330.46  4713.5  333.71  4732.9  333.97  4780.2  332.09    4907  329.77
  4935.5  323.46  4958.6  330.41  4964.1  326.62  5024.7  322.71  5027.4  322.21
  5030.7  322.71  5062.6  329.59  5136.9  331.14  5349.2   333.5  5757.4  355.75
  5849.6   355.3    5878  359.65  5924.2  364.88  5983.8  363.74  6020.2  365.69
#Mann= 18 ,-1 , 0
  2906.7     .08       0  2913.9     .05       0  2955.2     .08       0
  3125.6     .05       0  3443.2     .08       0    3549     .05       0
  3737.4     .08       0  3760.8     .05       0  4078.3     .08       0
  4184.2     .05       0  4607.6     .08       0  4713.5     .05       0
  4780.2     .08       0  5024.7     .07       0  5030.7     .08       0
  5136.9     .05       0    5878     .08       0  5983.8     .16       0
Bank Sta=4732.9,5349.2
XS Rating Curve= 0 ,0
Exp/Cntr=0.3,0.1

Type RM Length L Ch R = 1 ,63057   ,976,976,976
BEGIN DESCRIPTION:
COON CREEK 81.0
END DESCRIPTION:
XS GIS Cut Line= 3
      3697095.27     10758496.79      3696323.58     10760237.64
      3695764.38     10761403.66
#Sta/Elev= 30
  2990.5  371.88    3134  360.92  3239.6  350.76  3515.5  343.21  3669.2  335.85
  3726.3  334.81  3936.8  330.73  4042.5  330.98  4147.9  332.07  4739.7  334.46
  4780.4  333.47  4960.1  334.28  4982.8  325.72  5025.1  322.54  5027.8  322.04
  5031.1  322.54  5099.1  326.13  5169.6  335.03  5175.1  331.25  5248.5  331.21
  5312.6  332.22  5497.5  337.97    5526  338.62  5837.6  354.97  5995.5  369.69
  6059.7  372.99  6120.5  381.63  6137.6  376.79  6166.4  382.87  6187.9  381.86
#Mann= 20 ,-1 , 0
  2990.5     .08       0    3134     .05       0  3515.5     .08       0
  3669.2     .05       0  3726.3     .08       0  3936.8     .05       0
  4042.5     .08       0  4147.9     .05       0  4739.7     .16       0
  4780.4     .08       0  5025.1     .03       0  5031.1     .05       0
  5099.1     .08       0  5248.5     .16       0  5312.6     .05       0
  5497.5     .16       0    5526     .05       0  5995.5     .16       0
  6059.7     .05       0  6166.4     .08       0
Bank Sta=4960.1,5169.6
XS Rating Curve= 0 ,0
Exp/Cntr=0.3,0.1

Type RM Length L Ch R = 1 ,62081   ,534,534,534
BEGIN DESCRIPTION:
COON CREEK 80.0
END DESCRIPTION:
XS GIS Cut Line= 3
      3696699.58     10758910.22      3696149.61     10759410.19
      3694699.57     10760360.21
#Sta/Elev= 30
  4283.9  352.39  4333.5  349.28  4382.8  338.43  4411.2  334.93  4482.2  327.43
  4511.1  326.79    4914  327.12  4942.4  327.97  4956.5  330.64    4960  329.96
  4970.7  324.54  4988.7  322.81  4991.4  322.31  4994.7  322.81  5013.3  323.92
  5020.1  325.58  5023.8  328.83  5034.7  329.79  5075.9  329.73    5086  331.13
    5113   327.9  5329.5  327.76  5836.6  328.53  5966.3  330.39  6059.7  335.31
  6270.5  340.46    6414  349.51  6617.2  372.93  6680.7   377.9  6760.7  380.42
#Mann= 7 ,-1 , 0
  4283.9     .16       0  4511.1     .05       0    4960     .12       0
  4988.7     .07       0  4994.7     .12       0  5075.9     .16       0
  5329.5     .05       0
Bank Sta=4956.5,5034.7
XS Rating Curve= 0 ,0
Exp/Cntr=0.3,0.1

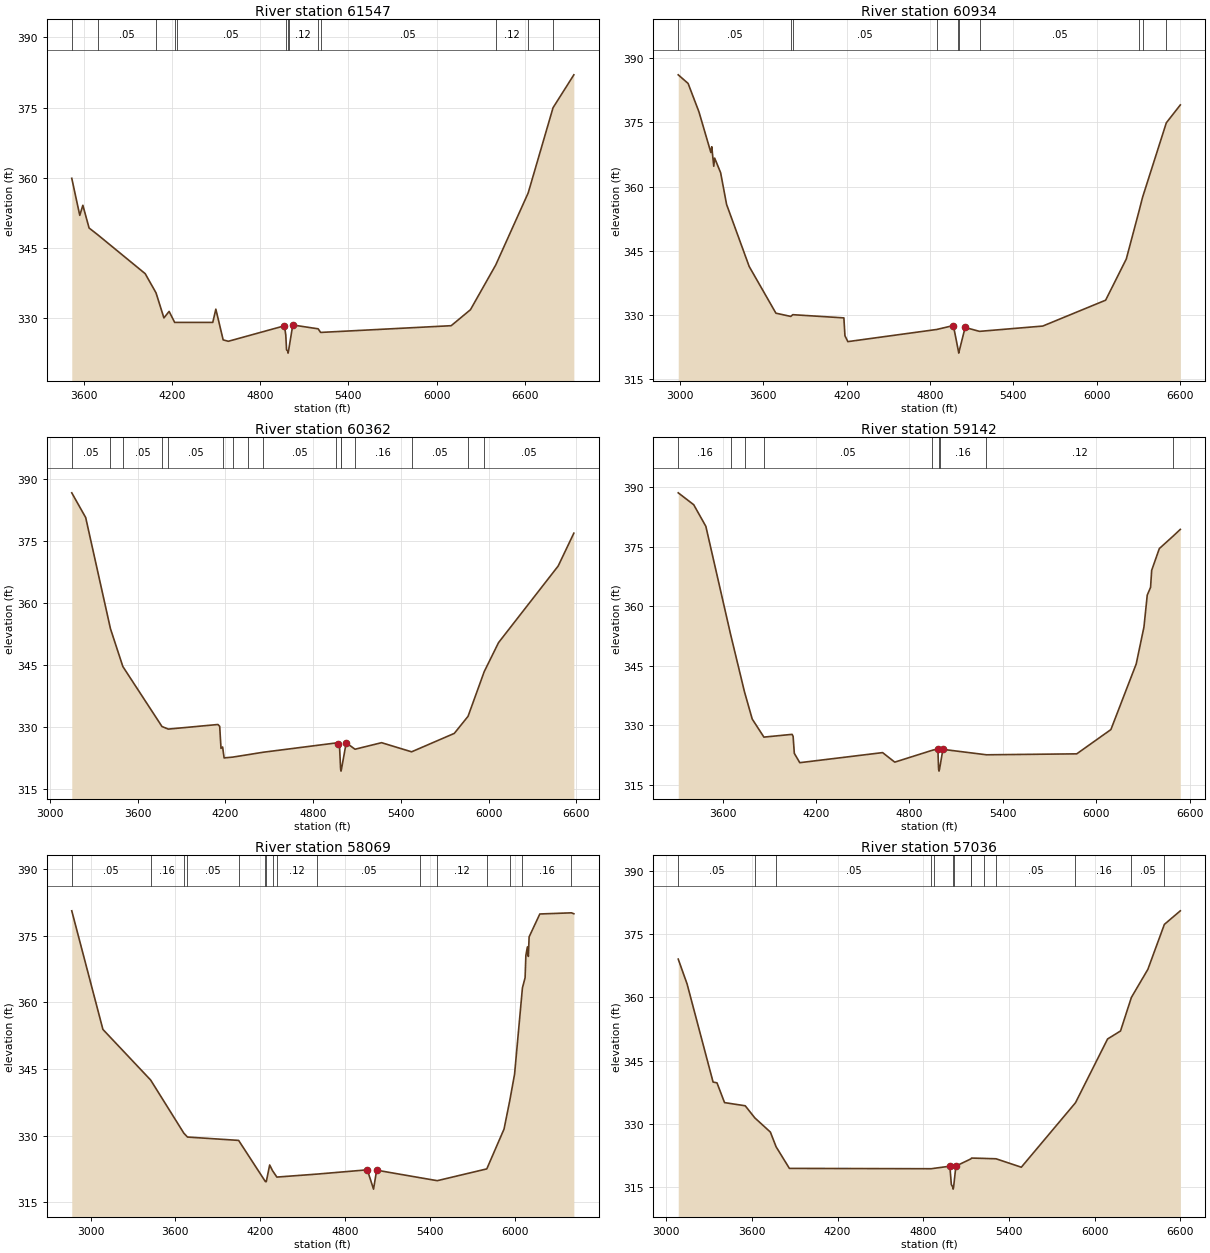
Type RM Length L Ch R = 1 ,61547   ,613,613,613
BEGIN DESCRIPTION:
COON CREEK 79.0
END DESCRIPTION:
XS GIS Cut Line= 3
      3697070.32     10757894.05      3695999.61     10758910.19
      3694399.59      10760010.2
#Sta/Elev= 30
  3517.1  359.92  3571.6  352.01  3592.6  354.16  3635.1   349.3  3693.9  347.86
    4017  339.55  4090.7  335.45  4144.4   330.1  4179.8  331.49  4217.6  329.14
  4232.4  329.14  4476.9  329.14  4497.9  331.97  4547.7  325.41  4582.9  325.11
  4965.1  328.42  4973.9  326.47  4979.3  323.25  4986.8  323.08  4989.5  322.58
  4992.8  323.08  5021.6  328.59  5194.4  327.77  5211.1     327    6100  328.44
    6231  331.85  6403.2  341.41  6623.9  356.78  6793.4     375  6934.9  382.02
#Mann= 13 ,-1 , 0
  3517.1     .16       0  3693.9     .05       0  4090.7     .12       0
  4217.6     .07       0  4232.4     .05       0  4973.9     .12       0
  4986.8     .07       0  4992.8     .12       0  5194.4     .16       0
  5211.1     .05       0  6403.2     .12       0  6623.9     .16       0
  6793.4     .05       0
Bank Sta=4965.1,5021.6
XS Rating Curve= 0 ,0
Exp/Cntr=0.3,0.1

Type RM Length L Ch R = 1 ,60934   ,572,572,572
BEGIN DESCRIPTION:
COON CREEK 78.0
END DESCRIPTION:
XS GIS Cut Line= 3
      3697099.65     10757460.16      3695549.61     10758760.19
      3694399.63     10759860.17
#Sta/Elev= 30
  2987.1  386.13  3058.1  384.12  3136.1  377.49    3222  367.97  3228.5  369.31
  3242.8  364.76  3249.3  366.66  3292.2  363.25  3335.1  355.83  3497.8  341.32
  3690.3  330.39  3797.5  329.63  3811.7  330.04  4179.5  329.29  4187.3  325.12
  4208.1  323.74  4847.6  326.58  4967.9   327.5  5003.9  321.55  5006.6  321.05
  5009.9  321.55  5052.4  327.05    5156  326.14  5611.3  327.38  6063.9  333.43
  6212.6  343.06  6306.3  354.51  6329.8   357.5  6500.8  374.91  6601.5  379.09
#Mann= 10 ,-1 , 0
  2987.1     .05       0  3797.5     .16       0  3811.7     .05       0
  4847.6     .16       0  5003.9     .07       0  5009.9     .16       0
    5156     .05       0  6306.3     .12       0  6329.8     .16       0
  6500.8     .05       0
Bank Sta=4967.9,5052.4
XS Rating Curve= 0 ,0
Exp/Cntr=0.3,0.1

Type RM Length L Ch R = 1 ,60362   ,1220,1220,1220
BEGIN DESCRIPTION:
COON CREEK 77.0
END DESCRIPTION:
XS GIS Cut Line= 3
      3696999.64     10757310.17      3695449.61     10758310.19
      3693999.65     10758960.17
#Sta/Elev= 30
  3148.7  386.76  3243.9  380.78  3413.3  353.89  3498.1  344.73  3765.7  330.22
  3808.8   329.6  4148.2  330.71  4160.3  330.27  4169.4  324.94  4180.4  325.27
  4190.5  322.63    4249  322.82    4351  323.39  4453.8  323.98  4958.9  326.26
  4970.6  326.02  4979.8  325.49  4987.3  319.93  4990.1  319.43  4993.3  319.93
  5025.4  326.27    5086  324.73  5267.3  326.31  5472.7   324.1  5764.7  328.56
  5858.8  332.69  5969.2  343.49  6067.3  350.52  6475.3  369.06  6582.3     377
#Mann= 16 ,-1 , 0
  3148.7     .05       0  3413.3     .16       0  3498.1     .05       0
  3765.7     .16       0  3808.8     .05       0  4180.4     .12       0
    4249     .16       0    4351     .12       0  4453.8     .05       0
  4958.9     .12       0  4987.3     .07       0  4993.3     .12       0
    5086     .16       0  5472.7     .05       0  5858.8     .16       0
  5969.2     .05       0
Bank Sta=4970.6,5025.4
XS Rating Curve= 0 ,0
Exp/Cntr=0.3,0.1

Type RM Length L Ch R = 1 ,59142   ,1073,1073,1073
BEGIN DESCRIPTION:
COON CREEK 75.0
END DESCRIPTION:
XS GIS Cut Line= 3
      3696099.58     10756160.22      3694999.61     10757460.19
      3693891.02     10758501.72
#Sta/Elev= 30
  3315.2   388.6  3414.6   385.6  3492.6  380.14  3651.2  352.93    3741  338.34
  3790.3  331.53  3865.4  326.97  4046.3  327.67  4052.9  327.16  4060.6  322.87
  4095.8  320.52  4627.5  323.06  4705.5  320.66  4946.4  323.65  4982.4  323.99
  4987.1  318.89  4989.9  318.39  4993.1  318.89  5014.8  323.88  5294.6  322.51
  5874.1  322.75  6093.4  328.87    6256  345.43  6305.8  354.76  6326.8  362.78
  6348.3  364.77  6355.2  369.03  6404.5  374.54  6493.1  377.68  6539.2  379.38
#Mann= 9 ,-1 , 0
  3315.2     .16       0  3651.2     .05       0    3741     .16       0
  3865.4     .05       0  4946.4     .16       0  4987.1     .07       0
  4993.1     .16       0  5294.6     .12       0  6493.1     .16       0
Bank Sta=4982.4,5014.8
XS Rating Curve= 0 ,0
Exp/Cntr=0.3,0.1

Type RM Length L Ch R = 1 ,58069   ,1033,1033,1033
BEGIN DESCRIPTION:
COON CREEK 73.0
END DESCRIPTION:
XS GIS Cut Line= 3
      3696016.72     10755507.93      3694389.13     10756705.84
       3693751.1      10758099.1
#Sta/Elev= 30
  2866.7  380.59  3087.1  353.92  3425.1  342.53  3659.6   330.6  3685.7  329.71
  4047.6  328.96  4237.3  319.68  4243.3  319.68  4267.3  323.43    4288  322.12
  4318.3  320.71  4602.2  321.38  4958.4  322.34  5002.4     318  5024.4  322.26
  5330.7  320.57  5453.5   319.9  5803.9  322.55    5926  331.51  5966.3  337.88
  6000.5  343.85  6056.2  363.28    6075  365.54  6080.5  370.55  6091.2  372.47
    6098  370.34  6103.5  374.73  6179.2  379.88    6403  380.14    6420  379.93
#Mann= 16 ,-1 , 0
  2866.7     .05       0  3425.1     .16       0  3659.6     .08       0
  3685.7     .05       0  4047.6     .12       0  4237.3     .03       0
  4243.3     .12       0    4288     .05       0  4318.3     .12       0
  4602.2     .05       0  5330.7     .16       0  5453.5     .12       0
  5803.9     .16       0  5966.3     .12       0  6056.2     .16       0
    6403     .05       0
Bank Sta=4958.4,5024.4
XS Rating Curve= 0 ,0
Exp/Cntr=0.3,0.1

Type RM Length L Ch R = 1 ,57036   ,452,452,452
BEGIN DESCRIPTION:
COON CREEK 72.0
END DESCRIPTION:
XS GIS Cut Line= 4
      3694973.97     10755871.48      3693411.44     10756782.96
      3693333.31     10757008.65      3693498.14     10758466.09
#Sta/Elev= 30
  3084.7  369.06  3146.7  363.16  3328.6  339.89    3356   339.7  3408.9  335.01
  3553.6  334.26    3621  331.38  3729.7  328.02  3769.9  324.52  3862.8   319.4
  4857.4  319.32  4878.5  319.43    4986  319.92  4996.5  315.56  5006.3  314.98
  5009.1  314.48  5012.3  314.98  5028.3  319.95  5133.6  321.66  5137.5  321.85
  5226.6  321.77  5309.3  321.68  5486.3  319.68  5865.5  334.98  6090.1  350.11
  6180.7  352.01  6256.6  359.96  6371.9  366.62  6487.6   377.3  6599.2  380.52
#Mann= 14 ,-1 , 0
  3084.7     .05       0    3621     .16       0  3769.9     .05       0
  4857.4     .16       0  4878.5     .05       0  5006.3     .03       0
  5012.3     .05       0  5133.6     .16       0  5137.5     .05       0
  5226.6     .16       0  5309.3     .05       0  5865.5     .16       0
  6256.6     .05       0  6487.6     .16       0
Bank Sta=4986,5028.3
XS Rating Curve= 0 ,0
Exp/Cntr=0.3,0.1

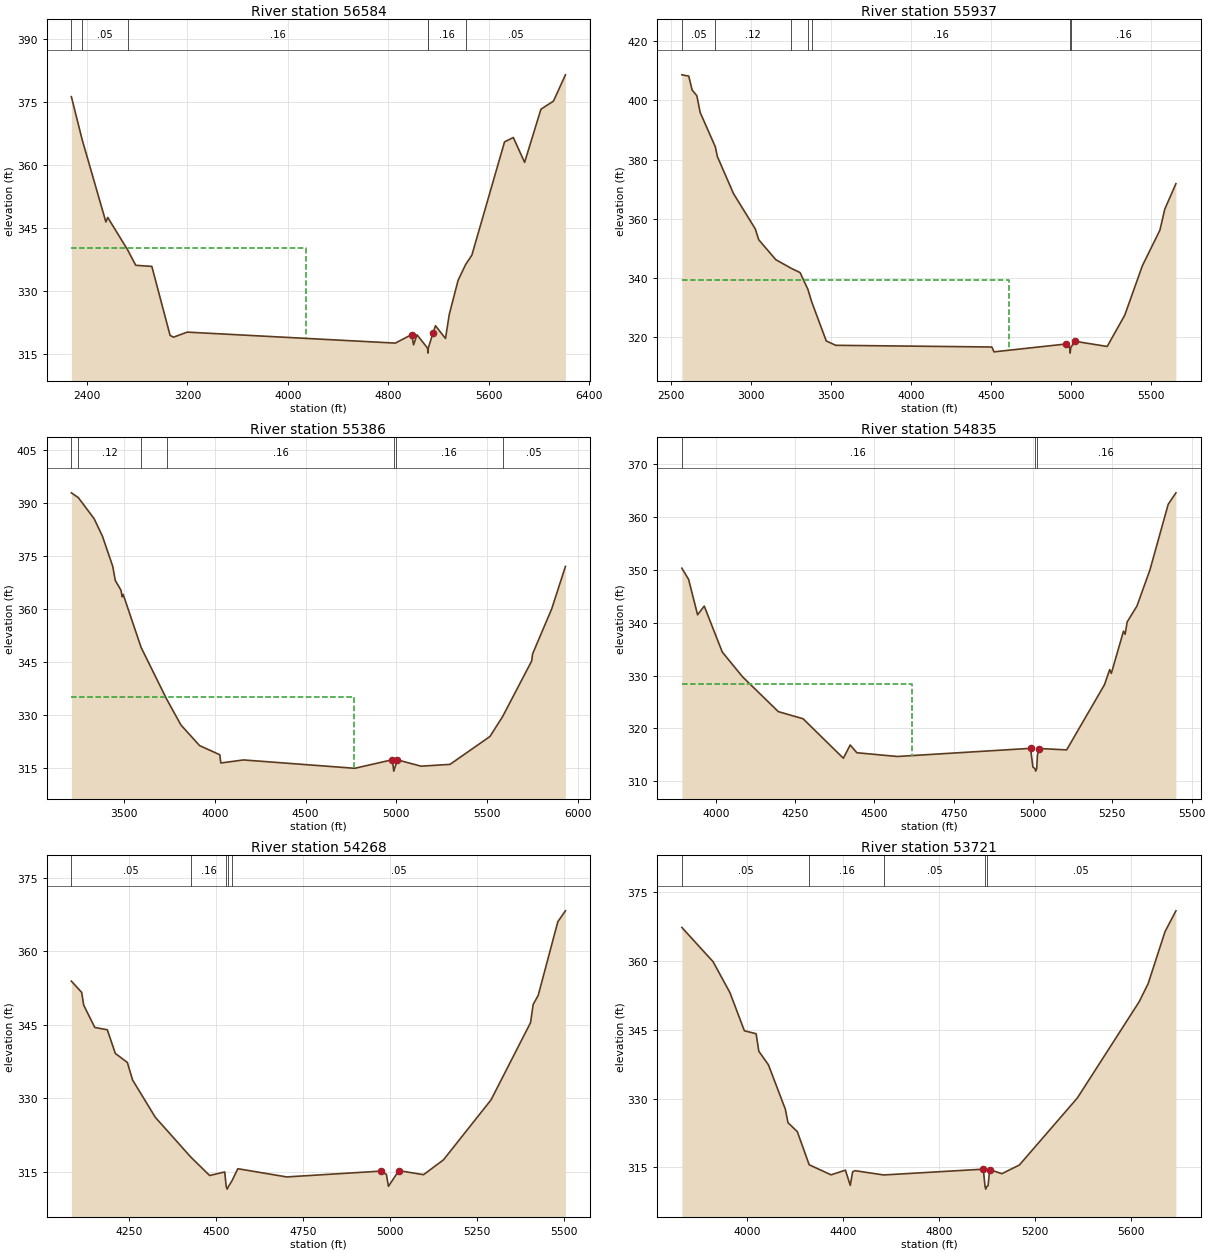
Type RM Length L Ch R = 1 ,56584   ,647,647,647
BEGIN DESCRIPTION:
COON CREEK 71.0
END DESCRIPTION:
XS GIS Cut Line= 4
      3695233.49     10755119.76      3693089.39     10756630.18
      3692933.14     10756725.67      3691804.65     10756725.67
#Sta/Elev= 30
  2276.3  376.32  2362.3  366.07  2551.2  346.45    2566  347.52  2723.7  339.83
    2789  336.11  2917.1  335.85  3062.4  319.41  3089.5  318.97  3198.5  320.18
  4855.8  317.56    4986  319.59  5001.4  317.15  5028.6  319.54  5112.6  316.37
  5115.4  315.17  5118.6  316.37  5155.6  319.95  5175.6   321.7  5255.6  318.67
  5285.6   324.4  5355.6  332.51  5415.6  336.28  5465.6  338.54  5725.6  365.53
  5795.6  366.59  5885.6  360.66  6015.6  373.33  6115.6  375.27  6210.6  381.53
#Mann= 6 ,-1 , 0
  2276.3     .16       0  2362.3     .05       0  2723.7     .16       0
  5112.6     .07       0  5118.6     .16       0  5415.6     .05       0
#XS Ineff= 2 , 0
         4144.89  340.32
Permanent Ineff=
       F       F
Bank Sta=4986,5155.6
XS Rating Curve= 0 ,0
Exp/Cntr=0.3,0.1

Type RM Length L Ch R = 1 ,55937   ,551,551,551
BEGIN DESCRIPTION:
COON CREEK 70.0
END DESCRIPTION:
XS GIS Cut Line= 3
      3694999.58     10754660.21      3692999.61     10756060.19
      3692349.59     10756060.19
#Sta/Elev= 30
  2566.6  408.65  2609.7  408.23  2630.7  403.55  2660.3   401.6  2681.2  395.95
  2776.2  384.33  2788.5  381.11  2889.6  368.58  3026.5  356.59  3047.4  352.99
  3154.7  346.24  3250.3  343.35  3306.4  341.89  3355.5  336.21  3377.9  332.18
  3470.3   318.8  3529.6  317.34  4506.1  316.77  4519.9  315.13  4971.3  317.79
  4994.4  316.61  4996.1   314.7  5000.5  316.65  5027.9  318.68  5227.9  316.95
  5337.9  327.52  5447.9  344.19  5557.9  356.23  5587.9  363.27  5657.9  371.89
#Mann= 7 ,-1 , 0
  2566.6     .05       0  2776.2     .12       0  3250.3     .16       0
  3355.5     .16       0  3377.9     .16       0  4996.1     .07       0
  5000.5     .16       0
#XS Ineff= 2 , 0
         4611.93  339.24
Permanent Ineff=
       F       F
Bank Sta=4971.3,5027.9
XS Rating Curve= 0 ,0
Exp/Cntr=0.3,0.1

Type RM Length L Ch R = 1 ,55386   ,551,551,551
BEGIN DESCRIPTION:
COON CREEK 69.0
END DESCRIPTION:
XS GIS Cut Line= 3
      3694649.63     10754660.18      3693099.61     10755510.19
      3692143.87     10755467.02
#Sta/Elev= 30
    3208  392.76  3246.3  391.41  3333.5  385.45  3379.1  380.54  3436.1     372
  3450.2     368  3481.7  365.23  3488.1  363.37  3493.8  364.06  3592.4   349.1
  3732.7  334.55  3812.5  327.15  3915.1  321.34  4026.5  318.76  4032.2  316.43
  4157.3  317.29  4770.5  314.93  4978.3  317.35  4985.6  314.13  4988.8  314.63
    4997  315.86  5005.8  317.31    5136  315.53  5296.1  316.04  5516.3  323.92
  5586.4  329.57  5746.5  345.26  5751.5  347.26  5856.7  359.96  5932.5  371.96
#Mann= 7 ,-1 , 0
    3208     .05       0  3246.3     .12       0  3592.4     .05       0
  3732.7     .16       0  4988.8     .07       0    4997     .16       0
  5586.4     .05       0
#XS Ineff= 2 , 0
         4765.91  334.98
Permanent Ineff=
       F       F
Bank Sta=4978.3,5005.8
XS Rating Curve= 0 ,0
Exp/Cntr=0.3,0.1

Type RM Length L Ch R = 1 ,54835   ,567,567,567
BEGIN DESCRIPTION:
COON CREEK 68.0
END DESCRIPTION:
XS GIS Cut Line= 3
      3693899.62     10754160.17      3693149.61     10754960.19
      3692699.59     10755060.19
#Sta/Elev= 30
  3892.8  350.32  3914.1   348.2  3942.4   341.5  3963.4  343.15  4020.1  334.47
    4084  329.78  4196.9  323.18    4275  321.83    4402  314.36  4423.5  316.87
  4444.5   315.4    4572  314.69    4992  316.23  4999.6  312.69  5005.6  312.42
  5008.4  311.92  5011.6  312.42  5013.7  314.94  5020.1   316.2  5105.9  315.94
    5225  328.25  5241.7  331.14  5246.8  330.42  5285.2  338.41  5290.3  337.82
  5296.7  340.15  5327.5  343.15  5368.4  349.98  5426.1  362.41  5450.4  364.58
#Mann= 3 ,-1 , 0
  3892.8     .16       0  5005.6     .03       0  5011.6     .16       0
#XS Ineff= 2 , 0
         4617.16  328.48
Permanent Ineff=
       F       F
Bank Sta=4992,5020.1
XS Rating Curve= 0 ,0
Exp/Cntr=0.3,0.1

Type RM Length L Ch R = 1 ,54268   ,547,547,547
BEGIN DESCRIPTION:
COON CREEK 67.0
END DESCRIPTION:
XS GIS Cut Line= 3
      3693799.58      10754010.2      3692999.61     10754460.19
      3692599.65     10754760.16
#Sta/Elev= 30
  4085.3  353.91  4114.9  351.61  4120.6  349.02  4152.5  344.45  4188.5  343.97
  4211.5  339.14  4245.9  337.31  4260.9  333.73  4326.2   326.1    4428  317.98
  4482.1  314.21  4525.4  314.94  4529.7  311.93  4532.5  311.43  4535.7  311.93
  4546.2  313.13    4563   315.6  4703.2  313.92  4973.5  315.11  4989.4  314.43
  4995.2     312    5025  315.21  5095.9  314.38  5153.1  317.41  5289.6  329.66
  5403.1  345.45  5410.4  349.13    5425     351  5481.3  366.05  5503.1  368.27
#Mann= 5 ,-1 , 0
  4085.3     .05       0    4428     .16       0  4529.7     .03       0
  4535.7     .16       0  4546.2     .05       0
Bank Sta=4973.5,5025
XS Rating Curve= 0 ,0
Exp/Cntr=0.3,0.1

Type RM Length L Ch R = 1 ,53721   ,599,599,599
BEGIN DESCRIPTION:
COON CREEK 66.0
END DESCRIPTION:
XS GIS Cut Line= 3
      3693949.59     10753960.19      3692699.61     10754060.19
      3692299.61     10754760.19
#Sta/Elev= 30
  3727.3  367.32  3857.7  359.84  3927.9   353.1  3988.1  344.79    4037  344.15
  4048.3  340.33  4088.4  337.36  4158.7  327.71  4169.9  324.76  4208.8   322.8
  4258.3  315.58  4349.3  313.39  4409.5   314.4  4429.5  311.09  4439.5  314.05
  4449.6  314.29  4568.8  313.36  4984.2  314.62  4991.9  310.77  4994.7  310.27
  4997.9  310.77  5004.3  311.02  5010.8  314.52  5061.9  313.64  5134.6  315.52
  5376.5  330.14  5634.2  351.11  5671.6  355.05  5742.1   366.4  5787.5  370.94
#Mann= 5 ,-1 , 0
  3727.3     .05       0  4258.3     .16       0  4568.8     .05       0
  4991.9     .03       0  4997.9     .05       0
Bank Sta=4984.2,5010.8
XS Rating Curve= 0 ,0
Exp/Cntr=0.3,0.1

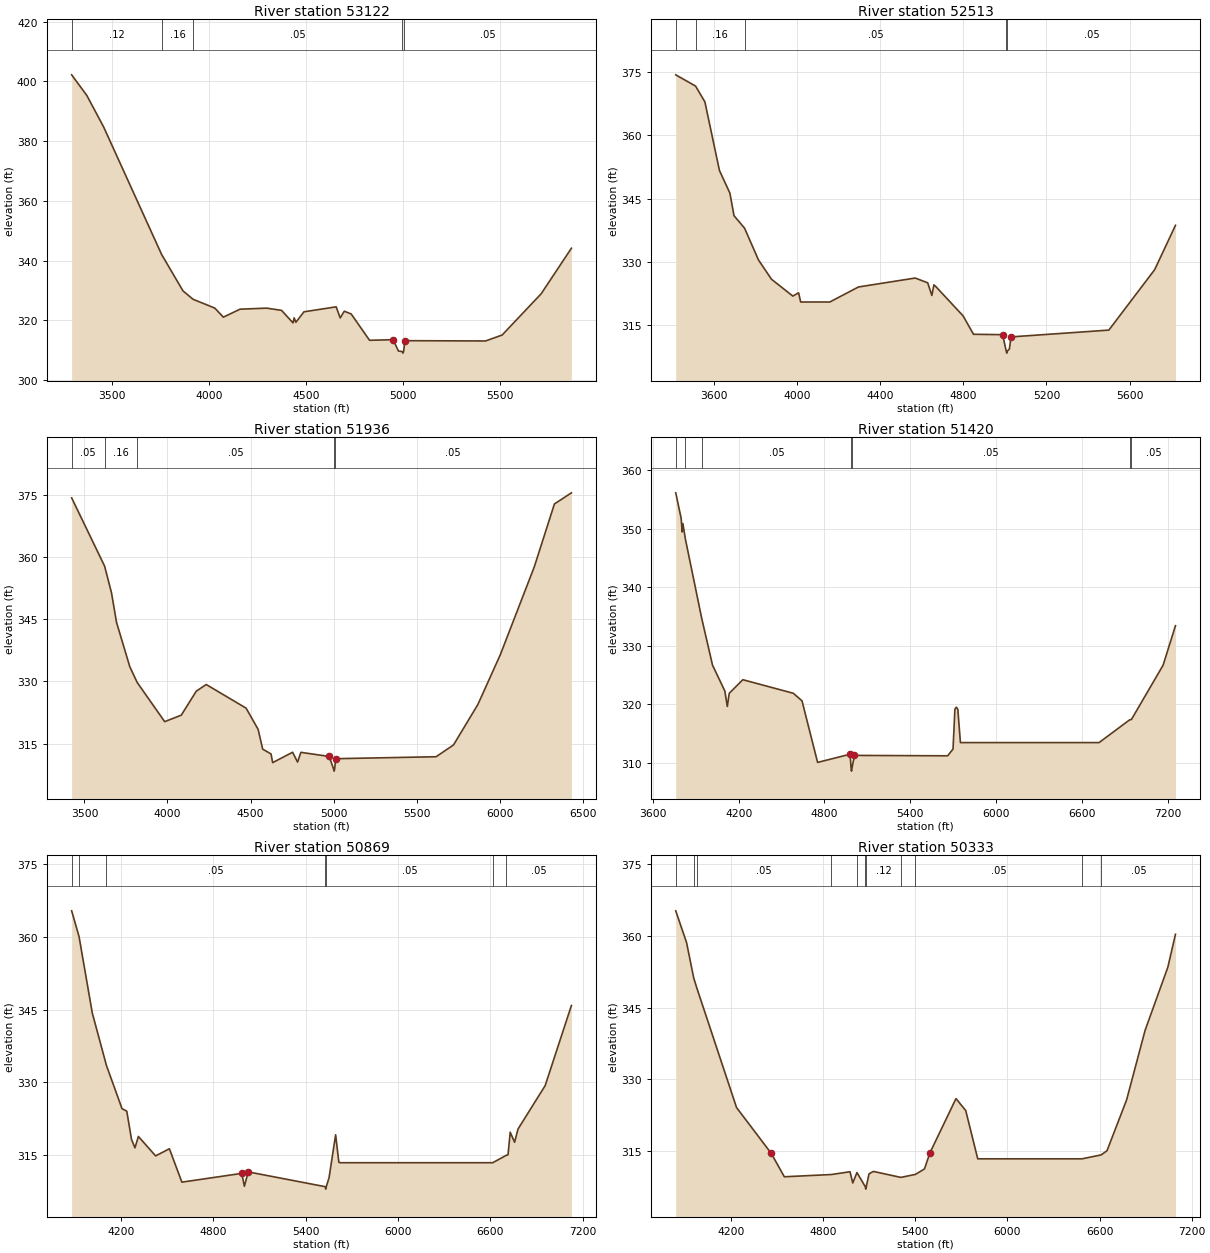
Type RM Length L Ch R = 1 ,53122   ,609,609,609
BEGIN DESCRIPTION:
COON CREEK 65.0
END DESCRIPTION:
XS GIS Cut Line= 3
      3693999.63     10752710.17      3692599.61     10753710.19
      3692299.61     10754510.19
#Sta/Elev= 30
  3292.2  402.22  3370.9  395.26  3456.9  384.78  3755.8  342.05  3866.1  329.84
  3918.3  327.03  4029.6  324.11  4073.8  321.07  4159.8  323.73  4296.2  324.09
  4373.7  323.34  4432.7  319.14  4438.8  320.83  4447.4  319.35  4489.2  322.86
  4655.1  324.52    4676  320.81  4696.9  323.06  4732.5  322.13  4827.1  313.32
  4948.8  313.51  4975.8  309.73  4996.2  309.52  4998.9  309.02  5002.2  309.52
  5009.6  313.19  5424.8  313.09  5510.2  315.08  5711.3   328.9  5867.1  344.15
#Mann= 5 ,-1 , 0
  3292.2     .12       0  3755.8     .16       0  3918.3     .05       0
  4996.2     .03       0  5002.2     .05       0
Bank Sta=4948.8,5009.6
XS Rating Curve= 0 ,0
Exp/Cntr=0.3,0.1

Type RM Length L Ch R = 1 ,52513   ,577,577,577
BEGIN DESCRIPTION:
COON CREEK 64.0
END DESCRIPTION:
XS GIS Cut Line= 3
      3692099.61     10752060.18      3692199.61     10753660.19
      3692249.61      10754460.2
#Sta/Elev= 30
  3416.1  374.28  3511.6  371.62  3556.4  367.88  3626.5  351.63  3676.6   346.3
  3696.6  340.94  3747.3  337.99  3814.4  330.45    3877  325.89  3979.7  321.91
  4007.3  322.69  4017.3  320.51  4157.5  320.51  4295.3  324.07  4568.3  326.18
  4628.5  325.06  4648.5  322.07  4658.5  324.57  4668.5  324.12  4798.8  317.23
  4848.9  312.87  4989.2  312.78  5006.2  308.91    5009  308.41  5012.2  308.91
  5021.7  309.39  5029.2  312.25  5500.2  313.86  5720.6  328.16  5820.8  338.66
#Mann= 5 ,-1 , 0
  3416.1     .05       0  3511.6     .16       0  3747.3     .05       0
  5006.2     .03       0  5012.2     .05       0
Bank Sta=4989.2,5029.2
XS Rating Curve= 0 ,0
Exp/Cntr=0.3,0.1

Type RM Length L Ch R = 1 ,51936   ,516,516,516
BEGIN DESCRIPTION:
COON CREEK 63.0
END DESCRIPTION:
XS GIS Cut Line= 3
      3691699.61     10752010.21      3691649.61     10753610.19
      3692299.63     10754860.23
#Sta/Elev= 30
  3422.8  374.26  3621.2   357.8  3662.9  351.34  3692.9  344.25  3772.9  333.55
  3817.1  329.76    3983  320.28  4083.1  321.85  4173.1  327.62  4233.2  329.24
  4473.3  323.54  4545.8  318.43  4573.3  313.65  4623.4   312.5  4633.4   310.4
  4753.4   312.9  4783.4  310.53  4803.4  312.88  4973.5  311.89  5000.5  308.85
  5003.3  308.35  5006.5  308.85  5013.5  311.35  5617.5  311.82  5722.4  314.66
  5868.9   324.4  6004.1   336.4  6208.8   357.6  6330.1  372.78  6432.5  375.47
#Mann= 5 ,-1 , 0
  3422.8     .05       0  3621.2     .16       0  3817.1     .05       0
  5000.5     .03       0  5006.5     .05       0
Bank Sta=4973.5,5013.5
XS Rating Curve= 0 ,0
Exp/Cntr=0.3,0.1

Type RM Length L Ch R = 1 ,51420   ,551,551,551
BEGIN DESCRIPTION:
COON CREEK 62.0
END DESCRIPTION:
XS GIS Cut Line= 2
      3691433.48     10752182.75      3690769.41      10755615.1
#Sta/Elev= 30
  3759.3  356.14  3797.4  351.77  3804.3  349.45  3809.4  350.88  3827.2  348.19
  3941.5  334.62  4016.5  326.67    4103  322.23  4120.1  319.59  4133.6  321.84
  4228.7  324.17  4581.7  321.85  4642.8  320.55  4751.7  310.02  4978.9  311.42
  4986.1  309.03  4988.9  308.53  4992.1  309.03  5009.5  311.22  5661.4  311.15
  5699.1   312.3  5712.3  319.13  5722.5  319.47  5732.7  319.09  5750.9  313.41
  6720.7  313.41  6935.1  317.31  6947.1  317.36  7168.8  326.66  7255.3  333.41
#Mann= 7 ,-1 , 0
  3759.3     .05       0  3827.2     .16       0  3941.5     .05       0
  4986.1     .03       0  4992.1     .05       0  6935.1     .16       0
  6947.1     .05       0
Bank Sta=4978.9,5009.5
XS Rating Curve= 0 ,0
Exp/Cntr=0.3,0.1

Type RM Length L Ch R = 1 ,50869   ,536,536,536
BEGIN DESCRIPTION:
COON CREEK 61.0
END DESCRIPTION:
XS GIS Cut Line= 3
      3691199.62     10752210.17      3690699.61     10753210.19
       3689099.6      10754610.2
#Sta/Elev= 30
  3881.9   365.4  3929.8   360.1  4016.1  344.28  4107.7  333.49  4208.9  324.57
  4239.7  324.05  4270.4  318.24  4292.8  316.48  4315.2  318.83    4427  314.82
  4516.4  316.29  4597.5   309.4    4986  311.21  5003.3  308.55    5028  311.52
  5528.5  308.46  5531.2  307.96  5534.5  308.46  5552.8  310.31  5595.5  319.18
  5616.4  313.51    5624  313.41  6615.1  313.41  6702.6  314.93  6714.5  315.05
  6728.8  319.71  6757.3  317.63  6779.1  320.34  6955.6  329.32    7126  345.86
#Mann= 7 ,-1 , 0
  3881.9     .05       0  3929.8     .16       0  4107.7     .05       0
  5528.5     .03       0  5534.5     .05       0  6615.1     .07       0
  6702.6     .05       0
Bank Sta=4986,5028
XS Rating Curve= 0 ,0
Exp/Cntr=0.3,0.1

Type RM Length L Ch R = 1 ,50333   ,530,530,530
BEGIN DESCRIPTION:
COON CREEK 60.0
END DESCRIPTION:
XS GIS Cut Line= 3
       3691149.6      10752110.2      3690349.61     10752910.19
      3688899.58     10754460.22
#Sta/Elev= 30
  3840.6  365.21  3911.3  358.57  3957.5  351.22  3976.4  349.25  4236.6  324.12
  4462.8  314.54  4547.7  309.66  4854.5  310.13  4975.4  310.71  4993.2  308.37
  5020.5  310.54  5075.2  307.58    5078  307.08  5081.2  307.58  5099.2  310.28
  5127.5  310.78  5306.1  309.53  5400.8  310.15  5460.2   311.3  5495.4  314.64
  5665.4  325.99  5728.9  323.49    5807  313.41  6486.3  313.41  6610.7  314.23
  6648.7  315.11  6776.2  325.71  6896.4  340.22  7044.9  353.45  7094.5  360.32
#Mann= 11 ,-1 , 0
  3840.6     .05       0  3957.5     .16       0  3976.4     .05       0
  4854.5     .16       0  5020.5     .12       0  5075.2     .07       0
  5081.2     .12       0  5306.1     .16       0  5400.8     .05       0
  6486.3     .07       0  6610.7     .05       0
Bank Sta=4462.8,5495.4
XS Rating Curve= 0 ,0
Exp/Cntr=0.3,0.1