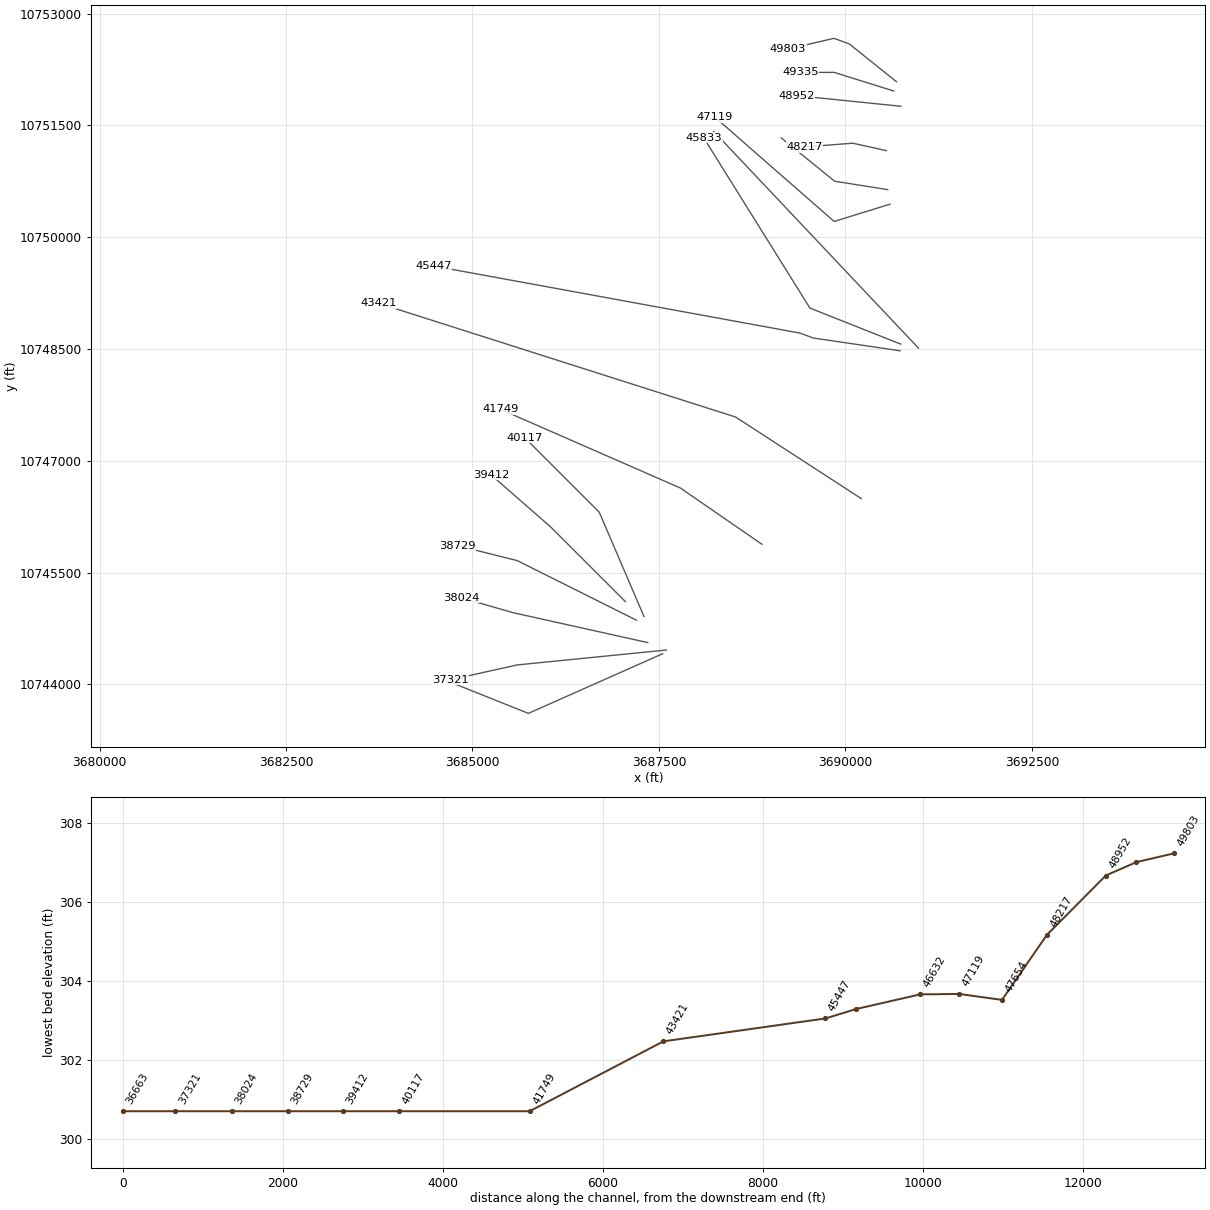
HEC-RAS study COON CREEK.prj: COON CREEK Base Level Engineering

--- COON CREEK.g01 (geometry) --- (continued)

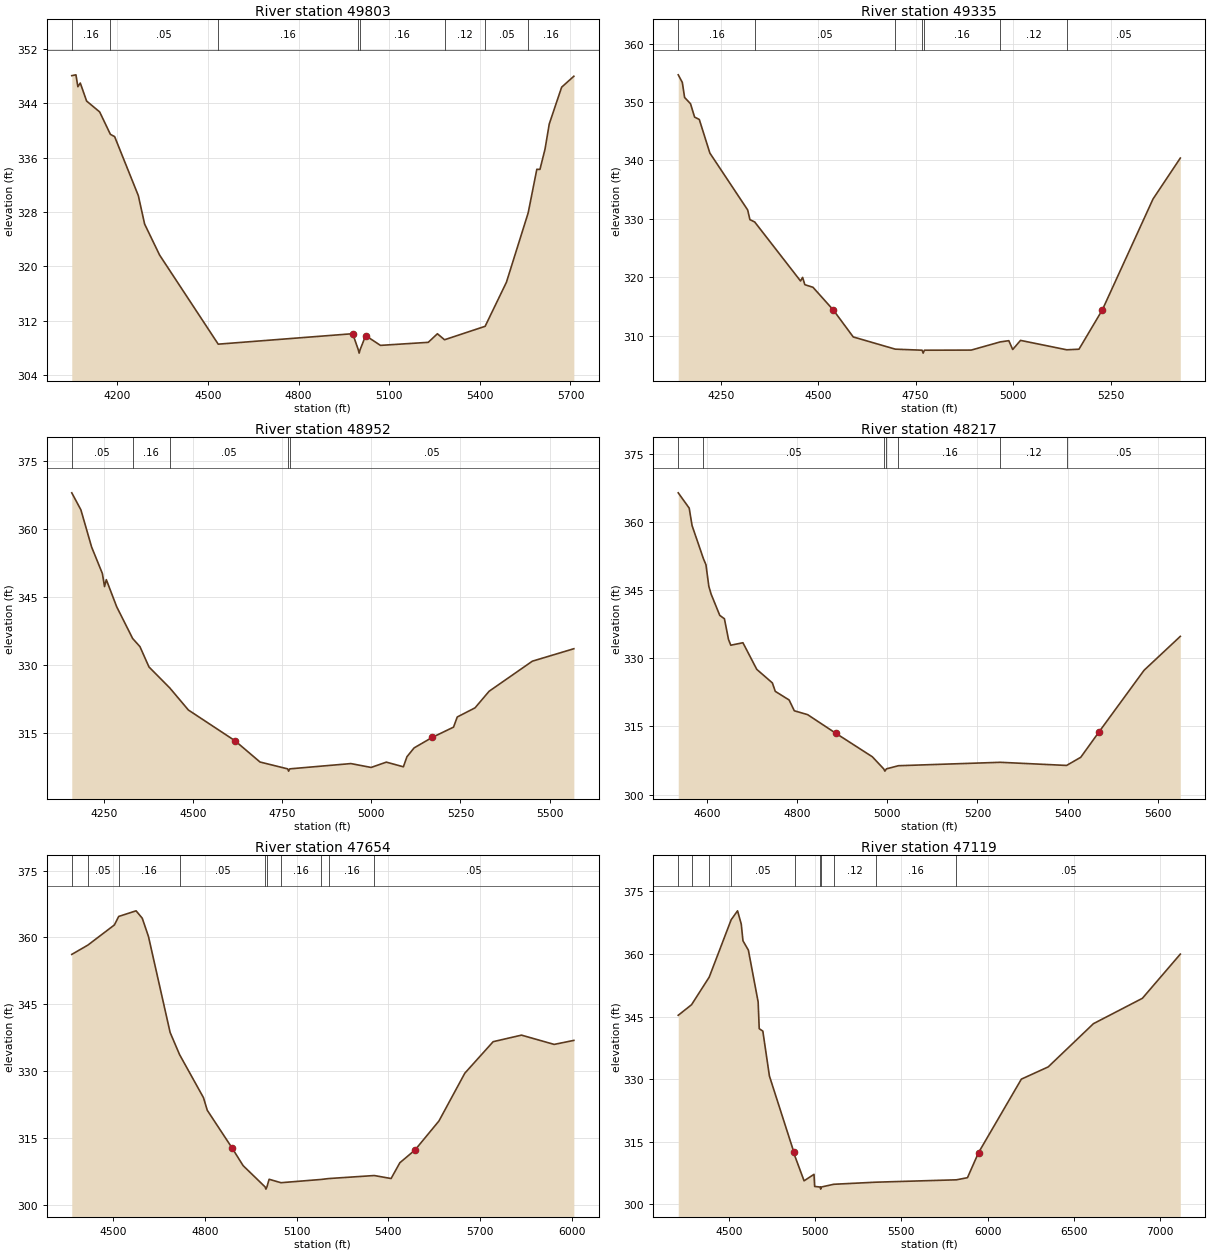
Type RM Length L Ch R = 1 ,49803   ,468,468,468
BEGIN DESCRIPTION:
COON CREEK 59.0
END DESCRIPTION:
XS GIS Cut Line= 4
      3690684.28     10752085.63      3690050.62     10752593.42
      3689846.63     10752667.21       3689230.3     10752523.97
#Sta/Elev= 30
  4049.5  348.09  4063.3  348.21  4069.7  346.46  4077.7     347  4098.6  344.35
  4141.8  342.75  4177.3  339.45  4191.4  339.11  4269.8  330.42  4290.6  326.24
  4340.2  321.67  4534.2  308.55  4979.3  310.09  4997.8  307.73  5000.6  307.23
  5003.8  307.73  5022.1  309.81  5071.2  308.37  5229.4  308.82  5259.6  310.08
  5283.3   309.2  5417.6  311.18  5488.1  317.67  5560.1  327.89  5588.7   334.3
    5599  334.28  5615.9  337.29  5629.8  340.97  5670.8  346.39  5711.2     348
#Mann= 8 ,-1 , 0
  4049.5     .16       0  4177.3     .05       0  4534.2     .16       0
  4997.8     .07       0  5003.8     .16       0  5283.3     .12       0
  5417.6     .05       0  5560.1     .16       0
Bank Sta=4979.3,5022.1
XS Rating Curve= 0 ,0
Exp/Cntr=0.3,0.1

Type RM Length L Ch R = 1 ,49335   ,383,383,383
BEGIN DESCRIPTION:
COON CREEK 58.0
END DESCRIPTION:
XS GIS Cut Line= 3
      3690649.65     10751960.17      3689849.61     10752210.19
      3689399.61     10752210.19
#Sta/Elev= 30
  4140.9  354.66  4151.4  353.36  4157.2  350.79  4172.4  349.71  4182.9  347.42
  4194.9  347.02  4222.1  341.26  4319.1  331.52  4324.8  329.87  4337.2  329.46
  4454.7  319.36    4460  319.98  4465.7  318.73  4486.7  318.28  4539.1  314.37
  4589.9  309.78  4697.8  307.69  4766.6  307.51  4769.3  307.01  4772.6  307.51
  4892.7  307.53  4967.1  308.93  4989.1  309.14  4999.1  307.63  5019.1  309.19
  5137.7  307.58  5169.1  307.68  5229.1  314.42  5359.1   333.4  5429.1  340.41
#Mann= 7 ,-1 , 0
  4140.9     .16       0  4337.2     .05       0  4697.8     .16       0
  4766.6     .07       0  4772.6     .16       0  4967.1     .12       0
  5137.7     .05       0
Bank Sta=4539.1,5229.1
XS Rating Curve= 0 ,0
Exp/Cntr=0.3,0.1

Type RM Length L Ch R = 1 ,48952   ,735,735,735
BEGIN DESCRIPTION:
COON CREEK 57.0
END DESCRIPTION:
XS GIS Cut Line= 2
      3690745.05     10751755.75      3689343.84     10751898.91
#Sta/Elev= 30
  4159.6   367.9  4185.2  364.16  4215.3  355.97  4245.5  350.14  4251.5  347.28
  4256.5   348.8  4285.7  342.82  4330.5  335.84  4350.9  334.06  4376.2  329.59
  4434.7  324.96  4486.7  320.12  4617.4  313.36  4687.8  308.67  4765.2  307.17
  4767.9  306.67  4771.2  307.17  4942.6  308.33  4999.4  307.48  5042.1  308.65
  5089.9  307.62  5099.9  309.84    5120  311.78  5170.3  314.07  5230.6  316.35
    5241  318.58  5290.9  320.59  5330.4  324.24  5451.7  330.86  5568.1   333.6
#Mann= 5 ,-1 , 0
  4159.6     .05       0  4330.5     .16       0  4434.7     .05       0
  4765.2     .03       0  4771.2     .05       0
Bank Sta=4617.4,5170.3
XS Rating Curve= 0 ,0
Exp/Cntr=0.3,0.1

Type RM Length L Ch R = 1 ,48217   ,563,563,563
BEGIN DESCRIPTION:
COON CREEK 56.0
END DESCRIPTION:
XS GIS Cut Line= 3
      3690549.56      10751160.2      3690099.61     10751260.19
      3689449.56     10751210.18
#Sta/Elev= 30
  4536.8  366.36  4561.1     363  4567.5  359.15  4592.7  351.86  4598.2  350.57
  4604.6  345.82  4609.7  344.09  4628.9  339.41  4639.2  338.67  4648.2  334.13
  4653.3  332.85  4680.2   333.4  4710.9  327.54  4745.5  324.56  4751.9  322.71
  4782.6  320.81  4794.1  318.44  4823.6  317.59  4886.3  313.48    4967  308.33
  4992.2  305.67  4994.9  305.17  4998.2  305.67    5025  306.36  5250.9  307.11
  5397.6  306.42    5429  308.21  5469.1  313.74  5569.4  327.35  5649.7   334.8
#Mann= 7 ,-1 , 0
  4536.8     .12       0  4592.7     .05       0  4992.2     .03       0
  4998.2     .05       0    5025     .16       0  5250.9     .12       0
  5397.6     .05       0
Bank Sta=4886.3,5469.1
XS Rating Curve= 0 ,0
Exp/Cntr=0.3,0.1

Type RM Length L Ch R = 1 ,47654   ,535,535,535
BEGIN DESCRIPTION:
COON CREEK 55.0
END DESCRIPTION:
XS GIS Cut Line= 3
      3690567.51     10750637.26      3689855.74     10750750.11
      3689139.61     10751331.69
#Sta/Elev= 30
    4364  356.18  4416.7  358.27  4503.6   362.8  4517.6   364.7  4574.5  365.96
  4594.7   364.3    4615  360.21  4685.9  338.67  4716.9  333.69    4795  324.05
  4807.4  321.22  4888.4  312.78  4924.7   308.8  4996.7  304.02  4999.5  303.52
  5002.7  304.02  5009.9  305.73  5048.8  304.96    5180  305.69  5204.4  305.89
    5354  306.57  5409.1   305.9  5437.8  309.44  5487.4   312.3  5565.7  318.81
  5650.4  329.53  5743.1   336.6  5835.8  338.07  5942.8  335.99  6007.2  336.89
#Mann= 10 ,-1 , 0
    4364     .16       0  4416.7     .05       0  4517.6     .16       0
  4716.9     .05       0  4996.7     .03       0  5002.7     .05       0
  5048.8     .16       0    5180     .12       0  5204.4     .16       0
    5354     .05       0
Bank Sta=4888.4,5487.4
XS Rating Curve= 0 ,0
Exp/Cntr=0.3,0.1

Type RM Length L Ch R = 1 ,47119   ,487,487,487
BEGIN DESCRIPTION:
COON CREEK 54.0
END DESCRIPTION:
XS GIS Cut Line= 3
       3690597.9     10750441.94      3689849.61     10750210.19
       3688249.6      10751610.2
#Sta/Elev= 30
  4206.7   345.3  4283.9  347.84  4386.3  354.45  4513.4  368.18  4550.4  370.32
    4572  367.12  4581.8  363.15  4613.2   360.9  4669.8  348.49    4676  342.09
  4696.9  341.51  4735.1  330.76  4875.9  312.64    4882  311.66  4935.9  305.66
  4993.4  307.21  4997.2  304.31  5029.3  304.17    5032  303.67  5035.3  304.17
  5107.6  304.83  5350.1  305.33  5818.8   305.9  5882.7  306.41  5946.8  312.41
    6195  330.01  6350.6  332.94  6612.6  343.29  6896.4  349.37  7116.1  359.95
#Mann= 10 ,-1 , 0
  4206.7     .16       0  4283.9     .05       0  4386.3     .16       0
  4513.4     .05       0    4882     .16       0  5029.3     .07       0
  5035.3     .16       0  5107.6     .12       0  5350.1     .16       0
  5818.8     .05       0
Bank Sta=4875.9,5946.8
XS Rating Curve= 0 ,0
Exp/Cntr=0.3,0.1

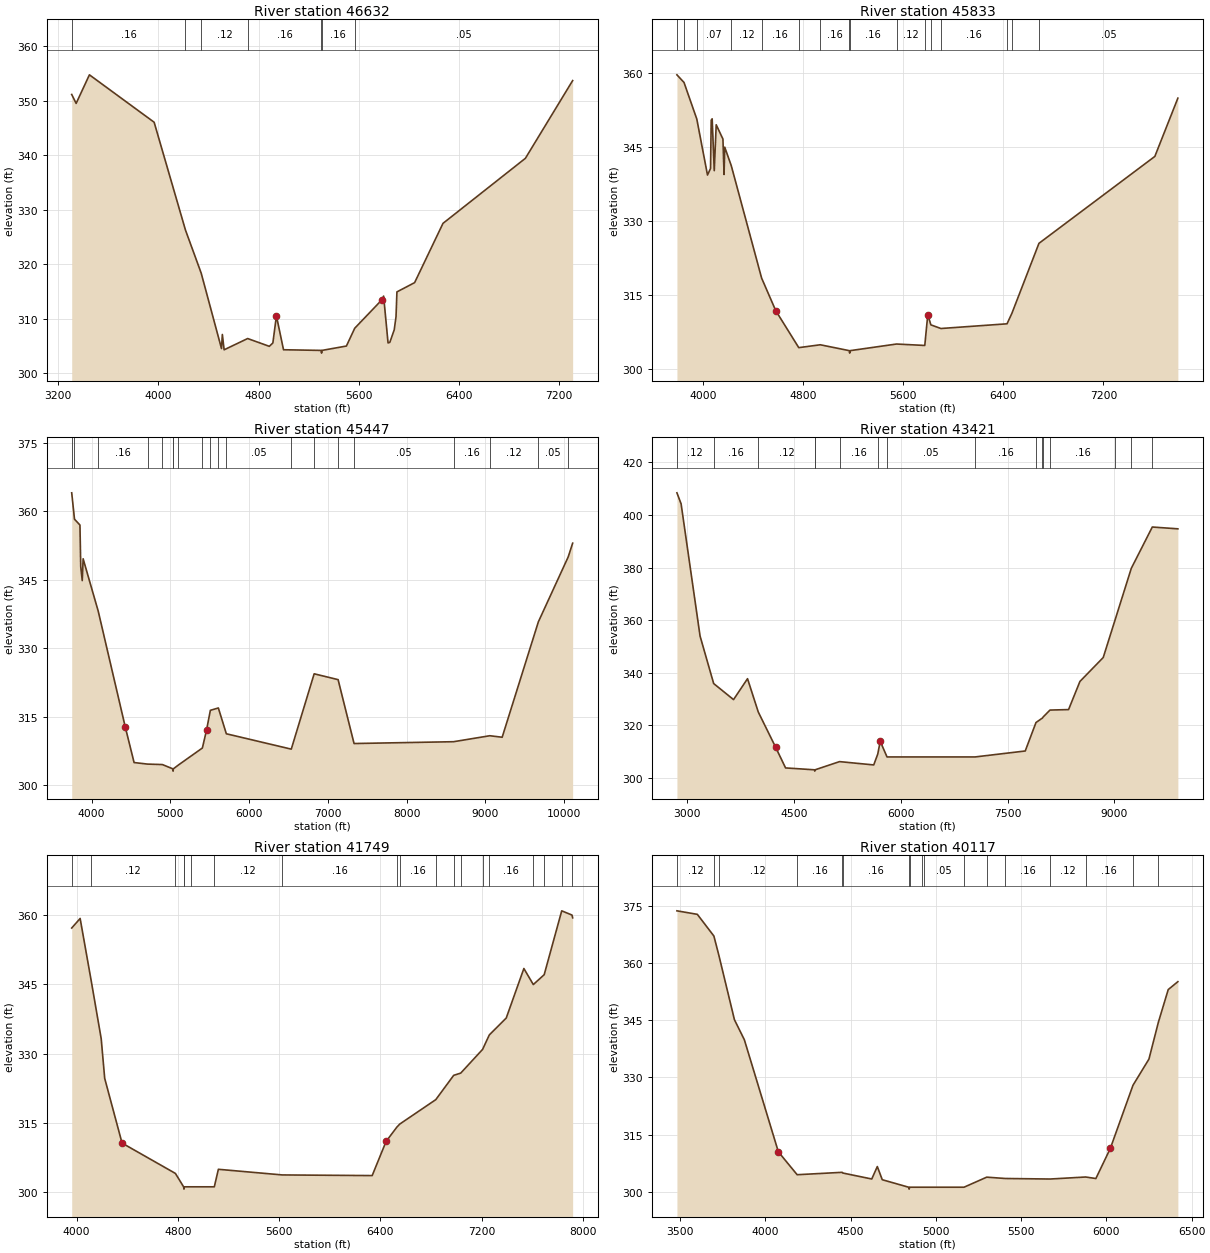
Type RM Length L Ch R = 1 ,46632   ,799,799,799
BEGIN DESCRIPTION:
COON CREEK 53.0
END DESCRIPTION:
XS GIS Cut Line= 2
      3690980.03     10748510.61      3688234.79     10751418.61
#Sta/Elev= 30
  3308.8  351.18  3344.2  349.54  3450.2  354.79  3966.8  346.08  4216.8  326.28
  4342.6  318.35  4504.5   304.5  4511.4  307.09  4525.5  304.27  4713.4  306.34
  4886.4  304.91  4914.7  305.53    4943   310.5  4999.7  304.28  5300.5  304.16
  5303.3  303.66  5306.5  304.16  5501.7  304.96  5568.1  308.23  5784.5  313.44
  5798.7  314.14  5834.3  305.53  5848.4  305.64  5883.6  307.95  5897.8  310.35
  5905.1  314.91  6046.3  316.61  6272.8   327.5  6930.6  339.45  7307.9  353.73
#Mann= 7 ,-1 , 0
  3308.8     .16       0  4216.8     .05       0  4342.6     .12       0
  4713.4     .16       0  5300.5     .07       0  5306.5     .16       0
  5568.1     .05       0
Bank Sta=4943,5784.5
XS Rating Curve= 0 ,0
Exp/Cntr=0.3,0.1

Type RM Length L Ch R = 1 ,45833   ,386,386,386
BEGIN DESCRIPTION:
COON CREEK 52.0
END DESCRIPTION:
XS GIS Cut Line= 3
      3690741.33     10748564.88       3689524.7     10749047.97
      3688099.34     10751334.45
#Sta/Elev= 30
  3791.8  359.58  3848.5  358.03  3950.7  350.63  4036.1  339.31  4060.4  340.63
  4065.8   350.4  4073.4  350.68  4090.1   340.2  4105.7  349.48  4159.5  346.59
  4168.4  339.42  4173.8  344.95  4226.3  341.19  4468.6  318.47  4581.5  311.88
  4765.5   304.4  4937.5  304.98  5169.4  303.79  5172.2  303.29  5175.4  303.79
  5546.8  305.13  5772.6  304.84  5796.6  311.09  5821.1  309.01  5901.5  308.27
  6429.9  309.22  6468.6  311.33  6685.1   325.5  7611.3  343.08  7795.2  354.86
#Mann= 16 ,-1 , 0
  3791.8     .16       0  3848.5     .12       0  3950.7     .07       0
  4226.3     .12       0  4468.6     .16       0  4765.5     .08       0
  4937.5     .16       0  5169.4     .07       0  5175.4     .16       0
  5546.8     .12       0  5772.6     .16       0  5821.1     .12       0
  5901.5     .16       0  6429.9     .12       0  6468.6     .16       0
  6685.1     .05       0
Bank Sta=4581.5,5796.6
XS Rating Curve= 0 ,0
Exp/Cntr=0.3,0.1

Type RM Length L Ch R = 1 ,45447   ,2026,2026,2026
BEGIN DESCRIPTION:
Mapping XS 663b76cd
END DESCRIPTION:
XS GIS Cut Line= 4
      3690733.09      10748475.1       3689568.5     10748646.71
      3689394.89     10748711.82       3684479.5     10749612.43
#Sta/Elev= 30
  3747.3  364.07  3782.6  358.29  3851.9  357.01    3862  347.86  3881.1  344.82
  3892.3  349.61  4084.5  338.09  4428.1  312.67  4539.2  304.93  4709.9  304.59
  4898.3  304.49  5031.7  303.55  5034.5  303.05  5037.7  303.55  5101.8  304.39
  5406.3  308.12  5458.7  312.02  5507.6  316.38    5609   316.9  5710.3  311.24
  6534.8  307.87  6825.3  324.39  7129.3  323.11    7332   309.1  8595.8   309.5
  9055.1  310.81  9212.3  310.48  9671.3  335.76 10051.2  350.04 10107.1  353.03
#Mann= 20 ,-1 , 0
  3747.3     .16       0  3782.6     .07       0  4084.5     .16       0
  4709.9     .12       0  4898.3     .16       0  5031.7     .07       0
  5037.7     .16       0  5101.8     .05       0  5406.3     .16       0
  5507.6     .12       0    5609     .16       0  5710.3     .05       0
  6534.8     .16       0  6825.3     .12       0  7129.3     .16       0
    7332     .05       0  8595.8     .16       0  9055.1     .12       0
  9671.3     .05       0 10051.2     .16       0
Bank Sta=4428.1,5458.7
XS Rating Curve= 0 ,0
Exp/Cntr=0.3,0.1

Type RM Length L Ch R = 1 ,43421   ,1672,1672,1672
BEGIN DESCRIPTION:
COON CREEK 48.0
END DESCRIPTION:
XS GIS Cut Line= 3
      3690212.32     10746492.48      3688528.28     10747586.24
       3683736.6     10749114.02
#Sta/Elev= 30
  2855.8  408.44  2914.3  404.27    3181  353.89    3372  335.82  3651.1   329.7
  3847.5  337.67  3998.5  324.99  4242.9  311.54    4382  303.69  4789.6  302.97
  4792.3  302.47  4795.6  302.97  5140.3  306.09  5620.5  304.83    5677  308.95
  5711.8  313.83  5807.2  307.87  7044.6  307.87  7748.9  310.14  7899.9  320.97
  7991.3  322.71  8001.4   323.1  8096.5  325.72  8357.6   325.9  8517.4  336.62
  8844.7  345.73  9015.6  360.44    9239  379.69  9534.2  395.42  9893.2  394.73
#Mann= 16 ,-1 , 0
  2855.8     .12       0    3372     .16       0  3998.5     .12       0
  4789.6     .07       0  4795.6     .12       0  5140.3     .16       0
    5677     .08       0  5807.2     .05       0  7044.6     .16       0
  7899.9     .05       0  7991.3     .16       0  8001.4     .05       0
  8096.5     .16       0  9015.6     .12       0    9239     .05       0
  9534.2     .12       0
Bank Sta=4242.9,5711.8
XS Rating Curve= 0 ,0
Exp/Cntr=0.3,0.1

Type RM Length L Ch R = 1 ,41749   ,1632,1632,1632
BEGIN DESCRIPTION:
COON CREEK 47.0
END DESCRIPTION:
XS GIS Cut Line= 3
      3688881.46     10745878.71      3687787.72     10746633.91
      3685378.83     10747688.61
#Sta/Elev= 30
  3960.7  357.19  4027.3  359.26  4115.6  345.64  4193.8  333.24  4221.4  324.66
  4358.6  310.66  4780.1   304.1    4845   301.2  4847.8   300.7    4851   301.2
  4903.7   301.2  5087.6   301.2  5119.8  304.99  5624.5  303.77  6335.2  303.63
  6445.2  311.02  6530.1  314.11  6553.4  314.78  6837.9  320.06  6979.4  325.32
    7035   325.8  7207.7  330.93  7261.1  334.07  7394.7  337.72    7534  348.43
  7608.6  344.96  7694.5  347.09  7833.2  360.91  7914.4  359.99  7919.5   359.4
#Mann= 19 ,-1 , 0
  3960.7     .16       0  4115.6     .12       0  4780.1     .16       0
    4845     .03       0    4851     .16       0  4903.7     .05       0
  5087.6     .12       0  5624.5     .16       0  6530.1     .05       0
  6553.4     .16       0  6837.9     .05       0  6979.4      .1       0
    7035     .08       0  7207.7     .05       0  7261.1     .16       0
  7608.6     .12       0  7694.5     .16       0  7833.2     .12       0
  7914.4     .16       0
Bank Sta=4358.6,6445.2
XS Rating Curve= 0 ,0
Exp/Cntr=0.3,0.1

Type RM Length L Ch R = 1 ,40117   ,705,705,705
BEGIN DESCRIPTION:
COON CREEK 44.0
END DESCRIPTION:
XS GIS Cut Line= 3
      3687299.59     10744910.23      3686699.61     10746310.19
      3685699.63     10747310.17
#Sta/Elev= 30
  3482.1  373.72  3601.7   372.8  3698.7  367.12  3727.4  362.16  3819.3  345.15
  3877.4   339.9  4076.8  310.49    4187  304.48  4451.4  305.11  4454.3  304.93
  4624.4  303.36  4657.1  306.62  4686.1  303.17  4840.8   301.2  4843.6   300.7
  4846.8   301.2  4921.3   301.2  4929.6   301.2  5165.3   301.2  5298.8  303.84
  5407.6  303.49  5670.3  303.35  5878.7  303.88  5938.6  303.48  6023.4  311.39
  6156.2  327.95  6249.7  334.81  6305.5  344.55  6362.9  353.06  6419.4  355.13
#Mann= 17 ,-1 , 0
  3482.1     .12       0  3698.7     .07       0  3727.4     .12       0
    4187     .16       0  4451.4     .12       0  4454.3     .16       0
  4840.8    .033       0  4846.8     .16       0  4921.3     .07       0
  4929.6     .05       0  5165.3     .16       0  5298.8     .12       0
  5407.6     .16       0  5670.3     .12       0  5878.7     .16       0
  6156.2     .05       0  6305.5     .16       0
Bank Sta=4076.8,6023.4
XS Rating Curve= 0 ,0
Exp/Cntr=0.3,0.1

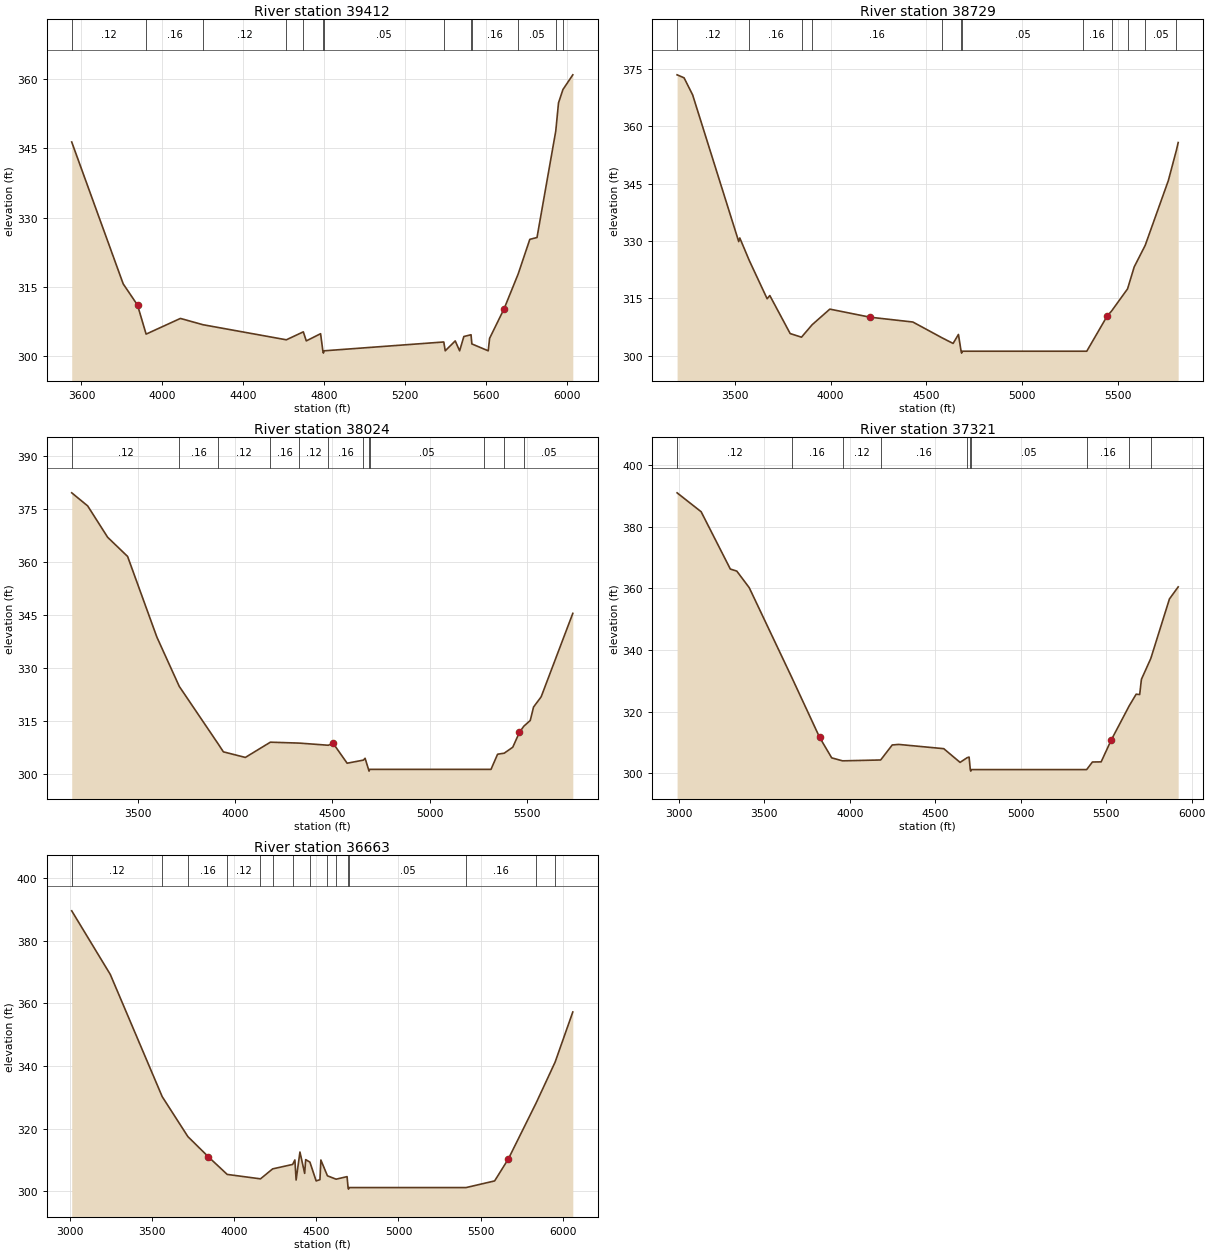
Type RM Length L Ch R = 1 ,39412   ,683,683,683
BEGIN DESCRIPTION:
COON CREEK 43.0
END DESCRIPTION:
XS GIS Cut Line= 3
      3687049.59     10745110.21      3686049.61     10746110.19
      3685249.61     10746810.19
#Sta/Elev= 30
  3551.9  346.33  3806.4  315.67  3877.1  311.09  3919.7  304.81  4089.3   308.2
  4200.6  306.84  4612.9  303.58  4696.9   305.3  4711.5  303.34  4782.2   304.9
  4793.4   301.2  4796.1   300.7  4799.4   301.2  5391.3  303.11  5398.4   301.2
  5447.8  303.34  5469.6   301.2  5490.5  304.29    5526  304.67  5530.1  302.69
    5611   301.2  5617.7  303.89  5688.8  310.23    5759   317.8  5816.5  325.29
  5852.1  325.69  5944.9  348.71  5958.4  354.78  5980.3  357.67  6029.1  360.85
#Mann= 13 ,-1 , 0
  3551.9     .12       0  3919.7     .16       0  4200.6     .12       0
  4612.9     .16       0  4696.9     .05       0  4793.4    .033       0
  4799.4     .05       0  5391.3     .16       0    5526     .05       0
  5530.1     .16       0    5759     .05       0  5944.9     .16       0
  5980.3     .08       0
Bank Sta=3877.1,5688.8
XS Rating Curve= 0 ,0
Exp/Cntr=0.3,0.1

Type RM Length L Ch R = 1 ,38729   ,705,705,705
BEGIN DESCRIPTION:
COON CREEK 42.0
END DESCRIPTION:
XS GIS Cut Line= 3
      3687199.61     10744860.19      3685599.61     10745660.19
      3684799.59     10745860.19
#Sta/Elev= 30
  3199.4  373.43  3235.7  372.65  3280.5  368.18  3520.8  329.85  3526.4   330.8
  3576.2  324.87    3669  314.91    3683  315.75  3789.2  305.81  3848.3  304.87
  3903.7  308.12    3996   312.2  4205.6  310.09  4429.2  308.83  4580.9  304.71
  4638.9  303.23  4666.8  305.58  4680.6   301.2  4683.3   300.7  4686.6   301.2
  5315.7   301.2  5336.1   301.2  5441.8  310.33    5466  311.74  5548.8  317.49
  5583.5  323.23  5640.8  328.86  5761.3  345.76    5804   353.8  5812.9  355.73
#Mann= 12 ,-1 , 0
  3199.4     .12       0  3576.2     .16       0  3848.3     .12       0
  3903.7     .16       0  4580.9     .05       0  4680.6    .033       0
  4686.6     .05       0  5315.7     .16       0    5466     .05       0
  5548.8     .16       0  5640.8     .05       0    5804     .16       0
Bank Sta=4205.6,5441.8
XS Rating Curve= 0 ,0
Exp/Cntr=0.3,0.1

Type RM Length L Ch R = 1 ,38024   ,703,703,703
BEGIN DESCRIPTION:
COON CREEK 41.0
END DESCRIPTION:
XS GIS Cut Line= 3
      3687349.65     10744560.18      3685549.61     10744960.19
      3684849.57      10745160.2
#Sta/Elev= 30
  3162.3  379.55  3244.3  375.84  3346.7  366.96  3449.2  361.52    3599  338.73
  3714.1  324.73  3914.9  308.34  3940.9  306.16  4053.6  304.58  4181.9   308.9
  4330.3  308.64  4479.3  308.03  4504.3  308.57    4576  302.94  4659.6  303.82
  4668.2  304.34  4685.7   301.2  4688.4   300.7  4691.7   301.2  5278.1   301.2
  5314.4   301.2  5348.2  305.49  5382.2  305.78  5426.2  307.48    5460  311.65
    5483  313.44  5515.9  315.05  5532.8  318.86  5571.8  321.75  5734.3   345.4
#Mann= 12 ,-1 , 0
  3162.3     .12       0  3714.1     .16       0  3914.9     .12       0
  4181.9     .16       0  4330.3     .12       0  4479.3     .16       0
  4659.6     .05       0  4685.7    .033       0  4691.7     .05       0
  5278.1     .07       0  5382.2      .1       0    5483     .05       0
Bank Sta=4504.3,5460
XS Rating Curve= 0 ,0
Exp/Cntr=0.3,0.1

Type RM Length L Ch R = 1 ,37321   ,658,658,658
BEGIN DESCRIPTION:
COON CREEK 40.0
END DESCRIPTION:
XS GIS Cut Line= 3
      3687599.61     10744460.19      3685599.61     10744260.19
      3684699.64     10744060.19
#Sta/Elev= 30
  2989.4  391.06  3130.1  384.92  3300.9  366.31  3338.6  365.65  3411.5  360.26
  3660.4  331.12  3823.5  311.64  3893.9  305.01  3957.4  304.04  4180.5  304.32
  4248.1  309.19  4285.8  309.37  4549.6  307.99  4645.1  303.54  4686.5  305.06
  4697.9  305.26  4704.9   301.2  4707.7   300.7  4710.9   301.2  5385.7   301.2
  5419.4  303.66  5470.6  303.71  5528.2  310.65  5634.3  321.86  5675.5  325.69
    5696  325.56  5706.2  330.52  5760.8  337.23  5870.1   356.6  5921.3  360.52
#Mann= 10 ,-1 , 0
  2989.4     .12       0  3660.4     .16       0  3957.4     .12       0
  4180.5     .16       0  4686.5     .05       0  4704.9    .033       0
  4710.9     .05       0  5385.7     .16       0  5634.3     .05       0
  5760.8     .16       0
Bank Sta=3823.5,5528.2
XS Rating Curve= 0 ,0
Exp/Cntr=0.3,0.1

Type RM Length L Ch R = 1 ,36663   ,644,644,644
BEGIN DESCRIPTION:
COON CREEK 39.0
END DESCRIPTION:
XS GIS Cut Line= 3
      3687549.57     10744410.17      3685749.61     10743610.19
      3684749.57      10744010.2
#Sta/Elev= 30
  3013.4  389.48    3248  369.18  3563.6   330.2  3719.8  317.45    3845  310.98
  3958.8  305.39  4161.2  303.98  4234.9  307.15  4356.8  308.58  4370.3  310.01
  4377.8  303.61  4401.1  312.54  4429.8  305.73    4436  310.12  4461.7  309.31
  4499.6  303.32  4522.8  303.72  4528.3  309.99  4568.2  304.95  4621.2  303.87
  4687.7  304.69  4693.6   301.2  4696.3   300.7  4699.6   301.2  5411.6   301.2
  5584.9  303.32  5668.4  310.34  5839.2   328.4  5952.5   341.2  6060.2  357.21
#Mann= 15 ,-1 , 0
  3013.4     .12       0  3563.6     .05       0  3719.8     .16       0
  3958.8     .12       0  4161.2     .16       0  4234.9     .12       0
  4356.8     .16       0  4461.7     .12       0  4568.2     .16       0
  4621.2     .05       0  4693.6    .033       0  4699.6     .05       0
  5411.6     .16       0  5839.2     .05       0  5952.5     .16       0
Bank Sta=3845,5668.4
XS Rating Curve= 0 ,0
Exp/Cntr=0.3,0.1