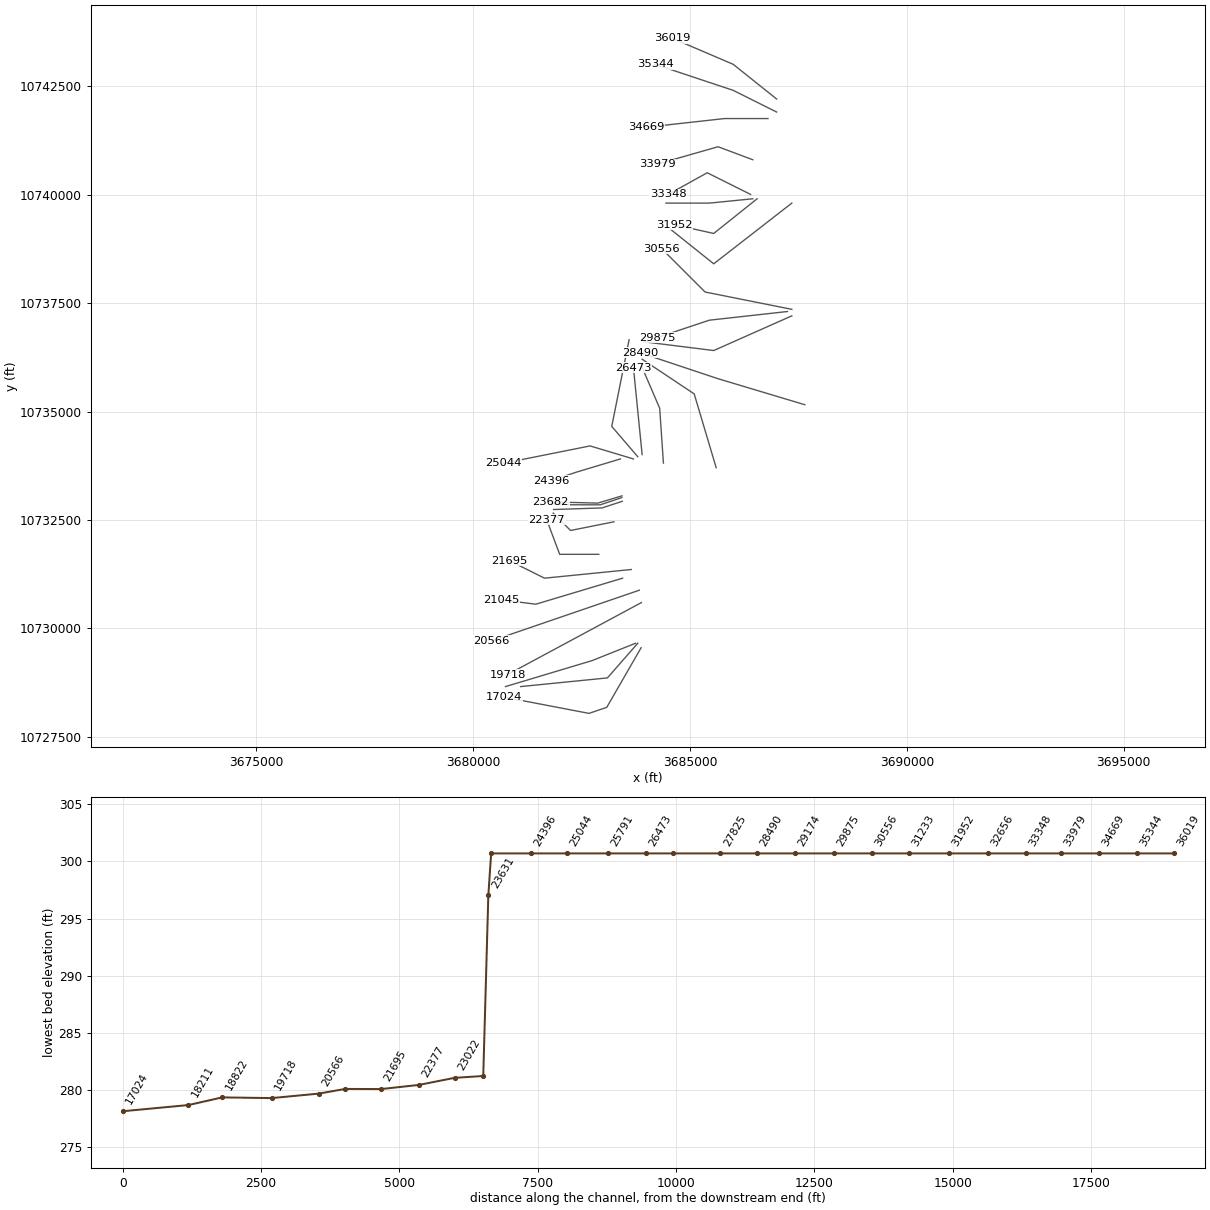
HEC-RAS study COON CREEK.prj: COON CREEK Base Level Engineering

--- COON CREEK.g01 (geometry) --- (continued)

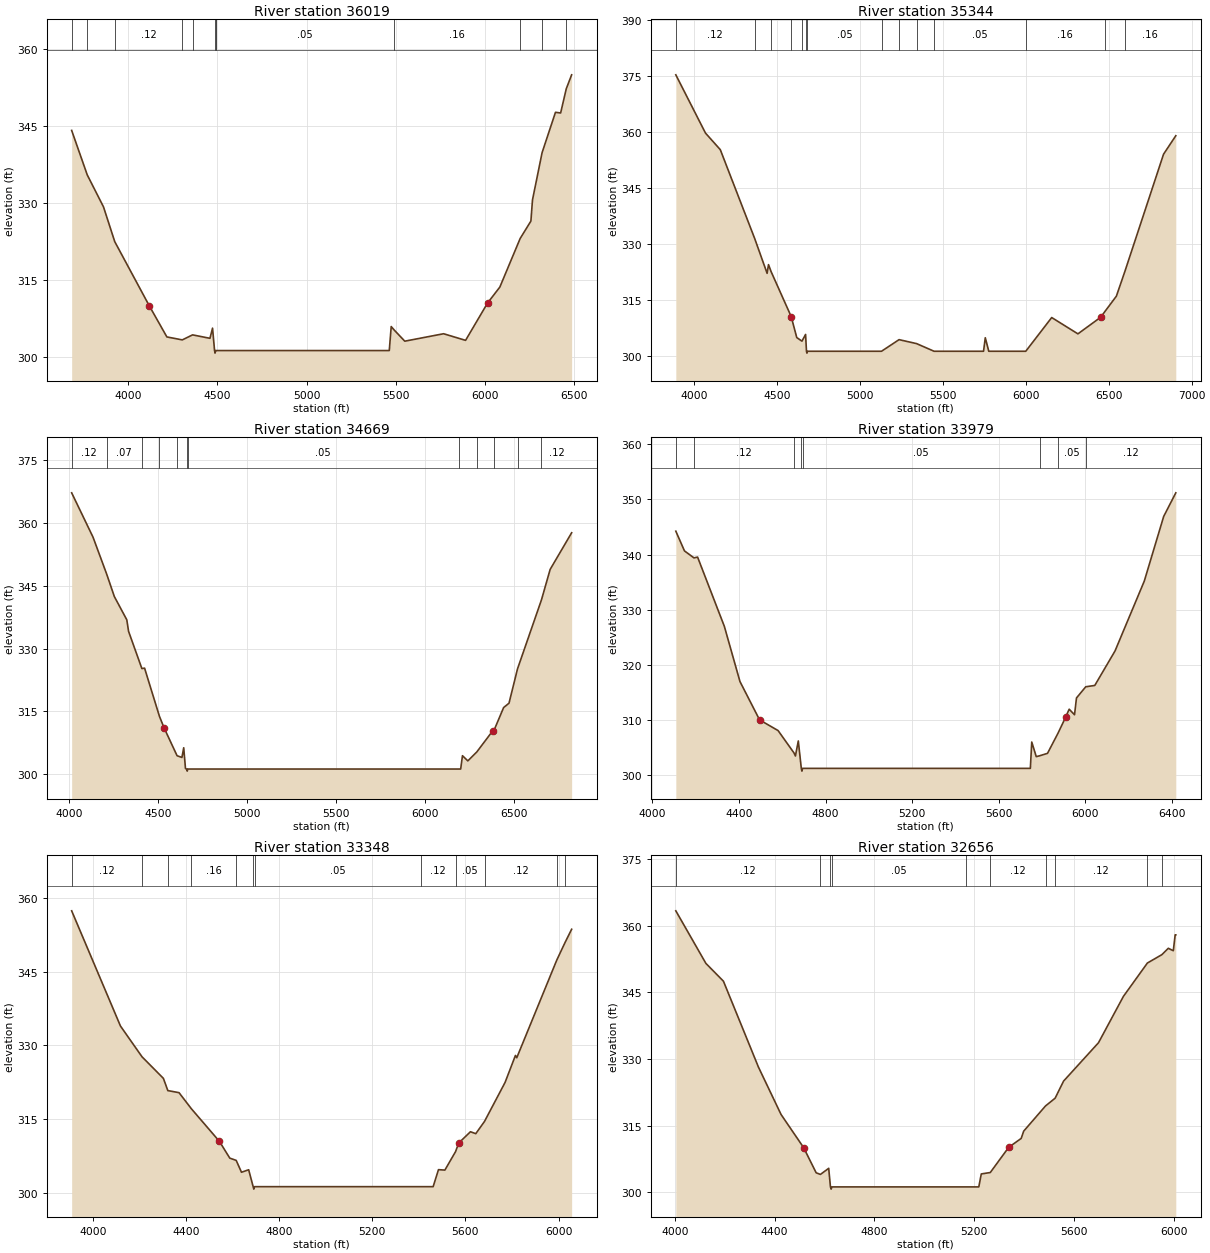
Type RM Length L Ch R = 1 ,36019   ,675,675,675
BEGIN DESCRIPTION:
COON CREEK 38.0
END DESCRIPTION:
XS GIS Cut Line= 3
       3686999.6     10742210.19      3685999.61     10743010.19
      3684599.59      10743610.2
#Sta/Elev= 30
  3682.8  344.13  3770.3  335.45  3861.3  329.22  3924.4  322.44  4117.4  309.97
  4216.7  303.86  4303.2  303.28  4360.9  304.26  4458.4  303.59  4472.8  305.57
  4484.2   301.2  4486.9   300.7  4490.2   301.2  4491.8   301.2  5463.9   301.2
  5474.8  305.88    5492  305.19  5550.9  303.03  5768.5  304.48  5891.8  303.19
  6015.1  310.47    6084  313.58  6197.9  323.05  6258.1  326.45  6267.2   330.6
  6320.8  339.78  6395.9  347.66  6424.9  347.53  6456.4  352.24  6486.6  354.97
#Mann= 12 ,-1 , 0
  3682.8     .12       0  3770.3     .07       0  3924.4     .12       0
  4303.2     .05       0  4360.9     .07       0  4484.2    .033       0
  4490.2     .07       0  4491.8     .05       0    5492     .16       0
  6197.9     .05       0  6320.8     .16       0  6456.4     .12       0
Bank Sta=4117.4,6015.1
XS Rating Curve= 0 ,0
Exp/Cntr=0.3,0.1

Type RM Length L Ch R = 1 ,35344   ,675,675,675
BEGIN DESCRIPTION:
COON CREEK 37.0
END DESCRIPTION:
XS GIS Cut Line= 3
      3686999.61     10741910.19      3685999.61     10742410.19
      3684199.61     10743010.19
#Sta/Elev= 30
    3889  375.23  4067.9  359.63  4157.3  355.18  4364.5  331.41  4439.6  322.07
    4448   324.4  4463.3  322.57  4584.8  310.49  4618.5  304.86  4649.8  303.91
  4671.6  305.71    4677   301.2  4679.8   300.7    4683   301.2  5129.6   301.2
  5235.3  304.31    5341  303.25  5446.7   301.2  5744.9   301.2  5755.4  304.82
  5776.5   301.2  5999.5   301.2    6156  310.23  6314.1  305.86  6451.1   310.3
    6475  311.73    6546  315.95  6597.1  322.55  6830.6  353.98  6904.4  358.92
#Mann= 14 ,-1 , 0
    3889     .12       0  4364.5     .07       0  4463.3     .12       0
  4584.8     .16       0  4649.8     .05       0    4677    .033       0
    4683     .05       0  5129.6     .07       0  5235.3     .05       0
    5341     .16       0  5446.7     .05       0  5999.5     .16       0
    6475     .05       0  6597.1     .16       0
Bank Sta=4584.8,6451.1
XS Rating Curve= 0 ,0
Exp/Cntr=0.3,0.1

Type RM Length L Ch R = 1 ,34669   ,690,690,690
BEGIN DESCRIPTION:
COON CREEK 36.0
END DESCRIPTION:
XS GIS Cut Line= 3
       3686799.6     10741760.19      3685799.61     10741760.19
      3683999.57     10741560.18
#Sta/Elev= 30
    4014  367.24    4134  356.65  4210.7  347.83    4254  342.44    4324  336.88
    4334  334.12  4408.7  325.23    4424  325.32  4507.7  313.78    4534  311.01
  4606.7  304.38    4634  303.97    4644  306.29    4654   301.3    4661   301.2
  4663.7   300.7    4667   301.2  6189.5   301.2  6201.2   301.2  6211.3  304.39
  6241.5  303.15  6291.8  305.28  6382.4  310.39  6390.9  310.68  6442.7   315.9
  6472.9  316.94  6520.7  325.14  6655.6  341.67  6704.3  348.93  6825.1  357.69
#Mann= 12 ,-1 , 0
    4014     .12       0  4210.7     .07       0  4408.7     .12       0
  4507.7     .16       0  4606.7     .05       0    4661    .033       0
    4667     .05       0  6189.5     .16       0  6291.8     .12       0
  6390.9     .05       0  6520.7     .16       0  6655.6     .12       0
Bank Sta=4534,6382.4
XS Rating Curve= 0 ,0
Exp/Cntr=0.3,0.1

Type RM Length L Ch R = 1 ,33979   ,631,631,631
BEGIN DESCRIPTION:
COON CREEK 35.0
END DESCRIPTION:
XS GIS Cut Line= 3
       3686449.6     10740810.19      3685649.61     10741110.19
      3684249.62     10740710.19
#Sta/Elev= 30
  4108.2  344.25  4148.2  340.67  4192.1   339.4  4208.8  339.55  4332.5  326.97
  4404.6  316.96  4495.3     310  4580.8  308.06  4654.5  303.99  4660.9  303.45
  4674.2  306.18  4688.1   301.2  4690.9   300.7  4694.1   301.2  5746.5   301.2
    5753  305.98  5773.8  303.33  5788.9  303.48  5825.8  303.93    5874  307.56
    5909  310.44  5925.9  311.94  5950.6  310.93  5959.7  313.98  6002.5  316.01
  6044.2  316.25  6137.8  322.51    6273  335.19  6362.7  346.93  6418.6  351.21
#Mann= 8 ,-1 , 0
  4108.2     .16       0  4192.1     .12       0  4654.5     .05       0
  4688.1    .033       0  4694.1     .05       0  5788.9     .12       0
    5874     .05       0  6002.5     .12       0
Bank Sta=4495.3,5909
XS Rating Curve= 0 ,0
Exp/Cntr=0.3,0.1

Type RM Length L Ch R = 1 ,33348   ,692,692,692
BEGIN DESCRIPTION:
COON CREEK 34.0
END DESCRIPTION:
XS GIS Cut Line= 3
      3686399.62     10740010.19      3685399.61     10740510.19
      3684499.61     10740010.19
#Sta/Elev= 30
  3908.6  357.45  4118.2  333.96  4210.9  327.68  4302.7  323.28  4321.7  320.79
  4369.8  320.37  4422.8  317.09  4543.1  310.45  4587.8  307.02  4615.3  306.56
  4638.1  304.14  4668.9  304.65  4688.2   301.2    4691   300.7  4694.2   301.2
  5408.4   301.2  5461.3   301.2  5484.2  304.67  5511.7  304.58  5557.6  308.35
  5571.2   310.1  5621.5   312.4  5644.4  312.01    5682  314.51  5770.2  322.45
  5814.8  327.96  5820.5  327.49  5992.4  347.41  6027.1  350.91  6056.2  353.69
#Mann= 12 ,-1 , 0
  3908.6     .12       0  4210.9     .16       0  4321.7     .12       0
  4422.8     .16       0  4615.3     .05       0  4688.2    .033       0
  4694.2     .05       0  5408.4     .12       0  5557.6     .05       0
    5682     .12       0  5992.4     .16       0  6027.1     .12       0
Bank Sta=4543.1,5571.2
XS Rating Curve= 0 ,0
Exp/Cntr=0.3,0.1

Type RM Length L Ch R = 1 ,32656   ,704,704,704
BEGIN DESCRIPTION:
COON CREEK 33.0
END DESCRIPTION:
XS GIS Cut Line= 3
      3686449.63     10739910.19      3685449.61     10739810.19
      3684449.62     10739810.19
#Sta/Elev= 30
  4004.1   363.4  4124.7  351.56  4195.1  347.54  4335.8  328.15  4426.2  317.51
  4516.7  310.05  4566.9  304.38    4584  304.01  4617.2  305.39  4624.2   301.2
    4627   300.7  4630.2   301.2  5166.1   301.2  5219.1   301.2  5229.1  304.12
  5265.1  304.44  5339.1  310.12  5389.1  312.12  5399.1  313.76  5486.6  319.44
  5525.1  321.18  5559.1  325.04  5699.1  333.68  5799.1  344.13  5895.2  351.64
  5953.4  353.53  5979.1  354.96  5999.1  354.41  6006.6  357.99  6009.1  357.99
#Mann= 10 ,-1 , 0
  4004.1     .12       0    4584     .05       0  4624.2    .033       0
  4630.2     .05       0  5166.1     .07       0  5265.1     .12       0
  5486.6     .05       0  5525.1     .12       0  5895.2     .16       0
  5953.4     .12       0
Bank Sta=4516.7,5339.1
XS Rating Curve= 0 ,0
Exp/Cntr=0.3,0.1

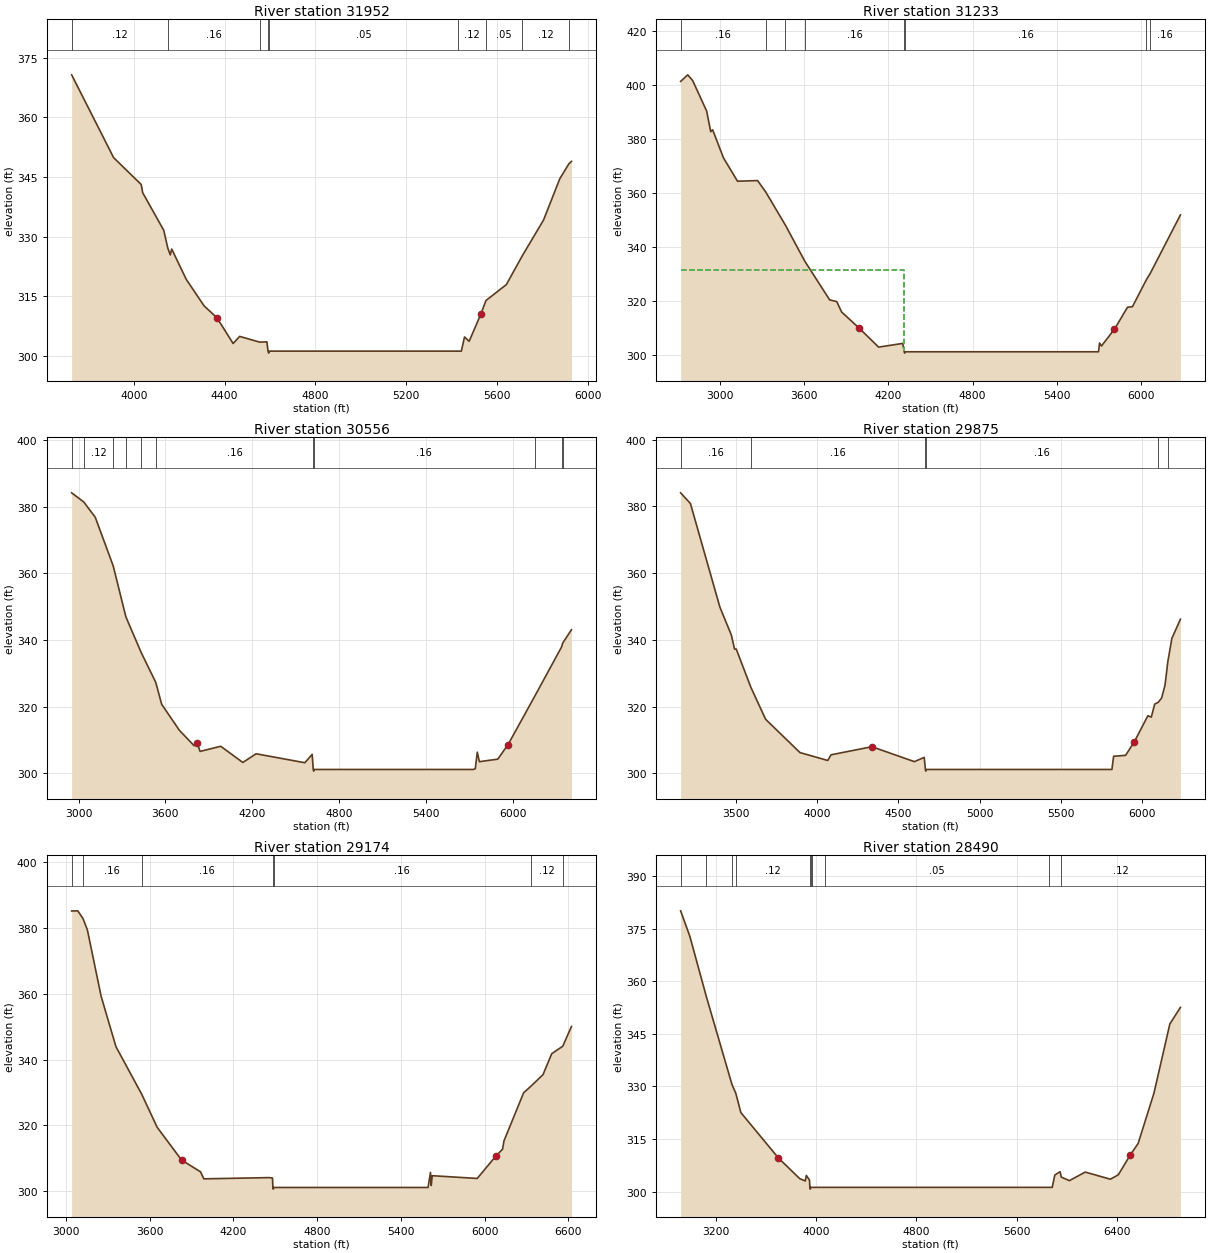
Type RM Length L Ch R = 1 ,31952   ,719,719,719
BEGIN DESCRIPTION:
COON CREEK 32.0
END DESCRIPTION:
XS GIS Cut Line= 3
      3686549.61     10739910.19      3685549.61     10739110.19
      3684649.59     10739310.19
#Sta/Elev= 30
  3725.9  370.71  3910.8  349.88  4032.4  343.12  4038.9  341.06  4131.7   331.6
  4149.6  327.13  4160.5  325.42  4166.9  326.88  4230.9  319.26  4309.4   312.6
  4366.2  309.59  4437.4  303.12  4466.3  304.91  4554.4  303.47  4586.3  303.54
  4591.3   301.2  4594.1   300.7  4597.3   301.2  5430.6   301.2  5443.2   301.2
  5457.3  304.77  5477.7  303.67    5529   310.5  5551.8  313.94  5641.6  317.94
    5712   325.2  5805.6   334.2  5877.3  344.59  5917.4  348.35  5928.5  348.94
#Mann= 9 ,-1 , 0
  3725.9     .12       0  4149.6     .16       0  4554.4     .05       0
  4591.3    .033       0  4597.3     .05       0  5430.6     .12       0
  5551.8     .05       0    5712     .12       0  5917.4     .16       0
Bank Sta=4366.2,5529
XS Rating Curve= 0 ,0
Exp/Cntr=0.3,0.1

Type RM Length L Ch R = 1 ,31233   ,677,677,677
BEGIN DESCRIPTION:
COON CREEK 31.0
END DESCRIPTION:
XS GIS Cut Line= 3
       3687349.6     10739810.18      3685549.61     10738410.19
      3684549.58     10739210.21
#Sta/Elev= 30
  2719.7  401.36  2770.4   403.8  2805.7  401.67  2905.2  390.37  2934.1  382.74
  2947.7  383.44  3025.5  372.99  3125.1  364.38  3268.1  364.63  3326.3  360.38
  3466.9  348.05  3603.8  334.82    3782   320.4  3831.8  319.81  3867.1  315.92
  3987.5  310.17  4130.4  302.93  4302.4   304.3  4312.9   301.2  4315.7   300.7
  4318.9   301.2  5697.2   301.2  5704.4  304.45    5718  303.34  5810.8  309.56
  5903.7   317.7  5938.9   317.9  6038.1   327.9  6065.9  330.26  6280.7  351.91
#Mann= 8 ,-1 , 0
  2719.7     .16       0  3326.3     .12       0  3466.9     .16       0
  3603.8     .16       0  4312.9    .033       0  4318.9     .16       0
  6038.1     .12       0  6065.9     .16       0
#XS Ineff= 2 , 0
         4311.36  331.54
Permanent Ineff=
       F       F
Bank Sta=3987.5,5810.8
XS Rating Curve= 0 ,0
Exp/Cntr=0.3,0.1

Type RM Length L Ch R = 1 ,30556   ,681,681,681
BEGIN DESCRIPTION:
COON CREEK 30.0
END DESCRIPTION:
XS GIS Cut Line= 3
      3687349.57      10737360.2      3685349.61     10737760.19
       3684349.6      10738760.2
#Sta/Elev= 30
  2952.1  384.11  3035.8  381.37  3115.2  376.79  3239.2  362.21  3326.9  346.93
  3431.7  336.32  3533.4  327.29  3574.1  320.74  3696.5  312.94  3798.5  308.31
  3818.9  309.25  3839.3  306.61  3982.1  308.15    4135   303.3  4226.8   305.9
  4563.4  303.22  4614.3  305.73  4621.5   301.2  4624.3   300.7  4627.5   301.2
  5727.1   301.2  5741.2  301.42  5755.3  306.38  5769.5  303.53  5896.8  304.29
  5967.5  308.63  6151.3  323.07  6338.3  337.97  6344.6  339.02  6405.9  343.09
#Mann= 11 ,-1 , 0
  2952.1     .05       0  3035.8     .12       0  3239.2     .16       0
  3326.9     .12       0  3431.7     .16       0  3533.4     .16       0
  4621.5    .033       0  4627.5     .16       0  6151.3     .12       0
  6338.3     .16       0  6344.6     .12       0
Bank Sta=3818.9,5967.5
XS Rating Curve= 0 ,0
Exp/Cntr=0.3,0.1

Type RM Length L Ch R = 1 ,29875   ,701,701,701
BEGIN DESCRIPTION:
COON CREEK 29.0
END DESCRIPTION:
XS GIS Cut Line= 3
      3687249.65     10737310.19      3685449.61     10737110.19
      3684249.64      10736710.2
#Sta/Elev= 30
  3160.1  384.09  3220.5  380.88  3401.6  349.87  3472.1   341.5  3492.2  337.26
  3502.2   337.3  3592.8  325.77  3683.3  316.23  3894.6  306.26  4065.7  303.89
  4085.8  305.59  4337.3  308.01  4598.9  303.54  4659.3  304.82  4666.4   301.2
  4669.1   300.7  4672.4   301.2  5814.5   301.2    5825  305.15  5898.8  305.43
  5952.9  309.53  6035.9   317.3  6056.9  316.89    6078   320.8  6099.1   321.3
  6120.2  322.59  6141.3  326.47  6158.9  333.61  6183.4  340.46  6236.1  346.22
#Mann= 6 ,-1 , 0
  3160.1     .16       0  3592.8     .16       0  4666.4    .033       0
  4672.4     .16       0  6099.1     .16       0  6158.9     .12       0
Bank Sta=4337.3,5952.9
XS Rating Curve= 0 ,0
Exp/Cntr=0.3,0.1

Type RM Length L Ch R = 1 ,29174   ,684,684,684
BEGIN DESCRIPTION:
COON CREEK 28.0
END DESCRIPTION:
XS GIS Cut Line= 3
      3687349.61     10737210.19      3685549.61     10736410.19
      3683949.64     10736610.19
#Sta/Elev= 30
  3040.7  385.04  3084.5  385.09  3122.1  382.74  3153.6  379.27    3252  359.17
  3358.1   343.9    3542  329.55  3653.5  319.46  3828.6  309.52  3964.7  305.94
    3988  303.82  4457.2  304.19  4480.4  304.06  4482.9   301.2  4485.6   300.7
  4488.9   301.2    5595   301.2  5612.6  305.77  5617.7  301.81  5625.2  304.77
  5947.7  303.94  6078.7  310.61  6129.1  312.81  6139.2  315.32  6280.3  329.93
  6330.7  331.85  6418.9  335.41  6481.8  341.78  6560.7  344.04  6622.9  350.03
#Mann= 7 ,-1 , 0
  3040.7     .05       0  3122.1     .16       0    3542     .16       0
  4482.9    .033       0  4488.9     .16       0  6330.7     .12       0
  6560.7     .16       0
Bank Sta=3828.6,6078.7
XS Rating Curve= 0 ,0
Exp/Cntr=0.3,0.1

Type RM Length L Ch R = 1 ,28490   ,665,665,665
BEGIN DESCRIPTION:
COON CREEK 27.0
END DESCRIPTION:
XS GIS Cut Line= 3
      3687649.61     10735160.19      3685649.61     10735760.19
      3683849.64     10736360.18
#Sta/Elev= 30
  2920.6  380.05  2993.7  372.84    3126  355.55    3330  330.54  3361.2  327.96
  3400.9  322.53    3701  309.56  3870.7  303.68    3915  303.03  3922.9  304.61
  3948.1   303.3  3951.2   301.2  3953.9   300.7  3957.2   301.2  3965.4   301.2
    4070   301.2  5856.6   301.2  5883.6   301.2  5904.6  304.72  5946.8  305.67
  5955.8  304.13  6020.6  303.12  6147.1  305.56  6347.4  303.53  6410.6  304.78
  6505.5  310.41  6568.7  313.71  6695.2   328.1  6821.7   347.8    6906  352.51
#Mann= 10 ,-1 , 0
  2920.6     .16       0    3126     .05       0    3330     .16       0
  3361.2     .12       0  3951.2    .033       0  3957.2     .12       0
  3965.4     .16       0    4070     .05       0  5856.6     .16       0
  5955.8     .12       0
Bank Sta=3701,6505.5
XS Rating Curve= 0 ,0
Exp/Cntr=0.3,0.1

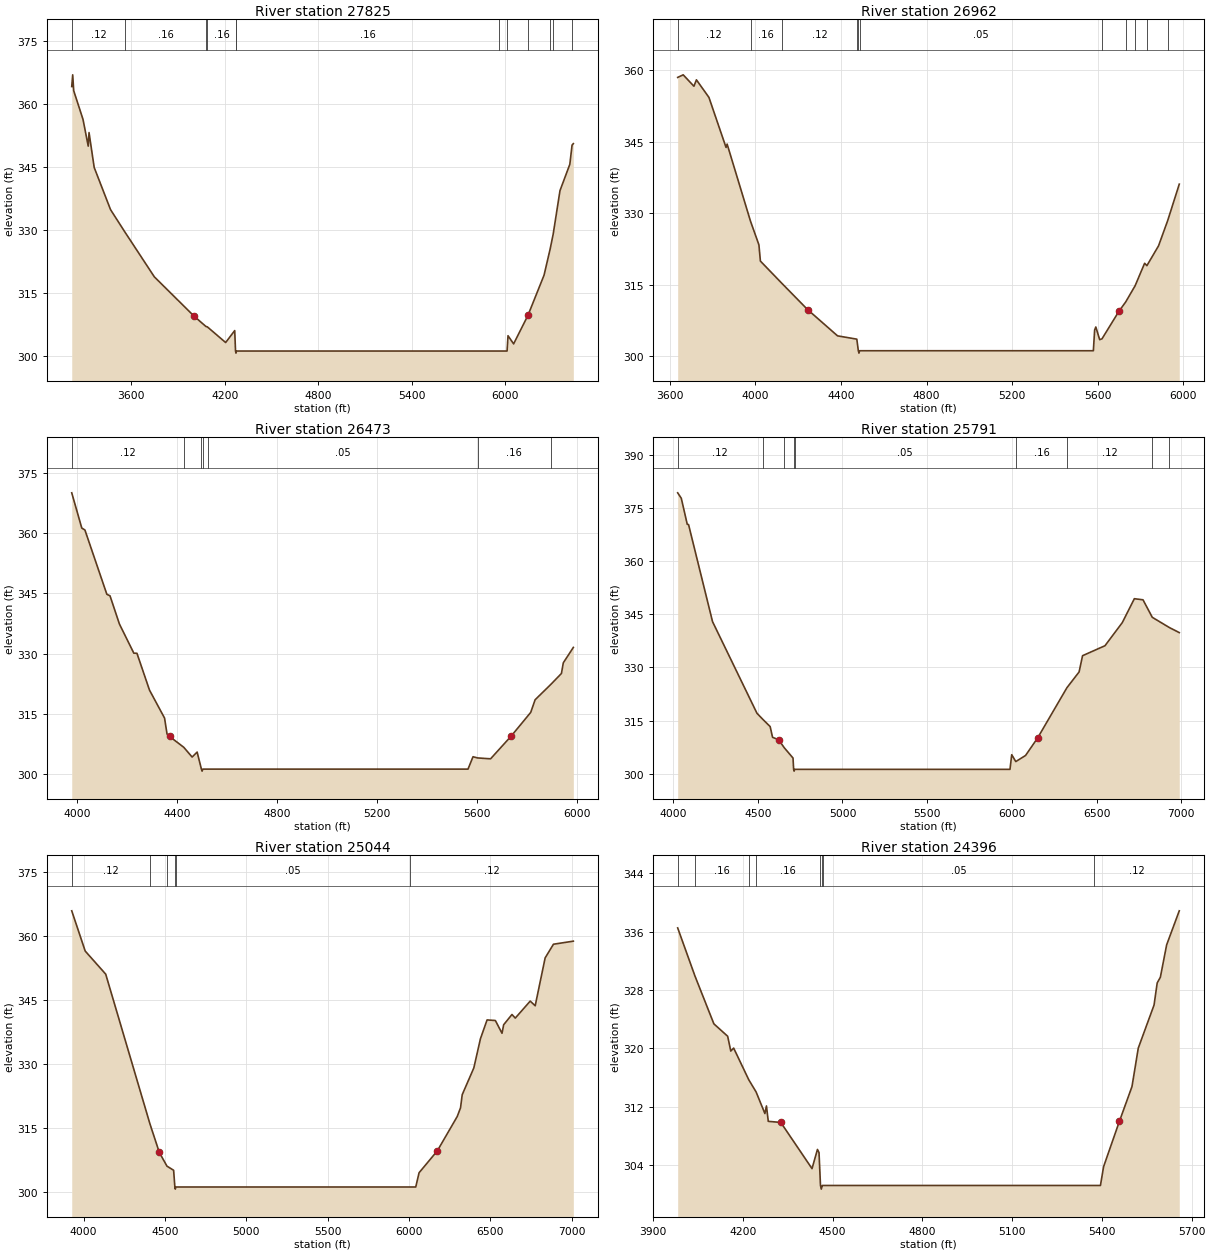
Type RM Length L Ch R = 1 ,27825   ,863,863,863
BEGIN DESCRIPTION:
COON CREEK 26.0
END DESCRIPTION:
XS GIS Cut Line= 3
      3685606.01     10733708.13      3685099.61     10735410.19
      3683899.62     10736210.18
#Sta/Elev= 30
  3217.6   364.1  3223.7  366.89  3230.2  363.11  3290.1  356.26  3323.3  349.93
  3328.5  353.16  3361.7  344.85  3466.5  334.83  3559.4  329.46  3747.6  318.84
  4002.2   309.5  4078.5  307.04  4087.7  306.94    4205  303.22  4263.1  306.06
  4268.4   301.2  4271.2   300.7  4274.4   301.2    5956   301.2  6010.5   301.2
  6016.5  304.84  6052.5   302.9  6144.9  309.72  6247.8  319.25  6286.7  325.44
  6306.4  329.02    6350  339.36  6413.1  345.61  6427.4  350.17  6435.6  350.52
#Mann= 12 ,-1 , 0
  3217.6     .12       0  3559.4     .16       0  4078.5     .12       0
  4087.7     .16       0  4268.4    .033       0  4274.4     .16       0
    5956     .16       0  6010.5     .12       0  6144.9     .16       0
  6286.7     .12       0  6306.4     .16       0  6427.4     .12       0
Bank Sta=4002.2,6144.9
XS Rating Curve= 0 ,0
Exp/Cntr=0.3,0.1

Type RM Length L Ch R = 1 ,26962   ,489,489,489
BEGIN DESCRIPTION:
COON CREEK 25.0
END DESCRIPTION:
XS GIS Cut Line= 3
      3684390.37     10733814.41      3684303.92     10735079.67
      3683878.59     10736069.23
#Sta/Elev= 30
  3636.3  358.51  3662.1  359.05  3712.3  356.66    3724     358  3782.4  354.32
  3862.5  343.82  3867.5  344.53  3976.9  328.35  4016.1  323.41    4023     320
  4124.4  315.29  4243.5  309.84  4383.8  304.32  4473.8  303.63    4481   301.2
  4483.8   300.7    4487   301.2  5579.9   301.2  5585.9  305.56  5591.4  306.18
  5609.5  303.52  5620.3   303.7  5699.6  309.48  5730.8  311.41  5775.2  314.83
  5819.6  319.54  5830.2  319.04  5884.7   323.2  5927.5   328.5  5981.6  336.13
#Mann= 11 ,-1 , 0
  3636.3     .12       0  3976.9     .16       0  4124.4     .12       0
  4473.8     .05       0    4481    .033       0    4487     .05       0
  5620.3     .16       0  5730.8     .12       0  5775.2     .16       0
  5830.2     .12       0  5927.5     .16       0
Bank Sta=4243.5,5699.6
XS Rating Curve= 0 ,0
Exp/Cntr=0.3,0.1

Type RM Length L Ch R = 1 ,26473   ,682,682,682
BEGIN DESCRIPTION:
COON CREEK 24.0
END DESCRIPTION:
XS GIS Cut Line= 3
      3683899.61     10734010.15      3683799.61     10735010.19
      3683699.61     10736010.18
#Sta/Elev= 30
  3977.1  370.09  4017.3  361.31  4029.9  360.82  4117.8  344.79  4130.4  344.41
  4168.1  337.39  4225.9  330.11  4238.4  330.08  4288.7   320.9    4349  313.93
    4359  309.94  4369.1  309.34  4425.7  306.66  4459.5  304.21  4479.6  305.45
  4496.7   301.2  4499.5   300.7  4502.7   301.2  4523.8   301.2    5565   301.2
  5585.1  304.29  5603.3  303.99  5655.5  303.77  5738.4  309.46  5816.3  315.34
  5833.9  318.49  5897.7  322.37  5939.4  325.05  5946.9  327.71  5987.1  331.54
#Mann= 7 ,-1 , 0
  3977.1     .12       0  4425.7     .16       0  4496.7    .033       0
  4502.7     .16       0  4523.8     .05       0  5603.3     .16       0
  5897.7     .12       0
Bank Sta=4369.1,5738.4
XS Rating Curve= 0 ,0
Exp/Cntr=0.3,0.1

Type RM Length L Ch R = 1 ,25791   ,747,747,747
BEGIN DESCRIPTION:
COON CREEK 23.0
END DESCRIPTION:
XS GIS Cut Line= 3
       3683799.6     10733960.19      3683199.61     10734660.19
      3683599.62     10736660.23
#Sta/Elev= 30
    4027  379.37  4048.4  377.82  4083.5  370.47  4091.2   370.4  4232.8  342.96
  4495.1  317.06  4528.4   315.4    4573  313.29  4587.3  310.25  4622.4  309.59
    4657  307.27    4708   304.4  4711.6   301.2  4714.4   300.7  4717.6   301.2
  5989.1   301.2  5999.3  305.34  6023.3   303.4  6080.9  305.12  6152.3  310.08
  6325.5   324.3  6397.1  328.73  6417.5  333.33    6550  336.15    6652  342.67
  6723.4  349.44  6774.4  349.13  6829.3  344.18    6930  341.29  6988.6  339.86
#Mann= 9 ,-1 , 0
    4027     .12       0  4528.4     .16       0    4657     .05       0
  4711.6    .033       0  4717.6     .05       0  6023.3     .16       0
  6325.5     .12       0  6829.3     .05       0    6930     .16       0
Bank Sta=4622.4,6152.3
XS Rating Curve= 0 ,0
Exp/Cntr=0.3,0.1

Type RM Length L Ch R = 1 ,25044   ,648,648,648
BEGIN DESCRIPTION:
COON CREEK 22.0
END DESCRIPTION:
XS GIS Cut Line= 3
      3683699.61     10733910.19      3682699.61     10734210.19
      3680699.65      10733810.2
#Sta/Elev= 30
  3927.1  365.93  4009.8   356.5  4135.9  351.09  4407.8     316  4465.6  309.29
  4512.4  306.09  4553.5  305.12    4561   301.2  4563.7   300.7    4567   301.2
  6006.3   301.2  6041.9   301.2  6062.3  304.54  6174.5  309.67  6296.9  317.72
  6317.3  319.77  6327.5  322.83  6398.9   329.1  6439.6  335.95  6480.4  340.36
  6531.4  340.22  6572.2  337.23  6582.4  339.23  6633.4  341.63  6653.8  340.79
  6745.6  344.77  6776.2  343.68  6837.4   354.9  6888.4   358.1  7010.7  358.82
#Mann= 6 ,-1 , 0
  3927.1     .12       0  4407.8     .16       0  4512.4     .05       0
    4561    .033       0    4567     .05       0  6006.3     .12       0
Bank Sta=4465.6,6174.5
XS Rating Curve= 0 ,0
Exp/Cntr=0.3,0.1

Type RM Length L Ch R = 1 ,24396   ,714,714,714
BEGIN DESCRIPTION:
COON CREEK 21.0
END DESCRIPTION:
XS GIS Cut Line= 3
      3683399.63      10733910.2      3682399.61     10733610.19
      3681799.62     10733410.19
#Sta/Elev= 30
  3982.2   336.5  4040.1  329.89  4103.2  323.35  4149.3  321.65  4159.7  319.62
  4169.3  320.03  4219.9  315.68  4244.4  314.01  4273.7  311.06  4278.9   312.1
    4285  309.99  4326.8  309.84  4431.2  303.51  4449.4  306.14  4454.6  305.71
  4459.5   301.2  4462.2   300.7  4465.5   301.2  4466.7   301.2    5375   301.2
  5395.2   301.2  5405.7  303.77  5458.4  309.97  5500.6  314.75  5521.7  320.03
  5574.4  325.93  5584.9  328.96  5595.5  329.74  5616.5  334.18  5658.7  338.84
#Mann= 8 ,-1 , 0
  3982.2     .12       0  4040.1     .16       0  4219.9     .12       0
  4244.4     .16       0  4459.5    .033       0  4465.5     .16       0
  4466.7     .05       0    5375     .12       0
Bank Sta=4326.8,5458.4
XS Rating Curve= 0 ,0
Exp/Cntr=0.3,0.1

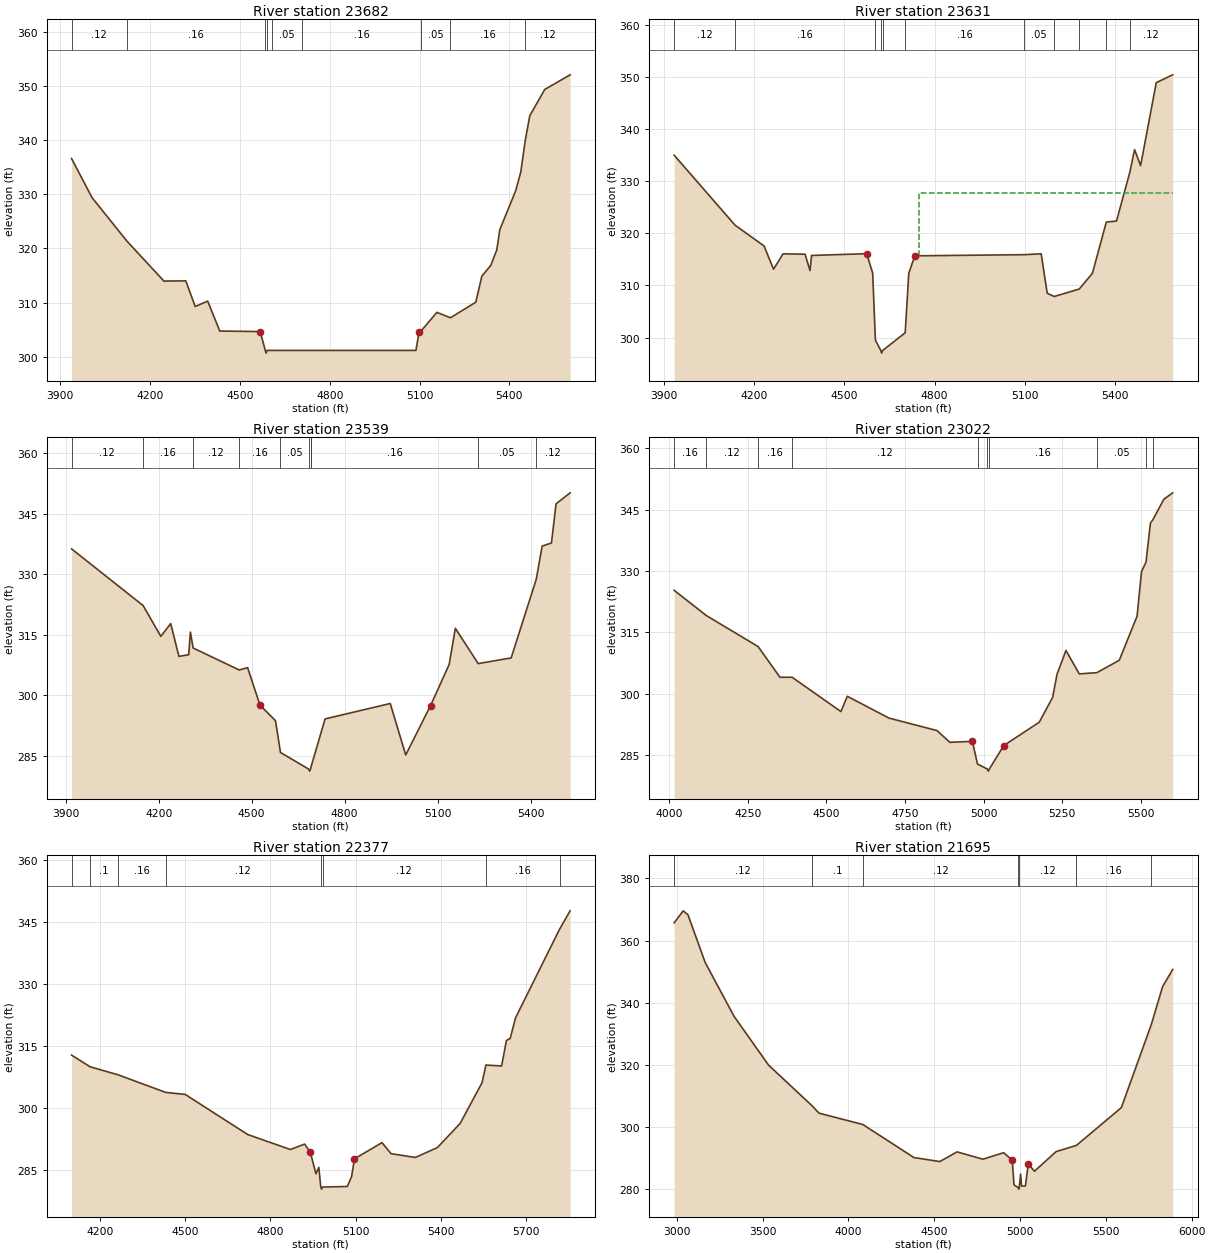
Type RM Length L Ch R = 1 ,23682   ,51,51,51
BEGIN DESCRIPTION:
COON CREEK 20.0
END DESCRIPTION:
XS GIS Cut Line= 3
      3683434.94     10733058.79      3682877.72      10732891.3
      3681794.85     10732920.05
#Sta/Elev= 30
  3937.6  336.58  4005.8  329.39  4122.3  321.37    4246  313.99  4319.1  314.03
  4350.4   309.3  4392.2  310.29  4432.6  304.77  4567.6  304.68  4584.6   301.2
  4587.3   300.7  4590.6   301.2  4608.2   301.2  4707.3   301.2  5087.8   301.2
  5097.8  304.53  5103.8  304.72  5157.8  308.22  5202.9  307.22  5287.8   310.1
  5307.8  314.89  5337.8  316.89  5357.9  319.75  5367.9  323.47  5421.2  330.69
  5437.9   334.1  5452.7  339.86  5467.9  344.47  5517.9  349.33  5602.7  352.03
#Mann= 9 ,-1 , 0
  3937.6     .12       0  4122.3     .16       0  4584.6     .07       0
  4590.6     .16       0  4608.2     .05       0  4707.3     .16       0
  5103.8     .05       0  5202.9     .16       0  5452.7     .12       0
Bank Sta=4567.6,5097.8
XS Rating Curve= 0 ,0
Exp/Cntr=0.3,0.1

Type RM Length L Ch R = 1 ,23631   ,92,92,92
BEGIN DESCRIPTION:
Mapping XS ebec5ef8
END DESCRIPTION:
XS GIS Cut Line= 4
      3683432.38     10733018.44      3682933.67     10732851.77
       3682268.3     10732853.07      3681803.18     10732878.31
#Sta/Elev= 30
  3934.1  334.99  4136.5  321.57  4232.9  317.58  4264.5  313.13  4296.1  316.07
  4369.3     316  4385.6  312.86  4390.9  315.76    4574   316.1    4594  312.36
    4603  299.53    4621  297.53  4623.7  297.03    4627  297.53    4702  300.93
    4714  312.35    4734  315.69  5097.9  315.91    5154  316.07  5174.1  308.52
  5197.2  307.89  5280.6  309.32  5324.3  312.33  5370.6  322.17  5404.4  322.35
  5448.4  331.65  5464.5  336.05  5484.5  332.98  5536.6   348.9  5591.1   350.4
#Mann= 11 ,-1 , 0
  3934.1     .12       0  4136.5     .16       0    4603     .05       0
    4621     .07       0    4627     .05       0    4702     .16       0
  5097.9     .05       0  5197.2     .16       0  5280.6     .05       0
  5370.6     .16       0  5448.4     .12       0
#XS Ineff= 2 , 0
                         4748.07          327.76
Permanent Ineff=
       F       F
Bank Sta=4574,4734
XS Rating Curve= 0 ,0
Exp/Cntr=0.3,0.1

Type RM Length L Ch R = 1 ,23539   ,517,517,517
BEGIN DESCRIPTION:
Mapping XS 2a005200
END DESCRIPTION:
XS GIS Cut Line= 3
      3683442.81     10732933.81      3682976.64     10732780.16
      3681859.47      10732743.7
#Sta/Elev= 30
  3919.1  336.26    4150  322.22  4207.1   314.6  4238.9  317.77  4265.4  309.65
  4297.1  310.06  4302.4  315.66  4311.4  311.72  4460.1  306.28    4487  306.87
    4527  297.57  4577.1  293.72  4593.1  285.86  4684.1  281.74  4686.9  281.24
  4690.1  281.74    4692  282.37  4737.1  294.17  4947.3  297.98  4997.3  285.24
  5077.3  297.45  5137.4  307.64  5157.4   316.6  5231.1  307.86  5337.5  309.27
  5418.5  328.75  5437.5  336.95  5467.5  337.73  5482.3  347.41  5527.7  350.14
#Mann= 10 ,-1 , 0
  3919.1     .12       0    4150     .16       0  4311.4     .12       0
  4460.1     .16       0  4593.1     .05       0  4684.1     .07       0
  4690.1     .05       0    4692     .16       0  5231.1     .05       0
  5418.5     .12       0
Bank Sta=4527,5077.3
XS Rating Curve= 0 ,0
Exp/Cntr=0.3,0.1

Type RM Length L Ch R = 1 ,23022   ,645,645,645
BEGIN DESCRIPTION:
COON CREEK 19.0
END DESCRIPTION:
XS GIS Cut Line= 3
      3683249.61     10732460.19      3682249.61     10732260.19
       3681849.6      10732660.2
#Sta/Elev= 30
  4015.9  325.29  4118.1  319.13  4282.9  311.54  4352.4  304.03  4391.1  304.03
  4546.2  295.65  4566.6  299.38  4699.2  294.05  4852.1  290.99  4892.9  288.12
  4964.3  288.37  4980.7  282.81  5012.3  281.58  5015.1  281.08  5018.3  281.58
    5064  287.32  5177.1  293.04  5219.5   299.1  5233.7  304.77    5262  310.58
  5304.4  304.85  5360.5  305.16  5431.7   308.2  5488.2  318.97  5502.4  329.89
  5516.6  332.18  5530.7  341.73  5538.9  342.61  5573.1  347.54  5601.4  349.13
#Mann= 10 ,-1 , 0
  4015.9     .16       0  4118.1     .12       0  4282.9     .16       0
  4391.1     .12       0  4980.7     .16       0  5012.3     .07       0
  5018.3     .16       0  5360.5     .05       0  5516.6     .16       0
  5538.9     .12       0
Bank Sta=4964.3,5064
XS Rating Curve= 0 ,0
Exp/Cntr=0.3,0.1

Type RM Length L Ch R = 1 ,22377   ,682,682,682
BEGIN DESCRIPTION:
COON CREEK 18.0
END DESCRIPTION:
XS GIS Cut Line= 3
      3682899.65     10731710.19      3681999.61     10731710.19
      3681699.62     10732510.15
#Sta/Elev= 30
  4100.2  312.86    4165  310.05    4264  308.09  4431.1  303.85  4500.2  303.35
  4720.2  293.65  4870.2  290.04  4920.2  291.35  4940.2   289.4  4960.2  284.17
  4970.2  285.73  4977.2  280.96    4980  280.46  4983.2  280.96  5070.6   281.1
  5085.7  283.51  5095.5  287.77  5192.5   291.7  5224.5  289.03    5310  288.12
  5387.4   290.5  5467.5  296.33  5544.9  306.21  5558.3  310.46  5613.5  310.23
  5630.4  316.39  5643.7  316.89  5662.4  321.84  5817.4  343.28  5854.6  347.74
#Mann= 8 ,-1 , 0
  4100.2     .16       0    4165      .1       0    4264     .16       0
  4431.1     .12       0  4977.2     .07       0  4983.2     .12       0
  5558.3     .16       0  5817.4     .12       0
Bank Sta=4940.2,5095.5
XS Rating Curve= 0 ,0
Exp/Cntr=0.3,0.1

Type RM Length L Ch R = 1 ,21695   ,650,650,650
BEGIN DESCRIPTION:
COON CREEK 17.0
END DESCRIPTION:
XS GIS Cut Line= 3
      3683649.64     10731360.19      3681649.61     10731160.19
      3680849.64     10731560.17
#Sta/Elev= 30
    2985  365.71  3037.8  369.56  3065.4   368.3  3165.9  352.94  3334.3  335.63
  3535.3  319.95  3787.1  306.97  3829.2  304.52  4084.4  300.87    4382  290.25
  4532.7  288.96  4633.2  292.07    4784  289.72  4904.6  291.81  4954.8   289.4
  4964.9  281.47  4989.5   280.6  4992.2   280.1  4995.5   280.6  5003.4  284.94
    5009  281.08  5031.3  281.12  5048.1  288.17  5084.4  285.86  5210.2  292.16
  5328.8  294.16  5590.4   306.3  5765.2  333.05  5830.7  345.19  5889.4   350.7
#Mann= 7 ,-1 , 0
    2985     .12       0  3787.1      .1       0  4084.4     .12       0
  4989.5     .07       0  4995.5     .12       0  5328.8     .16       0
  5765.2     .12       0
Bank Sta=4954.8,5048.1
XS Rating Curve= 0 ,0
Exp/Cntr=0.3,0.1

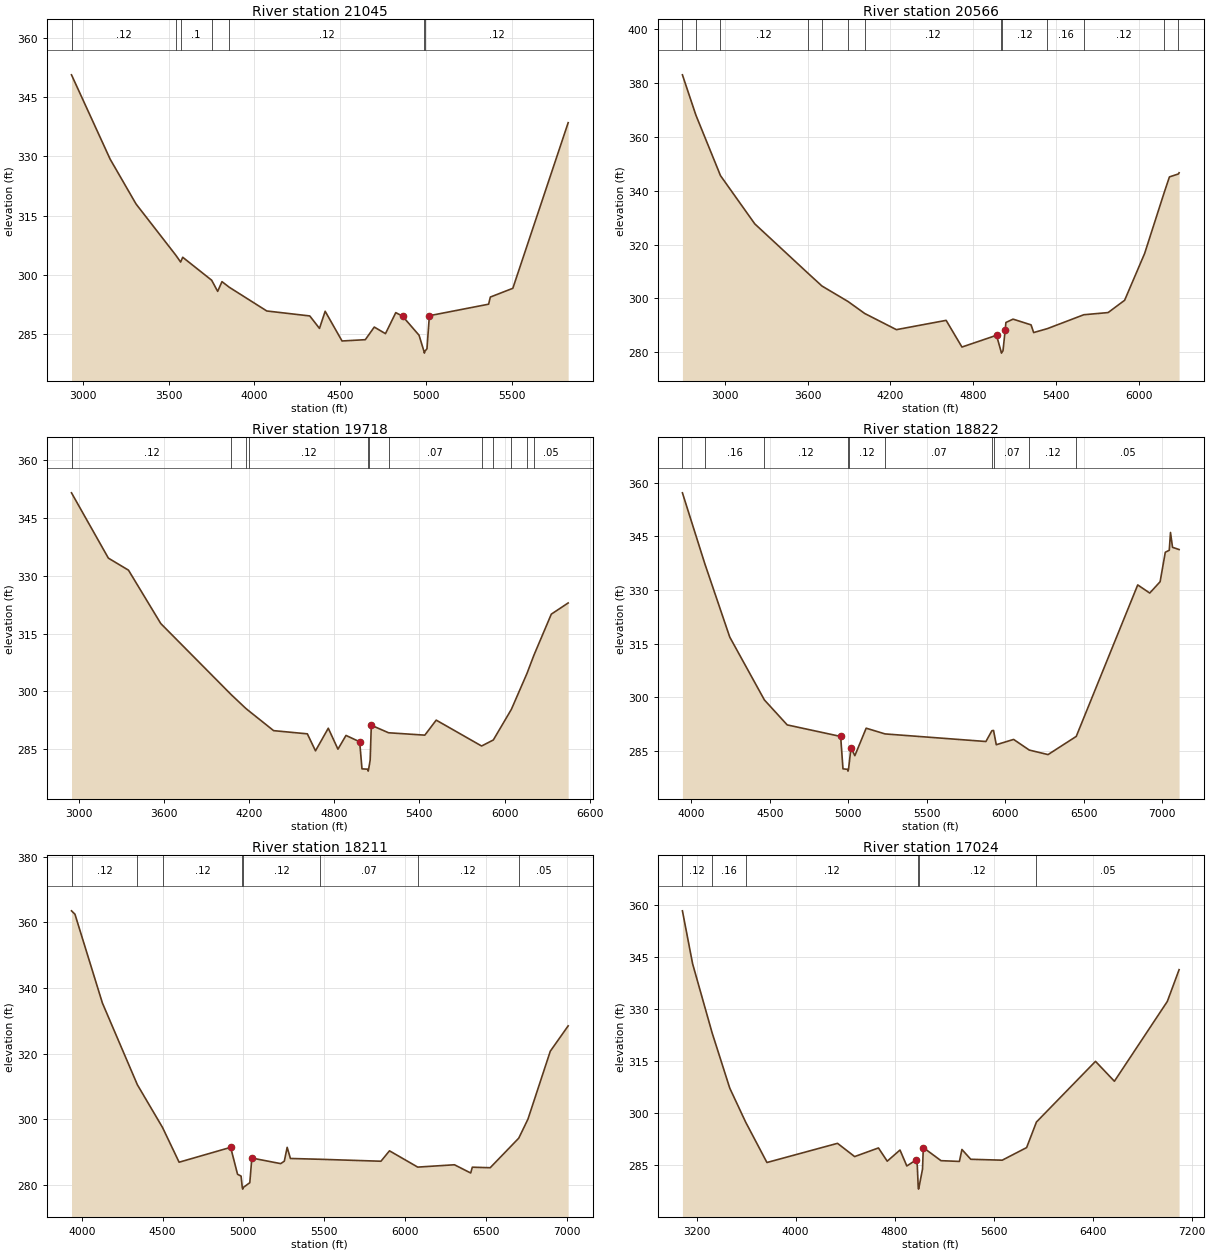
Type RM Length L Ch R = 1 ,21045   ,479,479,479
BEGIN DESCRIPTION:
COON CREEK 16.0
END DESCRIPTION:
XS GIS Cut Line= 3
      3683449.62     10731160.19      3681449.61     10730560.19
      3680649.61     10730660.19
#Sta/Elev= 30
  2934.7  350.69    3160   329.3  3310.6  317.95  3542.5  304.95  3570.6  303.21
  3582.9  304.42  3751.5   298.6  3786.5  295.77  3811.7  298.24  3853.6  296.83
  4072.7   290.8  4323.3  289.54  4379.8  286.38  4412.9  290.73  4511.2  283.19
  4646.9  283.52  4699.1  286.72  4764.4  285.05  4824.4  290.38  4863.6  289.49
  4960.1  284.65  4988.5  280.61  4991.2  280.11  4994.5  280.61  5006.2  281.22
  5020.2   289.6  5365.4  292.52  5375.5  294.33  5506.5  296.55    5829  338.55
#Mann= 7 ,-1 , 0
  2934.7     .12       0  3542.5     .16       0  3570.6      .1       0
  3751.5     .16       0  3853.6     .12       0  4988.5     .07       0
  4994.5     .12       0
Bank Sta=4863.6,5020.2
XS Rating Curve= 0 ,0
Exp/Cntr=0.3,0.1

Type RM Length L Ch R = 1 ,20566   ,848,848,848
BEGIN DESCRIPTION:
COON CREEK 15.0
END DESCRIPTION:
XS GIS Cut Line= 2
      3683835.17     10730882.95      3680433.45     10729716.64
#Sta/Elev= 30
  2693.9  383.06  2791.2  368.13  2969.5  345.63  3217.8  327.71  3600.8  309.48
  3704.1  304.63  3892.5  298.89  4013.9  294.42  4243.2  288.42  4603.3  291.87
  4717.8  281.96    4968  286.32  5001.6   280.2  5004.3   279.7  5007.6   280.2
  5014.9  280.51  5030.6  288.11  5036.1  291.08  5087.8  292.32  5218.2   290.2
  5236.9  287.34  5336.9  288.81  5600.4  293.96  5776.1  294.76  5895.6  299.33
  6040.4   316.7  6182.4  339.38  6220.1  345.15  6285.7  346.26    6290  346.68
#Mann= 13 ,-1 , 0
  2693.9     .12       0  2791.2     .16       0  2969.5     .12       0
  3600.8     .16       0  3704.1     .05       0  3892.5     .16       0
  4013.9     .12       0  5001.6     .07       0  5007.6     .12       0
  5336.9     .16       0  5600.4     .12       0  6182.4     .16       0
  6285.7     .12       0
Bank Sta=4968,5030.6
XS Rating Curve= 0 ,0
Exp/Cntr=0.3,0.1

Type RM Length L Ch R = 1 ,19718   ,896,896,896
BEGIN DESCRIPTION:
COON CREEK 14.0
END DESCRIPTION:
XS GIS Cut Line= 2
      3683883.72      10730598.2      3680800.44      10728938.5
#Sta/Elev= 30
    2947  351.56  3206.9  334.61  3348.8  331.48  3576.3  317.63  4074.6  299.11
    4176  295.59  4201.5  294.83  4371.9  289.82  4609.8  288.99  4667.2  284.58
  4757.4  290.45  4825.5  285.01  4882.3  288.58  4978.8  286.92    4995   279.9
  5035.8  279.81  5038.6  279.31  5041.8  279.81  5052.7  282.18  5060.7  291.22
  5182.2  289.27    5438  288.65  5518.3  292.55  5838.3  285.83    5921   287.4
  6047.9  295.33    6158  304.65  6207.4  309.43  6329.7  320.06  6448.6  322.97
#Mann= 12 ,-1 , 0
    2947     .12       0  4074.6     .16       0    4176     .05       0
  4201.5     .12       0  5035.8     .07       0  5041.8     .12       0
  5182.2     .07       0  5838.3     .12       0    5921     .07       0
  6047.9     .16       0    6158     .12       0  6207.4     .05       0
Bank Sta=4978.8,5060.7
XS Rating Curve= 0 ,0
Exp/Cntr=0.3,0.1

Type RM Length L Ch R = 1 ,18822   ,611,611,611
BEGIN DESCRIPTION:
COON CREEK 13.0
END DESCRIPTION:
XS GIS Cut Line= 3
      3683749.61     10729660.19      3682749.61     10729260.19
       3680749.6     10728660.19
#Sta/Elev= 30
  3942.2  357.15  4084.7  337.37  4243.8  316.84  4464.7  299.26    4610  292.29
  4950.6  289.06  4965.4  280.01  4994.7  279.87  4997.4  279.37  5000.7  279.87
  5016.5  285.88    5041  283.69  5113.2  291.37  5233.5  289.77  5876.2  287.65
  5914.3  290.66  5924.9  290.74  5942.3  286.75  6052.8  288.23  6152.6  285.26
  6272.1  283.99  6451.9  289.07  6843.7  331.41  6920.2  329.14  6986.4  332.31
  7019.4  340.54  7044.7   341.1  7052.5  346.07  7065.5  341.92  7107.3   341.3
#Mann= 10 ,-1 , 0
  3942.2     .12       0  4084.7     .16       0  4464.7     .12       0
  4994.7     .07       0  5000.7     .12       0  5233.5     .07       0
  5914.3     .12       0  5924.9     .07       0  6152.6     .12       0
  6451.9     .05       0
Bank Sta=4950.6,5016.5
XS Rating Curve= 0 ,0
Exp/Cntr=0.3,0.1

Type RM Length L Ch R = 1 ,18211   ,1187,1187,1187
BEGIN DESCRIPTION:
COON CREEK 12.0
END DESCRIPTION:
XS GIS Cut Line= 3
      3683799.61     10729660.19      3683099.61     10728860.19
       3681099.6     10728660.19
#Sta/Elev= 30
  3936.8  363.49  3958.2  362.46  4128.1  335.39  4344.4   310.5  4500.1  297.48
  4602.6   286.9  4921.5  291.43  4964.2  283.22  4986.1  282.67  4993.5   279.2
  4996.2   278.7  4999.5   279.2    5040  280.66  5052.6  288.17    5231  286.47
  5253.6  287.22  5271.2  291.43  5291.3  288.04  5477.1  287.79  5851.5   287.2
  5904.3  290.37    6079  285.41  6306.3  286.12  6406.8  283.61  6416.8  285.38
  6527.4  285.22  6704.2  294.24  6761.1  300.04  6899.2  320.72  7009.8  328.44
#Mann= 8 ,-1 , 0
  3936.8     .12       0  4344.4     .16       0  4500.1     .12       0
  4993.5     .07       0  4999.5     .12       0  5477.1     .07       0
    6079     .12       0  6704.2     .05       0
Bank Sta=4921.5,5052.6
XS Rating Curve= 0 ,0
Exp/Cntr=0.3,0.1

Type RM Length L Ch R = 1 ,17024   ,2398,2398,2398
BEGIN DESCRIPTION:
COON CREEK 11.0
END DESCRIPTION:
XS GIS Cut Line= 4
      3683875.97     10729556.16      3683084.28     10728181.12
      3682674.55     10728042.23      3680716.22     10728417.23
#Sta/Elev= 30
    3085  358.44  3167.4  343.16  3325.6  323.17  3467.7  307.28  3595.7  297.51
    3768  285.84  4338.1  291.37  4476.6  287.55    4669  290.04  4739.9  286.22
  4843.1  289.44  4898.3  284.84    4974   286.6  4982.8  285.01  4990.4  278.66
  4993.1  278.16  4996.4  278.66    5025  283.93  5031.5  290.14  5174.4  286.37
  5323.1  286.15  5343.5   289.6  5414.8  286.77  5669.3  286.51  5866.1  290.14
  5945.6  297.52  6422.8  315.02  6575.5  309.28  7003.1   332.3  7098.2  341.46
#Mann= 6 ,-1 , 0
    3085     .12       0  3325.6     .16       0  3595.7     .12       0
  4990.4     .07       0  4996.4     .12       0  5945.6     .05       0
Bank Sta=4974,5031.5
XS Rating Curve= 0 ,0
Exp/Cntr=0.3,0.1