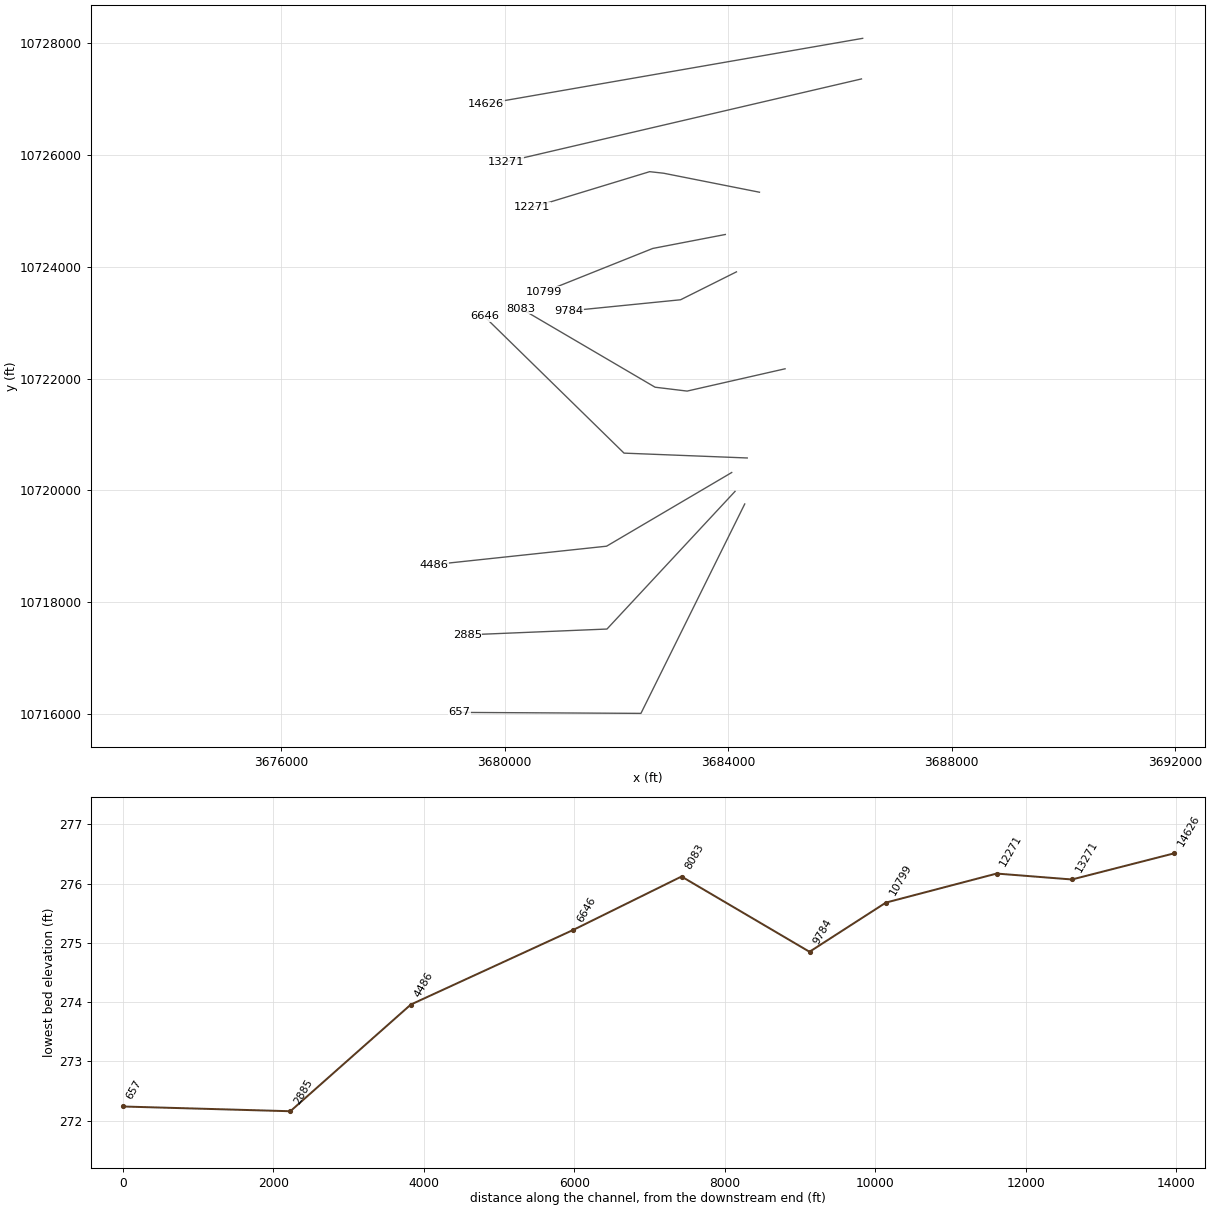
HEC-RAS study COON CREEK.prj: COON CREEK Base Level Engineering

--- COON CREEK.g01 (geometry) --- (continued)

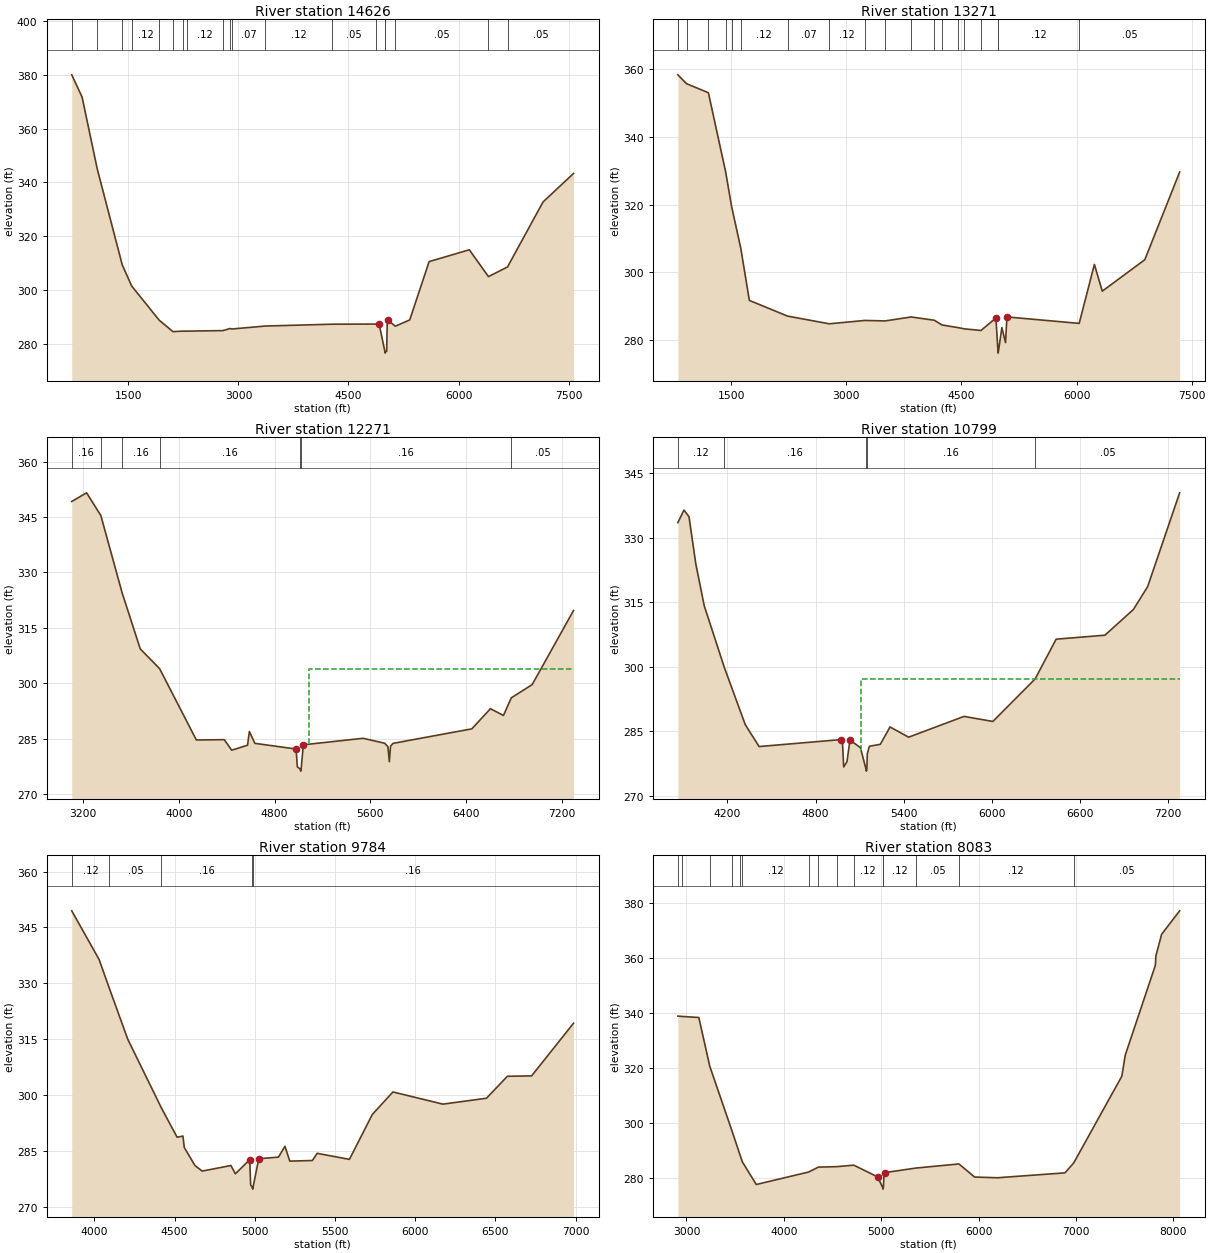
Type RM Length L Ch R = 1 ,14626   ,1355,1355,1355
BEGIN DESCRIPTION:
COON CREEK 10.0
END DESCRIPTION:
XS GIS Cut Line= 2
      3686408.56     10728092.14      3679670.31     10726920.27
#Sta/Elev= 30
   728.2  380.04   869.2  371.77  1075.7  345.04  1415.9   309.4  1544.5   301.5
  1920.8  288.75  2107.6  284.51  2249.3   284.7  2293.9  284.69  2788.7  284.89
  2886.4  285.66  2912.3  285.49  3367.8  286.59  4280.1  287.27  4870.8  287.32
  4919.1  287.21  4997.3  277.01  5000.1  276.51  5003.3  277.01  5020.6  277.15
  5027.5  286.97  5040.9  288.65  5139.1  286.53  5335.3  288.87  5599.2  310.55
  6147.3  314.95  6408.6  304.97  6667.8  308.56  7152.2  332.75  7567.6  343.34
#Mann= 19 ,-1 , 0
   728.2     .16       0  1075.7     .12       0  1415.9     .16       0
  1544.5     .12       0  1920.8     .07       0  2107.6     .12       0
  2249.3     .07       0  2293.9     .12       0  2788.7     .07       0
  2886.4     .12       0  2912.3     .07       0  3367.8     .12       0
  4280.1     .05       0  4870.8     .12       0  4997.3     .07       0
  5003.3     .12       0  5139.1     .05       0  6408.6     .12       0
  6667.8     .05       0
Bank Sta=4919.1,5040.9
XS Rating Curve= 0 ,0
Exp/Cntr=0.3,0.1

Type RM Length L Ch R = 1 ,13271   ,1000,1000,1000
BEGIN DESCRIPTION:
COON CREEK 9.0
END DESCRIPTION:
XS GIS Cut Line= 2
       3686386.9     10727365.15      3680017.57     10725878.61
#Sta/Elev= 30
   803.2  358.34   804.7   358.3   915.6  355.73  1201.2  353.04  1426.3  329.59
  1504.1  319.34  1623.2  307.09  1734.9  291.66  2232.2  287.02  2775.9  284.74
  3239.4  285.73  3506.2  285.59  3843.8  286.76    4146  285.79  4246.3  284.39
  4448.2  283.64  4539.2  283.24  4754.5  282.77    4949  286.46  4975.8  276.57
  4978.5  276.07  4981.8  276.57  5026.4  283.63  5074.1  279.18  5092.7  286.77
  6034.3  284.86  6232.6   302.3  6335.3  294.39  6889.8  303.68  7343.7  329.59
#Mann= 20 ,-1 , 0
   803.2     .16       0   804.7     .12       0   915.6     .16       0
  1201.2     .16       0  1426.3     .12       0  1504.1     .16       0
  1623.2     .12       0  2232.2     .07       0  2775.9     .12       0
  3239.4     .16       0  3506.2     .12       0  3843.8     .16       0
    4146      .1       0  4246.3     .05       0  4448.2     .07       0
  4539.2     .05       0  4754.5     .12       0  4975.8     .07       0
  4981.8     .12       0  6034.3     .05       0
Bank Sta=4949,5092.7
XS Rating Curve= 0 ,0
Exp/Cntr=0.3,0.1

Type RM Length L Ch R = 1 ,12271   ,1472,1472,1472
BEGIN DESCRIPTION:
COON CREEK 8.0
END DESCRIPTION:
XS GIS Cut Line= 4
      3684561.46     10725336.17      3682846.14     10725676.46
      3682596.14     10725704.23      3680496.37     10725063.61
#Sta/Elev= 30
  3104.1   349.2  3228.3  351.54  3347.3   345.4  3525.2  324.47  3676.9  309.28
  3838.9  303.91  4145.9  284.61  4379.5  284.69  4441.5  281.84    4574  283.19
  4589.4  286.91  4635.2  283.69  4980.2  282.16  4990.2  277.35  5015.9  276.67
  5018.7  276.17  5021.9  276.67  5040.5   283.3  5539.9  285.06  5720.4  283.73
    5748  282.76  5759.4  278.73  5769.9  282.95  5791.2  283.69  6449.5  287.62
    6605  293.08  6713.9  291.25  6779.5  296.02  6954.1  299.61  7299.7  319.66
#Mann= 7 ,-1 , 0
  3104.1     .16       0  3347.3     .12       0  3525.2     .16       0
  3838.9     .16       0  5015.9     .07       0  5021.9     .16       0
  6779.5     .05       0
#XS Ineff= 2 , 0
                         5085.23           303.8
Permanent Ineff=
       F       F
Bank Sta=4980.2,5040.5
XS Rating Curve= 0 ,0
Exp/Cntr=0.3,0.1

Type RM Length L Ch R = 1 ,10799   ,1015,1015,1015
BEGIN DESCRIPTION:
COON CREEK 6.0
END DESCRIPTION:
XS GIS Cut Line= 3
      3683950.27     10724579.23      3682651.69     10724329.23
       3680707.2     10723551.44
#Sta/Elev= 30
  3862.4  333.53  3903.8  336.45  3938.1   334.9  3984.9  323.85  4041.9  314.17
  4178.8  299.81  4321.3   286.5  4415.4   281.4  4973.1  283.02  4983.3   282.4
  4991.5  276.66  5013.8  277.88  5034.2  282.91  5105.5  281.14  5143.2  276.18
    5146  275.68  5149.2  276.18  5152.3  279.75  5166.6  281.47  5240.9  281.92
  5307.2  285.96  5433.7  283.58  5810.7  288.42  6007.2  287.24  6295.3  297.15
  6438.1  306.39  6770.3  307.32  6964.2   313.3  7061.1  318.61  7279.1  340.46
#Mann= 5 ,-1 , 0
  3862.4     .12       0  4178.8     .16       0  5143.2     .07       0
  5149.2     .16       0  6295.3     .05       0
#XS Ineff= 2 , 0
                         5111.36          297.03
Permanent Ineff=
       F       F
Bank Sta=4973.1,5034.2
XS Rating Curve= 0 ,0
Exp/Cntr=0.3,0.1

Type RM Length L Ch R = 1 ,9784    ,1701,1701,1701
BEGIN DESCRIPTION:
COON CREEK 4.0
END DESCRIPTION:
XS GIS Cut Line= 3
      3684149.57     10723910.17      3683149.61     10723410.19
      3681149.57     10723210.18
#Sta/Elev= 30
  3859.3  349.47  4029.8  336.43  4093.2  328.74  4208.6  315.03  4418.3  296.61
  4516.1  288.77  4552.4  289.08  4560.8  286.01  4627.9  281.14  4672.6  279.69
  4851.5  281.18  4879.5  278.96  4968.9  282.76  4974.5  275.97  4984.3  275.35
  4987.1  274.85    5025     283  5148.1  283.43  5188.3  286.34  5218.5  282.36
  5359.2  282.52  5389.3  284.45  5590.3  282.83  5733.5   294.9  5861.7   300.9
  6173.2  297.64  6444.6  299.22  6575.2  305.11    6726  305.21  6987.3  319.33
#Mann= 5 ,-1 , 0
  3859.3     .12       0  4093.2     .05       0  4418.3     .16       0
  4984.3     .07       0  4987.1     .16       0
Bank Sta=4968.9,5025
XS Rating Curve= 0 ,0
Exp/Cntr=0.3,0.1

Type RM Length L Ch R = 1 ,8083    ,1437,1437,1437
BEGIN DESCRIPTION:
COON CREEK 3.0
END DESCRIPTION:
XS GIS Cut Line= 4
      3685019.76     10722174.03      3683266.29     10721774.73
      3682693.37     10721844.17      3680297.55     10723250.41
#Sta/Elev= 30
  2912.2  338.98  2958.8  338.85  3127.4  338.46  3239.7  320.78  3469.1  297.16
  3550.9  288.51  3574.7     286  3717.6   277.8  4254.7  282.33  4355.4  284.12
    4543  284.28  4719.1  284.83  4963.9  280.57  5016.5  276.62  5019.2  276.12
  5022.5  276.62  5029.6  281.63  5039.6  282.13  5358.8  283.78  5798.9  285.27
  5960.1  280.51  6194.5  280.25  6888.1  282.03  6977.7  285.63    7472  317.14
  7507.4  324.83  7816.2  357.41    7822  360.89  7880.6   368.7  8065.7  377.22
#Mann= 15 ,-1 , 0
  2912.2     .05       0  2958.8     .16       0  3239.7     .05       0
  3469.1     .16       0  3550.9     .05       0  3574.7     .12       0
  4254.7      .1       0  4355.4     .05       0    4543      .1       0
  4719.1     .12       0  5016.5     .07       0  5022.5     .12       0
  5358.8     .05       0  5798.9     .12       0  6977.7     .05       0
Bank Sta=4963.9,5039.6
XS Rating Curve= 0 ,0
Exp/Cntr=0.3,0.1

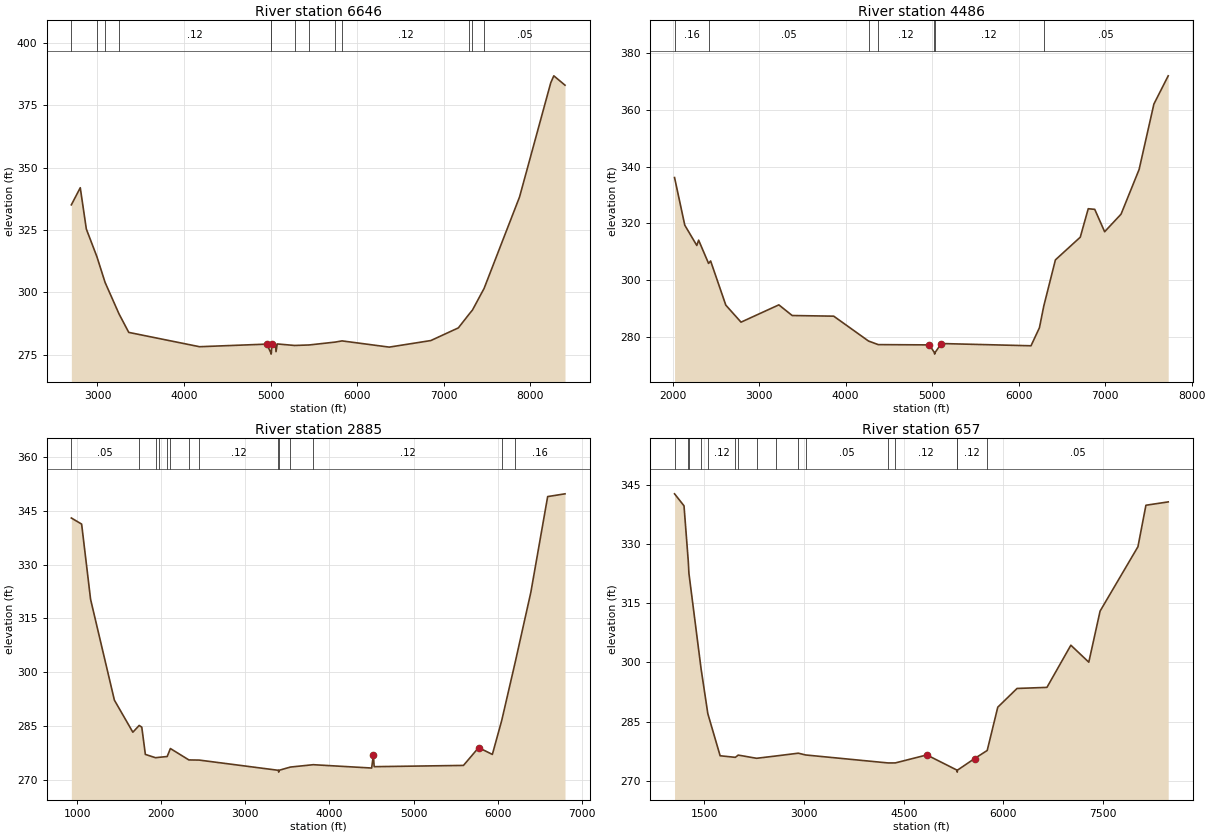
Type RM Length L Ch R = 1 ,6646    ,2160,2160,2160
BEGIN DESCRIPTION:
Mapping XS a3bf54c1
END DESCRIPTION:
XS GIS Cut Line= 3
      3684342.67     10720576.81      3682137.81     10720663.62
      3679637.79     10723111.56
#Sta/Elev= 30
  2697.8  335.06  2800.9  341.92    2871  325.36  2992.7  314.32  3087.9  303.95
  3248.5  291.36  3361.4  283.93  4179.4  278.19  4957.3  279.23  5003.7  275.72
  5006.5  275.22  5009.7  275.72  5013.8  279.44  5056.2  279.27  5063.3  276.21
  5077.5   279.3  5278.1  278.69  5445.6  278.89    5746  280.04  5826.4  280.52
  6371.5  278.03  6852.4  280.66  7170.6  285.74  7299.3  291.44  7333.5  292.88
  7468.3  301.58  7877.8  338.22  8238.4  383.98  8273.8  386.77  8403.3  383.02
#Mann= 13 ,-1 , 0
  2697.8     .16       0  2992.7     .05       0  3087.9     .16       0
  3248.5     .12       0  5003.7     .07       0  5009.7     .12       0
  5278.1     .16       0  5445.6     .12       0    5746     .16       0
  5826.4     .12       0  7299.3     .16       0  7333.5     .08       0
  7468.3     .05       0
Bank Sta=4957.3,5013.8
XS Rating Curve= 0 ,0
Exp/Cntr=0.3,0.1

Type RM Length L Ch R = 1 ,4486    ,1601,1601,1601
BEGIN DESCRIPTION:
Mapping XS 6583095a
END DESCRIPTION:
XS GIS Cut Line= 3
      3684064.91      10720316.4      3681825.31     10718996.95
      3678735.04     10718667.09
#Sta/Elev= 30
  2021.7  336.15  2140.2  319.37  2278.8  312.24  2300.2   314.1    2415  305.91
  2438.8  306.77  2614.5  291.21  2790.2  285.22  3227.5  291.31  3381.7  287.56
  3861.8  287.33  4264.3  278.57  4376.6  277.31  4968.7  277.21  5026.1  274.46
  5028.8  273.96  5032.1  274.46  5106.6  277.69  6142.7   276.9  6240.1  283.25
    6290  290.85  6424.9  307.16    6712  315.14  6804.4  325.17  6879.5  324.95
  6994.1  317.07  7183.9  323.27  7392.4  338.99  7563.4  362.04  7728.9  371.98
#Mann= 7 ,-1 , 0
  2021.7     .16       0    2415     .05       0  4264.3     .16       0
  4376.6     .12       0  5026.1     .07       0  5032.1     .12       0
    6290     .05       0
Bank Sta=4968.7,5106.6
XS Rating Curve= 0 ,0
Exp/Cntr=0.3,0.1

Type RM Length L Ch R = 1 ,2885    ,2228,2228,2228
BEGIN DESCRIPTION:
COON CREEK 2.0
END DESCRIPTION:
XS GIS Cut Line= 3
      3684124.21     10719978.58      3681832.55      10717513.3
      3679333.62     10717409.18
#Sta/Elev= 30
   932.2  343.02  1054.4  341.32  1160.9  320.33  1443.8  292.23  1663.2  283.29
  1738.1  285.17  1769.2  284.71  1811.8   277.1  1932.4  276.18  1969.8  276.28
  2071.3  276.51  2109.3  278.74  2328.9  275.56  2451.6  275.52  3393.8  272.66
  3396.5  272.16  3399.8  272.66    3535  273.57  3806.8  274.23  4501.2   273.3
  4521.2  276.87  4531.2  273.68  5592.2  274.03  5772.3  278.99  5935.8   277.1
  6047.4  286.61  6208.4  302.93  6392.9  322.28    6593  348.99  6799.2  349.76
#Mann= 14 ,-1 , 0
   932.2     .05       0  1738.1     .16       0  1932.4     .12       0
  1969.8     .16       0  2071.3     .07       0  2109.3     .12       0
  2328.9     .07       0  2451.6     .12       0  3393.8     .07       0
  3399.8     .12       0    3535     .07       0  3806.8     .12       0
  6047.4     .05       0  6208.4     .16       0
Bank Sta=4521.2,5772.3
XS Rating Curve= 0 ,0
Exp/Cntr=0.3,0.1

Type RM Length L Ch R = 1 ,657     ,0,0,0
BEGIN DESCRIPTION:
COON CREEK 1.0
END DESCRIPTION:
XS GIS Cut Line= 3
      3684297.83     10719752.89      3682440.19     10716002.88
      3679194.14     10716020.24
#Sta/Elev= 30
    1050  342.65  1192.5  339.62  1256.8  325.58  1266.5  322.53  1449.8  298.34
  1551.2  287.02  1736.2  276.38  1964.8  275.98  2008.7  276.55    2285  275.74
  2573.2  276.32  2912.8  277.03    3023  276.58  4266.2  274.56  4373.3  274.57
  4847.4  276.59  5302.5  272.74  5305.2  272.24  5308.5  272.74  5565.5  275.66
  5756.5  277.72  5915.5  288.67  6205.5  293.41  6655.5  293.68  7015.5  304.35
  7285.5  300.06  7455.5  312.98  8025.5  329.27  8145.5  339.76    8481  340.61
#Mann= 16 ,-1 , 0
    1050     .05       0  1256.8     .16       0  1266.5     .05       0
  1449.8     .16       0  1551.2     .12       0  1964.8     .16       0
  2008.7     .12       0    2285     .16       0  2573.2     .12       0
  2912.8     .16       0    3023     .05       0  4266.2     .16       0
  4373.3     .12       0  5302.5     .07       0  5308.5     .12       0
  5756.5     .05       0
Bank Sta=4847.4,5565.5
XS Rating Curve= 0 ,0
Exp/Cntr=0.3,0.1

Chan Stop Cuts=-1
Use User Specified Reach Order=0
Composite Channel Slope=5

--- COON CREEK.g02 (geometry) ---

Geom Title=Existing Conditions_backup
Program Version=4.10

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
River Reach=COON CREEK      ,Reach-1

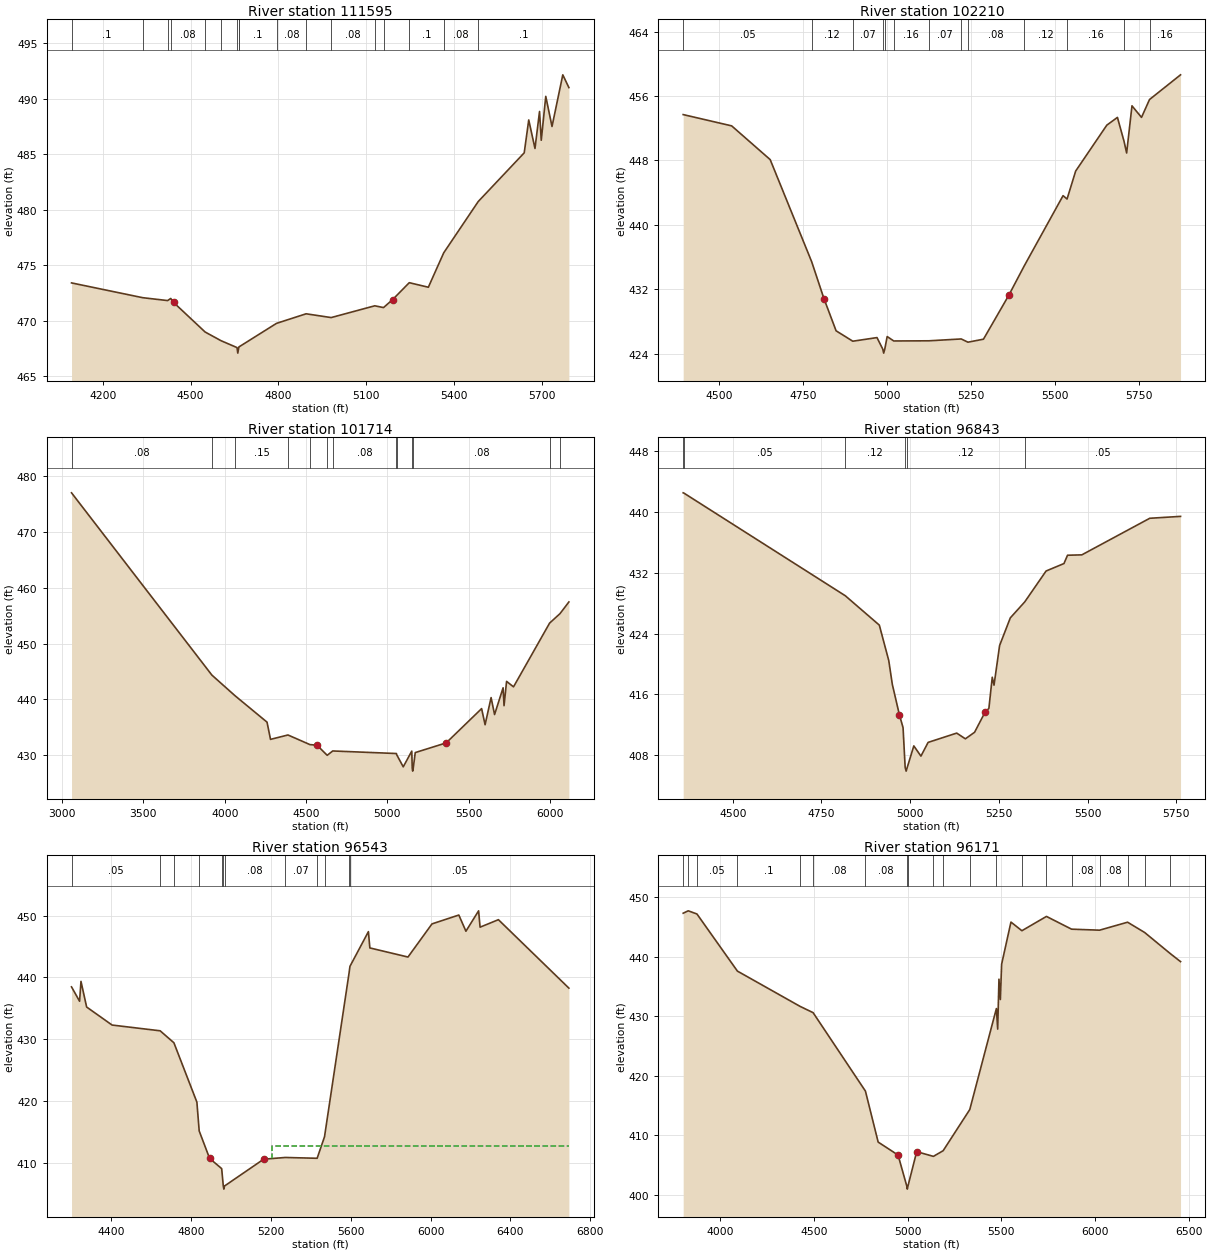
Type RM Length L Ch R = 1 ,111595  ,103,103,103
BEGIN DESCRIPTION:
Mapping XS 255b001d
END DESCRIPTION:
XS GIS Cut Line= 4
      3689516.42     10796512.29      3689284.19     10796132.49
      3689093.22     10795791.78      3688644.28     10795056.56
#Sta/Elev= 30
  4093.8  473.41  4336.6  472.08  4421.7  471.82  4432.3  472.01  4442.2  471.65
  4549.7  468.99  4603.9  468.21  4658.4  467.59  4661.2  467.09  4664.4  467.59
  4664.6  467.64  4793.3  469.77  4894.3  470.63  4979.8  470.29  5128.6  471.35
  5158.4  471.19  5189.2   471.9  5246.3  473.43  5311.4  473.02  5363.9  476.12
  5481.5  480.73  5638.6  485.12    5654  488.08  5675.3  485.51  5690.8  488.84
  5696.7  486.25  5712.1   490.2  5733.4  487.49  5770.2  492.14    5791  490.99
#Mann= 17 ,-1 , 0
  4093.8      .1       0  4336.6     .15       0  4421.7      .1       0
  4432.3     .08       0  4549.7      .1       0  4603.9     .08       0
  4658.4     .07       0  4664.4     .08       0  4664.6      .1       0
  4793.3     .08       0  4894.3      .1       0  4979.8     .08       0
  5128.6      .1       0  5158.4     .08       0  5246.3      .1       0
  5363.9     .08       0  5481.5      .1       0
Bank Sta=4442.2,5189.2
XS Rating Curve= 0 ,0
Exp/Cntr=0.3,0.1

Type RM Length L Ch R = 1 ,102210  ,496,496,496
BEGIN DESCRIPTION:
COON CREEK 158.0
END DESCRIPTION:
XS GIS Cut Line= 4
      3694214.64     10789664.38      3693793.62     10789390.93
      3693602.65     10789360.55      3692918.34     10789746.01
#Sta/Elev= 30
  4392.7  453.69    4537  452.29  4651.7   448.1  4775.1  435.43  4811.8  430.83
    4848  426.83  4897.7  425.54  4969.7  425.99  4986.9  424.56  4989.6  424.06
  4992.9  424.56    5000  426.12  5019.6  425.57  5124.4  425.59  5220.5  425.82
  5240.6  425.42  5286.7  425.79  5361.9  431.23  5407.4  434.84  5523.7  443.62
  5535.6   443.2  5561.3  446.68    5654  452.38  5685.6  453.34  5705.2  450.38
    5713  448.92  5728.9  454.78  5757.3  453.34  5781.1  455.56  5873.5  458.63
#Mann= 13 ,-1 , 0
  4392.7     .05       0  4775.1     .12       0  4897.7     .07       0
  4986.9     .07       0  4992.9     .07       0  5019.6     .16       0
  5124.4     .07       0  5220.5     .16       0  5240.6     .08       0
  5407.4     .12       0  5535.6     .16       0  5705.2     .08       0
  5781.1     .16       0
Bank Sta=4811.8,5361.9
XS Rating Curve= 0 ,0
Exp/Cntr=0.3,0.1

Type RM Length L Ch R = 1 ,101714  ,200,200,200
BEGIN DESCRIPTION:
COON CREEK 157.0
END DESCRIPTION:
XS GIS Cut Line= 2
      3695643.77     10787995.24      3693023.03     10789570.64
#Sta/Elev= 30
  3058.2  477.05  3921.1  444.33  4062.8  440.64  4260.2  435.88  4281.6  432.79
  4388.8  433.58  4524.1  431.85  4567.2  431.75  4630.1  429.93  4663.9  430.71
  5055.8  430.25  5057.3  430.04  5097.6  427.86    5150  430.68  5152.9  427.59
  5155.6  427.09  5158.9  427.59  5171.4  430.42  5361.6  432.16  5579.4  438.31
  5600.8  435.42  5637.7  440.29  5659.1  437.25  5711.5  442.05  5717.3  438.84
  5732.9   443.2  5775.6  442.22  5997.4  453.66  6061.6  455.37    6116  457.46
#Mann= 13 ,-1 , 0
  3058.2     .08       0  3921.1      .1       0  4062.8     .15       0
  4388.8      .1       0  4524.1     .08       0  4630.1      .1       0
  4663.9     .08       0  5055.8     .05       0  5057.3     .08       0
  5152.9     .07       0  5158.9     .08       0  5997.4     .16       0
  6061.6     .08       0
Bank Sta=4567.2,5361.6
XS Rating Curve= 0 ,0
Exp/Cntr=0.3,0.1

Type RM Length L Ch R = 1 ,96843   ,300,300,300
BEGIN DESCRIPTION:
COON CREEK 146.0
END DESCRIPTION:
XS GIS Cut Line= 3
      3693834.53     10785188.08      3693404.85     10784888.61
      3692533.51     10784780.24
#Sta/Elev= 30
  4360.2  442.46  4363.1   442.4  4817.2  428.95    4913   425.1  4939.6  420.45
  4949.7  417.31  4969.8  413.29  4979.9  411.65  4985.8  406.44  4988.6  405.94
  4991.8  406.44  5010.2  409.25  5030.3  407.91  5050.5  409.71  5131.1  410.93
  5155.5  410.18  5181.5  411.04  5211.7  413.74  5221.8  414.16  5231.3  418.26
  5236.3  417.22    5252  422.42  5282.2  426.05  5322.9  428.15    5383   432.2
  5433.4  433.18  5443.5  434.27  5483.8  434.32  5675.2  439.12    5762  439.37
#Mann= 6 ,-1 , 0
  4360.2     .08       0  4363.1     .05       0  4817.2     .12       0
  4985.8     .07       0  4991.8     .12       0  5322.9     .05       0
Bank Sta=4969.8,5211.7
XS Rating Curve= 0 ,0
Exp/Cntr=0.3,0.1

Type RM Length L Ch R = 1 ,96543   ,372,372,372
BEGIN DESCRIPTION:
COON CREEK 145.0
END DESCRIPTION:
XS GIS Cut Line= 4
      3693807.06     10785139.58      3693442.47      10784759.8
      3692747.97     10784173.87      3692018.89     10783412.18
#Sta/Elev= 30
  4202.9  438.48  4243.2  436.16  4250.2  439.37  4278.5  435.23  4405.8  432.32
  4646.5  431.39  4715.3  429.46  4830.4  419.87  4841.9  415.22  4894.1  410.79
  4954.4  409.14  4962.6  406.33  4965.3  405.83  4968.6  406.33  5164.5  410.66
    5273  410.94  5432.3  410.81  5469.2  414.28  5591.6  440.62  5596.6   441.8
  5688.9   447.4  5696.1  444.77    5887   443.3  6007.2  448.65  6141.5  450.08
    6177  447.47  6240.5  450.76  6247.8  448.12  6339.6  449.33  6692.4  438.28
#Mann= 12 ,-1 , 0
  4202.9     .05       0  4646.5     .08       0  4715.3     .05       0
  4841.9     .12       0  4954.4     .08       0  4962.6     .07       0
  4968.6     .08       0    5273     .07       0  5432.3     .05       0
  5469.2     .07       0  5591.6     .08       0  5596.6     .05       0
#XS Ineff= 2 , 0
                         5204.39          412.74
Permanent Ineff=
       F       F
Bank Sta=4894.1,5164.5
XS Rating Curve= 0 ,0
Exp/Cntr=0.3,0.1

Type RM Length L Ch R = 1 ,96171   ,472,472,472
BEGIN DESCRIPTION:
COON CREEK 144.0
END DESCRIPTION:
XS GIS Cut Line= 4
      3694054.47     10785085.34      3693503.24     10784566.66
      3692847.85     10783837.49      3692179.71     10783211.03
#Sta/Elev= 30
  3803.1  447.32  3830.1  447.72  3876.5  447.19  4092.3   437.6  4426.4  431.68
  4496.2  430.62  4775.3  417.45  4843.2  408.89  4949.4  406.71    4996  401.49
  4998.7  400.99    5002  401.49  5048.8  407.28  5137.9  406.49  5189.9  407.44
  5331.9  414.35  5473.9  431.31  5480.8  427.86  5487.6  436.24    5495  432.83
  5501.8  438.75  5551.6  445.83    5610  444.38    5741  446.78  5874.8  444.64
  6024.3  444.47  6173.7  445.81  6264.9  444.08  6400.7  440.56  6456.3  439.19
#Mann= 20 ,-1 , 0
  3803.1     .05       0  3830.1     .08       0  3876.5     .05       0
  4092.3      .1       0  4426.4     .05       0  4496.2     .08       0
  4775.3     .08       0    4996     .07       0    5002     .08       0
  5137.9     .05       0  5189.9     .08       0  5331.9      .1       0
  5473.9     .08       0    5610     .08       0    5741     .08       0
  5874.8     .08       0  6024.3     .08       0  6173.7     .08       0
  6264.9      .1       0  6400.7     .05       0
Bank Sta=4949.4,5048.8
XS Rating Curve= 0 ,0
Exp/Cntr=0.3,0.1