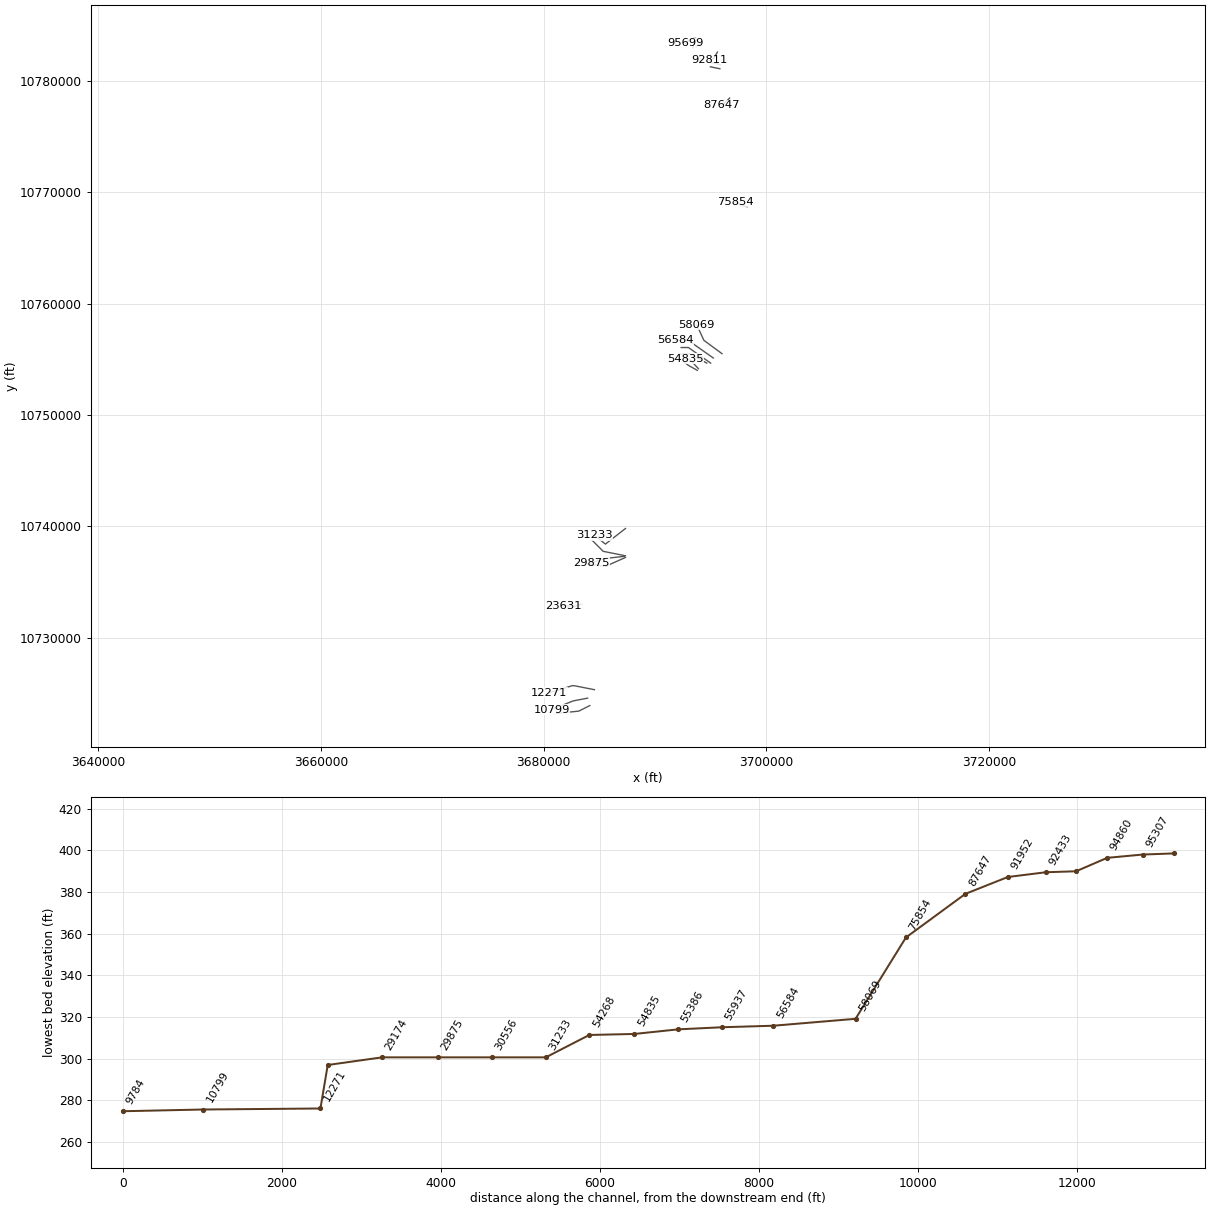
HEC-RAS study COON CREEK.prj: COON CREEK Base Level Engineering

--- COON CREEK.g02 (geometry) --- (continued)

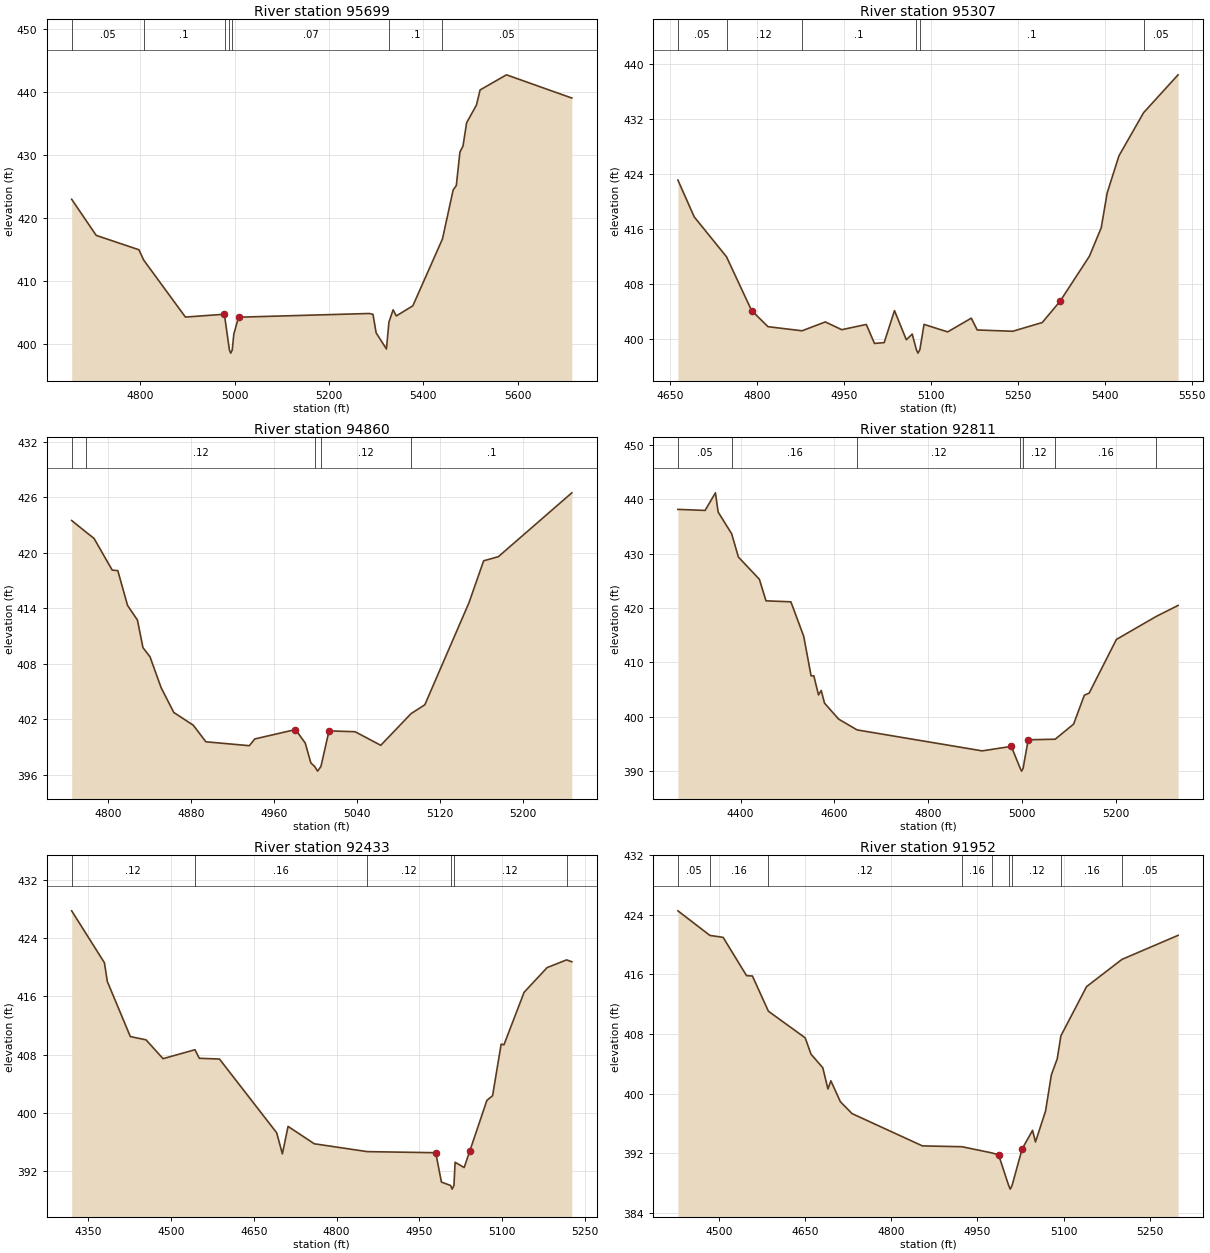
Type RM Length L Ch R = 1 ,95699   ,392,392,392
BEGIN DESCRIPTION:
COON CREEK 143.0
END DESCRIPTION:
XS GIS Cut Line= 3
      3693641.35     10783821.75      3693196.93     10783773.14
      3692733.14     10783371.65
#Sta/Elev= 30
  4654.7  422.97  4706.8  417.23  4797.3  414.95  4807.4  413.31  4895.9  404.25
  4978.4   404.7  4979.2  404.32  4989.2  399.02  4991.9  398.52  4995.2  399.02
  4998.5  401.54  5008.5  404.23    5286  404.82  5293.6  404.68  5300.3  401.74
  5322.1  399.18  5327.4  403.45  5336.3  405.41    5343  404.43  5378.1  406.04
  5440.9  416.67  5463.6  424.46  5470.3  425.16  5477.9  430.46  5484.5  431.45
  5492.1  435.13    5513  437.95  5520.7  440.35  5576.6  442.75  5715.2  439.06
#Mann= 7 ,-1 , 0
  4654.7     .05       0  4807.4      .1       0  4979.2     .07       0
  4989.2     .07       0  4995.2     .07       0  5327.4      .1       0
  5440.9     .05       0
Bank Sta=4978.4,5008.5
XS Rating Curve= 0 ,0
Exp/Cntr=0.3,0.1

Type RM Length L Ch R = 1 ,95307   ,447,447,447
BEGIN DESCRIPTION:
COON CREEK 142.0
END DESCRIPTION:
XS GIS Cut Line= 3
      3693749.58     10783710.16      3693499.61     10783460.19
      3693399.61      10782960.2
#Sta/Elev= 30
  4663.2  423.15  4691.4  417.79  4747.1  411.99  4790.4  404.17  4818.7  401.82
  4877.5  401.22  4917.7  402.51    4946  401.38  4988.4  402.14  5002.6  399.38
  5019.3   399.5  5037.1  404.16  5057.5  399.92  5067.7  400.74  5074.9  398.47
  5077.6  397.97  5080.9  398.47  5088.1  402.15  5128.9  401.06  5169.7  403.06
  5179.9  401.34  5241.1  401.15  5292.1  402.42  5322.7  405.49  5373.6  412.07
    5394  416.21  5404.2  421.26  5424.6  426.68  5467.1  432.95  5526.6  438.46
#Mann= 6 ,-1 , 0
  4663.2     .05       0  4747.1     .12       0  4877.5      .1       0
  5074.9     .07       0  5080.9      .1       0  5467.1     .05       0
Bank Sta=4790.4,5322.7
XS Rating Curve= 0 ,0
Exp/Cntr=0.3,0.1

Type RM Length L Ch R = 1 ,94860   ,391,391,391
BEGIN DESCRIPTION:
COON CREEK 141.0
END DESCRIPTION:
XS GIS Cut Line= 3
      3694099.59     10783310.18      3693849.61     10783210.19
      3693699.59     10783060.17
#Sta/Elev= 30
  4765.3  423.49  4779.4  422.21  4786.8  421.56  4804.3  418.13  4809.7  418.07
  4819.1  414.31  4828.6  412.73  4833.9  409.75  4840.7  408.76  4851.4  405.42
  4863.6  402.74  4882.4  401.36  4894.5  399.57  4936.3  399.15  4941.6  399.88
  4980.7  400.89  4990.1  399.44  4995.5  397.29  4999.2   396.9    5002   396.4
  5005.2   396.9    5013  400.75  5038.1  400.66  5062.8  399.19  5091.9  402.61
  5105.2  403.57  5147.7   414.6  5161.8  419.13    5176  419.58  5246.7  426.48
#Mann= 5 ,-1 , 0
  4765.3     .05       0  4779.4     .12       0  4999.2     .07       0
  5005.2     .12       0  5091.9      .1       0
Bank Sta=4980.7,5013
XS Rating Curve= 0 ,0
Exp/Cntr=0.3,0.1

Type RM Length L Ch R = 1 ,92811   ,378,378,378
BEGIN DESCRIPTION:
COON CREEK 136.0
END DESCRIPTION:
XS GIS Cut Line= 3
      3695607.08     10782590.27      3695277.24     10782021.73
      3694908.34     10781848.13
#Sta/Elev= 30
  4266.7  438.15  4324.6  437.96  4346.6   441.2  4352.4  437.66  4381.2  433.66
  4395.5  429.38  4440.2  425.28  4454.3  421.31  4507.3  421.13  4534.6  414.78
  4550.3   407.5  4556.1  407.51  4566.1  403.99  4571.9   404.8  4578.9  402.47
  4609.1  399.52  4648.3  397.54  4914.7  393.68  4976.6  394.51  4995.7  390.45
  4998.5  389.95  5001.7  390.45  5012.6  395.72  5070.1  395.83  5109.3  398.61
  5132.1  403.92  5142.4  404.32  5200.4   414.2    5285  418.43  5331.7  420.46
#Mann= 7 ,-1 , 0
  4266.7     .05       0  4381.2     .16       0  4648.3     .12       0
  4995.7     .07       0  5001.7     .12       0  5070.1     .16       0
    5285     .05       0
Bank Sta=4976.6,5012.6
XS Rating Curve= 0 ,0
Exp/Cntr=0.3,0.1

Type RM Length L Ch R = 1 ,92433   ,481,481,481
BEGIN DESCRIPTION:
Mapping XS f09daa53
END DESCRIPTION:
XS GIS Cut Line= 2
      3695870.51     10781460.65      3694990.06     10781675.56
#Sta/Elev= 30
  4319.9  427.78  4379.3  420.63  4384.5  418.06  4426.2  410.48  4454.6  410.03
  4485.5  407.44  4543.3  408.67  4551.2  407.49  4587.7  407.39  4691.4  397.24
  4701.7  394.34    4712  398.12  4759.5  395.73  4855.6  394.65  4979.6   394.5
  4989.9  390.46  5006.6  389.99  5009.3  389.49  5012.6  389.99  5014.7  393.19
  5031.1  392.46  5041.4  394.75  5072.3  401.71  5082.6  402.34  5098.1  409.43
  5103.2  409.35  5139.7  416.57  5181.4  419.97  5216.7  421.03  5226.2  420.77
#Mann= 6 ,-1 , 0
  4319.9     .12       0  4543.3     .16       0  4855.6     .12       0
  5006.6     .07       0  5012.6     .12       0  5216.7     .05       0
Bank Sta=4979.6,5041.4
XS Rating Curve= 0 ,0
Exp/Cntr=0.3,0.1

Type RM Length L Ch R = 1 ,91952   ,534,534,534
BEGIN DESCRIPTION:
COON CREEK 135.0
END DESCRIPTION:
XS GIS Cut Line= 2
      3695826.76     10781092.91      3694973.56     10781264.59
#Sta/Elev= 30
  4428.8  424.54  4484.5  421.24  4507.5  420.98  4548.3  415.84  4558.5  415.79
  4586.3  411.07  4650.3   407.5  4660.5   405.3  4680.9  403.49  4689.9  400.64
    4695  401.73  4711.5  398.93  4731.9  397.33  4854.3     393    4923  392.89
  4975.2  392.06  4986.9  391.79  5004.3   387.7  5007.1   387.2  5010.3   387.7
  5027.7  392.57  5045.9  395.09    5051  393.53  5068.5  397.66  5078.7  402.55
  5088.9  404.69  5095.2  407.76  5139.9  414.37  5201.4  418.02  5299.1  421.25
#Mann= 9 ,-1 , 0
  4428.8     .05       0  4484.5     .16       0  4586.3     .12       0
    4923     .16       0  4975.2     .12       0  5004.3     .07       0
  5010.3     .12       0  5095.2     .16       0  5201.4     .05       0
Bank Sta=4986.9,5027.7
XS Rating Curve= 0 ,0
Exp/Cntr=0.3,0.1

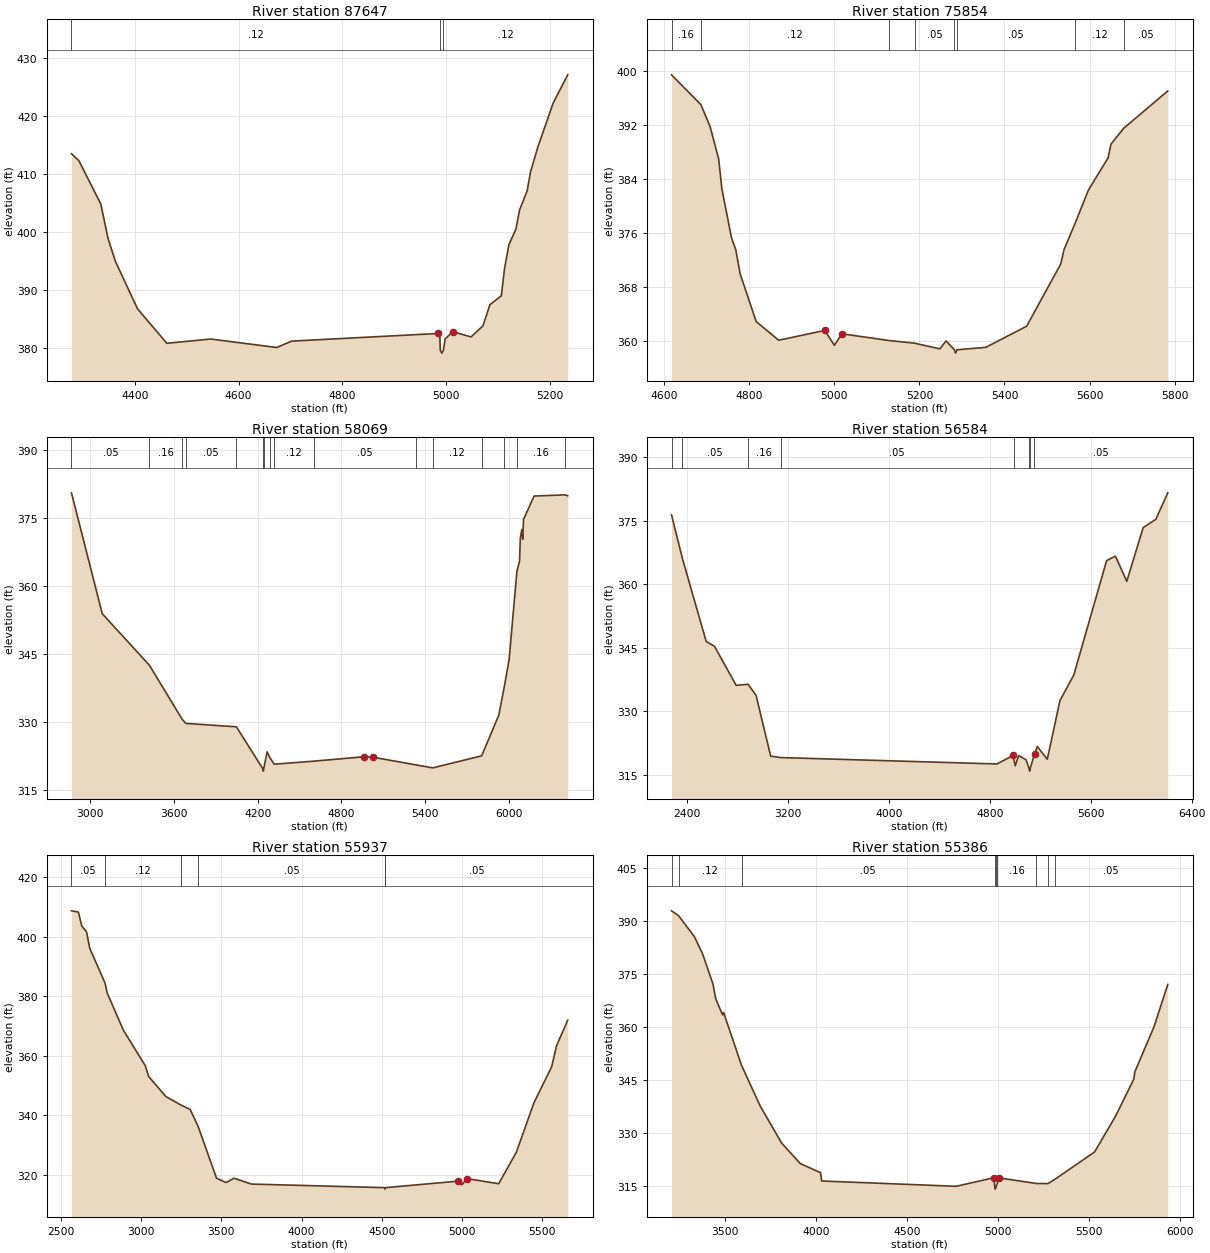
Type RM Length L Ch R = 1 ,87647   ,747,747,747
BEGIN DESCRIPTION:
COON CREEK 126.0
END DESCRIPTION:
XS GIS Cut Line= 3
      3696699.61     10778460.19      3696199.61     10777960.19
      3695999.62      10777810.2
#Sta/Elev= 30
  4277.8   413.5  4291.9  412.33  4334.4  404.82  4348.5  398.83  4362.7  394.91
  4405.1  386.76  4461.7   380.8  4546.5  381.53  4673.8  380.07  4702.1  381.17
  4984.9  382.49    4988  382.49  4989.2   379.6    4992   379.1  4995.2   379.6
  4998.5  381.55    5013  382.79  5048.5   381.9  5071.4  383.81  5084.9  387.46
  5106.8  388.99    5113  393.67  5121.4  397.78  5134.9  400.49  5142.2  403.84
  5156.8  407.16    5163  410.33  5177.6  414.75  5206.8  422.24  5234.9  427.12
#Mann= 3 ,-1 , 0
  4277.8     .12       0  4989.2     .07       0  4995.2     .12       0
Bank Sta=4984.9,5013
XS Rating Curve= 0 ,0
Exp/Cntr=0.3,0.1

Type RM Length L Ch R = 1 ,75854   ,634,634,634
BEGIN DESCRIPTION:
COON CREEK 105.0
END DESCRIPTION:
XS GIS Cut Line= 3
       3698299.6     10768710.19      3697899.61     10768760.19
      3697237.99     10769141.42
#Sta/Elev= 30
  4617.2  399.41  4686.3  394.99  4707.9  391.74    4728  386.96  4735.6  382.52
  4758.3  375.25  4768.4  373.49  4778.4  369.98  4816.2  362.88  4869.1  360.11
  4977.5  361.56  5000.1  359.36  5017.8  361.06  5128.4  360.07  5188.8  359.67
    5248  358.83  5262.7     360  5282.3   358.7  5285.1   358.2  5288.3   358.7
  5355.8  359.05    5452  362.18  5532.5  371.42  5539.7  373.48  5565.9   377.4
  5597.4  382.35  5643.5   387.1  5650.3  389.14  5680.3   391.5  5783.9  397.02
#Mann= 8 ,-1 , 0
  4617.2     .16       0  4686.3     .12       0  5128.4     .16       0
  5188.8     .05       0  5282.3     .07       0  5288.3     .05       0
  5565.9     .12       0  5680.3     .05       0
Bank Sta=4977.5,5017.8
XS Rating Curve= 0 ,0
Exp/Cntr=0.3,0.1

Type RM Length L Ch R = 1 ,58069   ,1033,1033,1033
BEGIN DESCRIPTION:
COON CREEK 73.0
END DESCRIPTION:
XS GIS Cut Line= 3
      3696016.72     10755507.93      3694389.13     10756705.84
       3693751.1      10758099.1
#Sta/Elev= 30
  2866.7  380.59  3087.1  353.92  3425.1  342.53  3659.6   330.6  3685.7  329.71
  4047.6  328.96  4237.3  319.68    4240  319.18  4243.3  319.68  4267.3  323.43
    4288  322.12  4318.3  320.71  4602.2  321.38  4958.4  322.34  5024.4  322.26
  5330.7  320.57  5453.5   319.9  5803.9  322.55    5926  331.51  5966.3  337.88
  6000.5  343.85  6056.2  363.28    6075  365.54  6080.5  370.55  6091.2  372.47
    6098  370.34  6103.5  374.73  6179.2  379.88    6403  380.14    6420  379.93
#Mann= 16 ,-1 , 0
  2866.7     .05       0  3425.1     .16       0  3659.6     .08       0
  3685.7     .05       0  4047.6     .12       0  4237.3     .03       0
  4243.3     .12       0    4288     .05       0  4318.3     .12       0
  4602.2     .05       0  5330.7     .16       0  5453.5     .12       0
  5803.9     .16       0  5966.3     .12       0  6056.2     .16       0
    6403     .05       0
Bank Sta=4958.4,5024.4
XS Rating Curve= 0 ,0
Exp/Cntr=0.3,0.1

Type RM Length L Ch R = 1 ,56584   ,647,647,647
BEGIN DESCRIPTION:
COON CREEK 71.0
END DESCRIPTION:
XS GIS Cut Line= 4
      3695233.49     10755119.76      3693089.39     10756630.18
      3692933.14     10756725.67      3691804.65     10756725.67
#Sta/Elev= 30
  2276.3  376.32  2362.3  366.07  2551.2  346.45  2616.5  345.34    2789  336.11
  2882.8  336.37  2946.6  333.76  3062.4  319.41  3141.5  319.07  4855.8  317.56
    4986  319.59  4987.8  319.03  5001.4  317.15  5028.6  319.54  5086.4  318.57
  5112.6  316.37  5115.4  315.87  5118.6  316.37  5151.7  319.68  5155.6  319.95
  5175.6   321.7  5255.6  318.67  5355.6  332.51  5465.6  338.54  5725.6  365.53
  5795.6  366.59  5885.6  360.66  6015.6  373.33  6115.6  375.27  6210.6  381.53
#Mann= 8 ,-1 , 0
  2276.3     .16       0  2362.3     .05       0  2882.8     .16       0
  3141.5     .05       0  4987.8     .16       0  5112.6     .07       0
  5118.6     .16       0  5151.7     .05       0
Bank Sta=4986,5155.6
XS Rating Curve= 0 ,0
Exp/Cntr=0.3,0.1

Type RM Length L Ch R = 1 ,55937   ,551,551,551
BEGIN DESCRIPTION:
COON CREEK 70.0
END DESCRIPTION:
XS GIS Cut Line= 3
      3694999.58     10754660.21      3692999.61     10756060.19
      3692349.59     10756060.19
#Sta/Elev= 30
  2566.6  408.65  2609.7  408.23  2630.7  403.55  2660.3   401.6  2681.2  395.95
  2776.2  384.33  2788.5  381.11  2889.6  368.58  3026.5  356.59  3047.4  352.99
  3154.7  346.24  3250.3  343.35  3306.4  341.89  3355.5  336.21  3470.3   318.8
  3529.6  317.34  3579.7   318.8  3687.4  316.83  4516.6  315.63  4519.4  315.13
  4522.6  315.63  4971.3  317.79  5000.5  316.65  5027.9  318.68  5227.9  316.95
  5337.9  327.52  5447.9  344.19  5557.9  356.23  5587.9  363.27  5657.9  371.89
#Mann= 6 ,-1 , 0
  2566.6     .05       0  2776.2     .12       0  3250.3     .16       0
  3355.5     .05       0  4516.6     .03       0  4522.6     .05       0
Bank Sta=4971.3,5027.9
XS Rating Curve= 0 ,0
Exp/Cntr=0.3,0.1

Type RM Length L Ch R = 1 ,55386   ,551,551,551
BEGIN DESCRIPTION:
COON CREEK 69.0
END DESCRIPTION:
XS GIS Cut Line= 3
      3694649.63     10754660.18      3693099.61     10755510.19
      3692143.87     10755467.02
#Sta/Elev= 30
    3208  392.76  3246.3  391.41  3333.5  385.45  3379.1  380.54  3436.1     372
  3450.2     368  3488.1  363.37  3493.8  364.06  3592.4   349.1  3694.7  337.63
  3812.5  327.15  3915.1  321.34  4026.5  318.76  4032.2  316.43  4770.5  314.93
  4978.3  317.35  4982.8  314.63  4985.6  314.13  4988.8  314.63    4997  315.86
  5005.8  317.31  5209.7  315.73    5275  315.69  5310.8  316.84  5530.6  324.62
  5646.5   334.8  5746.5  345.26  5751.5  347.26  5856.7  359.96  5932.5  371.96
#Mann= 9 ,-1 , 0
    3208     .05       0  3246.3     .12       0  3592.4     .05       0
  4982.8     .07       0  4988.8     .05       0    4997     .16       0
  5209.7     .05       0    5275     .16       0  5310.8     .05       0
Bank Sta=4978.3,5005.8
XS Rating Curve= 0 ,0
Exp/Cntr=0.3,0.1

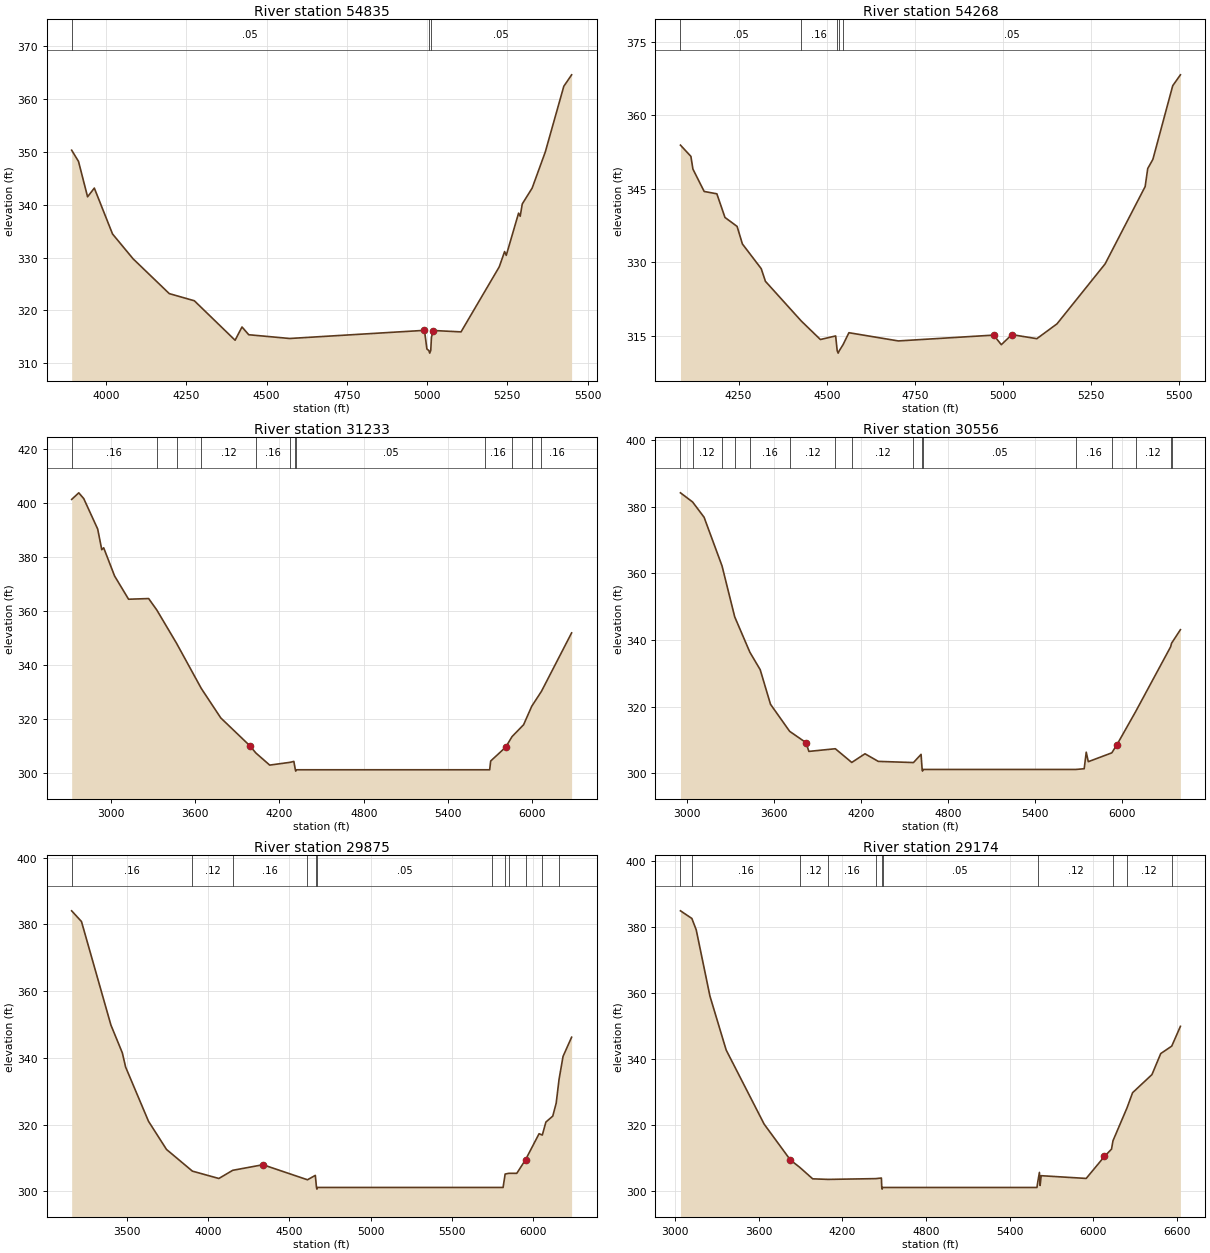
Type RM Length L Ch R = 1 ,54835   ,567,567,567
BEGIN DESCRIPTION:
COON CREEK 68.0
END DESCRIPTION:
XS GIS Cut Line= 3
      3693899.62     10754160.17      3693149.61     10754960.19
      3692699.59     10755060.19
#Sta/Elev= 30
  3892.8  350.32  3914.1   348.2  3942.4   341.5  3963.4  343.15  4020.1  334.47
    4084  329.78  4196.9  323.18    4275  321.83    4402  314.36  4423.5  316.87
  4444.5   315.4    4572  314.69    4992  316.23  4999.6  312.69  5005.6  312.42
  5008.4  311.92  5011.6  312.42  5013.7  314.94  5020.1   316.2  5105.9  315.94
    5225  328.25  5241.7  331.14  5246.8  330.42  5285.2  338.41  5290.3  337.82
  5296.7  340.15  5327.5  343.15  5368.4  349.98  5426.1  362.41  5450.4  364.58
#Mann= 3 ,-1 , 0
  3892.8     .05       0  5005.6     .03       0  5011.6     .05       0
Bank Sta=4992,5020.1
XS Rating Curve= 0 ,0
Exp/Cntr=0.3,0.1

Type RM Length L Ch R = 1 ,54268   ,547,547,547
BEGIN DESCRIPTION:
COON CREEK 67.0
END DESCRIPTION:
XS GIS Cut Line= 3
      3693799.58      10754010.2      3692999.61     10754460.19
      3692599.65     10754760.16
#Sta/Elev= 30
  4085.3  353.91  4114.9  351.61  4120.6  349.02  4152.5  344.45  4188.5  343.97
  4211.5  339.14  4245.9  337.31  4260.9  333.73  4314.4  328.67  4326.2   326.1
    4428  317.98  4482.1  314.21  4525.4  314.94  4529.7  311.93  4532.5  311.43
  4535.7  311.93  4546.2  313.13    4563   315.6  4703.2  313.92  4973.5  315.11
  4995.2  313.15    5025  315.21  5095.9  314.38  5153.1  317.41  5289.6  329.66
  5403.1  345.45  5410.4  349.13    5425     351  5481.3  366.05  5503.1  368.27
#Mann= 5 ,-1 , 0
  4085.3     .05       0    4428     .16       0  4529.7     .03       0
  4535.7     .16       0  4546.2     .05       0
Bank Sta=4973.5,5025
XS Rating Curve= 0 ,0
Exp/Cntr=0.3,0.1

Type RM Length L Ch R = 1 ,31233   ,677,677,677
BEGIN DESCRIPTION:
COON CREEK 31.0
END DESCRIPTION:
XS GIS Cut Line= 3
       3687349.6     10739810.18      3685549.61     10738410.19
      3684549.58     10739210.21
#Sta/Elev= 30
  2719.7  401.36  2770.4   403.8  2805.7  401.67  2905.2  390.37  2934.1  382.74
  2947.7  383.44  3025.5  372.99  3125.1  364.38  3268.1  364.63  3326.3  360.38
  3466.9  348.05  3643.4   331.3    3782   320.4  3987.5  310.17  4032.1   307.4
  4130.4  302.93  4275.6  303.96  4302.4   304.3  4312.9   301.2  4315.7   300.7
  4318.9   301.2  5660.5   301.2  5697.2   301.2  5704.4  304.45  5810.8  309.56
  5856.8  313.51  5938.9   317.9  5996.5  324.71  6065.9  330.26  6280.7  351.91
#Mann= 12 ,-1 , 0
  2719.7     .16       0  3326.3     .12       0  3466.9     .16       0
  3643.4     .12       0  4032.1     .16       0  4275.6     .05       0
  4312.9    .033       0  4318.9     .05       0  5660.5     .16       0
  5856.8     .05       0  5996.5     .12       0  6065.9     .16       0
Bank Sta=3987.5,5810.8
XS Rating Curve= 0 ,0
Exp/Cntr=0.3,0.1

Type RM Length L Ch R = 1 ,30556   ,681,681,681
BEGIN DESCRIPTION:
COON CREEK 30.0
END DESCRIPTION:
XS GIS Cut Line= 3
      3687349.57      10737360.2      3685349.61     10737760.19
       3684349.6      10738760.2
#Sta/Elev= 30
  2952.1  384.11  3035.8  381.37  3115.2  376.79  3239.2  362.21  3326.9  346.93
  3431.7  336.32  3502.8  331.11  3574.1  320.74  3706.3  312.63  3818.9  309.25
  3839.3  306.61  4021.9  307.41  4135.4   303.3  4226.8   305.9  4318.6  303.62
  4561.7  303.27  4614.3  305.73  4621.5   301.2  4624.3   300.7  4627.5   301.2
    5683   301.2  5741.2  301.42  5755.3  306.38  5769.5  303.53    5932  306.18
  5967.5  308.63  6095.9  318.48  6338.3  337.97  6344.6  339.02  6405.9  343.09
#Mann= 16 ,-1 , 0
  2952.1     .05       0  3035.8     .12       0  3239.2     .16       0
  3326.9     .12       0  3431.7     .16       0  3706.3     .12       0
  4021.9     .16       0  4135.4     .12       0  4561.7     .05       0
  4621.5    .033       0  4627.5     .05       0    5683     .16       0
    5932     .05       0  6095.9     .12       0  6338.3     .16       0
  6344.6     .12       0
Bank Sta=3818.9,5967.5
XS Rating Curve= 0 ,0
Exp/Cntr=0.3,0.1

Type RM Length L Ch R = 1 ,29875   ,701,701,701
BEGIN DESCRIPTION:
COON CREEK 29.0
END DESCRIPTION:
XS GIS Cut Line= 3
      3687249.65     10737310.19      3685449.61     10737110.19
      3684249.64      10736710.2
#Sta/Elev= 30
  3160.1  384.09  3220.5  380.88  3401.6  349.87  3472.1   341.5  3492.2  337.26
    3633  321.02  3743.7  312.59    3903  306.09  4065.7  303.89  4151.2  306.34
  4337.3  308.01    4611   303.5  4659.3  304.82  4666.4   301.2  4669.1   300.7
  4672.4   301.2  5746.8   301.2  5814.5   301.2  5827.2  305.22  5849.9  305.44
  5898.8  305.43  5952.9  309.53  6035.9   317.3  6055.9  316.91    6078   320.8
  6120.2  322.59  6141.3  326.47  6158.9  333.61  6183.4  340.46  6236.1  346.22
#Mann= 12 ,-1 , 0
  3160.1     .16       0    3903     .12       0  4151.2     .16       0
    4611     .05       0  4666.4    .033       0  4672.4     .05       0
  5746.8      .1       0  5827.2     .05       0  5849.9     .16       0
  5952.9     .12       0  6055.9     .16       0  6158.9     .12       0
Bank Sta=4337.3,5952.9
XS Rating Curve= 0 ,0
Exp/Cntr=0.3,0.1

Type RM Length L Ch R = 1 ,29174   ,684,684,684
BEGIN DESCRIPTION:
COON CREEK 28.0
END DESCRIPTION:
XS GIS Cut Line= 3
      3687349.61     10737210.19      3685549.61     10736410.19
      3683949.64     10736610.19
#Sta/Elev= 30
  3040.7  385.04  3122.1  382.74  3153.6  379.27    3252  359.17  3368.3  342.84
  3640.5  320.38  3828.6  309.52  3894.3  307.34    3988  303.82  4099.6  303.65
    4439  303.88  4480.4  304.06  4482.9   301.2  4485.6   300.7  4488.9   301.2
    5595   301.2  5601.2  302.97  5612.6  305.77  5617.7  301.81  5625.2  304.77
  5947.7  303.94  6078.7  310.61  6129.1  312.81  6139.8  315.37    6240   325.3
  6280.3  329.93  6418.9  335.41  6481.8  341.78  6560.7  344.04  6622.9  350.03
#Mann= 11 ,-1 , 0
  3040.7     .05       0  3122.1     .16       0  3894.3     .12       0
  4099.6     .16       0    4439     .05       0  4482.9    .033       0
  4488.9     .05       0  5601.2     .12       0  6139.8     .16       0
    6240     .12       0  6560.7     .16       0
Bank Sta=3828.6,6078.7
XS Rating Curve= 0 ,0
Exp/Cntr=0.3,0.1

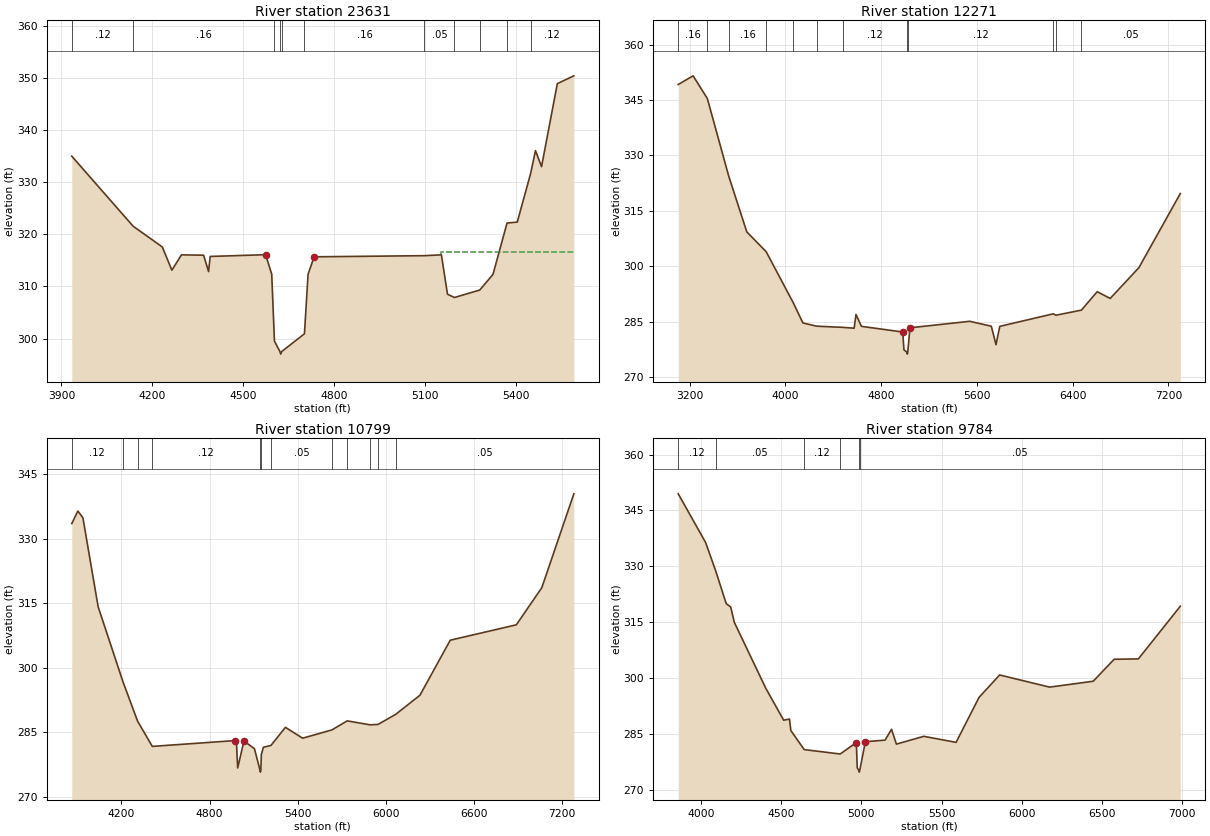
Type RM Length L Ch R = 1 ,23631   ,92,92,92
BEGIN DESCRIPTION:
Mapping XS ebec5ef8
END DESCRIPTION:
XS GIS Cut Line= 4
      3683432.38     10733018.44      3682933.67     10732851.77
       3682268.3     10732853.07      3681803.18     10732878.31
#Sta/Elev= 30
  3934.1  334.99  4136.5  321.57  4232.9  317.58  4264.5  313.13  4296.1  316.07
  4369.3     316  4385.6  312.86  4390.9  315.76    4574   316.1    4594  312.36
    4603  299.53    4621  297.53  4623.7  297.03    4627  297.53    4702  300.93
    4714  312.35    4734  315.69  5097.9  315.91    5154  316.07  5174.1  308.52
  5197.2  307.89  5280.6  309.32  5324.3  312.33  5370.6  322.17  5404.4  322.35
  5448.4  331.65  5464.5  336.05  5484.5  332.98  5536.6   348.9  5591.1   350.4
#Mann= 11 ,-1 , 0
  3934.1     .12       0  4136.5     .16       0    4603     .05       0
    4621     .07       0    4627     .05       0    4702     .16       0
  5097.9     .05       0  5197.2     .16       0  5280.6     .05       0
  5370.6     .16       0  5448.4     .12       0
#XS Ineff= 2 , 0
                         5151.92          316.59
Permanent Ineff=
       F       F
Bank Sta=4574,4734
XS Rating Curve= 0 ,0
Exp/Cntr=0.3,0.1

Type RM Length L Ch R = 1 ,12271   ,1472,1472,1472
BEGIN DESCRIPTION:
COON CREEK 8.0
END DESCRIPTION:
XS GIS Cut Line= 4
      3684561.46     10725336.17      3682846.14     10725676.46
      3682596.14     10725704.23      3680496.37     10725063.61
#Sta/Elev= 30
  3104.1   349.2  3228.3  351.54  3347.3   345.4  3525.2  324.47  3676.9  309.28
  3838.9  303.91  4066.4  290.01  4145.9  284.61  4260.6  283.74  4484.3  283.41
    4574  283.19  4589.4  286.91  4635.2  283.69  4980.2  282.16  4990.2  277.35
  5015.9  276.67  5018.7  276.17  5021.9  276.67  5040.5   283.3  5539.9  285.06
  5720.4  283.73  5759.4  278.73  5791.2  283.69  6238.4  287.09  6260.3   286.7
  6473.3  288.09    6605  293.08  6713.9  291.25  6954.1  299.61  7299.7  319.66
#Mann= 12 ,-1 , 0
  3104.1     .16       0  3347.3     .12       0  3525.2     .16       0
  3838.9     .05       0  4066.4     .12       0  4260.6     .07       0
  4484.3     .12       0  5015.9     .07       0  5021.9     .12       0
  6238.4     .05       0  6260.3     .12       0  6473.3     .05       0
Bank Sta=4980.2,5040.5
XS Rating Curve= 0 ,0
Exp/Cntr=0.3,0.1

Type RM Length L Ch R = 1 ,10799   ,1015,1015,1015
BEGIN DESCRIPTION:
COON CREEK 6.0
END DESCRIPTION:
XS GIS Cut Line= 3
      3683950.27     10724579.23      3682651.69     10724329.23
       3680707.2     10723551.44
#Sta/Elev= 30
  3862.4  333.53  3903.8  336.45  3938.1   334.9  4041.9  314.17  4210.4  296.75
  4310.4  287.54  4410.5  281.67  4973.1  283.02  4983.3   282.4  4991.5  276.66
  5034.2  282.91  5105.5  281.14  5143.2  276.18    5146  275.68  5149.2  276.18
  5152.3  279.75  5166.6  281.47  5218.1   281.9  5316.3   286.1  5433.7  283.58
    5632   285.5    5737  287.61  5893.1  286.69    5947  286.79  6067.1  289.14
  6231.8  293.58  6438.1  306.39  6887.7  309.97  7061.1  318.61  7279.1  340.46
#Mann= 12 ,-1 , 0
  3862.4     .12       0  4210.4     .16       0  4310.4     .08       0
  4410.5     .12       0  5143.2     .07       0  5149.2     .12       0
  5218.1     .05       0    5632     .07       0    5737     .05       0
  5893.1     .12       0    5947     .07       0  6067.1     .05       0
Bank Sta=4973.1,5034.2
XS Rating Curve= 0 ,0
Exp/Cntr=0.3,0.1

Type RM Length L Ch R = 1 ,9784    ,1701,1701,1701
BEGIN DESCRIPTION:
COON CREEK 4.0
END DESCRIPTION:
XS GIS Cut Line= 3
      3684149.57     10723910.17      3683149.61     10723410.19
      3681149.57     10723210.18
#Sta/Elev= 30
  3859.3  349.47  4029.8  336.43  4093.2  328.74  4158.3  320.02  4186.3  319.12
  4208.6  315.03  4404.3  297.38  4516.1  288.77  4552.4  289.08  4560.8  286.01
  4644.2  280.89  4868.1  279.71  4968.9  282.76  4974.5  275.97  4984.3  275.35
  4987.1  274.85  4990.3  275.35    5025     283  5148.1  283.43  5188.3  286.34
  5218.5  282.36  5389.3  284.45  5590.3  282.83  5733.5   294.9  5861.7   300.9
  6173.2  297.64  6444.6  299.22  6575.2  305.11    6726  305.21  6987.3  319.33
#Mann= 6 ,-1 , 0
  3859.3     .12       0  4093.2     .05       0  4644.2     .12       0
  4868.1     .05       0  4984.3     .03       0  4990.3     .05       0
Bank Sta=4968.9,5025
XS Rating Curve= 0 ,0
Exp/Cntr=0.3,0.1