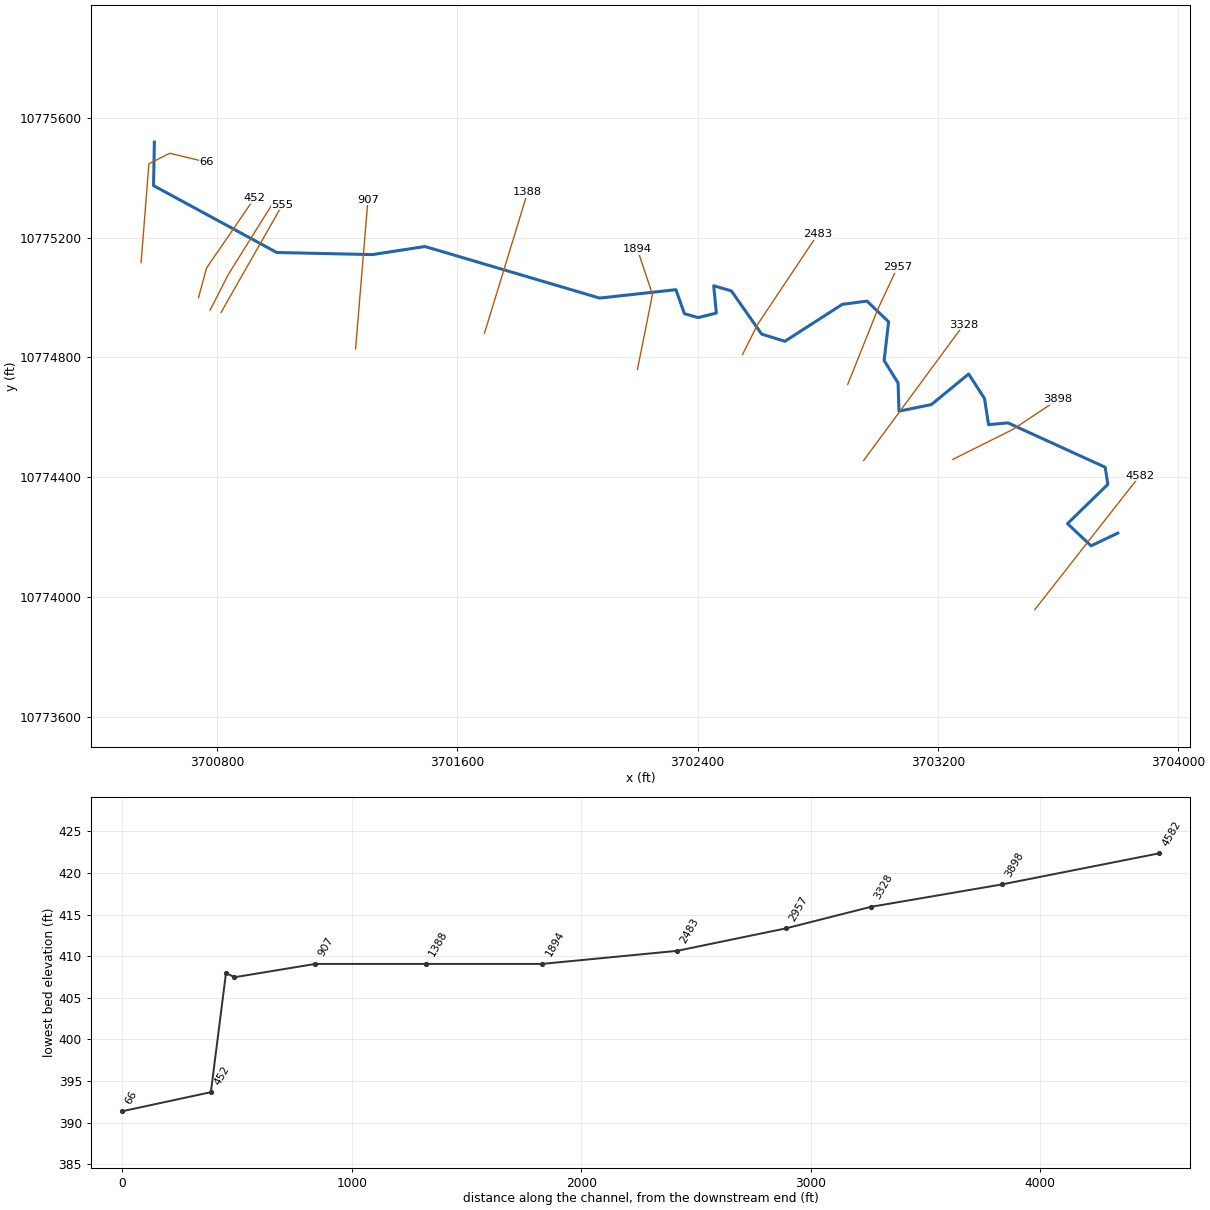
--- DARBY FARMS LAKE.prj (project) ---

Proj Title=DARBY FARMS LAKE Base Level Engineering
Current Plan=p01
Default Exp/Contr=0.3,0.1
English Units
Geom File=g01
Flow File=f01
Plan File=p01
BEGIN DESCRIPTION:
DARBY FARMS LAKE
END DESCRIPTION:

--- DARBY FARMS LAKE.p01 (plan) ---

Plan Title=Multiple Run
Short Identifier=Multiple
Geom File=g01
Flow File=f01
Subcritical Flow
K Sum by GR= 0
Std Step Tol= 0.01
Critical Tol= 0.01
Num of Std Step Trials= 20
Max Error Tol= 0.3
Flow Tol Ratio= 0.001
Split Flow NTrial= 30
Split Flow Tol= 0.02
Split Flow Ratio= 0.02
Log Output Level= 0
Friction Slope Method= 1
Unsteady Friction Slope Method= 2
Unsteady Bridges Friction Slope Method= 1
Parabolic Critical Depth
Global Vel Dist=  1 , 1 , 1
Global Log Level= 0
CheckData=True
Encroach Param= -1, 0, 0, 0
BEGIN DESCRIPTION:
Multiple Run
END DESCRIPTION:

--- DARBY FARMS LAKE.f01 (steady flow) ---

Flow Title=Multiple
Number of Profiles=7
Profile Names=10-year,25-year,50-year,1pct_min,100-year,1pct_plu,500-year
River Rch & RM= DARBY FARMS LAKE,Reach-1,4582
     322     417     491     426     576     778     791
Boundary for River Rch & Prof#=DARBY FARMS LAKE,Reach-1,1
Up Type=0
Dn Type=3
Dn Slope=0.005
Boundary for River Rch & Prof#=DARBY FARMS LAKE,Reach-1,2
Up Type=0
Dn Type=3
Dn Slope=0.005
Boundary for River Rch & Prof#=DARBY FARMS LAKE,Reach-1,3
Up Type=0
Dn Type=3
Dn Slope=0.005
Boundary for River Rch & Prof#=DARBY FARMS LAKE,Reach-1,4
Up Type=0
Dn Type=3
Dn Slope=0.005
Boundary for River Rch & Prof#=DARBY FARMS LAKE,Reach-1,5
Up Type=0
Dn Type=3
Dn Slope=0.005
Boundary for River Rch & Prof#=DARBY FARMS LAKE,Reach-1,6
Up Type=0
Dn Type=3
Dn Slope=0.005
Boundary for River Rch & Prof#=DARBY FARMS LAKE,Reach-1,7
Up Type=0
Dn Type=3
Dn Slope=0.005

--- DARBY FARMS LAKE.g01 (geometry) ---

Geom Title=Existing Conditions

River Reach=DARBY FARMS LAKE,Reach-1
Reach XY= 30
      3703798.42     10774214.34      3703709.75     10774172.00
      3703631.25     10774246.00      3703765.50     10774377.00
      3703756.75     10774434.00      3703433.00     10774582.00
      3703368.50     10774576.00      3703355.00     10774663.00
      3703302.25     10774745.00      3703178.25     10774643.00
      3703070.25     10774621.00      3703067.25     10774715.00
      3703020.75     10774790.00      3703035.75     10774919.00
      3702963.75     10774988.00      3702881.25     10774977.00
      3702690.50     10774854.00      3702613.00     10774878.00
      3702512.25     10775022.00      3702453.50     10775039.00
      3702462.25     10774948.00      3702401.50     10774933.00
      3702356.00     10774946.00      3702327.75     10775026.00
      3702073.75     10774998.00      3701492.25     10775170.00
      3701317.25     10775143.00      3700999.00     10775150.00
      3700588.72     10775372.98      3700591.50     10775518.00

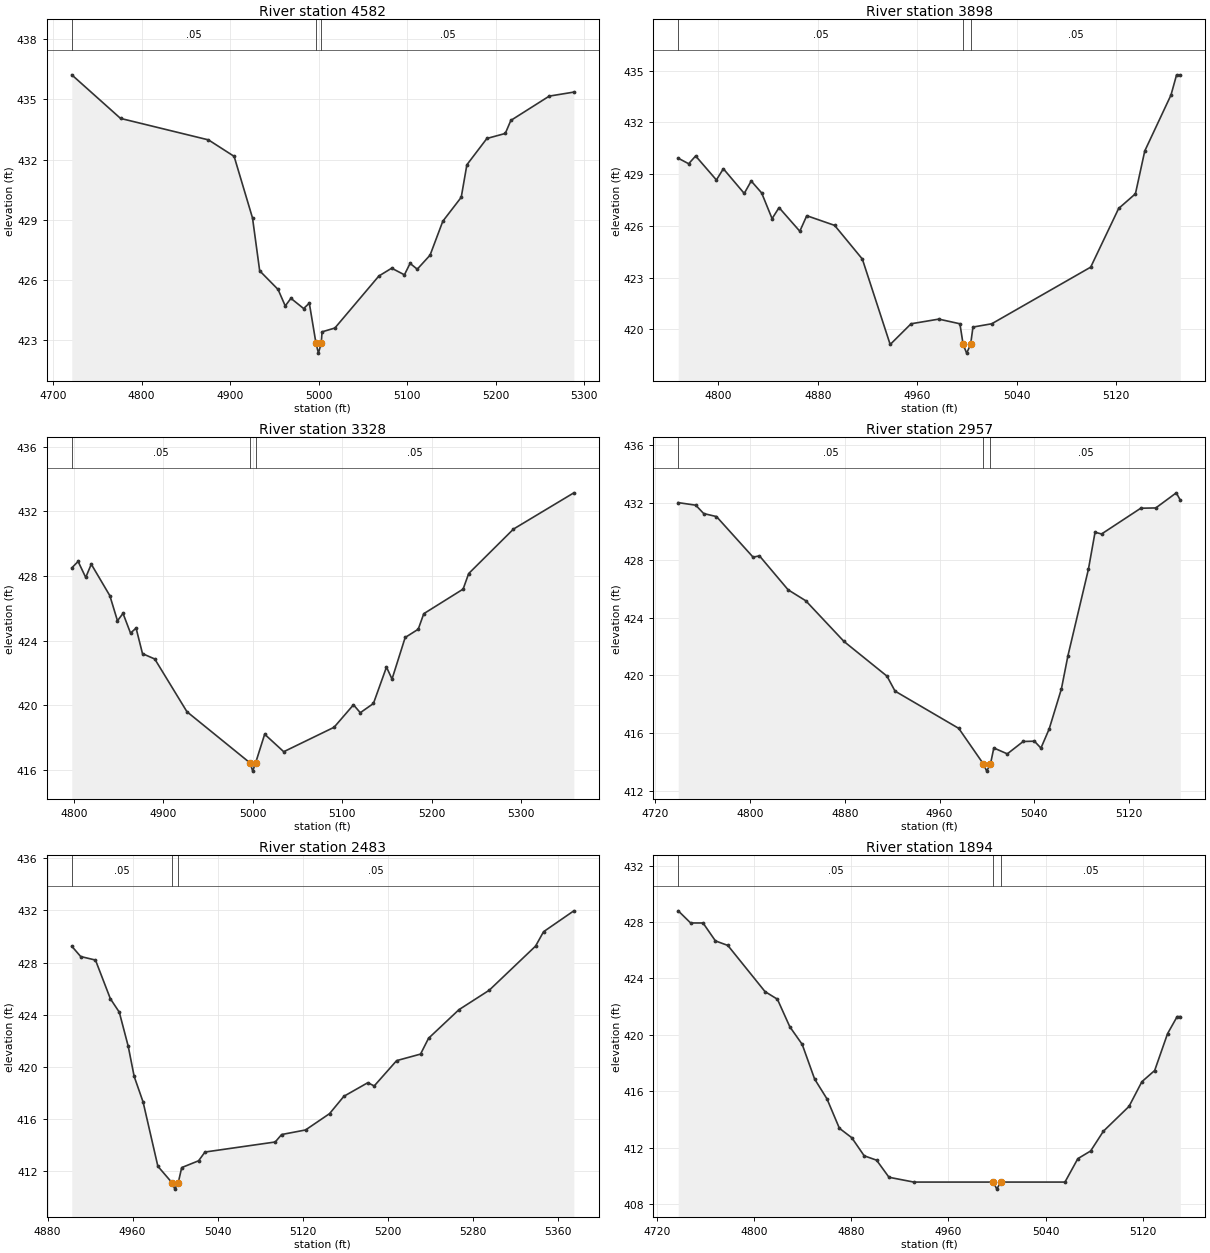
Type RM Length L Ch R = 1,4582,684,684,684
BEGIN DESCRIPTION:
DARBY FARMS LAKE 8.0
END DESCRIPTION:
XS GIS Cut Line= 2
      3703522.51     10773959.45      3703872.36     10774406.28
#Sta/Elev= 30
  4721.0  436.22  4776.1  434.05  4875.5  432.98  4904.5  432.16  4925.3  429.09
  4933.4  426.46  4954.2  425.53  4962.3  424.71  4968.7  425.09  4983.1  424.58
  4989.5  424.85  4997.0  422.86  4999.8  422.36  5003.0  422.86  5003.9  423.42
  5018.4  423.61  5068.1  426.20  5082.6  426.59  5097.0  426.26  5103.4  426.83
  5111.5  426.54  5126.0  427.24  5140.4  428.93  5161.2  430.12  5167.6  431.74
  5190.2  433.05  5211.0  433.30  5217.3  433.95  5260.7  435.16  5288.5  435.36
#Mann=3,-1,0
  4721.0    0.05       0  4997.0    0.03       0  5003.0    0.05       0
Bank Sta=4997,5003
Exp/Cntr=0.3,0.1

Type RM Length L Ch R = 1,3898,570,570,570
BEGIN DESCRIPTION:
DARBY FARMS LAKE 7.0
END DESCRIPTION:
XS GIS Cut Line= 3
      3703249.61     10774460.19      3703449.61     10774560.19
      3703599.62     10774660.20
#Sta/Elev= 30
  4767.8  429.92  4776.2  429.60  4781.8  430.05  4798.5  428.66  4804.1  429.31
  4820.9  427.88  4826.5  428.60  4834.9  427.91  4843.3  426.42  4848.9  427.06
  4865.6  425.69  4871.2  426.59  4893.6  426.03  4915.9  424.08  4938.3  419.13
  4955.1  420.33  4977.4  420.60  4994.4  420.33  4997.0  419.13  4999.8  418.63
  5003.0  419.13  5004.9  420.14  5020.0  420.33  5099.6  423.61  5122.1  427.01
  5135.6  427.86  5143.1  430.34  5164.2  433.58  5168.7  434.75  5171.7  434.75
#Mann=3,-1,0
  4767.8    0.05       0  4997.0    0.03       0  5003.0    0.05       0
Bank Sta=4997,5003
Exp/Cntr=0.3,0.1

Type RM Length L Ch R = 1,3328,371,371,371
BEGIN DESCRIPTION:
DARBY FARMS LAKE 6.0
END DESCRIPTION:
XS GIS Cut Line= 2
      3702952.59     10774456.46      3703285.26     10774908.68
#Sta/Elev= 30
  4797.5  428.50  4804.6  428.90  4813.1  427.91  4819.3  428.73  4840.1  426.78
  4848.6  425.23  4854.8  425.69  4863.2  424.47  4869.4  424.78  4876.6  423.20
  4890.3  422.87  4926.3  419.61  4997.0  416.44  4999.8  415.94  5003.0  416.44
  5013.2  418.22  5034.5  417.14  5090.8  418.65  5112.5  420.04  5120.1  419.55
  5134.8  420.12  5149.4  422.37  5155.6  421.63  5170.3  424.20  5184.9  424.71
  5191.1  425.67  5235.1  427.19  5241.3  428.15  5291.4  430.90  5358.9  433.14
#Mann=3,-1,0
  4797.5    0.05       0  4997.0    0.03       0  5003.0    0.05       0
Bank Sta=4997,5003
Exp/Cntr=0.3,0.1

Type RM Length L Ch R = 1,2957,474,474,474
BEGIN DESCRIPTION:
DARBY FARMS LAKE 5.0
END DESCRIPTION:
XS GIS Cut Line= 3
      3702899.63     10774710.23      3702999.61     10774960.19
      3703065.00     10775100.49
#Sta/Elev= 30
  4739.3  432.01  4754.1  431.83  4760.8  431.25  4771.6  431.04  4802.5  428.22
  4807.9  428.31  4832.1  425.95  4847.0  425.19  4879.3  422.36  4915.6  419.95
  4922.4  418.91  4976.2  416.32  4997.0  413.85  4999.8  413.35  5003.0  413.85
  5005.8  414.96  5017.2  414.55  5030.6  415.41  5040.1  415.43  5045.6  414.95
  5052.6  416.29  5062.9  419.07  5068.4  421.37  5085.7  427.38  5091.3  429.95
  5096.8  429.83  5129.9  431.62  5142.6  431.64  5159.9  432.69  5163.3  432.18
#Mann=3,-1,0
  4739.3    0.05       0  4997.0    0.03       0  5003.0    0.05       0
Bank Sta=4997,5003
Exp/Cntr=0.3,0.1

Type RM Length L Ch R = 1,2483,589,589,589
BEGIN DESCRIPTION:
DARBY FARMS LAKE 4.0
END DESCRIPTION:
XS GIS Cut Line= 3
      3702549.62     10774810.21      3702599.61     10774910.19
      3702799.59     10775210.16
#Sta/Elev= 30
  4902.8  429.25  4911.2  428.46  4925.1  428.19  4939.1  425.23  4947.5  424.20
  4955.9  421.59  4961.5  419.28  4969.9  417.32  4983.8  412.40  4997.0  411.15
  4999.8  410.65  5003.0  411.15  5006.2  412.30  5022.1  412.82  5028.1  413.49
  5094.2  414.26  5100.2  414.83  5122.7  415.18  5145.3  416.43  5158.8  417.76
  5181.3  418.80  5187.3  418.55  5208.4  420.49  5230.9  420.99  5238.4  422.20
  5267.0  424.39  5295.5  425.88  5339.1  429.26  5346.6  430.36  5375.1  431.96
#Mann=3,-1,0
  4902.8    0.05       0  4997.0    0.03       0  5003.0    0.05       0
Bank Sta=4997,5003
Exp/Cntr=0.3,0.1

Type RM Length L Ch R = 1,1894,506,506,506
BEGIN DESCRIPTION:
DARBY FARMS LAKE 3.0
END DESCRIPTION:
XS GIS Cut Line= 3
      3702199.60     10774760.16      3702249.61     10775010.19
      3702199.61     10775160.19
#Sta/Elev= 30
  4737.7  428.79  4747.9  427.93  4758.1  427.93  4768.3  426.66  4778.5  426.34
  4809.1  423.07  4819.3  422.53  4829.5  420.58  4839.7  419.33  4849.9  416.88
  4860.1  415.47  4870.3  413.39  4880.5  412.72  4890.7  411.44  4900.9  411.13
  4911.1  409.92  4931.5  409.58  4997.0  409.58  4999.8  409.08  5003.0  409.58
  5055.9  409.58  5066.5  411.24  5077.0  411.78  5087.5  413.18  5108.6  414.94
  5119.2  416.69  5129.7  417.48  5140.3  420.09  5148.2  421.30  5150.8  421.30
#Mann=3,-1,0
  4737.7    0.05       0  4997.0   0.033       0  5003.0    0.05       0
Bank Sta=4997,5003
Exp/Cntr=0.3,0.1

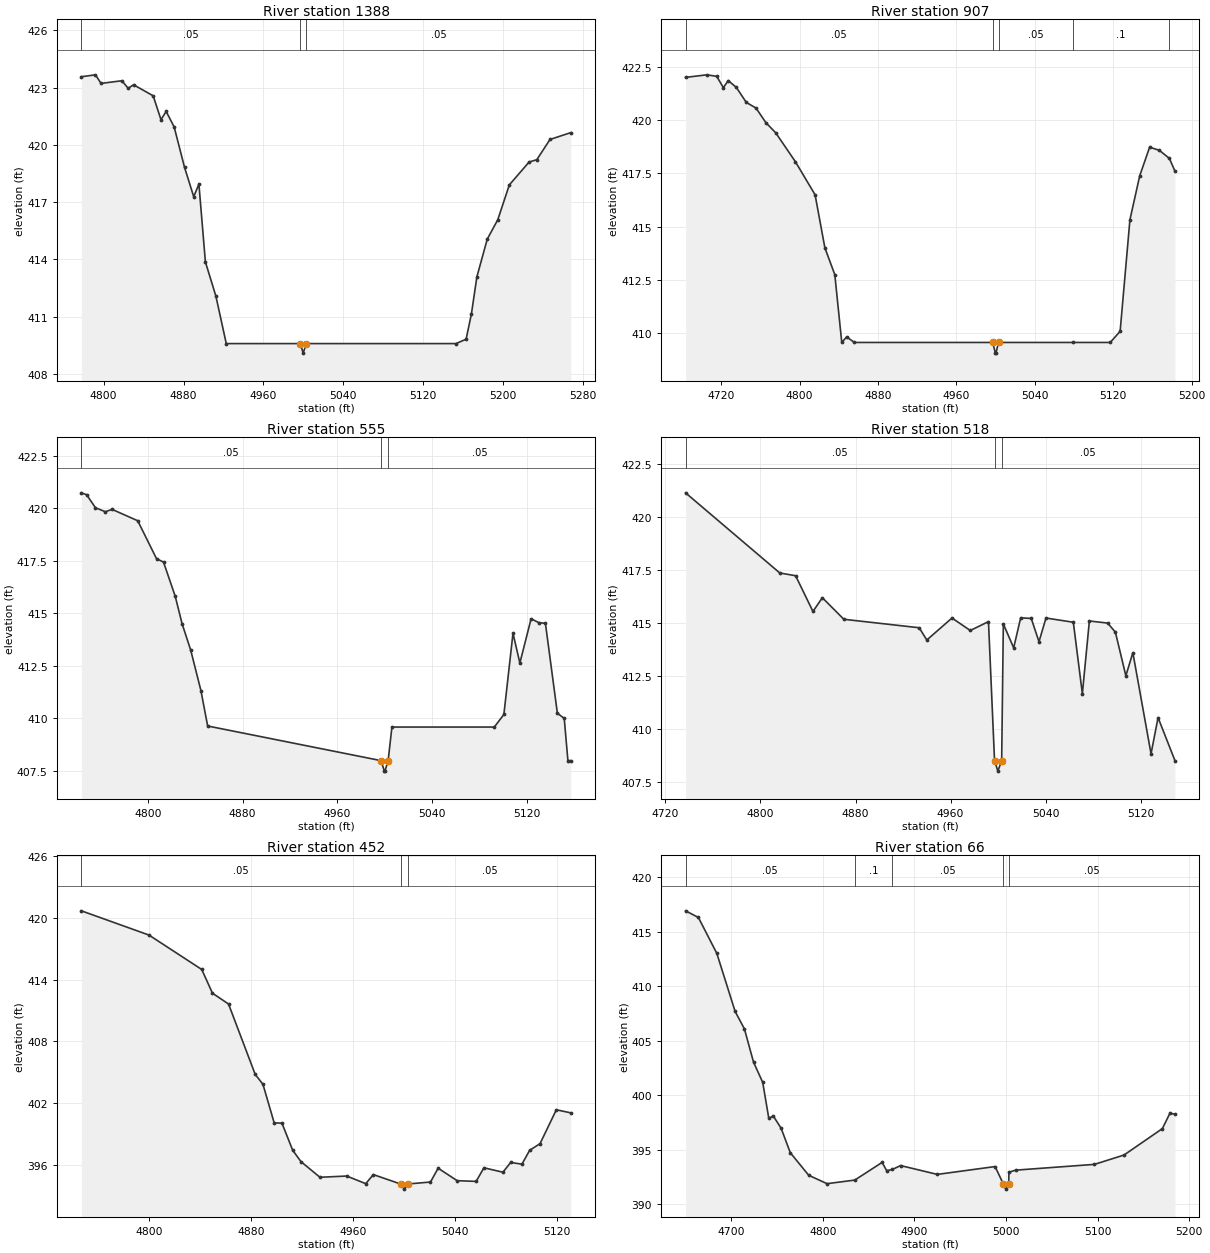
Type RM Length L Ch R = 1,1388,481,481,481
BEGIN DESCRIPTION:
Mapping XS 9c36bc2f
END DESCRIPTION:
XS GIS Cut Line= 2
      3701690.57     10774881.39      3701833.79     10775350.10
#Sta/Elev= 30
  4777.7  423.57  4791.8  423.67  4797.4  423.22  4818.3  423.36  4824.6  422.96
  4829.9  423.15  4849.6  422.57  4857.4  421.32  4862.6  421.75  4870.6  420.94
  4881.0  418.82  4890.2  417.28  4895.4  417.94  4901.9  413.86  4912.4  412.07
  4922.8  409.58  4997.0  409.58  4999.8  409.08  5003.0  409.58  5152.9  409.58
  5163.0  409.81  5168.3  411.13  5173.8  413.08  5184.2  415.06  5194.7  416.07
  5206.3  417.90  5226.1  419.10  5233.8  419.22  5247.0  420.28  5267.8  420.64
#Mann=3,-1,0
  4777.7    0.05       0  4997.0   0.033       0  5003.0    0.05       0
Bank Sta=4997,5003
Exp/Cntr=0.3,0.1

Type RM Length L Ch R = 1,907,352,352,352
BEGIN DESCRIPTION:
Mapping XS 329d8a0d
END DESCRIPTION:
XS GIS Cut Line= 2
      3701261.29     10774828.54      3701302.48     10775325.93
#Sta/Elev= 30
  4683.8  422.00  4705.5  422.12  4715.6  422.05  4722.3  421.52  4727.3  421.85
  4735.6  421.53  4745.7  420.83  4755.7  420.56  4765.7  419.88  4775.8  419.40
  4795.8  418.05  4815.9  416.50  4825.9  414.01  4836.0  412.76  4843.1  409.58
  4848.1  409.84  4856.0  409.58  4997.0  409.58  4999.8  409.08  5000.3  409.08
  5003.0  409.58  5078.6  409.58  5116.9  409.58  5127.0  410.10  5137.0  415.33
  5147.0  417.39  5157.1  418.73  5167.1  418.58  5177.3  418.20  5182.9  417.61
#Mann=5,-1,0
  4683.8    0.05       0  4997.0   0.033       0  5003.0    0.05       0
  5078.6     0.1       0  5177.3    0.05       0
Bank Sta=4997,5003
Exp/Cntr=0.3,0.1

Type RM Length L Ch R = 1,555,37,37,37
BEGIN DESCRIPTION:
Mapping XS 21025480
END DESCRIPTION:
XS GIS Cut Line= 2
      3700813.32     10774949.85      3701017.78     10775309.27
#Sta/Elev= 29
  4743.8  420.74  4748.2  420.65  4755.7  420.03  4764.0  419.84  4769.8  419.95
  4791.4  419.41  4807.3  417.60  4813.2  417.44  4823.1  415.81  4828.9  414.50
  4836.2  413.24  4844.8  411.32  4850.5  409.63  4997.0  407.98  4999.8  407.48
  5000.3  407.48  5003.0  407.98  5006.2  409.58  5092.7  409.58  5100.8  410.18
  5108.5  414.05  5114.3  412.63  5123.8  414.74  5130.1  414.56  5135.9  414.52
  5146.0  410.24  5151.8  409.99  5154.9  407.98  5157.3  407.98
#Mann=3,-1,0
  4743.8    0.05       0  4997.0    0.03       0  5003.0    0.05       0
Bank Sta=4997,5003
Exp/Cntr=0.3,0.1

Type RM Length L Ch R = 1,518,66,66,66
BEGIN DESCRIPTION:
Mapping XS aede6816
END DESCRIPTION:
XS GIS Cut Line= 3
      3700776.89     10774957.71      3700838.08     10775077.48
      3700984.93     10775312.71
#Sta/Elev= 30
  4737.0  421.16  4816.3  417.37  4829.6  417.24  4844.2  415.55  4852.1  416.20
  4870.2  415.18  4933.6  414.78  4940.0  414.20  4961.2  415.24  4976.6  414.65
  4991.9  415.07  4997.0  408.50  4999.8  408.00  5003.0  408.50  5004.4  414.96
  5013.1  413.83  5019.0  415.25  5027.9  415.22  5034.4  414.12  5040.3  415.24
  5063.3  415.04  5070.9  411.66  5076.8  415.10  5092.2  415.00  5098.7  414.57
  5107.5  412.51  5113.4  413.60  5128.7  408.82  5134.6  410.53  5148.8  408.50
#Mann=3,-1,0
  4737.0    0.05       0  4997.0    0.03       0  5003.0    0.05       0
Bank Sta=4997,5003
Exp/Cntr=0.3,0.1

Type RM Length L Ch R = 1,452,386,386,386
BEGIN DESCRIPTION:
DARBY FARMS LAKE 2.0
END DESCRIPTION:
XS GIS Cut Line= 3
      3700738.32     10774999.04      3700765.16     10775098.31
      3700924.00     10775330.06
#Sta/Elev= 30
  4746.7  420.67  4799.7  418.32  4841.1  414.98  4849.5  412.68  4862.1  411.63
  4883.0  404.81  4889.1  403.84  4897.9  400.10  4904.0  400.07  4912.4  397.45
  4918.9  396.34  4933.8  394.82  4954.8  394.94  4969.7  394.20  4975.7  395.08
  4997.0  394.17  4999.8  393.67  5003.0  394.17  5020.5  394.36  5026.5  395.70
  5041.4  394.49  5056.3  394.42  5062.4  395.74  5077.3  395.31  5083.4  396.26
  5092.2  396.09  5098.3  397.44  5106.4  398.08  5119.2  401.37  5130.5  401.07
#Mann=3,-1,0
  4746.7    0.05       0  4997.0    0.03       0  5003.0    0.05       0
Bank Sta=4997,5003
Exp/Cntr=0.3,0.1

Type RM Length L Ch R = 1,66,0,0,0
BEGIN DESCRIPTION:
DARBY FARMS LAKE 1.0
END DESCRIPTION:
XS GIS Cut Line= 4
      3700547.34     10775116.22      3700573.38     10775446.05
      3700642.82     10775480.77      3700764.91     10775451.24
#Sta/Elev= 30
  4650.3  416.90  4664.3  416.29  4684.4  413.00  4704.4  407.67  4714.5  406.08
  4724.5  403.02  4734.5  401.17  4741.1  397.89  4746.1  398.08  4754.6  396.96
  4764.6  394.72  4784.7  392.65  4804.7  391.88  4835.0  392.21  4864.8  393.83
  4869.8  393.07  4875.9  393.18  4885.0  393.54  4925.1  392.73  4988.1  393.45
  4997.0  391.88  4999.8  391.38  5003.0  391.88  5003.2  392.93  5010.5  393.12
  5096.6  393.65  5128.9  394.51  5170.7  396.93  5178.9  398.33  5184.4  398.26
#Mann=5,-1,0
  4650.3    0.05       0  4835.0     0.1       0  4875.9    0.05       0
  4997.0    0.03       0  5003.0    0.05       0
Bank Sta=4997,5003
Exp/Cntr=0.3,0.1

Chan Stop Cuts=-1