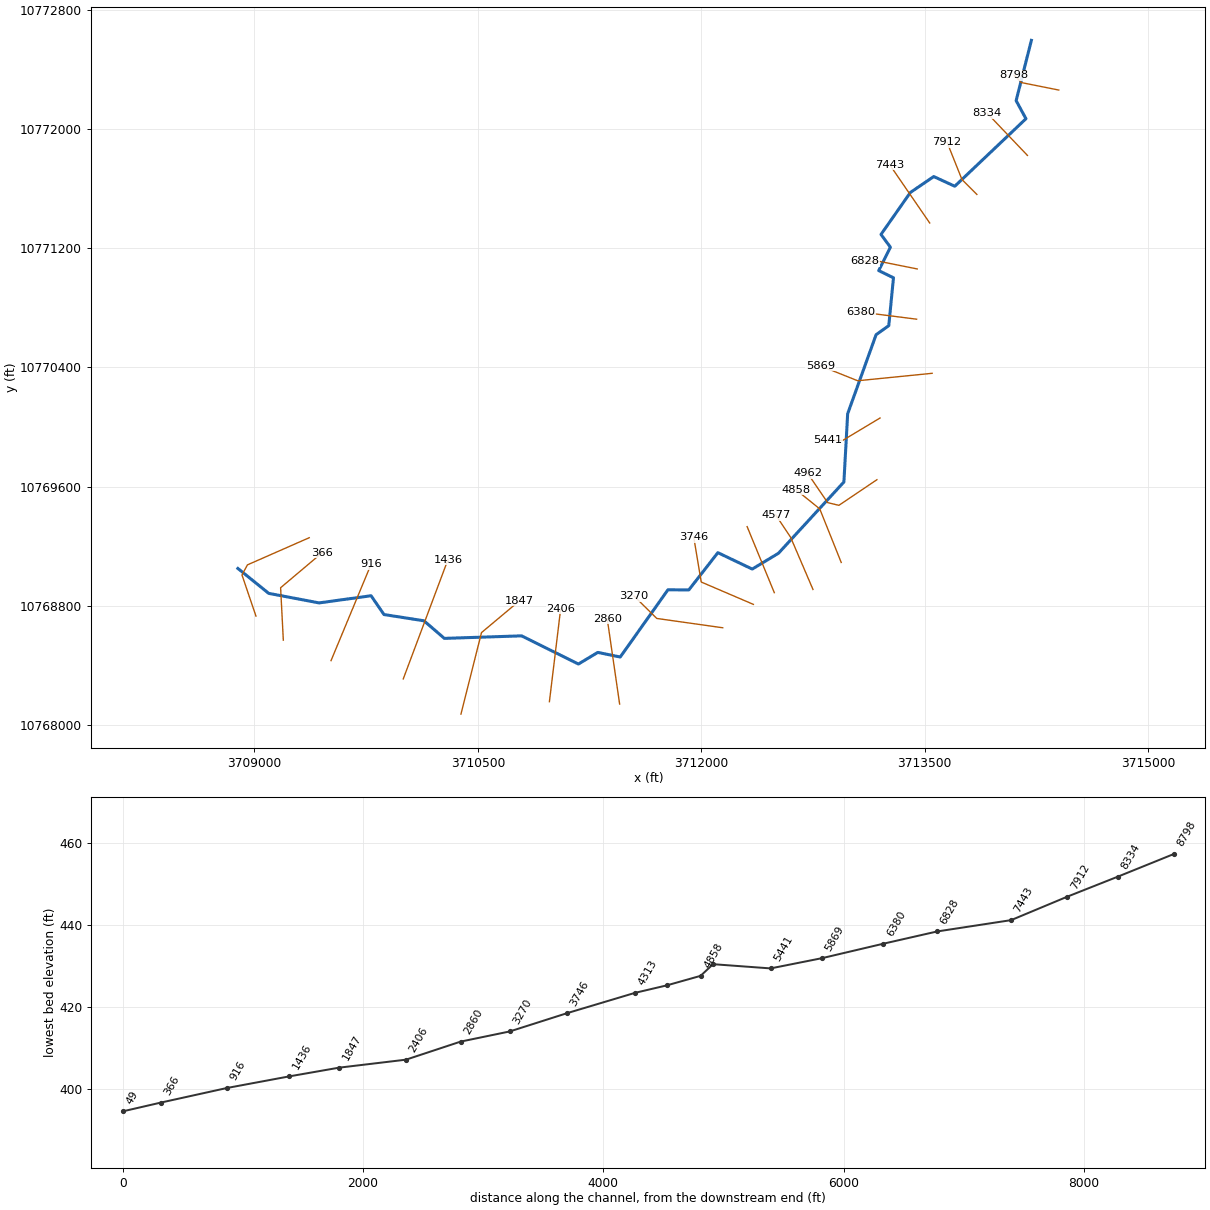
--- GOLD BRANCH.prj (project) ---

Proj Title=GOLD BRANCH Base Level Engineering
Current Plan=p01
Default Exp/Contr=0.3,0.1
English Units
Geom File=g01
Flow File=f01
Plan File=p01
BEGIN DESCRIPTION:
GOLD BRANCH
END DESCRIPTION:

--- GOLD BRANCH.p01 (plan) ---

Plan Title=Multiple Run
Short Identifier=Multiple
Geom File=g01
Flow File=f01
Subcritical Flow
K Sum by GR= 0
Std Step Tol= 0.01
Critical Tol= 0.01
Num of Std Step Trials= 20
Max Error Tol= 0.3
Flow Tol Ratio= 0.001
Split Flow NTrial= 30
Split Flow Tol= 0.02
Split Flow Ratio= 0.02
Log Output Level= 0
Friction Slope Method= 1
Unsteady Friction Slope Method= 2
Unsteady Bridges Friction Slope Method= 1
Parabolic Critical Depth
Global Vel Dist=  1 , 1 , 1
Global Log Level= 0
CheckData=True
Encroach Param= -1, 0, 0, 0
BEGIN DESCRIPTION:
Multiple Run
END DESCRIPTION:

--- GOLD BRANCH.f01 (steady flow) ---

Flow Title=Multiple
Number of Profiles=7
Profile Names=10-year,25-year,50-year,1pct_min,100-year,1pct_plu,500-year
River Rch & RM= GOLD BRANCH,Reach-1,8798
     624     852    1041     934    1263    1709    1863
River Rch & RM= GOLD BRANCH,Reach-1,4858
    1002    1401    1740    1584    2142    2897    3254
Boundary for River Rch & Prof#=GOLD BRANCH,Reach-1,1
Up Type=0
Dn Type=3
Dn Slope=0.005
Boundary for River Rch & Prof#=GOLD BRANCH,Reach-1,2
Up Type=0
Dn Type=3
Dn Slope=0.005
Boundary for River Rch & Prof#=GOLD BRANCH,Reach-1,3
Up Type=0
Dn Type=3
Dn Slope=0.005
Boundary for River Rch & Prof#=GOLD BRANCH,Reach-1,4
Up Type=0
Dn Type=3
Dn Slope=0.005
Boundary for River Rch & Prof#=GOLD BRANCH,Reach-1,5
Up Type=0
Dn Type=3
Dn Slope=0.005
Boundary for River Rch & Prof#=GOLD BRANCH,Reach-1,6
Up Type=0
Dn Type=3
Dn Slope=0.005
Boundary for River Rch & Prof#=GOLD BRANCH,Reach-1,7
Up Type=0
Dn Type=3
Dn Slope=0.005

--- GOLD BRANCH.g01 (geometry) ---

Geom Title=Existing Conditions

River Reach=GOLD BRANCH,Reach-1
Reach XY= 30
      3714215.64     10772593.64      3714113.25     10772189.00
      3714179.25     10772068.00      3713701.50     10771615.00
      3713560.25     10771680.00      3713403.25     10771573.00
      3713206.32     10771291.79      3713269.34     10771205.85
      3713191.00     10771049.00      3713290.00     10771001.00
      3713258.50     10770680.00      3713173.25     10770619.00
      3712982.50     10770089.00      3712957.25     10769631.00
      3712518.00     10769153.00      3712342.00     10769047.00
      3712111.25     10769157.00      3711916.25     10768907.00
      3711776.25     10768908.00      3711456.00     10768457.00
      3711305.25     10768488.00      3711175.25     10768410.00
      3710793.75     10768599.00      3710275.50     10768582.00
      3710138.50     10768700.00      3709870.25     10768742.00
      3709783.50     10768868.00      3709434.75     10768820.00
      3709096.50     10768884.00      3708889.75     10769051.00

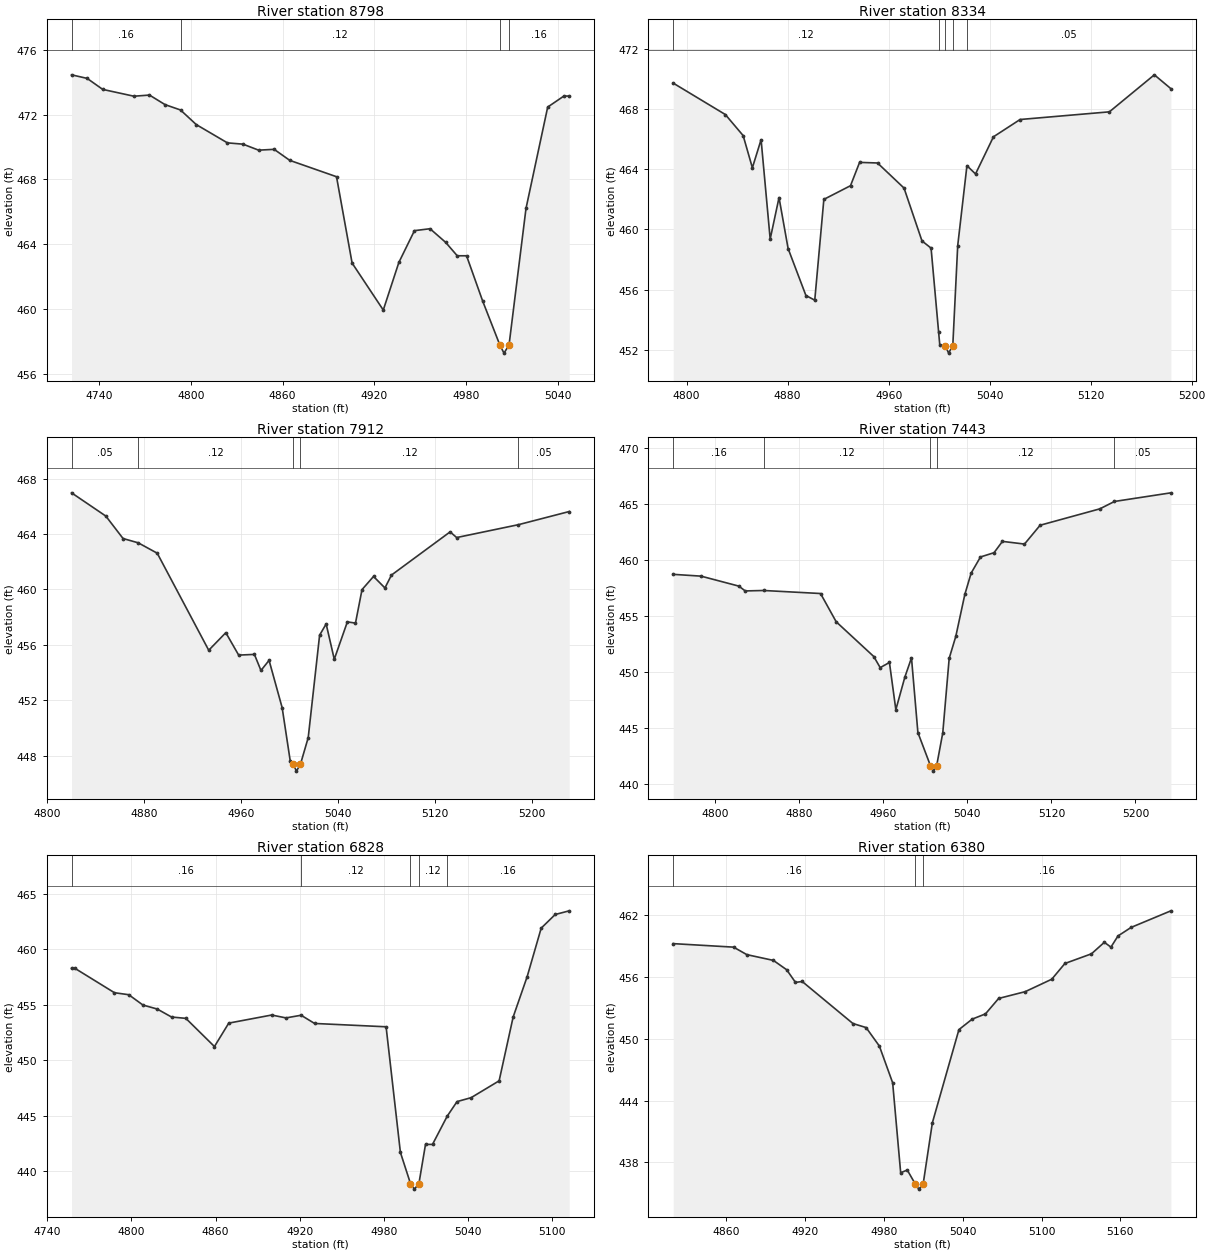
Type RM Length L Ch R = 1,8798,464,464,464
BEGIN DESCRIPTION:
GOLD BRANCH 19.0
END DESCRIPTION:
XS GIS Cut Line= 3
      3714399.64     10772260.18      3714149.61     10772310.19
      3714099.61     10772360.19
#Sta/Elev= 30
  4721.9  474.46  4732.1  474.24  4742.3  473.56  4762.7  473.14  4772.9  473.21
  4783.1  472.62  4793.2  472.29  4803.5  471.39  4823.9  470.26  4834.1  470.18
  4844.3  469.81  4854.5  469.86  4864.7  469.18  4895.3  468.17  4905.5  462.84
  4925.9  459.94  4936.1  462.88  4946.3  464.84  4956.5  464.96  4966.7  464.12
  4974.3  463.29  4980.4  463.29  4991.0  460.48  5002.2  457.78  5004.9  457.28
  5008.2  457.78  5019.3  466.21  5033.5  472.47  5044.1  473.15  5047.6  473.15
#Mann=4,-1,0
  4721.9    0.16       0  4793.2    0.12       0  5002.2    0.07       0
  5008.2    0.16       0
Bank Sta=5002.2,5008.2
Exp/Cntr=0.3,0.1

Type RM Length L Ch R = 1,8334,422,422,422
BEGIN DESCRIPTION:
GOLD BRANCH 18.0
END DESCRIPTION:
XS GIS Cut Line= 2
      3714189.46     10771821.48      3713917.34     10772106.56
#Sta/Elev= 30
  4789.4  469.73  4830.7  467.64  4844.8  466.24  4852.1  464.10  4859.0  465.97
  4866.2  459.36  4873.2  462.12  4880.4  458.73  4894.5  455.61  4901.5  455.30
  4908.7  462.00  4929.8  462.91  4937.0  464.46  4951.2  464.42  4972.2  462.75
  4986.4  459.24  4993.6  458.76  4999.6  453.16  5000.5  452.32  5004.8  452.28
  5007.5  451.78  5010.8  452.28  5014.7  458.93  5022.0  464.24  5028.8  463.69
  5043.0  466.16  5064.1  467.31  5134.8  467.82  5170.4  470.28  5183.5  469.36
#Mann=5,-1,0
  4789.4    0.12       0  4999.6    0.16       0  5004.8    0.07       0
  5010.8    0.16       0  5022.0    0.05       0
Bank Sta=5004.8,5010.8
Exp/Cntr=0.3,0.1

Type RM Length L Ch R = 1,7912,469,469,469
BEGIN DESCRIPTION:
GOLD BRANCH 17.0
END DESCRIPTION:
XS GIS Cut Line= 3
      3713849.63     10771560.17      3713749.61     10771660.19
      3713649.61     10771910.18
#Sta/Elev= 30
  4820.4  466.98  4848.7  465.30  4862.9  463.68  4875.4  463.37  4891.1  462.62
  4933.6  455.61  4947.7  456.88  4958.3  455.26  4971.3  455.31  4976.7  454.15
  4983.4  454.88  4994.2  451.46  5000.9  447.59  5003.3  447.38  5006.0  446.88
  5009.3  447.38  5015.7  449.30  5025.1  456.70  5030.5  457.51  5037.2  454.96
  5048.0  457.66  5054.7  457.57  5060.1  459.99  5069.6  460.94  5079.0  460.11
  5084.4  461.04  5132.8  464.16  5138.2  463.75  5189.2  464.68  5231.1  465.63
#Mann=5,-1,0
  4820.4    0.05       0  4875.4    0.12       0  5003.3    0.07       0
  5009.3    0.12       0  5189.2    0.05       0
Bank Sta=5003.3,5009.3
Exp/Cntr=0.3,0.1

Type RM Length L Ch R = 1,7443,615,615,615
BEGIN DESCRIPTION:
GOLD BRANCH 16.0
END DESCRIPTION:
XS GIS Cut Line= 2
      3713533.20     10771368.35      3713264.94     10771759.02
#Sta/Elev= 30
  4759.9  458.69  4786.4  458.53  4822.4  457.64  4828.5  457.21  4846.0  457.25
  4900.2  456.98  4915.1  454.46  4950.9  451.36  4957.0  450.37  4965.8  450.83
  4971.9  446.62  4980.5  449.53  4986.8  451.24  4992.9  444.58  5004.8  441.64
  5007.5  441.14  5010.8  441.64  5016.6  444.56  5022.7  451.20  5029.0  453.16
  5037.6  456.90  5043.6  458.80  5052.5  460.24  5065.4  460.62  5073.4  461.63
  5094.4  461.39  5109.3  463.07  5166.1  464.53  5180.1  465.19  5233.8  465.96
#Mann=5,-1,0
  4759.9    0.16       0  4846.0    0.12       0  5004.8    0.07       0
  5010.8    0.12       0  5180.1    0.05       0
Bank Sta=5004.8,5010.8
Exp/Cntr=0.3,0.1

Type RM Length L Ch R = 1,6828,448,448,448
BEGIN DESCRIPTION:
GOLD BRANCH 15.0
END DESCRIPTION:
XS GIS Cut Line= 3
      3713449.57     10771060.20      3713199.61     10771110.19
      3713099.62     10771110.19
#Sta/Elev= 30
  4757.3  458.27  4759.8  458.27  4787.9  456.08  4798.1  455.90  4808.2  454.97
  4818.4  454.61  4828.6  453.89  4838.8  453.77  4859.2  451.23  4869.4  453.34
  4900.0  454.07  4910.2  453.81  4921.0  454.05  4930.6  453.31  4981.6  453.01
  4991.8  441.69  4999.0  438.88  5001.8  438.38  5005.0  438.88  5009.7  442.41
  5014.7  442.41  5025.2  444.96  5032.2  446.27  5042.2  446.62  5062.2  448.14
  5072.2  453.89  5082.2  457.53  5092.2  461.90  5102.2  463.13  5112.2  463.46
#Mann=5,-1,0
  4757.3    0.16       0  4921.0    0.12       0  4999.0    0.07       0
  5005.0    0.12       0  5025.2    0.16       0
Bank Sta=4999,5005
Exp/Cntr=0.3,0.1

Type RM Length L Ch R = 1,6380,511,511,511
BEGIN DESCRIPTION:
GOLD BRANCH 14.0
END DESCRIPTION:
XS GIS Cut Line= 2
      3713445.17     10770723.24      3713069.69     10770770.98
#Sta/Elev= 30
  4819.9  459.26  4865.8  458.92  4875.9  458.19  4896.1  457.63  4906.2  456.72
  4912.9  455.49  4918.0  455.58  4956.6  451.49  4966.6  451.10  4976.7  449.30
  4986.8  445.73  4992.9  436.98  4997.9  437.25  5004.0  435.89  5006.7  435.39
  5010.0  435.89  5017.0  441.84  5037.2  450.90  5047.3  451.92  5057.4  452.43
  5067.4  453.93  5087.6  454.59  5107.8  455.80  5117.8  457.33  5138.0  458.27
  5147.8  459.39  5152.8  458.92  5158.2  460.01  5168.2  460.84  5198.4  462.45
#Mann=3,-1,0
  4819.9    0.16       0  5004.0    0.07       0  5010.0    0.16       0
Bank Sta=5004,5010
Exp/Cntr=0.3,0.1

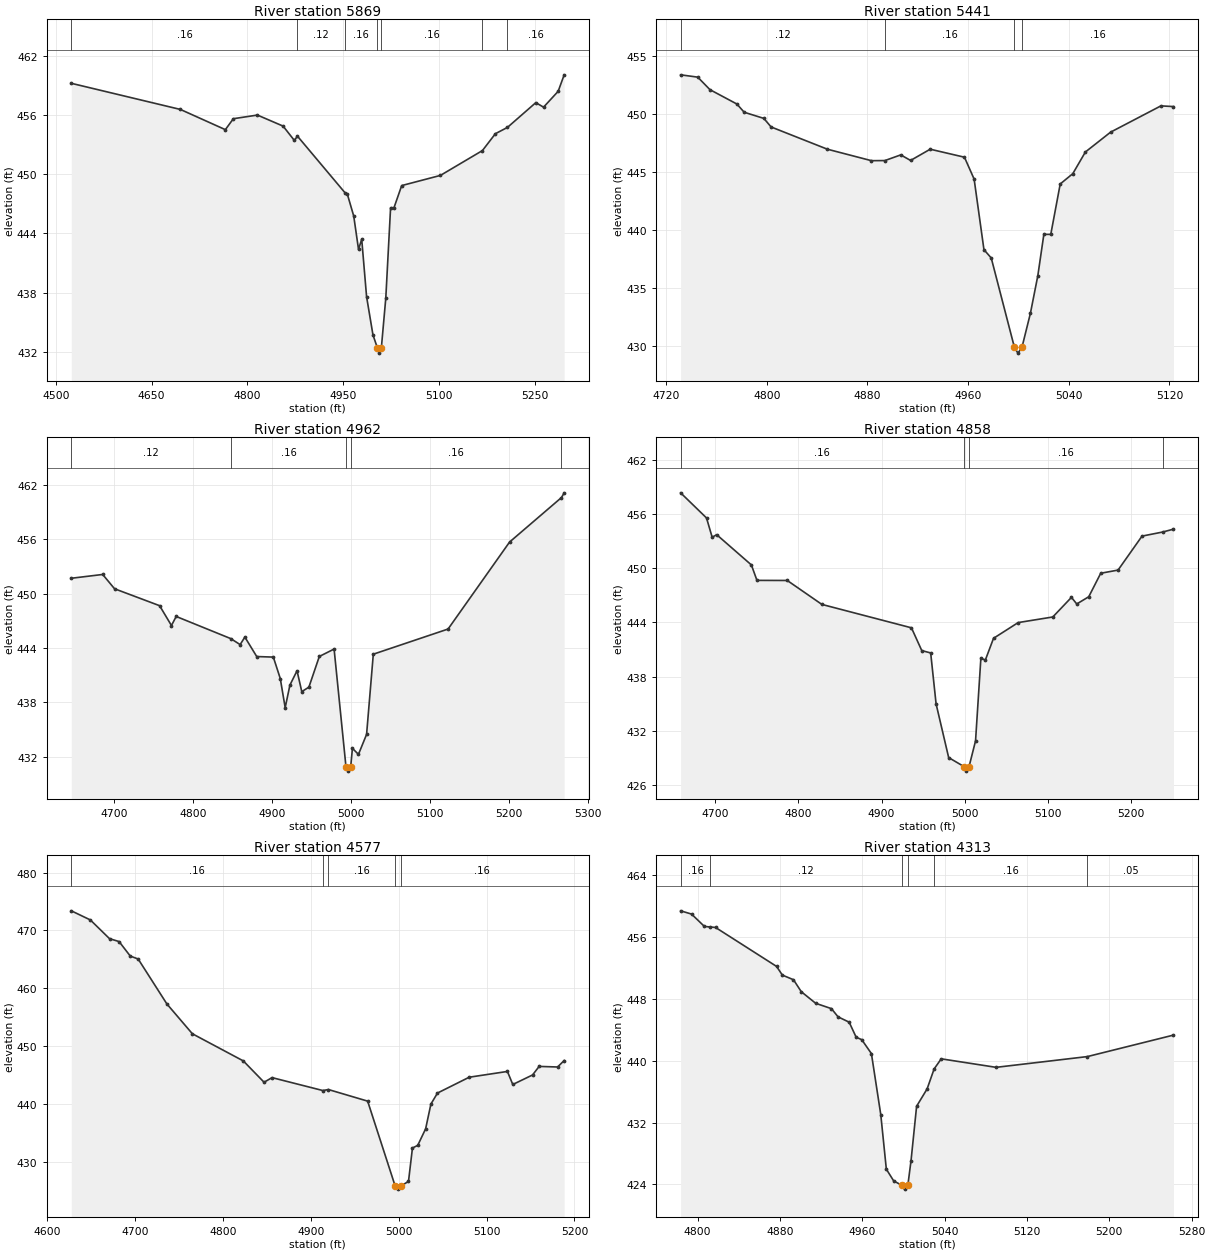
Type RM Length L Ch R = 1,5869,428,428,428
BEGIN DESCRIPTION:
GOLD BRANCH 13.0
END DESCRIPTION:
XS GIS Cut Line= 3
      3713549.58     10770360.19      3713049.61     10770310.19
      3712799.63     10770410.18
#Sta/Elev= 30
  4524.2  459.22  4695.0  456.57  4765.4  454.52  4777.9  455.63  4815.6  456.00
  4855.8  454.88  4873.4  453.43  4878.3  453.86  4952.5  448.14  4956.3  448.00
  4966.4  445.76  4973.9  442.38  4978.9  443.41  4986.5  437.59  4996.5  433.71
  5003.6  432.36  5006.3  431.86  5009.6  432.36  5016.6  437.44  5024.1  446.60
  5029.4  446.60  5041.5  448.85  5102.1  449.88  5167.9  452.40  5188.2  454.11
  5207.1  454.75  5251.5  457.26  5263.6  456.80  5286.5  458.41  5295.9  460.08
#Mann=7,-1,0
  4524.2    0.16       0  4878.3    0.12       0  4952.5    0.16       0
  5003.6    0.07       0  5009.6    0.16       0  5167.9    0.05       0
  5207.1    0.16       0
Bank Sta=5003.6,5009.6
Exp/Cntr=0.3,0.1

Type RM Length L Ch R = 1,5441,479,479,479
BEGIN DESCRIPTION:
GOLD BRANCH 12.0
END DESCRIPTION:
XS GIS Cut Line= 3
      3713199.61     10770060.19      3712949.61     10769910.19
      3712849.56     10769910.19
#Sta/Elev= 30
  4731.6  453.38  4745.2  453.18  4754.9  452.10  4776.3  450.86  4782.1  450.15
  4797.7  449.62  4803.5  448.88  4848.2  446.96  4883.2  445.97  4893.9  445.98
  4906.5  446.47  4914.3  445.99  4929.9  446.96  4957.1  446.27  4964.8  444.38
  4972.6  438.29  4978.4  437.57  4996.8  429.86  4999.6  429.36  5002.8  429.86
  5009.5  432.79  5015.4  436.04  5020.2  439.61  5025.7  439.61  5033.2  443.96
  5043.2  444.85  5053.2  446.72  5073.2  448.43  5113.2  450.70  5123.2  450.64
#Mann=4,-1,0
  4731.6    0.12       0  4893.9    0.16       0  4996.8    0.07       0
  5002.8    0.16       0
Bank Sta=4996.8,5002.8
Exp/Cntr=0.3,0.1

Type RM Length L Ch R = 1,4962,104,104,104
BEGIN DESCRIPTION:
GOLD BRANCH 11.0
END DESCRIPTION:
XS GIS Cut Line= 4
      3713178.91     10769646.44      3712923.66     10769474.54
      3712848.14     10769492.77      3712713.65     10769689.34
#Sta/Elev= 30
  4646.2  451.70  4685.9  452.12  4700.9  450.54  4757.9  448.67  4772.9  446.48
  4778.9  447.48  4848.0  445.03  4859.8  444.37  4865.8  445.20  4880.8  443.05
  4901.8  442.99  4910.6  440.62  4916.8  437.40  4922.8  439.90  4931.8  441.48
  4937.8  439.17  4946.8  439.67  4960.0  443.06  4978.7  443.88  4993.7  430.89
  4996.5  430.39  4999.7  430.89  5001.9  432.91  5009.5  432.24  5019.8  434.45
  5028.3  443.31  5122.9  446.09  5200.7  455.70  5266.4  460.62  5269.8  461.14
#Mann=5,-1,0
  4646.2    0.12       0  4848.0    0.16       0  4993.7    0.07       0
  4999.7    0.16       0  5266.4    0.05       0
Bank Sta=4993.7,4999.7
Exp/Cntr=0.3,0.1

Type RM Length L Ch R = 1,4858,281,281,281
BEGIN DESCRIPTION:
Mapping XS 0072329c
END DESCRIPTION:
XS GIS Cut Line= 3
      3712939.24     10769091.33      3712795.16     10769450.68
      3712635.46     10769579.13
#Sta/Elev= 30
  4658.6  458.34  4689.7  455.56  4696.5  453.42  4701.9  453.71  4743.6  450.36
  4750.3  448.65  4786.7  448.64  4828.3  445.99  4935.9  443.40  4948.3  440.88
  4959.0  440.62  4965.5  434.98  4980.6  429.04  4999.1  428.04  5001.9  427.54
  5005.1  428.04  5012.9  430.89  5019.3  440.03  5024.7  439.84  5034.5  442.24
  5064.1  443.98  5105.7  444.60  5128.1  446.77  5134.5  446.04  5148.9  446.84
  5163.3  449.44  5184.1  449.79  5212.9  453.55  5237.6  454.00  5250.7  454.32
#Mann=4,-1,0
  4658.6    0.16       0  4999.1    0.07       0  5005.1    0.16       0
  5237.6    0.05       0
Bank Sta=4999.1,5005.1
Exp/Cntr=0.3,0.1

Type RM Length L Ch R = 1,4577,264,264,264
BEGIN DESCRIPTION:
GOLD BRANCH 10.0
END DESCRIPTION:
XS GIS Cut Line= 3
      3712749.60     10768910.20      3712599.61     10769260.19
      3712499.64     10769410.15
#Sta/Elev= 30
  4627.3  473.39  4649.0  471.81  4670.8  468.57  4681.7  468.07  4694.4  465.56
  4703.4  465.05  4736.1  457.27  4765.1  452.11  4823.1  447.41  4846.7  443.72
  4855.8  444.52  4913.7  442.28  4919.9  442.46  4964.6  440.45  4996.0  425.72
  4998.8  425.22  5002.0  425.72  5011.1  426.56  5015.6  432.34  5021.6  432.79
  5030.6  435.66  5036.6  439.94  5044.1  441.85  5080.2  444.59  5123.7  445.59
  5129.8  443.33  5152.3  444.98  5159.8  446.46  5180.8  446.36  5188.3  447.48
#Mann=5,-1,0
  4627.3    0.16       0  4913.7    0.12       0  4919.9    0.16       0
  4996.0    0.07       0  5002.0    0.16       0
Bank Sta=4996,5002
Exp/Cntr=0.3,0.1

Type RM Length L Ch R = 1,4313,567,567,567
BEGIN DESCRIPTION:
GOLD BRANCH 9.0
END DESCRIPTION:
XS GIS Cut Line= 2
      3712490.06     10768888.85      3712307.79     10769331.49
#Sta/Elev= 30
  4783.6  459.39  4794.2  458.97  4806.7  457.37  4812.4  457.30  4817.5  457.24
  4876.8  452.20  4882.4  451.08  4893.2  450.48  4900.8  448.93  4914.8  447.43
  4930.1  446.74  4936.5  445.68  4947.3  444.99  4954.1  443.04  4959.5  442.73
  4968.9  440.93  4978.0  433.03  4983.4  425.98  4990.5  424.47  4998.3  423.90
  5001.1  423.40  5004.3  423.90  5007.4  427.10  5012.8  434.12  5023.0  436.36
  5029.8  438.94  5036.7  440.25  5090.0  439.15  5178.6  440.54  5262.3  443.32
#Mann=6,-1,0
  4783.6    0.16       0  4812.4    0.12       0  4998.3    0.07       0
  5004.3    0.12       0  5029.8    0.16       0  5178.6    0.05       0
Bank Sta=4998.3,5004.3
Exp/Cntr=0.3,0.1

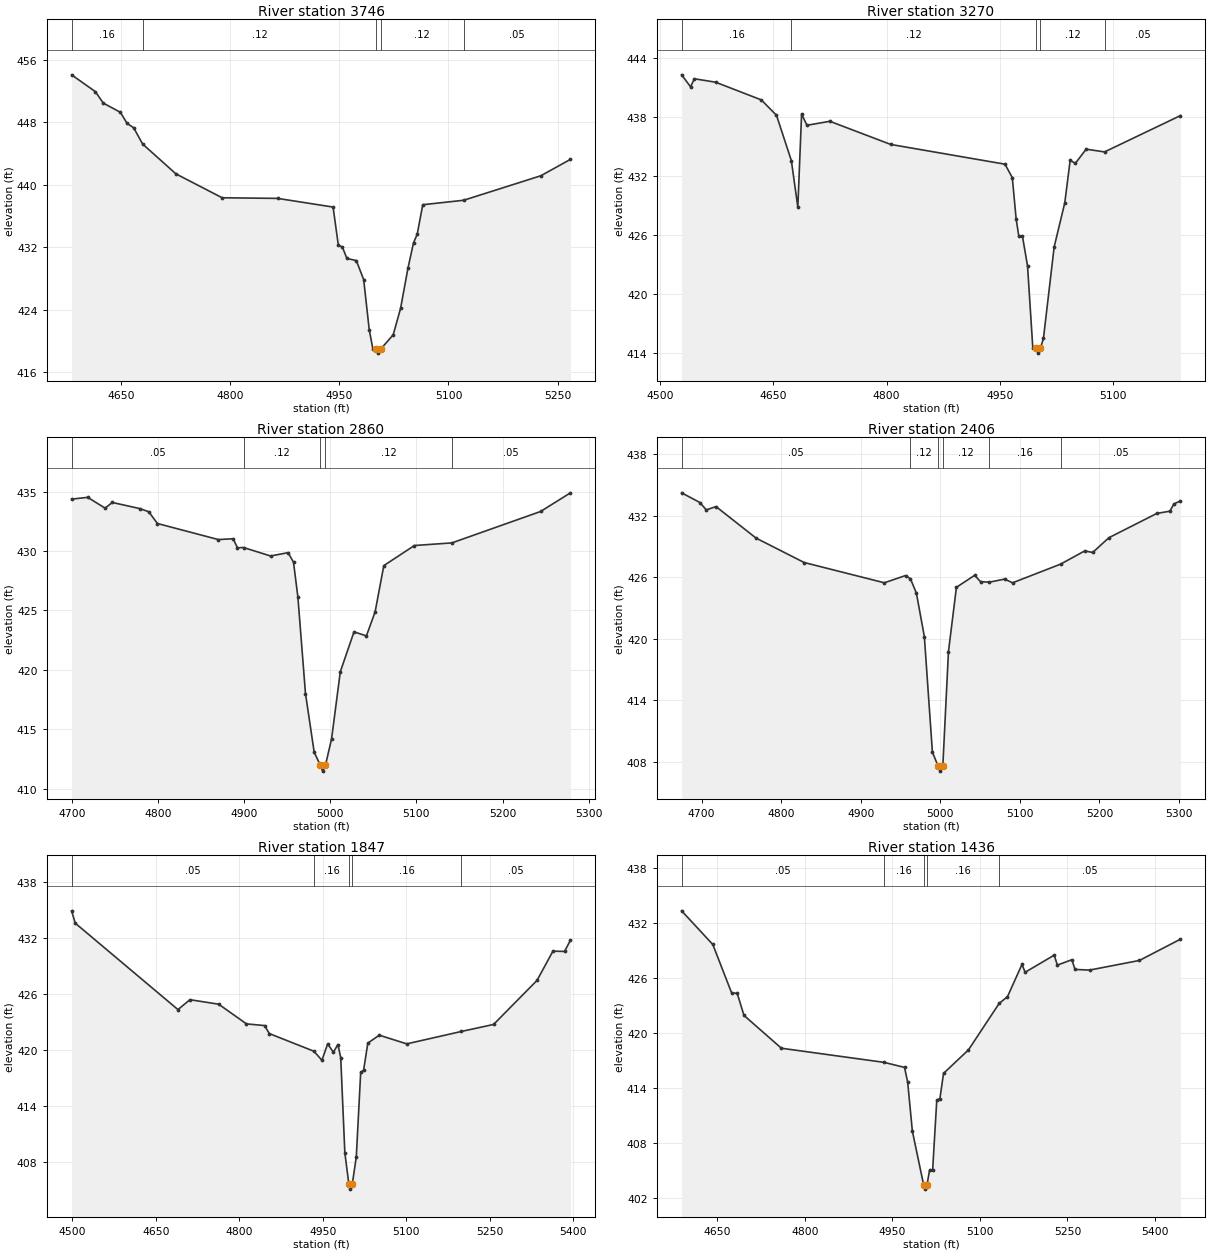
Type RM Length L Ch R = 1,3746,476,476,476
BEGIN DESCRIPTION:
GOLD BRANCH 8.0
END DESCRIPTION:
XS GIS Cut Line= 3
      3712349.57     10768810.21      3711999.61     10768960.19
      3711949.61     10769260.21
#Sta/Elev= 30
  4582.6  454.06  4615.2  451.91  4626.1  450.44  4649.6  449.26  4658.7  447.85
  4667.8  447.28  4680.1  445.20  4725.8  441.38  4789.3  438.32  4865.4  438.24
  4941.6  437.13  4948.8  432.24  4954.3  432.02  4960.6  430.55  4973.5  430.28
  4983.6  427.84  4991.2  421.44  4996.3  418.94  5000.9  418.93  5003.6  418.43
  5006.9  418.93  5024.2  420.79  5034.3  424.18  5044.4  429.31  5052.0  432.54
  5057.1  433.65  5064.7  437.43  5120.8  438.00  5226.9  441.14  5267.5  443.24
#Mann=5,-1,0
  4582.6    0.16       0  4680.1    0.12       0  5000.9    0.07       0
  5006.9    0.12       0  5120.8    0.05       0
Bank Sta=5000.9,5006.9
Exp/Cntr=0.3,0.1

Type RM Length L Ch R = 1,3270,410,410,410
BEGIN DESCRIPTION:
Mapping XS dd24f1f3
END DESCRIPTION:
XS GIS Cut Line= 3
      3712144.16     10768653.22      3711701.42     10768715.73
      3711548.55     10768866.01
#Sta/Elev= 30
  4528.2  442.32  4540.1  441.10  4545.1  441.92  4573.2  441.57  4633.8  439.77
  4654.0  438.20  4673.7  433.59  4682.3  428.85  4687.3  438.33  4694.4  437.18
  4724.7  437.59  4805.5  435.23  4957.0  433.22  4966.7  431.85  4971.8  427.64
  4975.3  425.91  4980.1  425.91  4986.9  422.86  4993.9  414.51  4998.0  414.48
  5000.7  413.98  5004.0  414.48  5008.0  415.48  5022.2  424.79  5036.3  429.29
  5043.4  433.61  5050.4  433.31  5064.6  434.75  5089.0  434.47  5189.7  438.17
#Mann=5,-1,0
  4528.2    0.16       0  4673.7    0.12       0  4998.0    0.07       0
  5004.0    0.12       0  5089.0    0.05       0
Bank Sta=4998,5004
Exp/Cntr=0.3,0.1

Type RM Length L Ch R = 1,2860,454,454,454
BEGIN DESCRIPTION:
GOLD BRANCH 6.0
END DESCRIPTION:
XS GIS Cut Line= 2
      3711451.87     10768141.65      3711368.55     10768714.52
#Sta/Elev= 30
  4699.9  434.36  4718.6  434.51  4738.8  433.60  4747.1  434.08  4779.3  433.56
  4789.4  433.30  4799.5  432.31  4870.2  430.96  4887.3  431.03  4892.4  430.27
  4899.4  430.29  4930.8  429.58  4951.1  429.86  4957.4  429.06  4962.5  426.12
  4971.3  418.01  4981.4  413.08  4988.5  411.99  4991.2  411.49  4994.5  411.99
  5001.6  414.21  5011.7  419.84  5027.6  423.20  5042.0  422.86  5052.1  424.88
  5062.2  428.77  5097.7  430.46  5141.2  430.68  5244.1  433.32  5278.8  434.89
#Mann=5,-1,0
  4699.9    0.05       0  4899.4    0.12       0  4988.5    0.07       0
  4994.5    0.12       0  5141.2    0.05       0
Bank Sta=4988.5,4994.5
Exp/Cntr=0.3,0.1

Type RM Length L Ch R = 1,2406,559,559,559
BEGIN DESCRIPTION:
GOLD BRANCH 5.0
END DESCRIPTION:
XS GIS Cut Line= 2
      3710980.52     10768157.27      3711056.04     10768779.70
#Sta/Elev= 30
  4674.9  434.25  4698.0  433.30  4705.9  432.58  4718.1  432.91  4768.5  429.83
  4828.9  427.45  4929.7  425.47  4956.4  426.18  4962.5  425.86  4970.0  424.46
  4980.0  420.21  4990.1  408.95  4997.2  407.59  4999.9  407.09  5003.2  407.59
  5010.3  418.76  5020.3  425.03  5043.2  426.20  5050.6  425.58  5061.7  425.53
  5080.8  425.83  5090.9  425.47  5151.2  427.29  5181.5  428.58  5191.6  428.43
  5211.9  429.87  5272.2  432.24  5288.6  432.46  5293.7  433.17  5301.9  433.46
#Mann=6,-1,0
  4674.9    0.05       0  4962.5    0.12       0  4997.2    0.07       0
  5003.2    0.12       0  5061.7    0.16       0  5151.2    0.05       0
Bank Sta=4997.2,5003.2
Exp/Cntr=0.3,0.1

Type RM Length L Ch R = 1,1847,411,411,411
BEGIN DESCRIPTION:
GOLD BRANCH 4.0
END DESCRIPTION:
XS GIS Cut Line= 3
      3710386.76     10768073.92      3710524.79     10768620.81
      3710779.99     10768834.35
#Sta/Elev= 30
  4498.6  434.94  4505.1  433.62  4689.8  424.36  4711.3  425.42  4762.9  424.94
  4813.0  422.83  4845.4  422.65  4854.1  421.79  4934.2  419.90  4948.6  418.93
  4958.9  420.69  4969.2  419.79  4977.3  420.62  4982.4  419.22  4989.8  409.02
  4997.1  405.63  4999.9  405.13  5003.1  405.63  5010.4  408.60  5018.3  417.64
  5023.5  417.85  5031.1  420.77  5051.7  421.62  5101.1  420.69  5199.4  422.02
  5257.2  422.77  5335.3  427.49  5363.9  430.62  5384.8  430.59  5395.4  431.80
#Mann=5,-1,0
  4498.6    0.05       0  4934.2    0.16       0  4997.1    0.07       0
  5003.1    0.16       0  5199.4    0.05       0
Bank Sta=4997.1,5003.1
Exp/Cntr=0.3,0.1

Type RM Length L Ch R = 1,1436,520,520,520
BEGIN DESCRIPTION:
GOLD BRANCH 3.0
END DESCRIPTION:
XS GIS Cut Line= 3
      3709999.60     10768310.15      3710149.61     10768710.19
      3710299.59     10769110.15
#Sta/Elev= 30
  4589.2  433.36  4642.6  429.69  4674.7  424.44  4684.5  424.35  4696.0  421.96
  4760.1  418.38  4935.9  416.84  4971.0  416.29  4976.4  414.67  4984.4  409.34
  5003.6  403.52  5006.4  403.02  5009.6  403.52  5013.8  405.06  5019.1  405.06
  5026.2  412.71  5031.6  412.90  5037.8  415.64  5080.5  418.20  5133.1  423.27
  5147.3  424.00  5172.2  427.52  5177.5  426.66  5227.4  428.53  5232.7  427.44
  5257.6  428.03  5263.0  426.97  5287.9  426.90  5373.3  427.95  5443.6  430.27
#Mann=5,-1,0
  4589.2    0.05       0  4935.9    0.16       0  5003.6    0.07       0
  5009.6    0.16       0  5133.1    0.05       0
Bank Sta=5003.6,5009.6
Exp/Cntr=0.3,0.1

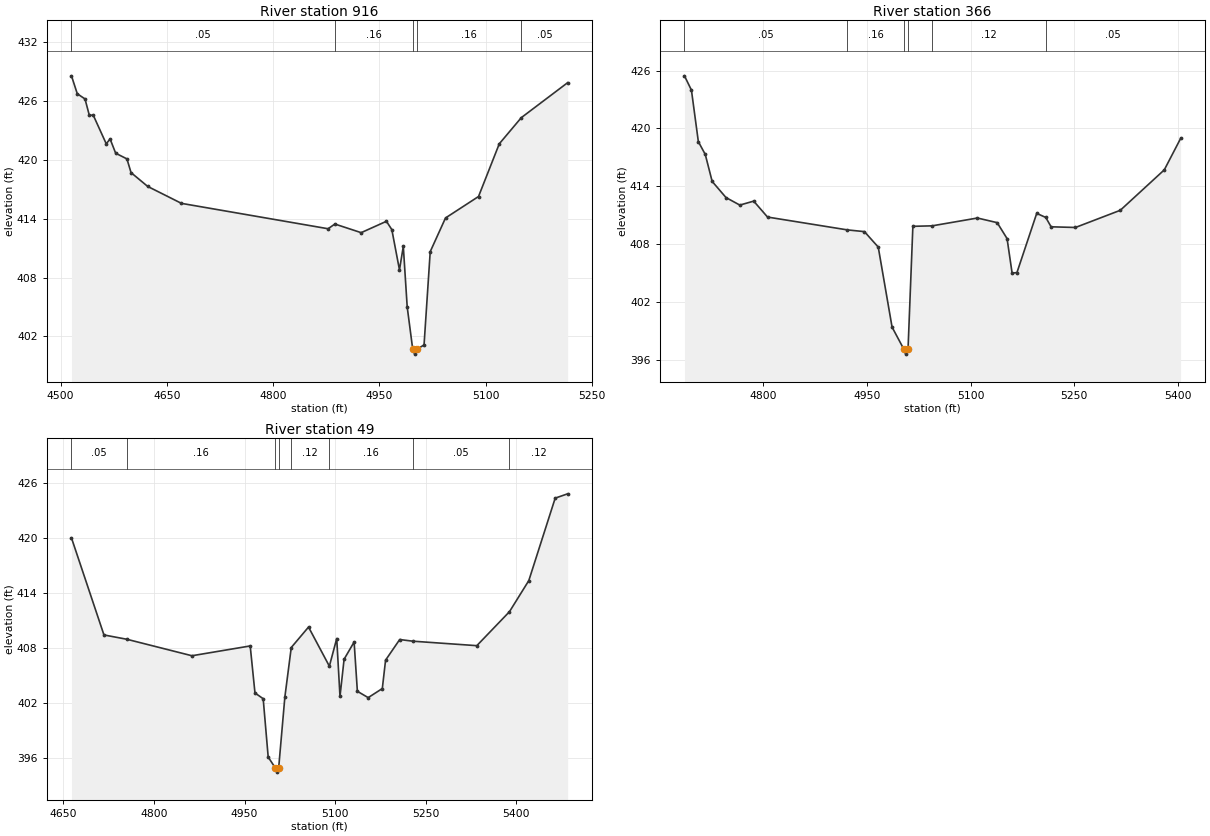
Type RM Length L Ch R = 1,916,550,550,550
BEGIN DESCRIPTION:
Mapping XS f73ac520
END DESCRIPTION:
XS GIS Cut Line= 2
      3709514.62     10768432.59      3709783.74     10769079.33
#Sta/Elev= 30
  4515.4  428.59  4523.6  426.76  4534.5  426.23  4540.6  424.56  4546.1  424.58
  4564.5  421.65  4569.9  422.15  4577.8  420.69  4593.7  420.11  4599.5  418.71
  4623.0  417.30  4670.7  415.57  4877.7  412.98  4887.3  413.46  4924.4  412.58
  4960.1  413.74  4967.7  412.89  4978.5  408.78  4983.9  411.18  4989.4  405.00
  4997.2  400.68  5000.0  400.18  5003.2  400.68  5013.2  401.12  5021.9  410.64
  5043.5  414.08  5090.1  416.27  5119.4  421.65  5150.5  424.32  5215.9  427.89
#Mann=5,-1,0
  4515.4    0.05       0  4887.3    0.16       0  4997.2    0.07       0
  5003.2    0.16       0  5150.5    0.05       0
Bank Sta=4997.2,5003.2
Exp/Cntr=0.3,0.1

Type RM Length L Ch R = 1,366,317,317,317
BEGIN DESCRIPTION:
GOLD BRANCH 2.0
END DESCRIPTION:
XS GIS Cut Line= 3
      3709194.54     10768570.15      3709176.31     10768921.76
      3709456.06     10769157.48
#Sta/Elev= 30
  4686.0  425.45  4696.1  423.97  4706.1  418.63  4716.1  417.31  4726.1  414.51
  4746.1  412.84  4766.1  412.06  4786.2  412.47  4806.2  410.82  4921.7  409.49
  4946.4  409.31  4966.4  407.71  4986.4  399.42  5003.5  397.12  5006.2  396.62
  5009.5  397.12  5016.5  409.86  5044.4  409.91  5109.9  410.72  5138.5  410.24
  5152.8  408.59  5160.1  405.01  5167.1  405.07  5195.7  411.20  5208.8  410.78
  5216.5  409.81  5251.7  409.74  5316.6  411.52  5380.3  415.71  5403.9  418.96
#Mann=6,-1,0
  4686.0    0.05       0  4921.7    0.16       0  5003.5    0.07       0
  5009.5    0.16       0  5044.4    0.12       0  5208.8    0.05       0
Bank Sta=5003.5,5009.5
Exp/Cntr=0.3,0.1

Type RM Length L Ch R = 1,49,0,0,0
BEGIN DESCRIPTION:
GOLD BRANCH 1.0
END DESCRIPTION:
XS GIS Cut Line= 4
      3709010.87     10768731.27      3708917.11     10769007.35
      3708953.57     10769075.06      3709368.51     10769257.36
#Sta/Elev= 30
  4663.3  420.04  4717.1  409.45  4754.9  408.98  4862.8  407.18  4959.3  408.25
  4967.2  403.12  4980.8  402.49  4989.1  396.12  5000.5  394.98  5003.3  394.48
  5006.5  394.98  5016.7  402.67  5027.3  408.08  5055.9  410.31  5090.4  406.04
  5102.6  409.06  5108.0  402.74  5114.8  406.80  5131.4  408.68  5136.8  403.30
  5154.7  402.61  5178.1  403.60  5183.5  406.70  5206.9  408.95  5228.5  408.77
  5334.6  408.28  5388.7  411.99  5420.7  415.38  5464.4  424.38  5485.0  424.85
#Mann=8,-1,0
  4663.3    0.05       0  4754.9    0.16       0  5000.5    0.07       0
  5006.5    0.16       0  5027.3    0.12       0  5090.4    0.16       0
  5228.5    0.05       0  5388.7    0.12       0
Bank Sta=5000.5,5006.5
Exp/Cntr=0.3,0.1

Chan Stop Cuts=-1