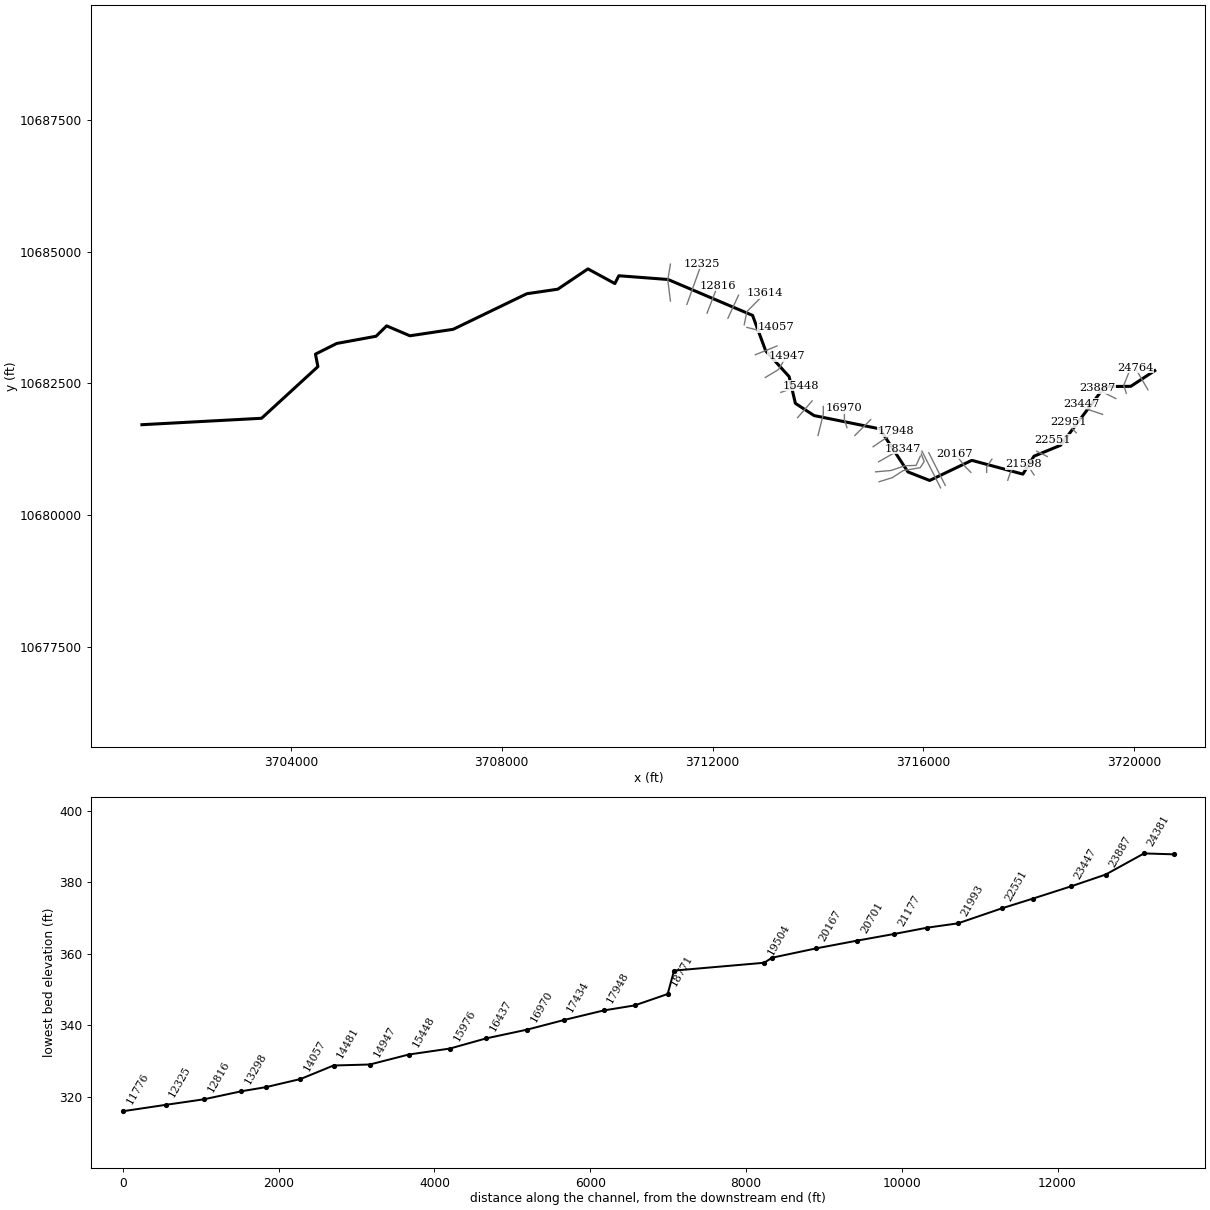
--- HOLLY SPRING BRANCH.prj (project) ---

Proj Title=HOLLY SPRING BRANCH Base Level Engineering
Current Plan=p01
Default Exp/Contr=0.3,0.1
English Units
Geom File=g01
Flow File=f01
Plan File=p01
Y Axis Title=Elevation
X Axis Title(PF)=Main Channel Distance
X Axis Title(XS)=Station
BEGIN DESCRIPTION:
OLLY SPRING BRANCH
END DESCRIPTION:
DSS Export Rating Curves= 0
DSS Export Rating Curve Sorted= 0
DSS Export Volume Flow Curves= 0
DXF OffsetX= 0
DXF OffsetY= 0
DXF ScaleX= 1
DXF ScaleY= 10

--- HOLLY SPRING BRANCH.p01 (plan) ---

Plan Title=Multiple Run
Program Version=4.10
Short Identifier=Multiple
Geom File=g01
Flow File=f01
Subcritical Flow
K Sum by GR= 0
Std Step Tol= 0.01
Critical Tol= 0.01
Num of Std Step Trials= 20
Max Error Tol= 0.3
Flow Tol Ratio= 0.001
Split Flow NTrial= 30
Split Flow Tol= 0.02
Split Flow Ratio= 0.02
Log Output Level= 0
Friction Slope Method= 1
Unsteady Friction Slope Method= 2
Unsteady Bridges Friction Slope Method= 1
Parabolic Critical Depth
Global Vel Dist= 1 , 1 , 1
Global Log Level= 0
CheckData=True
Encroach Param=-1 ,0,0, 0
BEGIN DESCRIPTION:
Multiple Run
END DESCRIPTION:
Computation Interval=1HOUR
Output Interval=1HOUR
Run HTab= 0
Run UNet= 0
Run PostProcess= 0
Run WQNet= 0
UNET Theta= 1
UNET Theta Warmup= 1
UNET ZTol= 0.02
UNET ZSATol= 0.05
UNET MxIter= 20
UNET MaxInSteps= 0
UNET DtIC= 0
UNET DtMin= 0
UNET MaxCRTS= 20
UNET WFStab= 2
UNET SFStab= 1
UNET WFX= 1
UNET SFX= 1
UNET DSS MLevel= 4
UNET DZMax Abort= 100
UNET Convert EG Bridges= 0
UNET Use Existing IB Tables=-1
UNET Froude Reduction=False
UNET Froude Limit= 1
UNET Froude Power= 10
UNET Time Slicing=0,0, 5
UNET Junction Losses=0
Instantaneous Interval=1HOUR
Write IC File= 0
Write IC File at Sim End=0
Echo Input=False
Echo Parameters=False
Echo Output=False
Write Detailed= 0
WQ AD Non Conservative
WQ ULTIMATE=-1
WQ Max Comp Step=1HOUR
WQ Output Interval=15MIN
WQ Output Selected Increments= 0
WQ Output face flow=0
WQ Output face velocity=0
WQ Output face area=0
WQ Output face dispersion=0
WQ Output cell volume=0
WQ Output cell surface area=0
WQ Output cell continuity=0
WQ Output cumulative cell continuity=0
WQ Output face conc=0
WQ Output face dconc_dx=0
WQ Output face courant=0
WQ Output face peclet=0
WQ Output face adv mass=0
WQ Output face disp mass=0
WQ Output cell mass=0
WQ Output cell source sink temp=0
WQ Output cell source sink nsm=0
WQ Output MaxMinRange=-1
WQ Daily Max Min Mean=-1
WQ Daily Range=0
WQ Daily Time=0
WQ Create Restart=0
WQ Fixed Restart=0
WQ System Summary=0
WQ Use Fixed Temperature=0
Sorting and Armoring Iterations= 10
XS Update Threshold= 0.02
Hydraulics Update Threshold= 0.02
Energy Slope Method= 1
Volume Change Method= 0
XS Weighting Method= 0
Number of US Weighted Cross Sections= 1
Number of DS Weighted Cross Sections= 1
Upstream XS Weight=0.25
Main XS Weight=0.5
Downstream XS Weight=0.25
Number of DS XS's Weighted with US Boundary= 1
Upstream Boundary Weight= 1
Weight of XSs Associated with US Boundary= 0
Number of US XS's Weighted with DS Boundary= 1
Downstream Boundary Weight= 0.5
Weight of XSs Associated with DS Boundary= 0.5
Sediment Output Level= 4
Mass or Volume Output= 0
Output Increment Type= 1
Profile and TS Output Increment= 10
XS Output Flag= 0
XS Output Increment= 10
Disregard all LS=0
Disregard all Conn=0
Disregard all Breaches=0
Disregard all Pumps=0

--- HOLLY SPRING BRANCH.f01 (steady flow) ---

Flow Title=Multiple
Program Version=4.10
Number of Profiles= 7
Profile Names=10-year,25-year,50-year,1pct_min,100-year,1pct_plu,500-year
River Rch & RM=HOLLY SPRING BRA,Reach-1         ,24764
     786    1105    1379    1267    1714    2317    2656
River Rch & RM=HOLLY SPRING BRA,Reach-1         ,22951
     985    1399    1757    1623    2195    2968    3439
River Rch & RM=HOLLY SPRING BRA,Reach-1         ,19605
    1200    1723    2179    2026    2740    3706    4351
River Rch & RM=HOLLY SPRING BRA,Reach-1         ,18347
    1253    1794    2267    2103    2844    3847    4498
River Rch & RM=HOLLY SPRING BRA,Reach-1         ,13614
    1713    2481    3157    2945    3983    5387    6373
River Rch & RM=HOLLY SPRING BRA,Reach-1         ,6432
    1871    2711    3450    3217    4351    5884    6955
Boundary for River Rch & Prof#=HOLLY SPRING BRA,Reach-1         , 1
Up Type= 0
Dn Type= 3
Dn Slope=0.003
Boundary for River Rch & Prof#=HOLLY SPRING BRA,Reach-1         , 2
Up Type= 0
Dn Type= 3
Dn Slope=0.003
Boundary for River Rch & Prof#=HOLLY SPRING BRA,Reach-1         , 3
Up Type= 0
Dn Type= 3
Dn Slope=0.003
Boundary for River Rch & Prof#=HOLLY SPRING BRA,Reach-1         , 4
Up Type= 0
Dn Type= 3
Dn Slope=0.003
Boundary for River Rch & Prof#=HOLLY SPRING BRA,Reach-1         , 5
Up Type= 0
Dn Type= 3
Dn Slope=0.003
Boundary for River Rch & Prof#=HOLLY SPRING BRA,Reach-1         , 6
Up Type= 0
Dn Type= 3
Dn Slope=0.003
Boundary for River Rch & Prof#=HOLLY SPRING BRA,Reach-1         , 7
Up Type= 0
Dn Type= 3
Dn Slope=0.003
DSS Import GetInterval= 0
DSS Import GetPeak= 0
DSS Import FillOption= 0

--- HOLLY SPRING BRANCH.g01 (geometry) ---

Geom Title=Existing Conditions
Program Version=4.10

River Reach=HOLLY SPRING BRA,Reach-1
Reach XY= 30
      3720389.05     10682740.17      3719933.75       10682442.
       3719440.5       10682438.      3718601.75       10681324.
       3718096.5       10681116.       3717886.5       10680776.
        3716918.       10681038.      3716118.25       10680656.
        3715706.       10680818.      3715172.25       10681635.
      3713925.75       10681887.      3713570.25       10682119.
       3713451.5       10682627.       3713007.5       10683114.
        3712758.       10683788.      3711153.75       10684469.
       3710220.5       10684540.       3710145.5       10684392.
       3709634.5       10684670.      3709062.25       10684285.
      3708475.25       10684199.        3707078.       10683524.
       3706256.5       10683401.        3705815.       10683589.
        3705614.       10683392.      3704867.25       10683255.
      3704464.75       10683053.      3704511.25       10682816.
       3703442.5       10681836.       3701172.5       10681714.

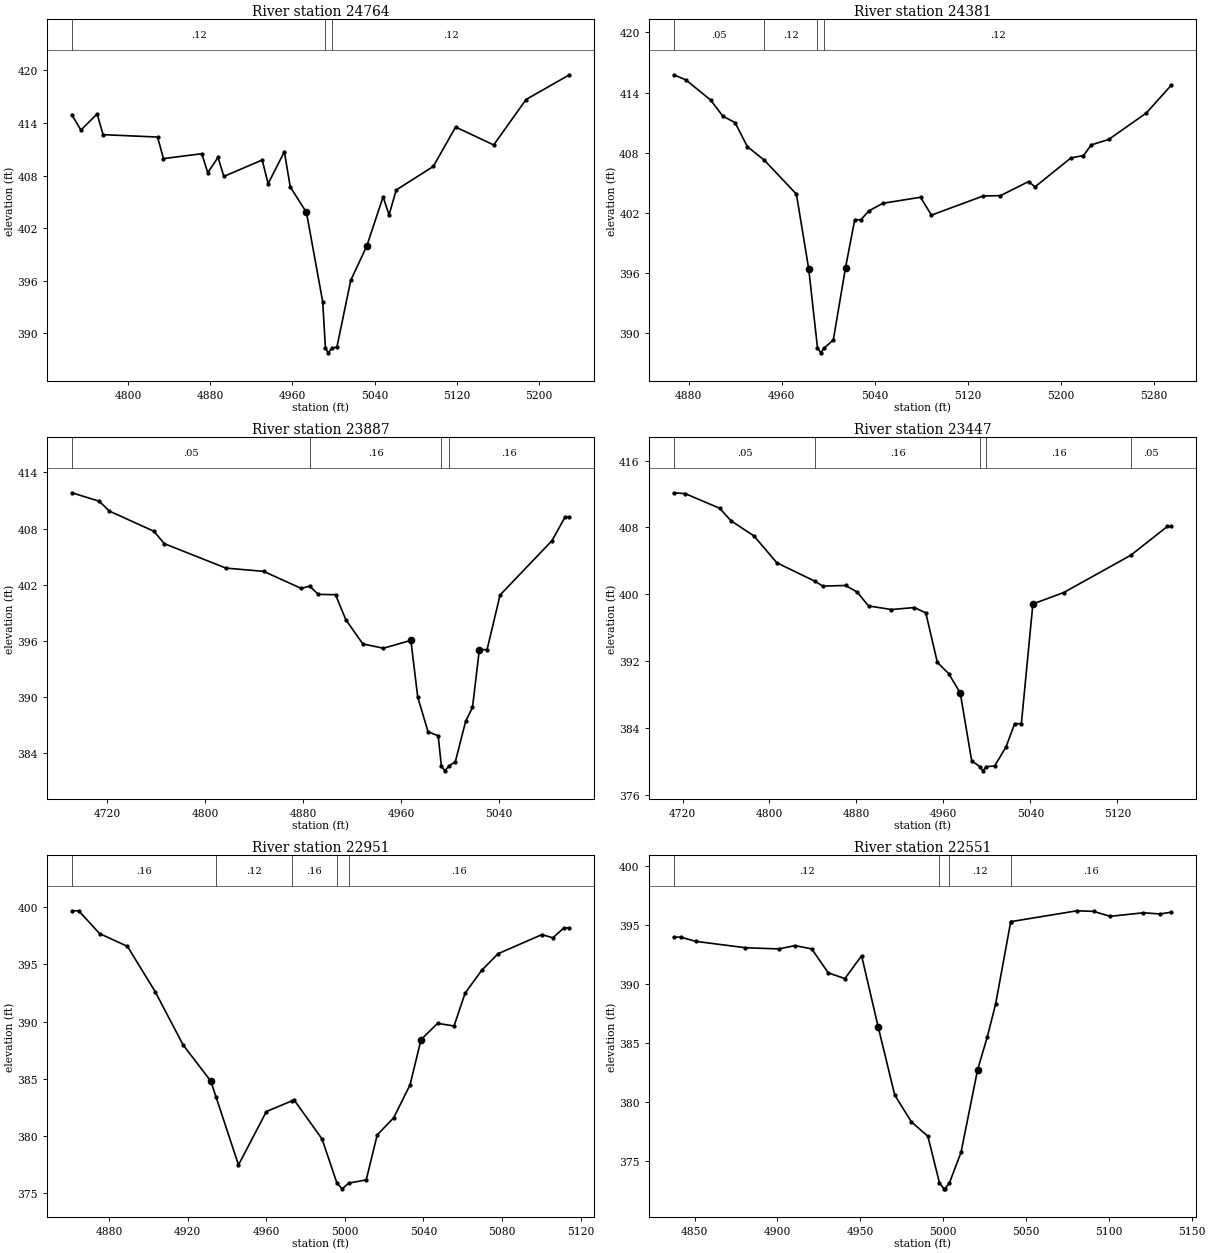
Type RM Length L Ch R = 1 ,24764   ,383,383,383
BEGIN DESCRIPTION:
HOLLY SPRING BRANCH 45.0
END DESCRIPTION:
XS GIS Cut Line= 2
      3720258.59     10682376.81      3720016.03      10682796.1
#Sta/Elev= 30
  4745.2  414.94    4754  413.19  4769.8  415.04  4775.6  412.67  4828.6   412.4
  4834.4  409.94  4871.7   410.5  4877.5  408.33  4887.5  410.08  4893.2  407.91
  4930.5  409.78  4936.3  407.08  4952.1  410.73  4957.8  406.72  4973.6   403.8
  4989.4  393.64  4992.1  388.29  4994.9  387.79  4998.1  388.29  5003.3  388.47
  5016.7  396.05  5032.4  399.99  5048.2  405.58    5054  403.52    5061  406.36
  5097.1  409.05  5118.8  413.54  5155.9   411.5  5187.4  416.68  5229.6   419.5
#Mann= 3 ,-1 , 0
  4745.2     .12       0  4992.1     .07       0  4998.1     .12       0
Bank Sta=4973.6,5032.4
XS Rating Curve= 0 ,0
Exp/Cntr=0.3,0.1

Type RM Length L Ch R = 1 ,24381   ,494,494,494
BEGIN DESCRIPTION:
HOLLY SPRING BRANCH 44.0
END DESCRIPTION:
XS GIS Cut Line= 3
      3719849.62     10682310.16      3719799.61     10682460.19
      3719899.61     10682710.18
#Sta/Elev= 30
  4867.2  415.77  4877.8  415.25  4898.9  413.25  4909.4  411.65  4919.9     411
  4930.5   408.6    4945  407.26  4972.6  403.87  4983.2  396.39  4990.7  388.55
  4993.5  388.05  4996.7  388.55  5004.3  389.34  5014.8  396.55  5022.7  401.32
    5028  401.32  5034.8   402.2  5046.9  402.96  5079.2  403.56  5088.6  401.78
  5133.1  403.69  5147.9  403.72  5172.1  405.13  5177.5  404.59  5208.4  407.48
  5219.2  407.72  5225.9  408.78  5240.8  409.32  5273.1  411.95  5294.6  414.73
#Mann= 4 ,-1 , 0
  4867.2     .05       0    4945     .12       0  4990.7     .07       0
  4996.7     .12       0
Bank Sta=4983.2,5014.8
XS Rating Curve= 0 ,0
Exp/Cntr=0.3,0.1

Type RM Length L Ch R = 1 ,23887   ,440,440,440
BEGIN DESCRIPTION:
HOLLY SPRING BRANCH 43.0
END DESCRIPTION:
XS GIS Cut Line= 3
      3719649.58      10682210.2      3719349.61     10682360.19
       3719299.6      10682410.2
#Sta/Elev= 30
  4691.2  411.82  4713.5  410.92  4721.9  409.86  4758.2  407.71  4766.6  406.39
  4816.9  403.78  4847.7  403.43  4878.4  401.61  4885.3  401.85  4892.4  400.97
  4906.4  400.94  4914.8  398.27  4928.7  395.68  4945.5  395.22  4967.9  396.06
  4973.5     390  4981.9  386.31  4990.2  385.87  4992.8  382.63  4995.6  382.13
  4998.8  382.63  5004.2  383.11  5012.6  387.41  5018.2   388.9  5023.8  395.07
  5030.1  395.07  5040.7   400.9  5083.1  406.71  5093.8  409.24  5097.3  409.24
#Mann= 4 ,-1 , 0
  4691.2     .05       0  4885.3     .16       0  4992.8     .07       0
  4998.8     .16       0
Bank Sta=4967.9,5023.8
XS Rating Curve= 0 ,0
Exp/Cntr=0.3,0.1

Type RM Length L Ch R = 1 ,23447   ,496,496,496
BEGIN DESCRIPTION:
HOLLY SPRING BRANCH 42.0
END DESCRIPTION:
XS GIS Cut Line= 3
      3719399.64     10681910.18      3719099.61     10682010.19
       3718999.6      10682110.2
#Sta/Elev= 30
  4711.9  412.14  4722.5  412.04  4754.1  410.29  4764.6  408.79  4785.7  406.98
  4806.8  403.76  4842.2  401.53    4849  400.97    4870  401.05  4880.6  400.27
  4891.1   398.6  4912.2  398.17  4933.3  398.41  4943.8  397.77  4954.4  391.85
  4964.9  390.49  4975.5  388.18    4986  380.07  4993.5  379.37  4996.3  378.87
  4999.5  379.37  5007.1  379.45  5017.6  381.73  5025.5  384.51  5031.7  384.51
  5042.3  398.84  5070.6   400.2  5132.3  404.66    5166  408.11  5169.6  408.11
#Mann= 5 ,-1 , 0
  4711.9     .05       0  4842.2     .16       0  4993.5     .07       0
  4999.5     .16       0  5132.3     .05       0
Bank Sta=4975.5,5042.3
XS Rating Curve= 0 ,0
Exp/Cntr=0.3,0.1

Type RM Length L Ch R = 1 ,22951   ,400,400,400
BEGIN DESCRIPTION:
HOLLY SPRING BRANCH 41.0
END DESCRIPTION:
XS GIS Cut Line= 3
       3718899.6      10681560.2      3718799.61     10681660.19
      3718749.61     10681760.18
#Sta/Elev= 30
  4861.1  399.68  4864.6  399.68  4875.2  397.69  4889.4  396.57  4903.5  392.62
  4917.7  387.97  4931.8  384.81  4934.4  383.46  4945.9  377.49  4960.1  382.15
  4972.9  383.07  4974.2  383.16  4988.4  379.76    4996   375.9  4998.7   375.4
    5002   375.9  5010.9  376.18  5016.5  380.11  5024.9  381.61  5033.2  384.48
  5038.8  388.43  5047.2  389.85  5055.6  389.62  5061.2  392.48  5069.6  394.47
    5078  395.93  5100.3   397.6  5105.9  397.32  5111.5  398.19  5114.3  398.19
#Mann= 5 ,-1 , 0
  4861.1     .16       0  4934.4     .12       0  4972.9     .16       0
    4996     .07       0    5002     .16       0
Bank Sta=4931.8,5038.8
XS Rating Curve= 0 ,0
Exp/Cntr=0.3,0.1

Type RM Length L Ch R = 1 ,22551   ,558,558,558
BEGIN DESCRIPTION:
HOLLY SPRING BRANCH 40.0
END DESCRIPTION:
XS GIS Cut Line= 2
       3718752.9     10681441.75      3718452.77      10681431.4
#Sta/Elev= 30
  4837.4  393.99  4841.5  393.99  4850.7  393.63  4880.7  393.09  4900.7  392.99
  4910.7  393.27  4920.7  392.99  4930.7  390.96  4940.7  390.48  4950.8  392.41
  4960.8  386.39  4970.8  380.61  4980.8  378.35  4990.8  377.12  4997.8  373.17
  5000.5  372.67    5001  372.67  5003.8  373.17  5010.8  375.76  5020.8  382.75
  5026.7  385.56  5031.7  388.33  5040.8   395.3  5040.9   395.3  5080.8  396.22
  5090.8  396.17  5100.8  395.75  5120.9  396.05  5130.9  395.95  5137.7   396.1
#Mann= 4 ,-1 , 0
  4837.4     .12       0  4997.8     .07       0  5003.8     .12       0
  5040.9     .16       0
Bank Sta=4960.8,5020.8
XS Rating Curve= 0 ,0
Exp/Cntr=0.3,0.1

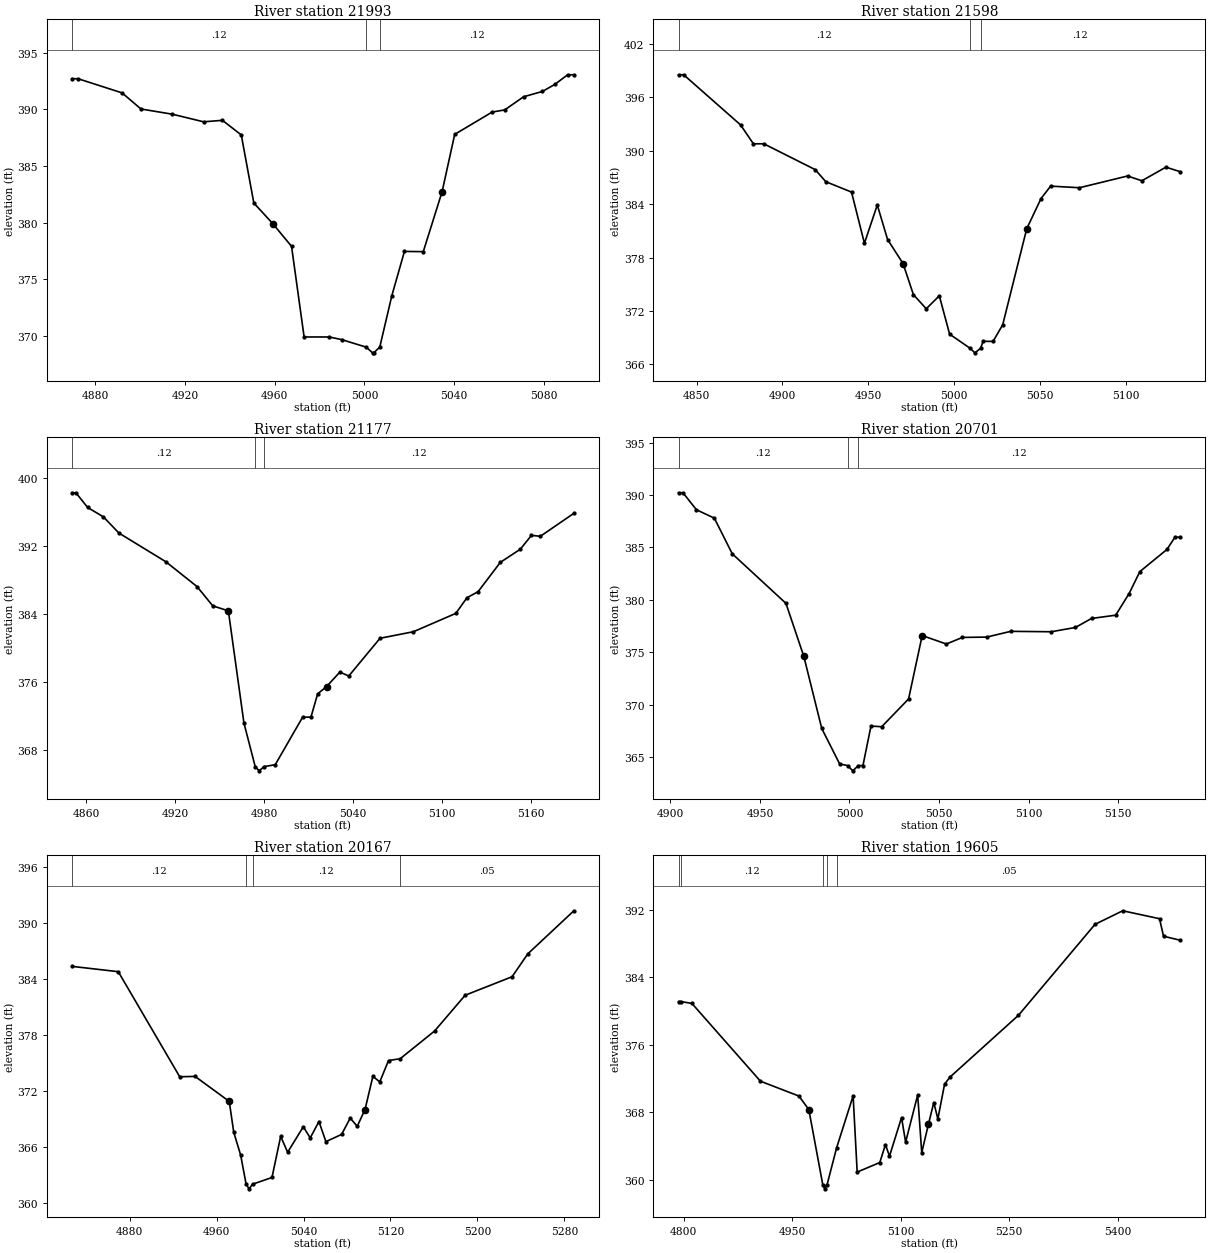
Type RM Length L Ch R = 1 ,21993   ,395,395,395
BEGIN DESCRIPTION:
HOLLY SPRING BRANCH 39.0
END DESCRIPTION:
XS GIS Cut Line= 3
      3718349.57     10681110.21      3718249.61     10681160.19
      3718149.57     10681210.21
#Sta/Elev= 30
  4869.7   392.7  4872.4   392.7    4892  391.45  4900.4  390.03  4914.4  389.57
  4928.3   388.9  4936.7  389.03  4945.1  387.74  4950.7  381.73  4959.1  379.92
  4967.5  377.91  4973.1  369.91  4984.3  369.91  4989.8  369.68  5000.8  369.01
  5003.6  368.51  5004.1  368.51  5006.8  369.01  5012.2  373.56  5017.8  377.46
  5026.2  377.44  5034.6  382.74  5040.2  387.79  5056.9  389.76  5062.5  389.95
  5070.9  391.11  5079.3  391.58  5084.9  392.21  5090.5  393.05  5093.3  393.05
#Mann= 3 ,-1 , 0
  4869.7     .12       0  5000.8     .07       0  5006.8     .12       0
Bank Sta=4959.1,5034.6
XS Rating Curve= 0 ,0
Exp/Cntr=0.3,0.1

Type RM Length L Ch R = 1 ,21598   ,421,421,421
BEGIN DESCRIPTION:
HOLLY SPRING BRANCH 38.0
END DESCRIPTION:
XS GIS Cut Line= 3
      3718099.62     10680760.17      3717999.61     10680910.19
      3717899.62     10680960.19
#Sta/Elev= 30
  4839.5  398.54  4842.5  398.54  4875.6  392.91  4883.1  390.78  4889.1  390.79
  4919.1  387.88  4925.2  386.53  4940.2  385.36  4947.7  379.61  4955.2  383.91
  4961.2  380.03  4970.2  377.33  4976.2  373.85  4983.7  372.25  4991.3  373.71
  4997.3   369.4  5009.3   367.8    5012   367.3  5015.3   367.8  5016.8  368.59
  5022.6  368.59  5028.2  370.45  5042.2  381.25  5050.5  384.63  5056.1  386.03
  5072.9  385.85  5100.9  387.17  5109.2  386.63  5123.2  388.16  5131.6  387.65
#Mann= 3 ,-1 , 0
  4839.5     .12       0  5009.3     .07       0  5015.3     .12       0
Bank Sta=4970.2,5042.2
XS Rating Curve= 0 ,0
Exp/Cntr=0.3,0.1

Type RM Length L Ch R = 1 ,21177   ,476,476,476
BEGIN DESCRIPTION:
HOLLY SPRING BRANCH 37.0
END DESCRIPTION:
XS GIS Cut Line= 3
      3717599.61      10680660.2      3717649.61     10680810.19
      3717749.62     10680960.21
#Sta/Elev= 30
  4850.6  398.27  4853.2  398.27  4861.1  396.54  4871.7  395.44  4882.2  393.53
  4913.8  390.16  4934.9  387.23  4945.5  384.96    4956  384.38  4966.5  371.18
  4974.1  366.05  4976.8  365.55  4980.1  366.05  4987.6  366.27  5006.1  371.87
  5011.7  371.87  5016.2  374.61  5022.2  375.46  5031.2  377.17  5037.2  376.71
  5058.3  381.15  5080.8  381.92  5109.4  384.08  5116.9  385.92  5124.4  386.63
  5139.4  390.08  5152.9  391.63  5160.4  393.26  5166.4  393.15    5189  395.85
#Mann= 3 ,-1 , 0
  4850.6     .12       0  4974.1     .07       0  4980.1     .12       0
Bank Sta=4956,5022.2
XS Rating Curve= 0 ,0
Exp/Cntr=0.3,0.1

Type RM Length L Ch R = 1 ,20701   ,534,534,534
BEGIN DESCRIPTION:
HOLLY SPRING BRANCH 36.0
END DESCRIPTION:
XS GIS Cut Line= 3
      3717199.61     10680810.19      3717199.61     10680910.19
      3717299.62     10681060.21
#Sta/Elev= 30
  4904.5  390.22    4907  390.22  4914.5   388.6  4924.5   387.8  4934.5   384.4
  4964.5  379.67  4974.5   374.6  4984.5  367.73  4994.5  364.35    4999  364.19
  5001.8  363.69    5005  364.19  5007.5  364.19    5012  367.96    5018   367.9
    5033  370.55  5040.6   376.6  5054.1  375.79  5063.1  376.42  5076.6  376.45
  5090.1     377  5112.7  376.96  5126.2  377.37  5135.2  378.23  5148.7  378.54
  5156.2  380.61  5162.2   382.7  5177.3  384.81  5181.8  385.98  5184.8  385.98
#Mann= 3 ,-1 , 0
  4904.5     .12       0    4999     .07       0    5005     .12       0
Bank Sta=4974.5,5040.6
XS Rating Curve= 0 ,0
Exp/Cntr=0.3,0.1

Type RM Length L Ch R = 1 ,20167   ,562,562,562
BEGIN DESCRIPTION:
HOLLY SPRING BRANCH 35.0
END DESCRIPTION:
XS GIS Cut Line= 3
      3716899.63     10680810.17      3716799.61     10680910.19
      3716599.61     10681160.19
#Sta/Elev= 30
  4827.1  385.38  4869.6  384.81  4926.1  373.53  4940.3  373.56  4971.7  370.88
  4975.8  367.58  4982.2  365.11  4987.2  361.99  4989.9  361.49  4993.2  361.99
    5011  362.71    5019  367.13  5025.4  365.42  5039.8  368.15  5046.2  366.96
  5054.2  368.72  5060.6  366.56    5075  367.33    5083  369.09  5089.4   368.2
  5096.6  370.01  5103.8  373.56  5110.2  372.98  5118.2  375.27  5128.9  375.46
  5160.6  378.44  5188.7  382.28  5231.9  384.27  5246.3  386.72  5288.7  391.35
#Mann= 4 ,-1 , 0
  4827.1     .12       0  4987.2     .07       0  4993.2     .12       0
  5128.9     .05       0
Bank Sta=4971.7,5096.6
XS Rating Curve= 0 ,0
Exp/Cntr=0.3,0.1

Type RM Length L Ch R = 1 ,19605   ,101,101,101
BEGIN DESCRIPTION:
HOLLY SPRING BRANCH 34.0
END DESCRIPTION:
XS GIS Cut Line= 2
      3716414.39     10680561.56       3716101.9     10681181.34
#Sta/Elev= 30
  4792.8  381.11    4796  381.12  4811.3   380.9  4906.1  371.67  4959.3  369.91
    4973  368.31  4992.3   359.4  4995.1   358.9  4998.3   359.4  5011.4  363.75
  5034.3  369.93  5039.9  360.89  5071.2  362.02    5079  364.15  5084.6  362.78
  5101.3  367.36  5106.9  364.44  5123.6  370.04  5129.2  363.19  5138.4  366.54
  5145.9  369.14  5151.5  367.19  5160.8  371.32  5168.2  372.15    5263  379.49
  5368.9  390.28  5407.2  391.89  5458.1  390.95  5463.7  388.87  5486.9  388.39
#Mann= 5 ,-1 , 0
  4792.8     .05       0    4796     .12       0  4992.3     .07       0
  4998.3     .12       0  5011.4     .05       0
Bank Sta=4973,5138.4
XS Rating Curve= 0 ,0
Exp/Cntr=0.3,0.1

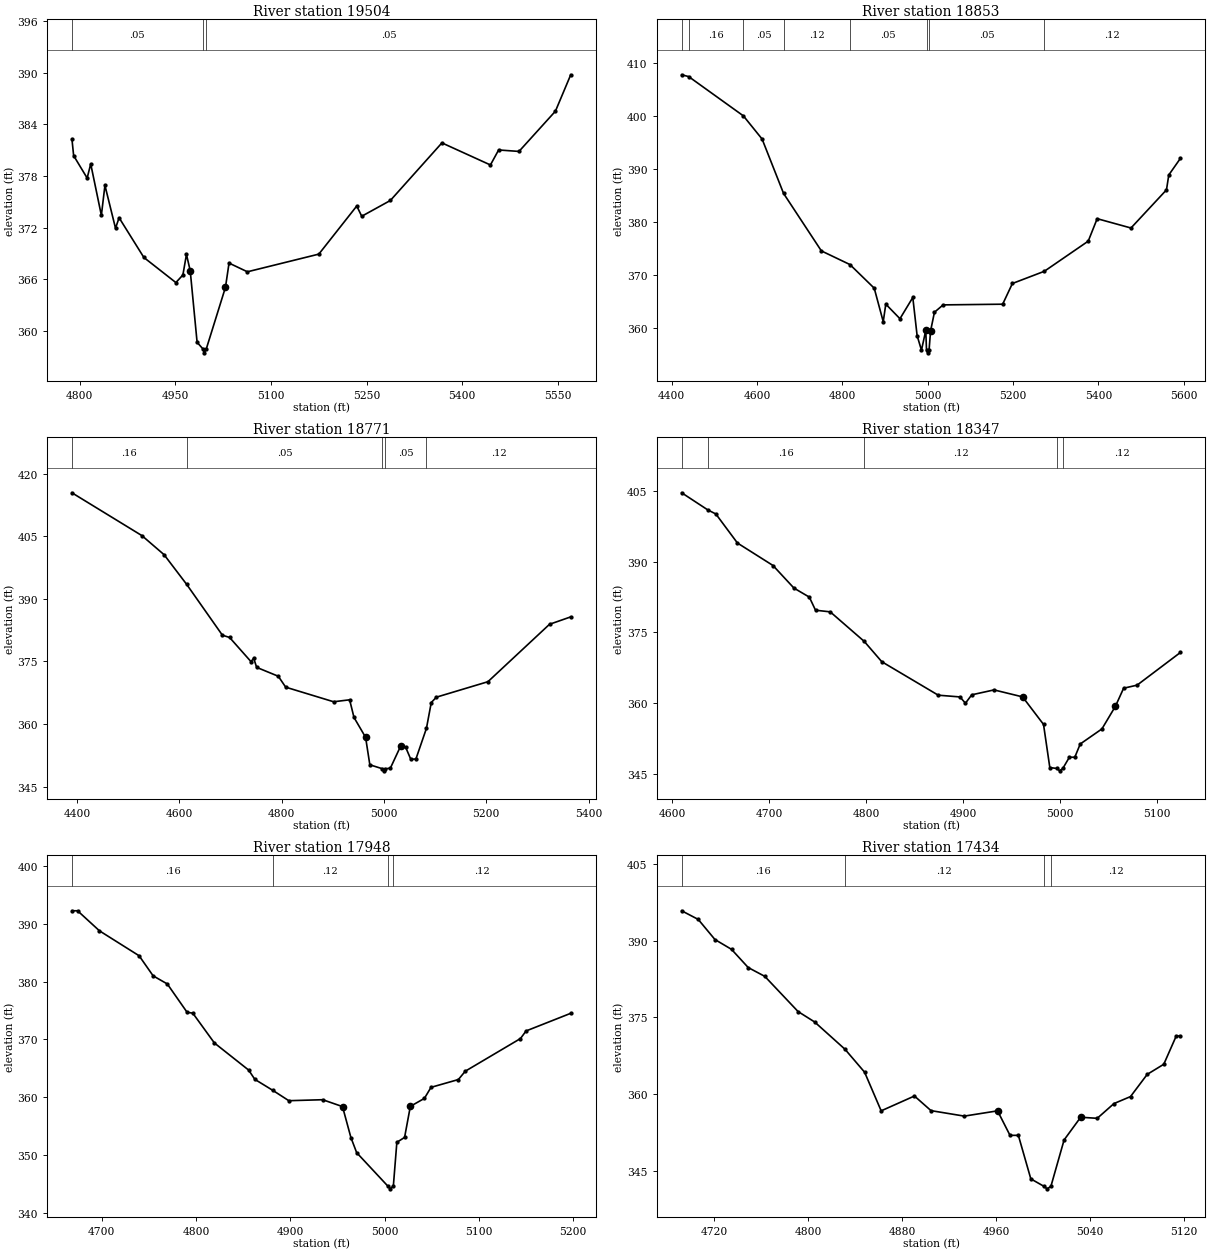
Type RM Length L Ch R = 1 ,19504   ,1157,1157,1157
BEGIN DESCRIPTION:
HOLLY SPRING BRANCH 33.0
END DESCRIPTION:
XS GIS Cut Line= 2
      3716325.84      10680514.7      3715971.69     10681212.58
#Sta/Elev= 30
  4787.8  382.31  4790.5  380.36  4811.7  377.76  4817.3   379.4    4834  373.44
  4839.6  376.91  4856.2  371.94  4861.8  373.16  4900.7  368.55  4950.9  365.64
  4961.9  366.52  4967.5   368.9  4973.4  367.02  4984.2  358.71  4992.8  357.99
  4995.6  357.49  4998.8  357.99  5028.7  365.09  5034.3   367.9  5063.1  366.89
  5175.2  368.94  5234.7  374.52  5242.5  373.33  5287.4  375.16  5368.3  381.84
  5444.4  379.28  5457.3  381.02  5489.2  380.85  5546.4  385.52  5570.4  389.74
#Mann= 3 ,-1 , 0
  4787.8     .05       0  4992.8     .04       0  4998.8     .05       0
Bank Sta=4973.4,5028.7
XS Rating Curve= 0 ,0
Exp/Cntr=0.3,0.1

Type RM Length L Ch R = 1 ,18853   ,82,82,82
BEGIN DESCRIPTION:
Mapping XS 754cb1a3
END DESCRIPTION:
XS GIS Cut Line= 6
      3715159.65      10680631.9      3715410.97     10680710.03
       3715615.4     10680842.84      3715938.32     10680898.83
      3716015.14     10681016.02      3715942.58     10681196.13
#Sta/Elev= 30
  4423.2  407.78  4439.6  407.44  4567.9  400.02  4611.7  395.65    4662  385.39
  4750.6  374.54  4817.6  371.96  4874.5   367.5  4895.6  361.18  4901.6  364.49
  4934.8  361.74  4964.9  365.75    4975  358.54  4985.2   355.8  4995.3  359.53
    4997   355.8  4999.8   355.3    5003   355.8  5006.5  359.41  5015.6  362.96
  5035.9  364.35  5175.5  364.48  5198.3  368.39  5273.1  370.69    5376  376.38
    5397  380.62  5476.2  378.86  5559.4  386.06  5564.8  388.87  5592.2  392.02
#Mann= 8 ,-1 , 0
  4423.2     .05       0  4439.6     .16       0  4567.9     .05       0
    4662     .12       0  4817.6     .05       0    4997     .04       0
    5003     .05       0  5273.1     .12       0
Bank Sta=4995.3,5006.5
XS Rating Curve= 0 ,0
Exp/Cntr=0.3,0.1

Type RM Length L Ch R = 1 ,18771   ,424,424,424
BEGIN DESCRIPTION:
Mapping XS 821c8a7e
END DESCRIPTION:
XS GIS Cut Line= 5
      3715093.22      10680819.4      3715386.23     10680845.45
      3715647.95     10680935.29      3715860.19      10680941.8
      3715940.36     10681116.35
#Sta/Elev= 30
  4389.9  415.46  4526.8  405.18  4570.1  400.61  4614.2   393.5  4684.1   381.3
  4698.2  380.75    4740  374.96  4745.3  375.76  4751.1  373.58  4793.4  371.45
  4807.9  368.83  4901.6  365.33  4932.9   365.8  4941.4  361.57  4964.1   356.8
  4972.4  350.21    4997  349.26  4999.8  348.76    5003  349.26  5012.5  349.39
  5032.5  354.66  5042.5   354.4  5052.5  351.52  5062.5   351.6  5083.1  358.96
  5092.5  365.14  5102.5  366.43  5203.3  370.14  5323.7  383.91  5365.2  385.69
#Mann= 5 ,-1 , 0
  4389.9     .16       0  4614.2     .05       0    4997     .04       0
    5003     .05       0  5083.1     .12       0
Bank Sta=4964.1,5032.5
XS Rating Curve= 0 ,0
Exp/Cntr=0.3,0.1

Type RM Length L Ch R = 1 ,18347   ,399,399,399
BEGIN DESCRIPTION:
HOLLY SPRING BRANCH 31.0
END DESCRIPTION:
XS GIS Cut Line= 3
      3715149.58     10681010.17      3715499.61     10681210.19
      3715599.65     10681260.21
#Sta/Elev= 30
  4609.5   404.6  4636.5  400.96  4644.8   400.1  4667.1  393.93  4703.8  389.16
  4725.4  384.37  4741.3  382.45  4747.7  379.67  4762.9  379.32    4798  373.05
  4816.1  368.74  4874.4  361.63  4896.8  361.26  4902.5  359.93    4909  361.71
    4932  362.75  4961.5  361.27  4983.1  355.43  4989.6  346.27    4997  346.07
  4999.8  345.57    5003  346.07  5009.8  348.46  5015.4  348.46    5021  351.27
  5043.4  354.47  5057.4   359.3  5065.8  363.11  5079.7  363.76  5124.5  370.71
#Mann= 5 ,-1 , 0
  4609.5     .05       0  4636.5     .16       0    4798     .12       0
    4997     .07       0    5003     .12       0
Bank Sta=4961.5,5057.4
XS Rating Curve= 0 ,0
Exp/Cntr=0.3,0.1

Type RM Length L Ch R = 1 ,17948   ,514,514,514
BEGIN DESCRIPTION:
HOLLY SPRING BRANCH 30.0
END DESCRIPTION:
XS GIS Cut Line= 2
      3715044.65     10681295.94      3715482.13      10681592.8
#Sta/Elev= 30
  4668.6  392.27  4674.6  392.27  4697.8   388.8  4739.8  384.49  4754.7  381.01
  4769.7  379.61  4790.7   374.7  4796.7  374.56  4819.6   369.4  4855.9  364.71
  4862.5   363.1  4881.7  361.18  4898.5  359.41  4934.4  359.58  4955.4  358.39
  4964.3  353.04  4970.4  350.42  5003.3  344.66    5006  344.16  5009.3  344.66
    5013  352.21  5021.2  353.06  5027.3  358.43  5042.2  359.81  5049.2  361.72
  5078.2  363.07  5085.5  364.51    5144  370.16    5150  371.48  5197.3  374.53
#Mann= 4 ,-1 , 0
  4668.6     .16       0  4881.7     .12       0  5003.3     .07       0
  5009.3     .12       0
Bank Sta=4955.4,5027.3
XS Rating Curve= 0 ,0
Exp/Cntr=0.3,0.1

Type RM Length L Ch R = 1 ,17434   ,464,464,464
BEGIN DESCRIPTION:
HOLLY SPRING BRANCH 29.0
END DESCRIPTION:
XS GIS Cut Line= 3
      3714699.62     10681510.19      3714899.61     10681710.19
      3714999.64     10681810.22
#Sta/Elev= 30
  4692.6  395.83  4706.7  394.14  4720.9  390.21    4735  388.29  4749.2  384.73
  4763.3  383.01  4791.6  376.13  4805.7  374.09  4831.5  368.76  4848.2  364.27
  4862.3  356.71  4890.6  359.61  4904.7  356.75    4933  355.68  4961.3  356.71
  4971.9  351.92    4979  351.92  4989.6  343.41  5000.7  341.96  5003.5  341.46
  5006.7  341.96  5017.9  351.02    5032  355.46  5046.1  355.25  5060.3  358.13
  5074.4   359.5  5088.6  363.84  5102.7  365.82  5113.3  371.35  5116.9  371.35
#Mann= 4 ,-1 , 0
  4692.6     .16       0  4831.5     .12       0  5000.7     .07       0
  5006.7     .12       0
Bank Sta=4961.3,5032
XS Rating Curve= 0 ,0
Exp/Cntr=0.3,0.1

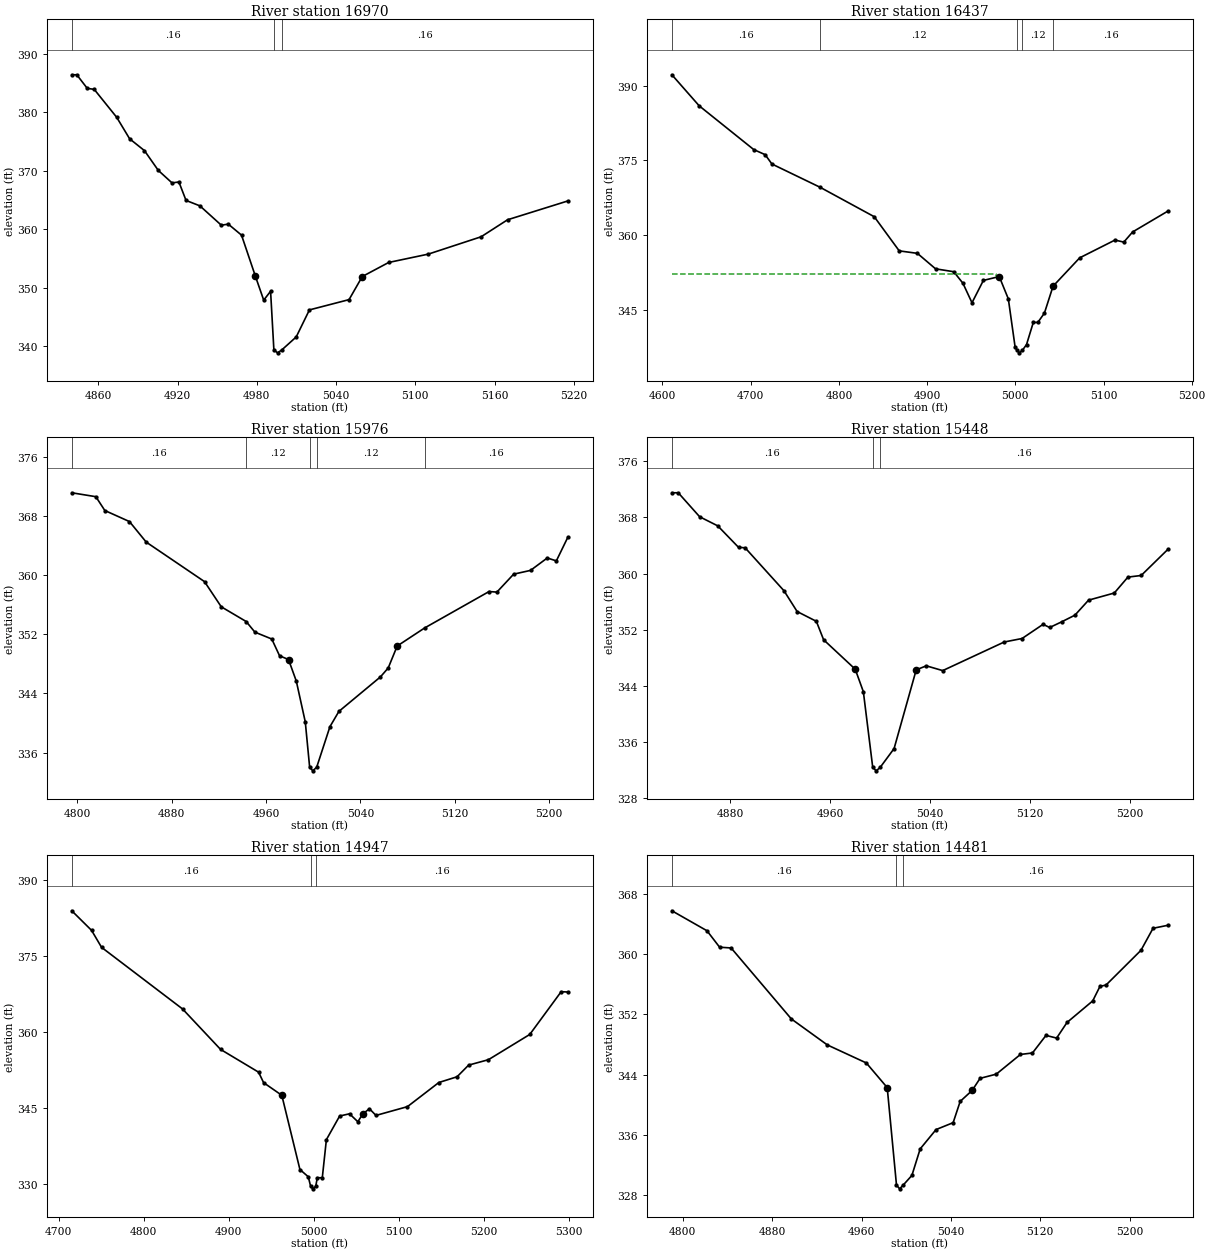
Type RM Length L Ch R = 1 ,16970   ,533,533,533
BEGIN DESCRIPTION:
Mapping XS 9def8324
END DESCRIPTION:
XS GIS Cut Line= 3
      3714549.42     10681657.86      3714501.26     10681807.57
      3714498.66     10682025.78
#Sta/Elev= 30
  4839.9  386.42  4843.7  386.42  4851.6   384.1  4856.9  383.92  4873.9  379.14
  4883.7  375.46  4894.9  373.44  4905.4  370.05  4915.8  367.91    4921  368.07
  4926.4  364.91  4936.9  363.98  4953.1  360.67  4958.4  360.85  4968.4  358.97
  4978.9  351.94  4985.2  347.84  4990.4  349.36  4992.9  339.32  4995.7  338.82
  4998.9  339.32  5009.8  341.54  5019.8  346.17  5049.8  347.93  5059.8  351.88
  5079.8  354.29  5109.8  355.72  5149.8  358.69  5169.8   361.6  5215.4  364.82
#Mann= 3 ,-1 , 0
  4839.9     .16       0  4992.9     .07       0  4998.9     .16       0
Bank Sta=4978.9,5059.8
XS Rating Curve= 0 ,0
Exp/Cntr=0.3,0.1

Type RM Length L Ch R = 1 ,16437   ,461,461,461
BEGIN DESCRIPTION:
HOLLY SPRING BRANCH 27.0
END DESCRIPTION:
XS GIS Cut Line= 3
      3713999.61     10681510.18      3714099.61     10681910.19
      3714099.61     10682060.17
#Sta/Elev= 30
  4610.7  392.21  4641.6  385.98  4703.5  377.18  4716.4  376.16  4724.1  374.28
  4778.9  369.59  4840.1  363.69  4868.4  356.83    4889  356.33  4909.6  353.22
  4930.2  352.64  4940.6  350.33  4950.9   346.4  4963.8  350.89  4981.8  351.67
  4992.1  347.18  4999.8  337.48    5002  336.84  5004.7  336.34    5008  336.84
  5012.7  337.99  5020.4  342.45  5025.5  342.45    5033  344.32  5042.8  349.73
    5073  355.43    5113     359    5123  358.59    5133  360.63    5173  364.82
#Mann= 5 ,-1 , 0
  4610.7     .16       0  4778.9     .12       0    5002     .07       0
    5008     .12       0  5042.8     .16       0
#XS Ineff= 2 , 0
         4978.16  352.09
Permanent Ineff=
       F       F
Bank Sta=4981.8,5042.8
XS Rating Curve= 0 ,0
Exp/Cntr=0.3,0.1

Type RM Length L Ch R = 1 ,15976   ,528,528,528
BEGIN DESCRIPTION:
HOLLY SPRING BRANCH 26.0
END DESCRIPTION:
XS GIS Cut Line= 2
       3713612.6     10681848.27      3713888.33     10682165.62
#Sta/Elev= 30
  4795.3  371.17  4815.7  370.64  4823.3  368.77  4844.2  367.27  4858.4  364.49
  4907.8  359.14    4922  355.73  4943.1  353.74  4950.5   352.3  4964.8  351.37
  4971.4   349.1    4979  348.59  4985.6  345.67  4993.2  340.15  4996.9  334.02
  4999.6  333.52  5002.9  334.02  5014.1   339.5  5021.7  341.57  5056.9  346.24
  5063.5  347.45  5071.1  350.42  5094.4  352.87    5149   357.8  5155.6  357.72
  5169.8  360.15  5184.1  360.66  5198.3  362.34    5206  361.95  5215.7  365.14
#Mann= 5 ,-1 , 0
  4795.3     .16       0  4943.1     .12       0  4996.9     .07       0
  5002.9     .12       0  5094.4     .16       0
Bank Sta=4979,5071.1
XS Rating Curve= 0 ,0
Exp/Cntr=0.3,0.1

Type RM Length L Ch R = 1 ,15448   ,501,501,501
BEGIN DESCRIPTION:
HOLLY SPRING BRANCH 25.0
END DESCRIPTION:
XS GIS Cut Line= 2
      3713294.92     10682327.46      3713669.86     10682457.65
#Sta/Elev= 30
  4833.3  371.52  4838.4  371.52  4855.5   368.1    4870   366.8  4886.6  363.74
  4891.9  363.67    4923  357.54  4933.5  354.58  4948.9  353.18  4954.7  350.55
    4980  346.35  4986.5  343.14    4994  332.35  4996.8  331.85    5000  332.35
  5011.1  335.03  5028.8  346.26  5036.9  346.83    5050  346.15  5099.2  350.23
  5113.5  350.73  5130.3  352.75  5135.6   352.3  5145.2  353.11  5155.8  354.06
  5166.7   356.2  5187.3  357.22  5198.2  359.49  5208.8  359.72  5230.2  363.45
#Mann= 3 ,-1 , 0
  4833.3     .16       0    4994     .07       0    5000     .16       0
Bank Sta=4980,5028.8
XS Rating Curve= 0 ,0
Exp/Cntr=0.3,0.1

Type RM Length L Ch R = 1 ,14947   ,466,466,466
BEGIN DESCRIPTION:
HOLLY SPRING BRANCH 24.0
END DESCRIPTION:
XS GIS Cut Line= 3
       3712999.6     10682610.18      3713249.61     10682760.19
      3713399.61     10683010.19
#Sta/Elev= 30
  4715.6   383.9  4738.9  380.03  4750.6  376.69  4845.8  364.54  4890.5  356.56
  4935.2  352.07  4941.1     350  4962.5  347.51  4983.8  332.87  4993.6  331.44
  4996.4  329.56  4999.1  329.06  5002.4  329.56  5004.2  331.25  5010.1  331.25
  5014.9  338.76  5030.5  343.42  5042.1  343.86  5051.9  342.29  5057.7  343.83
  5065.5  344.86  5073.2  343.54  5110.2  345.27  5147.1  350.03  5168.5  351.16
  5182.1  353.46  5205.4  354.53    5254  359.51  5290.9  367.94  5298.7  367.88
#Mann= 3 ,-1 , 0
  4715.6     .16       0  4996.4     .07       0  5002.4     .16       0
Bank Sta=4962.5,5057.7
XS Rating Curve= 0 ,0
Exp/Cntr=0.3,0.1

Type RM Length L Ch R = 1 ,14481   ,424,424,424
BEGIN DESCRIPTION:
HOLLY SPRING BRANCH 23.0
END DESCRIPTION:
XS GIS Cut Line= 2
      3712810.52     10683040.99      3713221.95     10683207.65
#Sta/Elev= 30
  4790.3   365.8  4821.7  363.14    4833  360.95  4843.3  360.85  4897.2   351.4
  4929.4  347.94  4964.3  345.54    4983  342.26  4991.3  329.28  4994.1  328.78
  4997.3  329.28  5005.1  330.57  5012.5   334.1  5026.7  336.67    5042  337.59
  5048.3  340.42    5059  341.88  5066.1  343.49  5080.6  344.05  5102.2  346.67
    5113  346.87  5125.1  349.21  5134.6  348.85  5143.9  350.93  5166.9   353.8
  5173.4  355.74  5178.8  355.91  5210.1  360.54  5220.9  363.47  5234.2  363.87
#Mann= 3 ,-1 , 0
  4790.3     .16       0  4991.3     .07       0  4997.3     .16       0
Bank Sta=4983,5059
XS Rating Curve= 0 ,0
Exp/Cntr=0.3,0.1

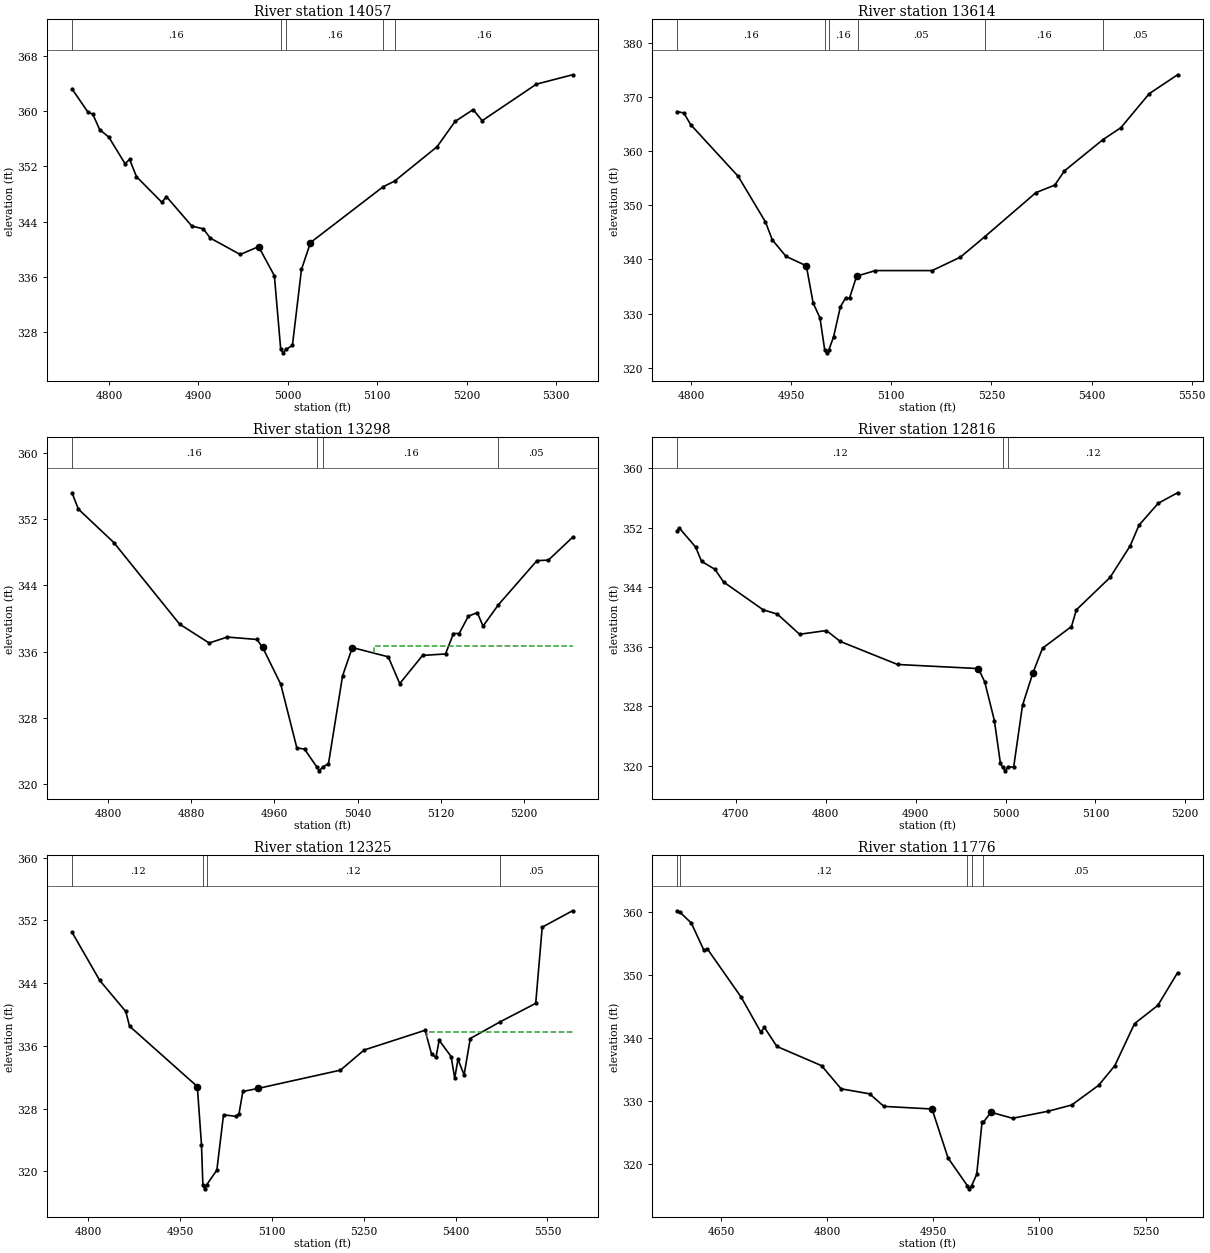
Type RM Length L Ch R = 1 ,14057   ,443,443,443
BEGIN DESCRIPTION:
HOLLY SPRING BRANCH 22.0
END DESCRIPTION:
XS GIS Cut Line= 3
      3712649.63     10683560.18      3712849.61     10683510.19
      3713199.62     10683560.19
#Sta/Elev= 30
  4758.6  363.25  4776.6  359.84  4781.8   359.6  4789.5  357.35  4799.8  356.25
  4817.9  352.41    4823  353.03  4830.7  350.53  4859.1  346.81  4864.2  347.63
  4892.6  343.37  4905.5  342.96  4913.2  341.63  4946.7  339.25  4967.3  340.39
  4984.9  336.17    4992   325.5  4994.8     325    4998   325.5  5005.1  326.08
  5015.2  337.08  5025.3  340.98  5106.6  349.07  5119.3  349.88  5166.8  354.86
    5187  358.53  5207.2  360.24  5217.3  358.64  5277.9  363.93  5318.3  365.29
#Mann= 5 ,-1 , 0
  4758.6     .16       0    4992     .07       0    4998     .16       0
  5106.6     .12       0  5119.3     .16       0
Bank Sta=4967.3,5025.3
XS Rating Curve= 0 ,0
Exp/Cntr=0.3,0.1

Type RM Length L Ch R = 1 ,13614   ,316,316,316
BEGIN DESCRIPTION:
HOLLY SPRING BRANCH 21.0
END DESCRIPTION:
XS GIS Cut Line= 3
      3712599.62     10683610.23      3712649.61     10683860.19
      3712999.62      10684210.2
#Sta/Elev= 30
    4779  367.36  4789.2  367.08  4799.4  364.93  4870.7  355.36  4911.5  346.93
  4921.7  343.63  4942.1  340.59  4972.7  338.83  4982.9  331.96  4993.1   329.2
  5000.3  323.24  5003.1  322.74  5006.3  323.24  5013.5  325.69  5023.7  331.24
  5031.4  332.85  5037.4  332.85  5048.1  336.94  5049.7  336.98  5076.3  337.95
  5161.2  337.95  5203.6  340.44  5239.7  344.17  5316.8  352.37    5345  353.75
  5359.2  356.36    5417  362.15    5444  364.37  5486.5  370.66  5528.9  374.15
#Mann= 6 ,-1 , 0
    4779     .16       0  5000.3     .07       0  5006.3     .16       0
  5049.7     .05       0  5239.7     .16       0    5417     .05       0
Bank Sta=4972.7,5048.1
XS Rating Curve= 0 ,0
Exp/Cntr=0.3,0.1

Type RM Length L Ch R = 1 ,13298   ,482,482,482
BEGIN DESCRIPTION:
HOLLY SPRING BRANCH 20.0
END DESCRIPTION:
XS GIS Cut Line= 2
      3712290.19     10683733.66      3712491.61     10684171.23
#Sta/Elev= 30
  4765.2  355.19  4771.3  353.22  4805.4  349.18  4868.7  339.32  4897.2  337.03
  4914.6  337.75  4943.1  337.46  4948.6  336.52  4966.1  332.05  4981.6  324.35
    4989  324.21  5000.6  322.08  5003.3  321.58  5006.6  322.08    5012  322.41
  5025.6  333.06    5035  336.48  5069.6  335.36  5080.6  332.12  5102.6  335.53
  5124.7  335.71  5132.3  338.18  5137.8  338.18  5146.7  340.28  5155.3   340.7
  5160.8  339.07  5175.6  341.66  5212.7  346.99  5223.7  347.05  5246.9   349.8
#Mann= 4 ,-1 , 0
  4765.2     .16       0  5000.6     .07       0  5006.6     .16       0
  5175.6     .05       0
#XS Ineff= 2 , 0
                         5055.46          336.65
Permanent Ineff=
       F       F
Bank Sta=4948.6,5035
XS Rating Curve= 0 ,0
Exp/Cntr=0.3,0.1

Type RM Length L Ch R = 1 ,12816   ,491,491,491
BEGIN DESCRIPTION:
HOLLY SPRING BRANCH 19.0
END DESCRIPTION:
XS GIS Cut Line= 2
      3711894.38     10683830.92      3712095.18     10684350.25
#Sta/Elev= 30
  4634.6   351.6  4637.2  351.94  4655.3  349.39  4661.8  347.48  4676.7  346.41
  4686.4   344.7  4730.3  340.97  4746.3  340.38  4770.9  337.68  4800.8  338.18
  4816.1  336.72  4879.9  333.62  4969.8  333.07  4976.9  331.28  4987.6  326.09
  4994.3  320.37  4996.7  319.83  4999.5  319.33  5002.7  319.83  5009.1  319.85
  5018.9  328.13  5030.5   332.5  5041.2  335.81  5073.4  338.72  5078.8  340.96
  5116.3  345.31  5138.7  349.56  5148.5  352.34  5169.9  355.28  5191.4  356.69
#Mann= 3 ,-1 , 0
  4634.6     .12       0  4996.7     .07       0  5002.7     .12       0
Bank Sta=4969.8,5030.5
XS Rating Curve= 0 ,0
Exp/Cntr=0.3,0.1

Type RM Length L Ch R = 1 ,12325   ,549,549,549
BEGIN DESCRIPTION:
HOLLY SPRING BRANCH 18.0
END DESCRIPTION:
XS GIS Cut Line= 2
      3711512.43     10683997.59      3711789.62     10684766.77
#Sta/Elev= 30
  4773.3  350.49  4818.6  344.34  4861.1  340.39  4867.3  338.51    4978  330.82
  4984.8  323.42  4987.1  318.28  4989.8  317.78  4993.1  318.28  5009.9  320.16
  5020.8  327.22  5040.8  327.02  5046.1  327.35  5052.4  330.19  5076.8  330.57
  5211.9  332.91  5250.4  335.47  5350.1  337.99  5360.7  334.94  5367.8  334.53
  5373.1  336.71  5392.6  334.64  5398.5  331.87  5403.8   334.3  5413.8   332.3
  5423.9  336.94  5472.8  339.07  5530.8  341.42  5541.4  351.13  5590.9  353.22
#Mann= 4 ,-1 , 0
  4773.3     .12       0  4987.1     .07       0  4993.1     .12       0
  5472.8     .05       0
#XS Ineff= 2 , 0
                         5353.51          337.74
Permanent Ineff=
       F       F
Bank Sta=4978,5076.8
XS Rating Curve= 0 ,0
Exp/Cntr=0.3,0.1

Type RM Length L Ch R = 1 ,11776   ,453,453,453
BEGIN DESCRIPTION:
HOLLY SPRING BRANCH 17.0
END DESCRIPTION:
XS GIS Cut Line= 3
      3711199.61      10684060.2      3711149.61     10684460.19
       3711199.6     10684760.15
#Sta/Elev= 30
  4587.9  360.17  4591.6  359.98    4608  358.23  4625.7  353.93  4630.7  354.12
  4678.6  346.43  4706.3  340.89  4711.3  341.64    4729  338.62    4792  335.57
  4819.7  331.89    4860  331.09  4880.1   329.1  4948.2  328.68  4970.8   320.9
  4998.1   316.5  5000.9     316  5004.1   316.5  5011.3  318.29  5018.9  326.67
  5020.5  326.55  5031.5  328.16    5062  327.21  5112.7  328.34  5145.6  329.32
  5183.6  332.45  5206.4  335.56  5234.3  342.24  5267.3  345.15  5295.1  350.33
#Mann= 5 ,-1 , 0
  4587.9     .05       0  4591.6     .12       0  4998.1     .07       0
  5004.1     .12       0  5020.5     .05       0
Bank Sta=4948.2,5031.5
XS Rating Curve= 0 ,0
Exp/Cntr=0.3,0.1