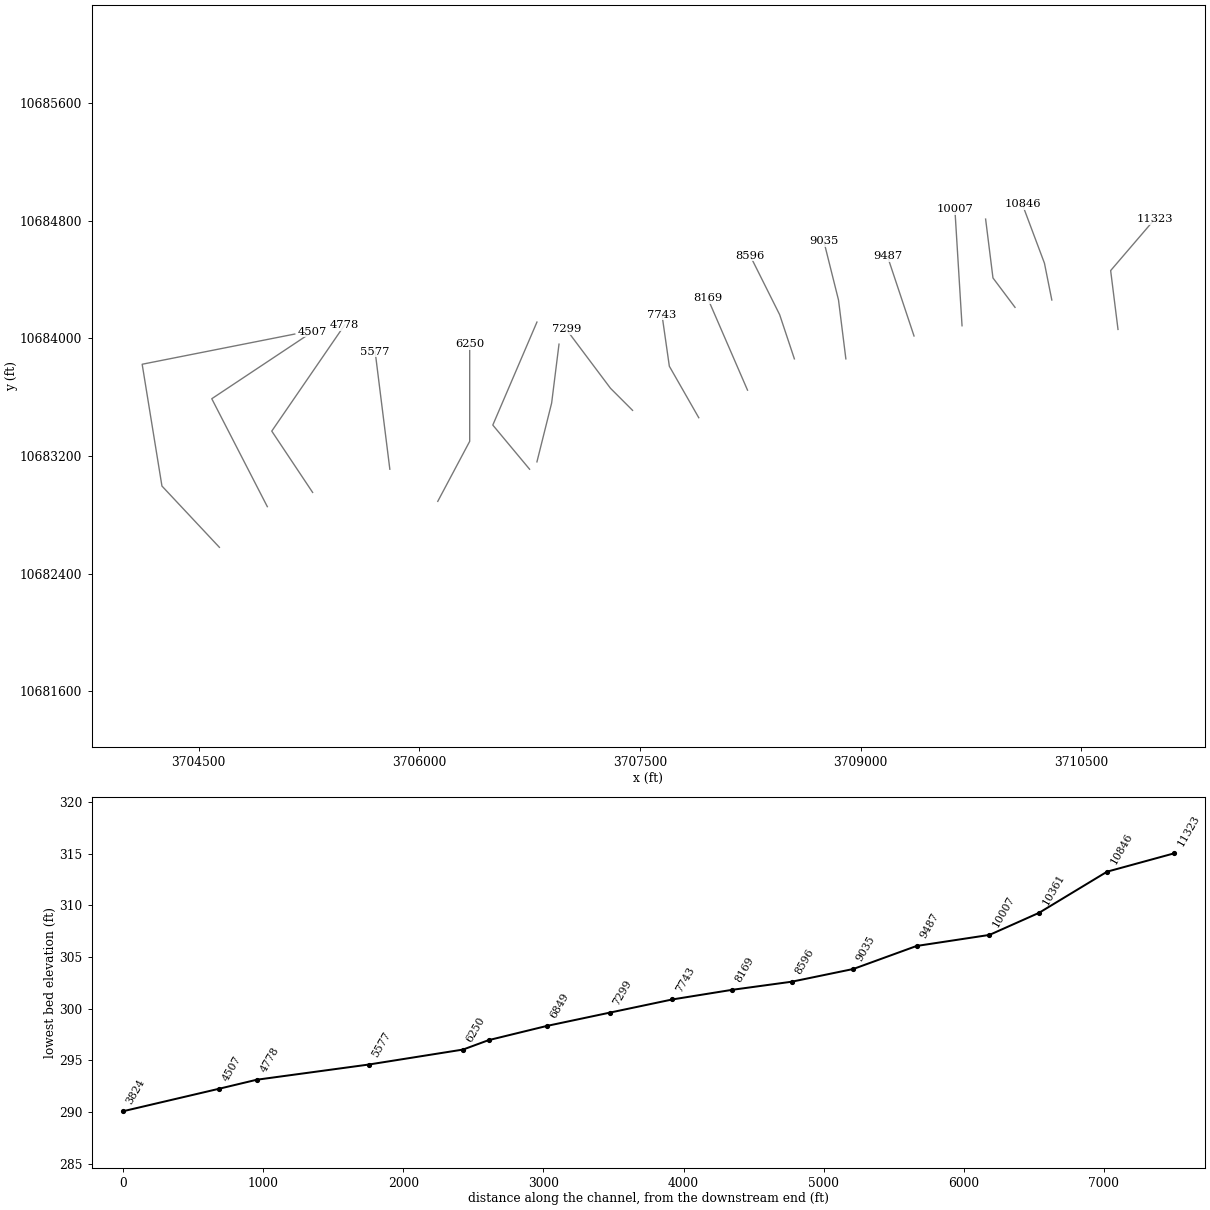
HEC-RAS study HOLLY SPRING BRANCH.prj: HOLLY SPRING BRANCH Base Level Engineering

--- HOLLY SPRING BRANCH.g01 (geometry) --- (continued)

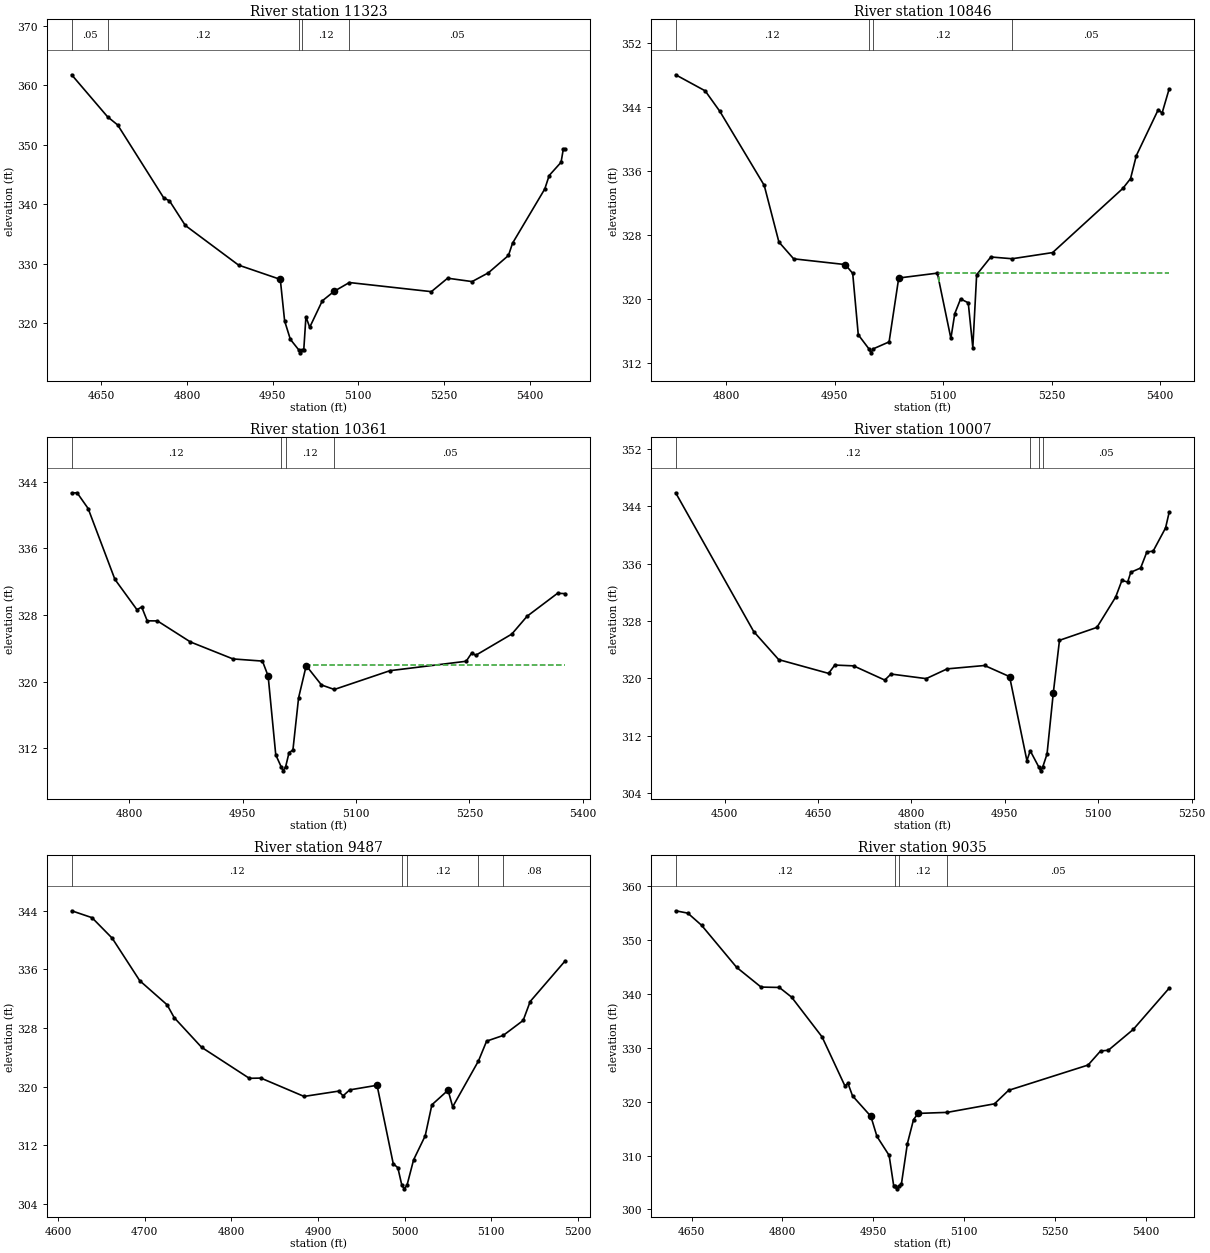
Type RM Length L Ch R = 1 ,11323   ,477,477,477
BEGIN DESCRIPTION:
HOLLY SPRING BRANCH 16.0
END DESCRIPTION:
XS GIS Cut Line= 3
      3710749.61      10684060.2      3710699.61     10684460.19
      3710999.62      10684810.2
#Sta/Elev= 30
  4598.2  361.73  4661.2  354.66  4678.8   353.3  4759.4  341.05  4769.5  340.55
  4797.2  336.42  4890.4  329.76  4963.5  327.36  4971.1  320.37  4981.1  317.29
  4995.8  315.52  4998.5  315.02  5001.8  315.52  5004.6  315.52  5008.4  321.08
    5015  319.31    5037  323.75  5057.8  325.36  5084.4  326.83    5228   325.3
  5256.5  327.56  5299.3  326.99  5327.8  328.46    5363  331.38  5370.1  333.43
  5426.6  342.55  5434.3  344.81  5455.1  347.03    5459  349.23  5462.3  349.23
#Mann= 5 ,-1 , 0
  4598.2     .05       0  4661.2     .12       0  4995.8     .07       0
  5001.8     .12       0  5084.4     .05       0
Bank Sta=4963.5,5057.8
XS Rating Curve= 0 ,0
Exp/Cntr=0.3,0.1

Type RM Length L Ch R = 1 ,10846   ,485,485,485
BEGIN DESCRIPTION:
HOLLY SPRING BRANCH 15.0
END DESCRIPTION:
XS GIS Cut Line= 3
       3710299.6     10684260.21      3710249.61     10684510.19
      3710099.62     10684910.16
#Sta/Elev= 30
  4730.2  348.03    4771  346.02  4791.4  343.44  4852.6   334.2  4872.9  327.11
  4893.3  325.01  4964.7  324.29  4974.9  323.19  4982.6  315.51  4997.3  313.75
    5000  313.25  5003.3  313.75  5025.2  314.62  5038.5  322.61  5091.9  323.22
  5110.6  315.06    5116  318.16    5124  319.99  5134.6  319.51  5140.9  313.91
  5146.2  323.02  5165.8  325.24  5195.3  325.02  5251.2  325.79  5348.2  333.81
  5358.9  335.04  5366.9  337.92  5397.2  343.67  5402.5  343.24  5412.3  346.27
#Mann= 4 ,-1 , 0
  4730.2     .12       0  4997.3     .07       0  5003.3     .12       0
  5195.3     .05       0
#XS Ineff= 2 , 0
                         5094.39          323.24
Permanent Ineff=
       F       F
Bank Sta=4964.7,5038.5
XS Rating Curve= 0 ,0
Exp/Cntr=0.3,0.1

Type RM Length L Ch R = 1 ,10361   ,354,354,354
BEGIN DESCRIPTION:
HOLLY SPRING BRANCH 14.0
END DESCRIPTION:
XS GIS Cut Line= 3
      3710049.58     10684210.23      3709899.61     10684410.19
       3709849.6     10684810.22
#Sta/Elev= 30
  4723.6  342.66  4730.8  342.69  4745.4   340.8  4780.8  332.29    4810  328.64
  4816.3  328.96  4823.6   327.3  4837.1  327.29  4880.8  324.76  4937.1  322.72
  4976.1  322.46  4983.6  320.67  4993.7  311.19  5000.8  309.77  5003.5  309.27
  5006.8  309.77  5011.3  311.47  5016.4  311.76  5023.9  318.04    5034  321.91
  5054.2  319.59  5071.2  319.05  5144.9  321.31  5245.7  322.44  5253.2  323.46
  5258.2  323.15  5306.1  325.71  5326.3  327.85  5366.6  330.61  5376.7  330.57
#Mann= 4 ,-1 , 0
  4723.6     .12       0  5000.8     .07       0  5006.8     .12       0
  5071.2     .05       0
#XS Ineff= 2 , 0
                          5037.4          321.98
Permanent Ineff=
       F       F
Bank Sta=4983.6,5034
XS Rating Curve= 0 ,0
Exp/Cntr=0.3,0.1

Type RM Length L Ch R = 1 ,10007   ,520,520,520
BEGIN DESCRIPTION:
HOLLY SPRING BRANCH 13.0
END DESCRIPTION:
XS GIS Cut Line= 2
      3709689.34     10684085.12      3709640.78     10684875.93
#Sta/Elev= 30
  4421.5  345.88  4546.8  326.54  4586.9  322.63    4667  320.71    4677  321.87
  4707.1  321.76  4757.2  319.78  4767.2  320.62  4823.7  319.98  4857.4  321.34
  4917.5  321.81  4957.6  320.26  4985.4  308.55  4990.7  309.93  5004.7  307.63
  5007.4  307.13  5010.7  307.63  5017.7  309.47  5027.7  317.93  5037.7  325.32
  5097.8  327.12  5127.9  331.35  5137.9  333.66  5147.2  333.45  5152.2   334.8
    5168   335.4    5178  337.64    5188  337.74    5208  340.98  5213.8  343.17
#Mann= 4 ,-1 , 0
  4421.5     .12       0  4990.7     .05       0  5004.7     .04       0
  5010.7     .05       0
Bank Sta=4957.6,5027.7
XS Rating Curve= 0 ,0
Exp/Cntr=0.3,0.1

Type RM Length L Ch R = 1 ,9487    ,452,452,452
BEGIN DESCRIPTION:
HOLLY SPRING BRANCH 12.0
END DESCRIPTION:
XS GIS Cut Line= 2
      3709362.95     10684015.66      3709182.77     10684556.22
#Sta/Elev= 30
  4615.7  343.97  4639.2  343.03  4662.6  340.22  4694.3  334.44  4725.9  331.15
  4734.1   329.4  4765.7  325.36  4820.8  321.13  4834.2  321.16    4884  318.66
  4923.8  319.38  4929.1  318.74  4936.7  319.55  4968.3  320.18    4987  309.48
  4992.3  308.94  4996.9  306.56  4999.7  306.06  5002.9  306.56  5010.5  310.02
  5023.9  313.29  5031.6  317.52  5050.3  319.51  5055.6  317.24  5085.4   323.5
  5094.8   326.2  5113.9  326.97    5137  329.02  5145.1   331.6  5185.5  337.14
#Mann= 5 ,-1 , 0
  4615.7     .12       0  4996.9     .07       0  5002.9     .12       0
  5085.4     .05       0  5113.9     .08       0
Bank Sta=4968.3,5050.3
XS Rating Curve= 0 ,0
Exp/Cntr=0.3,0.1

Type RM Length L Ch R = 1 ,9035    ,439,439,439
BEGIN DESCRIPTION:
HOLLY SPRING BRANCH 11.0
END DESCRIPTION:
XS GIS Cut Line= 3
      3708899.61      10683860.2      3708849.61     10684260.19
      3708749.61     10684660.18
#Sta/Elev= 30
  4623.5  355.47  4643.6  355.03  4666.3  352.78  4724.3  344.96  4764.6   341.3
  4794.8  341.23    4815  339.44  4865.4  332.05  4903.1  322.96  4908.2  323.42
  4915.7   321.1    4946   317.3  4956.1  313.56  4976.2  310.04  4983.8  304.37
  4985.8  304.33  4988.6  303.83  4991.8  304.33  4996.4  304.66  5006.4  312.25
  5016.5  316.68  5024.1  317.84  5072.2  318.03  5150.3  319.62  5173.5  322.12
  5304.9  326.82  5325.5  329.43  5338.4  329.57  5379.6  333.44  5438.9   341.1
#Mann= 4 ,-1 , 0
  4623.5     .12       0  4985.8     .07       0  4991.8     .12       0
  5072.2     .05       0
Bank Sta=4946,5024.1
XS Rating Curve= 0 ,0
Exp/Cntr=0.3,0.1

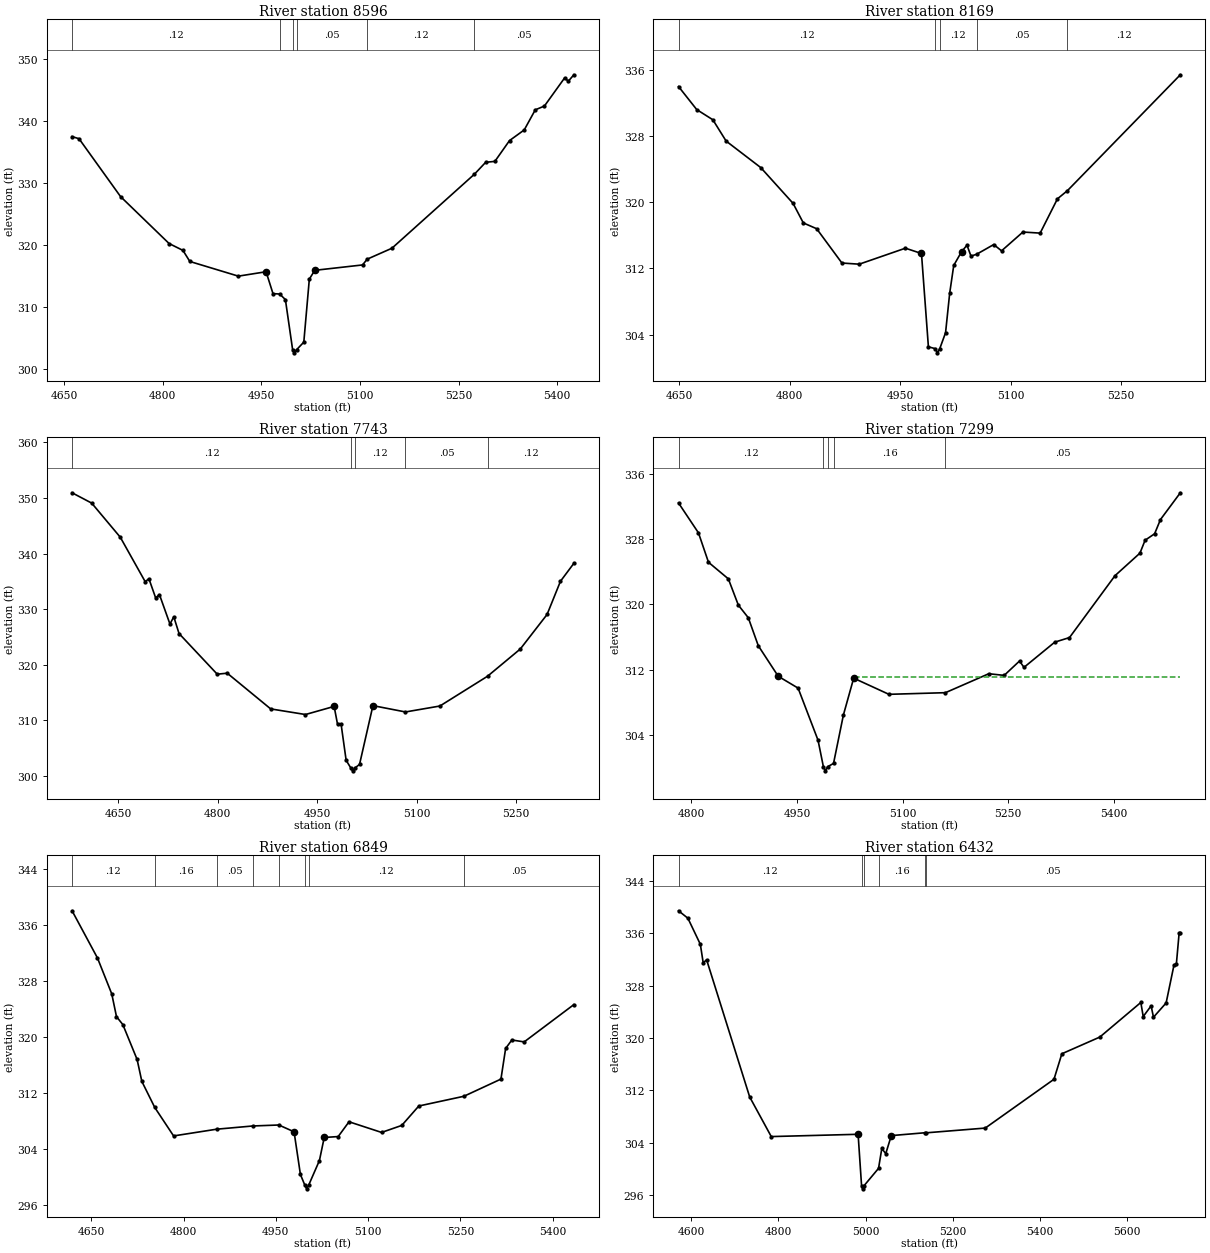
Type RM Length L Ch R = 1 ,8596    ,427,427,427
BEGIN DESCRIPTION:
HOLLY SPRING BRANCH 10.0
END DESCRIPTION:
XS GIS Cut Line= 3
      3708549.61     10683860.18      3708449.61     10684160.19
      3708249.59     10684560.23
#Sta/Elev= 30
    4662  337.53  4672.6  337.19  4735.8  327.84  4809.6  320.26  4830.7  319.15
  4841.2  317.36    4915  314.99  4957.2   315.7  4967.7  312.17  4977.9   312.1
  4986.6   311.2  4997.6   303.1  5000.3   302.6  5003.6   303.1  5014.6  304.33
    5023  314.51  5031.3  315.93    5104   316.8    5111  317.73  5148.7   319.5
  5274.2  331.46  5291.3  333.38  5305.3  333.53  5327.6  336.89    5350  338.61
  5366.8  341.86  5380.7  342.47  5411.5  347.02  5417.1  346.48  5425.5  347.52
#Mann= 6 ,-1 , 0
    4662     .12       0  4977.9     .05       0  4997.6     .04       0
  5003.6     .05       0    5111     .12       0  5274.2     .05       0
Bank Sta=4957.2,5031.3
XS Rating Curve= 0 ,0
Exp/Cntr=0.3,0.1

Type RM Length L Ch R = 1 ,8169    ,426,426,426
BEGIN DESCRIPTION:
HOLLY SPRING BRANCH 9.0
END DESCRIPTION:
XS GIS Cut Line= 2
      3708231.03     10683647.55      3707960.18     10684272.59
#Sta/Elev= 30
    4649  333.95  4673.7  331.17  4695.6  329.94  4713.6  327.37  4760.6  324.17
  4804.5  319.85  4818.4  317.49  4836.5  316.79  4870.8  312.65  4894.3  312.51
    4957  314.44  4978.8   313.8  4988.2  302.54  4997.6  302.31  5000.4  301.81
  5003.6  302.31  5011.5  304.24  5017.1  309.01  5022.6  312.36  5033.3  314.03
  5040.6   314.8    5046  313.49  5053.5   313.7  5076.9  314.88  5087.5  314.12
  5116.5  316.39  5139.9  316.26  5163.4   320.4    5177  321.39  5330.2  335.37
#Mann= 5 ,-1 , 0
    4649     .12       0  4997.6     .07       0  5003.6     .12       0
  5053.5     .05       0    5177     .12       0
Bank Sta=4978.8,5033.3
XS Rating Curve= 0 ,0
Exp/Cntr=0.3,0.1

Type RM Length L Ch R = 1 ,7743    ,444,444,444
BEGIN DESCRIPTION:
HOLLY SPRING BRANCH 8.0
END DESCRIPTION:
XS GIS Cut Line= 3
      3707899.63     10683460.15      3707699.61     10683810.19
      3707649.61     10684160.18
#Sta/Elev= 30
  4580.4  350.94    4610  349.08  4653.1  342.94  4690.6  334.95  4696.3  335.46
  4706.4  332.03  4712.2   332.6    4728  327.31  4733.8  328.61  4741.7   325.6
  4799.3  318.28  4814.4  318.46  4879.9  312.03  4932.4  311.02  4975.6  312.48
  4980.7  309.28  4986.1  309.28  4993.7  302.78  5000.8  301.38  5003.5  300.88
  5006.8  301.38  5013.9  302.04  5034.1  312.62  5083.2  311.48  5135.1  312.55
  5206.9  317.91  5256.3  322.81  5296.7  329.03  5316.9  335.01  5337.1  338.24
#Mann= 5 ,-1 , 0
  4580.4     .12       0  5000.8     .07       0  5006.8     .12       0
  5083.2     .05       0  5206.9     .12       0
Bank Sta=4975.6,5034.1
XS Rating Curve= 0 ,0
Exp/Cntr=0.3,0.1

Type RM Length L Ch R = 1 ,7299    ,450,450,450
BEGIN DESCRIPTION:
HOLLY SPRING BRANCH 7.0
END DESCRIPTION:
XS GIS Cut Line= 3
      3707449.64     10683510.16      3707299.61     10683660.19
      3706999.59     10684060.21
#Sta/Elev= 30
    4782  332.41  4810.3  328.75  4824.5  325.15  4852.7  323.12  4866.9   319.9
    4881  318.36  4895.2  314.93  4923.5  311.19  4951.7  309.74    4980  303.36
  4987.6  300.11  4990.4  299.61  4993.6  300.11    5002  300.52    5016  306.45
  5030.6  310.96  5080.6  308.98  5160.8  309.18  5222.3   311.5  5244.2   311.3
    5266  313.06  5272.3  312.28    5316  315.37  5336.9  315.93  5401.5  323.51
  5436.9  326.27  5444.2  327.85  5457.7  328.64    5466  330.38  5494.2  333.66
#Mann= 5 ,-1 , 0
    4782     .12       0  4987.6     .07       0  4993.6     .12       0
    5002     .16       0  5160.8     .05       0
#XS Ineff= 2 , 0
                         5034.35          311.15
Permanent Ineff=
       F       F
Bank Sta=4923.5,5030.6
XS Rating Curve= 0 ,0
Exp/Cntr=0.3,0.1

Type RM Length L Ch R = 1 ,6849    ,417,417,417
BEGIN DESCRIPTION:
HOLLY SPRING BRANCH 6.0
END DESCRIPTION:
XS GIS Cut Line= 3
       3706799.6     10683160.15      3706899.61     10683560.19
      3706949.61     10683960.23
#Sta/Elev= 30
  4618.9     338  4660.2  331.26  4683.4  326.14  4691.1  322.89  4701.4  321.76
  4724.6  316.78  4732.3  313.65  4753.3  309.93  4783.9  305.87  4853.8  306.83
  4912.4  307.29  4954.9  307.43  4979.7  306.46    4990  300.37  4997.3  298.82
  5000.1  298.32  5003.3  298.82  5020.9  302.36  5028.7  305.65  5051.4  305.78
    5069  307.89  5121.9  306.37  5154.7  307.37  5182.4  310.14  5255.7  311.53
  5315.9  313.98  5323.5  318.35  5333.6  319.56  5353.7  319.29  5434.4  324.61
#Mann= 8 ,-1 , 0
  4618.9     .12       0  4753.3     .16       0  4853.8     .05       0
  4912.4     .16       0  4954.9     .12       0  4997.3     .07       0
  5003.3     .12       0  5255.7     .05       0
Bank Sta=4979.7,5028.7
XS Rating Curve= 0 ,0
Exp/Cntr=0.3,0.1

Type RM Length L Ch R = 1 ,6432    ,182,182,182
BEGIN DESCRIPTION:
HOLLY SPRING BRANCH 5.0
END DESCRIPTION:
XS GIS Cut Line= 3
      3706749.62     10683110.17      3706499.61     10683410.19
       3706799.6     10684110.18
#Sta/Elev= 30
  4570.7  339.45  4592.2  338.31  4620.8  334.32  4627.3   331.5  4635.2  331.95
  4734.1  310.98  4783.6  304.93    4983  305.28  4990.9  297.44  4993.6  296.94
  4996.9  297.44  5029.9  300.07  5037.4  303.11  5046.5  302.32  5059.2  305.08
  5137.4  305.52  5138.5   305.5  5274.9  306.23  5432.7  313.69  5450.8  317.59
  5537.9  320.14  5632.1  325.43  5637.6  323.28  5655.7  324.91  5661.2  323.18
  5690.2  325.36  5708.3  331.17  5713.7   331.3  5720.1  336.07  5722.8  336.07
#Mann= 6 ,-1 , 0
  4570.7     .12       0  4990.9     .07       0  4996.9     .12       0
  5029.9     .16       0  5137.4     .12       0  5138.5     .05       0
Bank Sta=4983,5059.2
XS Rating Curve= 0 ,0
Exp/Cntr=0.3,0.1

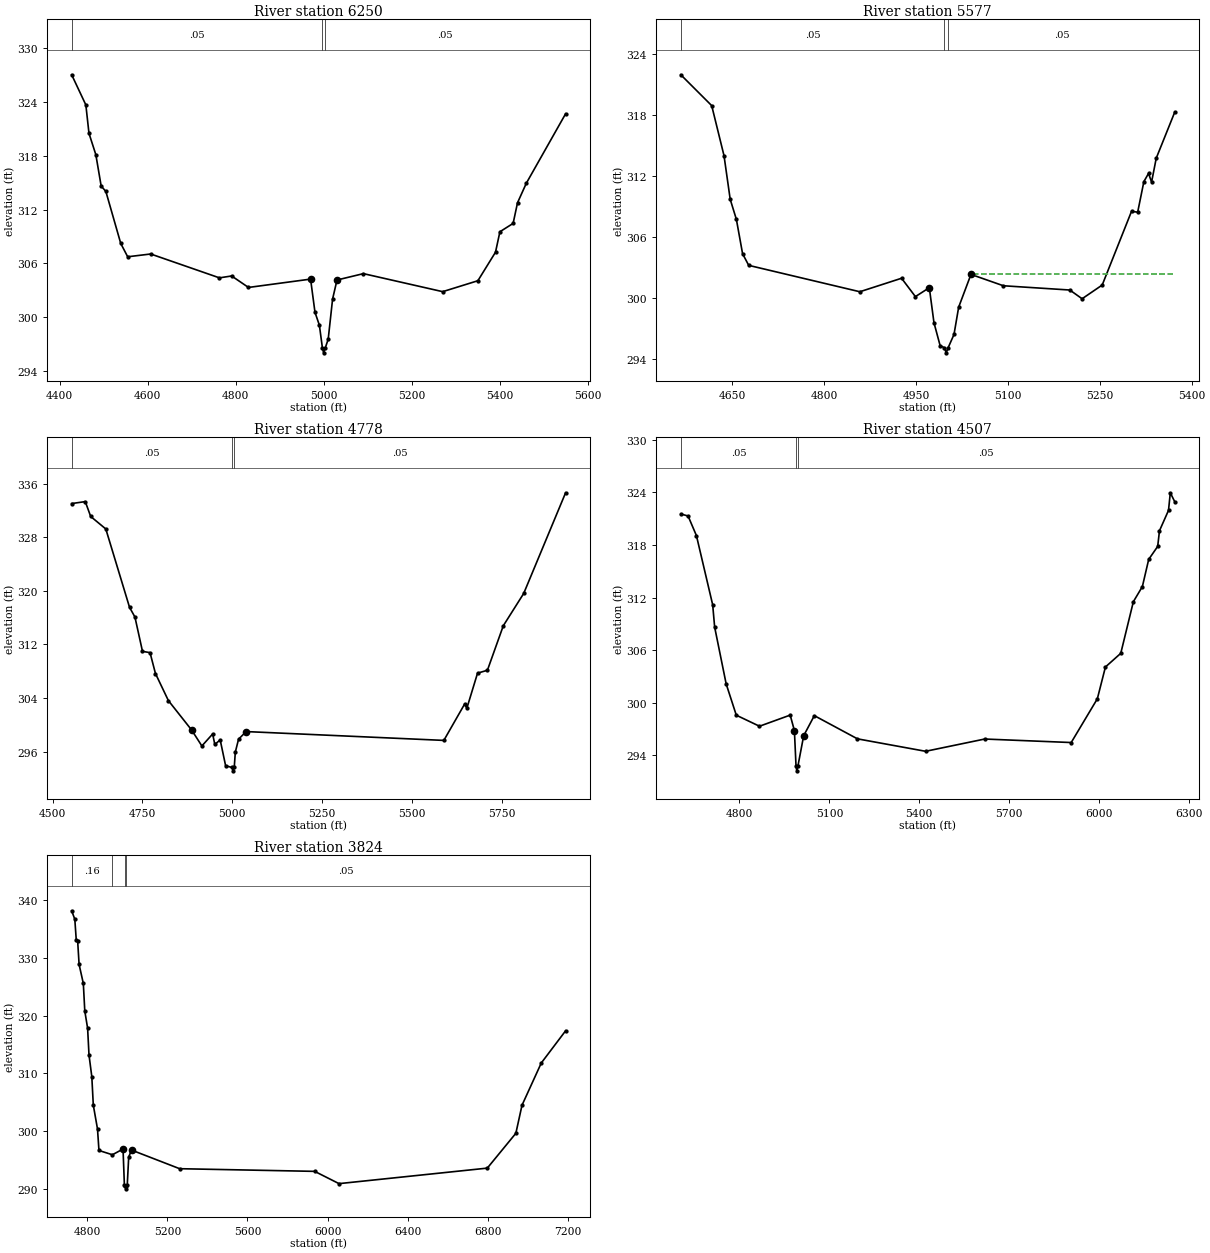
Type RM Length L Ch R = 1 ,6250    ,673,673,673
BEGIN DESCRIPTION:
HOLLY SPRING BRANCH 4.0
END DESCRIPTION:
XS GIS Cut Line= 3
      3706125.47     10682891.72      3706342.47     10683299.67
      3706342.47      10683959.4
#Sta/Elev= 30
  4427.6  327.03  4459.8  323.67  4466.9   320.5  4482.5  318.12  4494.6  314.62
  4505.2  314.03  4539.1  308.22  4554.8  306.74  4607.1  307.05  4763.2  304.39
  4790.9   304.6  4829.2  303.32  4970.2  304.25  4980.2  300.55  4990.2  299.11
  4997.2  296.53  4999.9  296.03  5003.2  296.53  5010.2  297.54  5020.2  302.03
  5030.2  304.15  5090.2  304.86  5270.2  302.85  5350.2  304.07  5390.2  307.25
  5400.2  309.53  5430.2  310.46  5440.2  312.76  5460.2  314.94  5549.4  322.68
#Mann= 3 ,-1 , 0
  4427.6     .05       0  4997.2     .03       0  5003.2     .05       0
Bank Sta=4970.2,5030.2
XS Rating Curve= 0 ,0
Exp/Cntr=0.3,0.1

Type RM Length L Ch R = 1 ,5577    ,799,799,799
BEGIN DESCRIPTION:
HOLLY SPRING BRANCH 3.0
END DESCRIPTION:
XS GIS Cut Line= 3
      3705799.61     10683110.21      3705749.61     10683510.19
      3705699.61     10683910.19
#Sta/Elev= 30
  4566.1  321.98  4616.5  318.94  4636.6  314.01  4646.7  309.71  4656.8  307.73
  4666.9  304.35  4676.9   303.2  4858.3   300.6  4926.4  301.93    4949  300.12
  4971.7     301  4979.3  297.55  4989.3   295.3  4996.4  295.08  4999.2  294.58
  5002.4  295.08    5012  296.39  5019.6  299.08  5039.7  302.31  5092.6  301.19
    5201  300.77  5221.1  299.91  5253.9  301.26  5301.8  308.53  5311.8  308.44
  5321.9  311.45  5329.5  312.26  5334.5  311.41  5342.1  313.76  5372.3   318.3
#Mann= 3 ,-1 , 0
  4566.1     .05       0  4996.4     .03       0  5002.4     .05       0
#XS Ineff= 2 , 0
                         5045.52          302.32
Permanent Ineff=
       F       F
Bank Sta=4971.7,5039.7
XS Rating Curve= 0 ,0
Exp/Cntr=0.3,0.1

Type RM Length L Ch R = 1 ,4778    ,271,271,271
BEGIN DESCRIPTION:
HOLLY SPRING BRANCH 2.0
END DESCRIPTION:
XS GIS Cut Line= 3
      3705274.78     10682952.43      3704996.98     10683369.12
      3705491.76     10684089.58
#Sta/Elev= 30
    4553  333.07  4590.9  333.36  4605.9  331.14    4648  329.27  4714.1  317.55
  4729.1   316.1  4750.1  310.97  4771.1  310.78  4786.2  307.66  4822.2  303.61
  4886.8  299.22  4915.4  296.83  4945.4  298.62  4951.4  297.06  4966.4  297.73
  4981.5  293.87  4999.5  293.61  5002.3  293.11  5005.5  293.61  5008.5  295.91
  5017.5  297.84  5038.6  298.98  5588.9  297.66  5646.8   303.1  5652.9  302.46
  5682.7  307.71  5710.2  308.15  5754.4   314.8  5811.2  319.63  5927.8  334.68
#Mann= 3 ,-1 , 0
    4553     .05       0  4999.5     .03       0  5005.5     .05       0
Bank Sta=4886.8,5038.6
XS Rating Curve= 0 ,0
Exp/Cntr=0.3,0.1

Type RM Length L Ch R = 1 ,4507    ,683,683,683
BEGIN DESCRIPTION:
Mapping XS 7e6f719f
END DESCRIPTION:
XS GIS Cut Line= 3
      3704966.77     10682855.69      3704589.15     10683589.22
      3705274.74     10684044.83
#Sta/Elev= 30
  4604.2  321.54  4628.4  321.31  4656.2  319.08  4710.5  311.18  4717.1  308.63
  4755.5  302.15  4789.3  298.58  4866.7  297.32  4969.2  298.59  4983.2  296.82
  4988.7  292.73  4991.4  292.23  4994.7  292.73  5014.2  296.24  5049.7  298.53
  5193.7  295.88    5421  294.46  5618.3  295.86  5906.9  295.46  5994.1  300.45
  6021.1  304.08  6072.3  305.64  6114.3  311.53  6144.4  313.26  6165.5  316.36
  6195.5  317.84  6201.5  319.63  6231.6  321.95  6237.6  323.96  6252.4  322.94
#Mann= 3 ,-1 , 0
  4604.2     .05       0  4988.7     .03       0  4994.7     .05       0
Bank Sta=4983.2,5014.2
XS Rating Curve= 0 ,0
Exp/Cntr=0.3,0.1

Type RM Length L Ch R = 1 ,3824    ,0,0,0
BEGIN DESCRIPTION:
HOLLY SPRING BRANCH 1.0
END DESCRIPTION:
XS GIS Cut Line= 4
      3704641.06     10682579.22      3704250.46     10682995.86
      3704116.06     10683823.59      3705153.27     10684028.85
#Sta/Elev= 30
  4721.9  338.11  4737.6  336.64  4744.9     333  4751.7  332.92    4759  328.83
  4780.1  325.55  4787.4  320.79  4801.5  317.81  4808.4  313.21  4822.5  309.43
  4829.9  304.53  4850.9   300.4  4858.2  296.69  4925.2  295.95  4978.4  296.94
  4985.2  290.72  4989.5  290.56  4992.3  290.06  4995.5  290.56  4999.4  290.64
  5006.7  295.55  5020.8  296.76  5261.2  293.54  5935.6  293.08  6057.2  290.96
  6797.8  293.64  6940.5  299.66  6971.1   304.5  7067.5  311.81  7188.9  317.37
#Mann= 4 ,-1 , 0
  4721.9     .16       0  4925.2     .05       0  4989.5     .03       0
  4995.5     .05       0
Bank Sta=4978.4,5020.8
XS Rating Curve= 0 ,0
Exp/Cntr=0.3,0.1

Chan Stop Cuts=-1
Use User Specified Reach Order=0
Composite Channel Slope=5