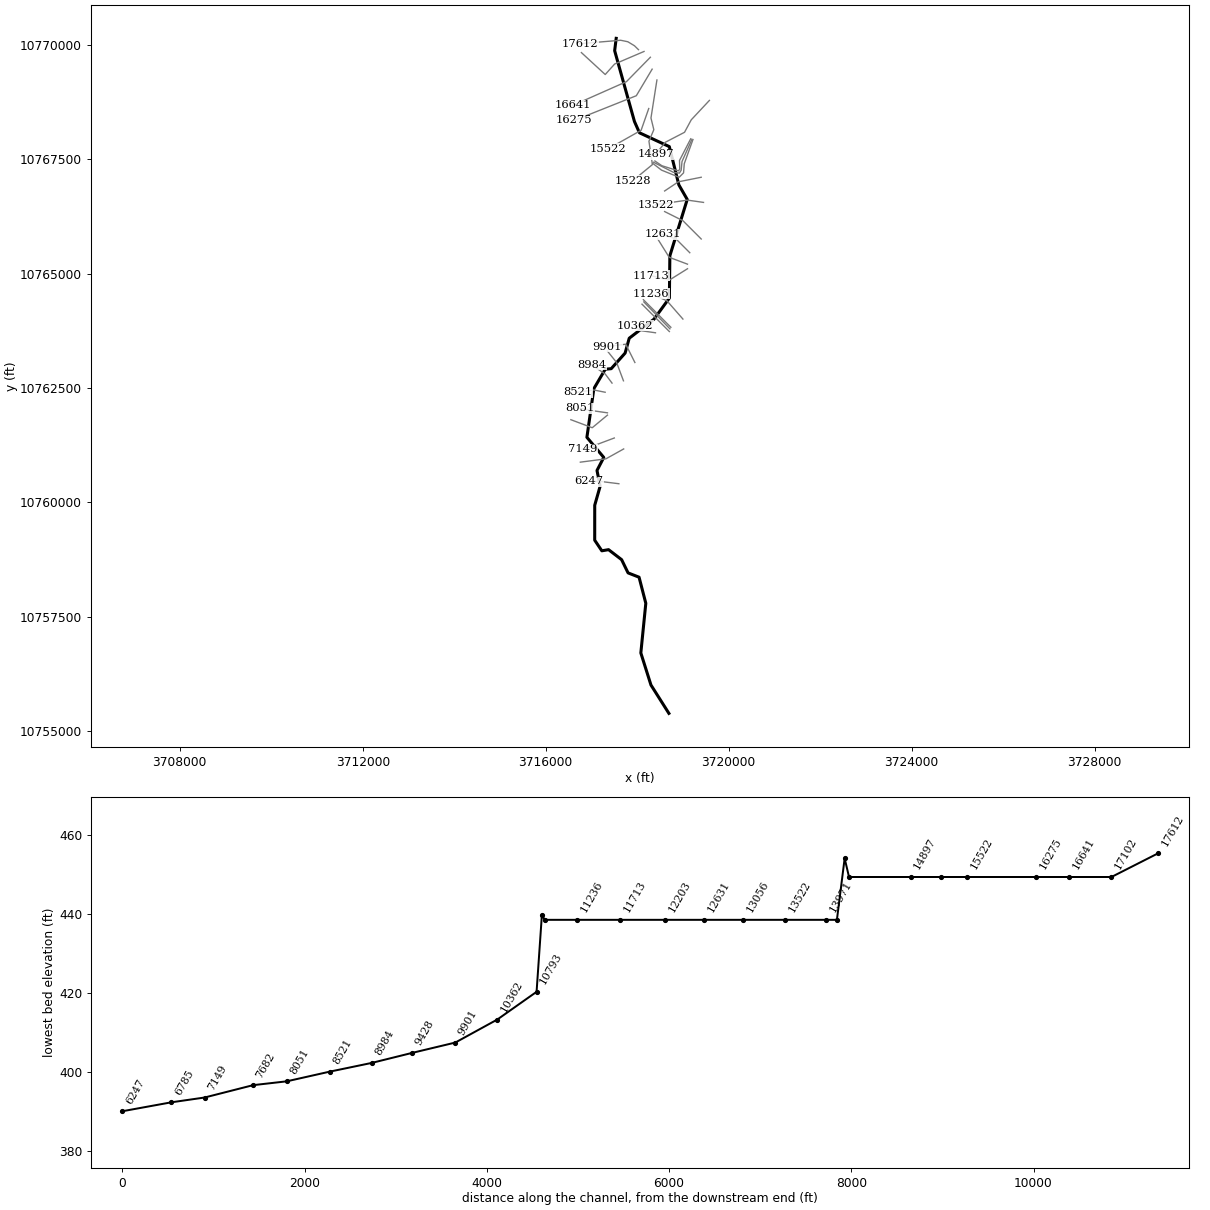
--- KILE BRANCH.prj (project) ---

Proj Title=KILE BRANCH Base Level Engineering
Current Plan=p01
Default Exp/Contr=0.3,0.1
English Units
Geom File=g01
Flow File=f01
Plan File=p01
BEGIN DESCRIPTION:
KILE BRANCH
END DESCRIPTION:

--- KILE BRANCH.p01 (plan) ---

Plan Title=Multiple Run
Short Identifier=Multiple
Geom File=g01
Flow File=f01
Subcritical Flow
K Sum by GR= 0
Std Step Tol= 0.01
Critical Tol= 0.01
Num of Std Step Trials= 20
Max Error Tol= 0.3
Flow Tol Ratio= 0.001
Split Flow NTrial= 30
Split Flow Tol= 0.02
Split Flow Ratio= 0.02
Log Output Level= 0
Friction Slope Method= 1
Unsteady Friction Slope Method= 2
Unsteady Bridges Friction Slope Method= 1
Parabolic Critical Depth
Global Vel Dist=  1 , 1 , 1
Global Log Level= 0
CheckData=True
Encroach Param= -1, 0, 0, 0
BEGIN DESCRIPTION:
Multiple Run
END DESCRIPTION:

--- KILE BRANCH.f01 (steady flow) ---

Flow Title=Multiple
Number of Profiles=7
Profile Names=10-year,25-year,50-year,1pct_min,100-year,1pct_plu,500-year
River Rch & RM= KILE BRANCH,Reach-1,17612
     565     763     926     825    1116    1510    1624
River Rch & RM= KILE BRANCH,Reach-1,14089
     862    1194    1473    1334    1804    2439    2708
River Rch & RM= KILE BRANCH,Reach-1,13522
    1001    1395    1729    1570    2123    2871    3208
River Rch & RM= KILE BRANCH,Reach-1,9428
    1172    1643    2042    1858    2513    3399    3817
River Rch & RM= KILE BRANCH,Reach-1,3903
    1286    1806    2248    2048    2770    3746    4216
Boundary for River Rch & Prof#=KILE BRANCH,Reach-1,1
Up Type=0
Dn Type=3
Dn Slope=0.005
Boundary for River Rch & Prof#=KILE BRANCH,Reach-1,2
Up Type=0
Dn Type=3
Dn Slope=0.005
Boundary for River Rch & Prof#=KILE BRANCH,Reach-1,3
Up Type=0
Dn Type=3
Dn Slope=0.005
Boundary for River Rch & Prof#=KILE BRANCH,Reach-1,4
Up Type=0
Dn Type=3
Dn Slope=0.005
Boundary for River Rch & Prof#=KILE BRANCH,Reach-1,5
Up Type=0
Dn Type=3
Dn Slope=0.005
Boundary for River Rch & Prof#=KILE BRANCH,Reach-1,6
Up Type=0
Dn Type=3
Dn Slope=0.005
Boundary for River Rch & Prof#=KILE BRANCH,Reach-1,7
Up Type=0
Dn Type=3
Dn Slope=0.005

--- KILE BRANCH.g01 (geometry) ---

Geom Title=Existing Conditions

River Reach=KILE BRANCH,Reach-1
Reach XY= 30
      3717540.75     10770147.00      3717507.25     10769877.00
      3717940.00     10768329.00      3718049.50     10768082.00
      3718702.25     10767780.00      3718910.75     10766943.00
      3719093.75     10766625.00      3718714.00     10765393.00
      3718703.50     10764469.00      3718366.75     10764007.00
      3717825.75     10763591.00      3717735.75     10763266.00
      3717431.75     10762925.00      3717302.00     10762914.00
      3717052.75     10762489.00      3716900.50     10761425.00
      3717269.25     10760985.00      3717121.25     10760700.00
      3717189.75     10760355.00      3717071.50     10759940.00
      3717071.00     10759176.00      3717226.75     10758944.00
      3717374.00     10758969.00      3717659.50     10758750.00
      3717800.25     10758461.00      3718040.75     10758367.00
      3718188.25     10757797.00      3718079.50     10756711.00
      3718300.75     10756010.00      3718693.00     10755390.00

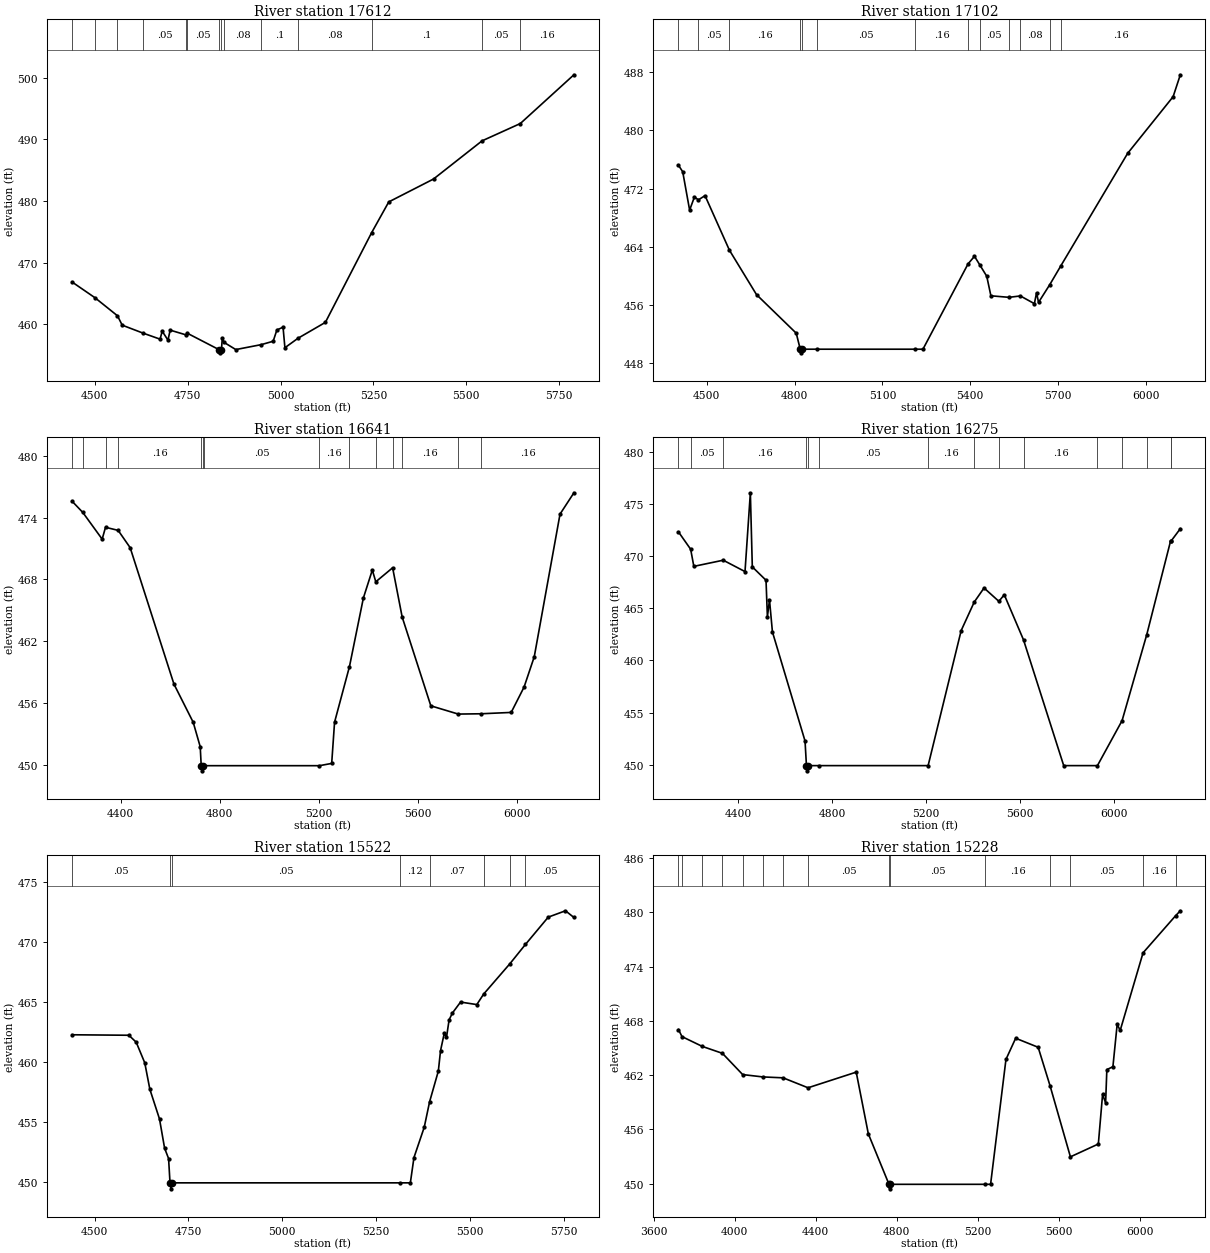
Type RM Length L Ch R = 1,17612,510,510,510
BEGIN DESCRIPTION:
Mapping XS 191cb632
END DESCRIPTION:
XS GIS Cut Line= 5
      3718028.01     10769899.34      3717939.49     10769985.26
      3717794.96     10770072.50      3717638.71     10770105.05
      3716743.06     10770029.66
#Sta/Elev= 30
  4439.0  466.88  4500.8  464.32  4561.2  461.40  4573.9  459.88  4629.9  458.59
  4675.8  457.61  4681.6  458.90  4697.1  457.45  4703.0  459.07  4745.9  458.30
  4749.1  458.57  4835.1  455.89  4837.8  455.39  4841.1  455.89  4843.2  457.78
  4847.9  457.09  4879.6  455.92  4948.1  456.72  4980.2  457.27  4990.2  459.10
  5006.8  459.55  5011.8  456.22  5047.2  457.76  5120.7  460.33  5245.2  474.88
  5291.3  479.87  5411.7  483.58  5542.3  489.77  5645.3  492.58  5789.6  500.49
#Mann=14,-1,0
  4439.0    0.08       0  4500.8    0.05       0  4561.2    0.08       0
  4629.9    0.05       0  4745.9    0.12       0  4749.1    0.05       0
  4835.1    0.07       0  4841.1    0.05       0  4847.9    0.08       0
  4948.1     0.1       0  5047.2    0.08       0  5245.2     0.1       0
  5542.3    0.05       0  5645.3    0.16       0
Bank Sta=4835.1,4841.1
Exp/Cntr=0.3,0.1

Type RM Length L Ch R = 1,17102,461,461,461
BEGIN DESCRIPTION:
KILE BRANCH 35.0
END DESCRIPTION:
XS GIS Cut Line= 4
      3718149.60     10769860.18      3717506.73     10769585.19
      3717301.00     10769356.02      3716780.17     10769835.19
#Sta/Elev= 30
  4403.2  475.20  4417.7  474.31  4441.3  469.04  4457.6  470.83  4471.5  470.45
  4493.9  471.03  4577.4  463.52  4669.9  457.42  4805.6  452.12  4819.3  449.92
  4822.1  449.42  4825.3  449.92  4877.9  449.92  5212.4  449.92  5238.6  449.92
  5392.8  461.65  5414.7  462.69  5432.5  461.53  5456.6  459.95  5470.8  457.26
  5532.6  457.05  5571.5  457.24  5619.4  456.18  5626.8  457.68  5633.6  456.36
  5672.1  458.80  5710.4  461.42  5938.1  476.84  6093.5  484.63  6118.1  487.64
#Mann=13,-1,0
  4403.2    0.08       0  4471.5    0.05       0  4577.4    0.16       0
  4819.3   0.033       0  4825.3    0.16       0  4877.9    0.05       0
  5212.4    0.16       0  5392.8     0.1       0  5432.5    0.05       0
  5532.6     0.1       0  5571.5    0.08       0  5672.1    0.05       0
  5710.4    0.16       0
Bank Sta=4819.3,4825.3
Exp/Cntr=0.3,0.1

Type RM Length L Ch R = 1,16641,366,366,366
BEGIN DESCRIPTION:
KILE BRANCH 34.0
END DESCRIPTION:
XS GIS Cut Line= 3
      3718287.98     10769733.63      3717764.54     10769199.77
      3716595.30     10768681.55
#Sta/Elev= 30
  4203.8  475.59  4247.2  474.50  4325.3  471.91  4338.9  473.06  4389.9  472.76
  4438.4  471.08  4615.2  457.84  4693.0  454.13  4721.3  451.76  4725.3  449.92
  4728.1  449.42  4731.3  449.92  4735.5  449.92  5202.6  449.92  5252.2  450.14
  5263.8  454.14  5323.9  459.53  5380.2  466.20  5416.3  468.91  5430.3  467.77
  5498.3  469.13  5536.8  464.35  5652.6  455.73  5763.3  454.93  5856.2  454.96
  5977.1  455.09  6029.1  457.55  6070.2  460.49  6174.3  474.34  6230.4  476.41
#Mann=14,-1,0
  4203.8    0.16       0  4247.2     0.1       0  4338.9    0.05       0
  4389.9    0.16       0  4725.3   0.033       0  4731.3    0.16       0
  4735.5    0.05       0  5202.6    0.16       0  5323.9    0.05       0
  5430.3     0.1       0  5498.3    0.08       0  5536.8    0.16       0
  5763.3    0.05       0  5856.2    0.16       0
Bank Sta=4725.3,4731.3
Exp/Cntr=0.3,0.1

Type RM Length L Ch R = 1,16275,753,753,753
BEGIN DESCRIPTION:
KILE BRANCH 33.0
END DESCRIPTION:
XS GIS Cut Line= 3
      3718327.02     10769473.17      3717980.69     10768892.48
      3716622.93     10768351.46
#Sta/Elev= 30
  4145.4  472.31  4197.3  470.65  4210.8  469.01  4336.0  469.60  4428.8  468.51
  4451.6  476.06  4459.9  468.96  4518.3  467.68  4524.2  464.17  4533.1  465.80
  4545.6  462.73  4684.5  452.28  4690.5  449.92  4693.3  449.42  4696.5  449.92
  4741.9  449.92  5208.8  449.92  5349.6  462.86  5405.2  465.59  5447.0  466.94
  5510.2  465.66  5533.2  466.29  5615.1  461.97  5786.4  449.92  5930.0  449.92
  6035.0  454.23  6139.9  462.45  6241.6  471.44  6244.9  471.47  6283.1  472.62
#Mann=15,-1,0
  4145.4    0.16       0  4197.3    0.05       0  4336.0    0.16       0
  4690.5   0.033       0  4696.5    0.16       0  4741.9    0.05       0
  5208.8    0.16       0  5405.2     0.1       0  5510.2    0.05       0
  5615.1    0.16       0  5930.0    0.12       0  6035.0    0.16       0
  6139.9    0.12       0  6241.6    0.16       0  6244.9     0.1       0
Bank Sta=4690.5,4696.5
Exp/Cntr=0.3,0.1

Type RM Length L Ch R = 1,15522,294,294,294
BEGIN DESCRIPTION:
KILE BRANCH 32.0
END DESCRIPTION:
XS GIS Cut Line= 3
      3718252.38     10768612.95      3718085.72     10768137.27
      3717360.02     10767727.55
#Sta/Elev= 30
  4440.2  462.28  4591.5  462.24  4611.1  461.66  4633.9  459.94  4647.5  457.73
  4673.2  455.25  4686.8  452.81  4697.4  451.95  4701.2  449.92  4703.9  449.42
  4707.2  449.92  5314.6  449.92  5341.7  449.92  5351.3  452.03  5378.7  454.56
  5393.0  456.69  5416.3  459.25  5422.1  460.95  5432.2  462.42  5438.0  462.06
  5445.0  463.53  5453.9  464.10  5475.5  465.01  5518.8  464.80  5537.1  465.68
  5607.0  468.21  5648.4  469.82  5709.2  472.10  5755.1  472.63  5777.6  472.07
#Mann=8,-1,0
  4440.2    0.05       0  4701.2   0.033       0  4707.2    0.05       0
  5314.6    0.12       0  5393.0    0.07       0  5537.1    0.12       0
  5607.0    0.07       0  5648.4    0.05       0
Bank Sta=4701.2,4707.2
Exp/Cntr=0.3,0.1

Type RM Length L Ch R = 1,15228,331,331,331
BEGIN DESCRIPTION:
KILE BRANCH 31.0
END DESCRIPTION:
XS GIS Cut Line= 6
      3718431.21     10769236.25      3718301.00     10768405.50
      3718363.50     10768150.29      3718256.73     10767897.69
      3718332.40     10767386.71      3717897.51     10767029.95
#Sta/Elev= 30
  3722.4  467.04  3739.7  466.26  3839.5  465.18  3939.3  464.41  4039.2  462.06
  4139.0  461.80  4238.8  461.70  4361.8  460.60  4599.6  462.33  4659.4  455.50
  4761.4  449.92  4764.1  449.42  4767.4  449.92  5235.8  449.92  5262.7  449.92
  5338.6  463.74  5386.5  466.08  5497.5  465.08  5556.5  460.80  5656.7  452.96
  5794.5  454.38  5815.5  459.88  5830.4  458.92  5836.5  462.61  5866.4  462.93
  5887.4  467.61  5902.4  466.95  6015.2  475.53  6175.7  479.63  6199.1  480.18
#Mann=15,-1,0
  3722.4    0.16       0  3739.7    0.05       0  3839.5    0.08       0
  3939.3     0.1       0  4039.2    0.08       0  4139.0     0.1       0
  4238.8    0.08       0  4361.8    0.05       0  4761.4   0.033       0
  4767.4    0.05       0  5235.8    0.16       0  5556.5    0.08       0
  5656.7    0.05       0  6015.2    0.16       0  6175.7    0.08       0
Bank Sta=4761.4,4767.4
Exp/Cntr=0.3,0.1

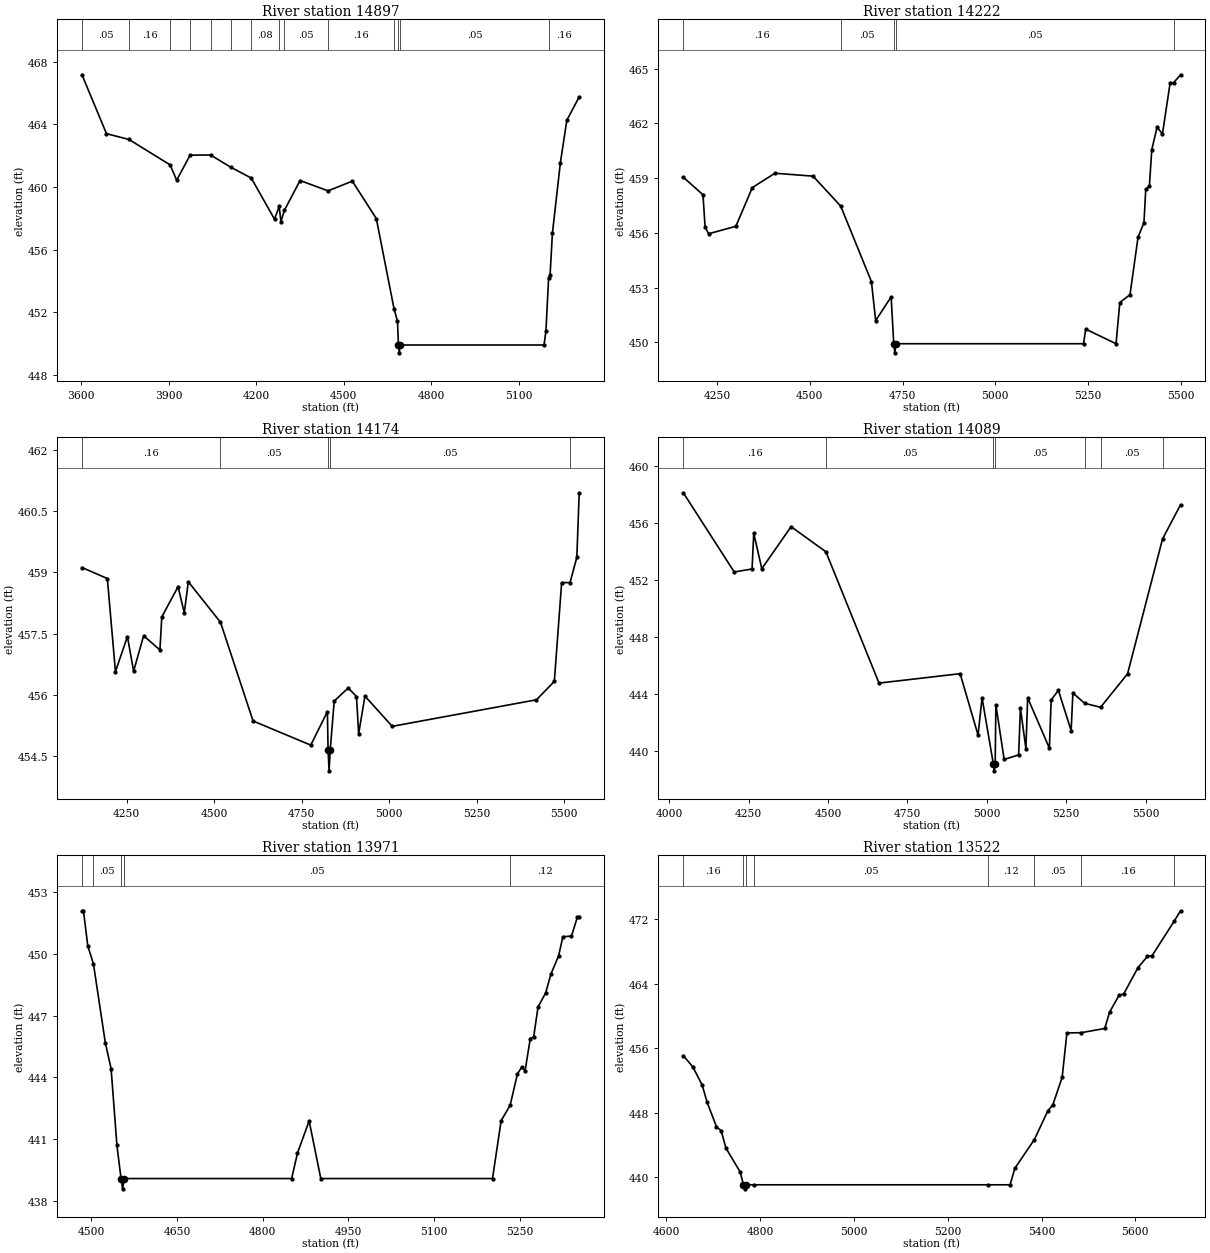
Type RM Length L Ch R = 1,14897,675,675,675
BEGIN DESCRIPTION:
KILE BRANCH 30.0
END DESCRIPTION:
XS GIS Cut Line= 5
      3719578.80     10768790.08      3719182.07     10768366.00
      3719034.50     10768092.57      3718615.67     10767875.55
      3718399.58     10767610.15
#Sta/Elev= 30
  3602.5  467.17  3686.6  463.41  3763.8  463.04  3904.6  461.42  3927.4  460.44
  3973.3  462.04  4043.8  462.05  4112.5  461.27  4183.1  460.58  4262.9  457.95
  4278.9  458.77  4284.8  457.80  4296.9  458.52  4350.5  460.42  4446.5  459.76
  4529.7  460.38  4612.1  457.99  4672.7  452.24  4684.6  451.44  4687.9  449.92
  4690.7  449.42  4693.9  449.92  5187.2  449.92  5193.7  450.80  5203.0  454.20
  5208.0  454.38  5215.9  457.04  5243.4  461.57  5265.5  464.27  5307.9  465.76
#Mann=14,-1,0
  3602.5    0.05       0  3763.8    0.16       0  3904.6    0.05       0
  3973.3    0.16       0  4043.8     0.1       0  4112.5    0.16       0
  4183.1    0.08       0  4278.9    0.16       0  4296.9    0.05       0
  4446.5    0.16       0  4672.7    0.05       0  4687.9   0.033       0
  4693.9    0.05       0  5203.0    0.16       0
Bank Sta=4687.9,4693.9
Exp/Cntr=0.3,0.1

Type RM Length L Ch R = 1,14222,48,48,48
BEGIN DESCRIPTION:
Mapping XS feda03ca
END DESCRIPTION:
XS GIS Cut Line= 6
      3719169.71     10767950.83      3718924.89     10767476.83
      3718930.10     10767284.12      3718898.85     10767250.27
      3718539.48     10767362.24      3718386.55     10767465.82
#Sta/Elev= 30
  4159.3  459.05  4212.3  458.09  4218.0  456.32  4227.5  455.95  4300.9  456.36
  4345.2  458.48  4406.1  459.27  4508.9  459.11  4583.4  457.47  4666.2  453.33
  4677.7  451.19  4719.4  452.49  4726.4  449.92  4729.2  449.42  4732.4  449.92
  5237.9  449.92  5243.7  450.72  5325.5  449.92  5335.6  452.18  5363.1  452.61
  5384.7  455.76  5400.7  456.56  5405.5  458.39  5415.3  458.56  5421.8  460.57
  5436.1  461.80  5450.5  461.42  5471.3  464.24  5480.3  464.23  5499.3  464.67
#Mann=5,-1,0
  4159.3    0.16       0  4583.4    0.05       0  4726.4    0.03       0
  4732.4    0.05       0  5480.3    0.16       0
Bank Sta=4726.4,4732.4
Exp/Cntr=0.3,0.1

Type RM Length L Ch R = 1,14174,85,85,85
BEGIN DESCRIPTION:
Mapping XS 3dd94fe4
END DESCRIPTION:
XS GIS Cut Line= 6
      3719195.74     10767937.80      3718979.58     10767453.39
      3718961.35     10767263.29      3718922.29     10767200.79
      3718789.48     10767219.02      3718357.15     10767437.79
#Sta/Elev= 30
  4122.1  459.12  4194.6  458.85  4217.8  456.57  4252.0  457.43  4269.7  456.58
  4298.4  457.45  4344.9  457.10  4350.3  457.91  4396.8  458.65  4414.5  458.01
  4426.1  458.77  4518.0  457.78  4611.2  455.36  4776.1  454.77  4823.6  455.59
  4825.6  454.64  4828.4  454.14  4831.6  454.64  4843.1  455.85  4883.1  456.17
  4906.7  455.96  4913.0  455.05  4930.9  455.97  5009.0  455.23  5421.2  455.88
  5472.3  456.33  5493.2  458.75  5517.2  458.75  5536.6  459.37  5543.4  460.95
#Mann=5,-1,0
  4122.1    0.16       0  4518.0    0.05       0  4825.6    0.03       0
  4831.6    0.05       0  5517.2    0.08       0
Bank Sta=4825.6,4831.6
Exp/Cntr=0.3,0.1

Type RM Length L Ch R = 1,14089,118,118,118
BEGIN DESCRIPTION:
KILE BRANCH 29.0
END DESCRIPTION:
XS GIS Cut Line= 6
      3719219.18     10767935.19      3719029.06     10767406.52
      3719013.44     10767205.99      3718917.08     10767109.64
      3718531.66     10767265.89      3718338.94     10767414.34
#Sta/Elev= 30
  4044.2  458.10  4204.5  452.54  4260.7  452.75  4266.0  455.25  4291.4  452.77
  4383.5  455.72  4493.1  453.96  4660.4  444.74  4915.8  445.40  4972.2  441.09
  4984.8  443.71  5020.2  439.08  5022.9  438.58  5026.2  439.08  5028.3  443.22
  5054.4  439.38  5100.0  439.70  5105.6  442.98  5122.9  440.14  5128.4  443.71
  5196.8  440.17  5202.4  443.56  5225.2  444.23  5265.3  441.40  5270.8  444.04
  5308.2  443.32  5357.9  443.04  5442.9  445.39  5553.1  454.86  5609.8  457.26
#Mann=7,-1,0
  4044.2    0.16       0  4493.1    0.05       0  5020.2    0.03       0
  5026.2    0.05       0  5308.2    0.16       0  5357.9    0.05       0
  5553.1    0.08       0
Bank Sta=5020.2,5026.2
Exp/Cntr=0.3,0.1

Type RM Length L Ch R = 1,13971,449,449,449
BEGIN DESCRIPTION:
KILE BRANCH 28.0
END DESCRIPTION:
XS GIS Cut Line= 3
      3719399.62     10767110.19      3718899.61     10767010.19
      3718599.58     10766810.17
#Sta/Elev= 30
  4483.6  452.09  4486.2  452.09  4493.8  450.38  4503.7  449.51  4524.4  445.69
  4534.6  444.42  4544.8  440.69  4552.0  439.08  4554.7  438.58  4558.0  439.08
  4850.7  439.08  4860.9  440.32  4881.3  441.88  4901.7  439.08  5202.3  439.08
  5217.4  441.89  5233.2  442.64  5245.9  444.16  5253.4  444.49  5259.4  444.32
  5268.4  445.88  5274.4  445.97  5282.0  447.41  5295.5  448.11  5304.5  449.01
  5318.0  449.90  5325.5  450.83  5340.5  450.86  5351.1  451.80  5354.1  451.80
#Mann=5,-1,0
  4483.6    0.16       0  4503.7    0.05       0  4552.0   0.033       0
  4558.0    0.05       0  5233.2    0.12       0
Bank Sta=4552,4558
Exp/Cntr=0.3,0.1

Type RM Length L Ch R = 1,13522,466,466,466
BEGIN DESCRIPTION:
KILE BRANCH 27.0
END DESCRIPTION:
XS GIS Cut Line= 3
      3719449.56     10766560.20      3719099.61     10766610.19
      3718399.62     10766510.19
#Sta/Elev= 30
  4635.9  455.07  4656.1  453.70  4676.3  451.41  4686.4  449.35  4706.6  446.28
  4716.7  445.77  4726.8  443.63  4757.1  440.68  4764.2  439.08  4766.9  438.58
  4770.2  439.08  4785.8  439.08  5285.3  439.08  5332.9  439.08  5343.0  441.12
  5384.8  444.69  5413.7  448.28  5423.8  448.94  5444.0  452.39  5454.1  457.89
  5484.2  457.92  5534.9  458.44  5545.0  460.45  5565.2  462.54  5575.3  462.73
  5605.6  465.97  5625.8  467.37  5635.9  467.47  5683.1  471.75  5696.5  473.02
#Mann=8,-1,0
  4635.9    0.16       0  4764.2   0.033       0  4770.2    0.16       0
  4785.8    0.05       0  5285.3    0.12       0  5384.8    0.05       0
  5484.2    0.16       0  5683.1    0.08       0
Bank Sta=4764.2,4770.2
Exp/Cntr=0.3,0.1

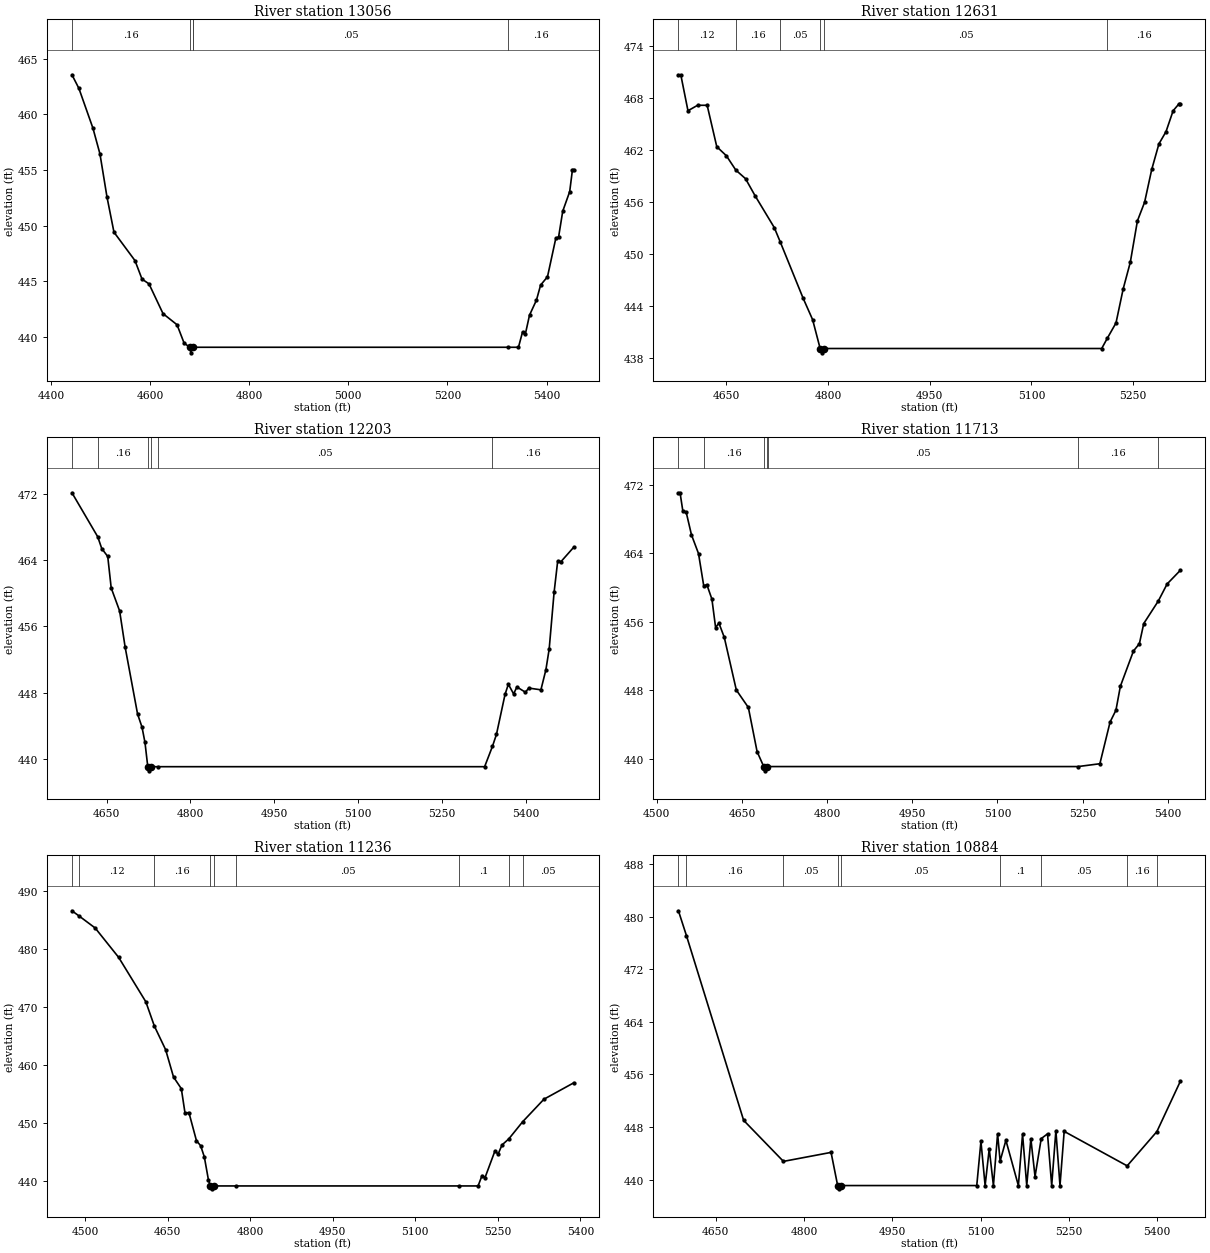
Type RM Length L Ch R = 1,13056,425,425,425
BEGIN DESCRIPTION:
KILE BRANCH 26.0
END DESCRIPTION:
XS GIS Cut Line= 3
      3719399.58     10765760.22      3718999.61     10766160.19
      3718599.57     10766360.21
#Sta/Elev= 30
  4442.3  463.54  4456.4  462.31  4484.7  458.74  4498.8  456.44  4513.0  452.57
  4527.1  449.41  4569.5  446.86  4583.7  445.20  4597.8  444.77  4626.1  442.10
  4654.4  441.10  4668.5  439.47  4679.7  439.08  4682.4  438.58  4685.7  439.08
  4686.1  439.08  5322.8  439.08  5343.4  439.08  5351.7  440.46  5357.3  440.26
  5365.7  441.96  5379.7  443.31  5388.1  444.66  5402.0  445.41  5418.8  448.87
  5424.4  448.98  5432.8  451.30  5446.8  453.05  5452.4  455.03  5455.2  455.03
#Mann=5,-1,0
  4442.3    0.16       0  4679.7   0.033       0  4685.7    0.16       0
  4686.1    0.05       0  5322.8    0.16       0
Bank Sta=4679.7,4685.7
Exp/Cntr=0.3,0.1

Type RM Length L Ch R = 1,12631,428,428,428
BEGIN DESCRIPTION:
KILE BRANCH 25.0
END DESCRIPTION:
XS GIS Cut Line= 3
      3719149.61     10765460.19      3718849.61     10765760.19
      3718549.60     10765860.19
#Sta/Elev= 30
  4579.2  470.67  4582.7  470.67  4593.3  466.52  4607.5  467.15  4621.6  467.15
  4635.8  462.37  4649.9  461.33  4663.9  459.67  4678.2  458.68  4692.3  456.71
  4720.6  453.04  4729.6  451.35  4763.0  444.92  4777.2  442.41  4788.3  439.08
  4791.1  438.58  4794.3  439.08  5203.7  439.08  5212.1  440.28  5224.8  442.03
  5235.4  445.96  5245.9  449.03  5256.4  453.81  5267.0  455.96  5277.5  459.74
  5288.1  462.69  5298.6  464.11  5309.1  466.52  5317.1  467.26  5319.7  467.26
#Mann=6,-1,0
  4579.2    0.12       0  4663.9    0.16       0  4729.6    0.05       0
  4788.3   0.033       0  4794.3    0.05       0  5212.1    0.16       0
Bank Sta=4788.3,4794.3
Exp/Cntr=0.3,0.1

Type RM Length L Ch R = 1,12203,490,490,490
BEGIN DESCRIPTION:
KILE BRANCH 24.0
END DESCRIPTION:
XS GIS Cut Line= 3
      3719099.62     10765210.19      3718699.61     10765360.19
      3718449.61     10765760.18
#Sta/Elev= 30
  4587.7  472.11  4633.9  466.80  4641.1  465.38  4651.8  464.43  4658.0  460.63
  4673.1  457.86  4682.9  453.52  4705.2  445.44  4713.2  443.84  4718.5  442.00
  4723.5  439.08  4726.3  438.58  4729.5  439.08  4741.1  439.08  5326.8  439.08
  5340.8  441.53  5348.0  442.98  5363.4  447.81  5369.3  449.02  5378.7  447.86
  5384.6  448.69  5399.9  448.06  5405.8  448.56  5427.6  448.35  5436.5  450.76
  5442.4  453.26  5451.2  460.10  5457.7  463.90  5463.6  463.81  5486.6  465.56
#Mann=6,-1,0
  4587.7    0.12       0  4633.9    0.16       0  4723.5   0.033       0
  4729.5    0.16       0  4741.1    0.05       0  5340.8    0.16       0
Bank Sta=4723.5,4729.5
Exp/Cntr=0.3,0.1

Type RM Length L Ch R = 1,11713,477,477,477
BEGIN DESCRIPTION:
KILE BRANCH 23.0
END DESCRIPTION:
XS GIS Cut Line= 3
      3719099.61     10765110.19      3718699.61     10764860.19
      3718299.62     10764960.19
#Sta/Elev= 30
  4538.2  471.10  4541.1  471.10  4545.9  469.01  4551.8  468.85  4561.2  466.18
  4573.6  463.99  4582.8  460.22  4588.3  460.35  4597.2  458.66  4603.7  455.34
  4609.5  455.86  4619.0  454.19  4640.2  448.03  4661.4  445.99  4676.8  440.82
  4688.5  439.08  4691.3  438.58  4694.5  439.08  4696.8  439.08  5242.1  439.08
  5280.5  439.41  5298.5  444.29  5308.8  445.67  5316.6  448.47  5339.7  452.60
  5350.1  453.45  5357.8  455.81  5383.4  458.44  5399.0  460.44  5422.2  462.03
#Mann=7,-1,0
  4538.2    0.12       0  4582.8    0.16       0  4688.5   0.033       0
  4694.5    0.16       0  4696.8    0.05       0  5242.1    0.16       0
  5383.4    0.12       0
Bank Sta=4688.5,4694.5
Exp/Cntr=0.3,0.1

Type RM Length L Ch R = 1,11236,352,352,352
BEGIN DESCRIPTION:
KILE BRANCH 22.0
END DESCRIPTION:
XS GIS Cut Line= 3
      3718999.59     10764010.21      3718649.61     10764410.19
      3718299.58     10764560.20
#Sta/Elev= 30
  4475.8  486.55  4489.2  485.62  4518.0  483.58  4560.7  478.51  4610.1  470.85
  4625.6  466.66  4646.1  462.58  4660.4  457.88  4674.6  455.86  4681.3  451.66
  4688.4  451.74  4702.1  446.89  4709.7  446.02  4716.4  444.10  4724.0  440.06
  4727.6  439.08  4730.4  438.58  4733.6  439.08  4774.2  439.08  5179.6  439.08
  5214.0  439.08  5221.2  440.87  5226.7  440.53  5244.8  445.15  5250.3  444.55
  5257.5  446.15  5269.8  447.19  5295.1  450.16  5333.7  454.04  5388.1  456.88
#Mann=9,-1,0
  4475.8    0.05       0  4489.2    0.12       0  4625.6    0.16       0
  4727.6   0.033       0  4733.6    0.16       0  4774.2    0.05       0
  5179.6     0.1       0  5269.8    0.16       0  5295.1    0.05       0
Bank Sta=4727.6,4733.6
Exp/Cntr=0.3,0.1

Type RM Length L Ch R = 1,10884,33,33,33
BEGIN DESCRIPTION:
Mapping XS d53b3e3e
END DESCRIPTION:
XS GIS Cut Line= 2
      3718736.25     10763830.09      3718134.68     10764434.27
#Sta/Elev= 30
  4586.5  480.92  4600.2  477.12  4697.3  449.01  4764.9  442.76  4845.8  444.13
  4857.0  439.08  4859.7  438.58  4863.0  439.08  5093.3  439.08  5100.4  445.80
  5107.5  439.08  5114.5  444.67  5121.6  439.08  5128.7  446.96  5133.0  442.81
  5142.8  445.97  5164.0  439.08  5171.1  446.90  5178.2  439.08  5185.2  446.21
  5192.3  440.45  5202.8  446.23  5213.5  446.95  5220.6  439.08  5227.7  447.43
  5234.7  439.08  5241.8  447.33  5348.8  442.08  5399.3  447.30  5439.1  454.95
#Mann=9,-1,0
  4586.5    0.12       0  4600.2    0.16       0  4764.9    0.05       0
  4857.0   0.033       0  4863.0    0.05       0  5133.0     0.1       0
  5202.8    0.05       0  5348.8    0.16       0  5399.3    0.05       0
Bank Sta=4857,4863
Exp/Cntr=0.3,0.1

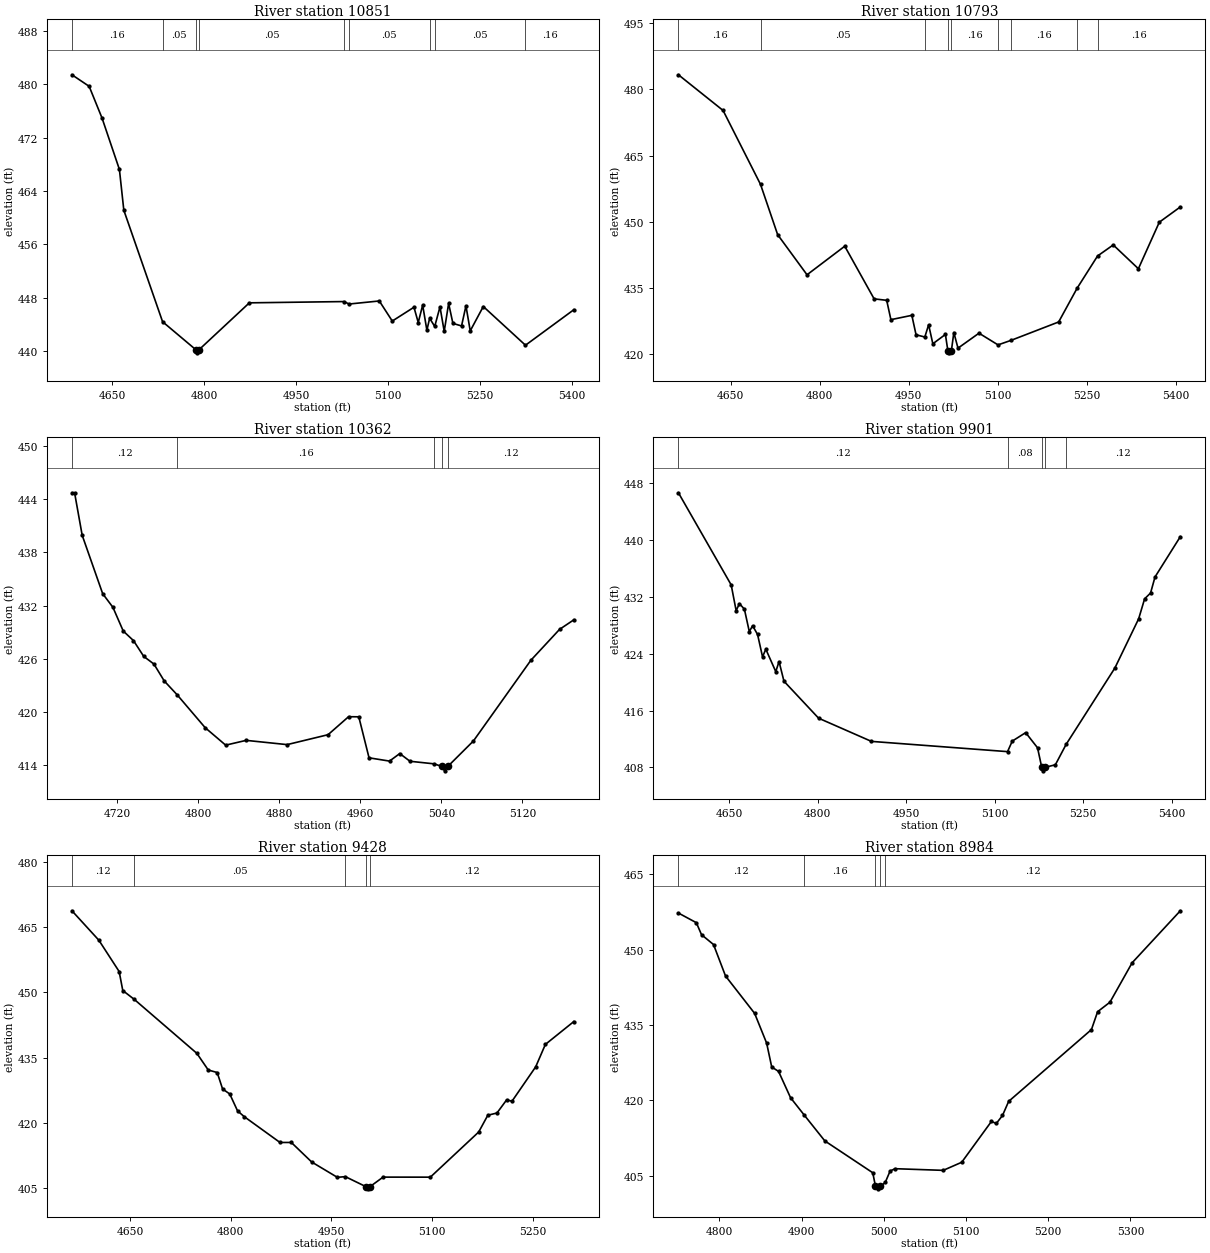
Type RM Length L Ch R = 1,10851,58,58,58
BEGIN DESCRIPTION:
Mapping XS 8ba0e669
END DESCRIPTION:
XS GIS Cut Line= 2
      3718715.40     10763796.26      3718145.05     10764384.84
#Sta/Elev= 30
  4583.8  481.40  4611.9  479.67  4633.0  474.90  4661.3  467.22  4668.5  461.11
  4731.8  444.41  4785.7  440.25  4788.4  439.75  4791.7  440.25  4873.5  447.24
  5028.1  447.43  5036.3  447.06  5085.7  447.52  5106.9  444.51  5142.3  446.58
  5149.3  444.29  5156.5  446.90  5163.4  443.14  5167.9  444.93  5176.2  443.70
  5184.8  446.64  5191.7  442.96  5198.9  447.15  5205.9  444.16  5220.0  443.78
  5227.2  446.79  5234.2  443.04  5255.5  446.69  5324.4  440.89  5403.4  446.21
#Mann=9,-1,0
  4583.8    0.16       0  4731.8    0.05       0  4785.7    0.03       0
  4791.7    0.05       0  5028.1    0.16       0  5036.3    0.05       0
  5167.9     0.1       0  5176.2    0.05       0  5324.4    0.16       0
Bank Sta=4785.7,4791.7
Exp/Cntr=0.3,0.1

Type RM Length L Ch R = 1,10793,431,431,431
BEGIN DESCRIPTION:
KILE BRANCH 21.0
END DESCRIPTION:
XS GIS Cut Line= 2
      3718703.22     10763737.26      3718104.94     10764335.54
#Sta/Elev= 30
  4562.0  483.31  4637.3  475.23  4700.4  458.50  4729.3  447.11  4778.8  438.03
  4842.4  444.50  4891.9  432.58  4913.1  432.25  4920.2  427.87  4955.5  428.85
  4962.6  424.45  4977.4  423.94  4983.8  426.72  4990.9  422.41  5012.1  424.53
  5016.2  420.86  5018.9  420.36  5022.2  420.86  5026.3  424.96  5033.3  421.42
  5068.7  424.81  5100.8  422.16  5123.0  423.20  5203.0  427.35  5234.2  435.01
  5268.6  442.29  5295.0  444.79  5337.4  439.40  5372.7  449.94  5408.1  453.39
#Mann=9,-1,0
  4562.0    0.16       0  4700.4    0.05       0  4977.4    0.16       0
  5016.2    0.07       0  5022.2    0.16       0  5100.8    0.05       0
  5123.0    0.16       0  5234.2    0.05       0  5268.6    0.16       0
Bank Sta=5016.2,5022.2
Exp/Cntr=0.3,0.1

Type RM Length L Ch R = 1,10362,461,461,461
BEGIN DESCRIPTION:
KILE BRANCH 20.0
END DESCRIPTION:
XS GIS Cut Line= 3
      3718399.65     10763710.18      3718049.61     10763760.19
      3717949.62     10763860.18
#Sta/Elev= 30
  4675.7  444.74  4678.3  444.74  4685.8  439.94  4706.0  433.35  4716.1  431.81
  4726.3  429.13  4736.4  428.05  4746.5  426.27  4756.6  425.40  4766.7  423.50
  4779.4  421.94  4807.1  418.22  4827.3  416.25  4847.5  416.79  4887.9  416.31
  4928.3  417.43  4948.5  419.46  4958.6  419.45  4968.7  414.82  4988.9  414.45
  4999.0  415.30  5009.1  414.43  5032.9  414.14  5040.4  413.85  5043.2  413.35
  5046.4  413.85  5071.7  416.73  5128.3  425.83  5156.6  429.32  5170.7  430.40
#Mann=5,-1,0
  4675.7    0.12       0  4779.4    0.16       0  5032.9    0.12       0
  5040.4    0.07       0  5046.4    0.12       0
Bank Sta=5040.4,5046.4
Exp/Cntr=0.3,0.1

Type RM Length L Ch R = 1,9901,473,473,473
BEGIN DESCRIPTION:
KILE BRANCH 19.0
END DESCRIPTION:
XS GIS Cut Line= 3
      3717949.59     10763060.23      3717749.61     10763460.19
      3717349.59     10763410.19
#Sta/Elev= 30
  4564.3  446.61  4653.7  433.66  4662.1  430.04  4667.7  431.03  4676.1  430.24
  4684.4  427.09  4690.0  427.92  4698.4  426.69  4706.8  423.55  4712.4  424.62
  4729.2  421.47  4734.8  422.88  4743.1  420.12  4801.8  414.92  4891.3  411.66
  5121.9  410.22  5129.9  411.70  5152.6  412.89  5172.7  410.76  5179.8  408.02
  5182.5  407.52  5185.8  408.02  5202.9  408.37  5221.2  411.25  5303.7  421.97
  5344.0  428.89  5354.1  431.70  5364.2  432.52  5371.7  434.77  5414.6  440.44
#Mann=5,-1,0
  4564.3    0.12       0  5121.9    0.08       0  5179.8    0.07       0
  5185.8    0.08       0  5221.2    0.12       0
Bank Sta=5179.8,5185.8
Exp/Cntr=0.3,0.1

Type RM Length L Ch R = 1,9428,444,444,444
BEGIN DESCRIPTION:
KILE BRANCH 18.0
END DESCRIPTION:
XS GIS Cut Line= 3
      3717699.62     10762660.16      3717549.61     10763060.19
      3717349.60     10763310.20
#Sta/Elev= 30
  4563.7  468.71  4603.8  461.95  4634.0  454.77  4639.4  450.41  4656.5  448.38
  4749.7  436.00  4766.7  432.17  4780.0  431.60  4788.0  427.83  4798.7  426.67
  4810.3  422.80  4820.1  421.49  4873.5  415.55  4890.4  415.55  4920.6  411.08
  4958.9  407.55  4970.8  407.71  5001.5  405.41  5004.3  404.91  5007.5  405.41
  5027.0  407.60  5097.4  407.59  5169.4  417.95  5183.0  421.80  5196.6  422.31
  5211.0  425.32  5219.0  425.02  5254.3  432.91  5268.7  438.05  5311.1  443.30
#Mann=5,-1,0
  4563.7    0.12       0  4656.5    0.05       0  4970.8    0.12       0
  5001.5    0.07       0  5007.5    0.12       0
Bank Sta=5001.5,5007.5
Exp/Cntr=0.3,0.1

Type RM Length L Ch R = 1,8984,463,463,463
BEGIN DESCRIPTION:
KILE BRANCH 17.0
END DESCRIPTION:
XS GIS Cut Line= 3
      3717449.59     10762610.21      3717299.61     10762810.19
      3716999.63     10763010.17
#Sta/Elev= 30
  4750.2  457.27  4772.0  455.35  4778.3  452.96  4792.9  451.00  4807.5  444.74
  4842.9  437.30  4857.5  431.38  4863.7  426.62  4872.0  425.75  4886.6  420.51
  4903.3  417.04  4928.3  411.91  4986.6  405.57  4989.9  402.87  4992.6  402.37
  4995.9  402.87  5001.8  403.65  5007.7  405.92  5013.7  406.38  5072.3  406.05
  5094.8  407.66  5130.9  415.78  5136.9  415.39  5144.4  416.97  5151.9  419.78
  5252.6  434.07  5260.1  437.63  5275.1  439.52  5302.1  447.37  5360.7  457.72
#Mann=5,-1,0
  4750.2    0.12       0  4903.3    0.16       0  4989.9    0.07       0
  4995.9    0.16       0  5001.8    0.12       0
Bank Sta=4989.9,4995.9
Exp/Cntr=0.3,0.1

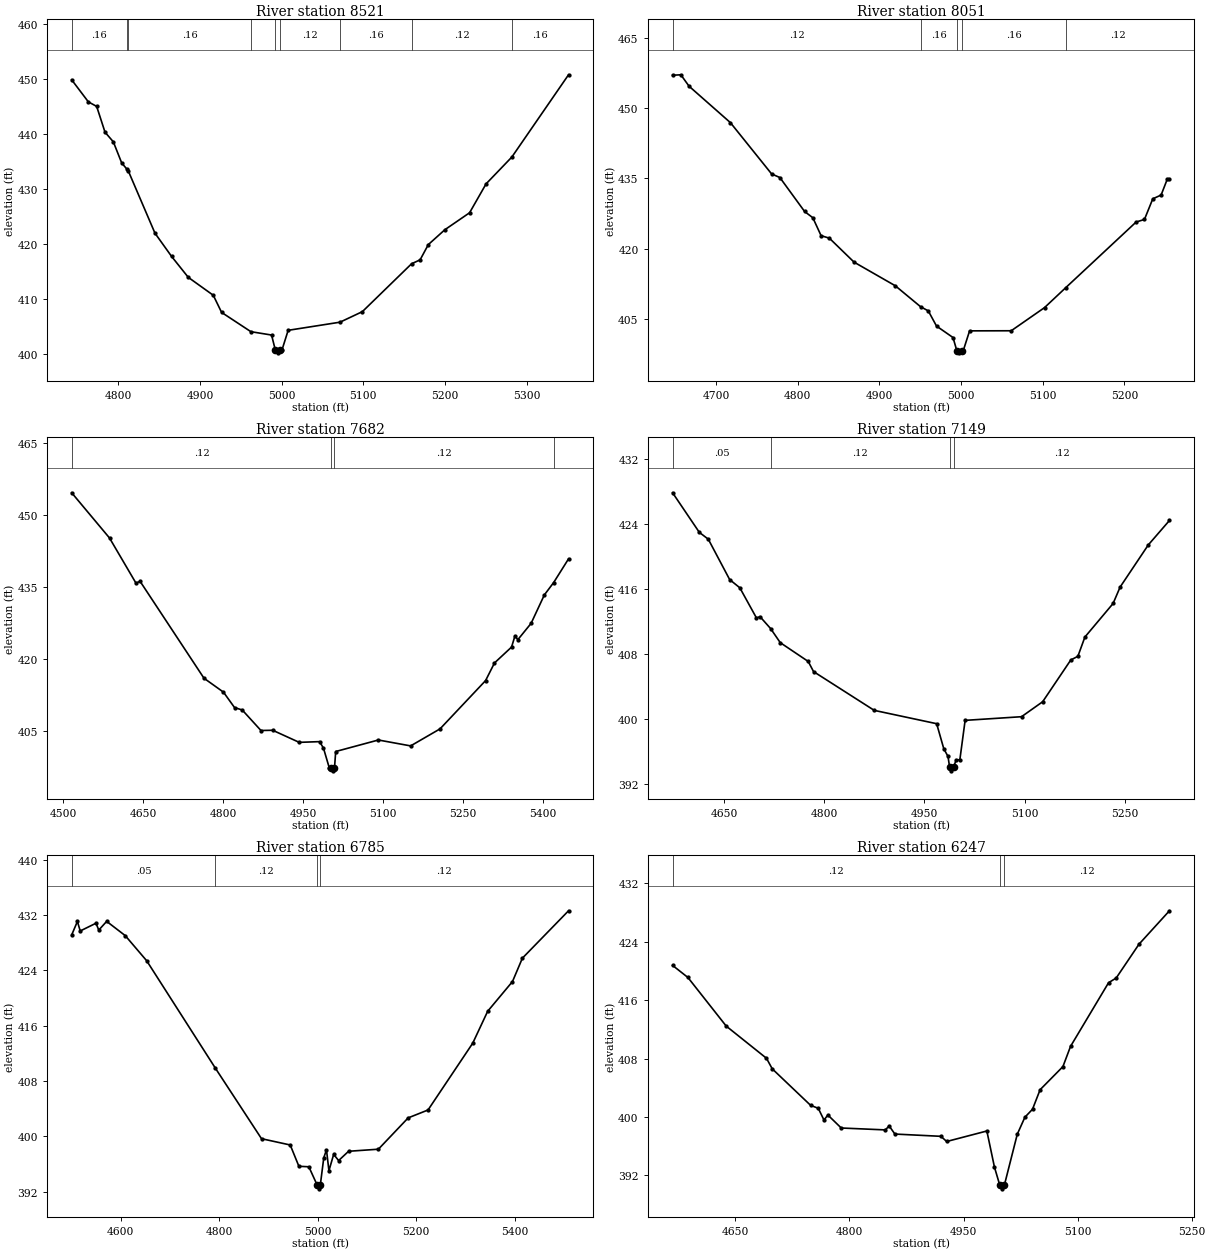
Type RM Length L Ch R = 1,8521,470,470,470
BEGIN DESCRIPTION:
KILE BRANCH 16.0
END DESCRIPTION:
XS GIS Cut Line= 3
      3717299.61     10762410.19      3717049.61     10762460.19
      3716699.61     10762410.19
#Sta/Elev= 30
  4742.8  449.85  4763.2  445.84  4773.4  445.01  4783.6  440.32  4793.8  438.56
  4804.0  434.73  4810.4  433.59  4812.0  433.31  4844.8  421.93  4865.2  417.69
  4885.6  413.89  4916.2  410.63  4926.4  407.51  4962.3  404.00  4987.6  403.39
  4992.2  400.65  4995.0  400.15  4998.2  400.65  5000.3  400.65  5007.9  404.25
  5071.4  405.73  5098.8  407.65  5159.1  416.37  5169.5  417.08  5179.6  419.86
  5199.8  422.56  5230.1  425.65  5250.3  430.91  5281.9  435.80  5351.3  450.77
#Mann=9,-1,0
  4742.8    0.16       0  4810.4    0.12       0  4812.0    0.16       0
  4962.3    0.12       0  4992.2    0.07       0  4998.2    0.12       0
  5071.4    0.16       0  5159.1    0.12       0  5281.9    0.16       0
Bank Sta=4992.2,4998.2
Exp/Cntr=0.3,0.1

Type RM Length L Ch R = 1,8051,369,369,369
BEGIN DESCRIPTION:
KILE BRANCH 15.0
END DESCRIPTION:
XS GIS Cut Line= 3
      3717349.66     10761960.18      3716999.61     10762010.19
      3716749.56     10762060.20
#Sta/Elev= 30
  4646.6  457.06  4656.7  457.16  4666.8  454.71  4717.4  446.93  4767.9  435.96
  4778.0  435.19  4808.3  427.93  4818.4  426.59  4828.5  422.76  4838.6  422.23
  4868.9  417.10  4919.4  412.05  4950.3  407.58  4959.8  406.68  4969.9  403.43
  4990.1  400.98  4994.7  398.21  4997.4  397.71  5000.7  398.21  5002.7  398.21
  5010.4  402.41  5061.4  402.43  5102.2  407.38  5128.1  411.63  5214.4  425.68
  5224.6  426.23  5234.8  430.64  5245.0  431.45  5252.6  434.86  5255.2  434.86
#Mann=5,-1,0
  4646.6    0.12       0  4950.3    0.16       0  4994.7    0.07       0
  5000.7    0.16       0  5128.1    0.12       0
Bank Sta=4994.7,5000.7
Exp/Cntr=0.3,0.1

Type RM Length L Ch R = 1,7682,533,533,533
BEGIN DESCRIPTION:
KILE BRANCH 14.0
END DESCRIPTION:
XS GIS Cut Line= 3
      3717349.59     10761910.17      3717017.12     10761634.38
      3716549.65     10761810.17
#Sta/Elev= 30
  4516.2  454.72  4587.1  445.29  4636.6  435.90  4644.5  436.24  4764.2  416.05
  4800.7  413.15  4821.5  409.93  4835.9  409.43  4871.0  405.15  4893.0  405.20
  4942.7  402.68  4980.9  402.83  4988.2  401.47  4998.9  397.43  5002.8  397.24
  5005.5  396.74  5008.8  397.24  5011.1  400.77  5091.1  403.17  5151.6  401.94
  5206.7  405.49  5292.1  415.56  5308.8  419.24  5340.8  422.55  5347.2  424.89
  5352.5  424.08  5377.4  427.49  5402.3  433.43  5419.7  436.00  5447.6  440.94
#Mann=4,-1,0
  4516.2    0.12       0  5002.8    0.07       0  5008.8    0.12       0
  5419.7    0.16       0
Bank Sta=5002.8,5008.8
Exp/Cntr=0.3,0.1

Type RM Length L Ch R = 1,7149,364,364,364
BEGIN DESCRIPTION:
KILE BRANCH 13.0
END DESCRIPTION:
XS GIS Cut Line= 3
      3717499.60     10761410.18      3717099.61     10761260.19
      3716799.62     10761160.19
#Sta/Elev= 30
  4573.2  427.82  4613.2  422.95  4626.6  422.11  4658.6  417.14  4673.8  416.13
  4698.7  412.42  4704.0  412.58  4719.9  411.11  4734.3  409.38  4776.1  407.07
  4784.1  405.82  4874.9  401.05  4968.3  399.41  4979.0  396.32  4985.3  395.38
  4987.6  394.11  4990.3  393.61  4993.6  394.11  4997.7  394.97  5003.0  394.97
  5010.9  399.82  5095.3  400.27  5126.9  402.11  5169.0  407.25  5179.6  407.70
  5190.1  410.07  5232.3  414.20  5242.8  416.22  5285.0  421.41  5316.6  424.41
#Mann=4,-1,0
  4573.2    0.05       0  4719.9    0.12       0  4987.6    0.07       0
  4993.6    0.12       0
Bank Sta=4987.6,4993.6
Exp/Cntr=0.3,0.1

Type RM Length L Ch R = 1,6785,538,538,538
BEGIN DESCRIPTION:
KILE BRANCH 12.0
END DESCRIPTION:
XS GIS Cut Line= 3
      3717704.66     10761170.86      3717316.60     10760954.69
      3716756.74     10760881.78
#Sta/Elev= 30
  4500.8  429.11  4512.4  431.06  4518.1  429.68  4550.1  430.80  4555.8  429.81
  4571.8  431.07  4609.5  429.01  4653.0  425.38  4792.3  409.87  4886.2  399.65
  4944.5  398.74  4962.1  395.66  4982.3  395.59  4999.5  392.90  5002.2  392.40
  5005.5  392.90  5012.6  396.88  5018.1  398.04  5023.1  395.02  5032.7  397.38
  5042.8  396.49  5063.0  397.83  5123.5  398.13  5184.0  402.66  5224.3  403.80
  5315.1  413.46  5345.4  418.07  5395.8  422.37  5415.9  425.75  5509.6  432.60
#Mann=4,-1,0
  4500.8    0.05       0  4792.3    0.12       0  4999.5    0.07       0
  5005.5    0.12       0
Bank Sta=4999.5,5005.5
Exp/Cntr=0.3,0.1

Type RM Length L Ch R = 1,6247,474,474,474
BEGIN DESCRIPTION:
KILE BRANCH 11.0
END DESCRIPTION:
XS GIS Cut Line= 3
      3717599.60     10760410.19      3717199.61     10760460.19
      3716949.61     10760460.19
#Sta/Elev= 30
  4567.6  420.77  4587.7  419.12  4638.1  412.45  4691.0  408.04  4698.6  406.59
  4749.0  401.59  4759.1  401.18  4766.6  399.57  4771.7  400.26  4789.3  398.48
  4847.2  398.22  4852.3  398.76  4859.8  397.65  4920.3  397.34  4927.9  396.63
  4980.7  398.07  4990.7  393.11  4997.7  390.64  5000.5  390.14  5003.7  390.64
  5020.7  397.63  5030.7  399.96  5040.7  401.05  5050.7  403.73  5080.7  406.90
  5090.7  409.67  5140.7  418.40  5150.7  419.04  5180.7  423.68  5220.7  428.26
#Mann=3,-1,0
  4567.6    0.12       0  4997.7    0.07       0  5003.7    0.12       0
Bank Sta=4997.7,5003.7
Exp/Cntr=0.3,0.1