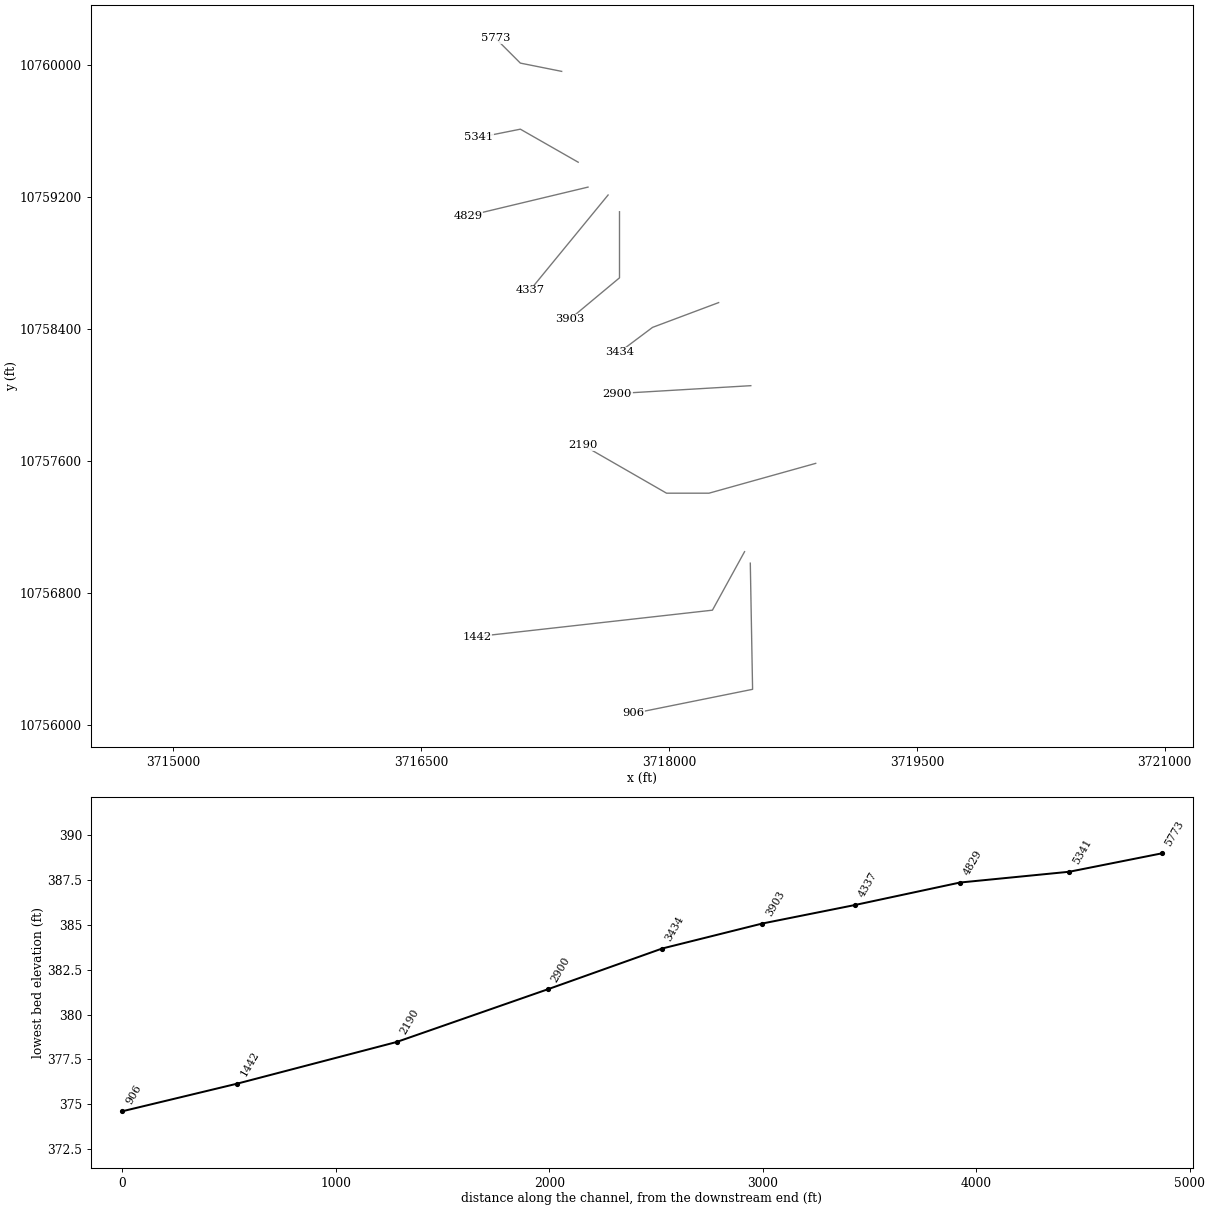
HEC-RAS study KILE BRANCH.prj: KILE BRANCH Base Level Engineering

--- KILE BRANCH.g01 (geometry) --- (continued)

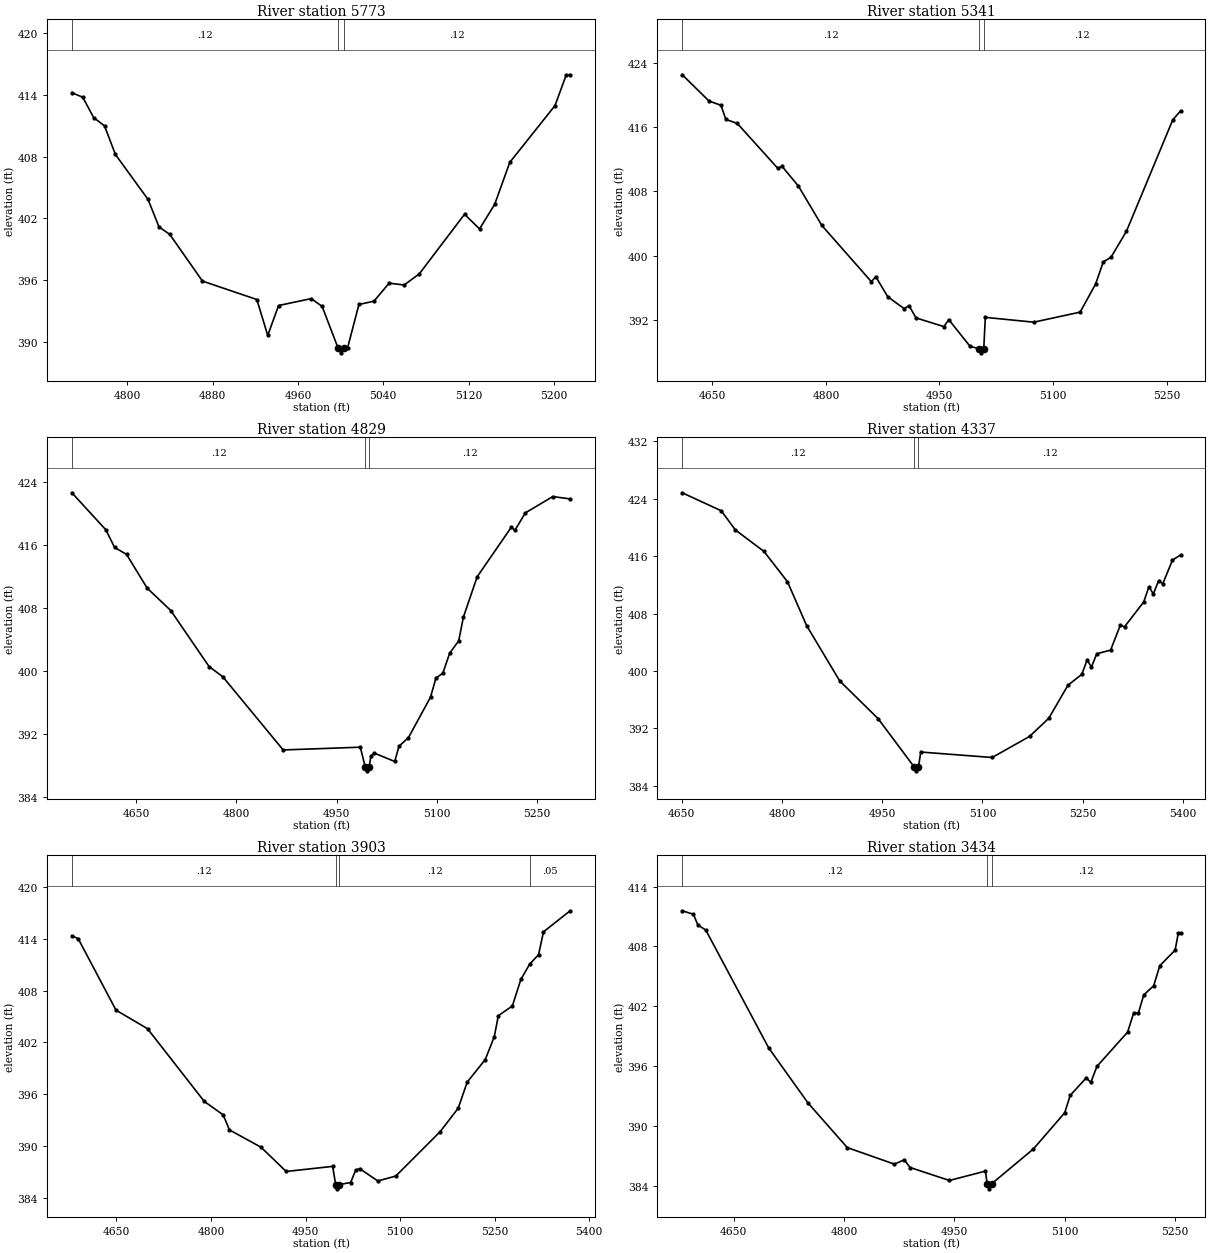
Type RM Length L Ch R = 1,5773,432,432,432
BEGIN DESCRIPTION:
KILE BRANCH 10.0
END DESCRIPTION:
XS GIS Cut Line= 3
      3717349.61     10759960.19      3717099.61     10760010.19
      3716949.59     10760160.20
#Sta/Elev= 30
  4748.1  414.19  4758.3  413.75  4768.5  411.78  4778.7  410.97  4788.9  408.20
  4819.5  403.84  4829.7  401.19  4839.9  400.44  4870.5  395.92  4921.5  394.13
  4931.7  390.65  4941.9  393.55  4972.5  394.22  4982.7  393.46  4997.5  389.46
  5000.2  388.96  5003.5  389.46  5006.6  389.46  5017.2  393.65  5031.3  393.97
  5045.5  395.72  5059.6  395.54  5073.8  396.62  5116.2  402.40  5130.3  400.98
  5144.5  403.37  5158.6  407.43  5201.0  412.94  5211.6  415.93  5215.2  415.93
#Mann=3,-1,0
  4748.1    0.12       0  4997.5    0.07       0  5003.5    0.12       0
Bank Sta=4997.5,5003.5
Exp/Cntr=0.3,0.1

Type RM Length L Ch R = 1,5341,512,512,512
BEGIN DESCRIPTION:
KILE BRANCH 9.0
END DESCRIPTION:
XS GIS Cut Line= 3
      3717449.63     10759410.17      3717099.61     10759610.19
      3716849.60     10759560.19
#Sta/Elev= 30
  4610.3  422.50  4645.6  419.24  4661.4  418.71  4667.9  416.95  4683.0  416.45
  4736.3  410.89  4742.1  411.12  4763.7  408.67  4794.6  403.78  4860.1  396.78
  4865.9  397.41  4881.7  394.91  4903.3  393.44  4909.8  393.80  4919.1  392.28
  4955.9  391.20  4962.3  392.07  4990.4  388.75  5002.5  388.44  5005.3  387.94
  5008.5  388.44  5010.6  392.35  5074.6  391.75  5135.8  393.00  5156.2  396.48
  5166.4  399.24  5176.6  399.82  5197.0  403.05  5258.2  416.90  5268.4  418.00
#Mann=3,-1,0
  4610.3    0.12       0  5002.5    0.07       0  5008.5    0.12       0
Bank Sta=5002.5,5008.5
Exp/Cntr=0.3,0.1

Type RM Length L Ch R = 1,4829,492,492,492
BEGIN DESCRIPTION:
KILE BRANCH 8.0
END DESCRIPTION:
XS GIS Cut Line= 2
      3717509.12     10759259.46      3716784.42     10759085.88
#Sta/Elev= 30
  4554.0  422.62  4604.9  417.91  4617.8  415.69  4635.8  414.80  4666.6  410.52
  4701.9  407.68  4759.2  400.57  4779.7  399.28  4870.0  389.99  4985.4  390.34
  4992.7  387.84  4995.4  387.34  4998.7  387.84  5001.2  389.22  5006.4  389.58
  5036.8  388.53  5043.3  390.46  5057.4  391.56  5090.4  396.69  5098.5  399.11
  5108.8  399.73  5119.1  402.28  5132.5  403.83  5139.6  406.85  5160.2  411.97
  5211.4  418.27  5216.5  417.84  5232.2  420.07  5273.3  422.14  5299.2  421.84
#Mann=3,-1,0
  4554.0    0.12       0  4992.7    0.07       0  4998.7    0.12       0
Bank Sta=4992.7,4998.7
Exp/Cntr=0.3,0.1

Type RM Length L Ch R = 1,4337,434,434,434
BEGIN DESCRIPTION:
KILE BRANCH 7.0
END DESCRIPTION:
XS GIS Cut Line= 2
      3717630.59     10759211.67      3717157.85     10758634.84
#Sta/Elev= 30
  4650.6  424.84  4709.0  422.33  4730.1  419.66  4772.9  416.67  4808.1  412.44
  4836.8  406.32  4886.3  398.62  4943.7  393.37  4998.1  386.59  5000.9  386.09
  5004.1  386.59  5007.6  388.71  5114.5  387.95  5170.5  390.89  5199.2  393.41
  5227.9  398.02  5248.7  399.54  5256.6  401.54  5263.1  400.55  5271.0  402.40
  5291.8  402.92  5306.2  406.36  5312.6  406.16  5341.3  409.62  5349.2  411.76
  5355.7  410.73  5363.6  412.57  5370.0  412.19  5384.4  415.46  5396.4  416.17
#Mann=3,-1,0
  4650.6    0.12       0  4998.1    0.07       0  5004.1    0.12       0
Bank Sta=4998.1,5004.1
Exp/Cntr=0.3,0.1

Type RM Length L Ch R = 1,3903,469,469,469
BEGIN DESCRIPTION:
KILE BRANCH 6.0
END DESCRIPTION:
XS GIS Cut Line= 3
      3717699.61     10759110.22      3717699.61     10758710.19
      3717399.64     10758460.22
#Sta/Elev= 30
  4579.3  414.35  4589.3  414.01  4649.3  405.74  4699.3  403.59  4789.3  395.18
  4819.3  393.62  4829.3  391.88  4879.3  389.88  4919.3  387.07  4993.0  387.66
  4997.8  385.56  5000.6  385.06  5003.8  385.56  5021.6  385.79  5029.4  387.21
  5036.0  387.40  5064.6  385.97  5093.2  386.54  5163.5  391.67  5192.2  394.39
  5206.5  397.41  5235.1  400.02  5249.4  402.65  5255.9  405.10  5278.1  406.22
  5291.7  409.30  5305.7  411.07  5319.7  412.16  5327.5  414.80  5369.8  417.24
#Mann=4,-1,0
  4579.3    0.12       0  4997.8    0.07       0  5003.8    0.12       0
  5305.7    0.05       0
Bank Sta=4997.8,5003.8
Exp/Cntr=0.3,0.1

Type RM Length L Ch R = 1,3434,534,534,534
BEGIN DESCRIPTION:
KILE BRANCH 5.0
END DESCRIPTION:
XS GIS Cut Line= 3
      3718299.60     10758560.18      3717899.61     10758410.19
      3717699.60     10758260.18
#Sta/Elev= 30
  4580.2  411.58  4595.3  411.23  4601.5  410.15  4612.2  409.64  4697.7  397.81
  4751.1  392.29  4804.5  387.81  4868.5  386.15  4881.9  386.58  4889.9  385.81
  4943.3  384.51  4992.3  385.45  4994.6  384.17  4997.3  383.67  5000.6  384.17
  5057.4  387.67  5100.1  391.31  5107.4  393.04  5129.3  394.81  5135.5  394.35
  5143.8  395.96  5185.5  399.40  5193.8  401.34  5200.1  401.29  5207.4  403.13
  5220.9  404.05  5229.3  406.07  5250.1  407.63  5254.3  409.30  5257.4  409.30
#Mann=3,-1,0
  4580.2    0.12       0  4994.6    0.07       0  5000.6    0.12       0
Bank Sta=4994.6,5000.6
Exp/Cntr=0.3,0.1

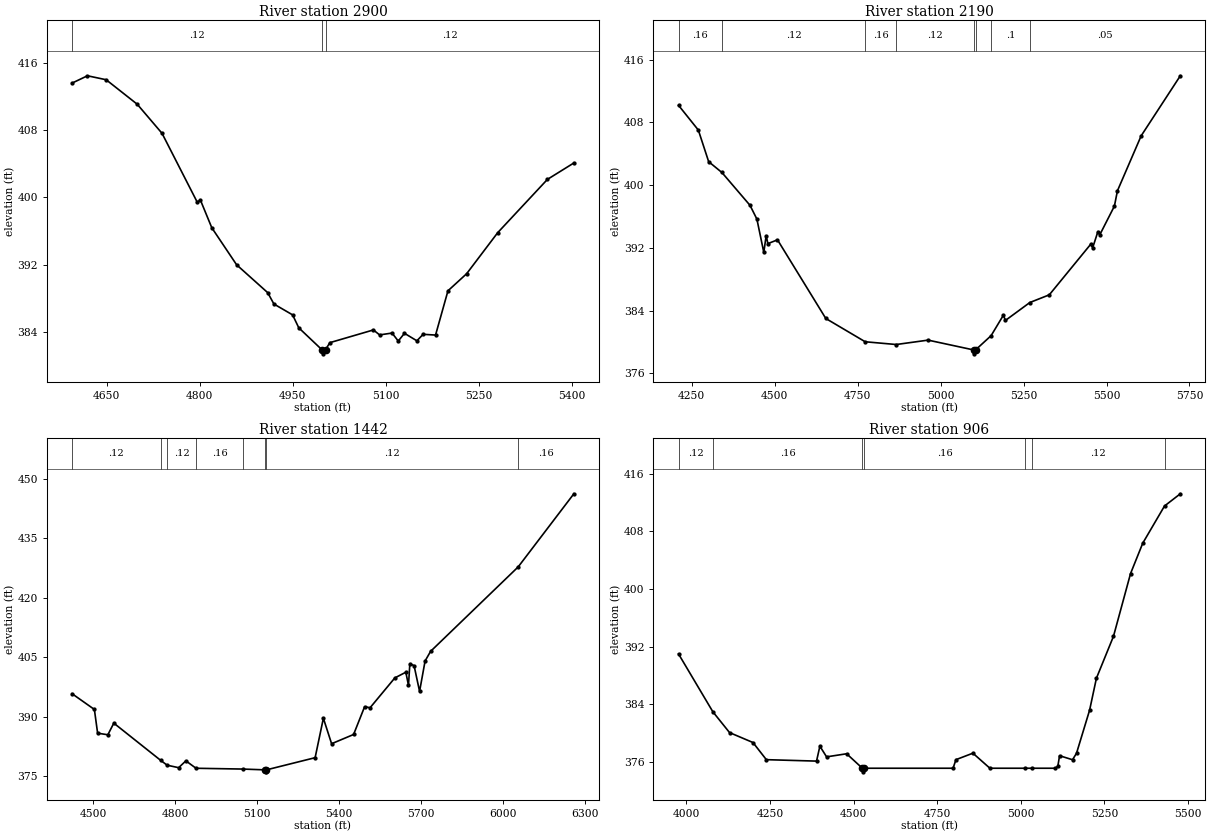
Type RM Length L Ch R = 1,2900,710,710,710
BEGIN DESCRIPTION:
KILE BRANCH 4.0
END DESCRIPTION:
XS GIS Cut Line= 2
      3718494.39     10758057.20      3717687.10     10758009.45
#Sta/Elev= 30
  4594.5  413.58  4619.3  414.45  4649.4  413.98  4699.5  411.07  4739.5  407.61
  4796.3  399.42  4801.3  399.69  4819.7  396.39  4859.7  391.99  4909.8  388.68
  4919.8  387.33  4949.9  386.04  4959.9  384.50  4997.0  381.91  4999.7  381.41
  5003.0  381.91  5010.0  382.74  5080.1  384.25  5090.1  383.66  5110.2  383.88
  5120.2  382.93  5130.2  383.85  5150.2  382.96  5160.3  383.73  5180.3  383.64
  5200.3  388.90  5230.4  390.93  5280.5  395.81  5360.6  402.14  5403.2  404.09
#Mann=3,-1,0
  4594.5    0.12       0  4997.0    0.07       0  5003.0    0.12       0
Bank Sta=4997,5003
Exp/Cntr=0.3,0.1

Type RM Length L Ch R = 1,2190,748,748,748
BEGIN DESCRIPTION:
KILE BRANCH 3.0
END DESCRIPTION:
XS GIS Cut Line= 4
      3718887.07     10757586.82      3718241.25     10757406.26
      3717984.30     10757406.26      3717477.35     10757697.93
#Sta/Elev= 30
  4210.0  410.18  4269.7  407.02  4300.8  402.99  4340.7  401.61  4425.4  397.42
  4446.2  395.66  4467.0  391.41  4474.1  393.55  4479.3  392.53  4508.2  393.02
  4653.9  382.98  4772.6  380.01  4866.0  379.66  4962.2  380.22  5099.2  378.97
  5102.0  378.47  5105.2  378.97  5152.1  380.79  5189.1  383.40  5195.2  382.73
  5268.9  385.02  5327.5  386.00  5452.4  392.46  5458.2  392.00  5474.0  394.07
  5479.8  393.67  5523.7  397.32  5532.9  399.28  5604.4  406.29  5722.4  413.95
#Mann=8,-1,0
  4210.0    0.16       0  4340.7    0.12       0  4772.6    0.16       0
  4866.0    0.12       0  5099.2    0.07       0  5105.2    0.12       0
  5152.1     0.1       0  5268.9    0.05       0
Bank Sta=5099.2,5105.2
Exp/Cntr=0.3,0.1

Type RM Length L Ch R = 1,1442,536,536,536
BEGIN DESCRIPTION:
KILE BRANCH 2.0
END DESCRIPTION:
XS GIS Cut Line= 3
      3718456.54     10757052.13      3718262.08     10756697.93
      3716838.48     10756538.21
#Sta/Elev= 30
  4422.5  395.85  4504.2  391.88  4516.0  385.90  4553.5  385.50  4575.3  388.43
  4746.9  379.04  4770.5  377.82  4812.6  377.20  4839.1  378.92  4876.2  377.05
  5047.7  376.85  5127.9  376.65  5130.7  376.15  5133.9  376.65  5312.1  379.72
  5342.3  389.66  5372.4  383.24  5452.9  385.57  5493.2  392.57  5513.3  392.32
  5603.9  399.84  5644.1  401.27  5653.8  397.97  5658.8  403.42  5674.3  402.93
  5694.4  396.44  5714.6  404.11  5734.7  406.53  6055.3  427.83  6259.1  446.27
#Mann=8,-1,0
  4422.5    0.12       0  4746.9    0.16       0  4770.5    0.12       0
  4876.2    0.16       0  5047.7    0.12       0  5127.9    0.07       0
  5133.9    0.12       0  6055.3    0.16       0
Bank Sta=5127.9,5133.9
Exp/Cntr=0.3,0.1

Type RM Length L Ch R = 1,906,0,0,0
BEGIN DESCRIPTION:
KILE BRANCH 1.0
END DESCRIPTION:
XS GIS Cut Line= 3
      3718491.25     10756982.63      3718505.13     10756218.76
      3717783.78     10756073.10
#Sta/Elev= 30
  3976.8  390.99  4079.4  382.96  4129.3  380.07  4199.3  378.69  4239.3  376.31
  4389.3  376.11  4399.3  378.18  4419.3  376.70  4479.3  377.13  4526.3  375.12
  4529.1  374.62  4532.3  375.12  4797.4  375.12  4806.0  376.31  4856.7  377.21
  4907.5  375.12  5012.2  375.12  5033.8  375.12  5103.5  375.12  5110.6  375.40
  5115.7  376.86  5154.5  376.30  5166.4  377.20  5205.5  383.18  5225.9  387.62
  5276.9  393.44  5327.9  402.15  5364.4  406.37  5429.4  411.53  5476.7  413.23
#Mann=7,-1,0
  3976.8    0.12       0  4079.4    0.16       0  4526.3    0.07       0
  4532.3    0.16       0  5012.2    0.05       0  5033.8    0.12       0
  5429.4    0.16       0
Bank Sta=4526.3,4532.3
Exp/Cntr=0.3,0.1

Chan Stop Cuts=-1