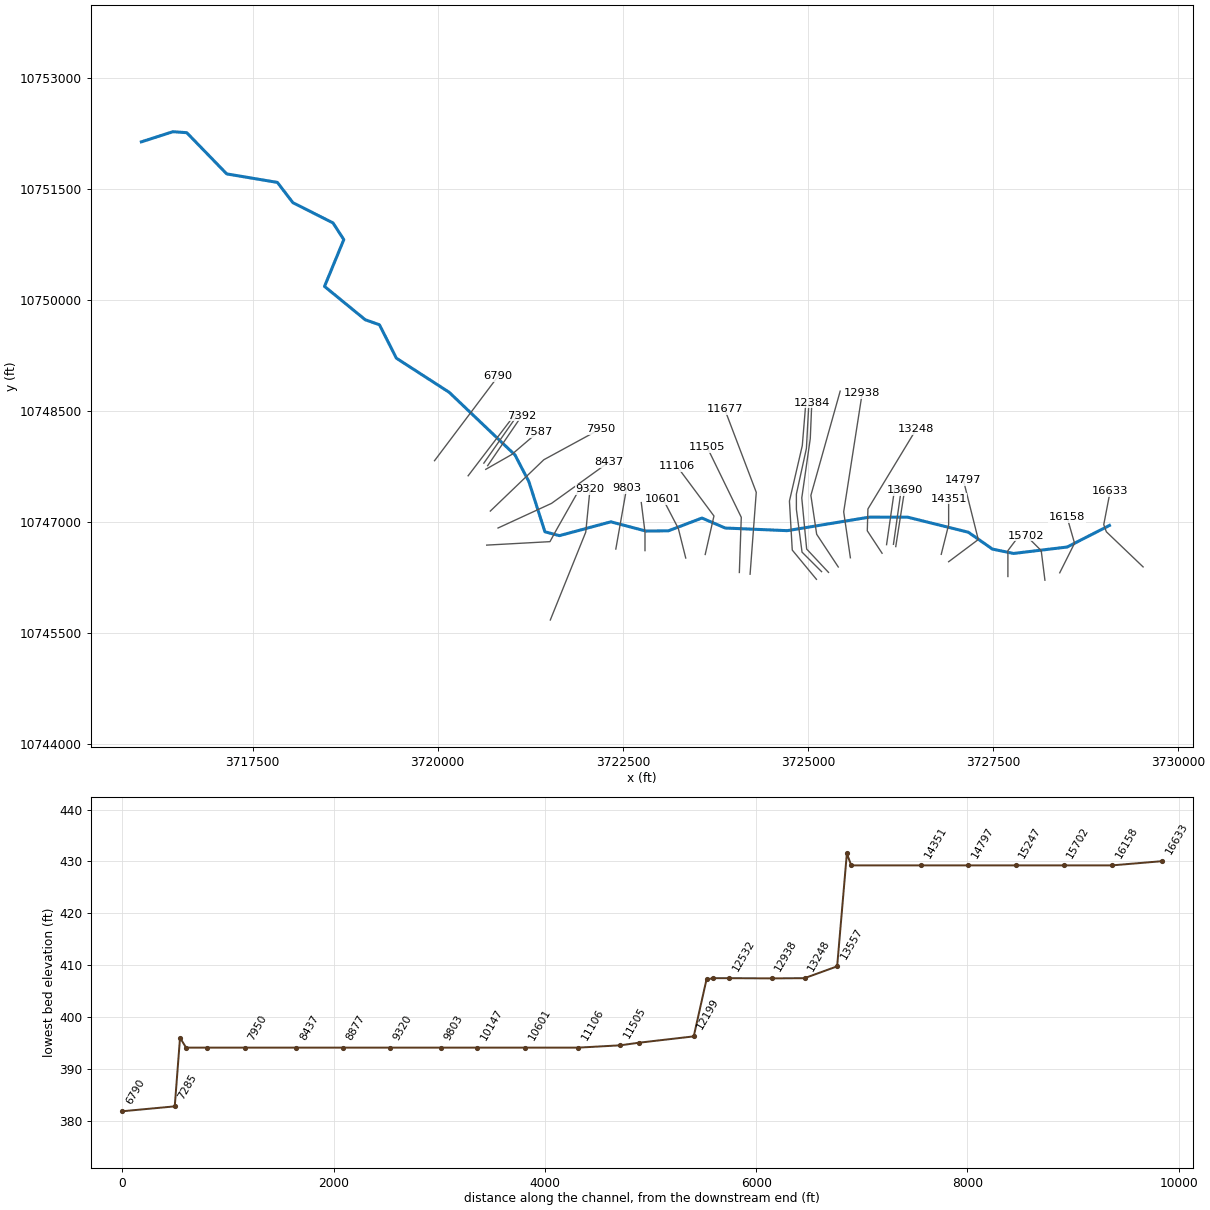
--- LITTLE ALDER CREEK.prj (project) ---

Proj Title=LITTLE ALDER CREEK Base Level Engineering
Current Plan=p01
Default Exp/Contr=0.3,0.1
English Units
Geom File=g01
Flow File=f01
Plan File=p01
BEGIN DESCRIPTION:
LITTLE ALDER CREEK
END DESCRIPTION:

--- LITTLE ALDER CREEK.p01 (plan) ---

Plan Title=Multiple Run
Short Identifier=Multiple
Geom File=g01
Flow File=f01
Subcritical Flow
K Sum by GR= 0
Std Step Tol= 0.01
Critical Tol= 0.01
Num of Std Step Trials= 20
Max Error Tol= 0.3
Flow Tol Ratio= 0.001
Split Flow NTrial= 30
Split Flow Tol= 0.02
Split Flow Ratio= 0.02
Log Output Level= 0
Friction Slope Method= 1
Unsteady Friction Slope Method= 2
Unsteady Bridges Friction Slope Method= 1
Parabolic Critical Depth
Global Vel Dist=  1 , 1 , 1
Global Log Level= 0
CheckData=True
Encroach Param= -1, 0, 0, 0
BEGIN DESCRIPTION:
Multiple Run
END DESCRIPTION:

--- LITTLE ALDER CREEK.f01 (steady flow) ---

Flow Title=Multiple
Number of Profiles=7
Profile Names=10-year,25-year,50-year,1pct_min,100-year,1pct_plu,500-year
River Rch & RM= LITTLE ALDER CRE,Reach-1,16633
     842    1170    1448    1316    1779    2406    2689
River Rch & RM= LITTLE ALDER CRE,Reach-1,16158
    1204    1701    2127    1949    2635    3564    4055
River Rch & RM= LITTLE ALDER CRE,Reach-1,11106
    1246    1759    2198    2011    2720    3679    4176
River Rch & RM= LITTLE ALDER CRE,Reach-1,8877
    2210    3197    4060    3768    5096    6891    8052
River Rch & RM= LITTLE ALDER CRE,Reach-1,3990
    2248    3249    4124    3825    5173    6996    8164
Boundary for River Rch & Prof#=LITTLE ALDER CRE,Reach-1,1
Up Type=0
Dn Type=3
Dn Slope=0.005
Boundary for River Rch & Prof#=LITTLE ALDER CRE,Reach-1,2
Up Type=0
Dn Type=3
Dn Slope=0.005
Boundary for River Rch & Prof#=LITTLE ALDER CRE,Reach-1,3
Up Type=0
Dn Type=3
Dn Slope=0.005
Boundary for River Rch & Prof#=LITTLE ALDER CRE,Reach-1,4
Up Type=0
Dn Type=3
Dn Slope=0.005
Boundary for River Rch & Prof#=LITTLE ALDER CRE,Reach-1,5
Up Type=0
Dn Type=3
Dn Slope=0.005
Boundary for River Rch & Prof#=LITTLE ALDER CRE,Reach-1,6
Up Type=0
Dn Type=3
Dn Slope=0.005
Boundary for River Rch & Prof#=LITTLE ALDER CRE,Reach-1,7
Up Type=0
Dn Type=3
Dn Slope=0.005

--- LITTLE ALDER CREEK.g01 (geometry) ---

Geom Title=Existing Conditions

River Reach=LITTLE ALDER CRE,Reach-1
Reach XY= 30
      3729071.03     10746951.07      3728499.75     10746659.00
      3727775.75     10746572.00      3727491.00     10746631.00
      3727165.50     10746859.00      3726345.25     10747063.00
      3725832.75     10747064.00      3724719.44     10746880.45
      3723883.00     10746916.00      3723568.50     10747051.00
      3723114.50     10746878.00      3722812.50     10746875.00
      3722338.50     10747000.00      3721644.00     10746813.00
      3721448.25     10746865.00      3721232.00     10747543.00
      3721044.50     10747904.00      3720156.00     10748752.00
      3719442.50     10749214.00      3719214.00     10749666.00
      3719022.00     10749734.00      3718472.50     10750185.00
      3718732.75     10750818.00      3718587.00     10751044.00
      3718045.25     10751318.00      3717836.00     10751592.00
      3717152.00     10751707.00      3716612.00     10752265.00
      3716425.50     10752278.00      3715999.50     10752141.00

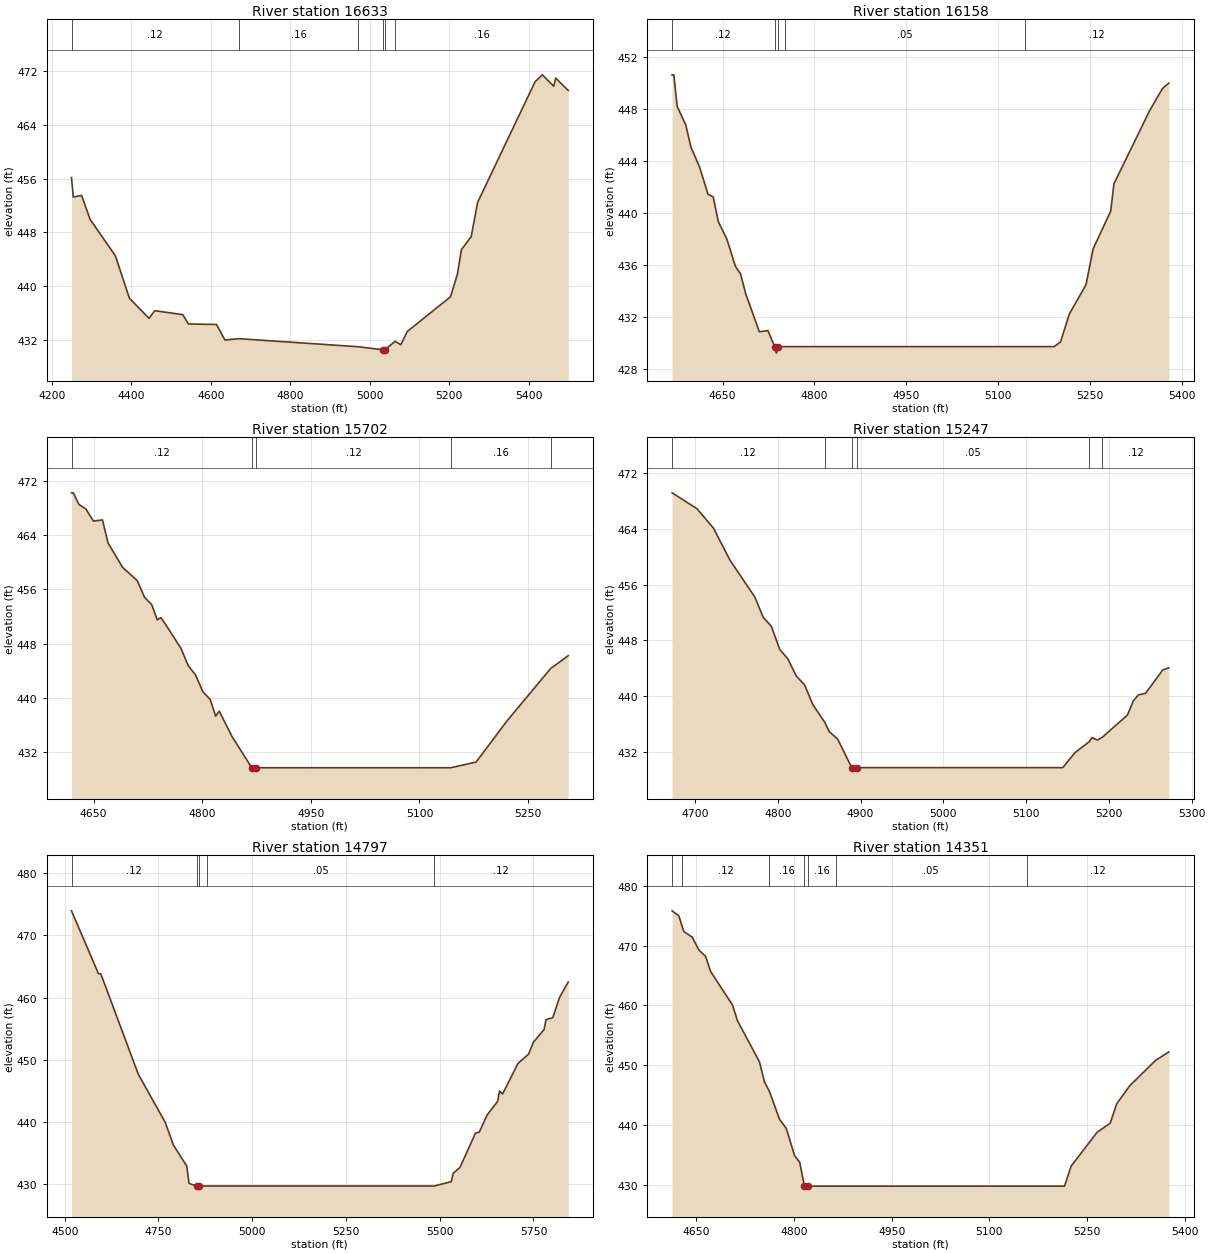
Type RM Length L Ch R = 1,16633,475,475,475
BEGIN DESCRIPTION:
LITTLE ALDER CREEK 34.0
END DESCRIPTION:
XS GIS Cut Line= 4
      3729525.36     10746389.86      3729028.85     10746865.54
      3728994.13     10746962.76      3729080.93     10747414.15
#Sta/Elev= 30
  4249.5  456.18  4253.9  453.28  4275.0  453.52  4296.3  449.95  4359.9  444.54
  4395.4  438.20  4444.8  435.22  4458.9  436.36  4529.7  435.77  4543.8  434.38
  4614.6  434.31  4635.7  431.99  4670.9  432.19  4971.7  430.99  5032.6  430.54
  5035.4  430.04  5038.6  430.54  5064.1  431.80  5078.5  431.29  5094.8  433.26
  5203.7  438.43  5221.0  441.80  5231.2  445.46  5255.7  447.37  5271.9  452.48
  5416.6  470.45  5434.9  471.47  5463.4  469.77  5468.5  470.98  5500.0  469.14
#Mann=6,-1,0
  4249.5    0.12       0  4670.9    0.16       0  4971.7    0.12       0
  5032.6    0.07       0  5038.6    0.12       0  5064.1    0.16       0
Bank Sta=5032.6,5038.6
Exp/Cntr=0.3,0.1

Type RM Length L Ch R = 1,16158,456,456,456
BEGIN DESCRIPTION:
LITTLE ALDER CREEK 33.0
END DESCRIPTION:
XS GIS Cut Line= 3
      3728399.61     10746310.20      3728599.61     10746710.19
      3728499.61     10747060.18
#Sta/Elev= 30
  4567.6  450.61  4570.4  450.61  4576.0  448.18  4589.9  446.77  4598.3  445.07
  4612.3  443.55  4626.3  441.43  4634.7  441.24  4643.1  439.33  4657.0  438.00
  4671.0  435.90  4679.4  435.32  4687.8  433.80  4710.1  430.87  4724.1  430.96
  4735.1  429.73  4737.8  429.23  4741.1  429.73  4751.3  429.73  5144.0  429.73
  5191.6  429.73  5202.0  430.09  5216.3  432.23  5243.6  434.49  5255.3  437.25
  5283.9  440.14  5289.1  442.23  5347.6  447.87  5368.4  449.56  5378.8  449.97
#Mann=5,-1,0
  4567.6    0.12       0  4735.1   0.033       0  4741.1    0.12       0
  4751.3    0.05       0  5144.0    0.12       0
Bank Sta=4735.1,4741.1
Exp/Cntr=0.3,0.1

Type RM Length L Ch R = 1,15702,455,455,455
BEGIN DESCRIPTION:
LITTLE ALDER CREEK 32.0
END DESCRIPTION:
XS GIS Cut Line= 3
      3728199.61     10746210.21      3728149.61     10746610.19
      3727949.63     10746810.17
#Sta/Elev= 30
  4619.5  470.19  4622.0  470.19  4629.6  468.51  4639.6  467.78  4649.7  466.03
  4662.3  466.20  4669.9  462.83  4690.0  459.23  4710.2  457.28  4720.3  454.83
  4730.3  453.73  4737.9  451.50  4742.9  451.82  4750.5  450.65  4770.6  447.31
  4780.7  444.75  4790.8  443.38  4800.9  440.91  4811.0  439.79  4818.5  437.33
  4823.5  438.06  4841.2  434.32  4868.4  429.73  4871.2  429.23  4874.4  429.73
  5143.3  429.73  5178.2  430.57  5220.6  436.59  5281.1  444.33  5305.4  446.22
#Mann=5,-1,0
  4619.5    0.12       0  4868.4   0.033       0  4874.4    0.12       0
  5143.3    0.16       0  5281.1    0.12       0
Bank Sta=4868.4,4874.4
Exp/Cntr=0.3,0.1

Type RM Length L Ch R = 1,15247,450,450,450
BEGIN DESCRIPTION:
LITTLE ALDER CREEK 31.0
END DESCRIPTION:
XS GIS Cut Line= 3
      3727699.61     10746260.18      3727699.61     10746610.19
      3727849.60     10746810.18
#Sta/Elev= 30
  4672.4  469.18  4702.4  466.91  4722.4  464.11  4742.4  459.51  4772.4  454.21
  4782.4  451.33  4792.4  450.00  4802.4  446.72  4812.4  445.32  4822.4  442.89
  4832.4  441.61  4842.4  438.78  4856.6  436.28  4862.4  434.88  4872.4  433.83
  4889.4  429.73  4892.2  429.23  4895.4  429.73  5144.3  429.73  5158.9  431.86
  5176.5  433.48  5179.7  434.05  5186.0  433.69  5192.1  434.09  5222.4  437.28
  5229.7  439.36  5236.0  440.19  5244.3  440.40  5265.1  443.75  5272.4  444.06
#Mann=6,-1,0
  4672.4    0.12       0  4856.6    0.05       0  4889.4   0.033       0
  4895.4    0.05       0  5176.5    0.16       0  5192.1    0.12       0
Bank Sta=4889.4,4895.4
Exp/Cntr=0.3,0.1

Type RM Length L Ch R = 1,14797,446,446,446
BEGIN DESCRIPTION:
LITTLE ALDER CREEK 30.0
END DESCRIPTION:
XS GIS Cut Line= 3
      3726899.64     10746460.21      3727299.61     10746760.19
      3727099.61     10747560.20
#Sta/Elev= 30
  4518.1  473.93  4589.9  463.85  4596.2  463.82  4696.2  447.69  4768.1  439.95
  4789.9  436.30  4825.4  432.94  4831.6  430.15  4851.5  429.73  4854.3  429.23
  4857.5  429.73  4878.4  429.73  5485.1  429.73  5530.9  430.43  5536.0  431.77
  5554.1  432.71  5595.3  438.23  5605.6  438.39  5626.2  441.12  5654.6  443.35
  5659.7  445.00  5667.5  444.50  5708.7  449.42  5737.0  450.92  5749.9  452.83
  5778.3  454.86  5783.4  456.44  5801.5  456.78  5819.5  460.01  5842.7  462.50
#Mann=5,-1,0
  4518.1    0.12       0  4851.5   0.033       0  4857.5    0.12       0
  4878.4    0.05       0  5485.1    0.12       0
Bank Sta=4851.5,4857.5
Exp/Cntr=0.3,0.1

Type RM Length L Ch R = 1,14351,661,661,661
BEGIN DESCRIPTION:
LITTLE ALDER CREEK 29.0
END DESCRIPTION:
XS GIS Cut Line= 3
      3726799.62     10746560.22      3726899.61     10746960.19
      3726899.61     10747310.21
#Sta/Elev= 30
  4613.0  475.82  4623.3  474.99  4628.4  473.25  4631.0  472.36  4643.9  471.41
  4654.2  469.26  4664.5  468.18  4672.2  465.66  4705.7  460.05  4713.5  457.39
  4747.0  450.56  4754.7  447.21  4762.4  445.58  4777.9  440.92  4788.2  439.40
  4801.1  434.81  4808.8  433.75  4816.1  429.73  4818.9  429.23  4822.1  429.73
  4864.4  429.73  5156.9  429.73  5215.3  429.73  5225.3  433.06  5265.3  438.76
  5285.3  440.26  5295.3  443.52  5315.3  446.53  5355.3  450.81  5375.3  452.19
#Mann=7,-1,0
  4613.0    0.16       0  4628.4    0.12       0  4762.4    0.16       0
  4816.1   0.033       0  4822.1    0.16       0  4864.4    0.05       0
  5156.9    0.12       0
Bank Sta=4816.1,4822.1
Exp/Cntr=0.3,0.1

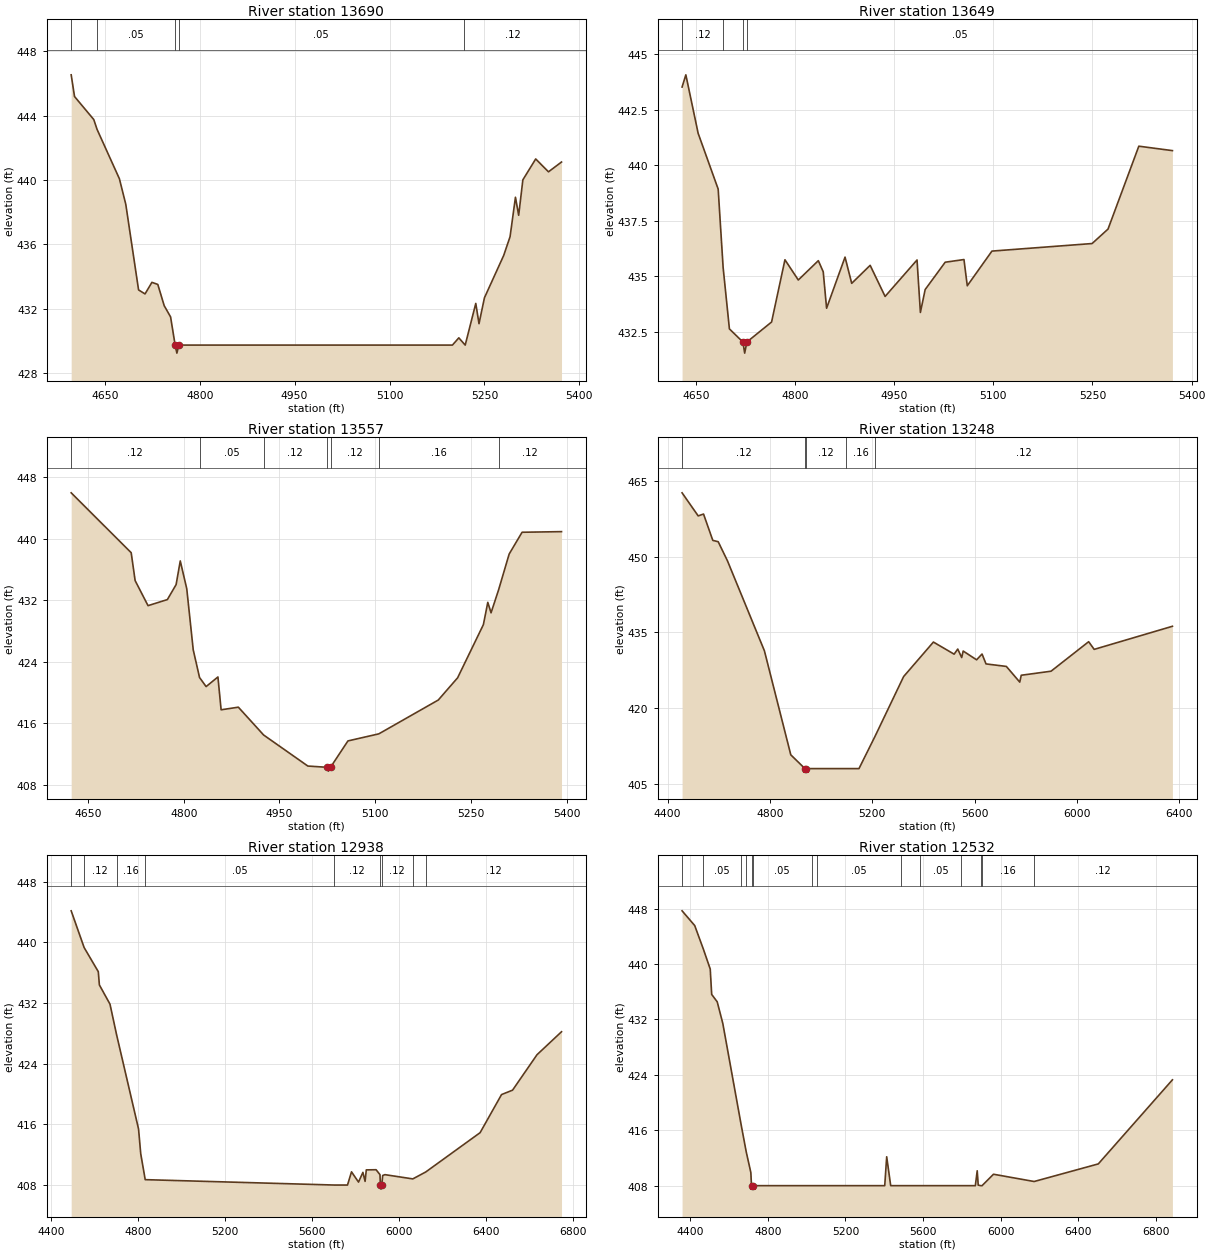
Type RM Length L Ch R = 1,13690,41,41,41
BEGIN DESCRIPTION:
LITTLE ALDER CREEK 28.0
END DESCRIPTION:
XS GIS Cut Line= 2
      3726185.54     10746664.94      3726305.32     10747430.52
#Sta/Elev= 30
  4596.9  446.53  4602.2  445.18  4632.6  443.75  4637.8  443.14  4673.1  440.07
  4683.2  438.48  4703.4  433.16  4713.6  432.91  4724.5  433.63  4733.8  433.50
  4743.9  432.18  4754.0  431.48  4761.2  429.73  4763.9  429.23  4767.2  429.73
  5199.4  429.73  5209.5  430.18  5216.9  429.85  5219.6  429.73  5236.3  432.32
  5241.4  431.06  5250.0  432.67  5280.4  435.30  5290.5  436.47  5299.0  438.92
  5304.1  437.80  5310.7  440.00  5331.0  441.30  5351.2  440.50  5371.8  441.11
#Mann=5,-1,0
  4596.9    0.12       0  4637.8    0.05       0  4761.2    0.04       0
  4767.2    0.05       0  5216.9    0.12       0
Bank Sta=4761.2,4767.2
Exp/Cntr=0.3,0.1

Type RM Length L Ch R = 1,13649,92,92,92
BEGIN DESCRIPTION:
Mapping XS ed73f1fe
END DESCRIPTION:
XS GIS Cut Line= 2
      3726154.28     10746696.15      3726258.45     10747430.50
#Sta/Elev= 30
  4629.2  443.51  4634.9  444.06  4653.5  441.43  4683.8  438.92  4691.3  435.39
  4700.8  432.63  4721.2  432.04  4723.9  431.54  4727.2  432.04  4764.6  432.94
  4784.8  435.74  4805.0  434.83  4835.3  435.70  4842.7  435.20  4847.8  433.56
  4875.7  435.86  4885.8  434.68  4913.7  435.49  4936.3  434.09  4984.6  435.73
  4989.7  433.37  4996.9  434.40  5027.2  435.63  5055.6  435.75  5060.6  434.57
  5097.9  436.13  5249.4  436.47  5273.5  437.12  5320.1  440.85  5370.9  440.65
#Mann=4,-1,0
  4629.2    0.12       0  4691.3    0.05       0  4721.2    0.04       0
  4727.2    0.05       0
Bank Sta=4721.2,4727.2
Exp/Cntr=0.3,0.1

Type RM Length L Ch R = 1,13557,309,309,309
BEGIN DESCRIPTION:
LITTLE ALDER CREEK 27.0
END DESCRIPTION:
XS GIS Cut Line= 2
      3726061.41     10746690.98      3726170.78     10747451.36
#Sta/Elev= 30
  4623.7  445.98  4717.7  438.19  4723.9  434.56  4744.1  431.30  4774.4  432.09
  4788.1  434.04  4794.6  437.12  4804.8  433.49  4814.9  425.56  4824.8  421.95
  4835.1  420.77  4853.6  422.02  4858.6  417.75  4885.6  418.09  4925.2  414.47
  4994.5  410.43  5024.0  410.27  5026.8  409.77  5030.0  410.27  5057.3  413.70
  5105.7  414.62  5198.8  419.02  5229.1  421.91  5269.5  428.83  5276.4  431.73
  5281.5  430.37  5293.3  433.35  5309.9  438.02  5330.1  440.85  5391.9  440.93
#Mann=7,-1,0
  4623.7    0.12       0  4824.8    0.05       0  4925.2    0.12       0
  5024.0    0.07       0  5030.0    0.12       0  5105.7    0.16       0
  5293.3    0.12       0
Bank Sta=5024,5030
Exp/Cntr=0.3,0.1

Type RM Length L Ch R = 1,13248,310,310,310
BEGIN DESCRIPTION:
LITTLE ALDER CREEK 26.0
END DESCRIPTION:
XS GIS Cut Line= 4
      3726000.65     10746574.97      3725800.99     10746878.80
      3725809.67     10747173.94      3726460.72     10748250.34
#Sta/Elev= 30
  4456.5  462.67  4519.4  458.10  4540.4  458.46  4576.6  453.24  4597.7  452.98
  4633.8  449.20  4778.4  431.34  4881.5  410.72  4936.8  407.99  4939.5  407.49
  4942.8  407.99  5097.0  407.99  5148.0  407.99  5210.8  414.39  5322.6  426.24
  5439.0  433.08  5520.0  430.68  5534.1  431.69  5549.6  430.01  5555.4  431.30
  5607.8  429.56  5629.1  430.71  5644.6  428.75  5724.2  428.25  5776.5  425.14
  5782.4  426.50  5898.8  427.30  6045.9  433.15  6067.5  431.63  6373.3  436.21
#Mann=5,-1,0
  4456.5    0.12       0  4936.8    0.07       0  4942.8    0.12       0
  5097.0    0.16       0  5210.8    0.12       0
Bank Sta=4936.8,4942.8
Exp/Cntr=0.3,0.1

Type RM Length L Ch R = 1,12938,406,406,406
BEGIN DESCRIPTION:
LITTLE ALDER CREEK 25.0
END DESCRIPTION:
XS GIS Cut Line= 3
      3725572.79     10746513.58      3725482.52     10747135.09
      3725732.52     10748742.74
#Sta/Elev= 30
  4493.7  444.18  4553.3  439.33  4618.4  436.15  4623.4  434.40  4672.2  431.86
  4702.2  427.87  4803.5  415.39  4813.6  412.11  4834.2  408.70  5703.0  407.99
  5764.5  407.99  5782.9  409.73  5815.1  408.38  5835.3  409.66  5845.4  408.47
  5850.9  409.99  5896.0  410.01  5913.8  409.36  5915.8  407.95  5918.6  407.45
  5921.8  407.95  5926.4  409.25  5936.5  409.36  6064.9  408.80  6124.6  409.72
  6374.3  414.90  6472.9  419.93  6523.5  420.51  6636.0  425.19  6748.7  428.22
#Mann=9,-1,0
  4493.7    0.05       0  4553.3    0.12       0  4702.2    0.16       0
  4834.2    0.05       0  5703.0    0.12       0  5915.8   0.033       0
  5921.8    0.12       0  6064.9    0.16       0  6124.6    0.12       0
Bank Sta=5915.8,5921.8
Exp/Cntr=0.3,0.1

Type RM Length L Ch R = 1,12532,148,148,148
BEGIN DESCRIPTION:
Mapping XS 00bac5d8
END DESCRIPTION:
XS GIS Cut Line= 4
      3725409.33     10746388.99      3725117.67     10746831.71
      3725039.54     10747357.75      3725435.00     10748767.88
#Sta/Elev= 30
  4358.4  447.67  4423.6  445.54  4468.1  442.14  4503.5  439.26  4511.0  435.60
  4539.5  434.53  4568.2  431.42  4663.3  416.70  4689.1  412.85  4712.7  409.89
  4716.1  407.99  4718.8  407.49  4722.1  407.99  5025.7  407.99  5054.7  407.99
  5402.6  407.99  5412.7  412.16  5433.3  407.99  5485.8  407.99  5586.1  407.99
  5794.5  407.99  5869.5  407.99  5879.1  410.14  5884.3  408.07  5897.4  407.99
  5904.2  407.99  5963.0  409.64  6172.5  408.59  6503.0  411.13  6884.9  423.27
#Mann=14,-1,0
  4358.4    0.16       0  4468.1    0.05       0  4663.3    0.16       0
  4689.1    0.05       0  4716.1   0.033       0  4722.1    0.05       0
  5025.7    0.16       0  5054.7    0.05       0  5485.8    0.16       0
  5586.1    0.05       0  5794.5    0.16       0  5897.4    0.05       0
  5904.2    0.16       0  6172.5    0.12       0
Bank Sta=4716.1,4722.1
Exp/Cntr=0.3,0.1

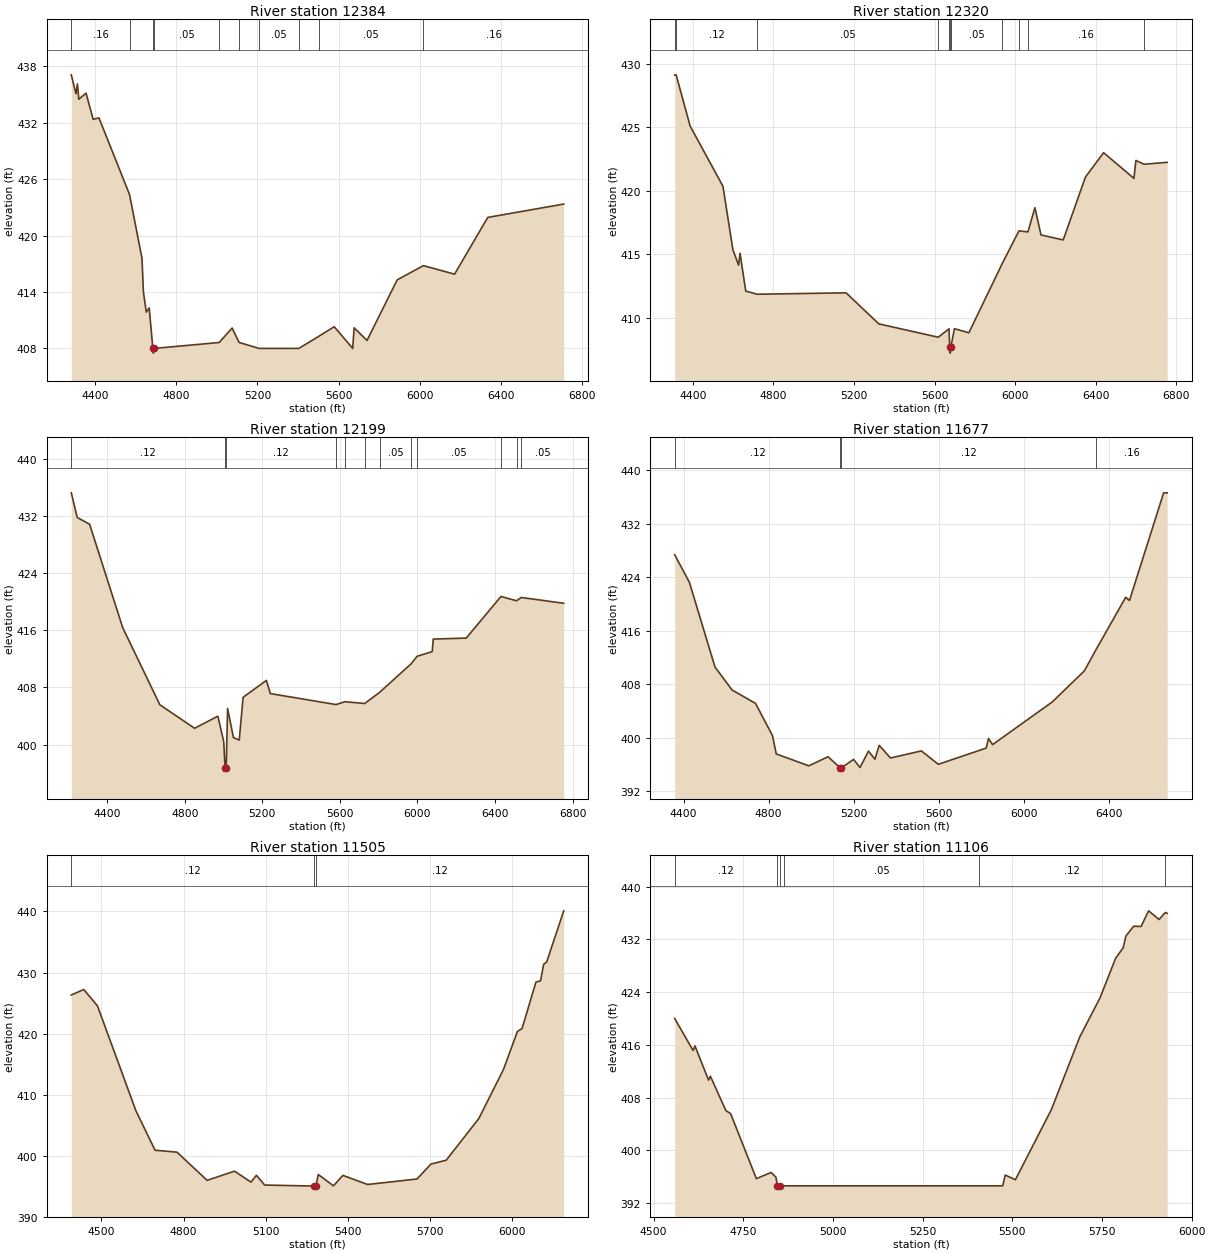
Type RM Length L Ch R = 1,12384,64,64,64
BEGIN DESCRIPTION:
Mapping XS 31b359ef
END DESCRIPTION:
XS GIS Cut Line= 5
      3725277.66     10746315.64      3724982.52     10746631.62
      3724916.54     10747322.59      3725031.13     10748124.67
      3725051.96     10748614.21
#Sta/Elev= 30
  4282.6  437.10  4305.5  435.08  4312.9  436.14  4319.7  434.50  4355.4  435.15
  4390.5  432.36  4418.9  432.52  4569.5  424.37  4630.9  417.59  4638.2  413.96
  4652.4  411.85  4666.5  412.30  4684.6  407.99  4687.3  407.49  4690.6  407.99
  5011.3  408.62  5075.2  410.16  5109.4  408.63  5207.5  407.99  5403.8  407.99
  5503.2  409.29  5578.4  410.30  5669.3  407.99  5676.3  410.18  5740.0  408.84
  5888.4  415.28  6017.6  416.80  6171.3  415.89  6334.9  421.93  6709.3  423.35
#Mann=10,-1,0
  4282.6    0.16       0  4569.5    0.05       0  4684.6   0.035       0
  4690.6    0.05       0  5011.3    0.12       0  5109.4    0.16       0
  5207.5    0.05       0  5403.8    0.16       0  5503.2    0.05       0
  6017.6    0.16       0
Bank Sta=4684.6,4690.6
Exp/Cntr=0.3,0.1

Type RM Length L Ch R = 1,12320,121,121,121
BEGIN DESCRIPTION:
Mapping XS 5ea6d81d
END DESCRIPTION:
XS GIS Cut Line= 6
      3725183.87     10746326.09      3724920.02     10746589.95
      3724843.63     10747169.81      3724843.63     10747374.67
      3724979.04     10747992.73      3725013.77     10748635.10
#Sta/Elev= 30
  4310.7  429.10  4317.7  429.12  4387.3  425.09  4550.0  420.36  4599.5  415.36
  4627.7  414.16  4634.8  415.10  4663.1  412.12  4719.8  411.87  5160.9  411.98
  5323.5  409.54  5618.1  408.49  5671.7  409.15  5675.0  407.74  5677.8  407.24
  5681.0  407.74  5698.5  409.16  5770.2  408.84  5934.7  414.25  6018.5  416.85
  6063.1  416.77  6097.8  418.67  6128.2  416.53  6238.3  416.14  6348.5  421.08
  6438.6  423.00  6589.1  420.98  6598.9  422.39  6639.0  422.09  6754.0  422.24
#Mann=11,-1,0
  4310.7    0.16       0  4317.7    0.12       0  4719.8    0.05       0
  5618.1    0.16       0  5671.7    0.05       0  5675.0    0.04       0
  5681.0    0.05       0  5934.7    0.16       0  6018.5    0.05       0
  6063.1    0.16       0  6639.0    0.05       0
Bank Sta=5675,5681
Exp/Cntr=0.3,0.1

Type RM Length L Ch R = 1,12199,522,522,522
BEGIN DESCRIPTION:
Mapping XS eaef5312
END DESCRIPTION:
XS GIS Cut Line= 5
      3725114.47     10746221.89      3724788.07     10746617.73
      3724749.88     10747280.92      3724923.49     10748030.92
      3724972.10     10748621.24
#Sta/Elev= 30
  4214.7  435.28  4245.4  431.82  4309.2  430.88  4479.9  416.38  4671.5  405.57
  4850.4  402.28  4970.6  403.97  5000.7  400.42  5007.7  396.77  5010.4  396.27
  5013.7  396.77  5020.7  405.06  5050.8  400.98  5080.8  400.62  5100.8  406.62
  5221.0  408.99  5241.1  407.14  5579.8  405.60  5626.1  406.00  5727.6  405.75
  5804.2  407.30  5967.9  411.33  5998.1  412.37  6076.0  413.02  6081.2  414.78
  6251.4  414.92  6430.5  420.75  6510.9  420.15  6535.0  420.61  6754.2  419.80
#Mann=12,-1,0
  4214.7    0.12       0  5007.7    0.07       0  5013.7    0.12       0
  5579.8    0.05       0  5626.1    0.16       0  5727.6    0.12       0
  5804.2    0.05       0  5967.9    0.16       0  5998.1    0.05       0
  6430.5    0.08       0  6510.9    0.16       0  6535.0    0.05       0
Bank Sta=5007.7,5013.7
Exp/Cntr=0.3,0.1

Type RM Length L Ch R = 1,11677,172,172,172
BEGIN DESCRIPTION:
LITTLE ALDER CREEK 24.0
END DESCRIPTION:
XS GIS Cut Line= 3
      3724218.63     10746291.34      3724301.96     10747398.98
      3723874.80     10748525.76
#Sta/Elev= 30
  4358.5  427.35  4427.5  423.24  4547.9  410.59  4628.1  407.16  4738.4  405.16
  4818.6  400.32  4835.9  397.61  4989.1  395.83  5079.4  397.19  5136.5  395.54
  5139.3  395.04  5142.5  395.54  5199.7  396.79  5229.8  395.58  5269.9  398.03
  5300.0  396.82  5320.1  398.89  5373.3  397.00  5518.4  398.06  5598.2  396.06
  5823.3  398.48  5834.2  399.91  5853.5  399.00  6133.6  405.36  6284.3  409.99
  6341.2  413.26  6479.3  421.00  6497.2  420.53  6657.6  436.59  6674.3  436.60
#Mann=4,-1,0
  4358.5    0.12       0  5136.5    0.07       0  5142.5    0.12       0
  6341.2    0.16       0
Bank Sta=5136.5,5142.5
Exp/Cntr=0.3,0.1

Type RM Length L Ch R = 1,11505,399,399,399
BEGIN DESCRIPTION:
LITTLE ALDER CREEK 23.0
END DESCRIPTION:
XS GIS Cut Line= 3
      3724073.56     10746314.57      3724099.60     10747061.09
      3723640.05     10748006.21
#Sta/Elev= 30
  4389.9  426.33  4435.5  427.23  4485.6  424.54  4625.7  407.39  4695.7  400.92
  4775.8  400.60  4885.8  395.99  4985.9  397.49  5045.9  395.70  5065.9  396.81
  5095.9  395.22  5277.2  395.05  5279.9  394.55  5283.2  395.05  5291.5  396.95
  5347.1  395.09  5381.5  396.80  5471.7  395.31  5652.2  396.21  5703.0  398.65
  5758.6  399.28  5877.7  406.10  5967.9  414.15  6018.6  420.35  6035.6  420.84
  6086.2  428.43  6103.2  428.66  6114.4  431.36  6125.5  431.73  6187.8  440.11
#Mann=3,-1,0
  4389.9    0.12       0  5277.2    0.07       0  5283.2    0.12       0
Bank Sta=5277.2,5283.2
Exp/Cntr=0.3,0.1

Type RM Length L Ch R = 1,11106,505,505,505
BEGIN DESCRIPTION:
LITTLE ALDER CREEK 22.0
END DESCRIPTION:
XS GIS Cut Line= 3
      3723612.62     10746558.12      3723730.67     10747078.97
      3723230.65     10747752.62
#Sta/Elev= 30
  4558.7  420.00  4610.0  415.14  4615.1  415.85  4653.1  410.65  4658.2  411.24
  4701.3  406.03  4714.6  405.56  4786.4  395.69  4827.4  396.63  4841.0  395.91
  4844.9  394.60  4847.7  394.10  4850.9  394.60  4864.0  394.60  5406.3  394.60
  5473.1  394.60  5480.3  396.24  5508.5  395.52  5608.7  406.16  5688.0  417.20
  5744.3  423.11  5788.1  429.16  5809.0  430.73  5816.6  432.52  5838.2  434.01
  5859.1  433.98  5879.9  436.35  5909.1  435.04  5926.6  436.10  5931.7  435.96
#Mann=6,-1,0
  4558.7    0.12       0  4844.9   0.033       0  4850.9    0.12       0
  4864.0    0.05       0  5406.3    0.12       0  5926.6    0.16       0
Bank Sta=4844.9,4850.9
Exp/Cntr=0.3,0.1

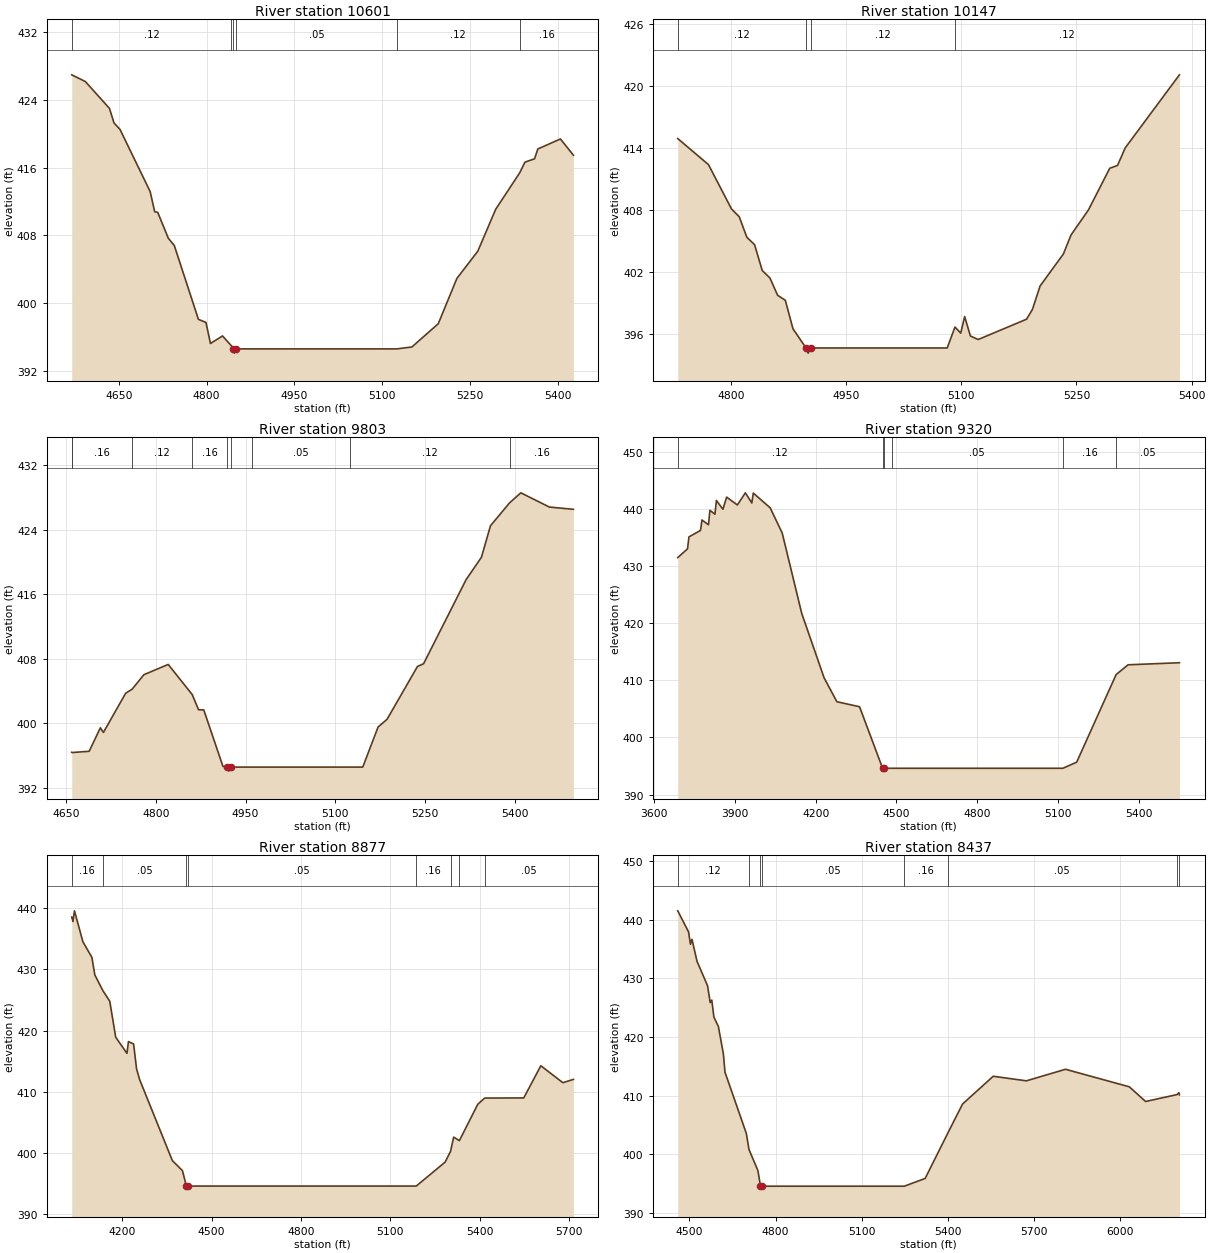
Type RM Length L Ch R = 1,10601,454,454,454
BEGIN DESCRIPTION:
LITTLE ALDER CREEK 21.0
END DESCRIPTION:
XS GIS Cut Line= 3
      3723349.62     10746510.15      3723249.61     10746910.19
      3723044.57     10747305.19
#Sta/Elev= 30
  4569.5  426.98  4592.7  426.19  4634.0  423.01  4641.7  421.30  4652.0  420.53
  4703.5  413.19  4711.3  410.80  4716.4  410.74  4734.5  407.68  4744.8  406.81
  4786.0  398.09  4798.9  397.73  4806.6  395.24  4827.2  396.13  4842.4  394.96
  4844.8  394.60  4847.6  394.10  4850.8  394.60  5125.1  394.60  5150.9  394.83
  5195.9  397.57  5227.8  402.93  5263.5  406.14  5294.1  411.10  5335.2  415.41
  5344.0  416.66  5360.5  417.06  5366.1  418.22  5404.7  419.40  5426.9  417.49
#Mann=6,-1,0
  4569.5    0.12       0  4842.4    0.05       0  4844.8   0.033       0
  4850.8    0.05       0  5125.1    0.12       0  5335.2    0.16       0
Bank Sta=4844.8,4850.8
Exp/Cntr=0.3,0.1

Type RM Length L Ch R = 1,10147,344,344,344
BEGIN DESCRIPTION:
LITTLE ALDER CREEK 20.0
END DESCRIPTION:
XS GIS Cut Line= 3
      3722799.61     10746610.17      3722799.61     10746860.19
      3722749.61     10747260.15
#Sta/Elev= 30
  4731.0  414.91  4771.0  412.38  4801.0  408.08  4811.0  407.33  4821.0  405.33
  4831.0  404.62  4841.0  402.11  4851.0  401.39  4861.0  399.71  4871.0  399.23
  4881.0  396.46  4898.0  394.60  4900.8  394.10  4904.0  394.60  5081.8  394.60
  5091.9  396.63  5099.4  396.04  5104.5  397.65  5112.0  395.76  5122.1  395.42
  5185.1  397.39  5192.7  398.33  5202.7  400.61  5233.0  403.71  5243.0  405.56
  5265.7  407.99  5293.4  412.03  5303.5  412.30  5313.6  414.01  5384.1  421.09
#Mann=4,-1,0
  4731.0    0.12       0  4898.0   0.033       0  4904.0    0.12       0
  5091.9    0.12       0
Bank Sta=4898,4904
Exp/Cntr=0.3,0.1

Type RM Length L Ch R = 1,9803,483,483,483
BEGIN DESCRIPTION:
LITTLE ALDER CREEK 19.0
END DESCRIPTION:
XS GIS Cut Line= 2
      3722405.68     10746631.57      3722551.28     10747456.62
#Sta/Elev= 30
  4659.7  396.43  4660.4  396.40  4688.8  396.56  4707.5  399.46  4712.6  398.89
  4749.7  403.74  4760.6  404.25  4780.2  406.04  4820.8  407.31  4860.8  403.59
  4871.5  401.70  4880.2  401.68  4912.2  394.69  4919.3  394.60  4922.1  394.10
  4925.3  394.60  4959.9  394.60  5123.8  394.60  5145.7  394.60  5171.3  399.56
  5186.3  400.52  5237.1  407.06  5247.3  407.40  5318.3  417.81  5343.9  420.58
  5359.0  424.48  5390.9  427.32  5409.7  428.56  5457.3  426.80  5497.5  426.52
#Mann=9,-1,0
  4659.7    0.05       0  4660.4    0.16       0  4760.6    0.12       0
  4860.8    0.16       0  4919.3   0.033       0  4925.3    0.16       0
  4959.9    0.05       0  5123.8    0.12       0  5390.9    0.16       0
Bank Sta=4919.3,4925.3
Exp/Cntr=0.3,0.1

Type RM Length L Ch R = 1,9320,443,443,443
BEGIN DESCRIPTION:
LITTLE ALDER CREEK 18.0
END DESCRIPTION:
XS GIS Cut Line= 3
      3721521.07     10745671.70      3721999.61     10746860.19
      3722057.06     10747440.04
#Sta/Elev= 30
  3687.7  431.52  3723.9  433.04  3729.3  435.14  3772.2  436.27  3777.6  438.10
  3801.8  437.27  3807.2  439.79  3825.9  439.11  3831.3  441.52  3855.5  439.99
  3869.3  442.11  3909.2  440.73  3938.8  442.86  3962.9  441.08  3968.3  442.82
  4031.0  440.24  4075.8  435.82  4148.3  421.73  4231.6  410.43  4279.0  406.26
  4363.2  405.38  4448.8  394.60  4451.6  394.10  4454.8  394.60  4482.5  394.60
  5118.7  394.60  5169.9  395.67  5316.5  411.02  5360.8  412.73  5551.6  413.09
#Mann=6,-1,0
  3687.7    0.12       0  4448.8   0.033       0  4454.8    0.12       0
  4482.5    0.05       0  5118.7    0.16       0  5316.5    0.05       0
Bank Sta=4448.8,4454.8
Exp/Cntr=0.3,0.1

Type RM Length L Ch R = 1,8877,440,440,440
BEGIN DESCRIPTION:
LITTLE ALDER CREEK 17.0
END DESCRIPTION:
XS GIS Cut Line= 4
      3720662.11     10746684.87      3721516.26     10746731.75
      3721604.81     10746893.21      3721922.37     10747455.44
#Sta/Elev= 30
  4029.9  438.55  4034.0  437.82  4039.0  439.57  4067.5  434.50  4097.5  431.98
  4107.5  429.09  4134.5  426.53  4157.6  424.80  4177.6  418.92  4215.4  416.28
  4220.4  418.20  4237.7  417.82  4247.7  413.73  4257.7  412.03  4367.9  398.76
  4401.8  397.12  4415.0  394.60  4417.7  394.10  4421.0  394.60  5187.2  394.60
  5284.2  398.51  5302.3  400.25  5313.0  402.60  5332.1  402.02  5393.9  407.96
  5417.3  408.98  5548.4  409.00  5605.8  414.26  5679.8  411.49  5715.2  412.03
#Mann=8,-1,0
  4029.9    0.16       0  4134.5    0.05       0  4415.0   0.033       0
  4421.0    0.05       0  5187.2    0.16       0  5302.3    0.05       0
  5332.1    0.16       0  5417.3    0.05       0
Bank Sta=4415,4421
Exp/Cntr=0.3,0.1

Type RM Length L Ch R = 1,8437,487,487,487
BEGIN DESCRIPTION:
LITTLE ALDER CREEK 16.0
END DESCRIPTION:
XS GIS Cut Line= 3
      3720815.44     10746916.32      3721537.62     10747249.63
      3722308.49     10747805.21
#Sta/Elev= 30
  4459.8  441.49  4497.4  437.90  4503.9  435.80  4509.4  436.65  4526.8  432.90
  4563.5  428.73  4572.7  425.87  4578.2  426.29  4585.5  423.41  4601.2  421.78
  4618.6  417.12  4624.1  414.02  4698.5  403.58  4707.6  400.85  4738.8  397.25
  4747.7  394.60  4750.5  394.10  4753.7  394.60  5248.1  394.60  5320.7  395.92
  5398.7  403.56  5450.8  408.59  5557.5  413.32  5672.9  412.54  5809.1  414.51
  6031.2  411.52  6087.7  409.02  6197.1  410.20  6203.4  410.52  6205.4  410.17
#Mann=8,-1,0
  4459.8    0.12       0  4707.6    0.05       0  4747.7   0.033       0
  4753.7    0.05       0  5248.1    0.16       0  5398.7    0.05       0
  6197.1    0.16       0  6203.4    0.12       0
Bank Sta=4747.7,4753.7
Exp/Cntr=0.3,0.1

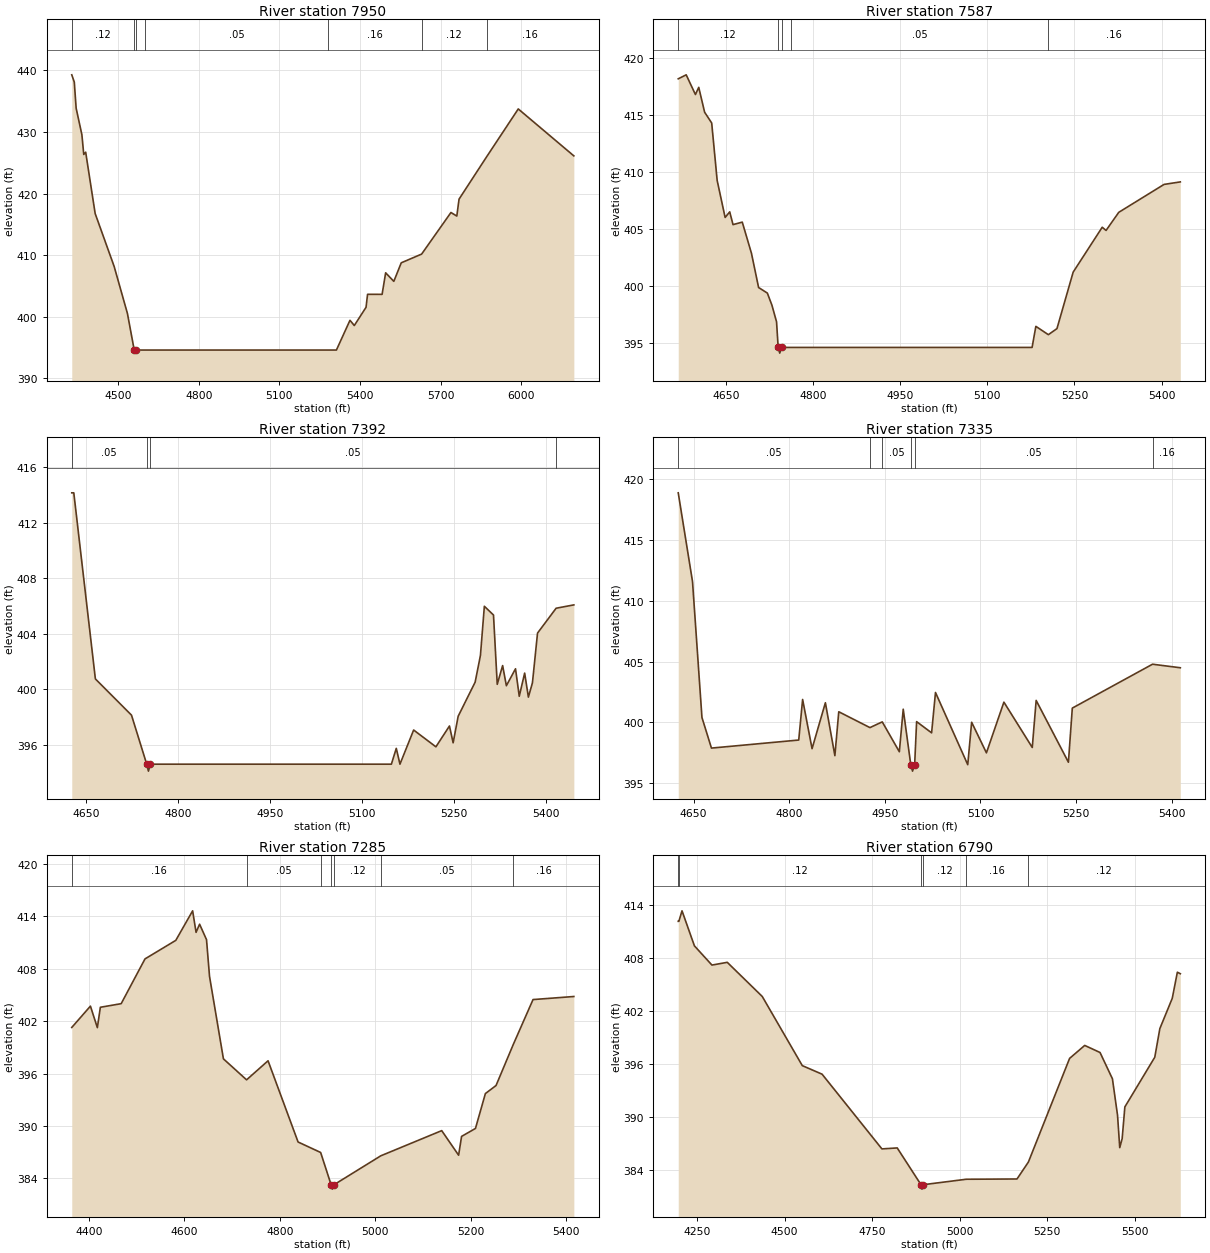
Type RM Length L Ch R = 1,7950,363,363,363
BEGIN DESCRIPTION:
LITTLE ALDER CREEK 15.0
END DESCRIPTION:
XS GIS Cut Line= 3
      3720711.20     10747145.44      3721433.46     10747839.91
      3722194.70     10748255.14
#Sta/Elev= 30
  4327.1  439.28  4336.5  438.10  4343.4  433.86  4364.8  429.55  4371.7  426.35
  4378.9  426.72  4414.2  416.76  4484.9  408.17  4534.3  400.54  4559.6  394.60
  4562.4  394.10  4565.6  394.60  4600.7  394.60  5282.4  394.60  5312.3  394.60
  5362.8  399.43  5378.9  398.58  5422.6  401.54  5428.3  403.65  5482.4  403.64
  5495.6  407.14  5526.0  405.75  5553.6  408.76  5629.6  410.18  5738.7  416.93
  5760.5  416.35  5768.9  419.10  5871.6  425.98  5989.3  433.74  6196.2  426.12
#Mann=7,-1,0
  4327.1    0.12       0  4559.6   0.033       0  4565.6    0.12       0
  4600.7    0.05       0  5282.4    0.16       0  5629.6    0.12       0
  5871.6    0.16       0
Bank Sta=4559.6,4565.6
Exp/Cntr=0.3,0.1

Type RM Length L Ch R = 1,7587,195,195,195
BEGIN DESCRIPTION:
LITTLE ALDER CREEK 14.0
END DESCRIPTION:
XS GIS Cut Line= 3
      3720649.57     10747710.17      3720999.61     10747910.19
      3721349.58     10748210.17
#Sta/Elev= 30
  4568.1  418.18  4581.8  418.53  4597.7  416.80  4603.4  417.43  4613.5  415.25
  4625.7  414.30  4635.1  409.26  4648.8  406.01  4656.7  406.50  4662.4  405.38
  4678.3  405.60  4694.1  402.87  4706.4  399.86  4721.5  399.37  4729.4  398.30
  4737.3  396.85  4740.1  394.60  4742.8  394.10  4746.1  394.60  4763.0  394.60
  5177.1  394.60  5183.6  396.45  5205.1  395.72  5219.9  396.25  5247.8  401.21
  5297.8  405.15  5304.4  404.87  5326.3  406.46  5404.2  408.91  5432.2  409.13
#Mann=5,-1,0
  4568.1    0.12       0  4740.1   0.033       0  4746.1    0.12       0
  4763.0    0.05       0  5205.1    0.16       0
Bank Sta=4740.1,4746.1
Exp/Cntr=0.3,0.1

Type RM Length L Ch R = 1,7392,57,57,57
BEGIN DESCRIPTION:
Mapping XS 9d0b52c4
END DESCRIPTION:
XS GIS Cut Line= 2
      3720675.42     10747759.69      3721136.68     10748435.97
#Sta/Elev= 30
  4627.1  414.14  4630.4  414.14  4665.6  400.74  4724.5  398.13  4749.3  394.60
  4752.1  394.10  4755.3  394.60  5148.2  394.60  5156.2  395.74  5162.2  394.60
  5184.5  397.06  5220.8  395.85  5242.9  397.35  5248.9  396.14  5257.1  398.05
  5284.8  400.51  5293.4  402.43  5299.8  405.97  5314.7  405.34  5320.8  400.35
  5329.6  401.70  5335.7  400.25  5350.6  401.47  5356.7  399.49  5365.5  401.16
  5371.6  399.43  5378.2  400.46  5386.5  404.04  5416.8  405.83  5445.7  406.07
#Mann=4,-1,0
  4627.1    0.05       0  4749.3    0.04       0  4755.3    0.05       0
  5416.8    0.16       0
Bank Sta=4749.3,4755.3
Exp/Cntr=0.3,0.1

Type RM Length L Ch R = 1,7335,50,50,50
BEGIN DESCRIPTION:
Mapping XS 08a4a533
END DESCRIPTION:
XS GIS Cut Line= 2
      3720623.77     10747793.97      3721074.90     10748439.44
#Sta/Elev= 30
  4626.0  418.84  4648.4  411.56  4663.2  400.41  4678.1  397.90  4815.0  398.56
  4821.1  401.89  4835.9  397.85  4856.8  401.62  4871.7  397.28  4877.8  400.88
  4926.7  399.58  4946.0  400.05  4972.8  397.60  4978.9  401.09  4990.8  396.51
  4993.5  396.01  4996.8  396.51  4999.9  400.07  5023.4  399.15  5029.5  402.46
  5080.1  396.54  5086.2  400.02  5109.4  397.51  5136.8  401.67  5181.3  397.95
  5187.4  401.81  5238.0  396.74  5244.1  401.18  5369.9  404.78  5413.5  404.49
#Mann=6,-1,0
  4626.0    0.05       0  4926.7    0.12       0  4946.0    0.05       0
  4990.8    0.04       0  4996.8    0.05       0  5369.9    0.16       0
Bank Sta=4990.8,4996.8
Exp/Cntr=0.3,0.1

Type RM Length L Ch R = 1,7285,495,495,495
BEGIN DESCRIPTION:
LITTLE ALDER CREEK 13.0
END DESCRIPTION:
XS GIS Cut Line= 2
      3720411.74     10747623.02      3721048.91     10748459.85
#Sta/Elev= 30
  4364.2  401.27  4403.3  403.71  4417.8  401.25  4424.1  403.58  4467.7  403.99
  4517.6  409.11  4582.1  411.23  4617.4  414.61  4624.6  412.15  4632.0  413.08
  4646.5  411.31  4652.8  407.11  4681.9  397.68  4730.4  395.28  4775.4  397.46
  4838.3  388.17  4885.6  386.97  4907.5  383.28  4910.3  382.78  4913.5  383.28
  5011.6  386.59  5139.2  389.47  5174.6  386.66  5180.8  388.81  5209.9  389.72
  5230.7  393.71  5253.0  394.63  5289.1  399.32  5330.5  404.46  5416.0  404.81
#Mann=7,-1,0
  4364.2    0.16       0  4730.4    0.05       0  4885.6    0.12       0
  4907.5    0.07       0  4913.5    0.12       0  5011.6    0.05       0
  5289.1    0.16       0
Bank Sta=4907.5,4913.5
Exp/Cntr=0.3,0.1

Type RM Length L Ch R = 1,6790,414,414,414
BEGIN DESCRIPTION:
LITTLE ALDER CREEK 12.0
END DESCRIPTION:
XS GIS Cut Line= 2
      3719957.74     10747827.01      3720818.89     10748972.89
#Sta/Elev= 30
  4196.3  412.20  4198.1  412.20  4207.1  413.39  4242.5  409.42  4292.5  407.24
  4336.3  407.55  4436.2  403.68  4550.5  395.84  4607.0  394.87  4777.8  386.40
  4821.5  386.51  4889.4  382.34  4892.1  381.84  4895.4  382.34  5018.7  382.96
  5163.5  382.99  5196.0  384.91  5313.6  396.66  5356.8  398.13  5400.5  397.33
  5435.9  394.35  5450.5  390.21  5456.8  386.54  5463.7  387.57  5471.4  391.16
  5556.8  396.79  5571.3  400.04  5606.7  403.47  5621.3  406.43  5629.7  406.26
#Mann=6,-1,0
  4196.3    0.16       0  4198.1    0.12       0  4889.4    0.07       0
  4895.4    0.12       0  5018.7    0.16       0  5196.0    0.12       0
Bank Sta=4889.4,4895.4
Exp/Cntr=0.3,0.1