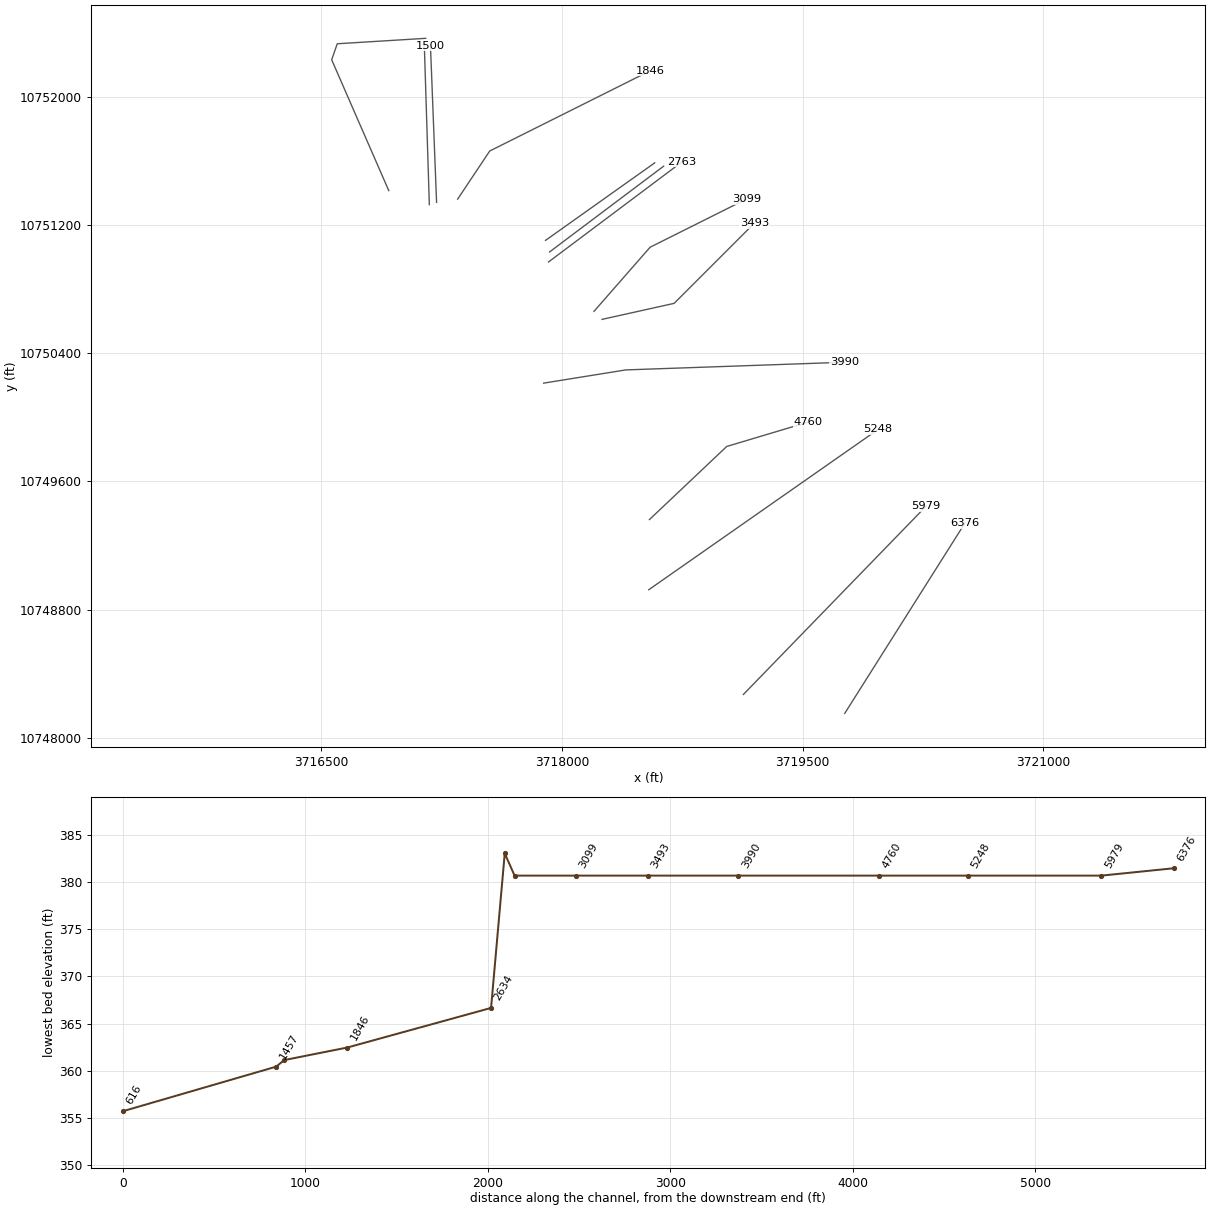
HEC-RAS study LITTLE ALDER CREEK.prj: LITTLE ALDER CREEK Base Level Engineering

--- LITTLE ALDER CREEK.g01 (geometry) --- (continued)

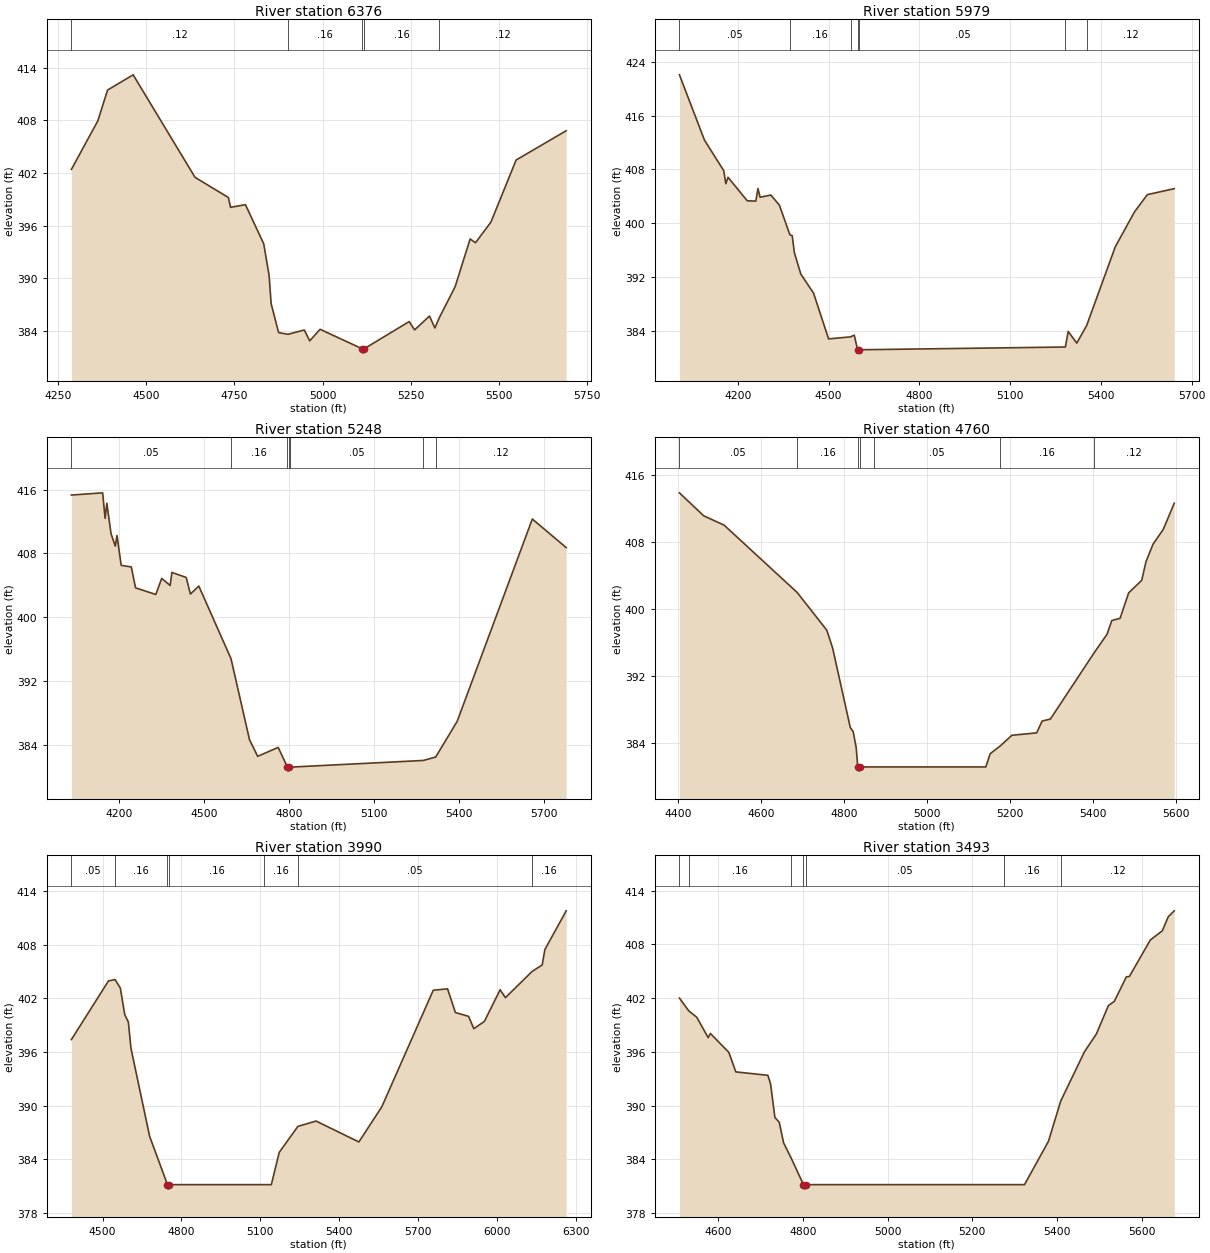
Type RM Length L Ch R = 1,6376,397,397,397
BEGIN DESCRIPTION:
LITTLE ALDER CREEK 11.0
END DESCRIPTION:
XS GIS Cut Line= 2
      3719763.30     10748153.40      3720513.30     10749340.89
#Sta/Elev= 30
  4287.1  402.41  4362.3  407.96  4389.7  411.46  4462.4  413.20  4638.1  401.50
  4732.7  399.20  4738.8  398.08  4781.2  398.38  4833.0  393.92  4848.2  390.33
  4854.1  387.08  4875.3  383.78  4901.9  383.59  4948.3  384.08  4963.5  382.84
  4993.0  384.16  5112.3  381.94  5115.1  381.44  5118.3  381.94  5245.9  385.04
  5261.2  384.09  5303.6  385.67  5318.9  384.31  5331.1  385.45  5376.5  389.04
  5418.9  394.47  5434.2  394.04  5477.9  396.39  5549.5  403.48  5691.6  406.82
#Mann=5,-1,0
  4287.1    0.12       0  4901.9    0.16       0  5112.3    0.07       0
  5118.3    0.16       0  5331.1    0.12       0
Bank Sta=5112.3,5118.3
Exp/Cntr=0.3,0.1

Type RM Length L Ch R = 1,5979,731,731,731
BEGIN DESCRIPTION:
LITTLE ALDER CREEK 10.0
END DESCRIPTION:
XS GIS Cut Line= 2
      3719131.38     10748271.49      3720270.29     10749445.12
#Sta/Elev= 30
  4007.1  422.08  4089.7  412.37  4153.5  407.81  4160.4  405.87  4167.6  406.83
  4231.2  403.33  4259.5  403.29  4266.6  405.16  4273.6  403.86  4309.1  404.19
  4337.4  402.69  4372.2  398.27  4379.8  398.14  4386.8  395.63  4408.1  392.44
  4450.5  389.57  4500.0  382.78  4573.0  383.08  4584.8  383.34  4596.0  381.16
  4598.7  380.66  4602.0  381.16  5282.5  381.57  5292.0  383.89  5320.3  382.15
  5352.9  384.76  5447.6  396.49  5511.1  401.68  5553.6  404.25  5642.5  405.14
#Mann=7,-1,0
  4007.1    0.05       0  4372.2    0.16       0  4573.0    0.05       0
  4596.0   0.033       0  4602.0    0.05       0  5282.5    0.16       0
  5352.9    0.12       0
Bank Sta=4596,4602
Exp/Cntr=0.3,0.1

Type RM Length L Ch R = 1,5248,488,488,488
BEGIN DESCRIPTION:
LITTLE ALDER CREEK 9.0
END DESCRIPTION:
XS GIS Cut Line= 2
      3718541.13     10748924.28      3719971.67     10749924.27
#Sta/Elev= 30
  4031.8  415.34  4142.0  415.62  4150.7  412.41  4156.8  414.31  4171.6  410.49
  4186.5  408.93  4192.6  410.26  4207.4  406.51  4243.1  406.31  4258.0  403.69
  4329.5  402.85  4350.4  404.87  4380.1  403.98  4386.2  405.62  4436.8  404.99
  4451.6  402.90  4481.2  403.91  4594.7  394.80  4660.0  384.62  4688.8  382.52
  4761.2  383.64  4793.9  381.16  4796.7  380.66  4799.9  381.16  4802.5  381.16
  5272.9  382.00  5316.8  382.43  5392.6  386.91  5657.7  412.33  5777.2  408.74
#Mann=7,-1,0
  4031.8    0.05       0  4594.7    0.16       0  4793.9   0.033       0
  4799.9    0.16       0  4802.5    0.05       0  5272.9    0.16       0
  5316.8    0.12       0
Bank Sta=4793.9,4799.9
Exp/Cntr=0.3,0.1

Type RM Length L Ch R = 1,4760,770,770,770
BEGIN DESCRIPTION:
LITTLE ALDER CREEK 8.0
END DESCRIPTION:
XS GIS Cut Line= 3
      3718545.53     10749361.98      3719027.30     10749817.70
      3719534.81     10749969.52
#Sta/Elev= 30
  4403.9  413.90  4462.2  411.16  4511.6  410.04  4687.5  402.01  4759.2  397.49
  4773.3  395.34  4815.8  385.86  4822.7  385.38  4830.0  383.47  4833.8  381.16
  4836.6  380.66  4839.8  381.16  4871.8  381.16  5142.5  381.16  5153.0  382.74
  5177.4  383.67  5205.2  384.94  5265.1  385.23  5278.2  386.64  5298.2  386.88
  5403.5  394.78  5434.8  397.01  5446.3  398.65  5466.1  398.91  5487.0  401.96
  5518.3  403.44  5528.7  405.68  5545.6  407.76  5570.5  409.55  5596.8  412.66
#Mann=7,-1,0
  4403.9    0.05       0  4687.5    0.16       0  4833.8   0.033       0
  4839.8    0.16       0  4871.8    0.05       0  5177.4    0.16       0
  5403.5    0.12       0
Bank Sta=4833.8,4839.8
Exp/Cntr=0.3,0.1

Type RM Length L Ch R = 1,3990,497,497,497
BEGIN DESCRIPTION:
LITTLE ALDER CREEK 7.0
END DESCRIPTION:
XS GIS Cut Line= 3
      3717885.79     10750212.67      3718397.96     10750295.13
      3719760.76     10750342.88
#Sta/Elev= 30
  4381.6  397.40  4522.7  403.97  4548.2  404.11  4567.8  403.16  4584.6  400.19
  4598.2  399.37  4608.3  396.41  4679.2  386.57  4747.1  381.16  4749.9  380.66
  4753.1  381.16  5113.7  381.16  5142.2  381.16  5172.2  384.77  5243.2  387.68
  5312.3  388.28  5475.3  385.94  5562.4  389.87  5758.2  402.92  5812.6  403.08
  5842.6  400.42  5892.6  400.00  5912.6  398.62  5952.7  399.43  6012.7  402.98
  6032.7  402.09  6133.4  405.00  6172.8  405.76  6182.8  407.47  6264.0  411.81
#Mann=7,-1,0
  4381.6    0.05       0  4548.2    0.16       0  4747.1   0.033       0
  4753.1    0.16       0  5113.7    0.16       0  5243.2    0.05       0
  6133.4    0.16       0
Bank Sta=4747.1,4753.1
Exp/Cntr=0.3,0.1

Type RM Length L Ch R = 1,3493,394,394,394
BEGIN DESCRIPTION:
LITTLE ALDER CREEK 6.0
END DESCRIPTION:
XS GIS Cut Line= 3
      3718249.65     10750610.20      3718699.61     10750710.19
      3719199.58     10751210.16
#Sta/Elev= 30
  4508.7  402.01  4530.4  400.60  4549.6  399.86  4576.5  397.59  4581.6  398.06
  4625.2  395.95  4641.8  393.76  4717.4  393.38  4723.8  392.42  4734.0  388.67
  4744.3  388.13  4754.5  385.84  4771.4  384.23  4801.5  381.16  4804.2  380.66
  4807.5  381.16  5273.8  381.16  5323.2  381.16  5379.8  386.01  5408.6  390.49
  5464.6  396.00  5492.9  398.00  5521.2  401.17  5535.3  401.65  5563.6  404.38
  5570.7  404.42  5620.2  408.50  5648.5  409.53  5662.6  411.10  5676.7  411.76
#Mann=7,-1,0
  4508.7    0.05       0  4530.4    0.16       0  4771.4    0.05       0
  4801.5   0.033       0  4807.5    0.05       0  5273.8    0.16       0
  5408.6    0.12       0
Bank Sta=4801.5,4807.5
Exp/Cntr=0.3,0.1

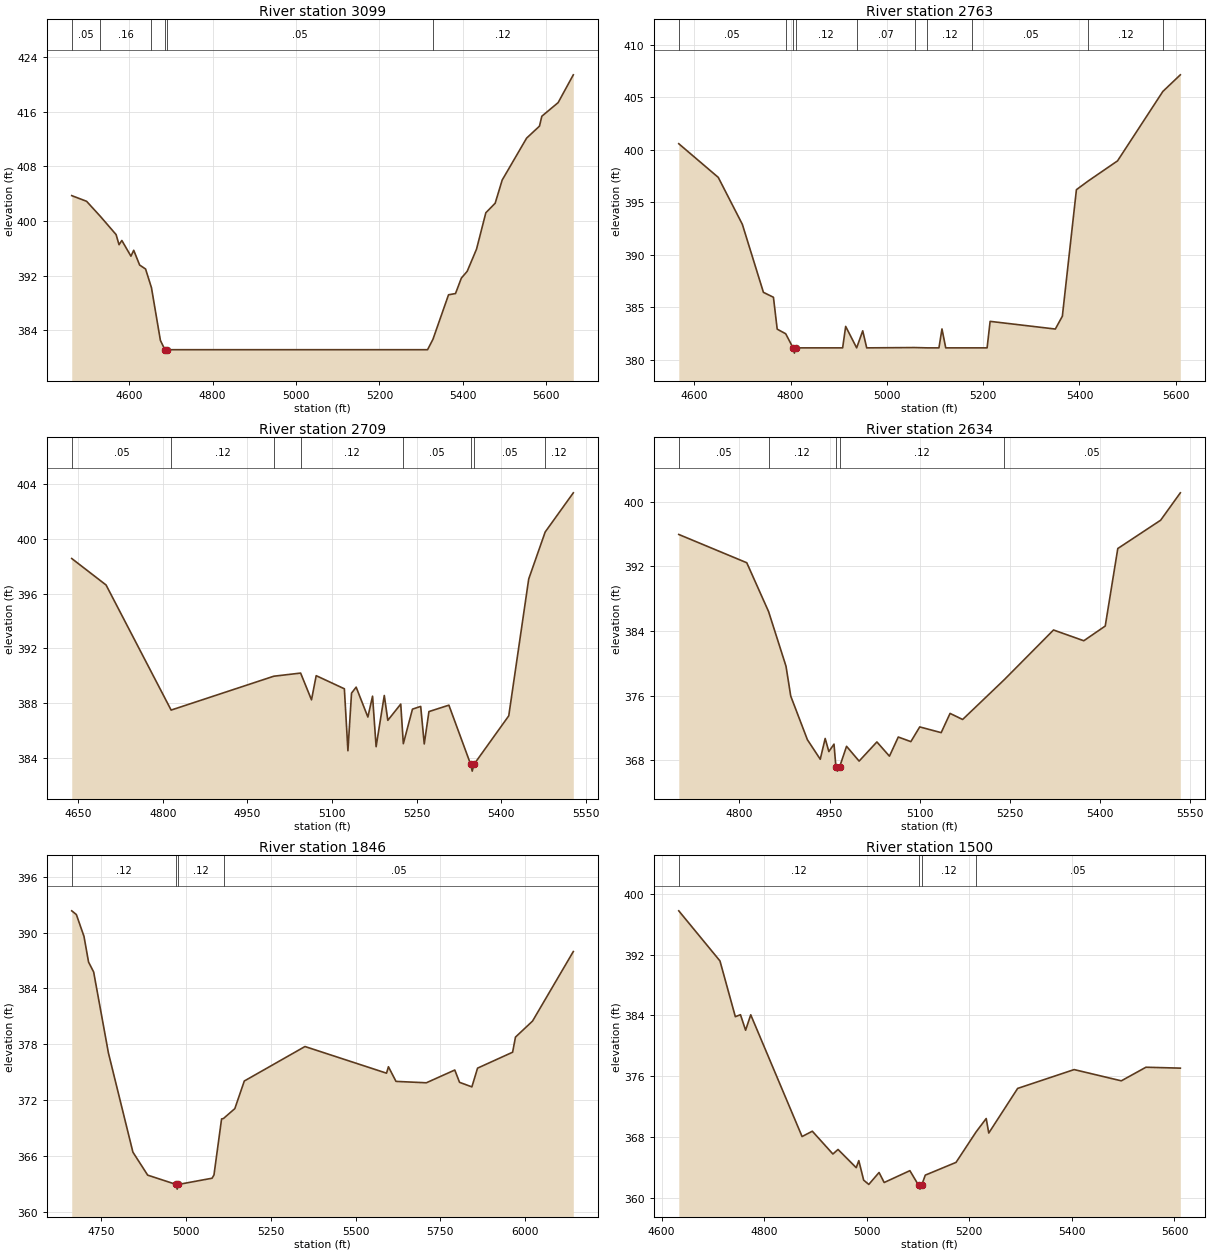
Type RM Length L Ch R = 1,3099,336,336,336
BEGIN DESCRIPTION:
LITTLE ALDER CREEK 5.0
END DESCRIPTION:
XS GIS Cut Line= 3
      3718199.59     10750660.17      3718549.61     10751060.19
      3719149.65     10751360.21
#Sta/Elev= 30
  4462.5  403.71  4498.1  402.88  4531.2  400.67  4568.8  398.01  4575.9  396.53
  4582.6  397.15  4604.4  394.85  4611.1  395.71  4625.3  393.55  4639.5  392.97
  4653.6  390.24  4675.1  382.51  4685.9  381.16  4688.6  380.66  4691.9  381.16
  5315.5  381.16  5328.4  382.68  5365.8  389.20  5382.5  389.38  5396.5  391.64
  5410.5  392.63  5432.9  395.88  5455.2  401.20  5477.6  402.60  5494.4  405.99
  5553.0  412.13  5583.8  413.88  5589.4  415.33  5628.5  417.32  5664.9  421.39
#Mann=6,-1,0
  4462.5    0.05       0  4531.2    0.16       0  4653.6    0.05       0
  4685.9   0.033       0  4691.9    0.05       0  5328.4    0.12       0
Bank Sta=4685.9,4691.9
Exp/Cntr=0.3,0.1

Type RM Length L Ch R = 1,2763,54,54,54
BEGIN DESCRIPTION:
LITTLE ALDER CREEK 4.0
END DESCRIPTION:
XS GIS Cut Line= 2
      3717916.06     10750968.19      3718749.34     10751593.15
#Sta/Elev= 30
  4567.9  400.57  4649.9  397.37  4699.9  392.91  4743.7  386.44  4764.5  385.97
  4772.3  382.94  4790.0  382.50  4805.2  381.16  4808.0  380.66  4811.2  381.16
  4908.2  381.16  4914.5  383.20  4937.3  381.16  4949.9  382.78  4958.2  381.16
  5057.6  381.19  5084.2  381.16  5108.2  381.16  5114.5  382.96  5122.3  381.16
  5177.8  381.16  5208.2  381.16  5214.5  383.68  5349.9  382.95  5364.5  384.17
  5393.7  396.20  5418.3  397.03  5479.1  398.94  5573.2  405.54  5609.5  407.12
#Mann=10,-1,0
  4567.9    0.05       0  4790.0    0.12       0  4805.2    0.07       0
  4811.2    0.12       0  4937.3    0.07       0  5057.6    0.05       0
  5084.2    0.12       0  5177.8    0.05       0  5418.3    0.12       0
  5573.2    0.07       0
Bank Sta=4805.2,4811.2
Exp/Cntr=0.3,0.1

Type RM Length L Ch R = 1,2709,75,75,75
BEGIN DESCRIPTION:
Mapping XS 50f475f1
END DESCRIPTION:
XS GIS Cut Line= 2
      3717922.95     10751030.88      3718634.09     10751565.53
#Sta/Elev= 30
  4638.3  398.58  4699.2  396.64  4814.6  387.48  4996.7  389.96  5044.3  390.19
  5063.6  388.23  5071.9  390.00  5121.9  389.04  5128.2  384.50  5134.6  388.72
  5142.8  389.16  5163.6  386.97  5171.9  388.50  5178.2  384.80  5192.7  388.55
  5199.0  386.73  5221.9  387.92  5226.5  385.02  5242.7  387.55  5257.3  387.75
  5263.6  385.00  5271.9  387.37  5307.3  387.84  5345.9  383.51  5348.7  383.01
  5351.9  383.51  5413.5  387.06  5448.9  397.08  5478.1  400.52  5528.0  403.39
#Mann=8,-1,0
  4638.3    0.05       0  4814.6    0.12       0  4996.7    0.07       0
  5044.3    0.12       0  5226.5    0.05       0  5345.9    0.07       0
  5351.9    0.05       0  5478.1    0.12       0
Bank Sta=5345.9,5351.9
Exp/Cntr=0.3,0.1

Type RM Length L Ch R = 1,2634,788,788,788
BEGIN DESCRIPTION:
LITTLE ALDER CREEK 3.0
END DESCRIPTION:
XS GIS Cut Line= 2
      3717897.60     10751102.95      3718578.38     10751586.26
#Sta/Elev= 30
  4699.1  395.94  4812.3  392.44  4848.6  386.40  4877.6  379.64  4885.5  375.94
  4913.2  370.55  4934.6  368.13  4942.8  370.70  4948.9  369.08  4957.5  370.00
  4960.7  367.16  4963.4  366.66  4966.7  367.16  4978.4  369.73  4999.3  367.90
  5028.9  370.27  5049.8  368.51  5064.5  370.88  5085.4  370.31  5100.2  372.13
  5135.9  371.42  5150.7  373.80  5171.6  373.05  5240.9  377.97  5322.9  384.12
  5373.3  382.79  5409.0  384.61  5429.9  394.20  5501.2  397.70  5534.0  401.09
#Mann=5,-1,0
  4699.1    0.05       0  4848.6    0.12       0  4960.7    0.07       0
  4966.7    0.12       0  5240.9    0.05       0
Bank Sta=4960.7,4966.7
Exp/Cntr=0.3,0.1

Type RM Length L Ch R = 1,1846,346,346,346
BEGIN DESCRIPTION:
LITTLE ALDER CREEK 2.0
END DESCRIPTION:
XS GIS Cut Line= 3
      3717349.59     10751360.15      3717549.61     10751660.19
      3718549.58     10752160.18
#Sta/Elev= 30
  4663.3  392.33  4676.9  391.93  4699.4  389.59  4712.9  386.83  4727.9  385.77
  4771.5  377.07  4843.6  366.44  4887.2  363.97  4971.3  362.97  4974.1  362.47
  4977.3  362.97  5077.0  363.64  5082.6  363.99  5105.0  370.00  5110.7  370.05
  5144.1  371.11  5172.0  374.07  5350.9  377.77  5591.3  374.91  5596.9  375.60
  5619.2  374.03  5708.7  373.88  5792.5  375.25  5806.5  373.93  5842.9  373.44
  5859.6  375.45  5963.0  377.16  5971.4  378.78  6021.7  380.50  6141.9  387.96
#Mann=4,-1,0
  4663.3    0.12       0  4971.3    0.07       0  4977.3    0.12       0
  5110.7    0.05       0
Bank Sta=4971.3,4977.3
Exp/Cntr=0.3,0.1

Type RM Length L Ch R = 1,1500,43,43,43
BEGIN DESCRIPTION:
Mapping XS c91e1541
END DESCRIPTION:
XS GIS Cut Line= 2
      3717218.11     10751339.95      3717180.00     10752317.11
#Sta/Elev= 30
  4633.5  397.76  4713.8  391.17  4743.8  383.83  4753.8  384.09  4763.8  382.05
  4773.8  384.08  4873.9  368.06  4893.9  368.76  4934.0  365.76  4944.0  366.36
  4979.5  363.96  4984.5  364.89  4994.0  362.32  5004.0  361.76  5024.0  363.33
  5034.0  362.01  5084.1  363.57  5101.1  361.64  5103.8  361.14  5107.1  361.64
  5114.1  362.98  5174.1  364.66  5213.1  368.66  5232.9  370.43  5237.9  368.52
  5294.2  374.39  5404.3  376.87  5496.3  375.39  5544.4  377.18  5611.4  377.06
#Mann=4,-1,0
  4633.5    0.12       0  5101.1    0.07       0  5107.1    0.12       0
  5213.1    0.05       0
Bank Sta=5101.1,5107.1
Exp/Cntr=0.3,0.1

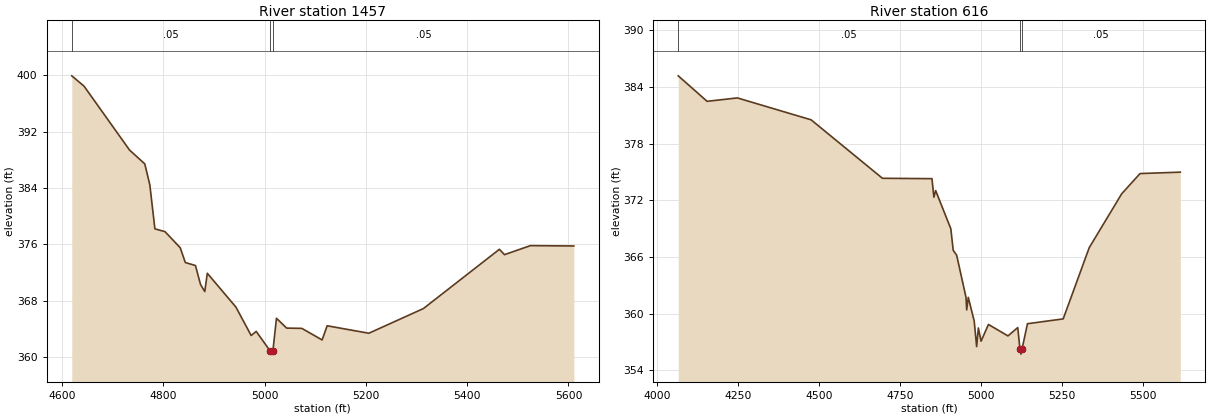
Type RM Length L Ch R = 1,1457,841,841,841
BEGIN DESCRIPTION:
Mapping XS 22f1cfcb
END DESCRIPTION:
XS GIS Cut Line= 2
      3717172.98     10751326.04      3717141.79     10752317.15
#Sta/Elev= 30
  4619.0  399.90  4643.2  398.44  4733.2  389.37  4763.2  387.42  4773.2  384.43
  4783.2  378.21  4803.2  377.81  4833.2  375.53  4843.3  373.43  4863.3  373.01
  4873.3  370.32  4881.7  369.32  4886.7  371.91  4943.3  367.11  4973.3  363.09
  4983.3  363.67  5010.3  360.95  5013.1  360.45  5016.3  360.95  5023.3  365.53
  5043.4  364.14  5073.4  364.10  5113.4  362.46  5123.4  364.47  5205.7  363.41
  5313.5  366.91  5463.6  375.31  5473.6  374.55  5524.8  375.83  5610.6  375.78
#Mann=3,-1,0
  4619.0    0.05       0  5010.3    0.04       0  5016.3    0.05       0
Bank Sta=5010.3,5016.3
Exp/Cntr=0.3,0.1

Type RM Length L Ch R = 1,616,0,0,0
BEGIN DESCRIPTION:
LITTLE ALDER CREEK 1.0
END DESCRIPTION:
XS GIS Cut Line= 4
      3716919.95     10751413.03      3716564.04     10752229.03
      3716598.76     10752328.86      3717149.98     10752362.71
#Sta/Elev= 30
  4065.6  385.20  4154.6  382.50  4248.0  382.86  4475.4  380.54  4695.3  374.35
  4848.0  374.31  4853.9  372.35  4859.4  373.05  4906.2  369.00  4913.5  366.73
  4924.2  366.20  4953.0  361.74  4955.1  360.41  4960.0  361.74  4978.2  359.24
  4985.8  356.53  4991.1  358.50  4999.4  357.10  5022.2  358.87  5082.4  357.66
  5112.5  358.54  5119.5  356.23  5122.3  355.73  5125.5  356.23  5142.5  358.95
  5252.7  359.46  5332.9  367.00  5433.1  372.71  5489.6  374.85  5613.8  375.00
#Mann=3,-1,0
  4065.6    0.05       0  5119.5    0.03       0  5125.5    0.05       0
Bank Sta=5119.5,5125.5
Exp/Cntr=0.3,0.1

Chan Stop Cuts=-1