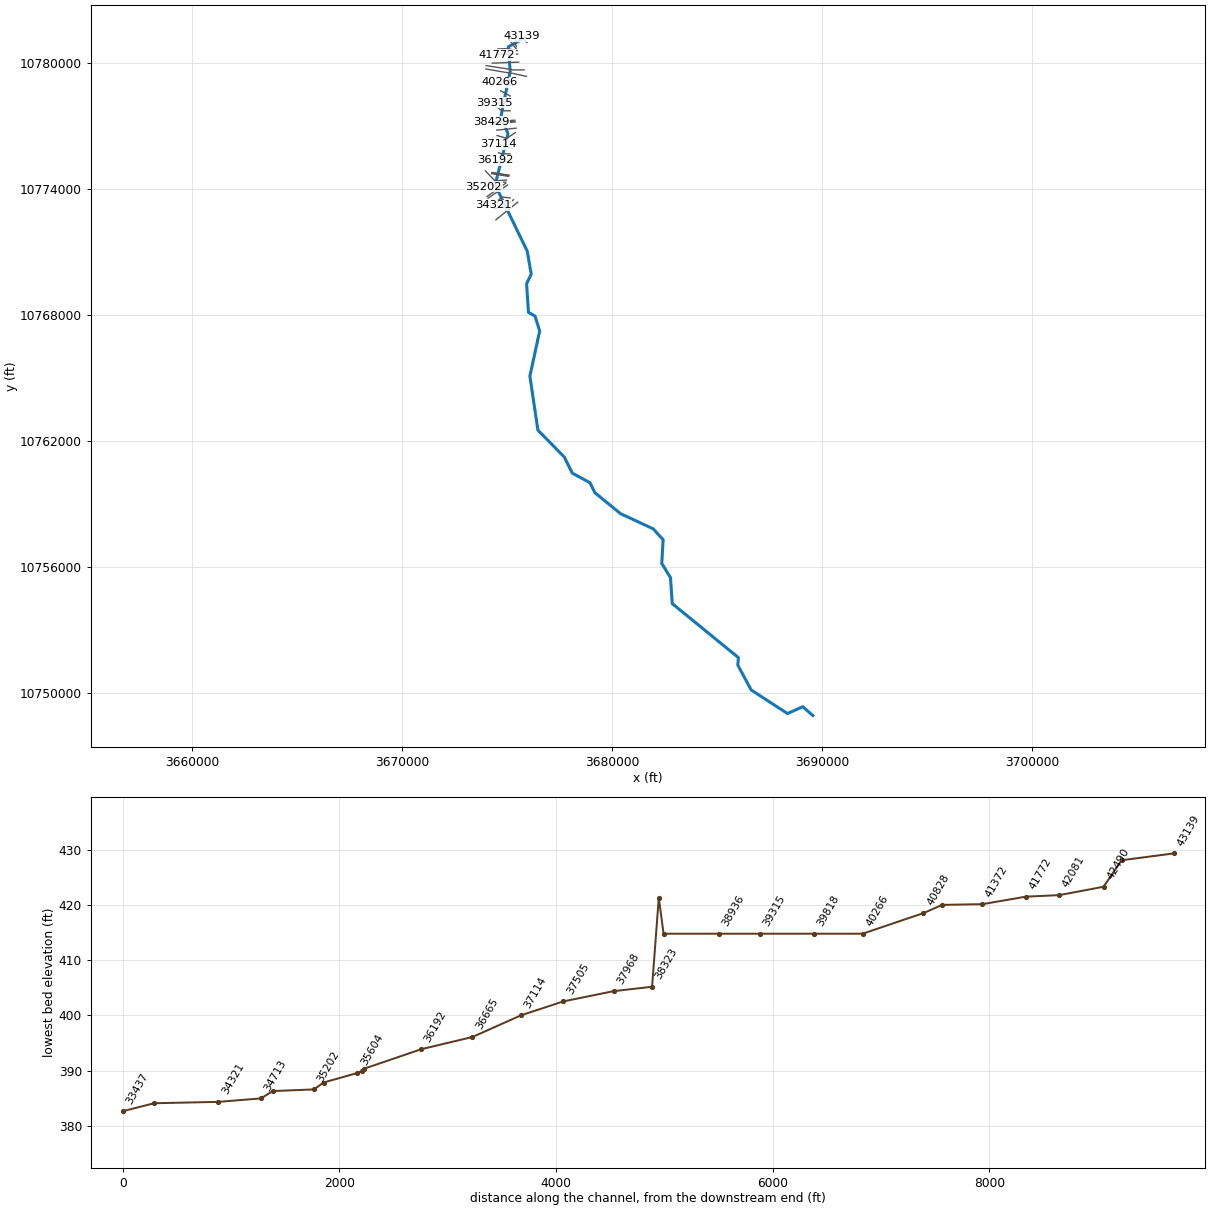
--- MILL BRANCH.prj (project) ---

Proj Title=MILL BRANCH Base Level Engineering
Current Plan=p01
Default Exp/Contr=0.3,0.1
English Units
Geom File=g01
Flow File=f01
Plan File=p01
Y Axis Title=Elevation
X Axis Title(PF)=Main Channel Distance
X Axis Title(XS)=Station
BEGIN DESCRIPTION:
MILL BRANCH
END DESCRIPTION:
DSS Export Rating Curves= 0
DSS Export Rating Curve Sorted= 0
DSS Export Volume Flow Curves= 0
DXF OffsetX= 0
DXF OffsetY= 0
DXF ScaleX= 1
DXF ScaleY= 10

--- MILL BRANCH.p01 (plan) ---

Plan Title=Multiple Run
Short Identifier=Multiple
Geom File=g01
Flow File=f01
Subcritical Flow
K Sum by GR= 0
Std Step Tol= 0.01
Critical Tol= 0.01
Num of Std Step Trials= 20
Max Error Tol= 0.3
Flow Tol Ratio= 0.001
Split Flow NTrial= 30
Split Flow Tol= 0.02
Split Flow Ratio= 0.02
Log Output Level= 0
Friction Slope Method= 1
Unsteady Friction Slope Method= 2
Unsteady Bridges Friction Slope Method= 1
Parabolic Critical Depth
Global Vel Dist=  1 , 1 , 1
Global Log Level= 0
CheckData=True
Encroach Param= -1, 0, 0, 0
BEGIN DESCRIPTION:
Multiple Run
END DESCRIPTION:

--- MILL BRANCH.f01 (steady flow) ---

Flow Title=Multiple
Program Version=4.10
Number of Profiles= 7
Profile Names=10-year,25-year,50-year,1pct_min,100-year,1pct_plu,500-year
River Rch & RM=MILL BRANCH,Reach-1         ,43139
     465     622     750     664     898    1214    1289
River Rch & RM=MILL BRANCH,Reach-1         ,42081
     770    1061    1304    1175    1589    2150    2367
River Rch & RM=MILL BRANCH,Reach-1         ,40828
     819    1128    1387    1249    1689    2284    2511
River Rch & RM=MILL BRANCH,Reach-1         ,38429
    1203    1691    2105    1918    2594    3508    3952
River Rch & RM=MILL BRANCH,Reach-1         ,35202
    1470    2084    2610    2391    3234    4374    4979
River Rch & RM=MILL BRANCH,Reach-1         ,32423
    1495    2120    2655    2432    3289    4448    5063
River Rch & RM=MILL BRANCH,Reach-1         ,29994
    2268    3275    4153    3846    5202    7035    8189
River Rch & RM=MILL BRANCH,Reach-1         ,29091
    2778    4034    5134    4769    6449    8722   10212
River Rch & RM=MILL BRANCH,Reach-1         ,28255
    2778    4034    5134    4769    6449    8722   10212
River Rch & RM=MILL BRANCH,Reach-1         ,25264
    2878    4173    5306    4922    6657    9002   10513
River Rch & RM=MILL BRANCH,Reach-1         ,20034
    2891    4184    5312    4921    6654    8999   10476
River Rch & RM=MILL BRANCH,Reach-1         ,18810
    2891    4184    5312    4921    6654    8999   10476
River Rch & RM=MILL BRANCH,Reach-1         ,16248
    3602    5254    6707    6242    8442   11417   13420
River Rch & RM=MILL BRANCH,Reach-1         ,15685
    4024    5886    7528    7018    9491   12835   15134
River Rch & RM=MILL BRANCH,Reach-1         ,14449
    4024    5886    7528    7018    9491   12835   15134
River Rch & RM=MILL BRANCH,Reach-1         ,9257
    4326    6335    8107    7562   10227   13830   16323
River Rch & RM=MILL BRANCH,Reach-1         ,8722
    4326    6335    8107    7562   10227   13830   16323
River Rch & RM=MILL BRANCH,Reach-1         ,4799
    4362    6379    8157    7600   10278   13899   16368
River Rch & RM=MILL BRANCH,Reach-1         ,2000
    4381    6402    8181    7618   10302   13933   16388
Boundary for River Rch & Prof#=MILL BRANCH,Reach-1         , 1
Up Type= 0
Dn Type= 3
Dn Slope=0.00239
Boundary for River Rch & Prof#=MILL BRANCH,Reach-1         , 2
Up Type= 0
Dn Type= 3
Dn Slope=0.00239
Boundary for River Rch & Prof#=MILL BRANCH,Reach-1         , 3
Up Type= 0
Dn Type= 3
Dn Slope=0.00239
Boundary for River Rch & Prof#=MILL BRANCH,Reach-1         , 4
Up Type= 0
Dn Type= 3
Dn Slope=0.00239
Boundary for River Rch & Prof#=MILL BRANCH,Reach-1         , 5
Up Type= 0
Dn Type= 3
Dn Slope=0.00239
Boundary for River Rch & Prof#=MILL BRANCH,Reach-1         , 6
Up Type= 0
Dn Type= 3
Dn Slope=0.00239
Boundary for River Rch & Prof#=MILL BRANCH,Reach-1         , 7
Up Type= 0
Dn Type= 3
Dn Slope=0.00239
DSS Import GetInterval= 0
DSS Import GetPeak= 0
DSS Import FillOption= 0

--- MILL BRANCH.g01 (geometry) ---

Geom Title=Existing Conditions
Program Version=4.10

River Reach=MILL BRANCH     ,Reach-1
Reach XY= 30
      3675869.63     10781197.61      3675060.75       10780755.
        3675153.       10779583.       3674725.5       10777501.
      3675047.75       10776606.      3674435.75       10774181.
       3675964.5       10771029.       3676155.5       10769930.
        3675935.       10769477.      3676023.25       10768113.
        3676335.       10767938.      3676556.25       10767224.
      3676091.25       10765078.       3676472.5       10762507.
       3677732.5       10761221.      3678109.25       10760460.
      3678950.25       10760004.        3679185.       10759528.
       3680409.5       10758530.        3681961.       10757807.
      3682433.25       10757294.      3682369.75       10756164.
      3682783.75       10755483.        3682870.       10754247.
        3686020.       10751676.      3685986.75       10751324.
        3686628.       10750135.       3688354.5       10749015.
       3689081.5       10749341.       3689559.5       10748921.

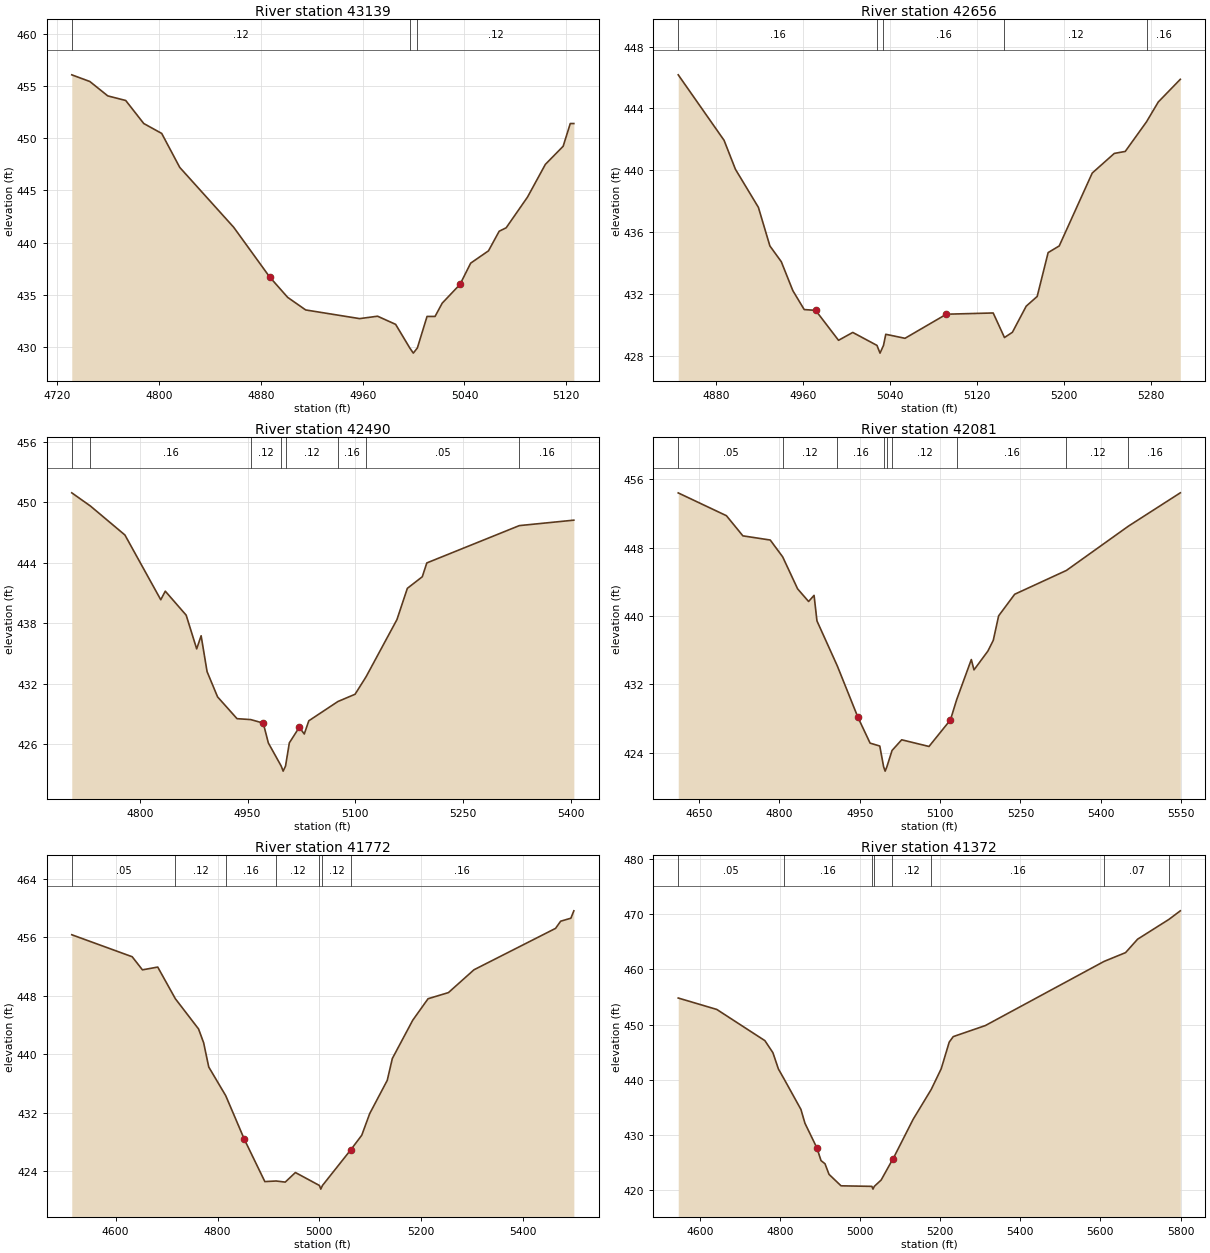
Type RM Length L Ch R = 1 ,43139   ,483,483,483
BEGIN DESCRIPTION:
MILL BRANCH 78.0
END DESCRIPTION:
XS GIS Cut Line= 3
      3675949.62     10780960.18      3675749.61     10781160.19
      3675699.59     10781260.23
#Sta/Elev= 30
  4731.3  456.09  4745.5  455.45  4759.6  454.07  4773.7  453.63  4787.9  451.42
    4802  450.47  4816.2  447.21  4858.6  441.47  4886.9   436.7    4901  434.75
  4915.2  433.54  4957.6  432.71  4971.7  432.94  4985.9  432.16    4997   429.9
  4999.8   429.4    5003   429.9  5010.6  432.92  5016.9  432.92  5022.5  434.19
  5036.5  435.99  5044.9  438.03  5058.9  439.21  5067.3  441.09  5072.8  441.42
  5089.6  444.37  5103.6   447.5  5117.6  449.24  5123.2  451.42    5126  451.42
#Mann= 3 ,-1 , 0
  4731.3     .12       0    4997     .07       0    5003     .12       0
Bank Sta=4886.9,5036.5
XS Rating Curve= 0 ,0
Exp/Cntr=0.3,0.1

Type RM Length L Ch R = 1 ,42656   ,166,166,166
BEGIN DESCRIPTION:
MILL BRANCH 77.0
END DESCRIPTION:
XS GIS Cut Line= 3
      3675449.62     10780760.15      3675399.61     10780910.19
      3675449.61     10781210.19
#Sta/Elev= 30
  4845.1  446.18  4887.3  441.94  4897.8  440.06  4918.9   437.6  4929.5   435.1
    4940  434.08  4950.6  432.21  4961.1  430.98  4971.6  430.93  4992.7  428.99
  5005.8   429.5  5028.1  428.66  5030.9  428.16  5034.1  428.66  5036.2  429.38
  5053.9  429.12    5092  430.68  5135.1  430.76  5145.5  429.17  5152.8  429.51
  5165.5   431.2  5175.6  431.83  5185.7  434.67  5195.9   435.1  5226.3  439.82
  5246.6  441.09  5256.7  441.22  5276.3  443.14  5287.1  444.42  5307.4  445.89
#Mann= 5 ,-1 , 0
  4845.1     .16       0  5028.1     .07       0  5034.1     .16       0
  5145.5     .12       0  5276.3     .16       0
Bank Sta=4971.6,5092
XS Rating Curve= 0 ,0
Exp/Cntr=0.3,0.1

Type RM Length L Ch R = 1 ,42490   ,409,409,409
BEGIN DESCRIPTION:
Mapping XS 7e976db1
END DESCRIPTION:
XS GIS Cut Line= 2
      3675430.34      10780667.6      3675008.44     10781224.92
#Sta/Elev= 30
  4705.3  450.94  4731.3  449.63  4779.3  446.76  4829.2  440.34  4835.5  441.19
  4864.6  438.81  4879.2  435.47  4885.4  436.77  4893.7  433.21  4908.3  430.71
  4935.4  428.55  4954.4  428.46  4971.9  428.11    4979  426.14  4996.9  423.85
  4999.6  423.35  5002.9  423.85  5008.2  426.15  5022.1   427.7    5029  427.03
  5035.3  428.34  5075.8  430.25  5099.7  430.97    5115   432.7    5158  438.37
  5172.5  441.47  5193.3  442.62  5199.6  443.99  5328.4  447.69  5404.3  448.23
#Mann= 8 ,-1 , 0
  4705.3     .05       0  4731.3     .16       0  4954.4     .12       0
  4996.9     .07       0  5002.9     .12       0  5075.8     .16       0
    5115     .05       0  5328.4     .16       0
Bank Sta=4971.9,5022.1
XS Rating Curve= 0 ,0
Exp/Cntr=0.3,0.1

Type RM Length L Ch R = 1 ,42081   ,309,309,309
BEGIN DESCRIPTION:
Mapping XS 45b13d4b
END DESCRIPTION:
XS GIS Cut Line= 3
      3675487.66     10780571.24       3675034.5      10780667.6
      3674560.57     10780654.58
#Sta/Elev= 30
    4611  454.42    4701  451.75  4731.7  449.39  4782.8   448.9    4806  446.93
  4833.9  443.18  4854.4   441.7  4864.6  442.42    4870  439.43  4908.1  434.14
  4946.4  428.15  4969.2  425.11  4987.3  424.77  4994.5  422.33  4997.3  421.83
  5000.5  422.33  5010.2  424.25  5028.2   425.5  5079.2  424.72  5119.2  427.83
    5131  430.23  5158.2   434.9  5163.2  433.69  5189.2   435.9  5199.2  437.15
  5209.2  440.02  5239.2  442.55  5335.8  445.34  5451.6  450.53  5548.4  454.43
#Mann= 9 ,-1 , 0
    4611     .05       0    4806     .12       0  4908.1     .16       0
  4994.5     .07       0  5000.5     .16       0  5010.2     .12       0
    5131     .16       0  5335.8     .12       0  5451.6     .16       0
Bank Sta=4946.4,5119.2
XS Rating Curve= 0 ,0
Exp/Cntr=0.3,0.1

Type RM Length L Ch R = 1 ,41772   ,400,400,400
BEGIN DESCRIPTION:
MILL BRANCH 76.0
END DESCRIPTION:
XS GIS Cut Line= 2
      3675508.13     10780410.95      3674523.78     10780367.59
#Sta/Elev= 30
    4514  456.33  4632.6  453.32  4652.7  451.53  4682.7  451.91  4717.3  447.58
  4762.8  443.45  4772.8  441.56  4782.8  438.25  4816.2  434.32  4852.8  428.34
  4892.9  422.58  4915.2  422.66  4932.9  422.51  4952.9  423.82    5000  422.05
  5002.7  421.55    5006  422.05  5061.7  426.94  5083.1  428.92  5098.7  431.88
  5133.1  436.42  5143.1  439.41  5183.2  444.65  5213.2  447.58  5253.2  448.42
  5303.3  451.54  5463.4   457.2  5473.4  458.18  5493.5  458.59  5499.3   459.6
#Mann= 7 ,-1 , 0
    4514     .05       0  4717.3     .12       0  4816.2     .16       0
  4915.2     .12       0    5000     .07       0    5006     .12       0
  5061.7     .16       0
Bank Sta=4852.8,5061.7
XS Rating Curve= 0 ,0
Exp/Cntr=0.3,0.1

Type RM Length L Ch R = 1 ,41372   ,372,372,372
BEGIN DESCRIPTION:
MILL BRANCH 75.0
END DESCRIPTION:
XS GIS Cut Line= 2
      3675555.81     10780024.66      3674303.02     10779976.98
#Sta/Elev= 30
  4545.8   454.8  4642.1  452.73  4762.2  447.08  4782.2   444.9    4796  441.94
  4810.2  440.13  4852.2  434.62  4862.2  432.12  4892.3  427.62  4902.3  425.36
  4912.3  424.78  4922.3  422.87  4952.3  420.79  5029.4  420.69  5032.1  420.19
  5035.4  420.69  5052.4  421.83  5078.6  425.24  5082.4   425.7  5132.4  432.84
  5177.5  438.24  5202.5     442  5222.5  446.82  5232.5  447.81  5312.6  449.81
  5609.1  461.43  5662.8  463.02  5692.8  465.45  5771.1  469.04  5799.5  470.59
#Mann= 8 ,-1 , 0
  4545.8     .05       0  4810.2     .16       0  5029.4     .07       0
  5035.4     .16       0  5078.6     .12       0  5177.5     .16       0
  5609.1     .07       0  5771.1     .05       0
Bank Sta=4892.3,5082.4
XS Rating Curve= 0 ,0
Exp/Cntr=0.3,0.1

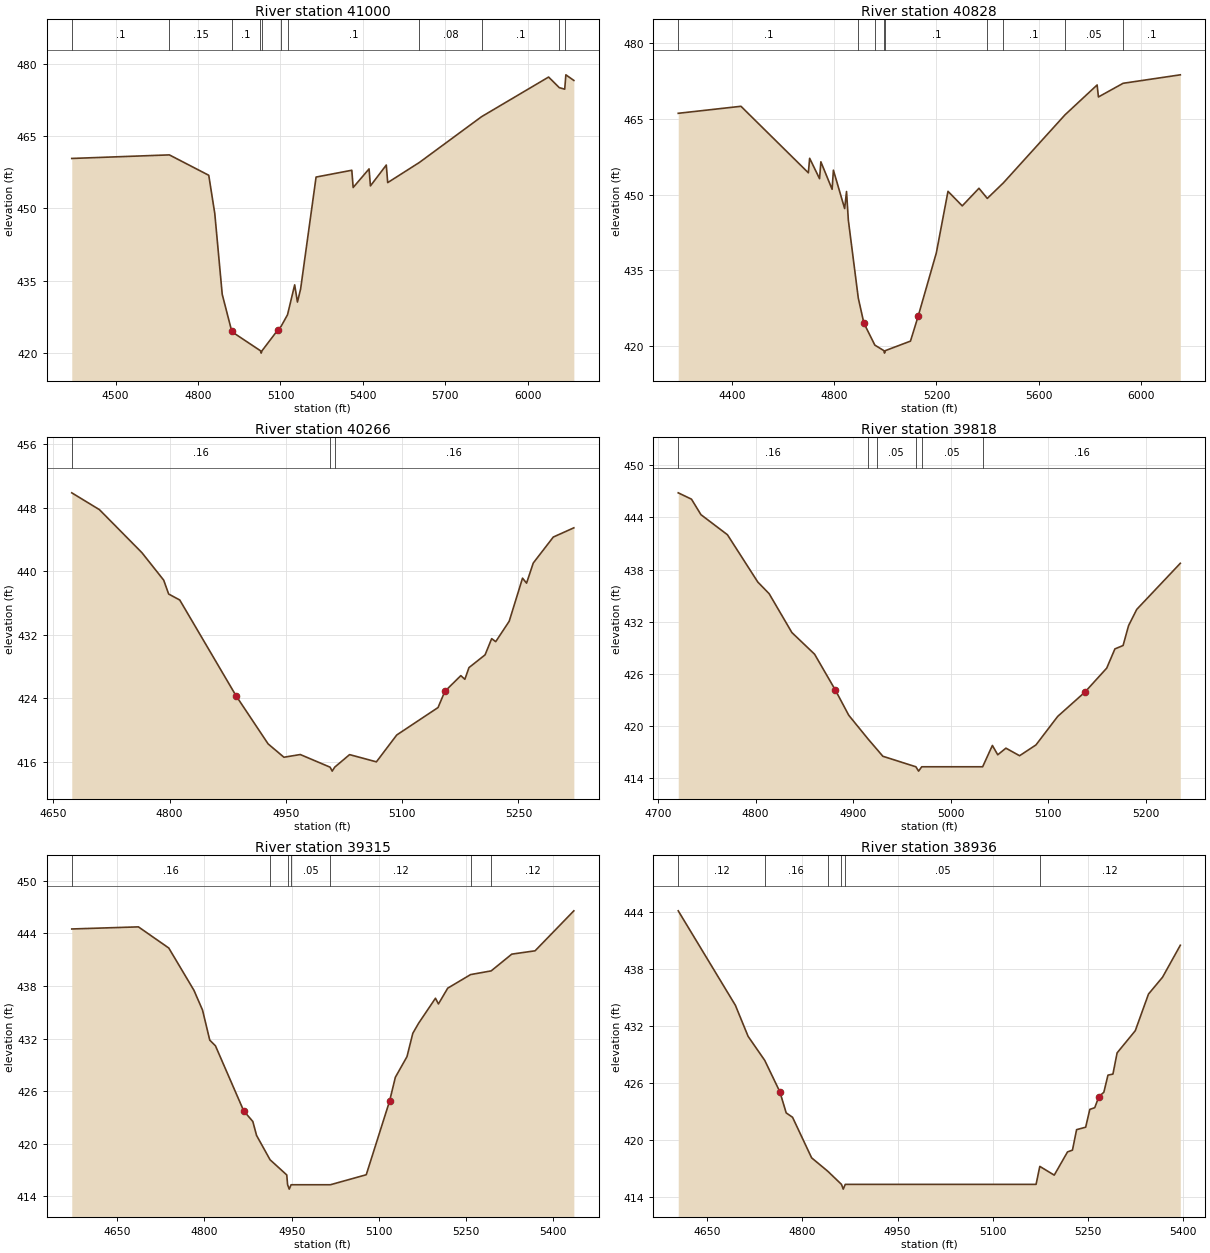
Type RM Length L Ch R = 1 ,41000   ,172,172,172
BEGIN DESCRIPTION:
MILL BRANCH 74.0
END DESCRIPTION:
XS GIS Cut Line= 4
      3675816.24     10779655.74      3675321.47      10779651.4
      3674896.12     10779720.84      3674006.37     10779859.73
#Sta/Elev= 30
  4340.9  460.35  4695.9  461.09  4839.2  456.87  4861.1  448.96  4888.2  432.23
  4922.5  424.65  4923.7  424.47  5027.1  420.56  5029.8  420.06  5033.1  420.56
  5090.9  424.89  5102.3   425.6  5125.7     428  5151.7  434.19  5161.8  430.63
  5173.3  433.33  5229.6   456.5  5359.5  457.91  5364.5  454.34  5422.3  458.19
  5427.3  454.67    5485  458.99  5490.1  455.35  5605.5  459.53  5831.6     469
  6075.4   477.2  6114.4     475    6134  474.69  6138.2  477.66  6167.2   476.5
#Mann= 11 ,-1 , 0
  4340.9      .1       0  4695.9     .15       0  4923.7      .1       0
  5027.1     .07       0  5033.1      .1       0  5102.3     .16       0
  5125.7      .1       0  5605.5     .08       0  5831.6      .1       0
  6114.4     .05       0    6134     .08       0
Bank Sta=4922.5,5090.9
XS Rating Curve= 0 ,0
Exp/Cntr=0.3,0.1

Type RM Length L Ch R = 1 ,40828   ,562,562,562
BEGIN DESCRIPTION:
MILL BRANCH 73.0
END DESCRIPTION:
XS GIS Cut Line= 4
      3675929.06       10779346.      3675286.75     10779486.61
      3674868.34     10779549.11      3674000.26     10779700.16
#Sta/Elev= 30
  4191.1  466.13  4436.2  467.52  4699.5  454.33  4704.6  457.21  4743.3  453.16
  4748.4  456.51  4792.3  451.06  4797.4  454.85  4841.3  447.24  4848.6  450.62
  4855.8  444.92  4894.6  429.49  4916.5  424.52  4959.3  420.16  4994.4  419.07
  4997.1  418.57  5000.4  419.07  5098.5  420.95  5128.8  425.93  5199.6  438.46
  5245.1  450.66  5300.8  447.77  5366.1  451.26  5398.7  449.25  5461.8  452.35
  5702.2  465.82  5827.8  471.75  5832.9  469.37  5929.3  472.08  6152.8  473.76
#Mann= 9 ,-1 , 0
  4191.1      .1       0  4894.6     .16       0  4959.3      .1       0
  4994.4     .07       0  5000.4      .1       0  5398.7     .05       0
  5461.8      .1       0  5702.2     .05       0  5929.3      .1       0
Bank Sta=4916.5,5128.8
XS Rating Curve= 0 ,0
Exp/Cntr=0.3,0.1

Type RM Length L Ch R = 1 ,40266   ,448,448,448
BEGIN DESCRIPTION:
MILL BRANCH 72.0
END DESCRIPTION:
XS GIS Cut Line= 2
      3675284.05     10778902.02      3674659.09     10779072.14
#Sta/Elev= 30
  4673.8  449.89  4709.5  447.77  4764.3  442.35  4792.4  438.89  4798.8  437.14
  4813.1  436.39  4885.7  424.33  4927.1  418.26  4947.5  416.58  4968.6  416.92
    5007  415.33  5009.8  414.83    5013  415.33  5032.2  416.91  5066.8     416
    5093  419.38  5146.3  422.84  5155.1  424.88  5175.7  426.86  5180.9   426.4
  5186.2  427.87    5207  429.48  5215.5  431.52  5220.7  431.14  5238.1  433.71
  5255.3  439.14  5260.5  438.51  5269.1  441.04    5295  444.32  5321.5  445.48
#Mann= 3 ,-1 , 0
  4673.8     .16       0    5007     .07       0    5013     .16       0
Bank Sta=4885.7,5155.1
XS Rating Curve= 0 ,0
Exp/Cntr=0.3,0.1

Type RM Length L Ch R = 1 ,39818   ,503,503,503
BEGIN DESCRIPTION:
MILL BRANCH 71.0
END DESCRIPTION:
XS GIS Cut Line= 3
      3675149.57     10778410.21      3674899.61     10778560.19
      3674699.62     10778660.18
#Sta/Elev= 30
  4720.6  446.82  4734.2  446.09  4743.9  444.31  4771.1     442  4802.2  436.57
  4813.9  435.22  4837.2  430.76  4860.5  428.27  4881.9  424.13  4895.5  421.26
  4915.6  418.49  4924.2  417.37  4930.5  416.54  4964.4  415.33  4967.2  414.83
  4970.4  415.33  5032.9  415.33  5042.9  417.78  5048.4  416.71  5056.8  417.47
  5070.8   416.6  5087.6  417.84  5109.9  421.12  5137.9  423.92  5160.2  426.67
  5168.6  428.88    5177  429.27  5182.6  431.55    5191  433.42  5235.7  438.72
#Mann= 6 ,-1 , 0
  4720.6     .16       0  4915.6     .12       0  4924.2     .05       0
  4964.4    .033       0  4970.4     .05       0  5032.9     .16       0
Bank Sta=4881.9,5137.9
XS Rating Curve= 0 ,0
Exp/Cntr=0.3,0.1

Type RM Length L Ch R = 1 ,39315   ,379,379,379
BEGIN DESCRIPTION:
MILL BRANCH 70.0
END DESCRIPTION:
XS GIS Cut Line= 3
      3675193.12     10778263.75      3674867.64     10778070.63
      3674383.02     10778098.75
#Sta/Elev= 30
  4571.7   444.5  4686.4  444.74  4738.6  442.33  4781.9  437.51  4796.7  435.25
  4809.1  431.83  4818.9  431.18  4867.6  423.75  4883.2  422.55  4889.7  420.95
  4912.9  418.18  4941.6  416.45  4943.1  415.33  4945.9  414.83  4949.1  415.33
  5016.7  415.33  5078.4  416.47  5118.5  424.86  5128.5  427.59  5148.5  429.94
  5158.5   432.6  5168.6  433.76  5197.5   436.6  5202.6  435.95  5218.6  437.75
    5258   439.3  5293.4  439.72  5328.8  441.63  5368.9  442.01  5435.6  446.57
#Mann= 7 ,-1 , 0
  4571.7     .16       0  4912.9     .05       0  4943.1    .033       0
  4949.1     .05       0  5016.7     .12       0    5258     .16       0
  5293.4     .12       0
Bank Sta=4867.6,5118.5
XS Rating Curve= 0 ,0
Exp/Cntr=0.3,0.1

Type RM Length L Ch R = 1 ,38936   ,507,507,507
BEGIN DESCRIPTION:
MILL BRANCH 69.0
END DESCRIPTION:
XS GIS Cut Line= 3
      3675149.63     10777710.19      3674749.61     10777710.19
      3674449.64     10777960.17
#Sta/Elev= 30
  4604.6  444.08  4694.6  434.15  4714.6  430.89  4740.9  428.35  4764.6  425.06
  4774.6  422.84  4784.6  422.38  4814.6  418.12  4839.9  416.72  4861.6  415.33
  4864.4  414.83  4867.6  415.33    5168  415.33  5173.9  417.22  5196.6   416.3
  5217.5  418.74  5225.3  418.93  5231.8  421.08  5246.1  421.34  5252.6  423.21
  5260.4  423.39  5266.9  424.56  5274.7  425.01  5281.2  426.81    5289  426.92
  5295.6  429.15  5324.2  431.48    5345  435.33  5367.1   437.1  5395.1  440.46
#Mann= 6 ,-1 , 0
  4604.6     .12       0  4740.9     .16       0  4839.9     .05       0
  4861.6    .033       0  4867.6     .05       0  5173.9     .12       0
Bank Sta=4764.6,5266.9
XS Rating Curve= 0 ,0
Exp/Cntr=0.3,0.1

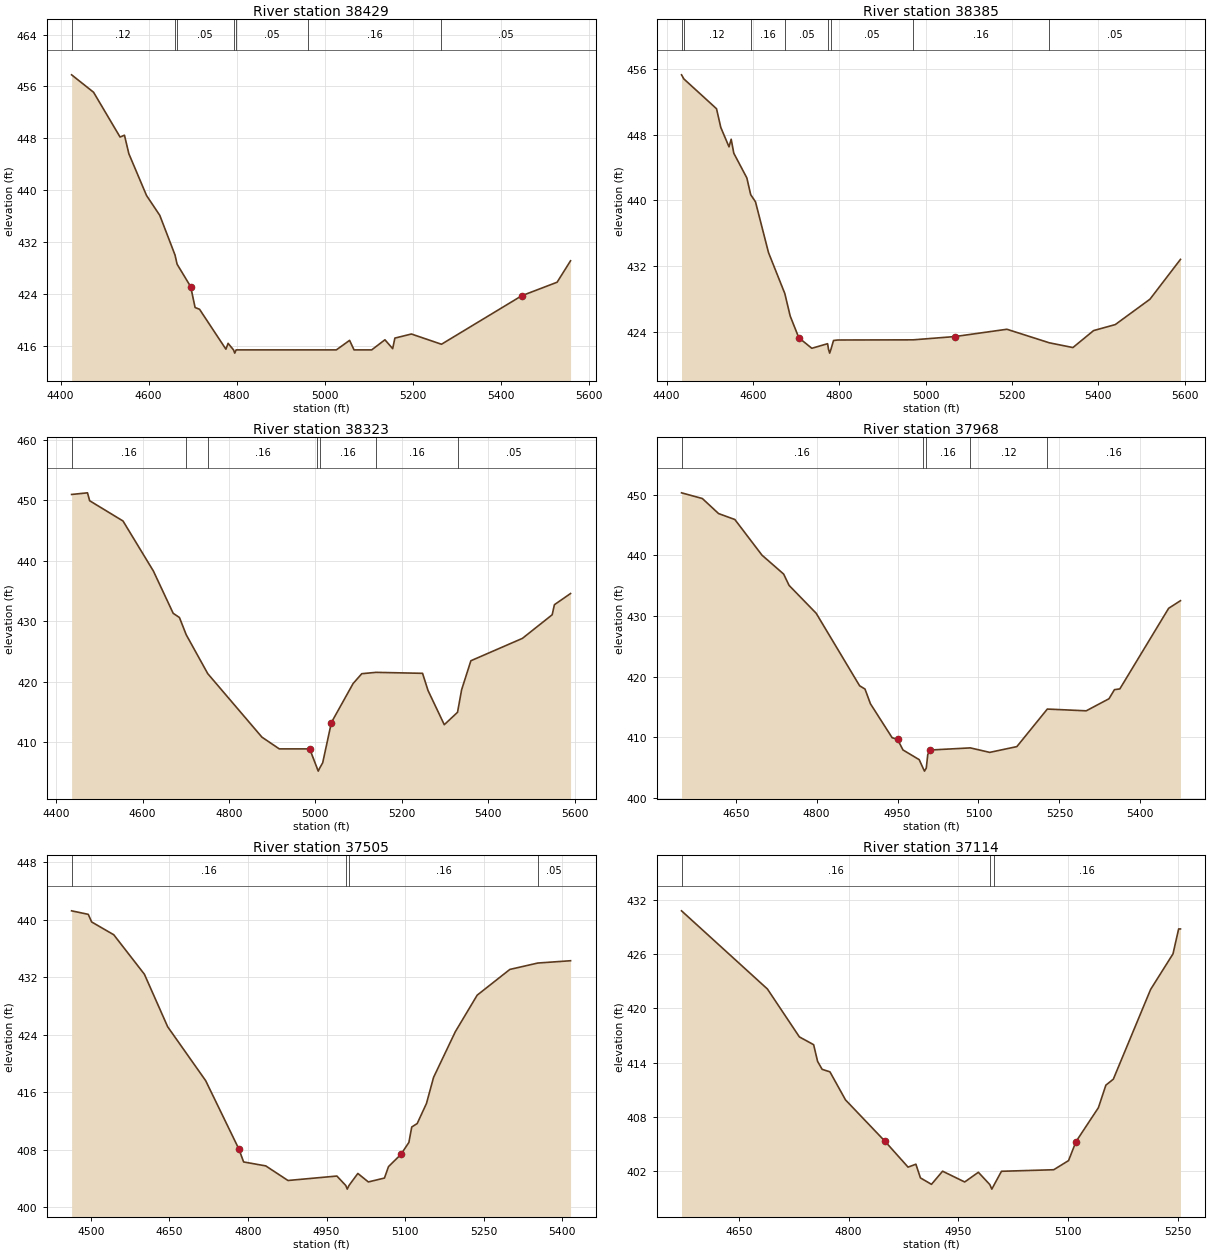
Type RM Length L Ch R = 1 ,38429   ,44,44,44
BEGIN DESCRIPTION:
Mapping XS 113b1a9b
END DESCRIPTION:
XS GIS Cut Line= 2
      3675369.34     10777263.48      3674239.14      10777173.2
#Sta/Elev= 30
  4425.1  457.78    4475  455.09  4535.2  448.18  4545.2  448.46  4555.2   445.6
  4595.4  439.15  4625.5  436.09  4660.1  429.97  4664.8  428.56  4695.7  425.08
  4705.7  421.87  4715.8   421.6  4775.7  415.44  4780.7  416.34    4793  415.33
  4795.8  414.83    4799  415.33  4961.8  415.33  5026.7  415.33  5056.8   416.8
  5066.9  415.33    5107  415.33  5137.1  416.89  5154.7  415.52  5159.7  417.15
  5197.3  417.78  5265.6   416.2  5448.1  423.69  5528.3  425.77  5558.9  429.08
#Mann= 7 ,-1 , 0
  4425.1     .12       0  4660.1     .16       0  4664.8     .05       0
    4793     .07       0    4799     .05       0  4961.8     .16       0
  5265.6     .05       0
Bank Sta=4695.7,5448.1
XS Rating Curve= 0 ,0
Exp/Cntr=0.3,0.1

Type RM Length L Ch R = 1 ,38385   ,62,62,62
BEGIN DESCRIPTION:
Mapping XS cb2fab45
END DESCRIPTION:
XS GIS Cut Line= 2
      3675370.27     10777225.29      3674219.22     10777122.86
#Sta/Elev= 30
  4434.7  455.31  4440.1  454.81  4515.7  451.18  4525.7  448.89  4544.7  446.53
  4549.7  447.46  4555.8  445.75    4586  442.74  4594.9   440.7    4606  439.83
  4636.2  433.63  4673.9  428.65  4686.4   425.9  4706.4  423.25  4736.5  421.97
    4773  422.53    4775  421.88  4777.8  421.38    4781  421.88  4786.7  422.92
  4796.8  422.98  4971.1     423  5067.9   423.4  5188.3  424.29  5286.5  422.64
  5341.2  422.06  5389.1  424.13  5439.3  424.86  5519.6  427.95  5590.3  432.81
#Mann= 8 ,-1 , 0
  4434.7     .16       0  4440.1     .12       0  4594.9     .16       0
  4673.9     .05       0    4775     .07       0    4781     .05       0
  4971.1     .16       0  5286.5     .05       0
Bank Sta=4706.4,5067.9
XS Rating Curve= 0 ,0
Exp/Cntr=0.3,0.1

Type RM Length L Ch R = 1 ,38323   ,355,355,355
BEGIN DESCRIPTION:
MILL BRANCH 68.0
END DESCRIPTION:
XS GIS Cut Line= 2
      3675397.98     10777179.28      3674248.72     10777061.23
#Sta/Elev= 30
  4435.5  450.97  4472.3  451.24  4477.3  449.93  4554.5  446.58  4624.9   438.3
  4670.7  431.31  4685.2  430.61  4700.9  427.76  4750.8  421.32  4876.2  410.82
  4916.4  408.88  4986.8  408.88  5003.9   405.7  5006.6   405.2  5009.9   405.7
  5016.9  406.58    5037  413.24  5087.3  419.69  5107.4  421.32  5140.4  421.54
  5248.1  421.38  5260.8  418.54  5298.4  412.88  5329.1  414.93  5338.6  418.67
    5360  423.46  5479.3  427.16  5548.3  431.07  5553.4  432.73  5590.8  434.58
#Mann= 7 ,-1 , 0
  4435.5     .16       0  4700.9     .05       0  4750.8     .16       0
  5003.9     .07       0  5009.9     .16       0  5140.4     .16       0
  5329.1     .05       0
Bank Sta=4986.8,5037
XS Rating Curve= 0 ,0
Exp/Cntr=0.3,0.1

Type RM Length L Ch R = 1 ,37968   ,463,463,463
BEGIN DESCRIPTION:
MILL BRANCH 67.0
END DESCRIPTION:
XS GIS Cut Line= 2
      3675437.97     10776881.54      3674517.83     10776787.79
#Sta/Elev= 30
  4549.5  450.28  4588.1  449.34  4618.2  446.86  4648.4  445.88  4698.6  440.01
  4738.8  436.89  4748.9  435.02  4799.1  430.43  4879.6  418.48  4889.6  417.94
  4899.7  415.51  4939.9  409.92  4949.9  409.65    4960   407.9  4990.1   406.3
  4997.2  404.91  4999.9  404.41  5003.2  404.91    5006  407.16    5011  407.89
  5084.9  408.24  5120.8   407.5  5171.1  408.45  5227.6  414.64  5299.7  414.35
  5341.9  416.34    5352  417.84    5362  417.96  5452.5  431.25  5474.4   432.5
#Mann= 5 ,-1 , 0
  4549.5     .16       0  4997.2     .07       0  5003.2     .16       0
  5084.9     .12       0  5227.6     .16       0
Bank Sta=4949.9,5011
XS Rating Curve= 0 ,0
Exp/Cntr=0.3,0.1

Type RM Length L Ch R = 1 ,37505   ,391,391,391
BEGIN DESCRIPTION:
MILL BRANCH 66.0
END DESCRIPTION:
XS GIS Cut Line= 4
      3675396.32     10776666.28       3675031.7     10776430.15
      3674889.34     10776426.68      3674528.27     10776530.83
#Sta/Elev= 30
  4463.2  441.25    4495  440.76  4501.5   439.7  4543.7  437.92  4602.2  432.43
  4646.6  425.13  4719.1  417.64  4782.4  408.15  4791.6  406.33  4833.9  405.78
  4876.3  403.75  4969.7  404.37  4986.7  403.05  4989.5  402.55  4992.7  403.05
  5009.7  404.73  5029.7  403.55  5060.5  404.09  5068.2  405.68  5091.8  407.37
  5107.1  409.04  5112.6  411.19    5123  411.67  5140.7  414.46  5154.2  418.08
  5195.8  424.44  5237.5  429.52  5299.9   433.1  5353.3  433.99  5415.8  434.31
#Mann= 4 ,-1 , 0
  4463.2     .16       0  4986.7     .07       0  4992.7     .16       0
  5353.3     .05       0
Bank Sta=4782.4,5091.8
XS Rating Curve= 0 ,0
Exp/Cntr=0.3,0.1

Type RM Length L Ch R = 1 ,37114   ,449,449,449
BEGIN DESCRIPTION:
MILL BRANCH 65.0
END DESCRIPTION:
XS GIS Cut Line= 3
      3675249.58      10775910.2      3674849.61     10776060.19
      3674599.63     10776110.18
#Sta/Elev= 30
  4571.6  430.76    4689  422.13  4732.7  416.84  4752.2  415.98  4757.6  414.14
  4763.8  413.26  4774.5  412.98  4795.8  409.88  4849.2  405.36  4881.3  402.46
    4892  402.78  4898.2  401.27  4913.3  400.56  4928.5  402.01  4958.7  400.82
  4977.4  401.89  4993.1  400.53  4995.8  400.03  4999.1  400.53    5009     402
  5080.4  402.17  5100.7  403.18  5110.9  405.28  5141.5  409.02  5151.7  411.51
  5161.9  412.17  5212.9  422.08  5243.5  426.01  5251.2  428.76  5253.7  428.76
#Mann= 3 ,-1 , 0
  4571.6     .16       0  4993.1     .07       0  4999.1     .16       0
Bank Sta=4849.2,5110.9
XS Rating Curve= 0 ,0
Exp/Cntr=0.3,0.1

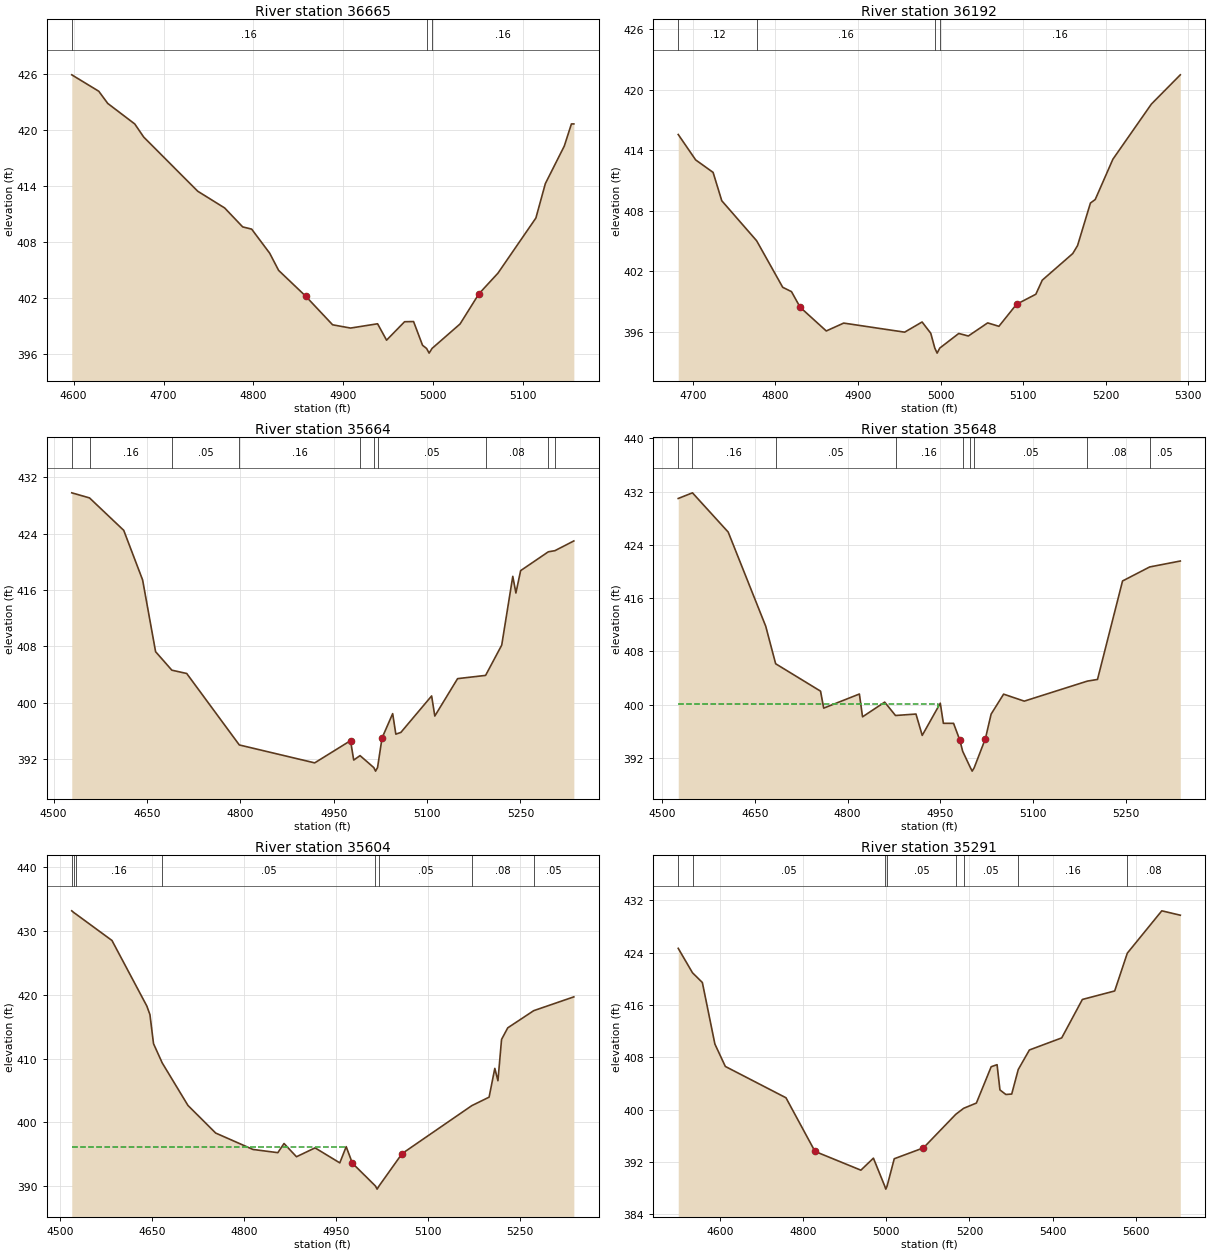
Type RM Length L Ch R = 1 ,36665   ,473,473,473
BEGIN DESCRIPTION:
MILL BRANCH 64.0
END DESCRIPTION:
XS GIS Cut Line= 3
      3675149.65     10775660.19      3674749.61     10775660.19
      3674599.57      10775710.2
#Sta/Elev= 30
    4598  425.96    4628   424.2    4638  422.89    4668  420.69    4678  419.28
    4738  413.47    4768  411.67    4788  409.64    4798   409.4    4818  406.82
    4828  404.97    4858  402.21    4888  399.13    4908  398.78    4938  399.24
    4948  397.48    4968  399.46    4978  399.48    4988  396.93  4992.5  396.59
  4995.3  396.09  4998.5  396.59  5029.7  399.22  5050.7  402.46  5071.8  404.67
    5114  410.59  5124.5  414.28  5145.6  418.32  5153.5  420.69  5156.2  420.69
#Mann= 3 ,-1 , 0
    4598     .16       0  4992.5     .07       0  4998.5     .16       0
Bank Sta=4858,5050.7
XS Rating Curve= 0 ,0
Exp/Cntr=0.3,0.1

Type RM Length L Ch R = 1 ,36192   ,528,528,528
BEGIN DESCRIPTION:
MILL BRANCH 63.0
END DESCRIPTION:
XS GIS Cut Line= 3
      3674999.64      10775310.2      3674699.61     10775210.19
      3674449.61     10775360.19
#Sta/Elev= 30
  4682.5  415.56  4703.6  413.04  4724.7   411.8  4735.2  408.99  4777.4  405.02
    4809   400.4  4819.6  399.97  4830.1  398.42  4861.7  396.07  4882.8  396.85
  4956.6  395.95  4977.7  396.96  4988.2  395.84  4993.1  394.37  4995.9  393.87
  4999.1  394.37  5022.1  395.82  5033.7  395.57  5057.1  396.87  5070.7  396.53
  5092.1  398.72  5115.4  399.71  5123.2  401.11  5160.1  403.75  5165.9  404.54
  5181.5  408.76  5187.3  409.11  5208.7  413.11  5255.3  418.58  5290.3  421.48
#Mann= 4 ,-1 , 0
  4682.5     .12       0  4777.4     .16       0  4993.1     .07       0
  4999.1     .16       0
Bank Sta=4830.1,5092.1
XS Rating Curve= 0 ,0
Exp/Cntr=0.3,0.1

Type RM Length L Ch R = 1 ,35664   ,16,16,16
BEGIN DESCRIPTION:
Mapping XS e992b69b
END DESCRIPTION:
XS GIS Cut Line= 2
      3675092.06     10774644.99       3674295.1       10774770.
#Sta/Elev= 30
  4529.1  429.78  4557.6  429.06  4612.6  424.46  4642.9  417.44  4663.8  407.26
  4689.9  404.64  4713.8  404.17  4798.3  394.04  4919.4   391.5    4977  394.65
  4982.1   391.9  4992.3  392.53  5014.4  390.83  5017.2  390.33  5020.4  390.83
  5027.6  395.02  5044.7  398.48  5049.8  395.57  5057.9  395.82  5107.3  400.99
  5112.4  398.14    5149  403.44    5194   403.9  5219.9  408.19  5237.7  417.94
  5242.7  415.58  5250.3  418.75  5294.8  421.42  5305.4  421.58  5335.8  422.96
#Mann= 10 ,-1 , 0
  4529.1     .12       0  4557.6     .16       0  4689.9     .05       0
  4798.3     .16       0  4992.3     .05       0  5014.4     .03       0
  5020.4     .05       0    5194     .08       0  5294.8     .05       0
  5305.4     .08       0
Bank Sta=4977,5027.6
XS Rating Curve= 0 ,0
Exp/Cntr=0.3,0.1

Type RM Length L Ch R = 1 ,35648   ,44,44,44
BEGIN DESCRIPTION:
Mapping XS 58e98fde
END DESCRIPTION:
XS GIS Cut Line= 2
      3675089.45     10774629.36      3674287.33     10774754.37
#Sta/Elev= 30
  4526.1  430.98  4549.1  431.83  4606.9  425.93  4667.6  411.77  4683.6  406.14
  4756.2  402.02  4761.3  399.47    4819  401.59  4824.1  398.16  4859.9  400.37
  4877.4  398.36  4910.5  398.58  4920.6  395.37  4949.8  400.21  4954.8  397.19
  4971.3  397.18  4981.4  394.66    4986  392.99  4998.6   390.5  5001.4     390
  5004.6   390.5  5022.7  394.87    5032  398.57  5052.2  401.57  5085.6  400.52
  5187.6  403.53    5204  403.78  5244.5  418.58  5288.4  420.69  5337.9  421.58
#Mann= 9 ,-1 , 0
  4526.1     .12       0  4549.1     .16       0  4683.6     .05       0
  4877.4     .16       0    4986     .05       0  4998.6     .03       0
  5004.6     .05       0  5187.6     .08       0  5288.4     .05       0
#XS Ineff= 2 , 0
         4945.45  400.06
Permanent Ineff=
       F       F
Bank Sta=4981.4,5022.7
XS Rating Curve= 0 ,0
Exp/Cntr=0.3,0.1

Type RM Length L Ch R = 1 ,35604   ,313,313,313
BEGIN DESCRIPTION:
Mapping XS 9a529631
END DESCRIPTION:
XS GIS Cut Line= 2
      3675081.13     10774585.09       3674273.3     10774714.96
#Sta/Elev= 30
  4519.2  433.13  4522.5  432.86  4525.9  432.63  4584.7  428.49  4641.5  418.23
  4646.6  416.88  4652.4  412.34  4666.6  409.32  4708.5  402.67  4753.7  398.34
  4814.5  395.77    4855  395.27  4865.1   396.7  4885.4  394.63  4915.7  396.02
    4956  393.67  4966.4  396.21  4976.5  393.62    5014  390.06  5016.8  389.56
    5020  390.06  5057.5  395.12  5171.1  402.63  5199.3  403.96  5208.6  408.46
  5213.7  406.53  5219.6     413  5229.7  414.81    5272   417.5  5337.4  419.66
#Mann= 8 ,-1 , 0
  4519.2     .16       0  4522.5     .12       0  4525.9     .16       0
  4666.6     .05       0    5014     .03       0    5020     .05       0
  5171.1     .08       0    5272     .05       0
#XS Ineff= 2 , 0
          4965.2  396.12
Permanent Ineff=
       F       F
Bank Sta=4976.5,5057.5
XS Rating Curve= 0 ,0
Exp/Cntr=0.3,0.1

Type RM Length L Ch R = 1 ,35291   ,89,89,89
BEGIN DESCRIPTION:
MILL BRANCH 62.0
END DESCRIPTION:
XS GIS Cut Line= 3
      3674977.49     10774413.22      3674427.96     10774374.16
      3673973.43     10774846.87
#Sta/Elev= 30
    4500  424.67  4534.3  420.93    4558  419.44  4588.1  410.03  4613.2   406.6
  4758.9  401.81  4828.7   393.6    4939  390.73  4969.1  392.57  4996.1  388.33
  4998.9  387.83  5002.1  388.33  5019.2  392.48  5089.3  394.14  5167.1  399.28
  5186.1   400.2  5216.6     401  5252.2  406.56  5266.3  406.87  5273.2  403.01
  5287.4  402.31  5301.5  402.38  5317.2  406.13    5344  409.12  5421.7  410.97
  5471.3  416.85    5549  418.15  5579.3  423.93  5662.2  430.41  5706.7  429.74
#Mann= 8 ,-1 , 0
    4500     .16       0  4534.3     .05       0  4996.1     .03       0
  5002.1     .05       0  5167.1     .08       0  5186.1     .05       0
  5317.2     .16       0  5579.3     .08       0
Bank Sta=4828.7,5089.3
XS Rating Curve= 0 ,0
Exp/Cntr=0.3,0.1

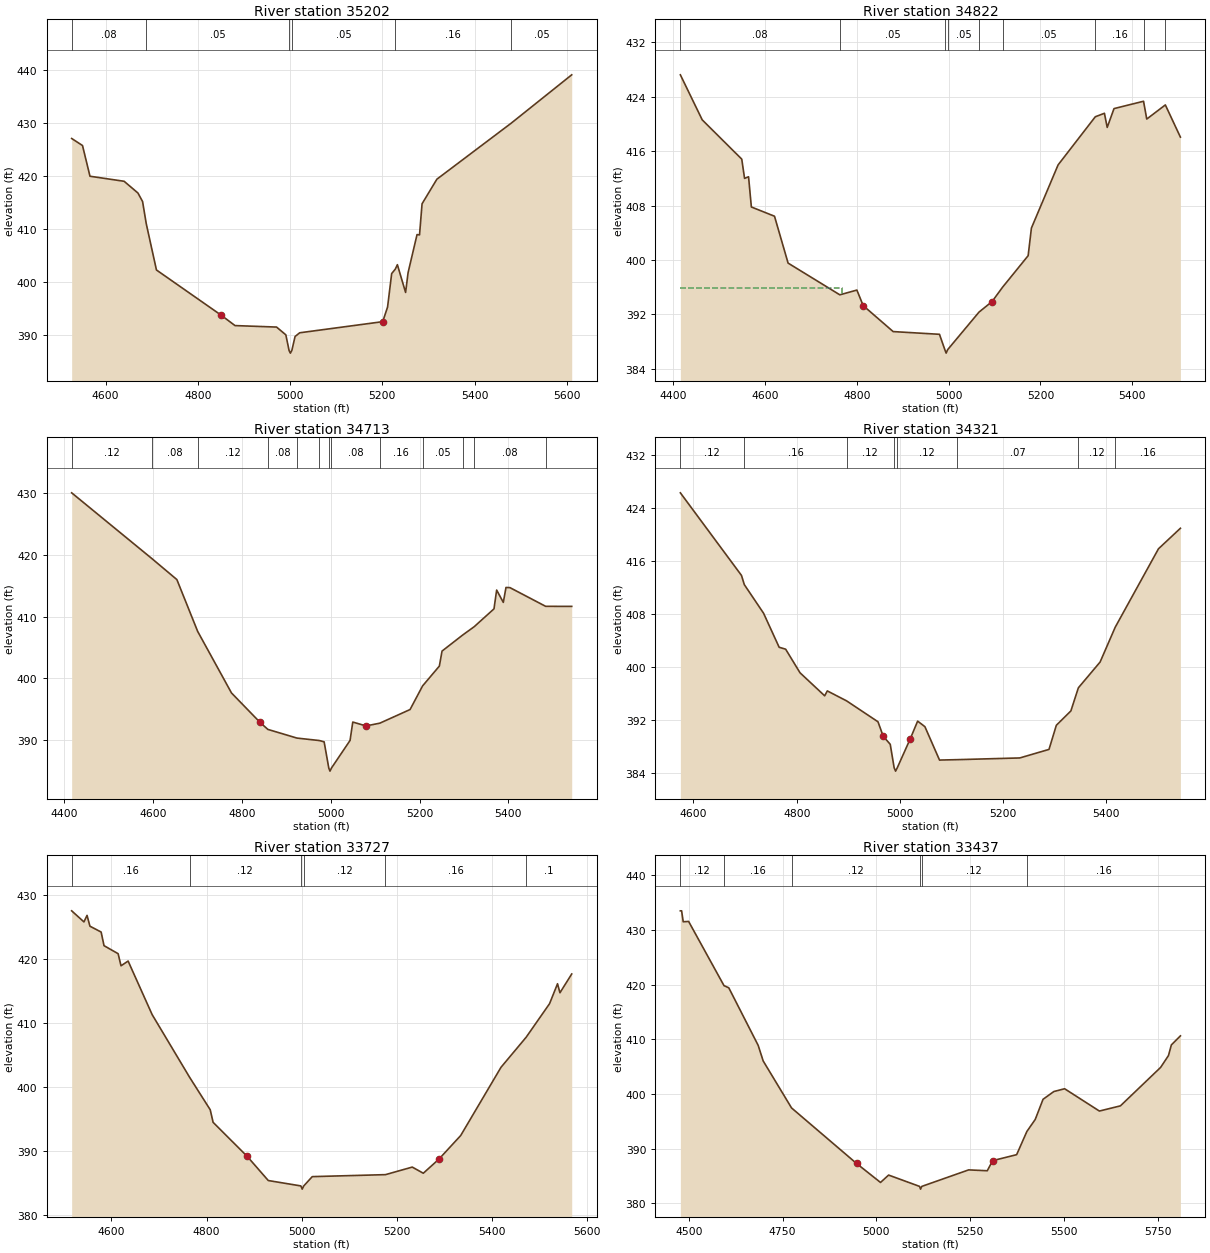
Type RM Length L Ch R = 1 ,35202   ,380,380,380
BEGIN DESCRIPTION:
MILL BRANCH 61.0
END DESCRIPTION:
XS GIS Cut Line= 3
      3674943.07     10774317.63      3674419.61     10774286.38
      3673896.17     10774088.46
#Sta/Elev= 30
  4526.6  427.11  4550.1  425.78  4566.3  419.98  4640.3  419.03  4670.3  416.81
  4680.3  415.21  4688.3  411.02  4710.4  402.28  4850.6  393.75  4880.7  391.78
  4970.8   391.5  4990.9  390.03  4997.9  387.08  5000.7  386.58  5003.9  387.08
  5010.9  389.72  5020.9  390.42  5200.9  392.52  5211.4  395.27  5220.3   401.6
  5228.1  402.43  5232.7  403.28  5250.5  398.04  5255.9  401.78  5275.3  408.96
  5280.7  408.91  5286.2  414.78  5318.3  419.42  5479.3  429.99  5610.6  439.13
#Mann= 6 ,-1 , 0
  4526.6     .08       0  4688.3     .05       0  4997.9     .03       0
  5003.9     .05       0  5228.1     .16       0  5479.3     .05       0
Bank Sta=4850.6,5200.9
XS Rating Curve= 0 ,0
Exp/Cntr=0.3,0.1

Type RM Length L Ch R = 1 ,34822   ,109,109,109
BEGIN DESCRIPTION:
Mapping XS 814703ea
END DESCRIPTION:
XS GIS Cut Line= 2
      3674943.08     10774262.96      3674054.99      10773632.7
#Sta/Elev= 30
  4415.8  427.24  4463.4  420.61  4549.5  414.83  4555.6     412  4564.3  412.24
  4570.4  407.79  4620.8  406.43  4650.4  399.53  4763.1  394.86  4800.2  395.56
    4814  393.27  4879.2  389.45  4980.1  389.05  4991.8  386.78  4994.6  386.28
  4997.8  386.78  5066.2  392.32  5094.5  393.86  5117.6  395.99  5173.2  400.62
  5180.3  404.68  5238.4  413.98  5319.5  421.07  5339.3  421.58  5345.4   419.5
  5360.2  422.27  5424.5  423.35  5431.5  420.73    5472  422.81  5504.8  418.07
#Mann= 9 ,-1 , 0
  4415.8     .08       0  4763.1     .05       0  4991.8     .04       0
  4997.8     .05       0  5066.2     .08       0  5117.6     .05       0
  5319.5     .16       0  5424.5     .08       0    5472     .05       0
#XS Ineff= 2 , 0
         4767.54  395.92
Permanent Ineff=
       F       F
Bank Sta=4814,5094.5
XS Rating Curve= 0 ,0
Exp/Cntr=0.3,0.1

Type RM Length L Ch R = 1 ,34713   ,392,392,392
BEGIN DESCRIPTION:
MILL BRANCH 60.0
END DESCRIPTION:
XS GIS Cut Line= 2
      3675031.59       10774177.      3674096.71     10773549.41
#Sta/Elev= 30
  4416.5  430.09  4596.7  419.45  4653.4  416.02  4700.2  407.62  4776.4  397.63
  4840.4  392.88  4858.2  391.72  4923.8  390.31  4974.4  389.91    4985   389.7
  4995.5  385.45  4998.2  384.95  5001.5  385.45  5043.4  389.93  5049.5  392.91
  5079.4  392.28  5110.5  392.73  5178.5  394.94  5206.8  398.78  5244.5  401.99
  5250.5  404.42  5297.1  407.03    5323  408.38  5367.5  411.27  5373.5  414.32
  5388.5  412.32  5394.5  414.74  5403.5  414.71  5483.8  411.68  5542.5  411.67
#Mann= 13 ,-1 , 0
  4416.5     .12       0  4596.7     .08       0  4700.2     .12       0
  4858.2     .08       0  4923.8     .12       0  4974.4     .08       0
  4995.5     .07       0  5001.5     .08       0  5110.5     .16       0
  5206.8     .05       0  5297.1     .16       0    5323     .08       0
  5483.8     .16       0
Bank Sta=4840.4,5079.4
XS Rating Curve= 0 ,0
Exp/Cntr=0.3,0.1

Type RM Length L Ch R = 1 ,34321   ,594,594,594
BEGIN DESCRIPTION:
MILL BRANCH 59.0
END DESCRIPTION:
XS GIS Cut Line= 3
      3675149.58     10773560.19      3674749.61     10773610.19
      3674349.59     10773210.17
#Sta/Elev= 30
  4574.6  426.34    4693  413.87  4698.5  412.48  4735.8  408.16    4766  403.02
  4778.6  402.73  4806.4  399.17  4854.2  395.69  4859.3  396.43  4896.6  394.93
  4957.5  391.77  4967.6  389.58  4981.2  388.37  4988.8  384.82  4991.6  384.32
  4994.8  384.82  5020.1  389.22  5034.3  391.87  5048.4  391.03  5076.7  385.99
  5110.2  386.05  5232.2  386.31  5288.8   387.6    5303  391.24  5331.2  393.41
  5345.7   396.9  5387.8  400.79  5417.1  406.05  5500.9  417.89  5543.4  420.99
#Mann= 8 ,-1 , 0
  4574.6     .12       0  4698.5     .16       0  4896.6     .12       0
  4988.8     .07       0  4994.8     .12       0  5110.2     .07       0
  5345.7     .12       0  5417.1     .16       0
Bank Sta=4967.6,5020.1
XS Rating Curve= 0 ,0
Exp/Cntr=0.3,0.1

Type RM Length L Ch R = 1 ,33727   ,290,290,290
BEGIN DESCRIPTION:
MILL BRANCH 58.0
END DESCRIPTION:
XS GIS Cut Line= 3
      3675310.72     10773473.94       3674839.4     10773143.23
      3674373.89     10773049.61
#Sta/Elev= 30
  4516.4  427.51  4542.2  425.78  4548.7   426.8  4554.8  425.11  4578.3   424.2
  4584.4  422.07    4614  420.82  4620.1  418.93    4635  419.67  4685.5  411.31
  4764.1  401.54  4807.5  396.46  4813.6  394.49  4885.1  389.19  4929.5  385.41
    4998  384.57  5000.8  384.07    5004  384.57  5021.9  386.02  5175.7  386.33
    5232  387.51  5255.2  386.55    5288  388.75  5333.8  392.44  5418.4  403.08
  5471.3  407.78  5520.4  413.01  5537.2  416.13  5542.3  414.72    5567  417.65
#Mann= 6 ,-1 , 0
  4516.4     .16       0  4764.1     .12       0    4998     .07       0
    5004     .12       0  5175.7     .16       0  5471.3      .1       0
Bank Sta=4885.1,5288
XS Rating Curve= 0 ,0
Exp/Cntr=0.3,0.1

Type RM Length L Ch R = 1 ,33437   ,447,447,447
BEGIN DESCRIPTION:
MILL BRANCH 57.0
END DESCRIPTION:
XS GIS Cut Line= 2
      3675511.24     10773359.35      3674474.86     10772520.87
#Sta/Elev= 30
  4477.4  433.52  4480.7  433.52    4485  431.52  4499.4  431.58  4593.7  419.84
  4606.5  419.44  4684.8  408.92  4698.2  406.06  4773.8  397.47    4947  387.32
    5011  383.84  5032.6  385.19  5115.1  383.12  5117.8  382.62  5121.1  383.12
    5246  386.14  5295.6  385.98    5310  387.83  5373.9  388.92  5401.2  393.17
  5423.5  395.37  5444.3  399.05  5473.1  400.47  5501.8  400.98  5594.5   396.9
  5650.6  397.85  5757.7  404.88  5778.7  407.05  5786.4     409  5810.5  410.65
#Mann= 6 ,-1 , 0
  4477.4     .12       0  4593.7     .16       0  4773.8     .12       0
  5115.1     .07       0  5121.1     .12       0  5401.2     .16       0
Bank Sta=4947,5310
XS Rating Curve= 0 ,0
Exp/Cntr=0.3,0.1