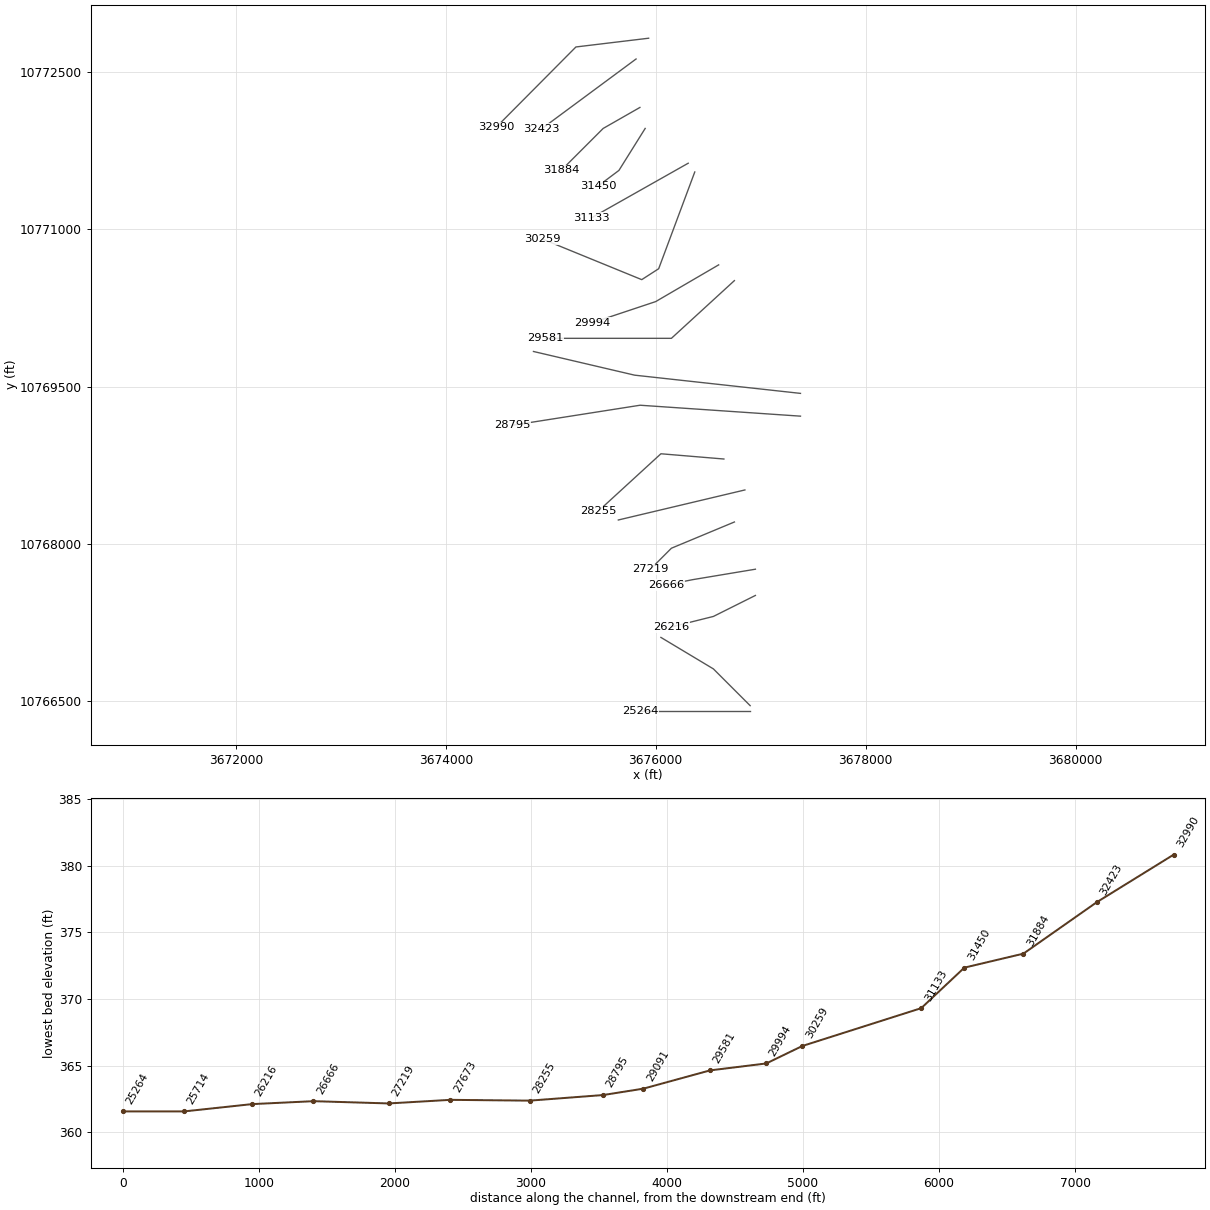
HEC-RAS study MILL BRANCH.prj: MILL BRANCH Base Level Engineering

--- MILL BRANCH.g01 (geometry) --- (continued)

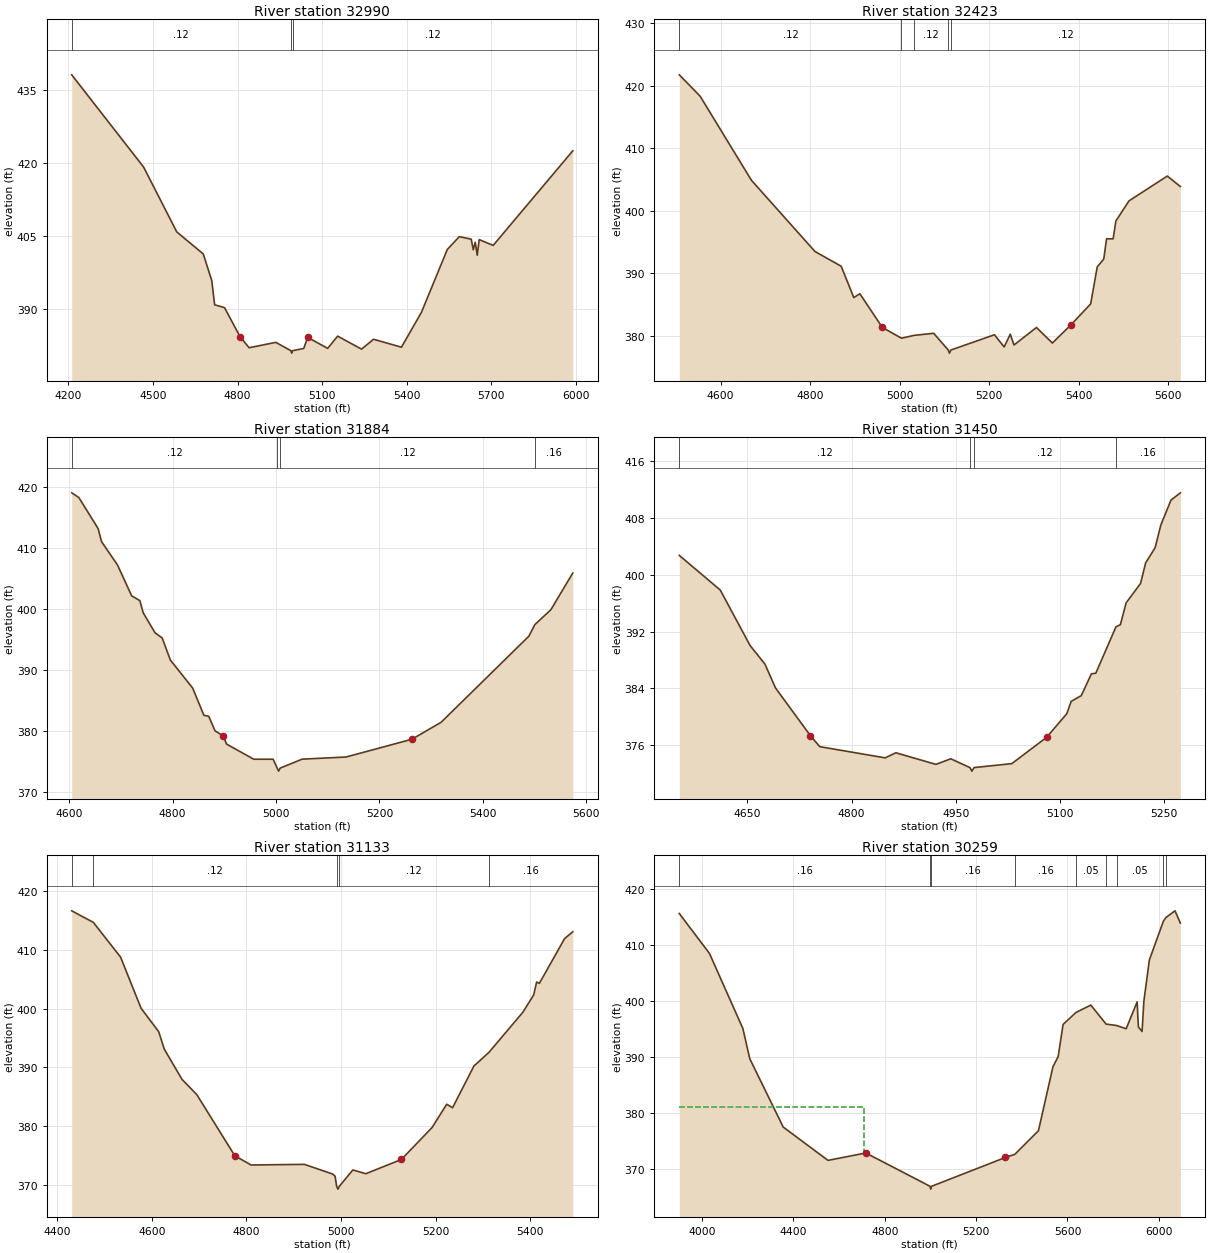
Type RM Length L Ch R = 1 ,32990   ,567,567,567
BEGIN DESCRIPTION:
MILL BRANCH 56.0
END DESCRIPTION:
XS GIS Cut Line= 3
      3675932.77     10772819.89      3675240.01     10772736.55
      3674479.62     10771970.95
#Sta/Elev= 30
  4211.9  438.19  4466.9  419.18  4584.4  405.82  4678.4  401.28  4708.6  395.77
  4718.7   390.8  4753.8  390.21  4809.3  384.17    4841  381.95  4935.6  383.06
  4989.2  381.34    4992  380.84  4995.2  381.34  5034.6  381.81  5048.8  384.08
  5119.5  381.82  5154.9  384.34  5239.7  381.66  5282.1   383.7  5381.1  382.06
  5451.9  389.23  5543.8   402.2  5586.2  404.84  5628.6  404.33  5635.7  402.14
  5642.8  403.69  5649.8  401.02  5656.9  404.23  5706.4  403.04  5988.7  422.53
#Mann= 3 ,-1 , 0
  4211.9     .12       0  4989.2     .07       0  4995.2     .12       0
Bank Sta=4809.3,5048.8
XS Rating Curve= 0 ,0
Exp/Cntr=0.3,0.1

Type RM Length L Ch R = 1 ,32423   ,539,539,539
BEGIN DESCRIPTION:
MILL BRANCH 55.0
END DESCRIPTION:
XS GIS Cut Line= 2
      3675812.94     10772621.98      3674913.23      10771956.3
#Sta/Elev= 30
  4507.6  421.71    4554  418.31  4668.8  404.86  4810.7  393.49  4869.2  391.14
  4897.4  386.13  4910.9  386.75    4961  381.37  5003.9  379.64  5032.2   380.1
  5075.8  380.43  5108.3  377.76    5111  377.26  5114.3  377.76  5211.5  380.19
  5233.2  378.25  5246.9  380.27  5255.3  378.56  5305.4  381.36  5340.9  378.87
  5382.6  381.79  5426.5  385.13  5441.1  391.03  5455.7  392.29    5462  395.52
  5476.6  395.51  5482.8  398.37  5512.1  401.58  5597.6  405.54  5626.8  403.87
#Mann= 5 ,-1 , 0
  4507.6     .12       0  5003.9     .16       0  5032.2     .12       0
  5108.3     .07       0  5114.3     .12       0
Bank Sta=4961,5382.6
XS Rating Curve= 0 ,0
Exp/Cntr=0.3,0.1

Type RM Length L Ch R = 1 ,31884   ,434,434,434
BEGIN DESCRIPTION:
MILL BRANCH 54.0
END DESCRIPTION:
XS GIS Cut Line= 3
       3675849.6     10772160.18      3675499.61     10771960.19
       3675099.6     10771560.18
#Sta/Elev= 30
  4605.1  418.98  4618.8  418.22  4656.2  413.12  4662.7  410.99  4693.6  407.17
    4721  402.11  4736.8  401.33  4743.3  399.33  4766.3  396.04    4780  395.22
  4795.8   391.6    4839     387  4860.6  382.55    4870  382.39  4882.2     380
  4898.1  379.16  4904.5  377.83  4957.1  375.35  4994.5  375.35  5002.3   373.9
  5005.1   373.4  5008.3   373.9  5050.6  375.36  5135.5  375.71  5262.8  378.62
  5319.3   381.4    5489   395.5  5500.7  397.41  5531.5  399.83  5573.9  405.85
#Mann= 4 ,-1 , 0
  4605.1     .12       0  5002.3     .07       0  5008.3     .12       0
  5500.7     .16       0
Bank Sta=4898.1,5262.8
XS Rating Curve= 0 ,0
Exp/Cntr=0.3,0.1

Type RM Length L Ch R = 1 ,31450   ,317,317,317
BEGIN DESCRIPTION:
MILL BRANCH 53.0
END DESCRIPTION:
XS GIS Cut Line= 3
      3675899.63     10771960.22      3675649.61     10771560.19
      3675449.64     10771410.21
#Sta/Elev= 30
  4551.8  402.76  4610.8  397.88  4653.8  390.05  4675.1  387.45  4690.4  384.07
  4740.5  377.37  4754.1   375.8  4848.4  374.22  4863.7  374.94  4921.5   373.3
  4942.8  374.09  4970.4  372.85  4973.2  372.35  4976.4  372.85  5030.8  373.41
  5080.8  377.11    5110  380.45  5116.2  382.18  5130.8  382.99  5145.4  386.07
  5151.7  386.15  5180.8   392.7  5187.1  392.99  5195.4  396.07  5216.2  398.81
  5223.5  401.71  5237.1  403.83  5245.4  407.05    5260  410.55  5273.5  411.58
#Mann= 4 ,-1 , 0
  4551.8     .12       0  4970.4     .07       0  4976.4     .12       0
  5180.8     .16       0
Bank Sta=4740.5,5080.8
XS Rating Curve= 0 ,0
Exp/Cntr=0.3,0.1

Type RM Length L Ch R = 1 ,31133   ,874,874,874
BEGIN DESCRIPTION:
MILL BRANCH 52.0
END DESCRIPTION:
XS GIS Cut Line= 2
       3676309.6     10771628.75      3675387.67     10771107.88
#Sta/Elev= 30
  4430.9  416.61  4476.6  414.65  4534.2  408.74  4577.5  400.05  4614.7  396.07
  4626.5  393.11  4664.1  387.95  4695.1  385.39  4775.5  374.99  4809.9  373.41
  4922.5  373.52  4981.7   371.9  4987.5  371.52  4990.7  369.81  4993.4  369.31
  4996.7  369.81    5025  372.57  5052.4  371.93  5127.6  374.35  5192.5  379.79
  5223.4  383.74  5235.8  383.15  5280.8  390.22  5312.9  392.58  5384.2  399.36
  5407.2  402.32  5413.4  404.51  5419.2  404.28  5472.6   411.9  5489.8  413.05
#Mann= 5 ,-1 , 0
  4430.9     .16       0  4476.6     .12       0  4990.7     .07       0
  4996.7     .12       0  5312.9     .16       0
Bank Sta=4775.5,5127.6
XS Rating Curve= 0 ,0
Exp/Cntr=0.3,0.1

Type RM Length L Ch R = 1 ,30259   ,265,265,265
BEGIN DESCRIPTION:
MILL BRANCH 51.0
END DESCRIPTION:
XS GIS Cut Line= 4
      3676372.09     10771545.42      3676028.33     10770623.53
      3675866.88     10770519.36      3674924.34     10770904.71
#Sta/Elev= 30
    3900  415.65  4032.1  408.53  4178.4  395.13  4208.7  389.74    4355  377.55
  4551.2   371.6  4716.7  372.92  4998.4  366.97  5001.1  366.47  5004.4  366.97
  5328.1  372.12  5369.4  372.68  5472.8  376.89  5536.4  388.31  5559.2  390.13
  5580.8  395.86  5637.1  397.99  5702.1  399.31  5769.1  395.92  5815.6  395.66
    5857  395.09    5905  399.88  5910.5  395.41  5926.6  394.59  5934.5     400
  5958.5  407.36  6019.9  414.27  6031.5  414.95  6070.8  416.13  6094.3  413.95
#Mann= 9 ,-1 , 0
    3900     .16       0  4998.4     .07       0  5004.4     .16       0
  5369.4     .16       0  5637.1     .05       0  5769.1     .12       0
  5815.6     .05       0  6019.9     .16       0  6031.5     .12       0
#XS Ineff= 2 , 0
         4706.82  381.18
Permanent Ineff=
       F       F
Bank Sta=4716.7,5328.1
XS Rating Curve= 0 ,0
Exp/Cntr=0.3,0.1

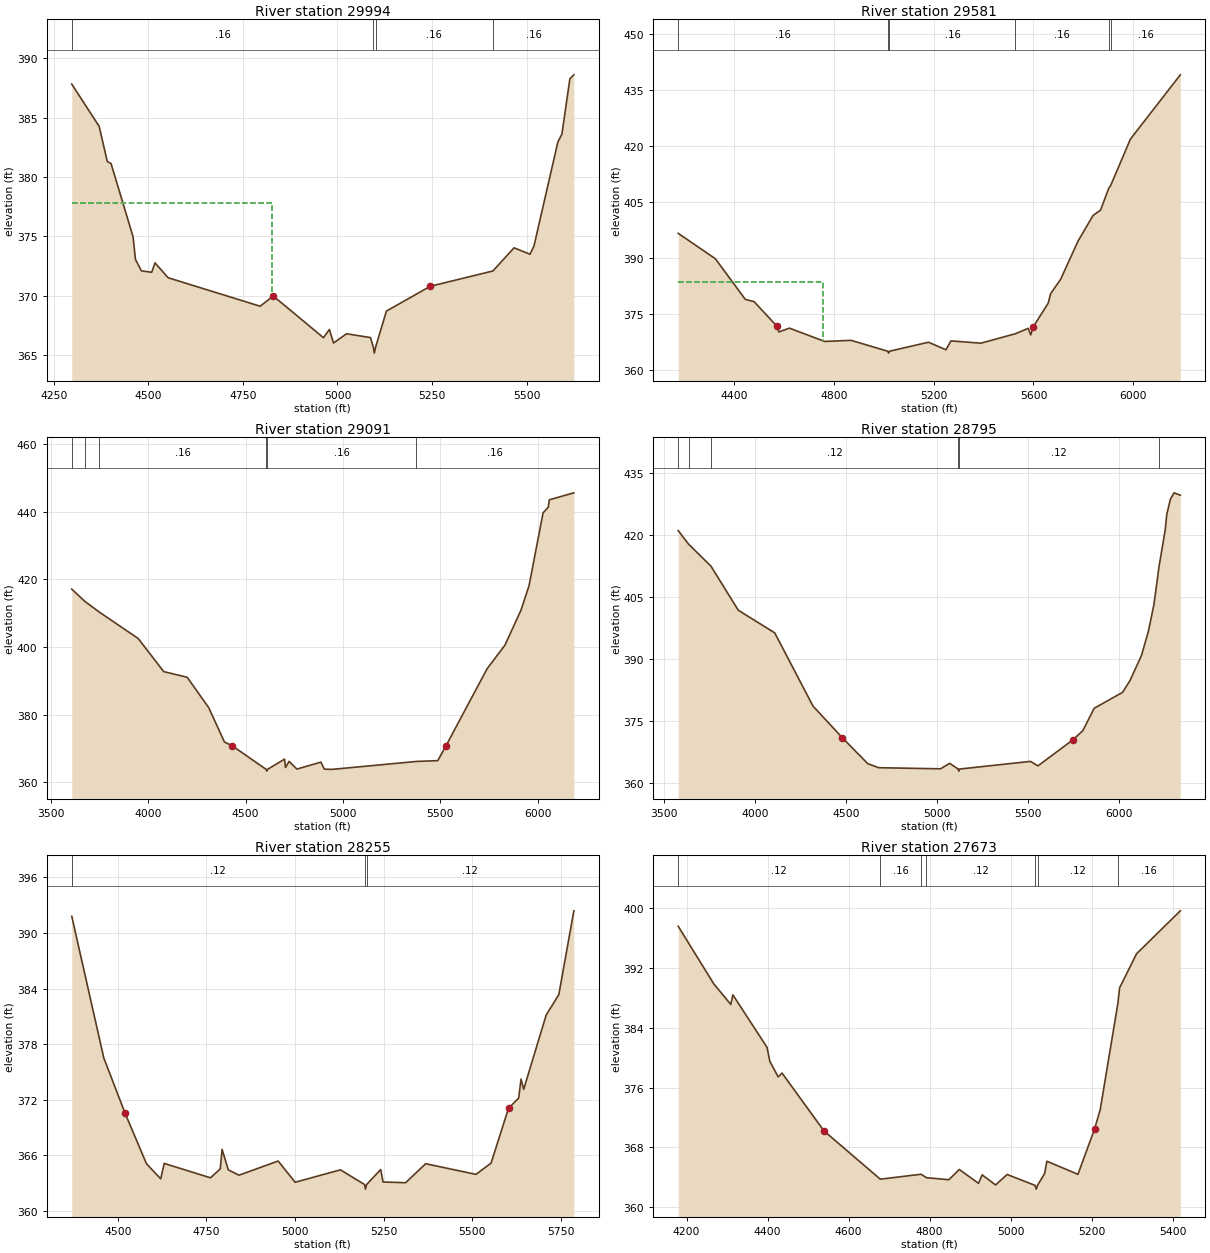
Type RM Length L Ch R = 1 ,29994   ,413,413,413
BEGIN DESCRIPTION:
MILL BRANCH 50.0
END DESCRIPTION:
XS GIS Cut Line= 3
      3676599.64     10770660.21      3675999.61     10770310.19
      3675399.62     10770110.19
#Sta/Elev= 30
  4297.7  387.82  4370.1  384.26  4391.6   381.3  4401.5  381.13  4459.8  374.95
    4466  373.06  4481.7  372.09    4509  371.97  4517.7  372.76  4552.4  371.51
  4795.6  369.11  4830.3  369.97    4963  366.46  4978.7  367.15  4989.5  366.01
    5024  366.79  5087.2  366.47  5094.8  365.66  5097.5  365.16  5100.8  365.66
  5129.4   368.7  5245.3  370.79    5411  372.08  5466.7  374.03  5508.9  373.49
  5519.4  374.18  5582.7  382.96  5593.2   383.6  5614.3  388.26  5624.8   388.6
#Mann= 4 ,-1 , 0
  4297.7     .16       0  5094.8     .07       0  5100.8     .16       0
    5411     .16       0
#XS Ineff= 2 , 0
         4826.36  377.77
Permanent Ineff=
       F       F
Bank Sta=4830.3,5245.3
XS Rating Curve= 0 ,0
Exp/Cntr=0.3,0.1

Type RM Length L Ch R = 1 ,29581   ,490,490,490
BEGIN DESCRIPTION:
MILL BRANCH 49.0
END DESCRIPTION:
XS GIS Cut Line= 3
       3676749.6     10770510.18      3676149.61     10769960.19
      3674949.64     10769960.19
#Sta/Elev= 30
  4175.2  396.72  4324.1  389.92  4444.3  379.03  4479.5  378.43  4571.4  371.81
  4578.8  370.32  4621.3  371.33  4762.5  367.77  4868.6  368.06  5016.1  365.14
  5018.9  364.64  5022.1  365.14  5179.1  367.56  5249.1  365.54  5269.1  367.92
  5389.1   367.3  5527.9  369.84  5579.1  371.27  5589.1  369.53  5599.1  371.67
  5659.1  378.01  5669.1  380.57  5709.1  384.41  5779.1  394.67  5839.1   401.5
  5869.1  402.94  5902.2   408.8  5909.2  409.45  5989.1  421.97  6189.1  439.17
#Mann= 6 ,-1 , 0
  4175.2     .16       0  5016.1     .07       0  5022.1     .16       0
  5527.9     .16       0  5902.2     .12       0  5909.2     .16       0
#XS Ineff= 2 , 0
         4754.26  383.63
Permanent Ineff=
       F       F
Bank Sta=4571.4,5599.1
XS Rating Curve= 0 ,0
Exp/Cntr=0.3,0.1

Type RM Length L Ch R = 1 ,29091   ,296,296,296
BEGIN DESCRIPTION:
MILL BRANCH 48.0
END DESCRIPTION:
XS GIS Cut Line= 3
      3677379.07     10769435.59      3675799.17     10769609.21
      3674835.66     10769834.89
#Sta/Elev= 30
  3607.1  417.07  3672.6  413.53  3746.8  410.36  3948.6  402.46  4079.4  392.69
  4200.1  391.01  4310.8  382.02  4391.3  371.89  4431.9  370.74    4606  363.77
  4608.7  363.27    4612  363.77    4700  366.81  4705.1  364.35  4723.2  366.15
  4763.5  363.88  4887.2  365.93  4904.3  363.85  4944.6  363.79  5377.6  366.13
  5487.3  366.37  5529.8   370.8  5740.4  393.52  5832.2  400.51    5915  410.91
  5956.1  418.11    6028  439.61  6054.8  441.31  6059.9  443.47  6186.1  445.54
#Mann= 6 ,-1 , 0
  3607.1     .16       0  3672.6     .05       0  3746.8     .16       0
    4606     .07       0    4612     .16       0  5377.6     .16       0
Bank Sta=4431.9,5529.8
XS Rating Curve= 0 ,0
Exp/Cntr=0.3,0.1

Type RM Length L Ch R = 1 ,28795   ,540,540,540
BEGIN DESCRIPTION:
MILL BRANCH 47.0
END DESCRIPTION:
XS GIS Cut Line= 3
      3677379.05     10769218.58      3675851.25     10769322.75
      3674636.01     10769131.78
#Sta/Elev= 30
  3576.6  421.05  3633.3  417.79  3756.7  412.44  3906.8  401.77  4107.3  396.29
  4317.8  378.55  4478.1  370.93  4618.5  364.62  4678.6  363.62  5019.4  363.35
  5069.5  364.68  5116.7  363.29  5119.5  362.79  5122.7  363.29  5514.5  365.15
    5555  364.06  5747.3  370.37  5801.9  372.59  5864.5  378.02  6020.7  381.88
  6062.3  384.81  6124.9  390.86  6162.4  396.64  6192.7  403.07  6221.4  412.42
  6255.1  421.22  6263.6  424.96  6283.8  428.69  6304.1  430.21  6338.1  429.64
#Mann= 6 ,-1 , 0
  3576.6     .16       0  3633.3     .05       0  3756.7     .12       0
  5116.7     .07       0  5122.7     .12       0  6221.4     .16       0
Bank Sta=4478.1,5747.3
XS Rating Curve= 0 ,0
Exp/Cntr=0.3,0.1

Type RM Length L Ch R = 1 ,28255   ,582,582,582
BEGIN DESCRIPTION:
MILL BRANCH 46.0
END DESCRIPTION:
XS GIS Cut Line= 3
      3676649.56     10768810.19      3676049.61     10768860.19
      3675449.59     10768310.17
#Sta/Elev= 30
  4370.5  391.79  4460.8  376.52    4521  370.54  4581.2  365.11  4621.3  363.48
  4631.4  365.14  4761.8  363.59  4789.4  364.56  4794.4  366.66    4812  364.45
  4842.1  363.87  4952.5   365.4  5000.6  363.11  5128.2  364.45  5196.1  362.87
  5198.9  362.37  5202.1  362.87  5241.7  364.48  5248.5  363.14    5312  363.06
  5368.7  365.11  5510.5  363.96  5553.1  365.18  5602.4   371.1  5630.8  372.18
  5637.6  374.23    5645  373.13  5708.5  381.14  5744.2  383.35  5786.5  392.38
#Mann= 3 ,-1 , 0
  4370.5     .12       0  5196.1     .07       0  5202.1     .12       0
Bank Sta=4521,5602.4
XS Rating Curve= 0 ,0
Exp/Cntr=0.3,0.1

Type RM Length L Ch R = 1 ,27673   ,454,454,454
BEGIN DESCRIPTION:
MILL BRANCH 45.0
END DESCRIPTION:
XS GIS Cut Line= 2
      3676849.55     10768515.46      3675643.76      10768229.2
#Sta/Elev= 30
  4179.4  397.58  4266.9   389.9  4309.1  387.13  4314.3  388.41  4398.7  381.38
  4405.5  379.52    4426  377.45  4435.7  377.95  4539.1  370.22  4678.1  363.76
  4778.9  364.42  4792.2  363.96  4847.4  363.69  4873.2  365.06  4920.5  363.21
  4929.6  364.34  4962.7  362.99  4991.3  364.39  5060.2  362.93    5063  362.43
  5066.2  362.93  5083.8  364.52  5089.3  366.16    5166  364.41  5207.1  370.47
  5221.1  373.08  5264.5  387.24  5268.8  389.34  5310.6   393.9  5418.7  399.65
#Mann= 7 ,-1 , 0
  4179.4     .12       0  4678.1     .16       0  4778.9     .07       0
  4792.2     .12       0  5060.2     .07       0  5066.2     .12       0
  5264.5     .16       0
Bank Sta=4539.1,5207.1
XS Rating Curve= 0 ,0
Exp/Cntr=0.3,0.1

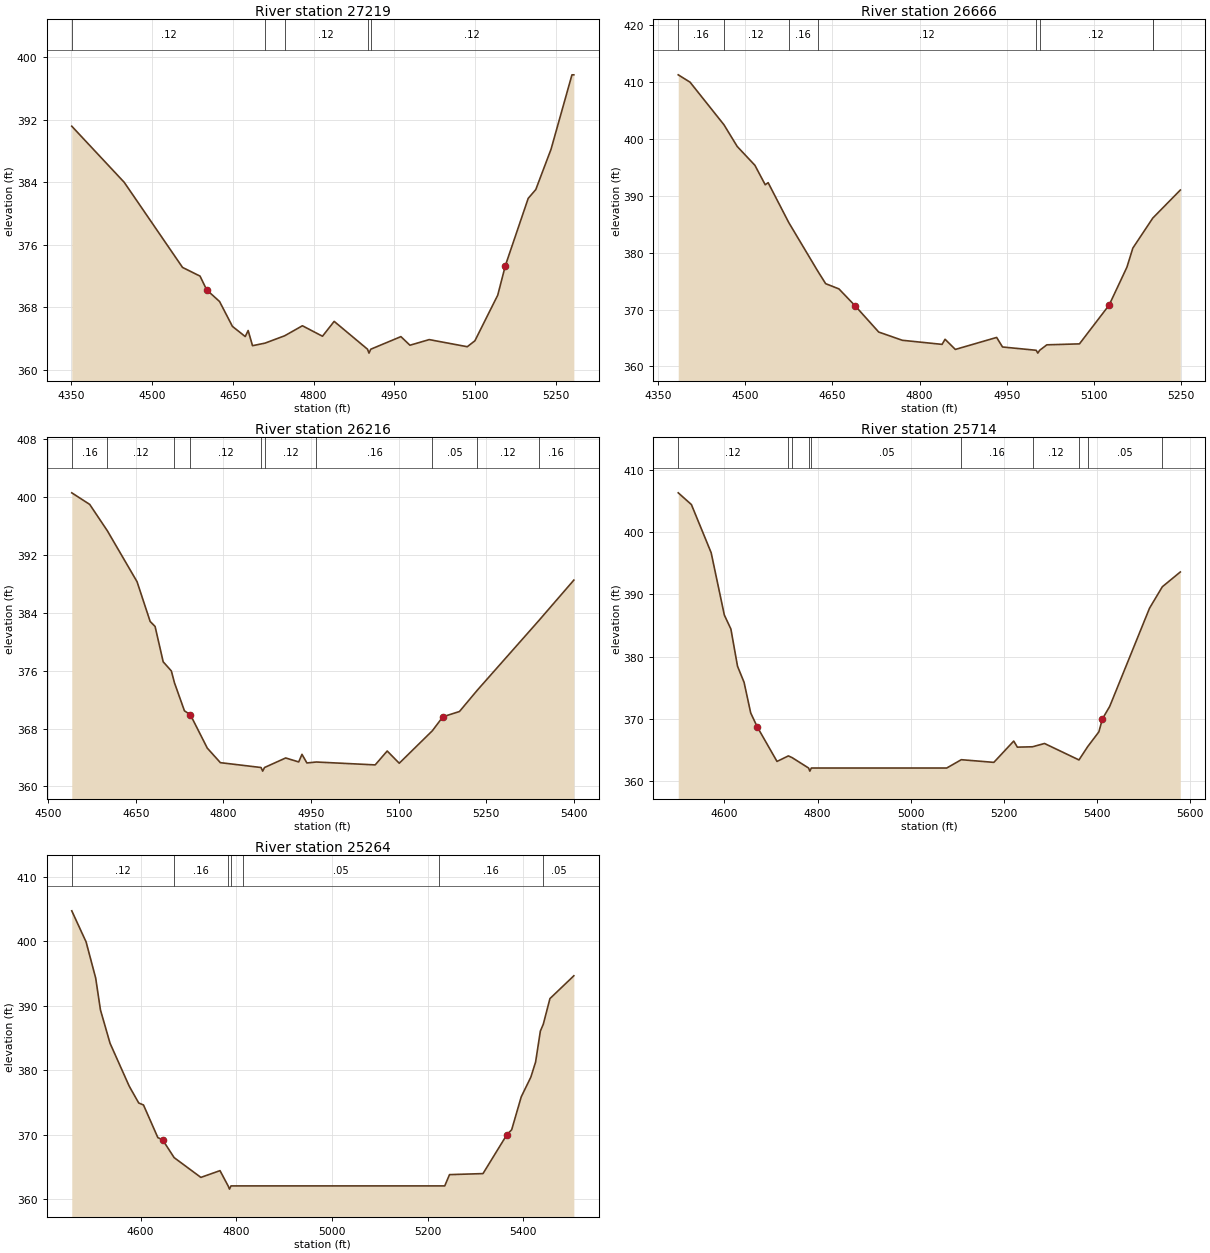
Type RM Length L Ch R = 1 ,27219   ,553,553,553
BEGIN DESCRIPTION:
MILL BRANCH 44.0
END DESCRIPTION:
XS GIS Cut Line= 3
       3676749.6     10768210.19      3676149.61     10767960.19
      3675949.63     10767760.21
#Sta/Elev= 30
  4350.8  391.18  4448.3     384  4556.6  373.12  4589.1  372.01  4601.6  370.24
  4625.4  368.76  4649.3  365.58  4673.1  364.28  4678.5  365.05  4686.6  363.11
  4709.9  363.44  4746.4  364.38  4779.3  365.66  4816.6  364.32  4838.3  366.22
  4900.3  362.66    4903  362.16  4906.3  362.66  4962.3  364.27  4979.1  363.17
  5014.9  363.89  5085.6  362.98  5099.8  363.74  5142.2  369.57  5156.4  373.36
  5198.8  381.95  5212.9  383.08  5241.2  388.23  5280.1  397.75  5283.6  397.75
#Mann= 5 ,-1 , 0
  4350.8     .12       0  4709.9     .16       0  4746.4     .12       0
  4900.3     .07       0  4906.3     .12       0
Bank Sta=4601.6,5156.4
XS Rating Curve= 0 ,0
Exp/Cntr=0.3,0.1

Type RM Length L Ch R = 1 ,26666   ,450,450,450
BEGIN DESCRIPTION:
MILL BRANCH 43.0
END DESCRIPTION:
XS GIS Cut Line= 3
      3676949.65      10767760.2      3676349.61     10767660.19
      3676099.58     10767610.18
#Sta/Elev= 30
  4384.9  411.29  4405.2     410  4463.5  402.51  4486.3  398.69  4516.7  395.38
  4534.5  391.95  4539.5  392.32  4574.9  385.31  4624.5  376.81  4638.4  374.55
  4661.2  373.63  4689.1  370.65  4729.6  366.04  4770.2  364.59  4838.6  363.87
  4843.7  364.77  4861.4  362.98  4932.4  365.09  4942.5  363.41  5000.4  362.83
  5003.2  362.33  5006.4  362.83  5018.7  363.79  5074.8  363.96  5125.8  370.78
  5156.4  377.45  5166.6  380.81  5200.7  386.06  5200.8  386.08  5248.2  391.02
#Mann= 8 ,-1 , 0
  4384.9     .16       0  4463.5     .12       0  4574.9     .16       0
  4624.5     .12       0  5000.4     .07       0  5006.4     .12       0
  5200.7     .16       0  5200.8     .12       0
Bank Sta=4689.1,5125.8
XS Rating Curve= 0 ,0
Exp/Cntr=0.3,0.1

Type RM Length L Ch R = 1 ,26216   ,502,502,502
BEGIN DESCRIPTION:
MILL BRANCH 42.0
END DESCRIPTION:
XS GIS Cut Line= 3
      3676949.61     10767510.19      3676549.61     10767310.19
      3676149.63     10767210.19
#Sta/Elev= 30
  4540.5  400.57  4571.2  398.97  4601.6   395.3  4652.3  388.28  4674.7  382.79
  4683.1  382.11    4697  377.22    4711  375.95  4716.3  374.32  4733.4  370.44
  4743.5  369.91  4772.5  365.29  4794.9  363.28  4864.5  362.61  4867.3  362.11
  4870.5  362.61  4906.7  363.93    4929  363.38  4934.6  364.43    4943  363.24
  4959.3  363.37  5059.9  362.97  5080.5  364.89  5101.1   363.2  5157.8  367.69
  5175.8  369.62  5204.2  370.35  5234.8   373.3  5339.6  382.87    5400  388.51
#Mann= 10 ,-1 , 0
  4540.5     .16       0  4601.6     .12       0  4716.3     .16       0
  4743.5     .12       0  4864.5     .07       0  4870.5     .12       0
  4959.3     .16       0  5157.8     .05       0  5234.8     .12       0
  5339.6     .16       0
Bank Sta=4743.5,5175.8
XS Rating Curve= 0 ,0
Exp/Cntr=0.3,0.1

Type RM Length L Ch R = 1 ,25714   ,450,450,450
BEGIN DESCRIPTION:
MILL BRANCH 41.0
END DESCRIPTION:
XS GIS Cut Line= 3
      3676899.62     10766460.18      3676549.61     10766810.19
      3676049.59      10767110.2
#Sta/Elev= 30
  4500.7  406.36    4529  404.47  4571.4  396.72  4599.7  386.69  4613.8  384.43
    4628  378.45  4642.1  375.85  4656.3  370.93  4670.4  368.68  4712.8  363.12
  4737.2  364.01  4745.3  363.73  4780.6  362.06  4783.3  361.56  4786.6  362.06
  5077.3  362.06  5108.5   363.4  5178.4  362.97  5221.1   366.4  5228.9  365.42
  5261.5  365.48  5287.2  366.01  5361.2  363.36  5379.7  365.48  5403.9  367.88
  5411.6  369.98  5427.2  371.98  5512.7  387.79  5540.2  391.24  5578.8  393.62
#Mann= 10 ,-1 , 0
  4500.7     .12       0  4737.2     .16       0  4745.3     .05       0
  4780.6    .035       0  4786.6     .05       0  5108.5     .16       0
  5261.5     .12       0  5361.2     .16       0  5379.7     .05       0
  5540.2     .12       0
Bank Sta=4670.4,5411.6
XS Rating Curve= 0 ,0
Exp/Cntr=0.3,0.1

Type RM Length L Ch R = 1 ,25264   ,422,422,422
BEGIN DESCRIPTION:
MILL BRANCH 40.0
END DESCRIPTION:
XS GIS Cut Line= 3
      3676899.62     10766410.19      3676349.61     10766410.19
      3675849.62     10766410.19
#Sta/Elev= 30
  4455.9  404.75  4485.9  399.92  4505.9  394.32  4515.9  389.37  4535.9  384.21
  4575.9  377.56  4595.9  374.93  4605.9  374.62  4635.9  369.56  4645.9  369.21
    4670  366.45  4725.9  363.38  4765.9  364.43  4782.9  362.06  4785.7  361.56
  4788.9  362.06    4815  362.06  5222.9  362.06  5235.9  362.06  5245.9  363.81
  5315.9  363.97  5365.9  370.01  5375.9  370.78  5395.9  375.89  5415.9  378.93
  5425.9  381.28  5435.9  386.09    5442  387.15  5455.9  391.13  5505.9  394.67
#Mann= 7 ,-1 , 0
  4455.9     .12       0    4670     .16       0  4782.9    .033       0
  4788.9     .16       0    4815     .05       0  5222.9     .16       0
    5442     .05       0
Bank Sta=4645.9,5365.9
XS Rating Curve= 0 ,0
Exp/Cntr=0.3,0.1