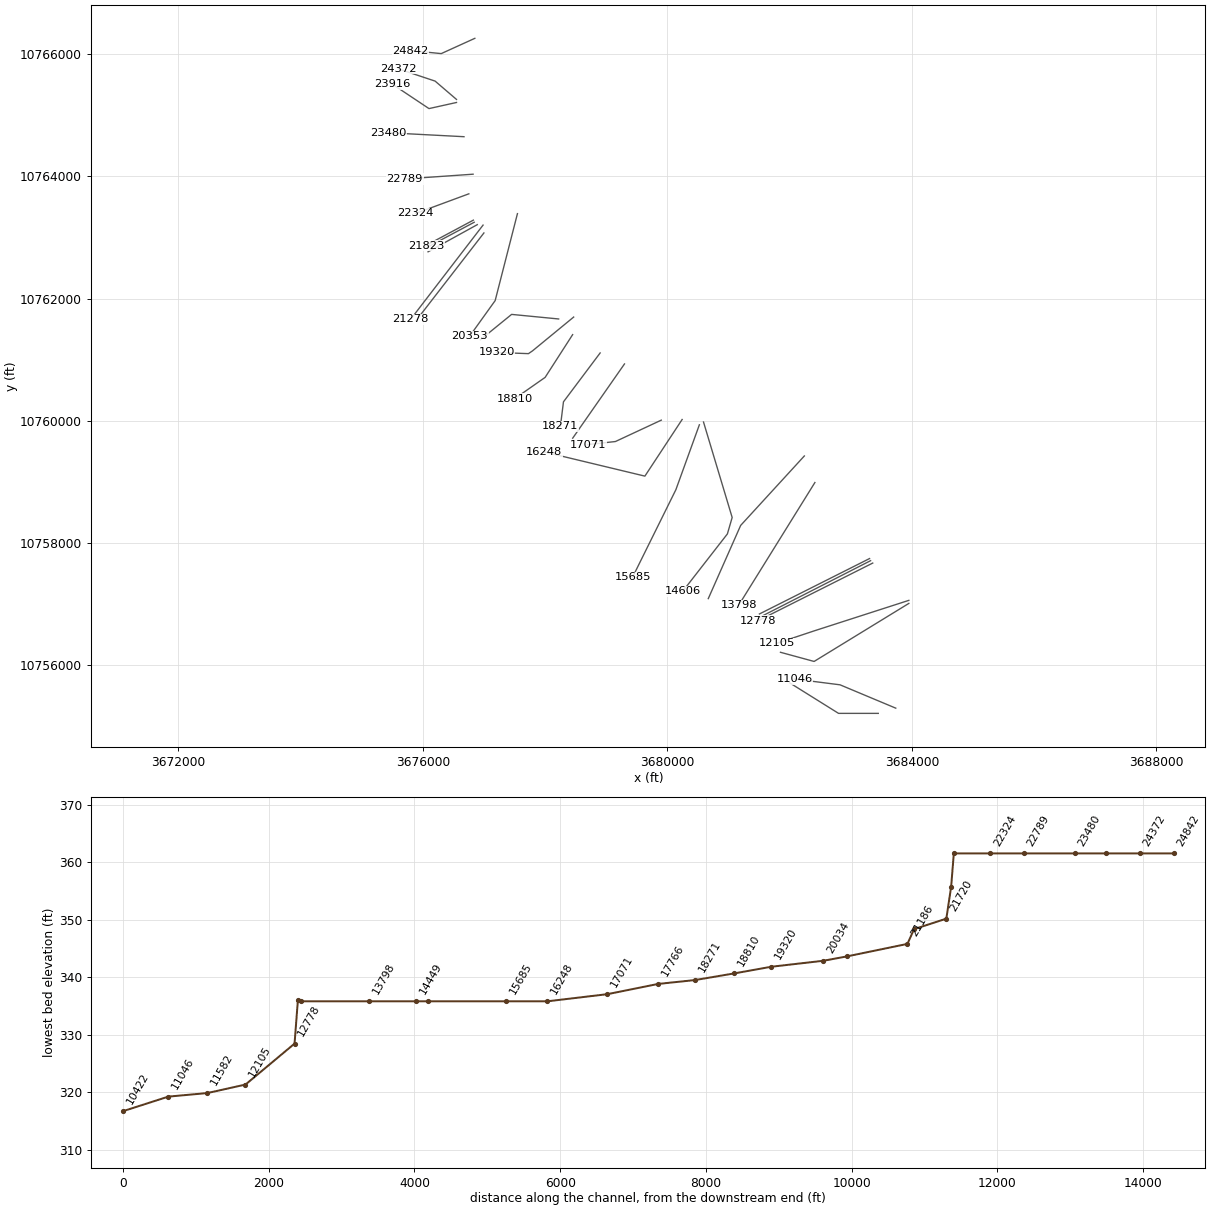
HEC-RAS study MILL BRANCH.prj: MILL BRANCH Base Level Engineering

--- MILL BRANCH.g01 (geometry) --- (continued)

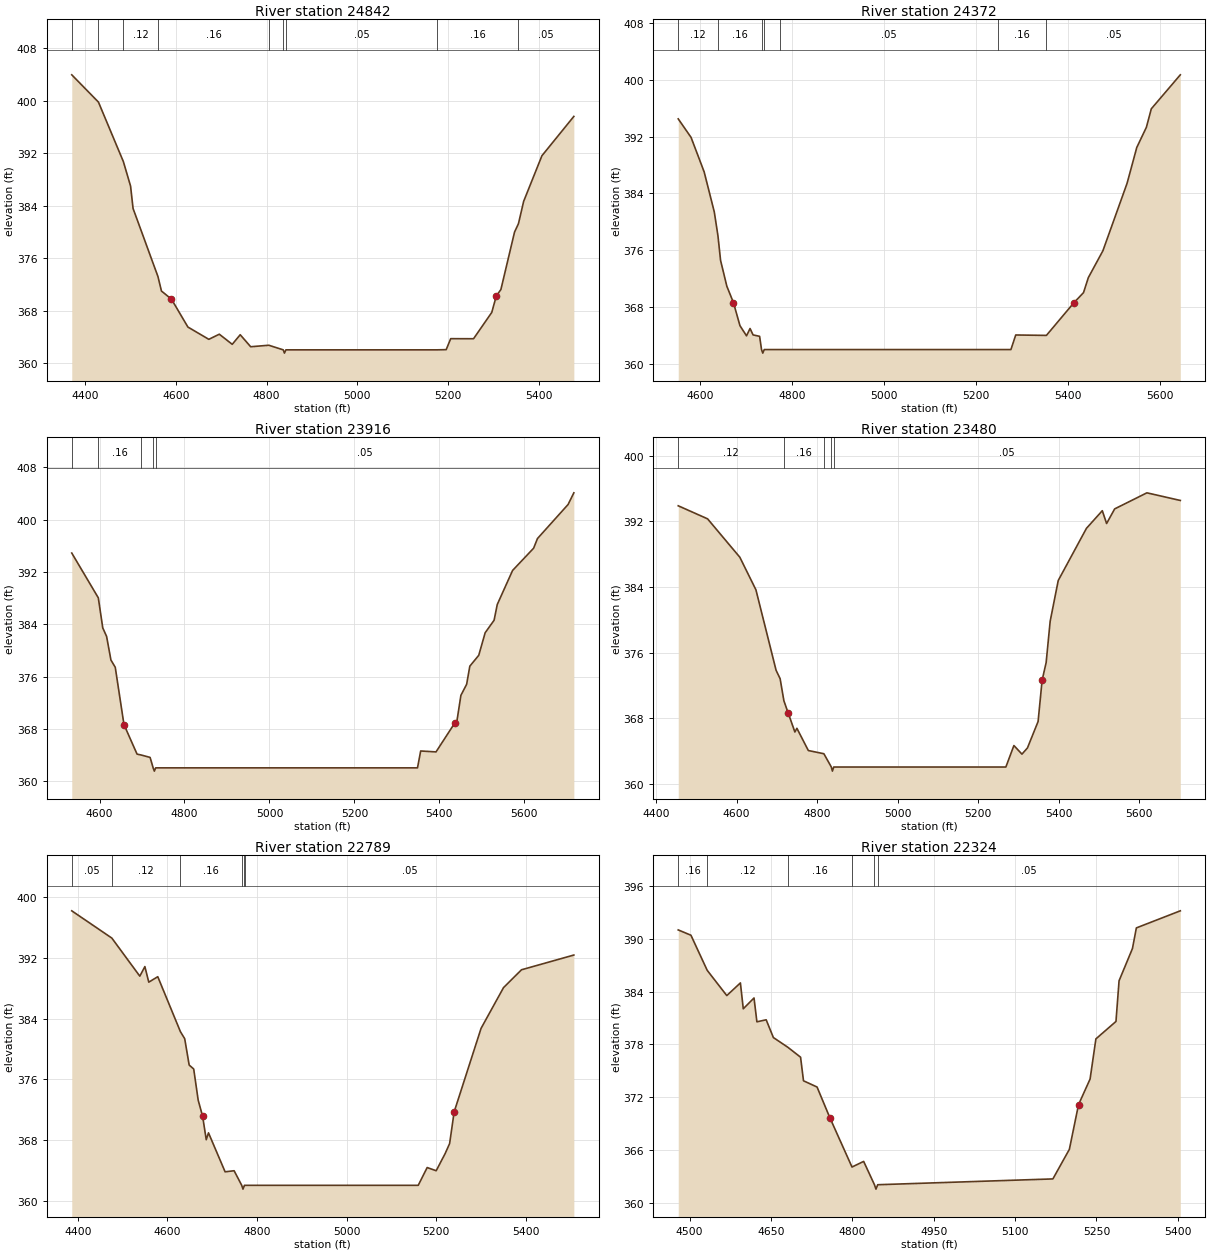
Type RM Length L Ch R = 1 ,24842   ,470,470,470
BEGIN DESCRIPTION:
MILL BRANCH 39.0
END DESCRIPTION:
XS GIS Cut Line= 3
      3676849.63      10766260.2      3676299.61     10766010.19
      3675799.58     10766060.19
#Sta/Elev= 30
  4370.6  403.92  4429.4  399.77  4484.3  390.72  4500.2  386.99  4505.7  383.58
  4560.6  373.21  4568.3  371.01  4590.3  369.78  4626.6  365.53  4672.7  363.66
  4695.8  364.44  4724.3   362.9  4741.9  364.36    4765  362.53  4804.9  362.76
  4836.7  362.06  4839.4  361.56  4842.7  362.06  5175.9  362.06  5195.9  362.09
  5205.9  363.76  5256.2  363.75  5296.4  367.76  5306.4  370.26  5316.5  371.24
  5346.6  379.99  5355.2  381.26  5366.7  384.67  5406.9   391.6  5477.3  397.59
#Mann= 9 ,-1 , 0
  4370.6     .12       0  4429.4     .16       0  4484.3     .12       0
  4560.6     .16       0  4804.9     .05       0  4836.7    .033       0
  4842.7     .05       0  5175.9     .16       0  5355.2     .05       0
Bank Sta=4590.3,5306.4
XS Rating Curve= 0 ,0
Exp/Cntr=0.3,0.1

Type RM Length L Ch R = 1 ,24372   ,456,456,456
BEGIN DESCRIPTION:
MILL BRANCH 38.0
END DESCRIPTION:
XS GIS Cut Line= 3
       3676549.6      10765260.2      3676199.61     10765560.19
      3675599.63     10765760.18
#Sta/Elev= 30
  4551.9  394.48  4579.9  391.87  4608.4  387.02  4630.4  381.41  4638.4  378.05
  4644.1  374.59  4657.8  370.95  4672.1  368.67  4686.3  365.42  4700.6  363.99
  4708.3  365.02  4714.9  364.12  4729.1  363.92  4733.3  362.06    4736  361.56
  4739.3  362.06  4773.3  362.06  5247.9  362.06  5276.4  362.06  5286.9  364.11
  5353.7  364.05  5413.4  368.63  5434.5  370.06    5445  372.17  5476.7  375.94
  5529.4  385.43  5550.5  390.46  5571.5  393.31  5582.1  395.89  5645.3  400.67
#Mann= 7 ,-1 , 0
  4551.9     .12       0  4638.4     .16       0  4733.3    .033       0
  4739.3     .16       0  4773.3     .05       0  5247.9     .16       0
  5353.7     .05       0
Bank Sta=4672.1,5413.4
XS Rating Curve= 0 ,0
Exp/Cntr=0.3,0.1

Type RM Length L Ch R = 1 ,23916   ,436,436,436
BEGIN DESCRIPTION:
MILL BRANCH 37.0
END DESCRIPTION:
XS GIS Cut Line= 3
      3676549.61     10765210.19      3676099.61     10765110.19
       3675499.6     10765510.19
#Sta/Elev= 30
  4534.6  394.91  4597.1  388.06  4607.6  383.46  4616.6  382.16  4626.8  378.55
    4637  377.44  4657.5  368.68  4688.3  364.16  4697.7  364.03    4719  363.66
  4726.2  362.06    4729  361.56  4732.2  362.06  5348.6  362.06  5356.1  364.64
  5392.2   364.5  5435.8  368.86  5441.8  369.38  5450.8  373.15  5464.3  374.84
  5471.8  377.61  5492.8  379.27  5507.9  382.72  5528.9  384.63  5536.4  387.04
  5572.5  392.25    5622  395.65  5631.1  397.13  5703.2  402.34  5716.7  404.12
#Mann= 5 ,-1 , 0
  4534.6     .12       0  4597.1     .16       0  4697.7     .05       0
  4726.2    .033       0  4732.2     .05       0
Bank Sta=4657.5,5435.8
XS Rating Curve= 0 ,0
Exp/Cntr=0.3,0.1

Type RM Length L Ch R = 1 ,23480   ,691,691,691
BEGIN DESCRIPTION:
MILL BRANCH 36.0
END DESCRIPTION:
XS GIS Cut Line= 2
      3676672.37     10764649.97      3675426.77     10764715.07
#Sta/Elev= 30
  4454.9   393.9  4527.8  392.31  4607.9  387.63  4647.9  383.66    4698  373.85
    4708  372.83  4717.4  370.13    4728  368.65  4744.7  366.33  4749.7  366.78
  4778.1  364.07  4816.7  363.68  4835.2  362.06  4837.9  361.56  4841.2  362.06
  5268.8  362.06  5288.8  364.68  5308.8  363.63  5322.5  364.39  5348.9  367.61
  5358.9  372.64  5368.9  374.79  5378.9  379.83  5398.9  384.79    5469  391.15
  5508.4   393.3  5519.1  391.74  5539.1  393.52  5619.2  395.48  5702.2  394.55
#Mann= 5 ,-1 , 0
  4454.9     .12       0  4717.4     .16       0  4816.7     .05       0
  4835.2    .033       0  4841.2     .05       0
Bank Sta=4728,5358.9
XS Rating Curve= 0 ,0
Exp/Cntr=0.3,0.1

Type RM Length L Ch R = 1 ,22789   ,465,465,465
BEGIN DESCRIPTION:
MILL BRANCH 35.0
END DESCRIPTION:
XS GIS Cut Line= 2
      3676821.11     10764036.29      3675703.03     10763958.28
#Sta/Elev= 30
  4386.4  398.19  4475.9   394.6  4538.3  389.59  4549.6  390.85  4558.3   388.8
  4578.4  389.52  4628.9  382.29  4638.5  381.36  4648.5  377.89  4658.6  377.37
  4668.6  373.27  4678.6  371.12  4686.6  368.06  4691.6  368.97  4728.7  363.84
  4748.8  363.98  4765.8  362.06  4768.6  361.56  4771.8  362.06  4772.9  362.06
  5159.8  362.06  5179.8   364.4  5199.9  363.98  5219.9  366.24  5229.9  367.56
    5240  371.72  5300.1  382.72  5350.2  388.08  5390.3  390.43  5507.2  392.37
#Mann= 6 ,-1 , 0
  4386.4     .05       0  4475.9     .12       0  4628.9     .16       0
  4765.8    .033       0  4771.8     .16       0  4772.9     .05       0
Bank Sta=4678.6,5240
XS Rating Curve= 0 ,0
Exp/Cntr=0.3,0.1

Type RM Length L Ch R = 1 ,22324   ,501,501,501
BEGIN DESCRIPTION:
MILL BRANCH 34.0
END DESCRIPTION:
XS GIS Cut Line= 2
      3676751.68     10763715.09      3675883.69     10763393.94
#Sta/Elev= 30
  4479.2  391.01  4502.6  390.41  4532.6  386.42  4568.7  383.55  4593.8  384.99
  4599.1  382.05  4618.9  383.28  4624.2  380.57  4641.3   380.8  4654.6  378.78
    4681  377.69  4704.7  376.55  4710.1  373.87  4735.1  373.16  4758.6  369.69
  4799.5  364.07    4821  364.71  4840.9  362.06  4843.7  361.56  4846.9  362.06
  5169.8  362.72  5200.2  366.08  5217.1  371.16  5238.4  374.07  5249.1  378.63
  5286.1  380.61  5291.8  385.23  5316.5   388.9  5323.7  391.24  5404.7  393.18
#Mann= 6 ,-1 , 0
  4479.2     .16       0  4532.6     .12       0    4681     .16       0
  4799.5     .05       0  4840.9    .033       0  4846.9     .05       0
Bank Sta=4758.6,5217.1
XS Rating Curve= 0 ,0
Exp/Cntr=0.3,0.1

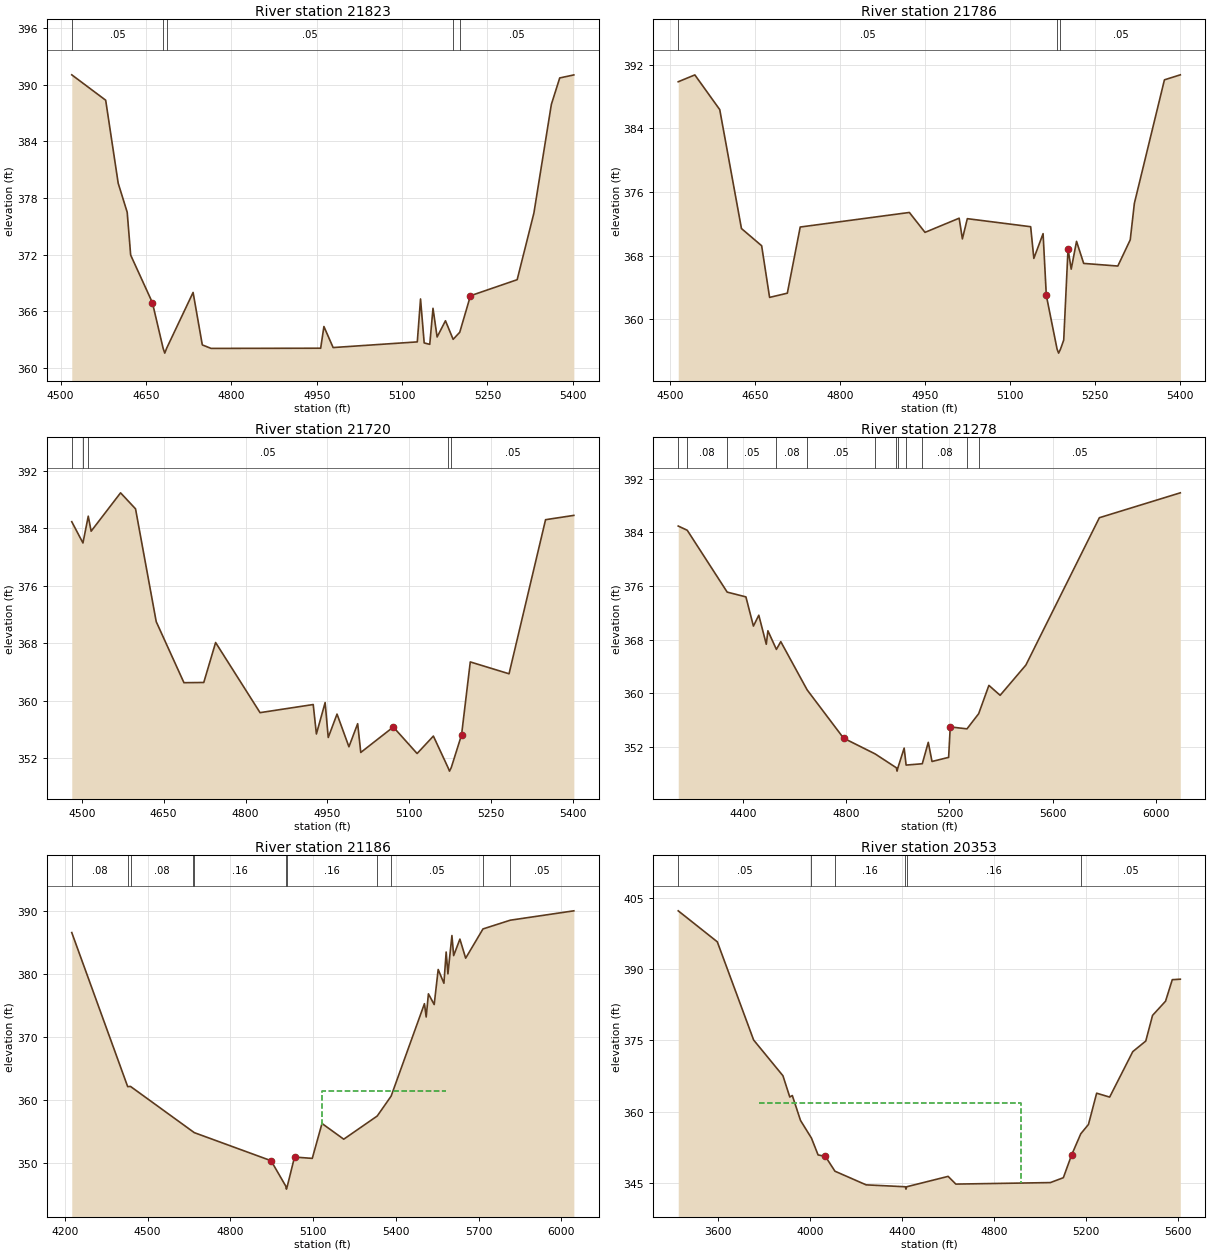
Type RM Length L Ch R = 1 ,21823   ,37,37,37
BEGIN DESCRIPTION:
Mapping XS 24fa8486
END DESCRIPTION:
XS GIS Cut Line= 2
      3676825.49     10763284.26      3676047.76     10762867.62
#Sta/Elev= 30
  4519.5  391.05  4579.1  388.36  4601.1  379.56  4616.9  376.49    4623  371.95
  4661.2  366.91  4680.1  362.06  4682.9  361.56  4686.1  362.06  4732.7  367.99
  4748.9  362.43  4764.4  362.06  4956.9  362.08  4962.6  364.38  4978.8  362.15
  5126.7  362.75  5132.4   367.3  5138.8  362.64  5148.6  362.49  5154.3  366.31
  5161.5  363.27  5176.2  364.99  5189.7  363.02  5201.3  363.77  5220.1  367.64
  5302.2  369.34  5331.6   376.4  5362.3  387.92    5377  390.72  5401.8  391.04
#Mann= 5 ,-1 , 0
  4519.5     .05       0  4680.1     .03       0  4686.1     .05       0
  5189.7     .16       0  5201.3     .05       0
Bank Sta=4661.2,5220.1
XS Rating Curve= 0 ,0
Exp/Cntr=0.3,0.1

Type RM Length L Ch R = 1 ,21786   ,66,66,66
BEGIN DESCRIPTION:
Mapping XS 6177a80e
END DESCRIPTION:
XS GIS Cut Line= 2
      3676839.41     10763249.55      3676058.17     10762832.89
#Sta/Elev= 30
  4514.5  389.84  4543.8   390.7  4587.7  386.34    4626   371.4  4661.6  369.24
  4675.6  362.75  4706.9  363.28  4729.6  371.59  4922.1  373.42  4949.7  370.92
  5009.9   372.7  5015.6   370.1  5024.3  372.64    5136  371.63  5141.6  367.65
  5157.9  370.76  5163.6     363  5182.6  356.25  5185.3  355.75  5188.6  356.25
  5194.3  357.39  5201.9  368.85  5207.5   366.3  5216.9  369.79  5229.5  367.02
  5289.7  366.69  5311.6  369.98  5318.9  374.57  5371.9  390.08  5399.9  390.71
#Mann= 3 ,-1 , 0
  4514.5     .05       0  5182.6     .03       0  5188.6     .05       0
Bank Sta=5163.6,5201.9
XS Rating Curve= 0 ,0
Exp/Cntr=0.3,0.1

Type RM Length L Ch R = 1 ,21720   ,442,442,442
BEGIN DESCRIPTION:
MILL BRANCH 33.0
END DESCRIPTION:
XS GIS Cut Line= 2
      3676889.56     10763210.17      3676084.29     10762765.89
#Sta/Elev= 30
  4481.7  384.93  4502.2  381.97  4511.9   385.7  4517.2  383.61  4571.1  388.95
  4598.5  386.72  4636.4  371.02  4687.2  362.52  4723.5  362.55  4745.2  368.11
  4826.6  358.35    4924  359.48  4929.8  355.38  4945.8  359.75  4951.5  354.89
  4967.6  358.15  4989.4   353.6  5005.4  356.81  5011.1  352.81  5070.7  356.35
  5114.3  352.66  5144.1  355.09  5170.9  350.71  5173.6  350.21  5176.9  350.71
  5195.7  355.25  5211.7  365.41  5282.7  363.76  5349.6  385.21  5401.4  385.81
#Mann= 5 ,-1 , 0
  4481.7     .05       0  4502.2     .08       0  4511.9     .05       0
  5170.9     .03       0  5176.9     .05       0
Bank Sta=5070.7,5195.7
XS Rating Curve= 0 ,0
Exp/Cntr=0.3,0.1

Type RM Length L Ch R = 1 ,21278   ,92,92,92
BEGIN DESCRIPTION:
MILL BRANCH 32.0
END DESCRIPTION:
XS GIS Cut Line= 2
      3676984.19     10763203.03      3675800.15     10761661.34
#Sta/Elev= 30
    4150  384.92  4184.9  384.29  4339.6  375.07    4412  374.36  4441.1  370.01
  4461.9  371.63  4490.9   367.3  4497.2  369.31  4530.1  366.53    4547  367.69
  4649.1   360.5    4790  353.31  4912.2  350.96  4994.5  348.89  4997.3  348.39
  5000.5  348.89  5024.7  351.82  5032.3  349.29  5094.9  349.49  5118.1  352.68
  5132.6  349.83  5196.9  350.44  5203.2  354.98    5268  354.69  5313.2  356.95
  5352.8  361.17  5396.3  359.69    5496   364.2  5780.5  386.16  6093.9  389.87
#Mann= 12 ,-1 , 0
    4150     .05       0  4184.9     .08       0  4339.6     .05       0
  4530.1     .08       0  4649.1     .05       0  4912.2     .08       0
  4994.5     .07       0  5000.5     .08       0  5032.3     .05       0
  5094.9     .08       0    5268     .16       0  5313.2     .05       0
Bank Sta=4790,5203.2
XS Rating Curve= 0 ,0
Exp/Cntr=0.3,0.1

Type RM Length L Ch R = 1 ,21186   ,833,833,833
BEGIN DESCRIPTION:
MILL BRANCH 31.0
END DESCRIPTION:
XS GIS Cut Line= 2
      3676998.05     10763074.51      3675884.64     10761635.07
#Sta/Elev= 30
  4225.4  386.62  4428.1  362.12  4438.4  362.15  4663.3     355  4669.7   354.8
  4947.7  350.34  5000.8  346.32  5003.5  345.82  5006.8  346.32  5032.8  350.92
  5097.1  350.71  5132.4  356.26  5211.2  353.76  5332.6  357.45  5382.9  360.61
  5503.7  375.31    5510   373.2  5518.1  376.88    5539  375.17  5553.5  380.75
  5574.3  378.56  5582.4  383.53  5588.8  380.05  5603.3  386.15  5609.6  382.96
  5632.2  385.58  5653.1  382.55  5715.9   387.2  5814.8  388.59  6045.2  390.08
#Mann= 11 ,-1 , 0
  4225.4     .08       0  4428.1     .05       0  4438.4     .08       0
  4663.3     .12       0  4669.7     .16       0  5000.8     .07       0
  5006.8     .16       0  5332.6     .16       0  5382.9     .05       0
  5715.9     .08       0  5814.8     .05       0
#XS Ineff= 1 ,-1
 5130.68 5582.39  361.48
Permanent Ineff=
       F
Bank Sta=4947.7,5032.8
XS Rating Curve= 0 ,0
Exp/Cntr=0.3,0.1

Type RM Length L Ch R = 1 ,20353   ,319,319,319
BEGIN DESCRIPTION:
MILL BRANCH 30.0
END DESCRIPTION:
XS GIS Cut Line= 3
      3677546.67      10763390.5       3677182.1      10761966.9
      3676765.42     10761385.29
#Sta/Elev= 30
  3426.5  402.33  3596.6  395.79  3754.6  375.09  3882.2  367.55    3912  363.06
    3923  363.38  3958.6  358.13  4006.3   354.4  4035.1  350.85  4066.8  350.55
  4108.5  347.42  4244.2  344.54  4414.8  344.14  4417.6  343.64  4420.8  344.14
  4601.1  346.33  4634.6   344.7    5046  345.02  5102.5  346.05  5138.1   350.8
  5178.3  355.31  5211.8  357.28  5247.4  363.87    5304  363.05  5404.7  372.64
  5461.2  374.87  5490.7  380.28  5547.2  383.27  5576.6  387.81  5611.5  387.91
#Mann= 6 ,-1 , 0
  3426.5     .05       0  4006.3     .16       0  4108.5     .16       0
  4414.8     .07       0  4420.8     .16       0  5178.3     .05       0
#XS Ineff= 1 ,-1
 3777.27 4919.32  361.81
Permanent Ineff=
       F
Bank Sta=4066.8,5138.1
XS Rating Curve= 0 ,0
Exp/Cntr=0.3,0.1

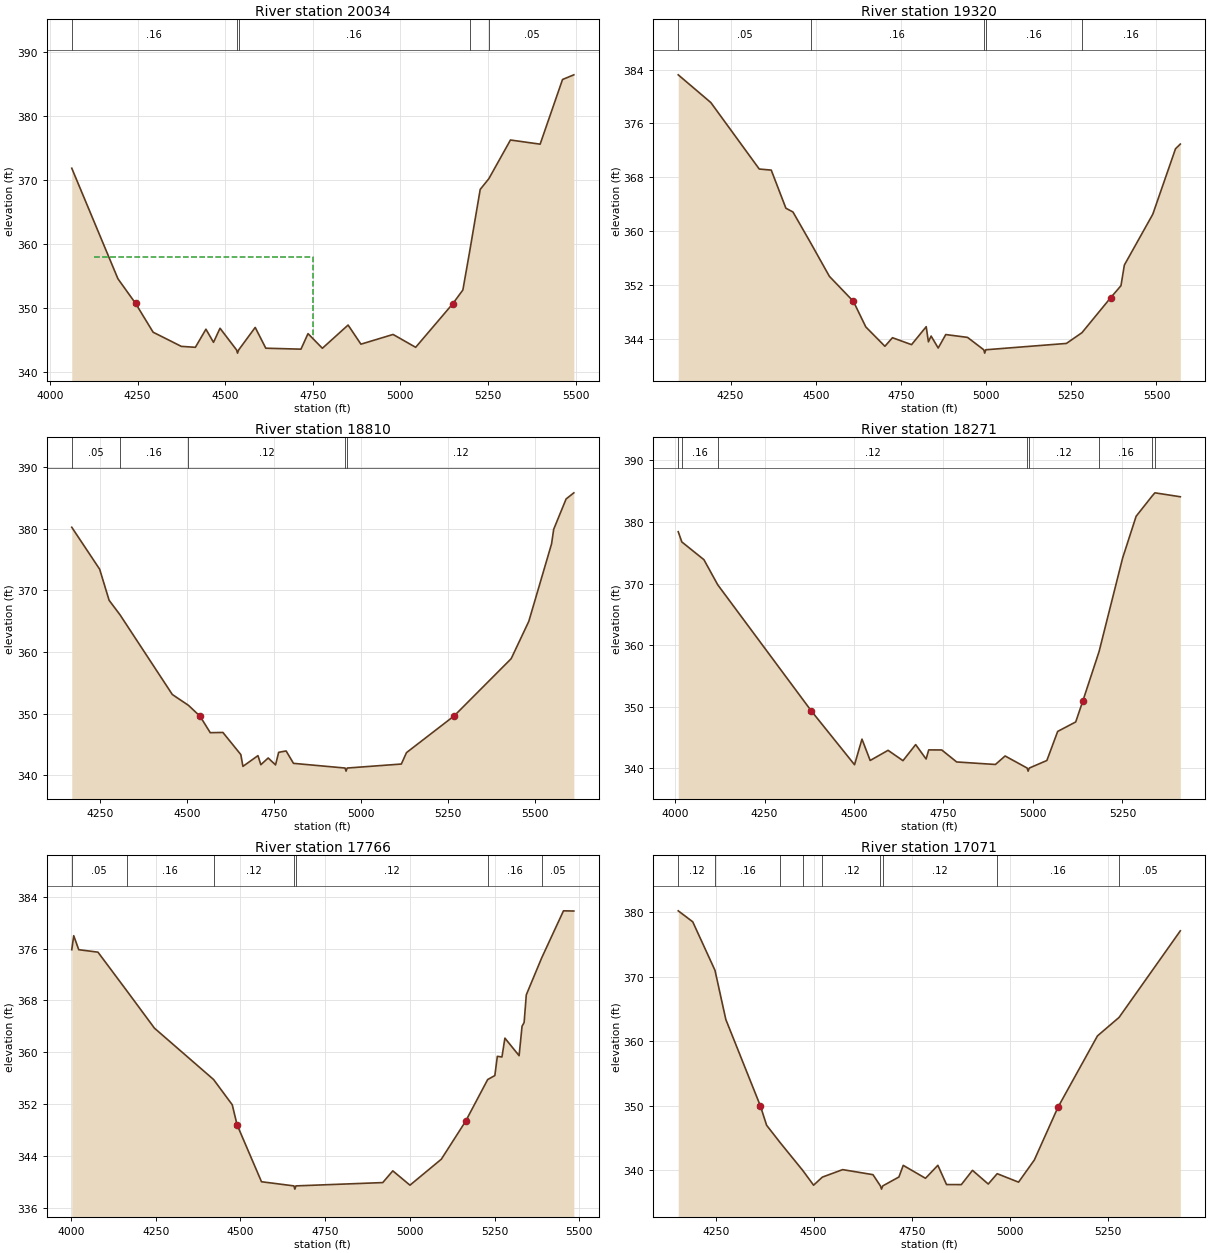
Type RM Length L Ch R = 1 ,20034   ,714,714,714
BEGIN DESCRIPTION:
MILL BRANCH 29.0
END DESCRIPTION:
XS GIS Cut Line= 3
      3678220.67     10761666.37      3677451.19     10761741.21
      3676939.47     10761324.89
#Sta/Elev= 30
  4062.3   371.8    4194  354.52  4244.2  350.68  4294.5  346.16  4374.8  343.95
    4415   343.8  4445.2  346.63  4466.8  344.58  4485.4  346.78  4532.6  343.39
  4535.3  342.89  4538.6  343.39  4585.8  346.91    4616  343.66  4716.4  343.51
  4736.5  345.94  4777.5  343.65  4850.9  347.28  4887.5  344.29  4979.3  345.81
  5043.7   343.8  5149.7  350.62  5178.4  352.76  5198.1  358.88  5227.9  368.49
  5252.4  370.15  5314.2  376.21  5398.9  375.56  5462.8  385.67  5495.1   386.4
#Mann= 5 ,-1 , 0
  4062.3     .16       0  4532.6     .07       0  4538.6     .16       0
  5198.1     .16       0  5252.4     .05       0
#XS Ineff= 1 ,-1
 4124.55    4750  357.96
Permanent Ineff=
       F
Bank Sta=4244.2,5149.7
XS Rating Curve= 0 ,0
Exp/Cntr=0.3,0.1

Type RM Length L Ch R = 1 ,19320   ,510,510,510
BEGIN DESCRIPTION:
MILL BRANCH 28.0
END DESCRIPTION:
XS GIS Cut Line= 4
      3678466.46     10761697.73      3677793.45     10761144.41
      3677726.41     10761098.75      3677205.56     10761118.28
#Sta/Elev= 30
  4096.4  383.21  4192.1  379.09  4334.2  369.21  4369.4  369.05  4412.4  363.39
  4433.2  362.82  4484.8  358.26  4540.1  353.26  4610.5  349.54    4647  345.74
    4703  342.87  4725.2  344.14  4781.2  343.11  4824.2  345.78  4830.7  343.53
  4838.6  344.39  4859.4  342.61  4881.6  344.61  4945.5  344.19  4993.1  342.35
  4995.9  341.85  4999.1  342.35  5235.7  343.29  5281.4  344.89  5365.8   350.1
  5395.8  351.87  5405.8  354.94  5489.2  362.49  5555.9  372.22    5570  372.92
#Mann= 5 ,-1 , 0
  4096.4     .05       0  4484.8     .16       0  4993.1     .07       0
  4999.1     .16       0  5281.4     .16       0
Bank Sta=4610.5,5365.8
XS Rating Curve= 0 ,0
Exp/Cntr=0.3,0.1

Type RM Length L Ch R = 1 ,18810   ,539,539,539
BEGIN DESCRIPTION:
MILL BRANCH 27.0
END DESCRIPTION:
XS GIS Cut Line= 3
      3678449.59     10761410.15      3677999.61     10760710.19
      3677499.65     10760360.22
#Sta/Elev= 30
  4168.1  380.22  4248.3  373.41  4275.4  368.38  4306.7  366.03    4457  353.11
  4503.2  351.36  4536.6  349.59    4566  346.92  4602.3  346.96  4653.8  343.37
  4659.8  341.46    4703   343.2  4711.3  341.73  4732.4  342.82  4753.5   341.7
  4762.5  343.74  4783.9  343.96  4805.1  341.95  4953.3  341.19  4956.1  340.69
  4959.3  341.19  5114.9  341.84  5129.7  343.69  5266.6  349.64  5430.5  358.92
  5481.1  364.97  5546.5  377.53  5552.6  379.89  5588.3  384.81  5610.5   385.8
#Mann= 5 ,-1 , 0
  4168.1     .05       0  4306.7     .16       0  4503.2     .12       0
  4953.3     .07       0  4959.3     .12       0
Bank Sta=4536.6,5266.6
XS Rating Curve= 0 ,0
Exp/Cntr=0.3,0.1

Type RM Length L Ch R = 1 ,18271   ,505,505,505
BEGIN DESCRIPTION:
MILL BRANCH 26.0
END DESCRIPTION:
XS GIS Cut Line= 3
      3678899.59     10761110.16      3678299.61     10760310.19
      3678249.61     10759910.17
#Sta/Elev= 30
  4008.8  378.42  4018.9  376.76  4080.6  373.88  4119.1  369.81  4380.6  349.32
  4501.5  340.57  4522.3  344.73  4545.2  341.26  4595.2  342.91  4636.9  341.23
  4672.3  343.84  4701.5   341.5  4708.8  342.98  4745.2  342.97  4786.9  341.02
  4895.2  340.61  4922.3  341.99  4983.9  340.03  4986.6  339.53  4989.9  340.03
    5039  341.26  5069.2  345.98  5119.6  347.52  5139.8  350.98  5184.7  358.92
  5250.6  374.13  5288.4  380.93  5333.7  384.26  5340.9  384.74  5411.9   384.1
#Mann= 8 ,-1 , 0
  4008.8     .05       0  4018.9     .16       0  4119.1     .12       0
  4983.9     .07       0  4989.9     .12       0  5184.7     .16       0
  5333.7     .12       0  5340.9     .16       0
Bank Sta=4380.6,5139.8
XS Rating Curve= 0 ,0
Exp/Cntr=0.3,0.1

Type RM Length L Ch R = 1 ,17766   ,695,695,695
BEGIN DESCRIPTION:
MILL BRANCH 25.0
END DESCRIPTION:
XS GIS Cut Line= 2
       3679297.7     10760930.24      3678450.56     10759715.08
#Sta/Elev= 30
  4002.6  375.82  4008.4  377.98  4023.2  375.82  4079.9  375.44  4164.7   369.5
  4246.5  363.71    4421  355.78  4476.1  351.88  4490.3  348.79  4562.4     340
    4658  339.36  4660.8  338.86    4664  339.36  4920.1  339.87  4949.8  341.68
  5000.4  339.47  5092.9  343.48  5164.4  349.32  5229.7  355.78  5250.8  356.39
  5258.2  359.36  5271.8  359.26  5280.5  362.17  5322.4  359.46  5331.1  364.01
  5337.2  364.58  5343.6  368.85  5388.8  374.53  5453.3  381.82  5483.9  381.79
#Mann= 7 ,-1 , 0
  4002.6     .05       0  4164.7     .16       0    4421     .12       0
    4658     .07       0    4664     .12       0  5229.7     .16       0
  5388.8     .05       0
Bank Sta=4490.3,5164.4
XS Rating Curve= 0 ,0
Exp/Cntr=0.3,0.1

Type RM Length L Ch R = 1 ,17071   ,823,823,823
BEGIN DESCRIPTION:
MILL BRANCH 24.0
END DESCRIPTION:
XS GIS Cut Line= 3
      3679899.58     10760010.18      3679149.61     10759660.19
       3678699.6     10759610.19
#Sta/Elev= 30
  4154.6  380.18  4191.6  378.48  4248.3  370.97    4276  363.35  4364.2  349.95
    4380  346.97  4414.8  344.26  4472.1  339.98  4499.8  337.69  4522.1  338.94
  4573.9   340.1  4651.2  339.32  4670.2  337.58    4673  337.08  4676.2  337.58
  4717.4  338.96  4728.4  340.76  4785.2  338.76  4816.7  340.77  4838.8  337.79
  4876.6  337.78    4905  339.99  4945.2  337.87    4968  339.47  5022.5  338.16
  5062.7  341.59  5123.1  349.77  5223.7  360.81  5278.9  363.68    5435  377.08
#Mann= 9 ,-1 , 0
  4154.6     .12       0  4248.3     .16       0  4414.8     .12       0
  4472.1     .16       0  4522.1     .12       0  4670.2     .07       0
  4676.2     .12       0    4968     .16       0  5278.9     .05       0
Bank Sta=4364.2,5123.1
XS Rating Curve= 0 ,0
Exp/Cntr=0.3,0.1

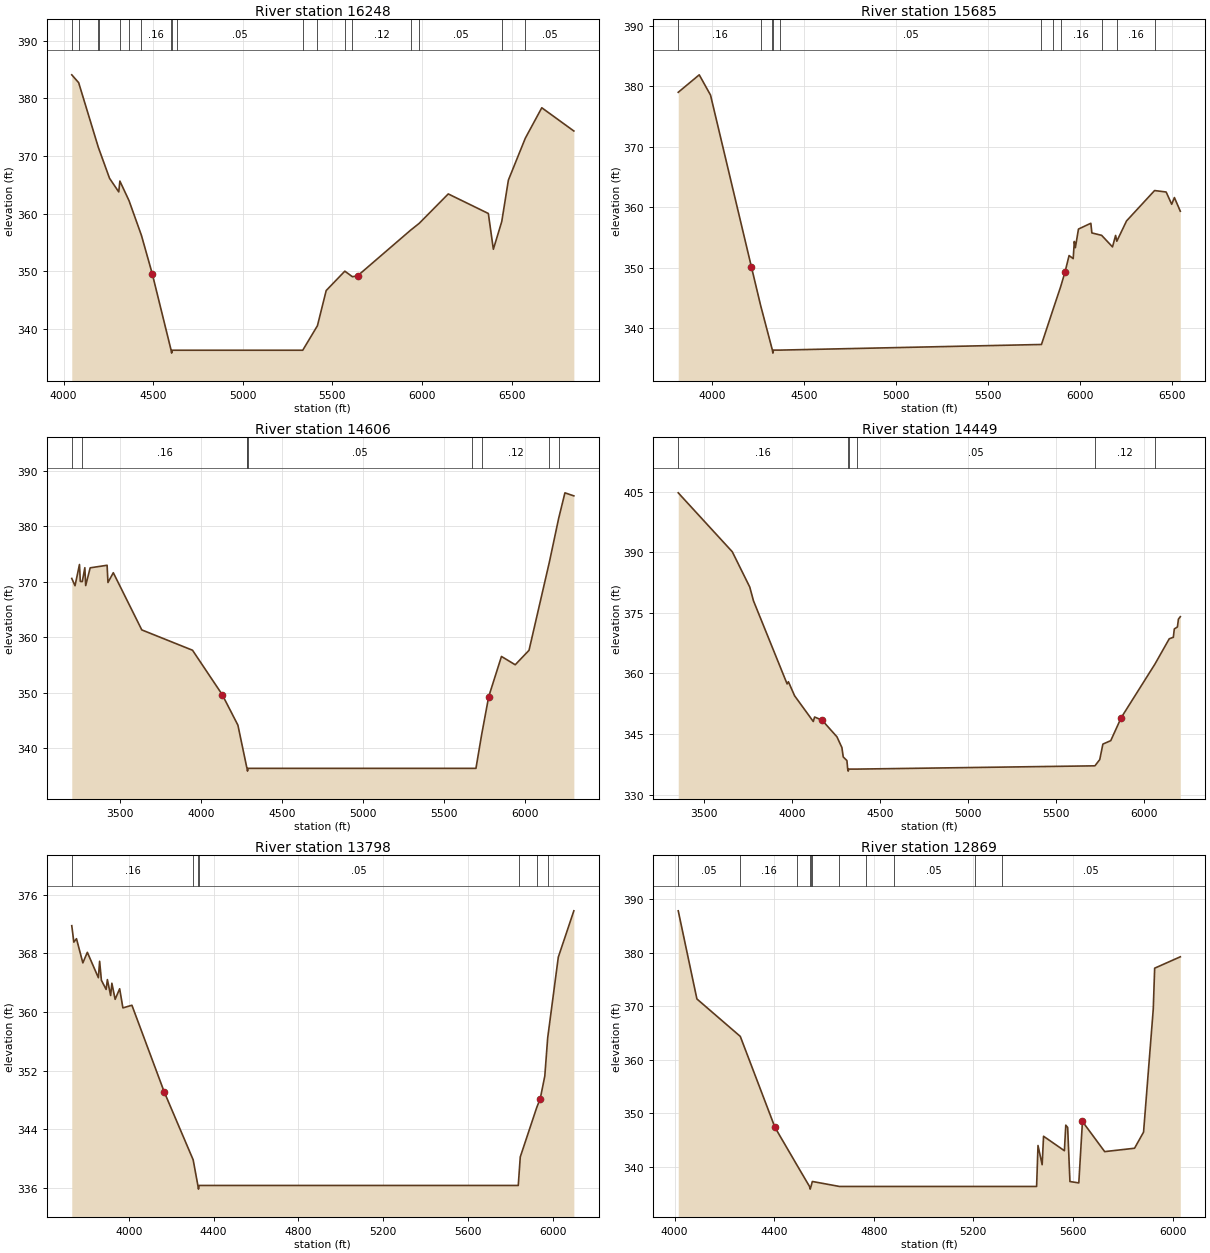
Type RM Length L Ch R = 1 ,16248   ,563,563,563
BEGIN DESCRIPTION:
MILL BRANCH 23.0
END DESCRIPTION:
XS GIS Cut Line= 3
       3680240.9     10760020.98      3679631.51     10759093.88
      3677985.69     10759489.71
#Sta/Elev= 30
  4045.3  384.09  4083.8  382.73  4193.2  371.56  4194.6  371.43  4256.3  366.14
  4307.6  363.79  4313.8  365.67  4364.8  362.28  4434.2  356.25  4494.3  349.63
  4599.8  336.34  4602.6  335.84  4605.8  336.34  4630.1  336.34  5334.4  336.34
  5416.4  340.59  5465.3  346.69  5569.3  350.05  5611.6  349.09  5640.1  349.23
  5936.6  357.16  5984.1  358.33  6146.6  363.44  6370.3  360.05  6398.3  353.85
  6445.3  358.67  6482.2  365.84  6576.6   373.1  6668.6  378.38  6847.5  374.35
#Mann= 18 ,-1 , 0
  4045.3     .16       0  4083.8     .12       0  4193.2     .16       0
  4194.6     .12       0  4313.8     .16       0  4364.8     .12       0
  4434.2     .16       0  4599.8    .033       0  4605.8     .16       0
  4630.1     .05       0  5334.4     .16       0  5416.4     .12       0
  5569.3     .16       0  5611.6     .12       0  5936.6     .16       0
  5984.1     .05       0  6445.3     .16       0  6576.6     .05       0
Bank Sta=4494.3,5640.1
XS Rating Curve= 0 ,0
Exp/Cntr=0.3,0.1

Type RM Length L Ch R = 1 ,15685   ,1079,1079,1079
BEGIN DESCRIPTION:
MILL BRANCH 21.0
END DESCRIPTION:
XS GIS Cut Line= 3
       3680522.8     10759934.32      3680138.55     10758871.74
      3679429.48     10757438.24
#Sta/Elev= 30
  3817.3  378.98  3931.5  381.87  3992.8  378.52  4215.1   350.1    4265  343.75
  4329.1  336.34  4331.9  335.84  4335.1  336.34  4370.7  336.34  5791.8  337.27
  5856.9  343.26  5895.6  346.78  5919.6  349.24  5941.9  351.98  5964.2  351.47
  5970.4  354.31    5976  353.28  5992.9  356.36  6060.2  357.32  6065.7  355.72
  6118.9  355.32  6177.9  353.41  6194.8  355.31  6201.4  354.35  6254.3  357.71
  6406.6  362.73  6469.5  362.49  6499.7  360.46  6514.4  361.57  6546.5  359.31
#Mann= 11 ,-1 , 0
  3817.3     .16       0    4265     .07       0  4329.1    .033       0
  4335.1     .07       0  4370.7     .05       0  5791.8     .16       0
  5856.9     .12       0  5895.6     .16       0  6118.9     .12       0
  6201.4     .16       0  6406.6     .12       0
Bank Sta=4215.1,5919.6
XS Rating Curve= 0 ,0
Exp/Cntr=0.3,0.1

Type RM Length L Ch R = 1 ,14606   ,157,157,157
BEGIN DESCRIPTION:
MILL BRANCH 20.0
END DESCRIPTION:
XS GIS Cut Line= 4
      3680590.53     10759979.46      3681059.27     10758416.99
      3680981.14     10758147.89      3680251.95     10757210.36
#Sta/Elev= 30
  3202.5   370.6  3222.6  369.29  3250.1  373.12  3255.3  370.06  3267.5  370.04
  3283.2  372.54  3288.4  369.32  3316.2  372.52  3420.6  372.98  3425.9  369.87
  3458.9  371.64  3634.7  361.32  3947.9  357.65  4130.9  349.66    4228  344.14
  4282.1   336.6  4284.5  336.34  4287.3  335.84  4290.5  336.34  5670.2  336.34
  5697.4  336.34  5732.2  342.36  5776.2  349.28  5854.9  356.53  5939.9  355.03
    6025  357.64    6151   373.6  6207.8  381.42  6246.7  386.05  6301.7   385.5
#Mann= 9 ,-1 , 0
  3202.5     .05       0  3267.5     .16       0  4282.1     .05       0
  4284.5    .033       0  4290.5     .05       0  5670.2     .16       0
  5732.2     .12       0    6151     .16       0  6207.8     .12       0
Bank Sta=4130.9,5776.2
XS Rating Curve= 0 ,0
Exp/Cntr=0.3,0.1

Type RM Length L Ch R = 1 ,14449   ,651,651,651
BEGIN DESCRIPTION:
MILL BRANCH 19.0
END DESCRIPTION:
XS GIS Cut Line= 3
      3682239.84     10759423.96      3681198.15     10758286.78
      3680668.64     10757088.86
#Sta/Elev= 30
  3353.1   404.7  3660.1  390.12  3759.4  381.39  3780.4  377.99  3971.5  357.42
  3978.9  357.96  4014.1  354.48  4120.2  348.12  4127.6  349.23  4170.1  348.45
  4254.6  344.33  4282.9  341.66  4290.3  339.35  4311.3  338.45  4315.7  336.34
  4318.5  335.84  4321.7  336.34    4366  336.34    5720  337.15  5747.4   338.7
  5765.2  342.53  5809.9  343.38  5869.4  349.08  6061.2  362.35  6142.1  368.58
  6165.4  368.96  6170.9  371.02  6188.7  371.51  6194.2  373.44    6205  374.05
#Mann= 6 ,-1 , 0
  3353.1     .16       0  4315.7    .033       0  4321.7     .16       0
    4366     .05       0    5720     .12       0  6061.2     .16       0
Bank Sta=4170.1,5869.4
XS Rating Curve= 0 ,0
Exp/Cntr=0.3,0.1

Type RM Length L Ch R = 1 ,13798   ,929,929,929
BEGIN DESCRIPTION:
MILL BRANCH 18.0
END DESCRIPTION:
XS GIS Cut Line= 2
      3682412.53     10758989.01      3681163.58     10756976.81
#Sta/Elev= 30
    3731  371.77  3740.8  369.53  3753.2     370  3783.3   366.7  3804.5  368.14
  3856.5  364.68  3862.4  366.92  3870.8  364.33  3893.1  363.08    3899  364.42
  3914.4  362.25  3920.2  363.92  3935.6  361.73  3956.9  363.17  3972.2  360.56
  4014.7  360.92  4167.1   349.1  4303.6  339.84  4325.9  336.34  4328.7  335.84
  4331.9  336.34  5837.1  336.34  5840.3  337.65  5846.6  340.23  5923.7  346.93
    5941   348.2  5962.3  351.26  5975.9  356.47    6026  367.48  6099.3   373.8
#Mann= 7 ,-1 , 0
    3731     .16       0  4303.6     .05       0  4325.9    .033       0
  4331.9     .05       0  5840.3     .16       0  5923.7     .12       0
  5975.9     .16       0
Bank Sta=4167.1,5941
XS Rating Curve= 0 ,0
Exp/Cntr=0.3,0.1

Type RM Length L Ch R = 1 ,12869   ,45,45,45
BEGIN DESCRIPTION:
MILL BRANCH 17.0
END DESCRIPTION:
XS GIS Cut Line= 2
      3683306.63     10757744.52      3681505.45     10756837.42
#Sta/Elev= 30
  4014.6  387.85  4089.6  371.38  4263.9  364.38  4403.1  347.38  4490.9  340.38
  4541.9  336.34  4544.6  335.84  4547.9  336.34  4553.3  337.27    4662  336.34
  4770.7  336.34  4879.4  336.34  5205.6  336.34  5314.3  336.34  5454.1  336.34
  5459.7  343.99  5476.4   340.4    5482  345.72  5565.7  343.02  5571.3   347.8
  5578.8  347.37    5588  337.26  5623.6     337  5638.2  348.48  5727.5  342.85
  5847.5  343.48  5883.7   346.5  5922.7  369.51  5928.3  377.13  6031.3  379.26
#Mann= 11 ,-1 , 0
  4014.6     .05       0  4263.9     .16       0  4490.9     .05       0
  4541.9    .033       0  4547.9     .05       0  4553.3     .16       0
    4662     .05       0  4770.7     .16       0  4879.4     .05       0
  5205.6     .16       0  5314.3     .05       0
Bank Sta=4403.1,5638.2
XS Rating Curve= 0 ,0
Exp/Cntr=0.3,0.1

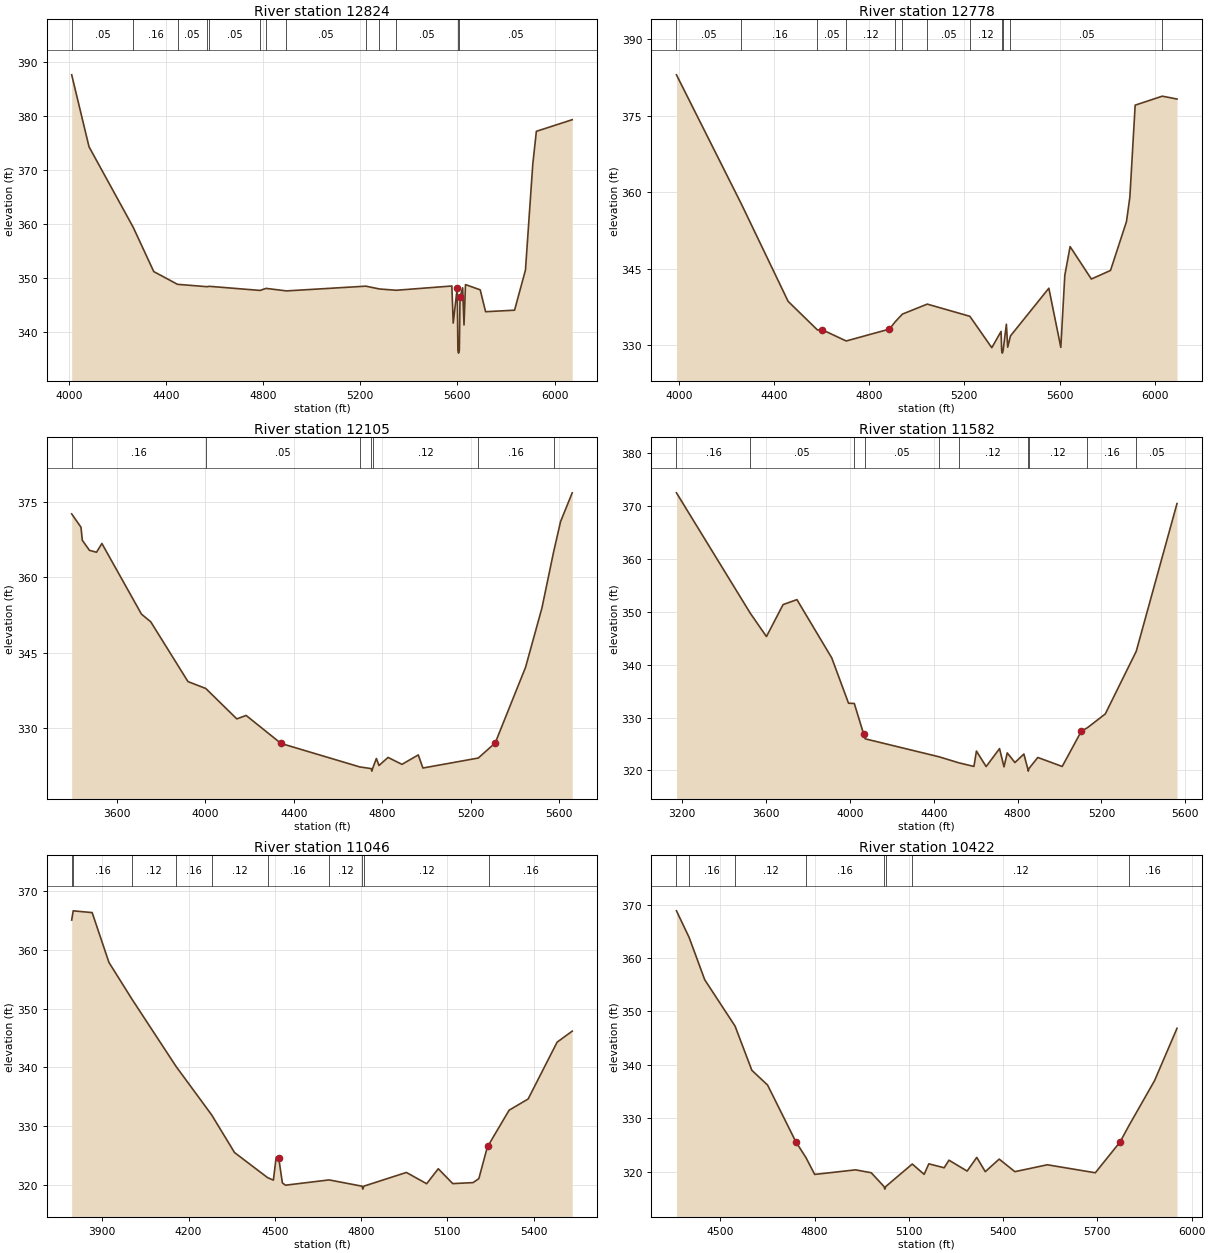
Type RM Length L Ch R = 1 ,12824   ,46,46,46
BEGIN DESCRIPTION:
Mapping XS 844bb3f7
END DESCRIPTION:
XS GIS Cut Line= 2
      3683323.96     10757709.78      3681488.07      10756772.3
#Sta/Elev= 30
  4011.4  387.62  4082.8   374.3    4265  359.37  4349.4  351.19  4447.2  348.83
  4569.1  348.39  4578.7  348.46  4787.1   347.7  4811.9  348.08    4896  347.61
    5223  348.49  5278.4  347.97  5348.3  347.73    5577  348.52  5582.7  341.65
  5599.3  348.24  5601.9  336.59  5604.6  336.09  5607.9  336.59  5610.7  346.42
  5621.5   348.2  5627.1  341.31  5633.2  348.78  5693.8  347.81    5716  343.76
  5835.3  344.04  5880.2  351.47  5910.4  371.11  5925.1  377.16  6072.8  379.31
#Mann= 13 ,-1 , 0
  4011.4     .05       0    4265     .16       0  4447.2     .05       0
  4569.1     .16       0  4578.7     .05       0  4787.1     .16       0
  4811.9     .12       0    4896     .05       0    5223     .16       0
  5278.4     .12       0  5348.3     .05       0  5601.9     .03       0
  5607.9     .05       0
Bank Sta=5599.3,5610.7
XS Rating Curve= 0 ,0
Exp/Cntr=0.3,0.1

Type RM Length L Ch R = 1 ,12778   ,673,673,673
BEGIN DESCRIPTION:
MILL BRANCH 16.0
END DESCRIPTION:
XS GIS Cut Line= 2
      3683358.67     10757670.71      3681480.03     10756724.88
#Sta/Elev= 30
  3990.2  382.98  4262.7  357.71  4459.4  338.62  4582.8  333.01  4601.1  333.09
  4703.4  330.86  4884.8  333.18    4909   334.6  4939.5  336.12  5044.1  338.08
  5223.1  335.69  5315.2  329.54  5354.2  332.73  5356.8  328.98  5359.6  328.48
  5362.8  328.98  5376.5  334.14  5382.1  329.64  5393.7  331.85    5555  341.19
  5605.3  329.61    5622  343.71  5644.3  349.34  5733.6  342.99  5814.1  344.67
  5881.2  354.24  5895.4  359.05  5917.7  377.04  6031.6   378.8  6093.5  378.24
#Mann= 12 ,-1 , 0
  3990.2     .05       0  4262.7     .16       0  4582.8     .05       0
  4703.4     .12       0    4909     .05       0  4939.5     .12       0
  5044.1     .05       0  5223.1     .12       0  5356.8     .07       0
  5362.8     .12       0  5393.7     .05       0  6031.6     .16       0
Bank Sta=4601.1,4884.8
XS Rating Curve= 0 ,0
Exp/Cntr=0.3,0.1

Type RM Length L Ch R = 1 ,12105   ,523,523,523
BEGIN DESCRIPTION:
MILL BRANCH 15.0
END DESCRIPTION:
XS GIS Cut Line= 3
      3683949.56     10757060.17      3682399.61     10756560.19
      3681799.57     10756360.18
#Sta/Elev= 30
    3397  372.63    3439  369.97    3445  367.38  3477.1  365.37  3509.1  364.99
  3533.5  366.73  3712.2  352.65  3754.2  351.12  3922.3  339.21  4002.8  337.83
    4143  331.77    4185  332.46  4342.6  326.88  4698.2   322.2  4750.2  321.86
  4752.9  321.36  4756.2  321.86  4773.4  323.88  4785.2  322.48    4826  324.09
    4889  322.71  4962.6  324.59  4983.6  321.98  5233.6  323.97  5310.2  326.98
  5447.2  342.05    5521  353.84  5574.2  365.09  5605.4   371.1  5658.1  376.83
#Mann= 7 ,-1 , 0
    3397     .16       0  4002.8     .05       0  4698.2     .12       0
  4750.2     .07       0  4756.2     .12       0  5233.6     .16       0
  5574.2     .12       0
Bank Sta=4342.6,5310.2
XS Rating Curve= 0 ,0
Exp/Cntr=0.3,0.1

Type RM Length L Ch R = 1 ,11582   ,536,536,536
BEGIN DESCRIPTION:
MILL BRANCH 14.0
END DESCRIPTION:
XS GIS Cut Line= 3
      3683949.62     10757010.19      3682399.61     10756060.19
      3681849.57      10756210.2
#Sta/Elev= 30
  3172.4  372.47  3524.6  349.72  3601.7  345.31  3681.1  351.35  3747.1  352.29
  3913.2  341.28  3993.4  332.71  4020.9  332.66    4066  326.82  4073.2  325.98
  4426.2  322.58  4519.5  321.45  4591.6  320.77  4603.6  323.67  4649.9  320.74
  4713.8  324.14  4735.1  320.69  4750.6  323.32  4787.3   321.5  4829.9  323.11
  4848.2  320.38  4850.9  319.88  4854.2  320.38  4896.5  322.46  5012.8  320.76
  5104.4  327.45  5133.4  328.09  5218.4  330.69    5366  342.52  5560.5  370.44
#Mann= 10 ,-1 , 0
  3172.4     .16       0  3524.6     .05       0  4020.9     .16       0
  4073.2     .05       0  4426.2     .16       0  4519.5     .12       0
  4848.2     .07       0  4854.2     .12       0  5133.4     .16       0
    5366     .05       0
Bank Sta=4066,5104.4
XS Rating Curve= 0 ,0
Exp/Cntr=0.3,0.1

Type RM Length L Ch R = 1 ,11046   ,624,624,624
BEGIN DESCRIPTION:
MILL BRANCH 13.0
END DESCRIPTION:
XS GIS Cut Line= 3
      3683735.46     10755295.68      3682823.97     10755677.63
      3682077.43     10755773.12
#Sta/Elev= 30
  3793.5  365.09  3798.7  366.66  3864.7  366.36  3923.1  357.87  4003.5  351.59
  4156.6  340.15  4280.2  331.91  4359.9  325.49  4474.8  321.22    4495  320.79
  4504.6  324.66  4513.4  324.61  4526.3  320.32  4537.1  319.93  4688.8  320.83
  4803.3  319.76  4806.1  319.26  4809.3  319.76  4957.6   322.1  5028.1  320.18
  5068.5  322.73  5118.9   320.2  5189.4  320.37  5209.6  321.05  5240.2  326.61
  5246.3  327.02  5314.8   332.7    5381  334.61  5481.8  344.29  5534.4  346.17
#Mann= 10 ,-1 , 0
  3793.5     .12       0  3798.7     .16       0  4003.5     .12       0
  4156.6     .16       0  4280.2     .12       0  4474.8     .16       0
  4688.8     .12       0  4803.3     .07       0  4809.3     .12       0
  5246.3     .16       0
Bank Sta=4513.4,5240.2
XS Rating Curve= 0 ,0
Exp/Cntr=0.3,0.1

Type RM Length L Ch R = 1 ,10422   ,543,543,543
BEGIN DESCRIPTION:
MILL BRANCH 12.0
END DESCRIPTION:
XS GIS Cut Line= 3
      3683449.58     10755210.19      3682799.61     10755210.19
      3681999.58     10755710.21
#Sta/Elev= 30
    4360  368.83  4400.3  363.85    4450  355.92  4546.6  347.24    4600  338.97
    4650  336.21    4740  325.59  4772.4  322.61    4800  319.47    4930  320.33
    4980  319.79  5020.5  317.22  5023.3  316.72  5026.5  317.22  5110.6  321.42
  5148.5  319.49  5163.3  321.46  5212.2  320.72  5227.5  322.14  5285.3   320.1
    5316  322.66  5343.1  319.99  5387.3  322.34  5437.4  319.99  5540.6  321.28
  5693.3  319.78  5772.4  325.57  5800.7  328.65    5882  337.04  5953.4  346.83
#Mann= 8 ,-1 , 0
    4360     .12       0  4400.3     .16       0  4546.6     .12       0
  4772.4     .16       0  5020.5     .07       0  5026.5     .16       0
  5110.6     .12       0  5800.7     .16       0
Bank Sta=4740,5772.4
XS Rating Curve= 0 ,0
Exp/Cntr=0.3,0.1