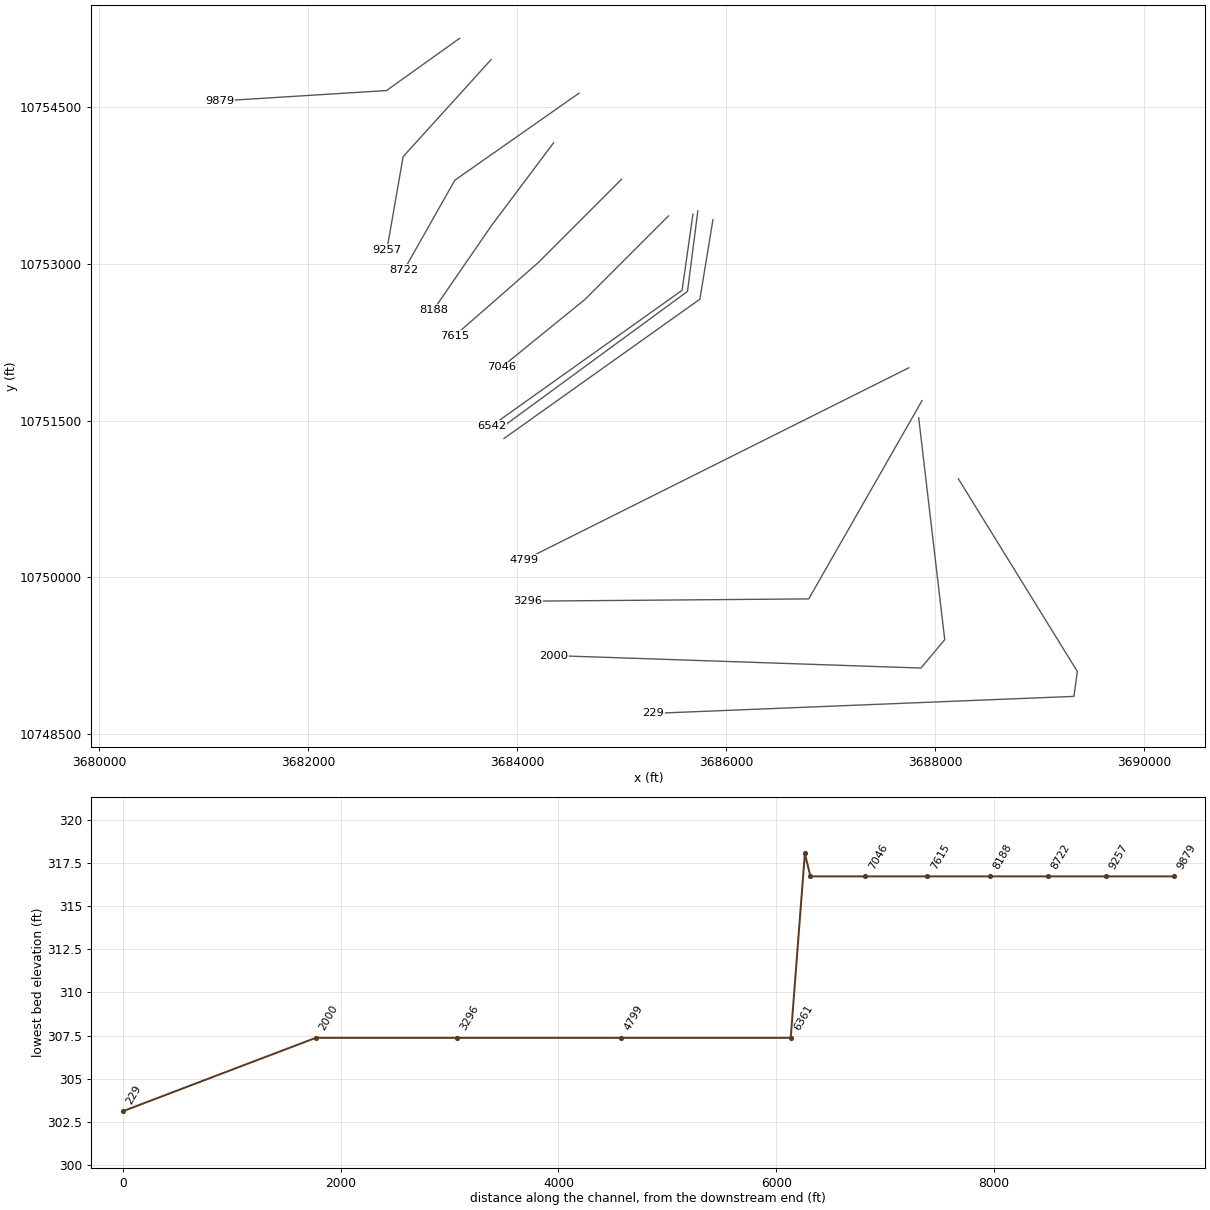
HEC-RAS study MILL BRANCH.prj: MILL BRANCH Base Level Engineering

--- MILL BRANCH.g01 (geometry) --- (continued)

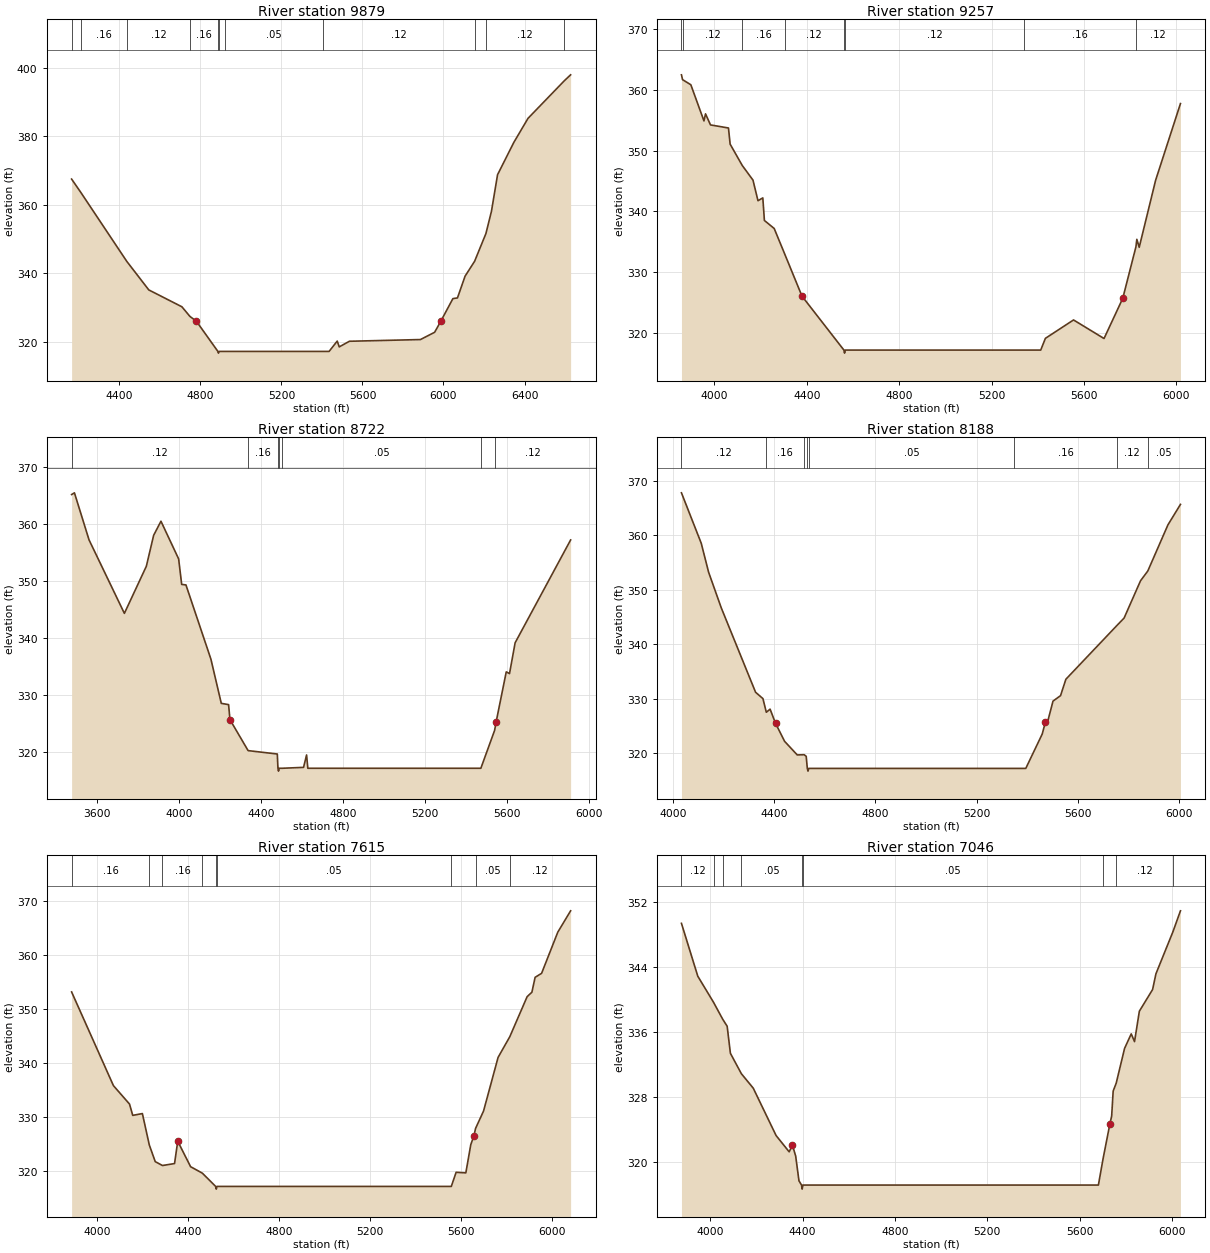
Type RM Length L Ch R = 1 ,9879    ,622,622,622
BEGIN DESCRIPTION:
MILL BRANCH 11.0
END DESCRIPTION:
XS GIS Cut Line= 3
      3683449.64     10755160.21      3682749.61     10754660.19
      3681149.61     10754560.19
#Sta/Elev= 30
  4164.2  367.49  4210.2  363.55  4436.9  343.46  4545.2  335.16  4708.6  330.24
  4748.4  327.42  4779.9  326.05  4886.3  317.22    4889  316.72  4892.3  317.22
  4920.4  317.22  5403.1  317.22  5435.3  317.22  5475.4  320.23  5485.4  318.54
  5535.5  320.18  5886.2  320.68  5956.3   322.8  5986.3  325.97  6046.5  332.62
    6069  332.82  6106.6  339.17  6153.8  343.53  6209.6  351.62  6236.8   358.1
  6266.9  368.76  6347.1  378.17  6417.2   385.2    6596  396.14  6627.6   397.9
#Mann= 11 ,-1 , 0
  4164.2     .12       0  4210.2     .16       0  4436.9     .12       0
  4748.4     .16       0  4886.3    .033       0  4892.3     .16       0
  4920.4     .05       0  5403.1     .12       0  6153.8     .16       0
  6209.6     .12       0    6596     .16       0
Bank Sta=4779.9,5986.3
XS Rating Curve= 0 ,0
Exp/Cntr=0.3,0.1

Type RM Length L Ch R = 1 ,9257    ,535,535,535
BEGIN DESCRIPTION:
MILL BRANCH 10.0
END DESCRIPTION:
XS GIS Cut Line= 3
      3683751.03     10754956.26      3682909.04     10754027.46
      3682752.94     10753134.24
#Sta/Elev= 30
  3857.1  362.43  3861.8  361.64  3897.7   360.8  3954.5  354.86  3961.3  356.02
  3982.9   354.2  4060.6   353.7  4067.8  351.05  4120.3  347.54  4166.7  345.14
  4188.4  341.75  4209.3  342.22  4216.2  338.51  4258.6  337.19  4303.8  333.03
  4378.9  326.08  4560.4  317.22  4563.2  316.72  4566.4  317.22  5338.5  317.22
  5412.5  317.22  5432.8  319.15  5554.6  322.17  5686.6  319.12  5767.8  325.73
  5824.7  334.18  5828.6  335.41  5838.9   334.1  5909.9  345.11  6017.5  357.71
#Mann= 8 ,-1 , 0
  3857.1     .16       0  3861.8     .12       0  4120.3     .16       0
  4303.8     .12       0  4560.4    .033       0  4566.4     .12       0
  5338.5     .16       0  5824.7     .12       0
Bank Sta=4378.9,5767.8
XS Rating Curve= 0 ,0
Exp/Cntr=0.3,0.1

Type RM Length L Ch R = 1 ,8722    ,534,534,534
BEGIN DESCRIPTION:
MILL BRANCH 9.0
END DESCRIPTION:
XS GIS Cut Line= 3
      3684593.03     10754635.07      3683403.83     10753801.77
      3682918.52     10752943.81
#Sta/Elev= 30
  3474.5  365.25  3488.3  365.55  3559.7  357.29  3732.3   344.4  3839.6  352.67
  3875.3   358.1    3911  360.57  3997.4  353.95  4012.2  349.48  4033.1  349.39
  4155.1  336.36  4205.7  328.61  4241.4  328.39    4248  325.76  4336.7  320.32
  4479.4  319.72  4482.5  317.22  4485.3  316.72  4488.5  317.22  4502.2  317.22
  4607.6  317.38  4622.4  319.56  4628.5  317.22  5473.8  317.22    5541  323.87
  5548.8  325.42  5597.9  334.14  5613.8  333.83  5641.2  339.24  5912.3  357.28
#Mann= 7 ,-1 , 0
  3474.5     .12       0  4336.7     .16       0  4482.5    .033       0
  4488.5     .16       0  4502.2     .05       0  5473.8     .16       0
    5541     .12       0
Bank Sta=4248,5548.8
XS Rating Curve= 0 ,0
Exp/Cntr=0.3,0.1

Type RM Length L Ch R = 1 ,8188    ,573,573,573
BEGIN DESCRIPTION:
MILL BRANCH 8.0
END DESCRIPTION:
XS GIS Cut Line= 3
      3684349.59     10754160.16      3683749.61     10753360.19
       3683199.6     10752560.18
#Sta/Elev= 30
  4034.1  367.77  4112.2  358.52  4141.4   353.2  4191.4  346.66  4326.8  331.19
  4355.9  330.02  4369.2  327.52  4384.1  328.09  4405.9  325.47  4441.4  322.19
  4491.4  319.69  4518.6  319.73  4526.8  319.44  4531.1  317.22  4533.8  316.72
  4537.1  317.22  5348.1  317.22    5394  317.22  5458.8  323.51  5471.8  325.75
  5480.6  325.84  5501.5  329.56  5531.3  330.57  5552.3  333.57  5753.8  343.43
  5782.3   344.8  5847.1  351.63    5876  353.44  5955.5   361.9  6004.9  365.65
#Mann= 8 ,-1 , 0
  4034.1     .12       0  4369.2     .16       0  4518.6     .05       0
  4531.1    .033       0  4537.1     .05       0  5348.1     .16       0
  5753.8     .12       0    5876     .05       0
Bank Sta=4405.9,5471.8
XS Rating Curve= 0 ,0
Exp/Cntr=0.3,0.1

Type RM Length L Ch R = 1 ,7615    ,569,569,569
BEGIN DESCRIPTION:
MILL BRANCH 7.0
END DESCRIPTION:
XS GIS Cut Line= 3
      3684999.64     10753810.22      3684199.61     10753010.19
      3683399.64     10752310.21
#Sta/Elev= 30
  3888.9  353.13  4072.8  335.83  4143.5  332.43  4157.7  330.34  4200.1  330.67
  4230.6  324.87  4256.6   321.8  4288.4  321.08  4341.5  321.44  4355.6  325.56
  4412.2  320.86  4463.8  319.67  4522.3  317.22  4525.1  316.72  4528.3  317.22
  5558.6  317.22  5579.8  319.83  5622.5  319.72  5644.4  324.96  5658.1  326.55
  5665.2  327.92  5700.4  331.14  5764.4  341.05    5816  344.88  5892.1  352.26
    5913  353.08  5927.2  355.83  5955.7  356.57  6026.9  364.17  6083.3  368.11
#Mann= 9 ,-1 , 0
  3888.9     .16       0  4230.6     .05       0  4288.4     .16       0
  4463.8     .05       0  4522.3    .033       0  4528.3     .05       0
  5558.6     .16       0  5665.2     .05       0    5816     .12       0
Bank Sta=4355.6,5658.1
XS Rating Curve= 0 ,0
Exp/Cntr=0.3,0.1

Type RM Length L Ch R = 1 ,7046    ,504,504,504
BEGIN DESCRIPTION:
MILL BRANCH 6.0
END DESCRIPTION:
XS GIS Cut Line= 3
      3685449.58     10753460.16      3684649.61     10752660.19
      3683849.62      10752010.2
#Sta/Elev= 30
  3875.1  349.42  3945.8  342.92  4014.2   339.7  4053.5  337.64  4073.1  336.76
  4087.2  333.43  4134.7  330.92  4186.2  329.14  4285.2  323.31  4341.8  321.31
  4355.9  322.14    4370  320.79  4384.2  317.75  4395.3  317.22  4398.1  316.72
  4401.3  317.22  5681.6  317.22  5701.5   320.4  5731.2  324.72  5739.1   325.7
  5745.6  328.78  5758.8  329.76  5795.1  334.04  5823.9  335.82  5838.2  334.87
  5859.1  338.61  5916.5  341.28  5930.9  343.21  6004.1  348.35  6037.2  350.96
#Mann= 9 ,-1 , 0
  3875.1     .12       0  4014.2     .16       0  4053.5     .12       0
  4134.7     .05       0  4395.3    .033       0  4401.3     .05       0
  5701.5     .16       0  5758.8     .12       0  6004.1     .16       0
Bank Sta=4355.9,5731.2
XS Rating Curve= 0 ,0
Exp/Cntr=0.3,0.1

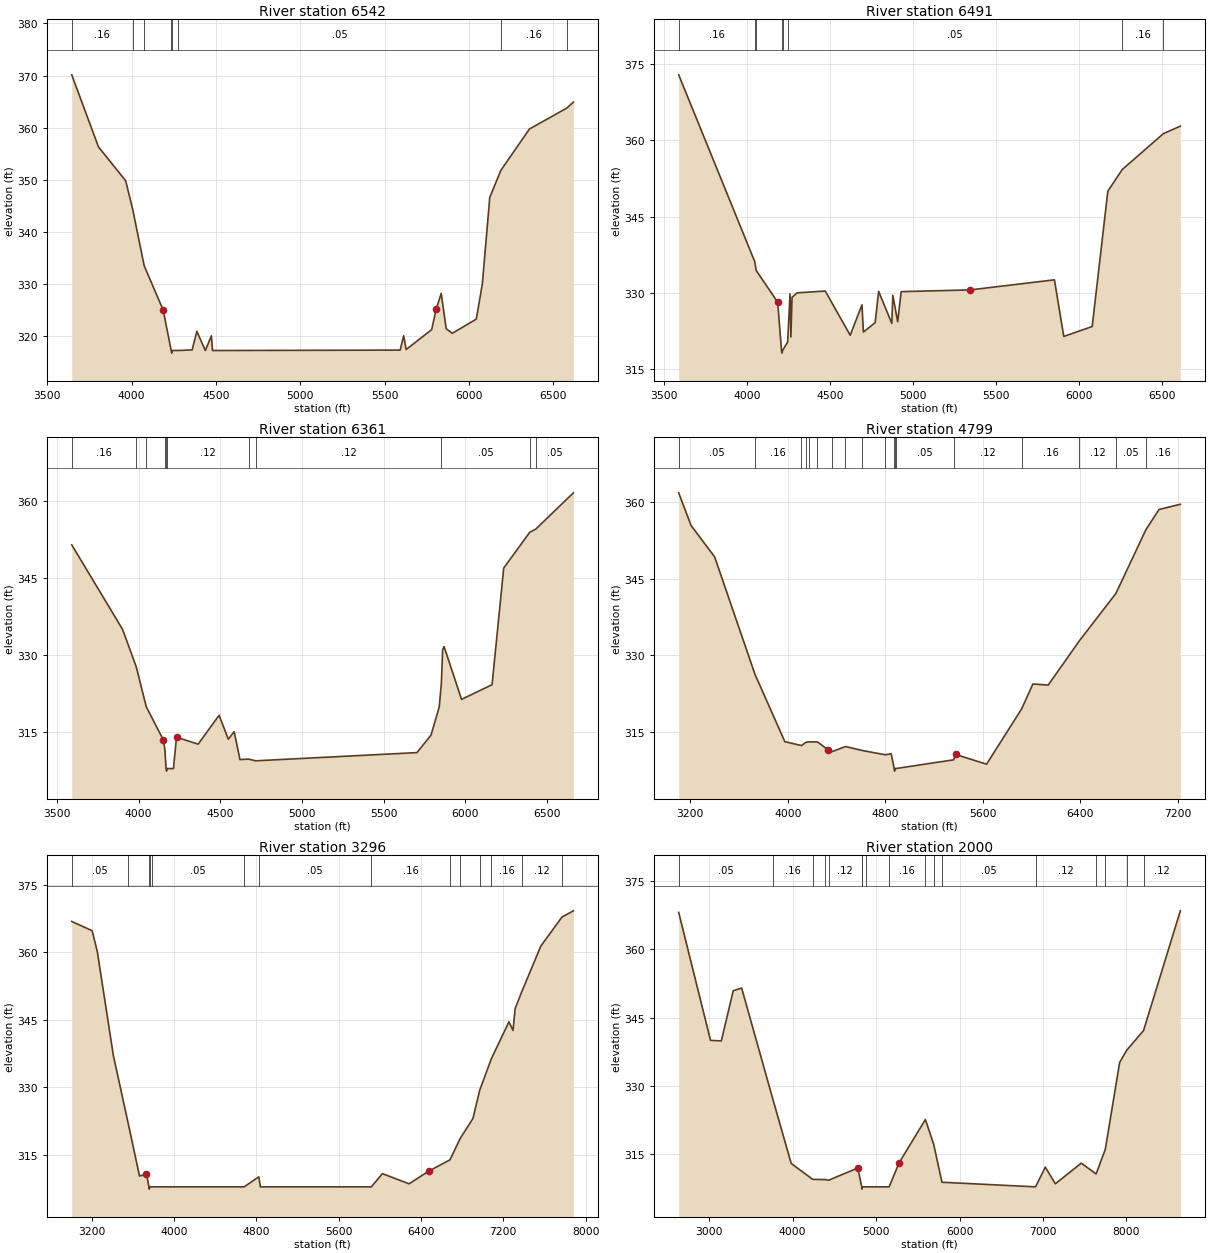
Type RM Length L Ch R = 1 ,6542    ,51,51,51
BEGIN DESCRIPTION:
Mapping XS f003954b
END DESCRIPTION:
XS GIS Cut Line= 3
      3685683.61     10753476.76      3685579.44     10752747.58
      3683756.56     10751450.73
#Sta/Elev= 30
  3645.5  370.14  3803.7  356.32  3965.3   349.8  4007.6   344.2    4075  333.48
  4187.5  324.99    4235  317.22  4237.8  316.72    4241  317.22  4274.1  317.22
  4359.2  317.34  4387.1   320.9  4437.5  317.22  4473.2  320.04  4480.1  317.22
  5592.2   317.3  5613.1  320.06  5627.9  317.41  5779.1  321.23  5806.2  325.19
  5835.7  328.19  5865.2  321.41  5900.9  320.52  6043.5  323.24  6079.2  329.93
  6123.5  346.61  6189.1   351.8  6358.3  359.73  6579.1  363.74  6619.2   364.9
#Mann= 8 ,-1 , 0
  3645.5     .16       0  4007.6     .12       0    4075     .16       0
    4235    .033       0    4241     .16       0  4274.1     .05       0
  6189.1     .16       0  6579.1     .05       0
Bank Sta=4187.5,5806.2
XS Rating Curve= 0 ,0
Exp/Cntr=0.3,0.1

Type RM Length L Ch R = 1 ,6491    ,130,130,130
BEGIN DESCRIPTION:
Mapping XS 38779936
END DESCRIPTION:
XS GIS Cut Line= 3
      3685730.48     10753507.99      3685631.52     10752737.16
        3683819.     10751409.02
#Sta/Elev= 30
    3588  372.95  4046.5   336.1  4055.3  334.35  4184.8  328.11  4207.9  318.55
  4210.6  318.05  4213.9  318.55  4244.9  320.25  4259.3  329.73  4264.4  321.25
  4271.4  329.06  4301.6  329.94  4471.5   330.3    4622  321.58    4693  327.58
  4701.5  322.21  4772.5  324.07  4793.4  330.24  4872.8  323.92    4879  329.44
  4908.4  324.25  4929.2  330.18  5345.3  330.52  5853.2  332.51  5909.5  321.34
  6080.9   323.3  6175.1  349.99  6261.8  354.26  6510.1  361.35  6612.2  362.83
#Mann= 8 ,-1 , 0
    3588     .16       0  4046.5     .12       0  4055.3     .16       0
  4207.9     .03       0  4213.9     .16       0  4244.9     .05       0
  6261.8     .16       0  6510.1     .05       0
Bank Sta=4184.8,5345.3
XS Rating Curve= 0 ,0
Exp/Cntr=0.3,0.1

Type RM Length L Ch R = 1 ,6361    ,1562,1562,1562
BEGIN DESCRIPTION:
MILL BRANCH 5.0
END DESCRIPTION:
XS GIS Cut Line= 3
      3685875.01     10753423.15      3685750.01     10752662.73
      3683874.98     10751329.37
#Sta/Elev= 30
  3590.6  351.48    3902  334.99  3985.4  327.71  4046.8  319.92    4152  313.42
  4160.7  311.58  4168.2  307.87    4171  307.37  4174.2  307.87  4213.2  307.87
  4232.1  313.98  4364.5  312.63  4492.8  318.25  4549.4  313.59    4585  315.05
  4620.7  309.62  4674.4  309.71  4715.9  309.38  5704.1  310.98  5790.2  314.38
  5840.6  319.89  5853.6  324.48  5861.5  331.06  5870.2  331.65  5977.2  321.36
  6164.1  324.22  6235.4  346.96  6394.2  353.91  6431.7  354.55    6662  361.62
#Mann= 11 ,-1 , 0
  3590.6     .16       0  3985.4     .12       0  4046.8     .16       0
  4160.7     .12       0  4168.2     .07       0  4174.2     .12       0
  4674.4     .05       0  4715.9     .12       0  5853.6     .05       0
  6394.2     .16       0  6431.7     .05       0
Bank Sta=4152,4232.1
XS Rating Curve= 0 ,0
Exp/Cntr=0.3,0.1

Type RM Length L Ch R = 1 ,4799    ,1503,1503,1503
BEGIN DESCRIPTION:
MILL BRANCH 4.0
END DESCRIPTION:
XS GIS Cut Line= 2
      3687750.69     10752006.11      3684070.13     10750165.83
#Sta/Elev= 30
  3105.1  361.78  3206.9  355.39  3400.2  349.25  3730.2  326.34    3976  313.13
  4111.5  312.37  4151.5  313.02  4172.7  313.09  4243.6  313.08  4333.8  311.48
  4364.9   311.2  4473.4  312.18  4610.1  311.41  4799.2  310.57  4848.1  310.76
    4873  307.87  4875.8  307.37    4879  307.87  4885.4  307.87  5360.6  309.58
  5375.9  310.63  5630.7  308.73  5918.1  319.52  6010.8  324.41  6136.2  324.19
  6391.3  332.83  6691.6  342.11    6937  354.54    7045  358.52  7220.1  359.54
#Mann= 18 ,-1 , 0
  3105.1     .05       0  3730.2     .16       0  4111.5     .12       0
  4151.5     .16       0  4172.7     .12       0  4243.6     .16       0
  4364.9     .12       0  4473.4     .16       0  4610.1     .12       0
  4799.2     .16       0    4873    .033       0    4879     .16       0
  4885.4     .05       0  5360.6     .12       0  5918.1     .16       0
  6391.3     .12       0  6691.6     .05       0    6937     .16       0
Bank Sta=4333.8,5375.9
XS Rating Curve= 0 ,0
Exp/Cntr=0.3,0.1

Type RM Length L Ch R = 1 ,3296    ,1296,1296,1296
BEGIN DESCRIPTION:
MILL BRANCH 3.0
END DESCRIPTION:
XS GIS Cut Line= 3
      3687877.24     10751692.13      3686792.17     10749793.27
      3684102.88     10749771.58
#Sta/Elev= 30
  3004.6  366.84  3202.6  364.79  3253.1  360.15  3408.6  337.12  3553.4  321.97
  3663.3  310.29  3731.1  310.66  3755.4  307.87  3758.2  307.37  3761.4  307.87
  3787.6  307.87  4680.1  307.87    4823   310.1  4838.1  307.87  5916.4  307.87
  6024.2  310.81  6284.2  308.55  6474.2  311.36  6681.4  313.88  6780.4  318.62
  6904.2  323.05  6971.1   329.4    7084  336.36  7254.2  344.53  7294.3  342.63
  7314.3  347.45    7380  351.27  7564.3  361.36    7770  367.82    7881   369.2
#Mann= 14 ,-1 , 0
  3004.6     .05       0  3553.4     .12       0  3755.4    .033       0
  3761.4     .12       0  3787.6     .05       0  4680.1     .16       0
    4823     .05       0  5916.4     .16       0  6681.4     .12       0
  6780.4      .1       0  6971.1     .05       0    7084     .16       0
    7380     .12       0    7770     .16       0
Bank Sta=3731.1,6474.2
XS Rating Curve= 0 ,0
Exp/Cntr=0.3,0.1

Type RM Length L Ch R = 1 ,2000    ,1771,1771,1771
BEGIN DESCRIPTION:
MILL BRANCH 2.0
END DESCRIPTION:
XS GIS Cut Line= 4
      3687844.69     10751529.36      3688094.26     10749402.64
      3687866.39     10749131.38      3684352.69     10749250.67
#Sta/Elev= 30
    2634  368.11  3015.8  340.02  3144.9  339.91  3287.6  350.92  3388.3  351.52
  3763.7  327.03  3982.4     313  4239.5  309.52  4391.2  309.46  4430.6  309.32
  4780.2  312.01  4827.6  307.87  4830.3  307.37  4833.6  307.87  4880.8  307.87
  5156.1  307.87  5276.4  313.19  5590.5  322.64  5689.7  317.22  5788.8  308.88
  6910.3  307.87  7027.5  312.19  7147.5  308.54  7457.7  313.07  7636.1  310.71
  7746.2  316.09    7918  335.15  8001.2  337.82  8204.7  342.19  8645.3  368.46
#Mann= 17 ,-1 , 0
    2634     .05       0  3763.7     .16       0  4239.5     .12       0
  4391.2     .16       0  4430.6     .12       0  4827.6    .033       0
  4833.6     .12       0  4880.8     .05       0  5156.1     .16       0
  5590.5     .12       0  5689.7     .16       0  5788.8     .05       0
  6910.3     .12       0  7636.1     .16       0  7746.2     .12       0
  8001.2     .05       0  8204.7     .12       0
Bank Sta=4780.2,5276.4
XS Rating Curve= 0 ,0
Exp/Cntr=0.3,0.1

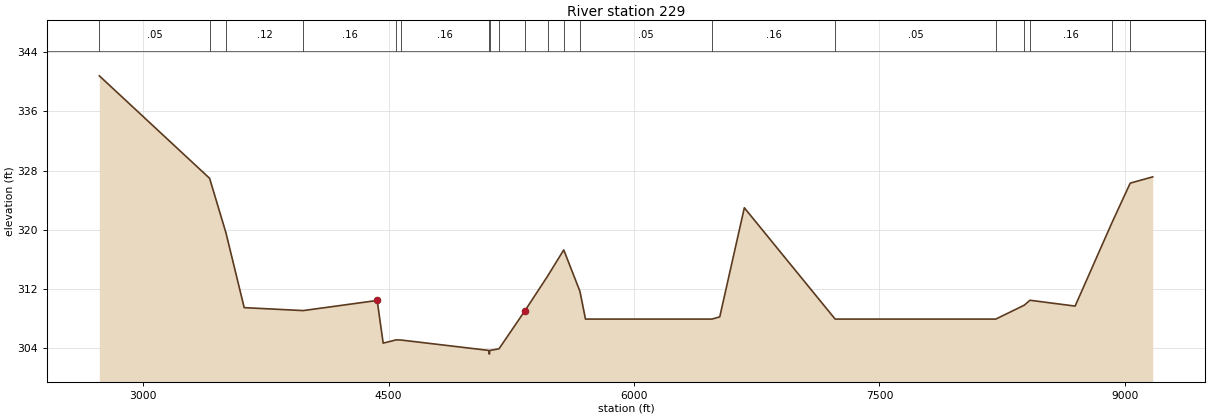
Type RM Length L Ch R = 1 ,229     ,0,0,0
BEGIN DESCRIPTION:
MILL BRANCH 1.0
END DESCRIPTION:
XS GIS Cut Line= 4
      3688224.49      10750943.4      3689363.79     10749098.83
      3689331.23     10748860.11       3685305.6     10748697.35
#Sta/Elev= 30
  2732.4  340.83  3406.4  326.94  3506.3  319.55  3617.7  309.42  3978.1  309.02
  4430.4  310.39  4467.1  304.61  4546.5  305.05  4576.5  305.03  5113.2  303.62
    5116  303.12  5119.2  303.62  5174.9  303.84    5331  308.92  5333.2  308.99
  5471.7  313.68  5570.6  317.24  5669.5  311.64  5703.5  307.87  6476.6  307.87
  6524.1  308.17  6674.3  322.95  7229.2  307.87  8211.5  307.87  8385.8  309.76
  8419.7  310.42  8695.9  309.63  8919.4  320.85  9032.6  326.29  9170.3  327.14
#Mann= 20 ,-1 , 0
  2732.4     .05       0  3406.4     .16       0  3506.3     .12       0
  3978.1     .16       0  4546.5     .12       0  4576.5     .16       0
  5113.2     .07       0  5119.2     .16       0  5174.9     .12       0
    5331     .16       0  5471.7     .12       0  5570.6     .16       0
  5669.5     .05       0  6476.6     .16       0  7229.2     .05       0
  8211.5     .16       0  8385.8     .12       0  8419.7     .16       0
  8919.4     .05       0  9032.6     .16       0
Bank Sta=4430.4,5333.2
XS Rating Curve= 0 ,0
Exp/Cntr=0.3,0.1

Chan Stop Cuts=-1
Use User Specified Reach Order=0
Composite Channel Slope=5