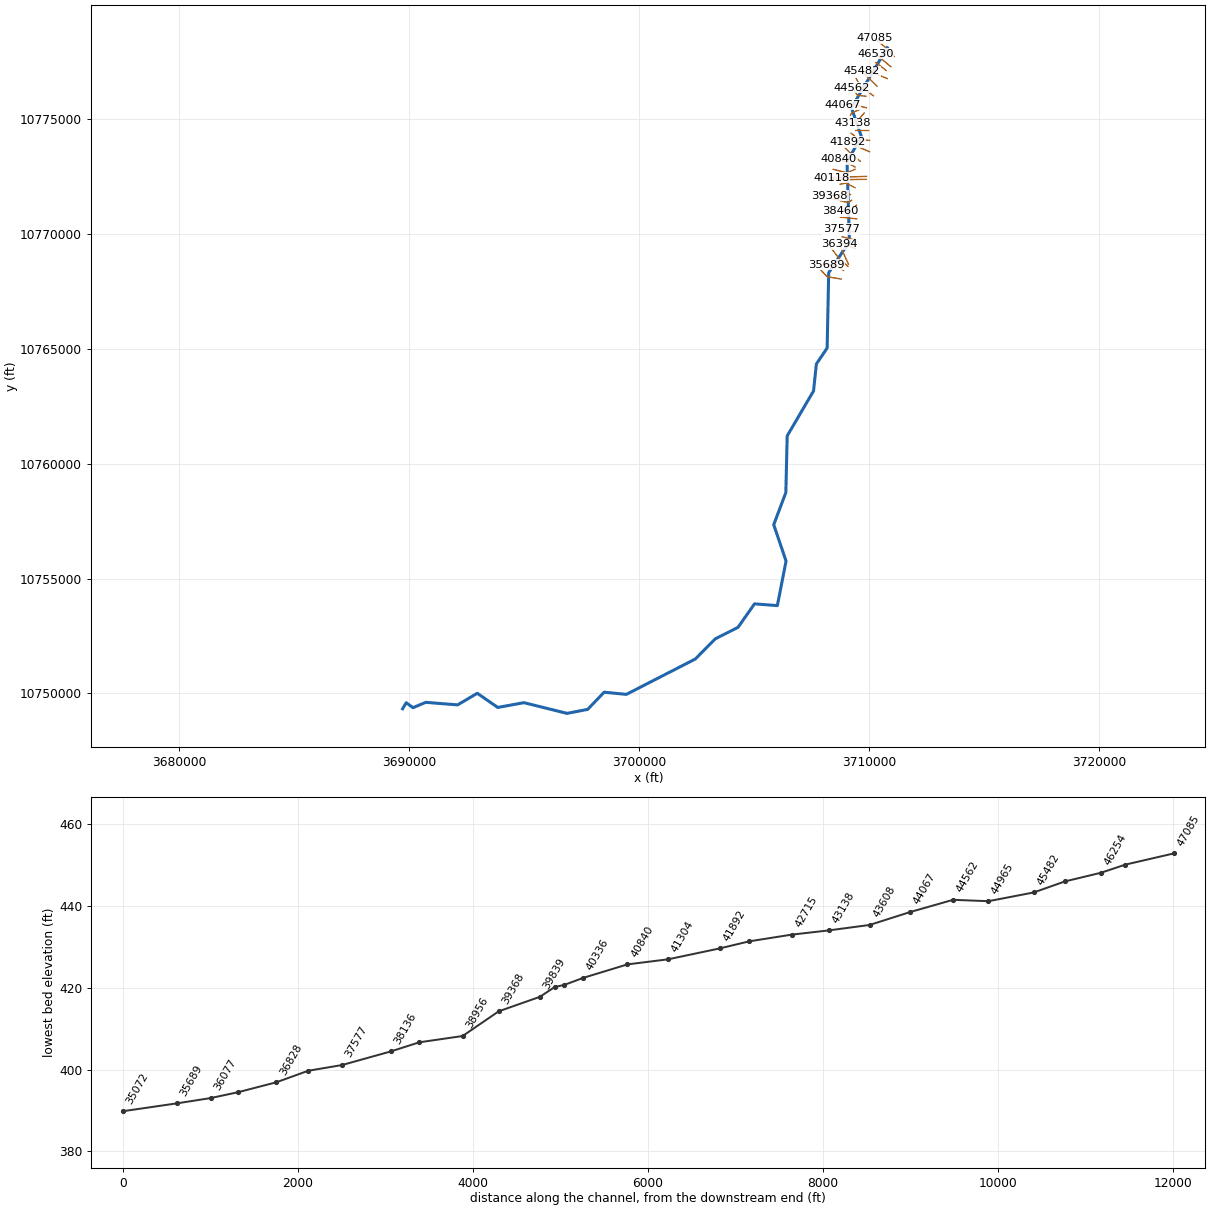
--- MINE CREEK.prj (project) ---

Proj Title=MINE CREEK Base Level Engineering
Current Plan=p01
Default Exp/Contr=0.3,0.1
English Units
Geom File=g01
Flow File=f01
Plan File=p01
Y Axis Title=Elevation
X Axis Title(PF)=Main Channel Distance
X Axis Title(XS)=Station
BEGIN DESCRIPTION:
MINE CREEK
END DESCRIPTION:
DSS Export Rating Curves= 0
DSS Export Rating Curve Sorted= 0
DSS Export Volume Flow Curves= 0
DXF OffsetX= 0
DXF OffsetY= 0
DXF ScaleX= 1
DXF ScaleY= 10

--- MINE CREEK.p01 (plan) ---

Plan Title=Multiple Run
Program Version=4.10
Short Identifier=Multiple
Geom File=g01
Flow File=f01
Subcritical Flow
K Sum by GR= 0
Std Step Tol= 0.01
Critical Tol= 0.01
Num of Std Step Trials= 20
Max Error Tol= 0.3
Flow Tol Ratio= 0.001
Split Flow NTrial= 30
Split Flow Tol= 0.02
Split Flow Ratio= 0.02
Log Output Level= 0
Friction Slope Method= 1
Unsteady Friction Slope Method= 2
Unsteady Bridges Friction Slope Method= 1
Parabolic Critical Depth
Global Vel Dist= 1 , 1 , 1
Global Log Level= 0
CheckData=True
Encroach Param=-1 ,0,0, 0
BEGIN DESCRIPTION:
Multiple Run
END DESCRIPTION:
Computation Interval=1HOUR
Output Interval=1HOUR
Run HTab= 0
Run UNet= 0
Run PostProcess= 0
Run WQNet= 0
UNET Theta= 1
UNET Theta Warmup= 1
UNET ZTol= 0.02
UNET ZSATol= 0.05
UNET MxIter= 20
UNET MaxInSteps= 0
UNET DtIC= 0
UNET DtMin= 0
UNET MaxCRTS= 20
UNET WFStab= 2
UNET SFStab= 1
UNET WFX= 1
UNET SFX= 1
UNET DSS MLevel= 4
UNET DZMax Abort= 100
UNET Convert EG Bridges= 0
UNET Use Existing IB Tables=-1
UNET Froude Reduction=False
UNET Froude Limit= 1
UNET Froude Power= 10
UNET Time Slicing=0,0, 5
UNET Junction Losses=0
Instantaneous Interval=1HOUR
Write IC File= 0
Write IC File at Sim End=0
Echo Input=False
Echo Parameters=False
Echo Output=False
Write Detailed= 0
WQ AD Non Conservative
WQ ULTIMATE=-1
WQ Max Comp Step=1HOUR
WQ Output Interval=15MIN
WQ Output Selected Increments= 0
WQ Output face flow=0
WQ Output face velocity=0
WQ Output face area=0
WQ Output face dispersion=0
WQ Output cell volume=0
WQ Output cell surface area=0
WQ Output cell continuity=0
WQ Output cumulative cell continuity=0
WQ Output face conc=0
WQ Output face dconc_dx=0
WQ Output face courant=0
WQ Output face peclet=0
WQ Output face adv mass=0
WQ Output face disp mass=0
WQ Output cell mass=0
WQ Output cell source sink temp=0
WQ Output cell source sink nsm=0
WQ Output MaxMinRange=-1
WQ Daily Max Min Mean=-1
WQ Daily Range=0
WQ Daily Time=0
WQ Create Restart=0
WQ Fixed Restart=0
WQ System Summary=0
WQ Use Fixed Temperature=0
Sorting and Armoring Iterations= 10
XS Update Threshold= 0.02
Hydraulics Update Threshold= 0.02
Energy Slope Method= 1
Volume Change Method= 0
XS Weighting Method= 0
Number of US Weighted Cross Sections= 1
Number of DS Weighted Cross Sections= 1
Upstream XS Weight=0.25
Main XS Weight=0.5
Downstream XS Weight=0.25
Number of DS XS's Weighted with US Boundary= 1
Upstream Boundary Weight= 1
Weight of XSs Associated with US Boundary= 0
Number of US XS's Weighted with DS Boundary= 1
Downstream Boundary Weight= 0.5
Weight of XSs Associated with DS Boundary= 0.5
Sediment Output Level= 4
Mass or Volume Output= 0
Output Increment Type= 1
Profile and TS Output Increment= 10
XS Output Flag= 0
XS Output Increment= 10
Disregard all LS=0
Disregard all Conn=0
Disregard all Breaches=0
Disregard all Pumps=0

--- MINE CREEK.f01 (steady flow) ---

Flow Title=Multiple
Program Version=4.10
Number of Profiles= 7
Profile Names=10-year,25-year,50-year,1pct_min,100-year,1pct_plu,500-year
River Rch & RM=MINE CREEK,Reach-1         ,47085
     577     774     935     828    1120    1514    1609
River Rch & RM=MINE CREEK,Reach-1         ,46254
     868    1190    1457    1305    1765    2387    2600
River Rch & RM=MINE CREEK,Reach-1         ,40008
    1098    1527    1887    1706    2307    3120    3461
River Rch & RM=MINE CREEK,Reach-1         ,36394
    1802    2556    3201    2928    3960    5355    6079
River Rch & RM=MINE CREEK,Reach-1         ,36077
    1802    2556    3201    2928    3960    5355    6079
River Rch & RM=MINE CREEK,Reach-1         ,28917
    1944    2758    3454    3159    4272    5778    6556
River Rch & RM=MINE CREEK,Reach-1         ,20179
    2552    3659    4615    4247    5743    7767    8924
River Rch & RM=MINE CREEK,Reach-1         ,19024
    2552    3659    4615    4247    5743    7767    8924
River Rch & RM=MINE CREEK,Reach-1         ,17717
    2671    3832    4837    4453    6022    8144    9367
River Rch & RM=MINE CREEK,Reach-1         ,16362
    2833    4075    5152    4751    6425    8689   10025
River Rch & RM=MINE CREEK,Reach-1         ,10500
    2935    4222    5337    4919    6653    8997   10372
River Rch & RM=MINE CREEK,Reach-1         ,7464
    3150    4530    5726    5275    7134    9648   11113
River Rch & RM=MINE CREEK,Reach-1         ,1956
    3353    4841    6135    5668    7665   10366   12003
Boundary for River Rch & Prof#=MINE CREEK,Reach-1         , 1
Up Type= 0
Dn Type= 3
Dn Slope=0.00326
Boundary for River Rch & Prof#=MINE CREEK,Reach-1         , 2
Up Type= 0
Dn Type= 3
Dn Slope=0.00326
Boundary for River Rch & Prof#=MINE CREEK,Reach-1         , 3
Up Type= 0
Dn Type= 3
Dn Slope=0.00326
Boundary for River Rch & Prof#=MINE CREEK,Reach-1         , 4
Up Type= 0
Dn Type= 3
Dn Slope=0.00326
Boundary for River Rch & Prof#=MINE CREEK,Reach-1         , 5
Up Type= 0
Dn Type= 3
Dn Slope=0.00326
Boundary for River Rch & Prof#=MINE CREEK,Reach-1         , 6
Up Type= 0
Dn Type= 3
Dn Slope=0.00326
Boundary for River Rch & Prof#=MINE CREEK,Reach-1         , 7
Up Type= 0
Dn Type= 3
Dn Slope=0.00326
DSS Import GetInterval= 0
DSS Import GetPeak= 0
DSS Import FillOption= 0

--- MINE CREEK.g01 (geometry) ---

Geom Title=Existing Conditions
Program Version=4.10

River Reach=MINE CREEK      ,Reach-1
Reach XY= 30
      3710799.95     10778101.36      3709242.75       10775489.
       3709677.5       10774231.      3709050.75       10773150.
        3709156.       10769665.      3708254.25       10768314.
        3708187.       10765031.       3707716.5       10764334.
        3707596.       10763165.       3706449.5       10761206.
      3706390.75       10758741.       3705863.5       10757342.
        3706400.       10755761.      3706021.25       10753821.
      3705027.25       10753897.      3704307.75       10752872.
      3703323.25       10752377.       3702453.5       10751497.
        3699455.       10749958.       3698488.5       10750052.
      3697772.75       10749305.      3696874.25       10749131.
        3695002.       10749597.        3693863.       10749389.
      3692970.75       10750006.      3692116.75       10749501.
      3690732.25       10749611.      3690176.75       10749379.
       3689880.5       10749595.      3689723.25       10749329.

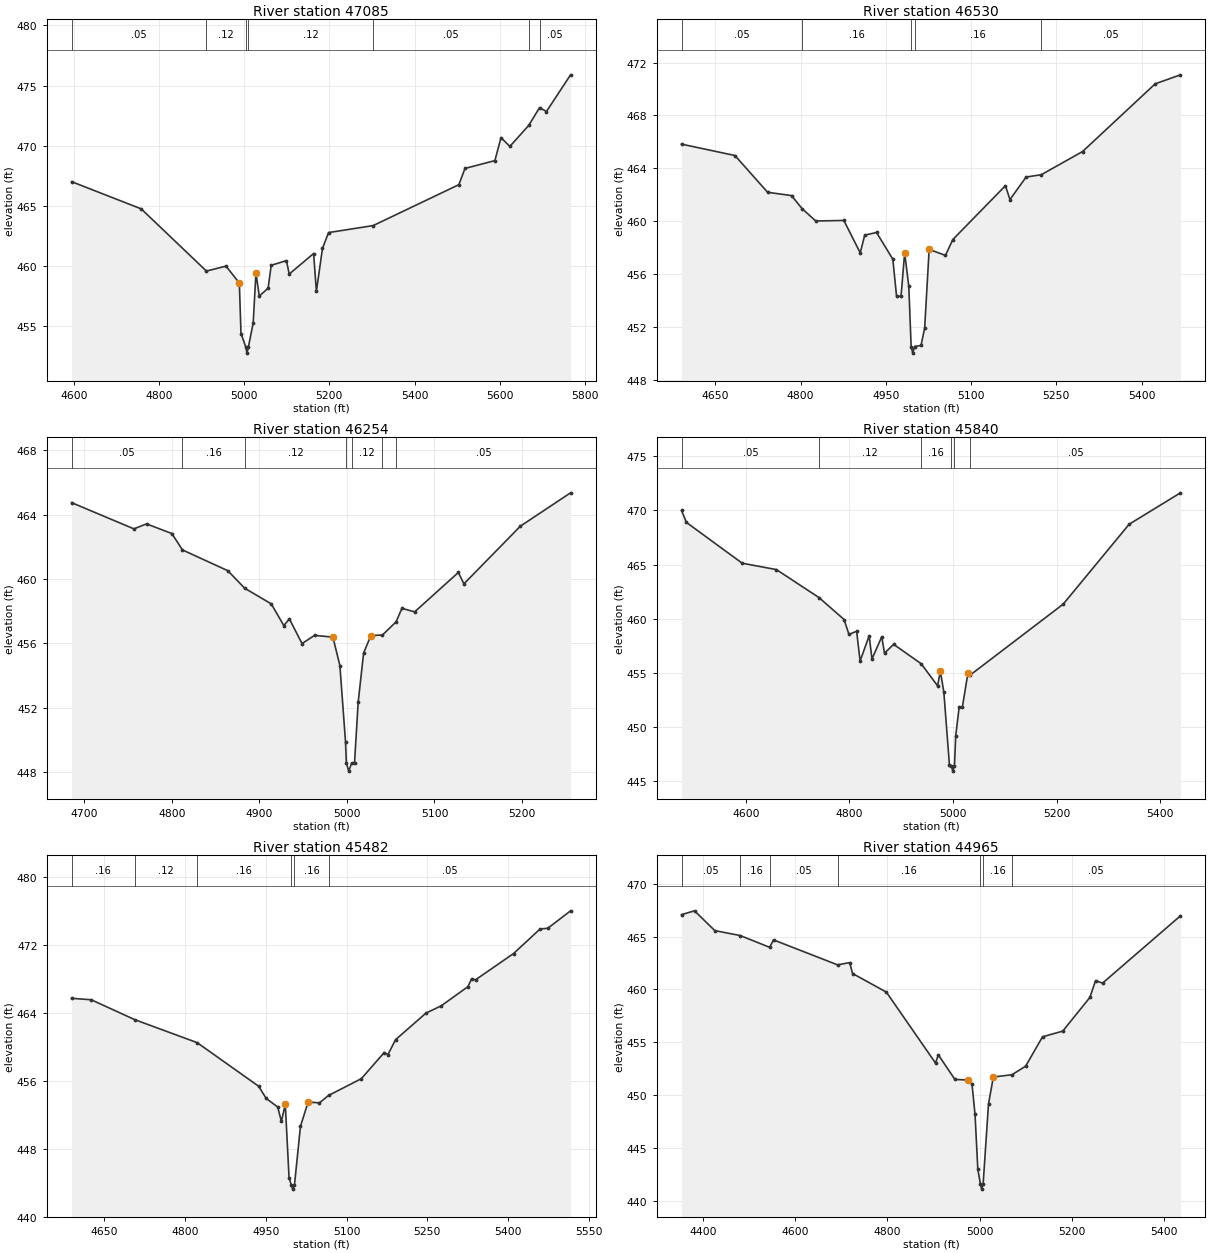
Type RM Length L Ch R = 1 ,47085   ,555,555,555
BEGIN DESCRIPTION:
MINE CREEK 96.0
END DESCRIPTION:
XS GIS Cut Line= 3
       3711099.6     10777710.19      3710849.61     10778010.19
      3710249.63     10778510.17
#Sta/Elev= 30
  4594.8  467.02  4758.2  464.76  4911.3  459.59  4957.3     460  4988.6   458.6
  4992.5   454.4  5003.8  453.27  5006.5  452.77  5009.8  453.27  5021.1  455.27
  5027.6  459.43  5035.4  457.51  5056.2  458.17  5063.4  460.07  5099.2  460.46
  5105.7  459.34    5163  461.05  5169.5   457.9  5183.8  461.47  5198.1  462.79
  5302.8  463.37    5504  466.77  5518.4  468.12  5588.6  468.77    5603  470.68
  5623.8  469.95  5668.2   471.7  5693.6  473.18  5709.7  472.85  5766.3   475.9
#Mann= 7 ,-1 , 0
  4594.8     .05       0  4911.3     .12       0  5003.8     .07       0
  5009.8     .12       0  5302.8     .05       0  5668.2     .16       0
  5693.6     .05       0
Bank Sta=4988.6,5027.6
XS Rating Curve= 0 ,0
Exp/Cntr=0.3,0.1

Type RM Length L Ch R = 1 ,46530   ,276,276,276
BEGIN DESCRIPTION:
MINE CREEK 95.0
END DESCRIPTION:
XS GIS Cut Line= 2
      3710959.64     10777277.54      3710279.07     10777832.41
#Sta/Elev= 30
  4590.4  465.83  4684.4  464.97  4741.9  462.19    4784  461.94  4802.6  460.95
  4826.6  460.02  4876.1  460.06  4904.9  457.61  4912.8  458.95  4933.6  459.15
  4962.3  457.13  4968.8  454.35  4976.7  454.32  4983.1  457.62  4990.4  455.07
  4994.5  450.53  4997.3  450.03  5000.5  450.53  5011.9  450.61  5018.3  451.92
  5026.2  457.87  5054.9  457.42  5067.9  458.62  5160.5  462.69  5168.4  461.64
  5196.8  463.34  5223.6  463.52  5296.2  465.27    5424  470.39  5468.5  471.07
#Mann= 5 ,-1 , 0
  4590.4     .05       0  4802.6     .16       0  4994.5     .07       0
  5000.5     .16       0  5223.6     .05       0
Bank Sta=4983.1,5026.2
XS Rating Curve= 0 ,0
Exp/Cntr=0.3,0.1

Type RM Length L Ch R = 1 ,46254   ,414,414,414
BEGIN DESCRIPTION:
MINE CREEK 94.0
END DESCRIPTION:
XS GIS Cut Line= 3
      3710749.62     10777110.18      3710499.61     10777310.19
      3710299.58     10777460.21
#Sta/Elev= 30
  4685.3  464.75  4756.5  463.12  4770.9  463.43  4799.8  462.83    4812  461.81
  4863.8  460.52  4883.1  459.43  4913.4  458.46  4927.8  457.11  4934.2  457.52
  4948.6  455.99    4963   456.5  4983.9  456.39  4991.9  454.62  4998.3  449.89
  4999.3  448.56    5002  448.06  5005.3  448.56  5008.6  448.56  5012.8  452.35
    5019   455.4  5027.3  456.49  5040.5  456.52  5056.1  457.34  5062.8  458.18
  5077.3  457.96  5127.3  460.41  5133.6   459.7  5198.2  463.29  5255.5  465.36
#Mann= 7 ,-1 , 0
  4685.3     .05       0    4812     .16       0  4883.1     .12       0
  4999.3     .07       0  5005.3     .12       0  5040.5     .16       0
  5056.1     .05       0
Bank Sta=4983.9,5027.3
XS Rating Curve= 0 ,0
Exp/Cntr=0.3,0.1

Type RM Length L Ch R = 1 ,45840   ,358,358,358
BEGIN DESCRIPTION:
MINE CREEK 93.0
END DESCRIPTION:
XS GIS Cut Line= 3
      3710799.59      10776760.2      3710299.61     10776960.19
      3709999.58     10777260.22
#Sta/Elev= 30
  4476.1     470  4485.5   468.9  4593.2  465.13  4659.2  464.54  4741.6  461.95
  4789.8  459.93  4799.2  458.55    4814  458.85  4820.7   456.1  4838.2  458.43
  4843.6  456.29  4862.5  458.34  4867.8  456.82  4885.4  457.64  4938.5  455.85
  4970.2  453.81  4975.6  455.15  4982.3  453.22  4993.1   446.5  4996.8  446.43
  4999.5  445.93  5002.8  446.43  5005.2  449.19  5011.9  451.87  5018.1  451.87
  5028.7  454.96  5033.3  454.81  5212.6  461.35  5339.9  468.73  5438.9  471.63
#Mann= 6 ,-1 , 0
  4476.1     .05       0  4741.6     .12       0  4938.5     .16       0
  4996.8     .07       0  5002.8     .16       0  5033.3     .05       0
Bank Sta=4975.6,5028.7
XS Rating Curve= 0 ,0
Exp/Cntr=0.3,0.1

Type RM Length L Ch R = 1 ,45482   ,517,517,517
BEGIN DESCRIPTION:
MINE CREEK 92.0
END DESCRIPTION:
XS GIS Cut Line= 2
      3710357.19     10776426.15      3709694.89     10777075.47
#Sta/Elev= 30
  4588.9  465.74  4625.4  465.57  4706.3  463.22  4822.3  460.51  4936.5  455.37
  4950.6  453.93  4971.9  452.92  4978.9  451.22  4986.1  453.25  4993.1   444.6
  4997.2  443.73    5000  443.23  5003.2  443.73  5014.3  450.63  5028.5   453.5
  5049.6  453.41  5066.5  454.28  5127.5  456.26  5169.9  459.34  5176.9   459.1
  5191.1  460.86  5247.7     464  5275.9  464.85  5325.5  467.11  5332.5  468.04
  5339.7  467.92  5410.4  471.02  5459.8  473.92    5474     474  5516.4  476.06
#Mann= 6 ,-1 , 0
  4588.9     .16       0  4706.3     .12       0  4822.3     .16       0
  4997.2     .07       0  5003.2     .16       0  5066.5     .05       0
Bank Sta=4986.1,5028.5
XS Rating Curve= 0 ,0
Exp/Cntr=0.3,0.1

Type RM Length L Ch R = 1 ,44965   ,403,403,403
BEGIN DESCRIPTION:
MINE CREEK 91.0
END DESCRIPTION:
XS GIS Cut Line= 3
      3710199.59      10776010.2      3709649.61     10776410.19
      3709449.59     10776760.22
#Sta/Elev= 30
  4353.1  467.07  4381.3  467.43  4425.3  465.56  4480.6  465.09  4544.3  463.98
  4552.8  464.68  4691.8  462.32  4718.2  462.53  4724.4   461.5  4797.8  459.74
  4904.5  453.03  4910.7   453.8  4946.6  451.48  4975.6  451.42  4983.7  451.05
  4990.3  448.17  4996.4  442.97  5001.9   441.6  5004.7   441.1  5007.9   441.6
  5019.6  449.18  5030.1  451.71  5070.4  451.92  5100.1  452.73  5136.8  455.51
  5180.7  456.05  5239.7  459.24    5252  460.83  5267.1  460.59  5436.3  466.96
#Mann= 7 ,-1 , 0
  4353.1     .05       0  4480.6     .16       0  4544.3     .05       0
  4691.8     .16       0  5001.9     .07       0  5007.9     .16       0
  5070.4     .05       0
Bank Sta=4975.6,5030.1
XS Rating Curve= 0 ,0
Exp/Cntr=0.3,0.1

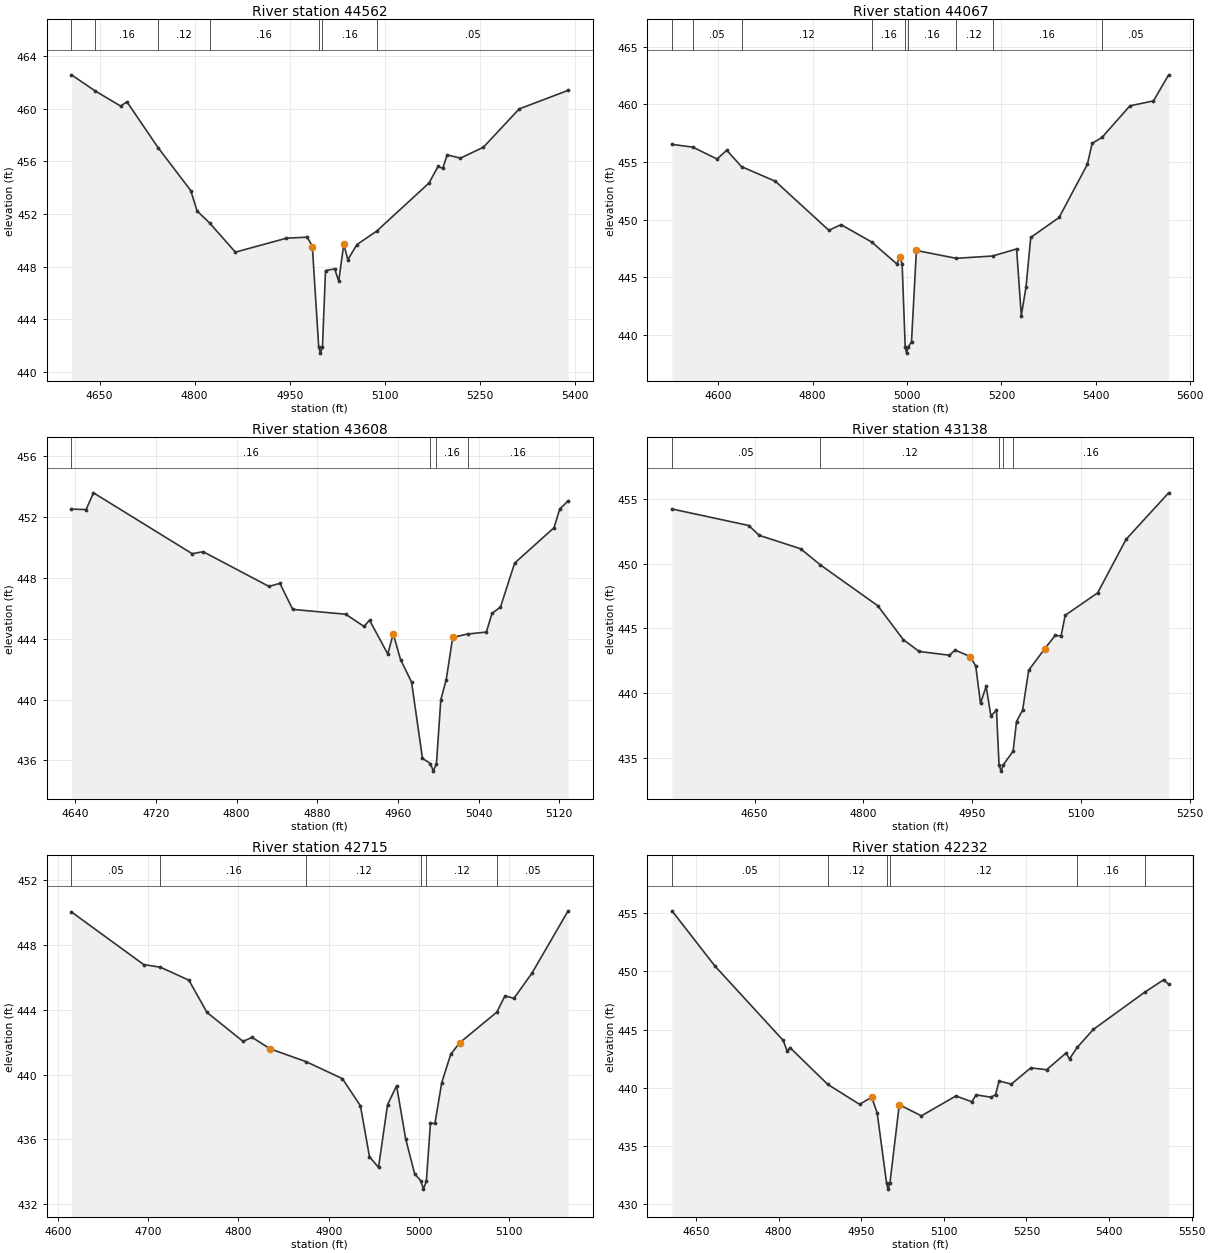
Type RM Length L Ch R = 1 ,44562   ,495,495,495
BEGIN DESCRIPTION:
MINE CREEK 90.0
END DESCRIPTION:
XS GIS Cut Line= 3
      3709866.53     10775990.67      3709514.95     10776029.73
      3709245.43     10776364.35
#Sta/Elev= 30
  4605.7  462.58  4642.3  461.38  4683.1  460.21  4693.2  460.53  4742.4  457.04
  4793.8  453.79  4803.8  452.24  4823.5  451.33  4864.2  449.11  4944.7  450.17
  4977.6  450.25  4985.6  449.53  4995.6  441.94  4998.3  441.44  5001.6  441.94
  5006.4  447.71  5020.8  447.84  5027.2  446.91  5035.2  449.72  5041.6  448.54
    5056  449.69  5086.9   450.7  5169.6  454.36    5184  455.63  5191.2  455.47
  5198.3   456.5  5219.2  456.25  5255.4  457.08  5311.9  459.99  5389.1   461.4
#Mann= 7 ,-1 , 0
  4605.7     .05       0  4642.3     .16       0  4742.4     .12       0
  4823.5     .16       0  4995.6     .07       0  5001.6     .16       0
  5086.9     .05       0
Bank Sta=4985.6,5035.2
XS Rating Curve= 0 ,0
Exp/Cntr=0.3,0.1

Type RM Length L Ch R = 1 ,44067   ,459,459,459
BEGIN DESCRIPTION:
MINE CREEK 89.0
END DESCRIPTION:
XS GIS Cut Line= 3
      3709892.25     10775489.36      3709315.82     10775631.73
      3708857.53     10775624.78
#Sta/Elev= 30
  4502.2  456.53  4546.5  456.29  4597.6  455.26  4618.2  456.02  4649.5   454.6
  4721.2  453.33  4834.5  449.08  4860.2  449.57    4925  448.07  4978.7  446.16
  4984.6  446.77  4989.7  446.18  4996.3  438.93  4999.1  438.43  5002.3  438.93
  5009.6  439.43  5019.9  447.33  5104.3  446.65  5181.2  446.85  5232.2  447.46
  5242.2  441.69  5252.2  444.17  5262.2  448.46  5322.2  450.19  5382.2   454.8
  5392.2  456.62  5413.1  457.13  5472.2  459.87  5522.2   460.3  5554.3  462.56
#Mann= 9 ,-1 , 0
  4502.2     .16       0  4546.5     .05       0  4649.5     .12       0
    4925     .16       0  4996.3     .07       0  5002.3     .16       0
  5104.3     .12       0  5181.2     .16       0  5413.1     .05       0
Bank Sta=4984.6,5019.9
XS Rating Curve= 0 ,0
Exp/Cntr=0.3,0.1

Type RM Length L Ch R = 1 ,43608   ,470,470,470
BEGIN DESCRIPTION:
MINE CREEK 88.0
END DESCRIPTION:
XS GIS Cut Line= 3
      3709599.61     10775410.19      3709249.61     10775260.19
       3709199.6     10775160.18
#Sta/Elev= 30
  4636.2  452.52  4650.7  452.49    4658  453.59  4755.9  449.59  4766.8  449.72
    4832  447.44  4842.9  447.64  4855.6  445.93  4908.2  445.61  4926.3  444.81
  4931.8  445.22  4949.9     443  4955.3  444.32  4962.6  442.63  4973.5  441.15
  4984.3  436.14  4992.2   435.8    4995   435.3  4998.2   435.8  5002.5  439.99
  5007.9  441.32  5014.3  444.09    5029  444.31  5047.7  444.44  5053.3  445.67
  5061.7  446.08  5075.7  448.97  5114.8   451.3  5120.4  452.51  5128.8  453.07
#Mann= 4 ,-1 , 0
  4636.2     .16       0  4992.2     .07       0  4998.2     .16       0
    5029     .16       0
Bank Sta=4955.3,5014.3
XS Rating Curve= 0 ,0
Exp/Cntr=0.3,0.1

Type RM Length L Ch R = 1 ,43138   ,423,423,423
BEGIN DESCRIPTION:
MINE CREEK 87.0
END DESCRIPTION:
XS GIS Cut Line= 3
      3709799.61     10775260.18      3709499.61     10774910.19
      3709299.59     10774810.18
#Sta/Elev= 30
  4536.2  454.25  4642.1  452.97  4656.4  452.21  4713.5  451.17  4740.8  449.92
  4819.9  446.76    4855  444.14    4877  443.22  4918.7  442.93  4926.4  443.33
  4947.2  442.83  4954.9  442.09  4961.5  439.21  4969.2  440.52  4975.8  438.24
  4983.5  438.67    4987  434.46  4989.8  433.96    4993  434.46  5006.4   435.5
  5011.1   437.8  5019.5  438.68  5027.9  441.77  5050.3  443.45  5064.3  444.46
  5072.6  444.43  5078.2  446.02    5123  447.76  5162.1   451.9  5220.8   455.5
#Mann= 5 ,-1 , 0
  4536.2     .05       0  4740.8     .12       0    4987     .07       0
    4993     .12       0  5006.4     .16       0
Bank Sta=4947.2,5050.3
XS Rating Curve= 0 ,0
Exp/Cntr=0.3,0.1

Type RM Length L Ch R = 1 ,42715   ,483,483,483
BEGIN DESCRIPTION:
MINE CREEK 86.0
END DESCRIPTION:
XS GIS Cut Line= 3
      3709949.58     10774510.19      3709549.61     10774510.19
      3709399.58     10774510.19
#Sta/Elev= 30
  4615.1  450.04  4695.1  446.79  4713.5  446.63  4745.1  445.83  4765.1  443.84
  4805.1  442.05  4815.1   442.3  4835.1  441.59  4875.3  440.79  4915.1  439.75
  4935.1  438.07  4945.1  434.93  4955.1  434.27  4965.1  438.14  4975.1  439.31
  4985.1  436.05  4995.1  433.88  5002.1  433.43  5004.8  432.93  5008.1  433.43
  5012.6  436.99  5017.6  436.99  5025.1   439.5  5035.1  441.26  5045.1  441.97
  5086.2  443.86  5095.1  444.86  5105.1  444.71  5125.1  446.27  5165.1  450.11
#Mann= 6 ,-1 , 0
  4615.1     .05       0  4713.5     .16       0  4875.3     .12       0
  5002.1     .07       0  5008.1     .12       0  5086.2     .05       0
Bank Sta=4835.1,5045.1
XS Rating Curve= 0 ,0
Exp/Cntr=0.3,0.1

Type RM Length L Ch R = 1 ,42232   ,340,340,340
BEGIN DESCRIPTION:
MINE CREEK 85.0
END DESCRIPTION:
XS GIS Cut Line= 3
      3710031.08     10774069.23      3709572.76     10774103.95
        3709229.     10774381.74
#Sta/Elev= 30
  4606.6  455.19  4684.4  450.46  4808.6  444.06  4815.8  443.13  4820.8  443.45
  4889.4  440.29  4947.1  438.58  4969.1  439.19  4979.1  437.84  4996.2   431.8
  4998.9   431.3  5002.2   431.8  5019.2  438.55  5059.4  437.59    5122   439.3
  5150.8   438.8  5158.8  439.39    5186  439.19    5194  439.42  5200.4  440.58
  5222.7  440.32  5257.9  441.71  5286.7  441.55  5321.9  442.98  5328.3  442.48
  5342.1  443.46  5371.5  445.01  5464.7   448.2  5499.4  449.28  5508.2  448.87
#Mann= 6 ,-1 , 0
  4606.6     .05       0  4889.4     .12       0  4996.2     .07       0
  5002.2     .12       0  5342.1     .16       0  5464.7     .05       0
Bank Sta=4969.1,5019.2
XS Rating Curve= 0 ,0
Exp/Cntr=0.3,0.1

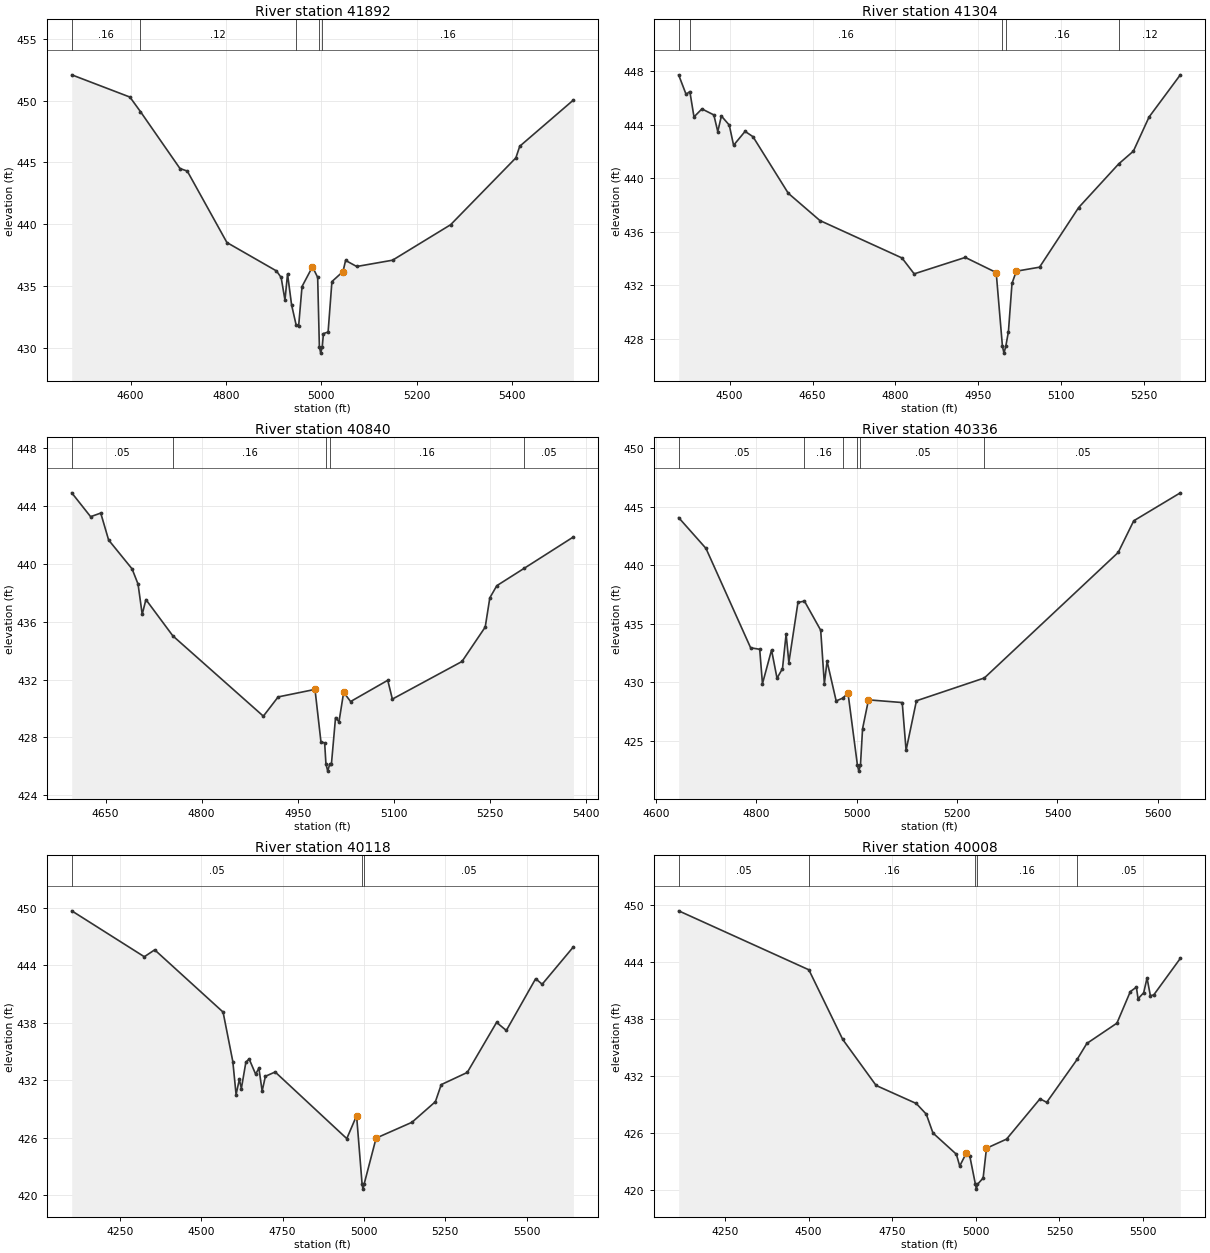
Type RM Length L Ch R = 1 ,41892   ,588,588,588
BEGIN DESCRIPTION:
MINE CREEK 84.0
END DESCRIPTION:
XS GIS Cut Line= 2
      3710031.13     10773572.68      3709069.29     10773999.78
#Sta/Elev= 30
  4476.5  452.08  4598.5  450.28  4620.7   449.1  4703.5   444.5  4718.9  444.29
    4802  438.51    4906  436.21  4915.8  435.68  4923.8  433.85  4929.2  435.97
  4937.7  433.46  4947.2  431.84  4952.5  431.76  4959.6  434.95  4981.5  436.55
  4992.4  435.69    4996  430.06  4998.8  429.56    5002  430.06  5004.5  431.14
  5014.3  431.27  5022.3  435.35  5045.5  436.16    5051  437.06  5074.3  436.57
  5149.5  437.08  5271.3  439.95  5408.2  445.36  5416.3   446.3  5528.9  450.04
#Mann= 5 ,-1 , 0
  4476.5     .16       0  4620.7     .12       0  4947.2     .16       0
    4996     .07       0    5002     .16       0
Bank Sta=4981.5,5045.5
XS Rating Curve= 0 ,0
Exp/Cntr=0.3,0.1

Type RM Length L Ch R = 1 ,41304   ,464,464,464
BEGIN DESCRIPTION:
MINE CREEK 83.0
END DESCRIPTION:
XS GIS Cut Line= 3
      3709628.35     10773159.47      3709149.61     10773560.19
      3708949.58     10773760.22
#Sta/Elev= 30
  4407.9  447.72  4421.3  446.27  4428.1  446.48  4435.6  444.58  4449.9  445.18
  4471.5  444.73  4478.6  443.48  4485.1  444.65  4499.4  443.97  4507.2  442.46
    4528   443.5  4542.3   443.1  4606.1  438.87  4663.3  436.83  4811.7  434.03
  4833.8  432.84  4926.2  434.07  4982.1  432.94  4993.4  427.41  4996.2  426.91
  4999.4  427.41  5004.2  428.51  5010.7  432.13  5018.5  433.04  5060.5  433.34
  5131.2   437.8  5203.7  441.07  5230.2  442.02  5258.5  444.57  5315.1  447.73
#Mann= 5 ,-1 , 0
  4407.9     .05       0  4428.1     .16       0  4993.4     .07       0
  4999.4     .16       0  5203.7     .12       0
Bank Sta=4982.1,5018.5
XS Rating Curve= 0 ,0
Exp/Cntr=0.3,0.1

Type RM Length L Ch R = 1 ,40840   ,504,504,504
BEGIN DESCRIPTION:
MINE CREEK 82.0
END DESCRIPTION:
XS GIS Cut Line= 3
       3709399.6      10772910.2      3709049.61     10773110.19
       3708699.6     10773260.19
#Sta/Elev= 30
    4597  444.91  4626.5  443.26  4642.3  443.51  4654.6  441.65  4691.3  439.65
  4700.6   438.6  4707.1  436.51  4712.9  437.53    4755  435.02  4896.4  429.47
  4919.5   430.8  4977.1  431.32  4986.4   427.7  4992.2  427.62  4994.2  426.17
    4997  425.67  5000.2  426.17  5002.8  426.17  5009.2  429.37  5014.6  429.08
  5021.9  431.12  5032.7  430.48  5090.8  431.95    5098  430.65  5206.8  433.25
  5243.1  435.63  5250.3  437.65  5261.2  438.49  5304.3   439.7  5380.9  441.86
#Mann= 5 ,-1 , 0
    4597     .05       0    4755     .16       0  4994.2     .07       0
  5000.2     .16       0  5304.3     .05       0
Bank Sta=4977.1,5021.9
XS Rating Curve= 0 ,0
Exp/Cntr=0.3,0.1

Type RM Length L Ch R = 1 ,40336   ,218,218,218
BEGIN DESCRIPTION:
MINE CREEK 81.0
END DESCRIPTION:
XS GIS Cut Line= 3
      3709399.65     10772810.21      3709049.61     10772660.19
      3708449.61     10772810.19
#Sta/Elev= 30
  4645.5  444.05  4699.9  441.42  4788.8  432.93  4806.9   432.8  4812.4  429.86
  4830.5  432.74  4841.4  430.33  4852.3  431.15  4859.5   434.1    4865  431.67
  4883.1   436.8    4896  436.92  4928.4  434.43  4935.7  429.86  4941.1  431.78
  4959.2  428.39  4972.5  428.63  4982.8  429.06  5001.6  422.89  5004.3  422.39
  5007.6  422.89  5011.8  426.01  5023.6  428.48  5090.8  428.25  5098.5  424.17
  5119.1   428.4  5254.4  430.35  5521.1  441.08    5552  443.78  5644.8  446.17
#Mann= 6 ,-1 , 0
  4645.5     .05       0    4896     .16       0  4972.5     .05       0
  5001.6     .03       0  5007.6     .05       0  5254.4     .05       0
Bank Sta=4982.8,5023.6
XS Rating Curve= 0 ,0
Exp/Cntr=0.3,0.1

Type RM Length L Ch R = 1 ,40118   ,110,110,110
BEGIN DESCRIPTION:
Mapping XS 16be5ee7
END DESCRIPTION:
XS GIS Cut Line= 2
      3709904.37     10772502.82      3708363.64     10772450.77
#Sta/Elev= 30
  4101.9  449.69  4324.9   444.9  4356.8  445.62  4566.9  439.13  4596.9  433.97
  4606.9  430.52  4616.9  432.11  4623.1  431.15    4637   433.9    4647  434.24
    4667  432.65    4677  433.28    4687  430.89    4697  432.43    4727  432.88
  4947.1  425.93  4977.2  428.32  4994.2  421.16  4996.9  420.66  5000.2  421.16
  5037.2  425.98  5147.3  427.63  5219.4  429.78  5237.3  431.56  5317.3  432.83
  5407.4  438.05  5437.4  437.21  5527.5  442.61  5547.5  442.03  5643.5  445.93
#Mann= 3 ,-1 , 0
  4101.9     .05       0  4994.2     .04       0  5000.2     .05       0
Bank Sta=4977.2,5037.2
XS Rating Curve= 0 ,0
Exp/Cntr=0.3,0.1

Type RM Length L Ch R = 1 ,40008   ,169,169,169
BEGIN DESCRIPTION:
Mapping XS c03bbc99
END DESCRIPTION:
XS GIS Cut Line= 3
      3709879.87      10772375.6      3709164.61     10772361.71
      3708380.07     10772377.82
#Sta/Elev= 30
  4111.3  449.35  4500.6  443.16  4601.7  435.86  4701.7  431.02  4821.7  429.13
  4851.7  428.01  4871.7  426.03  4941.7   423.8  4951.7  422.56  4971.7  423.95
  4981.7  423.63  4998.7  420.64  5001.5  420.14  5004.7  420.64  5021.7   421.3
  5031.7  424.43  5091.8  425.39  5191.8  429.62  5211.8  429.25  5302.7  433.75
  5331.8  435.43  5421.8  437.56  5461.8  440.87    5480  441.34    5485  440.12
  5501.8  440.75  5511.8   442.3  5521.8  440.45  5531.8  440.52  5611.4  444.36
#Mann= 5 ,-1 , 0
  4111.3     .05       0  4500.6     .16       0  4998.7     .07       0
  5004.7     .16       0  5302.7     .05       0
Bank Sta=4971.7,5031.7
XS Rating Curve= 0 ,0
Exp/Cntr=0.3,0.1

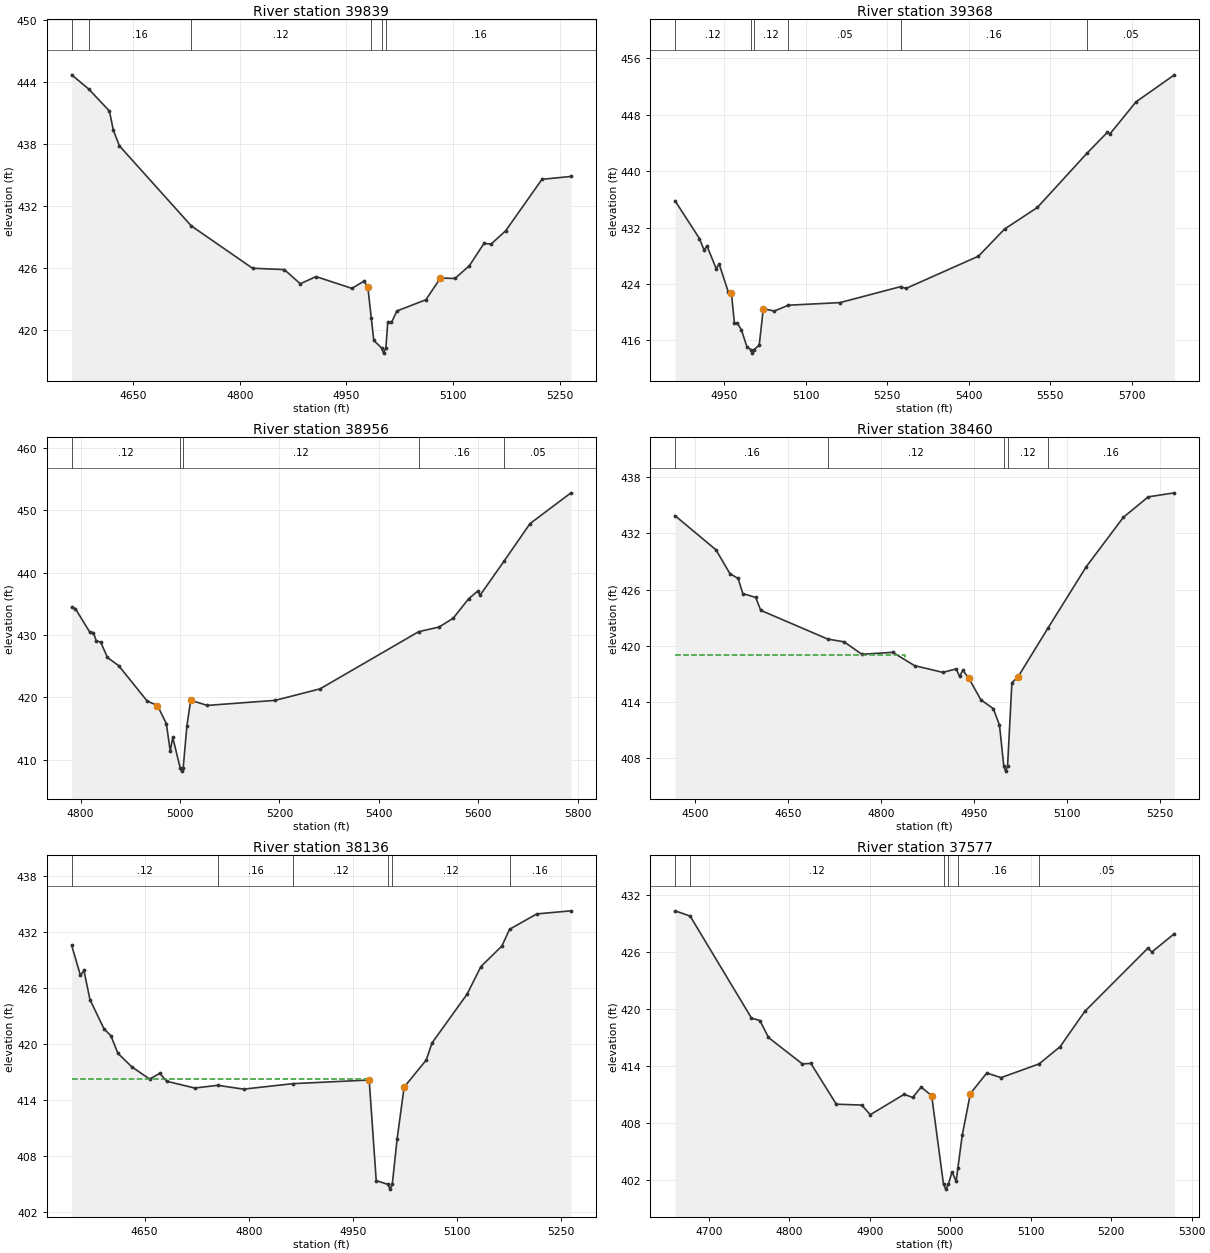
Type RM Length L Ch R = 1 ,39839   ,471,471,471
BEGIN DESCRIPTION:
MINE CREEK 80.0
END DESCRIPTION:
XS GIS Cut Line= 3
      3709399.64     10772010.17      3708999.61     10772210.19
      3708749.61     10772160.19
#Sta/Elev= 30
  4563.5   444.7  4587.4  443.33  4616.6   441.2  4622.2  439.33  4630.6  437.83
  4731.8  430.07  4817.9  425.97  4862.6  425.84    4885  424.47  4907.3  425.16
  4957.6  424.02  4974.4  424.71    4980  424.17  4984.8   421.2  4988.4  418.98
  4999.4  418.25  5002.1  417.75  5005.4  418.25    5008  420.72  5013.3  420.72
  5020.9  421.83  5061.7  422.92  5082.1  425.02  5102.5  424.98  5122.9  426.22
  5143.3  428.37  5153.5  428.32  5173.9   429.6  5224.9  434.58  5265.7  434.86
#Mann= 6 ,-1 , 0
  4563.5     .05       0  4587.4     .16       0  4731.8     .12       0
  4984.8     .16       0  4999.4     .07       0  5005.4     .16       0
Bank Sta=4980,5082.1
XS Rating Curve= 0 ,0
Exp/Cntr=0.3,0.1

Type RM Length L Ch R = 1 ,39368   ,412,412,412
BEGIN DESCRIPTION:
MINE CREEK 79.0
END DESCRIPTION:
XS GIS Cut Line= 3
      3709199.65     10771710.17      3709099.61     10771760.19
      3708299.59     10771660.19
#Sta/Elev= 30
  4860.1  435.79  4904.9  430.45  4913.3  428.83  4918.8  429.39  4935.6   426.2
  4941.2  426.82    4958  422.85  4963.6  422.77  4969.2  418.46  4974.5  418.46
    4982  417.52  4992.1  415.13  4999.2  414.71  5001.9  414.21  5005.2  414.71
  5014.8  415.34  5022.3  420.51  5042.5  420.17  5068.3     421  5163.4  421.37
  5275.1  423.64  5284.4  423.37  5417.9  427.95  5465.8  431.79  5526.2  434.85
  5617.2  442.52  5654.7  445.49  5659.8  445.29  5707.6  449.82  5778.2  453.65
#Mann= 6 ,-1 , 0
  4860.1     .12       0  4999.2     .07       0  5005.2     .12       0
  5068.3     .05       0  5275.1     .16       0  5617.2     .05       0
Bank Sta=4963.6,5022.3
XS Rating Curve= 0 ,0
Exp/Cntr=0.3,0.1

Type RM Length L Ch R = 1 ,38956   ,496,496,496
BEGIN DESCRIPTION:
MINE CREEK 78.0
END DESCRIPTION:
XS GIS Cut Line= 3
      3709249.64     10771460.21      3709099.61     10771360.19
      3708299.64     10771560.18
#Sta/Elev= 30
  4781.8  434.46  4789.3  434.22  4817.9  430.51  4825.4  430.36  4831.4  429.08
  4840.4  428.83  4853.9  426.39  4876.5  425.08  4933.6  419.43  4954.6  418.68
  4972.4  415.79  4980.2  411.41  4985.3  413.57  5000.3  408.68  5003.1  408.18
  5006.3  408.68  5013.7  415.38  5021.4  419.53  5054.9  418.71  5191.5  419.52
  5281.7  421.36  5480.1  430.52  5521.3  431.27  5549.7  432.68  5580.6  435.79
  5598.6     437  5603.8  436.37  5652.5  441.88  5704.3  447.84  5786.7  452.77
#Mann= 5 ,-1 , 0
  4781.8     .12       0  5000.3     .07       0  5006.3     .12       0
  5480.1     .16       0  5652.5     .05       0
Bank Sta=4954.6,5021.4
XS Rating Curve= 0 ,0
Exp/Cntr=0.3,0.1

Type RM Length L Ch R = 1 ,38460   ,324,324,324
BEGIN DESCRIPTION:
MINE CREEK 77.0
END DESCRIPTION:
XS GIS Cut Line= 3
      3709459.22     10771243.97      3709120.68     10770974.87
      3708747.36     10770979.21
#Sta/Elev= 30
    4468  433.88    4534  430.24  4556.5   427.7  4569.7  427.19  4577.3  425.58
  4598.1  425.16  4606.2  423.79  4714.4  420.72  4740.7  420.43  4769.5   419.1
  4819.2  419.31  4854.4  417.89  4900.2  417.17  4921.5  417.54  4927.2  416.75
  4932.2  417.39  4941.5   416.6  4961.5  414.24  4981.5  413.31  4991.5  411.54
  4998.5  407.14  5001.3  406.64  5004.5  407.14  5011.5  416.06  5021.5   416.7
  5069.6  421.88  5131.5  428.44  5191.5  433.72  5231.6  435.89  5273.8  436.32
#Mann= 5 ,-1 , 0
    4468     .16       0  4714.4     .12       0  4998.5     .07       0
  5004.5     .12       0  5069.6     .16       0
#XS Ineff= 2 , 0
         4839.29  419.03
Permanent Ineff=
       F       F
Bank Sta=4941.5,5021.5
XS Rating Curve= 0 ,0
Exp/Cntr=0.3,0.1

Type RM Length L Ch R = 1 ,38136   ,559,559,559
BEGIN DESCRIPTION:
MINE CREEK 76.0
END DESCRIPTION:
XS GIS Cut Line= 2
      3709475.83     10770653.75      3708760.64     10770726.66
#Sta/Elev= 30
    4545  430.57  4557.7  427.33  4562.7  427.87  4571.4  424.74  4591.5  421.62
  4601.5  420.87  4611.6  418.98  4631.7  417.53  4657.3  416.22  4671.9  416.84
  4681.9  415.99  4722.1  415.26  4755.3  415.55  4792.5  415.14  4863.8  415.73
  4973.4  416.12  4983.5  405.34  5000.6  404.92  5003.3  404.42  5006.6  404.92
  5013.6   409.8  5023.7  415.36  5055.5  418.26  5063.9   420.1  5114.2  425.31
  5134.3  428.29  5164.4  430.48  5175.5  432.28  5214.7  433.93  5263.9  434.26
#Mann= 6 ,-1 , 0
    4545     .12       0  4755.3     .16       0  4863.8     .12       0
  5000.6     .07       0  5006.6     .12       0  5175.5     .16       0
#XS Ineff= 2 , 0
         4972.48  416.28
Permanent Ineff=
       F       F
Bank Sta=4973.4,5023.7
XS Rating Curve= 0 ,0
Exp/Cntr=0.3,0.1

Type RM Length L Ch R = 1 ,37577   ,387,387,387
BEGIN DESCRIPTION:
MINE CREEK 75.0
END DESCRIPTION:
XS GIS Cut Line= 3
      3709399.63     10770060.18      3709099.61     10770160.19
       3708799.6     10770210.19
#Sta/Elev= 30
  4658.2  430.29  4676.9  429.74  4753.1  419.04  4763.6  418.78  4774.2     417
  4816.3  414.23  4826.9  414.28  4858.5     410  4890.1  409.91  4900.7   408.9
  4942.8  411.04  4953.4  410.71  4963.9   411.8    4977  410.89  4991.7  401.59
  4994.5  401.09  4997.7  401.59  5002.3   402.9  5007.4  401.93  5009.5  403.27
    5015  406.77  5025.1  411.12  5045.4  413.27  5063.2  412.79  5110.5  414.23
  5136.7  416.05  5167.1  419.73  5245.6  426.37  5250.7  425.98  5278.6   427.9
#Mann= 6 ,-1 , 0
  4658.2     .05       0  4676.9     .12       0  4991.7     .07       0
  4997.7     .12       0  5009.5     .16       0  5110.5     .05       0
Bank Sta=4977,5025.1
XS Rating Curve= 0 ,0
Exp/Cntr=0.3,0.1

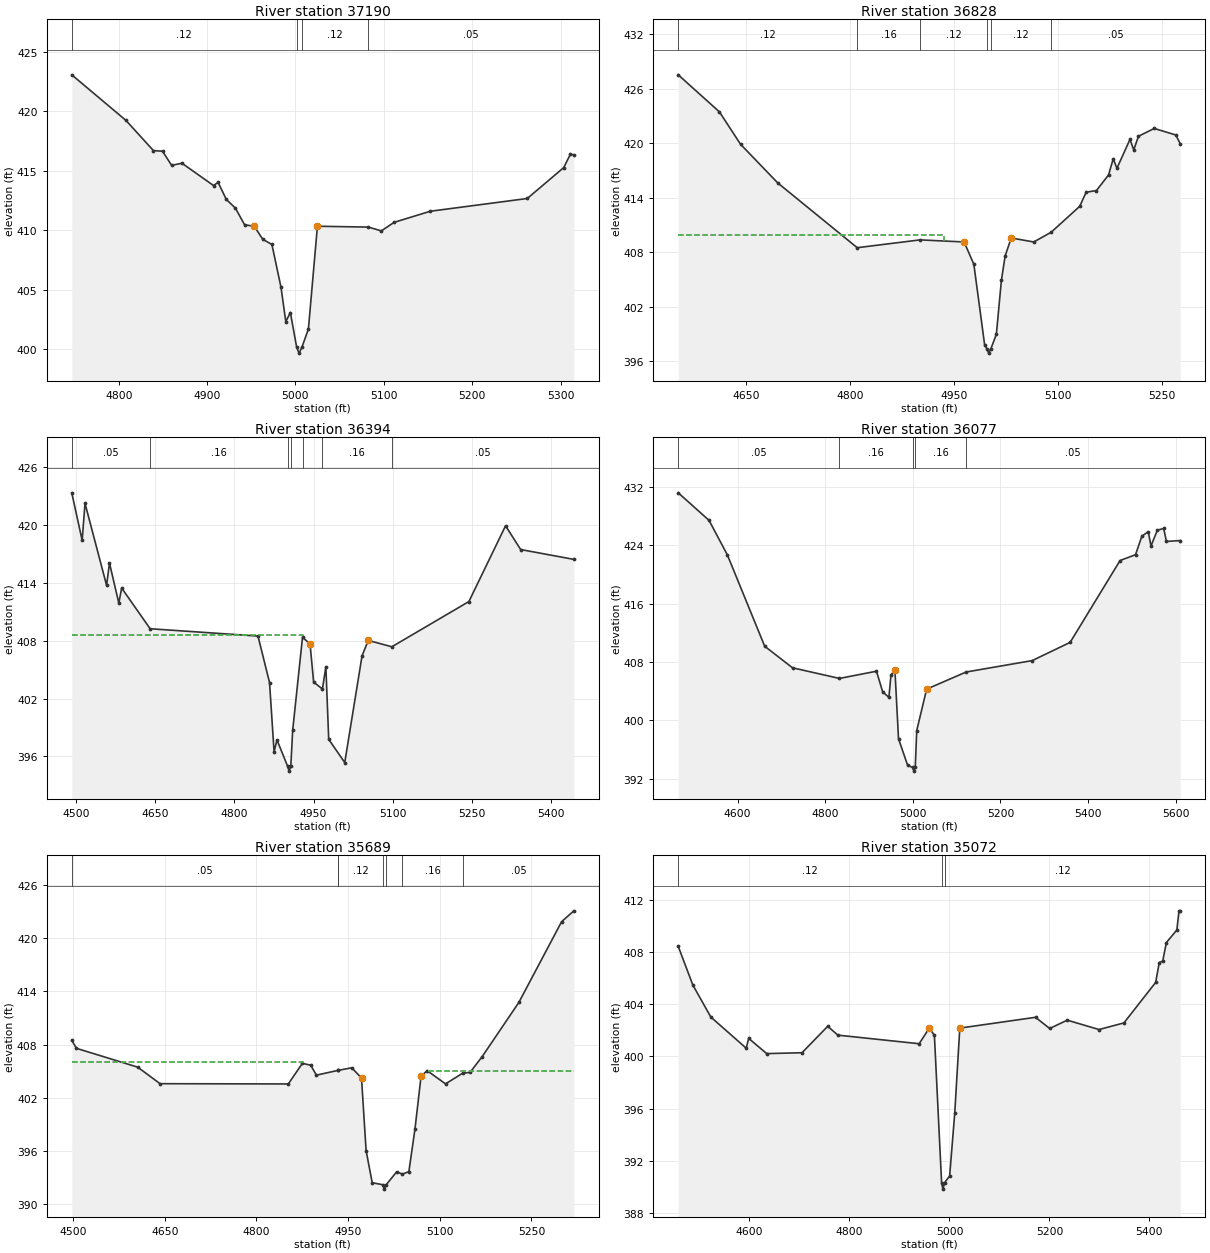
Type RM Length L Ch R = 1 ,37190   ,362,362,362
BEGIN DESCRIPTION:
Mapping XS ae6a1c1d
END DESCRIPTION:
XS GIS Cut Line= 2
      3709389.11     10769735.34      3708838.49     10769875.59
#Sta/Elev= 30
  4746.9  423.05  4808.3  419.22  4839.3  416.69  4849.6  416.64  4859.9  415.45
  4871.6  415.63  4907.3  413.76  4912.5  414.02  4921.8  412.59  4932.1  411.86
  4942.5  410.46  4953.4  410.34  4963.1  409.24  4973.4  408.81  4983.7  405.21
  4989.1  402.34  4994.3   403.1  5001.4  400.19  5004.1  399.69  5007.4  400.19
  5014.7  401.71  5024.9  410.34  5082.6  410.27  5097.2  409.95  5111.8  410.67
  5152.7   411.6  5262.4  412.67  5303.6  415.26  5311.1  416.37  5315.1  416.34
#Mann= 4 ,-1 , 0
  4746.9     .12       0  5001.4     .07       0  5007.4     .12       0
  5082.6     .05       0
Bank Sta=4953.4,5024.9
XS Rating Curve= 0 ,0
Exp/Cntr=0.3,0.1

Type RM Length L Ch R = 1 ,36828   ,434,434,434
BEGIN DESCRIPTION:
MINE CREEK 74.0
END DESCRIPTION:
XS GIS Cut Line= 2
      3709404.74     10769360.33       3708733.7     10769630.83
#Sta/Elev= 30
  4552.6  427.51    4612  423.43  4642.4  419.87  4696.1  415.61  4810.5  408.49
  4901.1  409.35  4964.6  409.12  4978.6  406.66  4994.2  397.76  4997.2  397.39
  4999.9  396.89  5003.2  397.39    5011  398.95  5018.3  404.91  5023.7  407.59
  5032.5  409.56  5064.9  409.12    5090  410.19  5131.1  413.04  5140.4  414.59
  5155.3  414.78  5172.7   416.5  5179.4  418.26  5184.8  417.23  5203.6  420.41
    5209  419.25  5215.8  420.75  5238.5  421.61  5269.7  420.89  5276.1  419.91
#Mann= 6 ,-1 , 0
  4552.6     .12       0  4810.5     .16       0  4901.1     .12       0
  4997.2     .07       0  5003.2     .12       0    5090     .05       0
#XS Ineff= 2 , 0
         4935.39  409.86
Permanent Ineff=
       F       F
Bank Sta=4964.6,5032.5
XS Rating Curve= 0 ,0
Exp/Cntr=0.3,0.1

Type RM Length L Ch R = 1 ,36394   ,317,317,317
BEGIN DESCRIPTION:
MINE CREEK 73.0
END DESCRIPTION:
XS GIS Cut Line= 2
      3709113.03     10768678.06      3708723.01      10769546.5
#Sta/Elev= 30
  4491.5  423.33  4511.2   418.4  4516.6  422.24  4557.5  413.74    4563  416.05
  4580.7   411.9  4586.1  413.46  4640.1  409.24  4844.6  408.48  4866.5  403.66
  4875.1  396.49  4880.6  397.72  4900.8  394.98  4903.5  394.48  4906.8  394.98
  4910.4  398.72    4929  408.35  4943.3  407.67  4950.1  403.71  4966.8  402.99
  4973.3  405.31  4978.7  397.78  5009.1  395.37  5041.9  406.43  5053.7  408.03
  5098.4  407.37  5244.5  412.06    5314  419.91  5342.7  417.45  5443.5  416.43
#Mann= 7 ,-1 , 0
  4491.5     .05       0  4640.1     .16       0  4900.8     .07       0
  4906.8     .16       0    4929     .12       0  4966.8     .16       0
  5098.4     .05       0
#XS Ineff= 2 , 0
       0 4929.35  408.58               0
Permanent Ineff=
       T       F
Bank Sta=4943.3,5053.7
XS Rating Curve= 0 ,0
Exp/Cntr=0.3,0.1

Type RM Length L Ch R = 1 ,36077   ,388,388,388
BEGIN DESCRIPTION:
MINE CREEK 72.0
END DESCRIPTION:
XS GIS Cut Line= 3
      3709092.21      10768584.3      3708727.62     10768907.22
      3708322.46     10769426.66
#Sta/Elev= 30
  4464.7  431.22  4534.9  427.45  4576.7  422.72    4662  410.17  4725.5  407.21
  4832.6  405.75  4917.1  406.74  4931.3   403.9  4945.5  403.16  4950.2  406.21
  4959.2   406.9  4967.4  397.48  4988.2  393.83  4999.6  393.53  5002.4  393.03
  5005.6  393.53    5009   398.6  5031.6  404.28  5121.7  406.63  5272.6   408.2
  5359.1   410.7    5473  421.93  5508.3  422.73  5522.8  425.28  5537.3  425.88
  5543.6  423.93  5558.1  426.09  5572.5  426.33  5578.9  424.55  5610.5  424.67
#Mann= 5 ,-1 , 0
  4464.7     .05       0  4832.6     .16       0  4999.6     .07       0
  5005.6     .16       0  5121.7     .05       0
Bank Sta=4959.2,5031.6
XS Rating Curve= 0 ,0
Exp/Cntr=0.3,0.1

Type RM Length L Ch R = 1 ,35689   ,617,617,617
BEGIN DESCRIPTION:
MINE CREEK 71.0
END DESCRIPTION:
XS GIS Cut Line= 3
      3708899.64     10768410.17      3708499.61     10768660.19
      3708149.65     10768660.19
#Sta/Elev= 30
  4497.8  408.48  4505.5  407.58  4605.7  405.46  4642.3   403.6  4852.2  403.57
  4875.2  405.89  4888.8  405.68  4898.2  404.56    4933  405.09  4933.8   405.1
    4956  405.39    4972  404.24  4979.5  396.07  4989.5  392.45  5006.5  392.23
  5009.3  391.73  5012.5  392.23  5029.5  393.68    5039  393.42  5049.5   393.7
  5059.5   398.5  5069.5  404.46  5079.5  405.06  5109.5  403.58    5138   404.8
  5149.5  404.86  5169.5  406.65  5229.5  412.75  5299.5  421.84  5319.5  423.06
#Mann= 7 ,-1 , 0
  4497.8     .05       0    4933     .16       0  4933.8     .12       0
  5006.5     .07       0  5012.5     .12       0    5039     .16       0
    5138     .05       0
#XS Ineff= 2 , 0
       0 4875.91  406.06 5080.01       0  405.05
Permanent Ineff=
       T       F
Bank Sta=4972,5069.5
XS Rating Curve= 0 ,0
Exp/Cntr=0.3,0.1

Type RM Length L Ch R = 1 ,35072   ,273,273,273
BEGIN DESCRIPTION:
MINE CREEK 70.0
END DESCRIPTION:
XS GIS Cut Line= 3
      3708793.75     10768030.05      3708182.61     10768141.16
      3707918.72     10768418.94
#Sta/Elev= 30
  4457.5  408.46  4486.7  405.49  4522.7  403.03  4593.4  400.64  4598.5  401.39
  4634.5  400.22  4705.2  400.29  4756.5  402.32  4776.8  401.64  4939.4  400.98
  4959.7  402.18  4969.9  401.63  4984.3  390.31    4987  389.81  4990.3  390.31
  5000.4  390.82  5010.6  395.65  5020.7  402.18  5172.2  403.01  5200.5  402.15
  5235.7  402.79  5299.2  402.07    5349  402.58  5412.5  405.69  5419.7  407.22
  5426.6  407.33  5433.9  408.75  5454.9  409.72  5459.2  411.19  5461.8  411.19
#Mann= 3 ,-1 , 0
  4457.5     .12       0  4984.3     .03       0  4990.3     .12       0
Bank Sta=4959.7,5020.7
XS Rating Curve= 0 ,0
Exp/Cntr=0.3,0.1