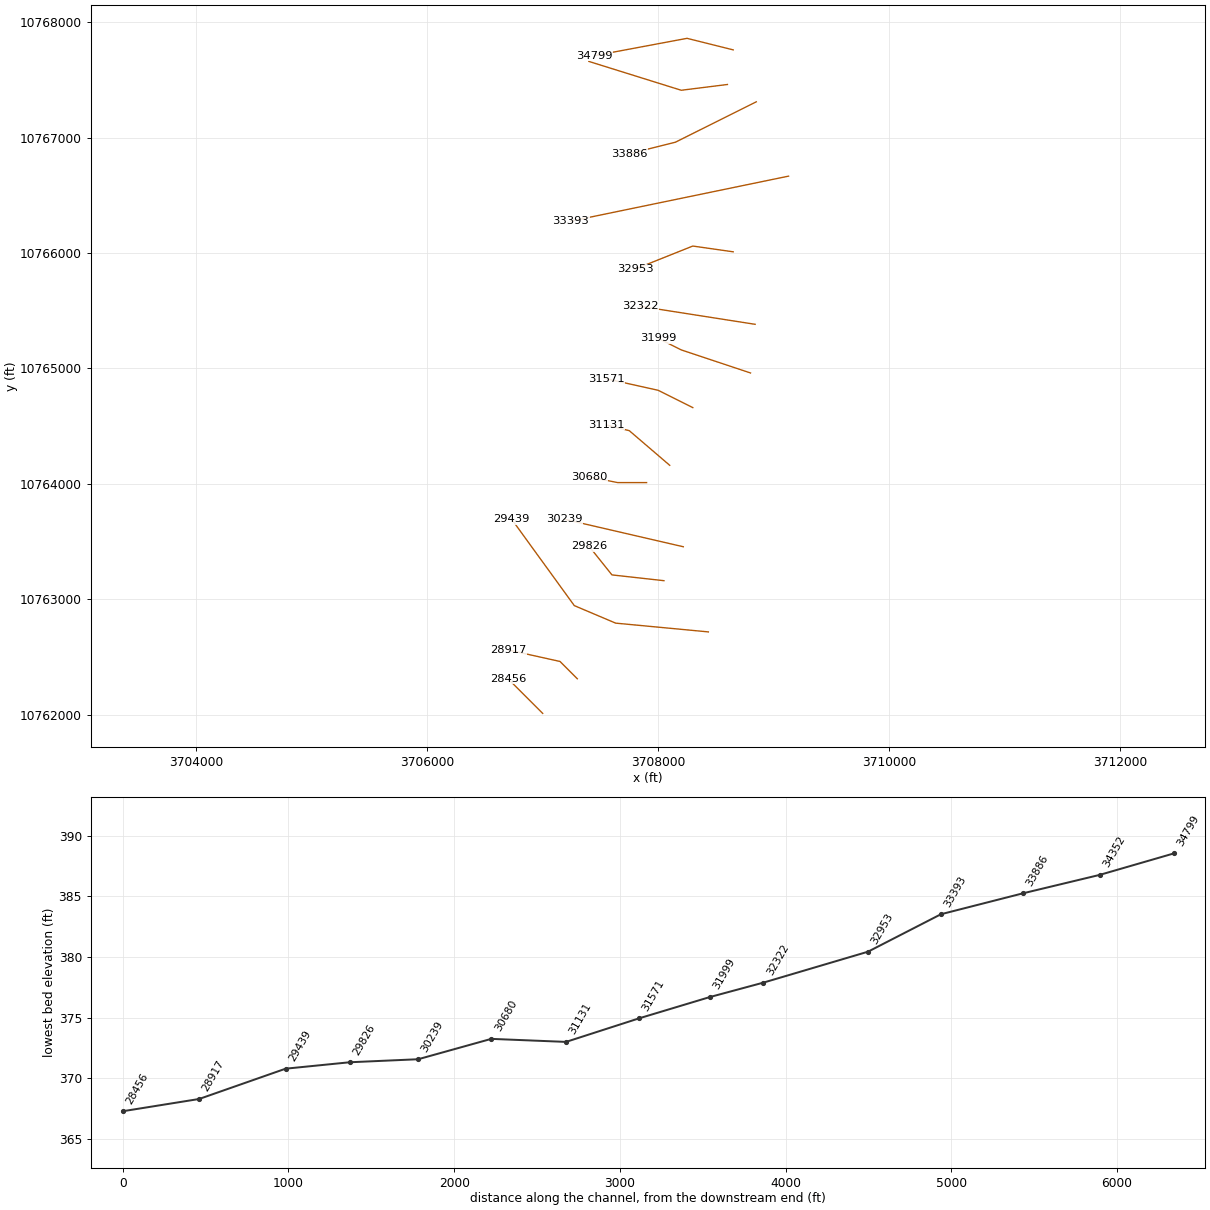
HEC-RAS study MINE CREEK.prj: MINE CREEK Base Level Engineering

--- MINE CREEK.g01 (geometry) --- (continued)

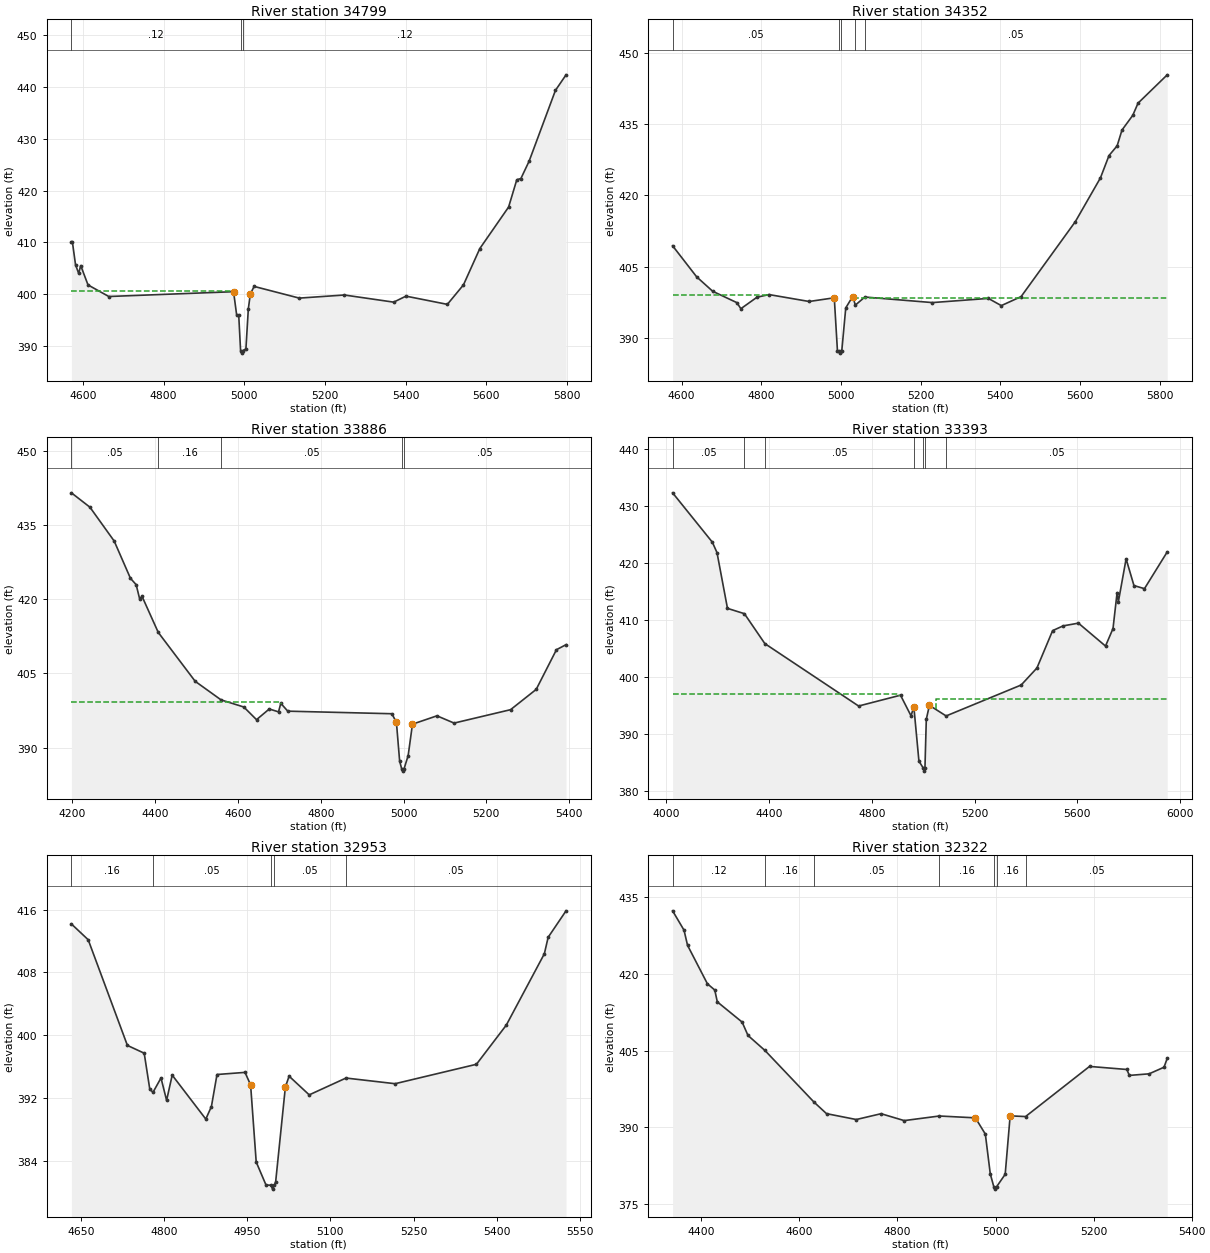
Type RM Length L Ch R = 1 ,34799   ,447,447,447
BEGIN DESCRIPTION:
MINE CREEK 69.0
END DESCRIPTION:
XS GIS Cut Line= 3
      3708649.57      10767760.2      3708249.61     10767860.19
      3707449.62     10767710.19
#Sta/Elev= 30
  4571.4  410.03  4573.9  410.03  4581.7  405.62  4589.4  403.98  4594.5  405.48
  4612.6  401.74  4664.1   399.5  4973.4  400.43  4981.1   395.9  4986.2   395.9
  4990.8  389.05  4993.6  388.55  4996.8  389.05    5004  389.35    5010  397.11
    5015     400  5024.4  401.45  5136.3  399.19  5248.2  399.79  5370.3  398.41
  5400.8  399.57  5503.4  397.98  5543.3  401.75  5583.9  408.78  5655.2   416.8
  5675.5  422.08  5685.7  422.32    5706  425.66  5771.3  439.36  5797.6  442.37
#Mann= 3 ,-1 , 0
  4571.4     .12       0  4990.8     .03       0  4996.8     .12       0
#XS Ineff= 2 , 0
         4970.94  400.48
Permanent Ineff=
       F       F
Bank Sta=4973.4,5015
XS Rating Curve= 0 ,0
Exp/Cntr=0.3,0.1

Type RM Length L Ch R = 1 ,34352   ,466,466,466
BEGIN DESCRIPTION:
MINE CREEK 68.0
END DESCRIPTION:
XS GIS Cut Line= 3
      3708599.57     10767460.18      3708199.61     10767410.19
      3707399.63     10767660.18
#Sta/Elev= 30
  4577.6   409.4    4638  402.85  4678.3  399.81  4738.8  397.42  4748.9  396.14
  4789.2  398.55  4819.4  399.12  4920.2  397.66  4983.3  398.44  4991.2  387.33
  4993.9  387.28  4996.7  386.78  4999.9  387.28  5002.2  387.32  5012.1  396.31
  5029.4  398.71  5036.2   396.9    5060   398.6  5229.5  397.43  5369.9  398.31
  5402.4  396.79  5452.1  398.69  5588.3   414.5  5651.2  423.71  5672.7  428.42
  5693.1  430.46  5705.2  433.78  5732.4   436.9  5745.5  439.45  5818.8  445.42
#Mann= 5 ,-1 , 0
  4577.6     .05       0  4993.9     .03       0  4999.9     .05       0
  5036.2     .16       0    5060     .05       0
#XS Ineff= 2 , 0
          4816.2  399.08 5031.59          398.47
Permanent Ineff=
       F       F
Bank Sta=4983.3,5029.4
XS Rating Curve= 0 ,0
Exp/Cntr=0.3,0.1

Type RM Length L Ch R = 1 ,33886   ,493,493,493
BEGIN DESCRIPTION:
MINE CREEK 67.0
END DESCRIPTION:
XS GIS Cut Line= 3
      3708849.61     10767310.19      3708149.61     10766960.19
      3707749.64      10766860.2
#Sta/Elev= 30
  4197.6   441.5  4242.3   438.6    4301  431.75  4340.2  424.23  4354.1  422.93
  4362.5  420.04  4368.1   420.6  4407.4  413.29  4496.7   403.4  4559.1  399.65
  4614.1  398.21  4644.8  395.65  4675.6  397.81  4697.9  397.23  4703.5  398.95
  4720.3  397.37  4971.8  396.85  4982.8  395.08  4990.5  387.29  4995.3  385.75
    4998  385.25  5001.3  385.75  5011.1  388.39  5021.5  394.74  5080.7  396.43
    5122  394.96  5258.5  397.67  5320.4  401.77  5369.3  409.79  5392.5  410.81
#Mann= 5 ,-1 , 0
  4197.6     .05       0  4407.4     .16       0  4559.1     .05       0
  4995.3     .03       0  5001.3     .05       0
#XS Ineff= 2 , 0
         4702.99  399.16
Permanent Ineff=
       F       F
Bank Sta=4982.8,5021.5
XS Rating Curve= 0 ,0
Exp/Cntr=0.3,0.1

Type RM Length L Ch R = 1 ,33393   ,440,440,440
BEGIN DESCRIPTION:
MINE CREEK 66.0
END DESCRIPTION:
XS GIS Cut Line= 2
      3709128.89     10766665.99      3707242.74     10766275.75
#Sta/Elev= 30
  4024.3  432.35  4179.1  423.69  4197.2  421.86    4238  412.08  4303.9  411.15
  4383.5   405.9  4748.6  394.95  4911.8  396.85  4952.8  393.22  4963.6  394.86
  4983.5  385.28  5000.9  384.03  5003.7  383.53  5006.9  384.03  5012.2  392.62
  5024.3  395.07  5089.4  393.21  5381.7  398.64    5443  401.62  5504.1  408.18
  5545.1  409.01  5604.5  409.49    5710  405.47  5739.2  408.54  5755.1  414.84
  5760.2  413.27  5790.2  420.76  5820.8  416.08  5861.7  415.54  5950.4  421.99
#Mann= 7 ,-1 , 0
  4024.3     .05       0  4303.9     .16       0  4383.5     .05       0
  4963.6     .16       0  5000.9     .07       0  5006.9     .16       0
  5089.4     .05       0
#XS Ineff= 2 , 0
         4906.65  397.09 5049.42          396.26
Permanent Ineff=
       F       F
Bank Sta=4963.6,5024.3
XS Rating Curve= 0 ,0
Exp/Cntr=0.3,0.1

Type RM Length L Ch R = 1 ,32953   ,631,631,631
BEGIN DESCRIPTION:
MINE CREEK 65.0
END DESCRIPTION:
XS GIS Cut Line= 3
      3708649.61     10766010.19      3708299.61     10766060.19
      3707799.58     10765860.18
#Sta/Elev= 30
  4632.9  414.17  4663.2  412.16  4733.9  398.72  4764.2  397.73  4774.3  393.14
  4780.1  392.76  4794.5  394.58  4804.6  391.73  4814.7  394.94  4875.3  389.35
  4885.4  390.94  4895.5  395.02    4946  395.29  4956.1   393.7  4966.2  383.89
  4983.9  380.96  4992.9  380.94  4995.6  380.44  4998.9  380.94  5001.3  381.38
  5018.8  393.42  5025.5  394.81  5061.8  392.43  5128.1  394.57  5216.7  393.85
  5363.4  396.32  5417.3  401.31  5485.9  410.38  5492.7  412.47    5525  415.84
#Mann= 5 ,-1 , 0
  4632.9     .16       0  4780.1     .05       0  4992.9     .07       0
  4998.9     .05       0  5128.1     .05       0
Bank Sta=4956.1,5018.8
XS Rating Curve= 0 ,0
Exp/Cntr=0.3,0.1

Type RM Length L Ch R = 1 ,32322   ,323,323,323
BEGIN DESCRIPTION:
MINE CREEK 64.0
END DESCRIPTION:
XS GIS Cut Line= 2
      3708839.71      10765381.9      3707843.05      10765537.9
#Sta/Elev= 30
  4341.4  432.39  4364.7   428.6  4371.9  425.63  4412.4   418.1  4427.4  416.88
  4432.6  414.56  4483.2   410.6  4495.2  407.98  4529.8  405.04  4629.6  394.95
  4655.3  392.67    4716  391.52  4766.6  392.66  4813.7  391.31  4885.4  392.21
  4958.9  391.85  4979.2  388.67  4989.3  380.87  4996.4  378.39  4999.2  377.89
  5002.4  378.39  5019.7   380.8  5029.8  392.24  5061.2   392.1  5191.7  401.92
  5267.8  401.32  5272.9  400.16  5313.2  400.47  5343.6  401.76  5350.2  403.51
#Mann= 7 ,-1 , 0
  4341.4     .12       0  4529.8     .16       0  4629.6     .05       0
  4885.4     .16       0  4996.4     .07       0  5002.4     .16       0
  5061.2     .05       0
Bank Sta=4958.9,5029.8
XS Rating Curve= 0 ,0
Exp/Cntr=0.3,0.1

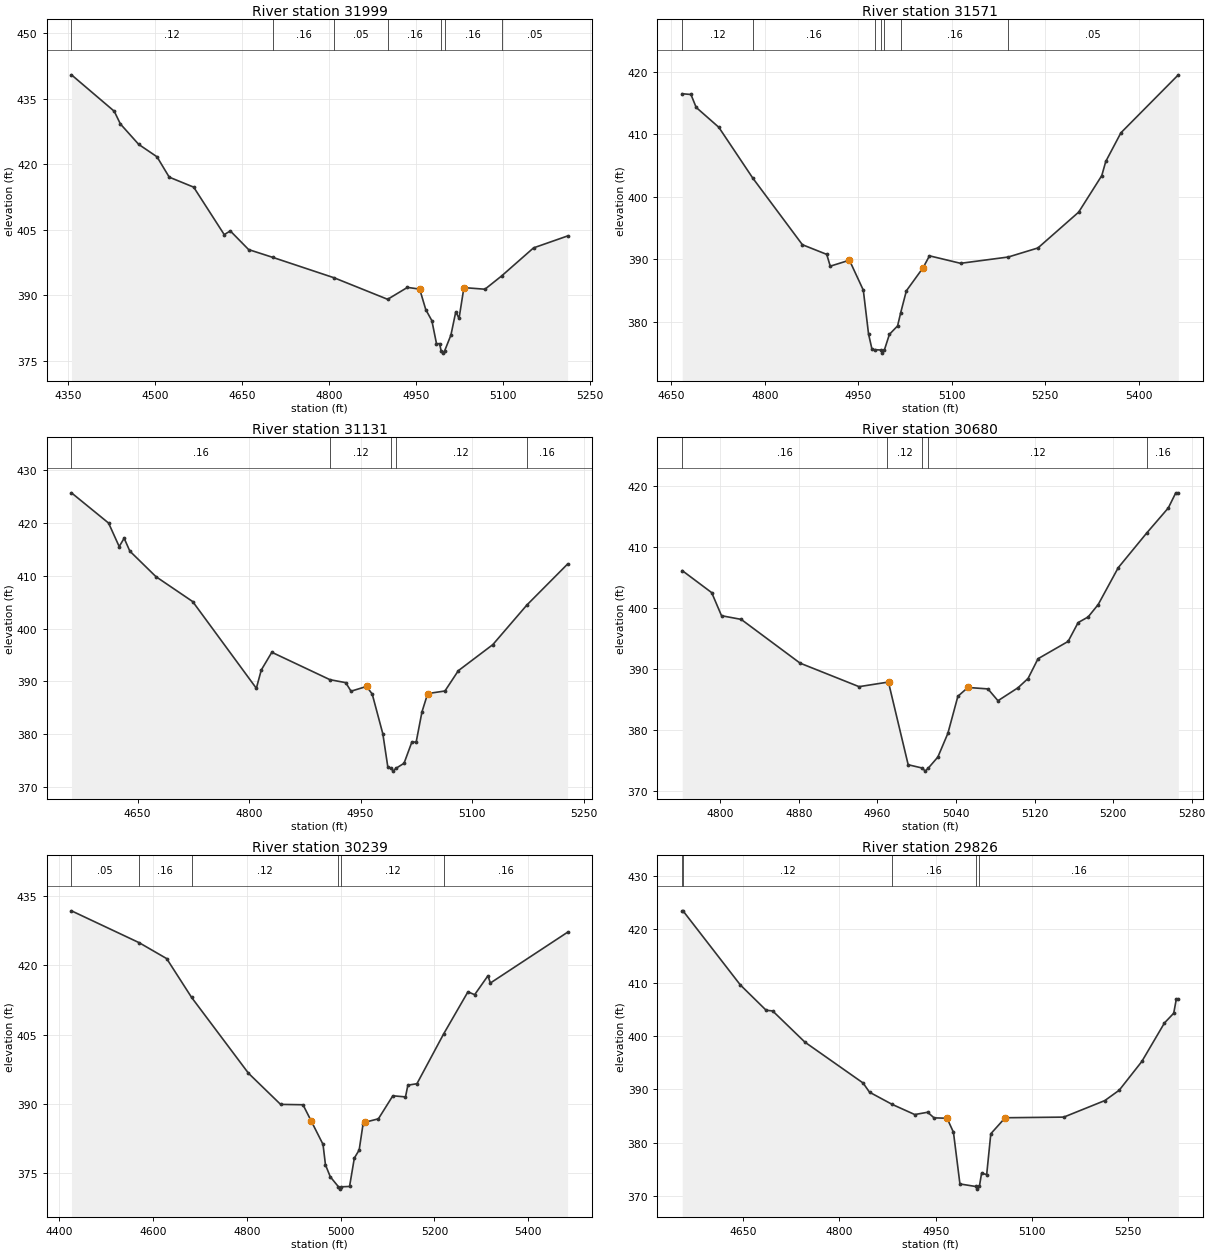
Type RM Length L Ch R = 1 ,31999   ,428,428,428
BEGIN DESCRIPTION:
MINE CREEK 63.0
END DESCRIPTION:
XS GIS Cut Line= 3
      3708799.64     10764960.18      3708199.61     10765160.19
       3707999.6     10765260.19
#Sta/Elev= 30
    4356  440.45  4429.8  432.11  4440.4   429.2    4472  424.52  4503.6  421.67
  4524.7  417.01  4566.9  414.72  4619.6  403.85  4630.1  404.69  4661.7  400.42
  4703.7  398.62  4809.4  393.95  4901.6  389.03  4935.8  391.76  4956.9  391.36
  4967.4  386.66  4977.9  384.14  4985.9  378.87  4991.3  378.87  4993.9   377.2
  4996.6   376.7  4999.9   377.2  5010.8  380.84  5019.2  386.18  5024.8  384.65
  5033.2  391.71  5069.5  391.34  5098.1  394.36  5153.4  400.81  5212.1  403.54
#Mann= 7 ,-1 , 0
    4356     .12       0  4703.7     .16       0  4809.4     .05       0
  4901.6     .16       0  4993.9     .07       0  4999.9     .16       0
  5098.1     .05       0
Bank Sta=4956.9,5033.2
XS Rating Curve= 0 ,0
Exp/Cntr=0.3,0.1

Type RM Length L Ch R = 1 ,31571   ,440,440,440
BEGIN DESCRIPTION:
MINE CREEK 62.0
END DESCRIPTION:
XS GIS Cut Line= 3
      3708299.63     10764660.18      3707999.61     10764810.19
      3707549.62     10764910.19
#Sta/Elev= 30
  4667.5   416.5  4681.5  416.38  4689.9  414.31  4726.2  411.13  4780.8  402.98
  4860.4  392.31  4899.5  390.76  4905.1  388.87  4935.9  389.83  4958.2  385.03
  4966.6     378  4972.2  375.53    4977  375.49    4986  375.44  4988.7  374.94
    4992  375.44  5000.1  377.95  5013.2   379.3  5018.2  381.41  5027.3  384.92
  5054.2  388.63  5064.4  390.53  5114.3  389.33  5190.9  390.34  5238.5  391.79
  5303.9  397.53    5341  403.38  5347.4  405.65  5371.7  410.24  5463.9  419.53
#Mann= 7 ,-1 , 0
  4667.5     .12       0  4780.8     .16       0    4977     .12       0
    4986     .07       0    4992     .12       0  5018.2     .16       0
  5190.9     .05       0
Bank Sta=4935.9,5054.2
XS Rating Curve= 0 ,0
Exp/Cntr=0.3,0.1

Type RM Length L Ch R = 1 ,31131   ,451,451,451
BEGIN DESCRIPTION:
MINE CREEK 61.0
END DESCRIPTION:
XS GIS Cut Line= 3
       3708099.6     10764160.19      3707749.61     10764460.19
      3707549.63     10764510.18
#Sta/Elev= 30
  4561.2  425.75  4611.1  420.02  4625.4  415.56    4632  417.15  4639.7   414.7
  4674.8  409.86  4724.2  405.14  4809.8   388.7  4816.4  392.16  4830.6  395.53
  4908.8  390.33    4930  389.77  4937.1  388.15    4958  389.05  4965.6  387.61
  4979.9  380.06  4986.5  373.87  4991.2   373.5  4993.9     373  4997.2   373.5
  5008.4  374.49  5018.9  378.51  5024.7  378.51  5032.5  384.23  5040.2   387.7
  5063.4  388.19  5081.4  392.04  5127.8  396.98  5173.6  404.49  5228.3  412.25
#Mann= 5 ,-1 , 0
  4561.2     .16       0  4908.8     .12       0  4991.2     .07       0
  4997.2     .12       0  5173.6     .16       0
Bank Sta=4958,5040.2
XS Rating Curve= 0 ,0
Exp/Cntr=0.3,0.1

Type RM Length L Ch R = 1 ,30680   ,441,441,441
BEGIN DESCRIPTION:
MINE CREEK 60.0
END DESCRIPTION:
XS GIS Cut Line= 3
      3707899.61     10764010.19      3707649.61     10764010.19
      3707399.56      10764060.2
#Sta/Elev= 30
  4761.4  406.18  4791.4  402.56  4801.4  398.77  4821.4  398.17  4881.4  390.98
  4941.4  387.12  4969.4  387.83  4971.4  387.81  4991.4   374.3  5005.9  373.75
  5008.7  373.25  5011.9  373.75  5021.6  375.56  5031.8  379.45    5042  385.54
  5052.2  386.99  5072.6  386.75  5082.8  384.81  5103.2  386.94  5113.4  388.46
  5123.6  391.71  5154.2  394.55  5164.4  397.64  5174.6  398.57  5184.8   400.6
  5205.2  406.65  5234.1  412.33  5256.2  416.47  5263.8  418.95  5266.4  418.95
#Mann= 5 ,-1 , 0
  4761.4     .16       0  4969.4     .12       0  5005.9     .07       0
  5011.9     .12       0  5234.1     .16       0
Bank Sta=4971.4,5052.2
XS Rating Curve= 0 ,0
Exp/Cntr=0.3,0.1

Type RM Length L Ch R = 1 ,30239   ,413,413,413
BEGIN DESCRIPTION:
MINE CREEK 59.0
END DESCRIPTION:
XS GIS Cut Line= 2
      3708217.37     10763454.18      3707186.55      10763692.9
#Sta/Elev= 30
  4425.8  431.77  4570.1  424.88  4628.8  421.44    4682  413.04  4803.3  396.64
  4871.8   389.9  4919.6  389.82  4936.7  386.39  4962.3  381.25  4967.5  376.83
  4977.8  374.24  4995.3  372.07  4998.1  371.57  5001.3  372.07  5018.9  372.15
  5029.1  378.29  5039.4  380.03  5047.7  385.66  5052.8  386.06  5080.4  386.78
  5111.2  391.76  5138.2  391.52  5143.3  394.06  5162.6  394.37  5219.6  405.15
  5271.4  414.25  5285.7  413.63  5314.1  417.73  5319.2  416.15  5483.9  427.14
#Mann= 6 ,-1 , 0
  4425.8     .05       0  4570.1     .16       0    4682     .12       0
  4995.3     .07       0  5001.3     .12       0  5219.6     .16       0
Bank Sta=4936.7,5052.8
XS Rating Curve= 0 ,0
Exp/Cntr=0.3,0.1

Type RM Length L Ch R = 1 ,29826   ,387,387,387
BEGIN DESCRIPTION:
MINE CREEK 58.0
END DESCRIPTION:
XS GIS Cut Line= 3
      3708049.65     10763160.18      3707599.61     10763210.19
      3707399.59     10763460.21
#Sta/Elev= 30
  4555.1  423.45  4556.3  423.45  4645.7  409.56  4685.9  404.82    4696   404.7
  4746.3  398.85  4836.9   391.2  4846.9  389.48  4882.1   387.2  4917.4  385.29
  4937.5  385.72  4947.5  384.67  4967.7   384.6  4977.7  381.98  4987.8  372.29
  5012.1  371.82  5014.9  371.32  5018.1  371.82  5021.5  374.27  5029.5  374.06
  5035.9  381.69  5058.3  384.69  5149.6  384.81  5213.6  387.91    5236  389.85
  5271.2  395.23  5306.5  402.45  5320.9  404.27  5324.9  406.88  5328.1  406.88
#Mann= 5 ,-1 , 0
  4555.1     .05       0  4556.3     .12       0  4882.1     .16       0
  5012.1     .07       0  5018.1     .16       0
Bank Sta=4967.7,5058.3
XS Rating Curve= 0 ,0
Exp/Cntr=0.3,0.1

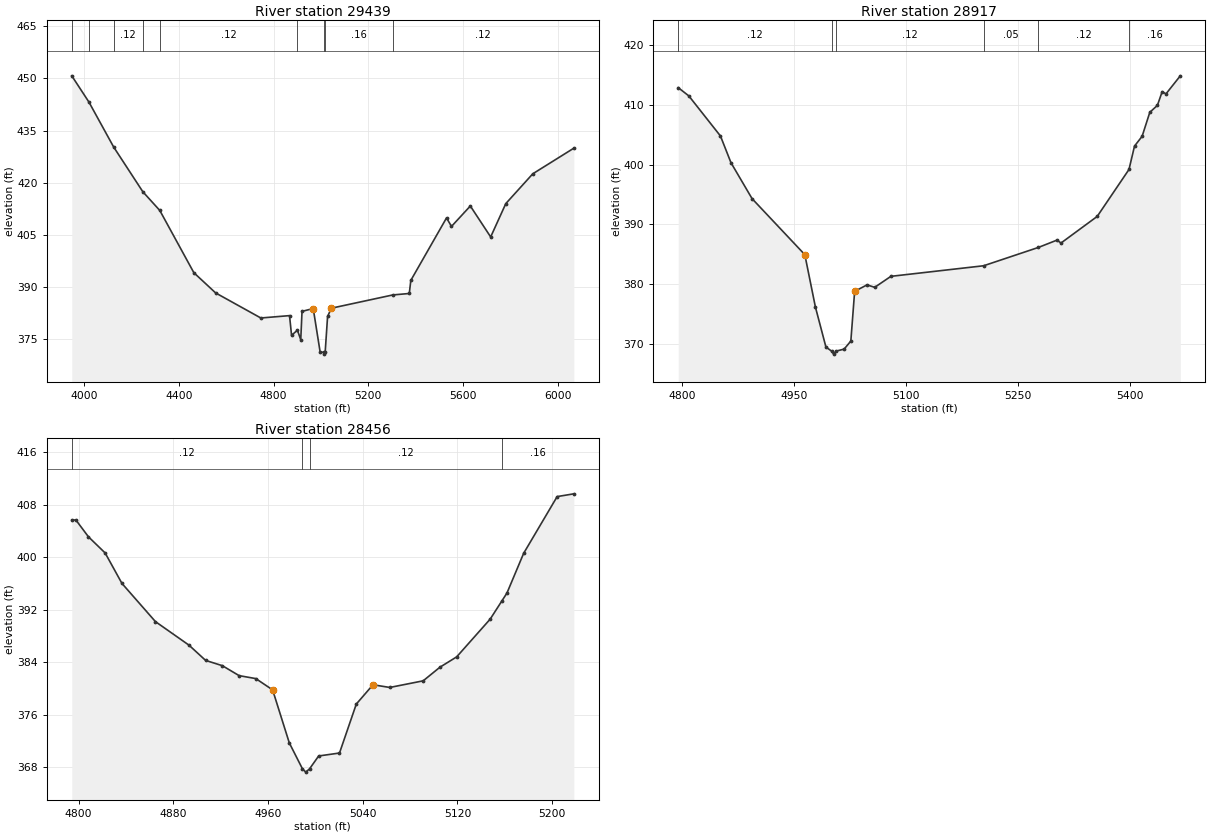
Type RM Length L Ch R = 1 ,29439   ,522,522,522
BEGIN DESCRIPTION:
MINE CREEK 57.0
END DESCRIPTION:
XS GIS Cut Line= 4
      3708434.45     10762716.33      3707631.47     10762792.28
      3707273.39     10762944.19      3706730.88     10763692.87
#Sta/Elev= 30
  3947.9  450.73  4020.3   443.2  4124.8  430.28  4247.9  417.44  4319.7  412.05
  4463.4  394.18  4555.4  388.37  4746.3  381.17  4867.4  381.85    4876   376.2
  4900.8  377.66  4914.8  374.93  4920.2  383.07  4967.5  383.89  4996.6  371.43
  5011.9  371.29  5014.6  370.79  5017.9  371.29  5028.1   381.6    5044  383.98
  5303.5  387.79  5373.1  388.21  5379.6  391.97  5530.4  409.92  5551.3  407.47
  5630.9  413.34  5716.8  404.45  5780.7  414.03  5894.6  422.59    6068  429.95
#Mann= 9 ,-1 , 0
  3947.9     .05       0  4020.3     .16       0  4124.8     .12       0
  4247.9     .16       0  4319.7     .12       0  4900.8     .16       0
  5011.9     .07       0  5017.9     .16       0  5303.5     .12       0
Bank Sta=4967.5,5044
XS Rating Curve= 0 ,0
Exp/Cntr=0.3,0.1

Type RM Length L Ch R = 1 ,28917   ,461,461,461
BEGIN DESCRIPTION:
MINE CREEK 56.0
END DESCRIPTION:
XS GIS Cut Line= 3
      3707299.62     10762310.17      3707149.61     10762460.19
      3706699.64     10762560.18
#Sta/Elev= 30
  4794.3  412.89  4808.5  411.51  4850.9   404.8    4865  400.33  4893.3  394.31
    4964  384.94  4978.2  376.17  4992.3  369.48  4999.9  368.79  5002.7  368.29
  5005.9  368.79  5016.7  369.13  5025.7  370.48  5030.8   378.8  5047.4  379.88
  5057.7  379.47  5079.4  381.31  5203.7  383.08  5277.2  386.15  5302.2  387.38
  5307.4  386.88    5356  391.34  5398.6   399.2    5406  403.11  5416.2  404.75
  5426.5  408.76  5436.7  409.93  5443.1  412.23  5448.2  411.85  5467.4  414.87
#Mann= 6 ,-1 , 0
  4794.3     .12       0  4999.9     .07       0  5005.9     .12       0
  5203.7     .05       0  5277.2     .12       0  5398.6     .16       0
Bank Sta=4964,5030.8
XS Rating Curve= 0 ,0
Exp/Cntr=0.3,0.1

Type RM Length L Ch R = 1 ,28456   ,328,328,328
BEGIN DESCRIPTION:
MINE CREEK 55.0
END DESCRIPTION:
XS GIS Cut Line= 3
      3706999.58     10762010.22      3706849.61     10762160.19
      3706699.63     10762310.17
#Sta/Elev= 30
  4794.2  405.69  4797.7  405.69  4808.3  403.13  4822.4  400.67  4836.6  396.03
  4864.9  390.21  4893.2  386.63  4907.3   384.3  4921.4   383.5  4935.6  381.98
  4949.7  381.53  4963.9  379.81    4978  371.73  4989.1  367.78  4991.9  367.28
  4995.1  367.78  5002.8  369.74  5020.4  370.19  5034.6  377.65  5048.7  380.59
  5062.9  380.18  5091.1  381.19  5105.3  383.27  5119.4  384.84  5147.7  390.59
  5157.7  393.39  5161.9  394.57    5176  400.62  5204.3  409.26  5218.4  409.68
#Mann= 4 ,-1 , 0
  4794.2     .12       0  4989.1     .07       0  4995.1     .12       0
  5157.7     .16       0
Bank Sta=4963.9,5048.7
XS Rating Curve= 0 ,0
Exp/Cntr=0.3,0.1