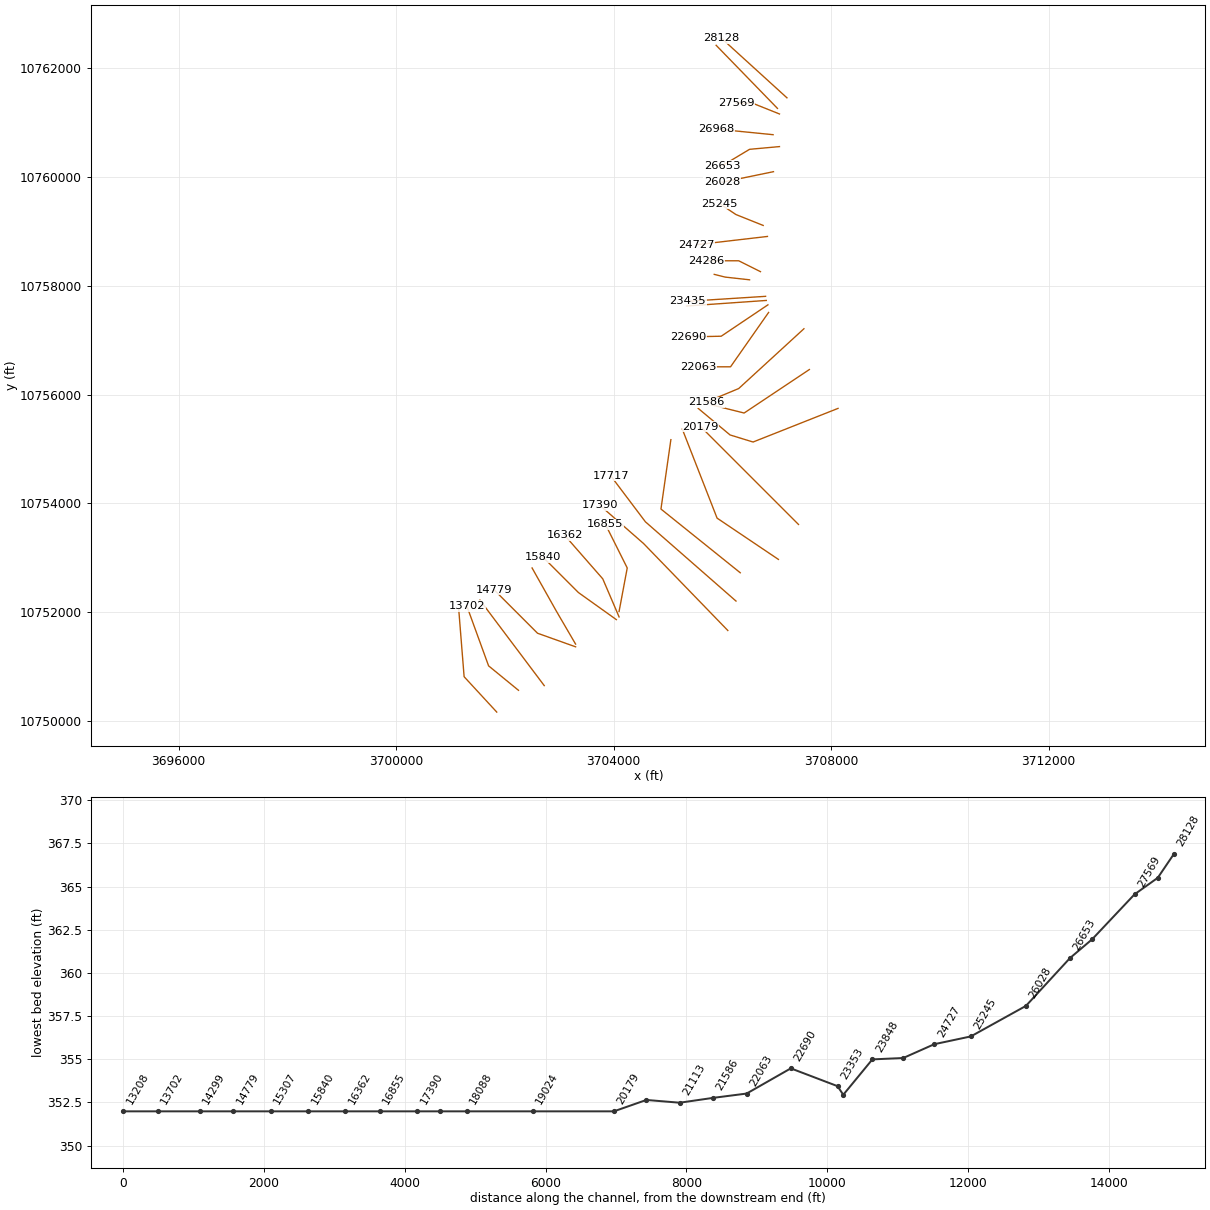
HEC-RAS study MINE CREEK.prj: MINE CREEK Base Level Engineering

--- MINE CREEK.g01 (geometry) --- (continued)

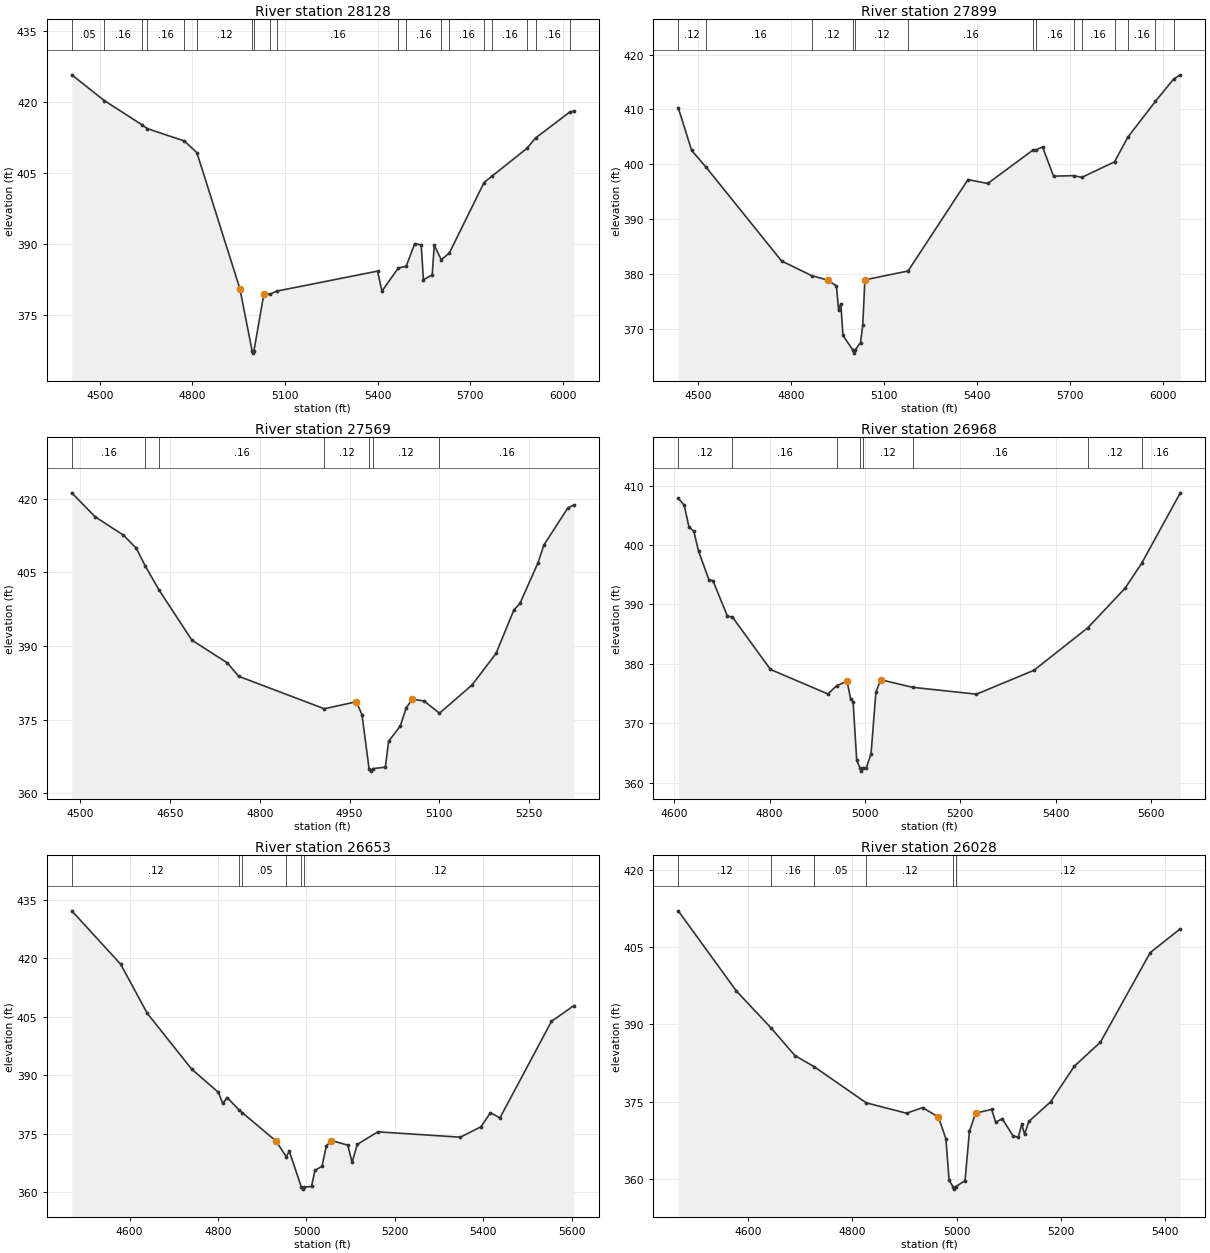
Type RM Length L Ch R = 1 ,28128   ,229,229,229
BEGIN DESCRIPTION:
Mapping XS 00ee41d8
END DESCRIPTION:
XS GIS Cut Line= 2
      3707186.57     10761457.67       3705983.4     10762552.44
#Sta/Elev= 30
  4409.1  425.76  4514.6  420.31  4635.1  415.25  4654.3  414.37  4773.8  411.77
  4814.5  409.29  4953.9  380.49  4993.4  367.39  4996.2  366.89  4999.4  367.39
  5031.6  379.45  5051.3  379.37  5073.4  380.01  5399.8  384.24    5414     380
  5467.4  384.92  5492.5  385.24  5520.1  390.01  5541.1  389.82  5548.5  382.41
  5576.9  383.45  5583.6  389.71  5606.1  386.65  5632.2  388.05  5744.9  402.98
  5771.9  404.39  5883.6   410.2  5911.7  412.39  6022.3  417.88  6035.8  418.07
#Mann= 19 ,-1 , 0
  4409.1     .05       0  4514.6     .16       0  4635.1     .05       0
  4654.3     .16       0  4773.8     .08       0  4814.5     .12       0
  4993.4     .07       0  4999.4     .12       0  5051.3     .05       0
  5073.4     .16       0  5467.4     .05       0  5492.5     .16       0
  5606.1     .05       0  5632.2     .16       0  5744.9     .05       0
  5771.9     .16       0  5883.6     .05       0  5911.7     .16       0
  6022.3     .05       0
Bank Sta=4953.9,5031.6
XS Rating Curve= 0 ,0
Exp/Cntr=0.3,0.1

Type RM Length L Ch R = 1 ,27899   ,330,330,330
BEGIN DESCRIPTION:
MINE CREEK 54.0
END DESCRIPTION:
XS GIS Cut Line= 2
      3707012.98     10761262.33      3705884.57      10762423.3
#Sta/Elev= 30
  4435.7   410.3    4479  402.51  4525.2  399.46  4768.9  382.33  4865.6  379.66
  4917.5  378.84  4945.8  377.77  4952.8  373.37  4959.9   374.5  4966.9  368.76
  4999.4  366.01  5002.1  365.51  5005.4  366.01  5023.5  367.44  5030.7  370.62
  5037.6  378.88  5176.8   380.5    5370  397.18  5433.7  396.47  5579.1  402.55
  5589.4  402.62  5610.5  403.14  5645.9  397.81  5710.9   397.9  5737.3  397.59
  5842.6  400.42  5885.2   404.9  5974.3  411.45  6033.1  415.53  6054.7   416.3
#Mann= 14 ,-1 , 0
  4435.7     .12       0  4525.2     .16       0  4865.6     .12       0
  4999.4     .07       0  5005.4     .12       0  5176.8     .16       0
  5579.1     .08       0  5589.4     .16       0  5710.9     .08       0
  5737.3     .16       0  5842.6     .08       0  5885.2     .16       0
  5974.3     .08       0  6033.1     .16       0
Bank Sta=4917.5,5037.6
XS Rating Curve= 0 ,0
Exp/Cntr=0.3,0.1

Type RM Length L Ch R = 1 ,27569   ,601,601,601
BEGIN DESCRIPTION:
MINE CREEK 53.0
END DESCRIPTION:
XS GIS Cut Line= 3
      3707049.61     10761160.19      3706549.61     10761360.19
      3706249.62     10761360.19
#Sta/Elev= 30
    4486  421.22    4525  416.34  4572.2  412.61  4593.7  409.95  4608.4   406.4
  4631.5  401.49  4686.6  391.22  4745.8  386.59  4764.7  383.86  4907.8  377.25
  4961.2  378.68  4970.7  376.06  4982.5  365.05  4985.2  364.55  4988.5  365.05
  5009.7  365.36  5015.1  370.62  5034.5   373.7  5044.5  377.39  5054.5  379.18
  5074.5  378.84    5100  376.34  5154.5  382.09  5194.5  388.51  5224.5  397.41
  5234.5   398.7  5264.5  406.94  5274.5   410.6  5314.5  418.14  5324.5  418.72
#Mann= 7 ,-1 , 0
    4486     .16       0  4608.4     .12       0  4631.5     .16       0
  4907.8     .12       0  4982.5     .07       0  4988.5     .12       0
    5100     .16       0
Bank Sta=4961.2,5054.5
XS Rating Curve= 0 ,0
Exp/Cntr=0.3,0.1

Type RM Length L Ch R = 1 ,26968   ,315,315,315
BEGIN DESCRIPTION:
MINE CREEK 52.0
END DESCRIPTION:
XS GIS Cut Line= 2
      3706932.13     10760779.19      3705884.09      10760883.3
#Sta/Elev= 30
  4608.5  407.87  4621.1  406.68  4631.1     403  4641.2  402.31  4651.2  398.94
  4672.8  394.18  4681.4  393.99  4711.5  388.06  4722.3  387.86    4802  379.06
  4922.6  374.93    4941  376.35  4962.8  377.06  4970.2  374.07  4975.3  373.64
  4982.9  363.77  4989.9  362.45  4992.7  361.95  4995.9  362.45    5003  362.46
    5013   364.9  5023.1  375.22  5033.1  377.33  5100.5  376.05  5234.1   374.9
  5354.7  378.92  5467.9  386.09  5545.6  392.71  5580.6  396.92  5661.7  408.78
#Mann= 8 ,-1 , 0
  4608.5     .12       0  4722.3     .16       0    4941     .12       0
  4989.9     .07       0  4995.9     .12       0  5100.5     .16       0
  5467.9     .12       0  5580.6     .16       0
Bank Sta=4962.8,5033.1
XS Rating Curve= 0 ,0
Exp/Cntr=0.3,0.1

Type RM Length L Ch R = 1 ,26653   ,625,625,625
BEGIN DESCRIPTION:
MINE CREEK 51.0
END DESCRIPTION:
XS GIS Cut Line= 3
      3707049.62     10760560.19      3706499.61     10760510.19
      3705999.59     10760210.18
#Sta/Elev= 30
  4469.2  432.16  4579.7   418.5  4639.9  405.91  4740.3  391.61  4800.6  385.68
  4810.6  382.81  4820.7  384.33  4847.6  381.13  4855.1  380.42  4931.1  373.18
  4954.2  369.19  4961.2  370.56  4988.4  361.36  4991.1  360.86  4994.4  361.36
  5011.4  361.54    5019  365.64  5035.1  366.73  5044.8  371.92  5056.5   373.3
  5093.4  372.13  5103.1   367.7  5114.8  372.32  5161.4  375.54    5348  374.17
  5394.7  376.84    5416  380.46  5437.4   379.1    5554  403.84  5604.6  407.87
#Mann= 6 ,-1 , 0
  4469.2     .12       0  4847.6     .16       0  4855.1     .05       0
  4954.2     .12       0  4988.4     .07       0  4994.4     .12       0
Bank Sta=4931.1,5056.5
XS Rating Curve= 0 ,0
Exp/Cntr=0.3,0.1

Type RM Length L Ch R = 1 ,26028   ,783,783,783
BEGIN DESCRIPTION:
MINE CREEK 49.0
END DESCRIPTION:
XS GIS Cut Line= 2
      3706939.12     10760098.63      3705994.73     10759904.19
#Sta/Elev= 30
  4465.5     412    4577  396.49  4643.8  389.31  4689.6  383.96  4726.2  381.83
  4826.5  374.81    4904  372.79  4934.6  373.88  4965.3  372.06  4979.5  367.82
  4985.7  359.81  4992.9  358.59  4995.7  358.09  4998.9  358.59  5016.3  359.75
  5024.7  369.29  5036.7  372.82  5067.4  373.53  5075.1  371.06  5087.8  371.72
  5108.2  368.44  5118.4  368.12  5125.4  370.69  5130.5  368.71  5138.8   371.2
  5180.8  375.02    5226  381.88  5276.3  386.56  5371.9  403.91  5429.7  408.52
#Mann= 6 ,-1 , 0
  4465.5     .12       0  4643.8     .16       0  4726.2     .05       0
  4826.5     .12       0  4992.9     .07       0  4998.9     .12       0
Bank Sta=4965.3,5036.7
XS Rating Curve= 0 ,0
Exp/Cntr=0.3,0.1

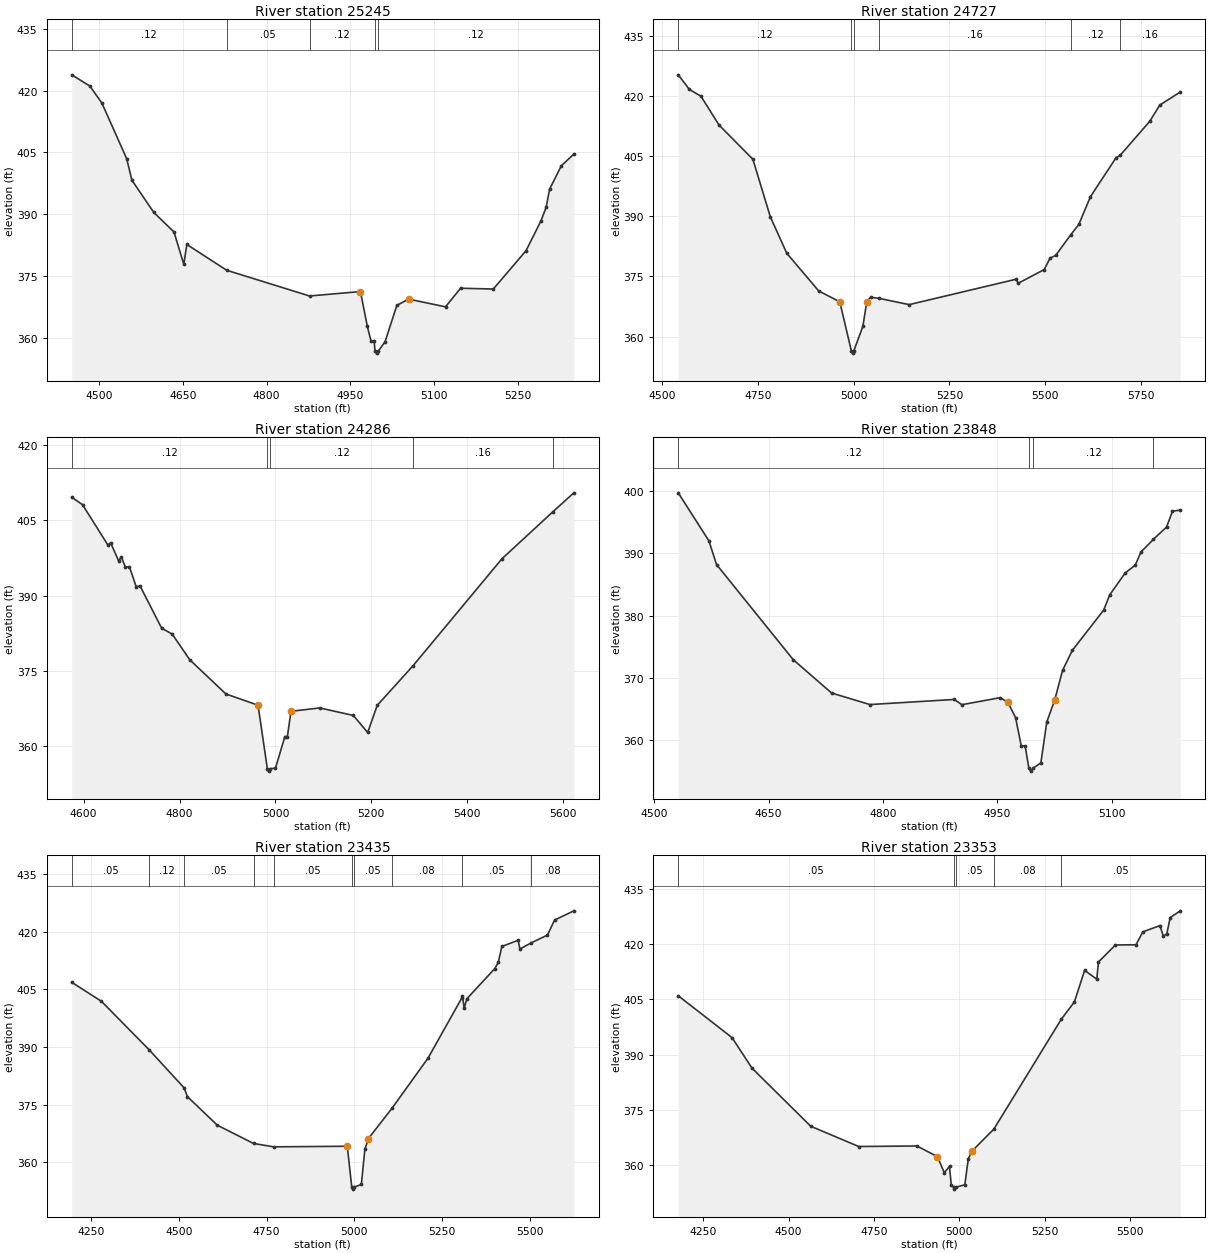
Type RM Length L Ch R = 1 ,25245   ,518,518,518
BEGIN DESCRIPTION:
MINE CREEK 48.0
END DESCRIPTION:
XS GIS Cut Line= 3
      3706749.58      10759110.2      3706249.61     10759310.19
      3705949.64     10759510.17
#Sta/Elev= 30
  4451.3  423.82  4483.6   421.1  4505.1  417.01  4549.5  403.52    4559  398.26
    4598  390.48  4634.4  385.69  4651.9  377.86  4657.3  382.68  4728.7  376.42
    4877  370.18  4968.2  371.25  4980.4  362.89  4987.1  359.23  4992.8  359.23
  4994.3  356.82    4997  356.32  5000.3  356.82  5012.3  359.09  5033.4  367.91
  5054.4  369.42  5120.5  367.55  5147.5  372.06  5206.1  371.87  5264.7  381.17
  5291.7  388.47  5300.8  391.74  5306.8  396.06  5327.8  401.74  5350.3  404.61
#Mann= 5 ,-1 , 0
  4451.3     .12       0  4728.7     .05       0    4877     .12       0
  4994.3     .07       0  5000.3     .12       0
Bank Sta=4968.2,5054.4
XS Rating Curve= 0 ,0
Exp/Cntr=0.3,0.1

Type RM Length L Ch R = 1 ,24727   ,441,441,441
BEGIN DESCRIPTION:
MINE CREEK 47.0
END DESCRIPTION:
XS GIS Cut Line= 2
      3706828.53     10758907.74      3705526.46     10758755.83
#Sta/Elev= 30
    4542  425.34  4571.1  421.69  4601.3     420  4648.5  412.81  4736.9  404.26
  4782.5  389.88  4825.4   380.8  4908.8  371.39  4963.8  368.68  4994.2  356.37
    4997  355.87  5000.2  356.37  5024.2  362.59  5034.2  368.67  5044.3  369.81
    5065  369.57    5145  367.98  5424.4  374.32  5429.4   373.3  5497.4  376.72
  5512.9  379.58  5527.6  380.28  5567.2  385.46    5588  388.02  5618.2  394.91
  5684.7  404.59    5696  405.26  5773.2  413.75  5799.4   417.8  5852.9  421.05
#Mann= 6 ,-1 , 0
    4542     .12       0  4994.2     .07       0  5000.2     .12       0
    5065     .16       0  5567.2     .12       0    5696     .16       0
Bank Sta=4963.8,5034.2
XS Rating Curve= 0 ,0
Exp/Cntr=0.3,0.1

Type RM Length L Ch R = 1 ,24286   ,438,438,438
BEGIN DESCRIPTION:
MINE CREEK 46.0
END DESCRIPTION:
XS GIS Cut Line= 3
      3706699.63     10758260.18      3706299.61     10758460.19
      3705699.65     10758460.19
#Sta/Elev= 30
  4575.2  409.59  4597.6  408.11  4650.7  400.06  4656.3  400.52  4673.1  396.88
  4678.6  397.75    4687  395.64  4695.4  395.77  4709.4  391.82  4717.8   391.9
  4762.5  383.55  4784.9  382.33  4821.2  377.25  4896.7  370.43  4963.7  368.19
  4983.1  355.57  4985.9  355.07  4989.1  355.57  5000.1  355.65  5019.6  361.94
  5024.9  361.94  5032.4  366.98  5092.4  367.65  5162.4  366.16  5192.4  362.76
  5212.4  368.18  5286.5  375.99  5472.4  397.34    5579  406.73  5622.4  410.47
#Mann= 5 ,-1 , 0
  4575.2     .12       0  4983.1     .07       0  4989.1     .12       0
  5286.5     .16       0    5579     .12       0
Bank Sta=4963.7,5032.4
XS Rating Curve= 0 ,0
Exp/Cntr=0.3,0.1

Type RM Length L Ch R = 1 ,23848   ,413,413,413
BEGIN DESCRIPTION:
MINE CREEK 45.0
END DESCRIPTION:
XS GIS Cut Line= 3
      3706499.58     10758110.19      3706049.61     10758160.19
      3705849.61     10758210.19
#Sta/Elev= 30
  4531.3  399.76  4571.5  392.05  4581.6  388.22  4682.2  372.92  4732.5  367.56
  4782.8   365.7  4893.5  366.52  4903.6  365.68  4953.9  366.81  4963.9  366.06
    4974   363.6  4981.5  359.04  4986.6  359.04  4991.4  355.49  4994.1  354.99
  4997.4  355.49  5007.2  356.33    5015  362.91  5025.3  366.39  5035.6  371.18
  5048.5  374.42  5089.7  380.91  5097.4  383.32    5118  386.89  5130.9   388.1
  5138.7  390.26    5155  392.29  5172.2  394.27  5179.9  396.79  5190.2     397
#Mann= 4 ,-1 , 0
  4531.3     .12       0  4991.4     .07       0  4997.4     .12       0
    5155     .16       0
Bank Sta=4963.9,5025.3
XS Rating Curve= 0 ,0
Exp/Cntr=0.3,0.1

Type RM Length L Ch R = 1 ,23435   ,82,82,82
BEGIN DESCRIPTION:
MINE CREEK 44.0
END DESCRIPTION:
XS GIS Cut Line= 2
        3706794.     10757806.15      3705364.59     10757715.19
#Sta/Elev= 30
  4194.2  406.87  4278.8  401.92  4415.8  389.19  4514.8  379.33  4524.3  377.04
  4609.4  369.61  4712.7  364.85  4769.8  363.97  4980.2  364.12    4993  353.44
  4995.7  352.94    4999  353.44  5020.3  354.15  5030.3  363.29  5040.3  366.11
  5108.5  374.12  5210.6  387.11  5306.4  402.71  5308.7   403.3  5313.7  400.11
  5320.9  402.54    5401  410.46    5411   412.1  5421.1  416.21  5467.6  417.84
  5472.6  415.55  5504.3  417.13  5551.3  419.19  5571.4  423.09  5626.5  425.51
#Mann= 10 ,-1 , 0
  4194.2     .05       0  4415.8     .12       0  4514.8     .05       0
  4712.7     .16       0  4769.8     .05       0    4993     .04       0
    4999     .05       0  5108.5     .08       0  5306.4     .05       0
  5504.3     .08       0
Bank Sta=4980.2,5040.3
XS Rating Curve= 0 ,0
Exp/Cntr=0.3,0.1

Type RM Length L Ch R = 1 ,23353   ,663,663,663
BEGIN DESCRIPTION:
MINE CREEK 43.0
END DESCRIPTION:
XS GIS Cut Line= 2
      3706806.82     10757730.45      3705340.07     10757628.21
#Sta/Elev= 30
  4176.6  405.98  4334.2   394.6  4392.7   386.3  4564.7  370.52  4705.1  365.02
  4875.5  365.16  4935.6  362.28  4955.7  357.89    4971  359.61    4976  354.68
  4982.8  353.94  4985.5  353.44  4988.8  353.94  5015.8  354.61  5025.9  361.61
  5035.9  363.68  5100.9  369.75  5298.8  399.66  5336.6  404.28  5366.7  412.86
  5402.2   410.5  5407.2  415.15  5456.9  419.78  5517.1  419.82  5537.1  423.33
  5587.2  425.04  5597.2   422.2  5607.3  422.78  5617.3  427.22  5646.9  429.05
#Mann= 5 ,-1 , 0
  4176.6     .05       0  4982.8     .04       0  4988.8     .05       0
  5100.9     .08       0  5298.8     .05       0
Bank Sta=4935.6,5035.9
XS Rating Curve= 0 ,0
Exp/Cntr=0.3,0.1

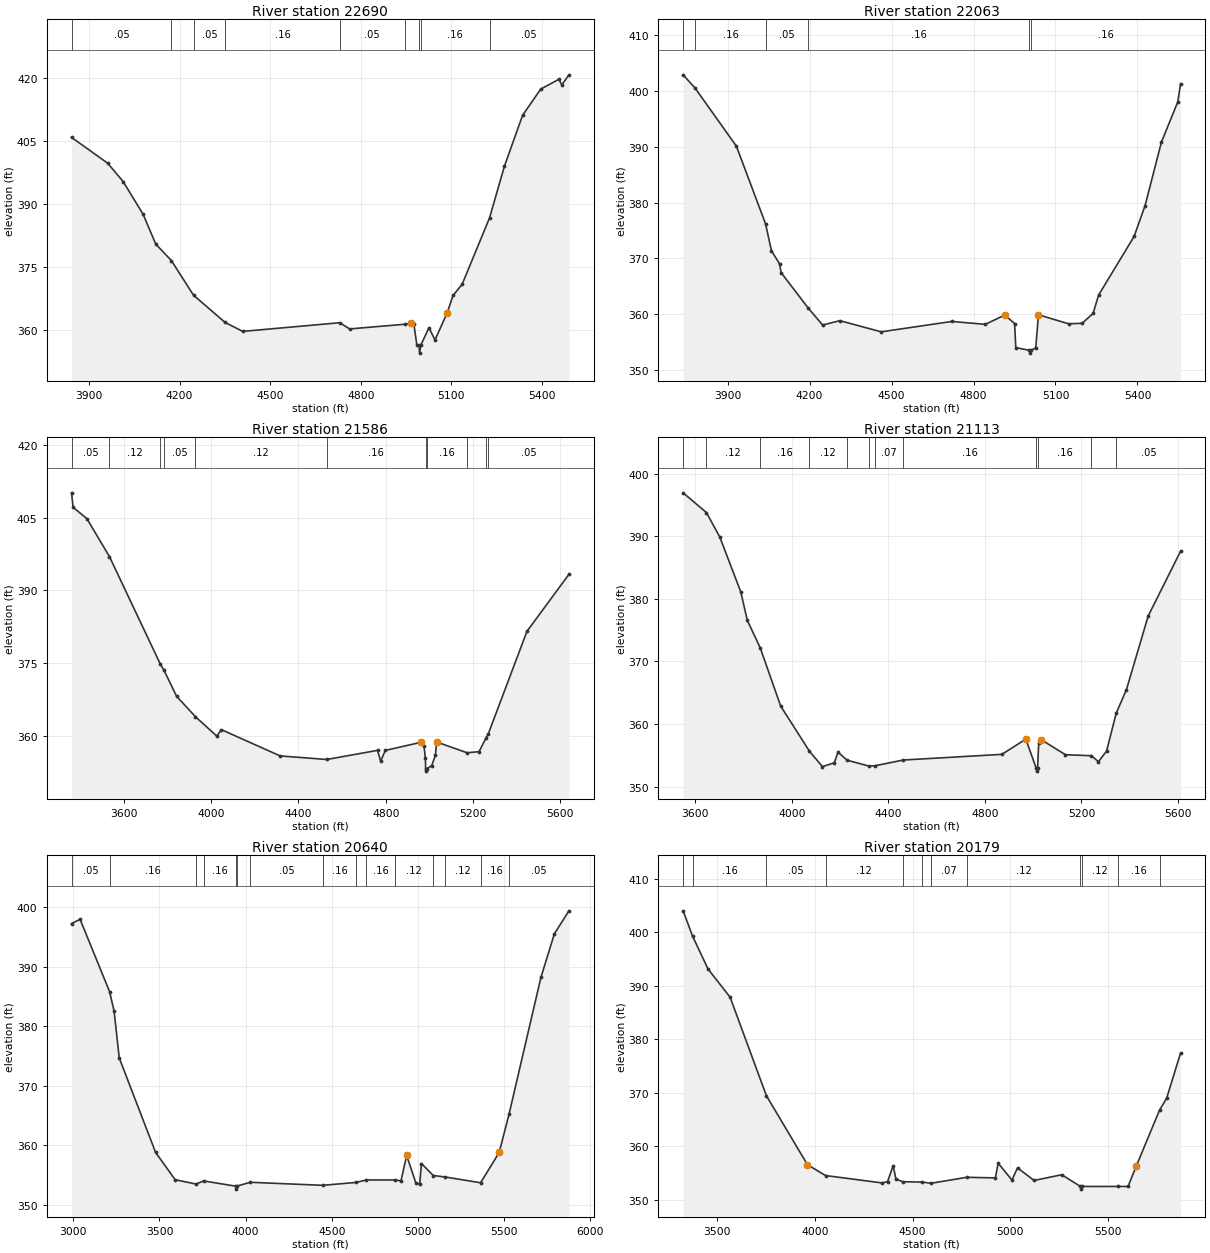
Type RM Length L Ch R = 1 ,22690   ,627,627,627
BEGIN DESCRIPTION:
MINE CREEK 42.0
END DESCRIPTION:
XS GIS Cut Line= 3
       3706837.4     10757649.89      3705978.05     10757072.65
      3705366.11     10757059.63
#Sta/Elev= 30
  3842.2  405.91  3962.1  399.74  4013.1  395.37  4079.1   387.6  4121.1  380.46
  4172.7  376.55  4246.2  368.28  4350.9  361.78  4409.2  359.65  4730.5  361.72
  4763.2  360.24    4945  361.35  4965.9  361.58  4975.9  361.39  4985.9   356.4
  4992.9  356.36 4994.75  354.47  4998.9  356.36  5025.9  360.52  5045.9  357.61
  5085.9  364.02  5105.9  368.23  5135.9   370.9  5226.7  386.74    5276  399.07
    5336  411.17    5396  417.41    5456  419.75    5466  418.44  5489.5  420.82
#Mann= 9 ,-1 , 0
  3842.2     .05       0  4172.7     .16       0  4246.2     .05       0
  4350.9     .16       0  4730.5     .05       0    4945     .16       0
  4992.9     .07       0  4998.9     .16       0  5226.7     .05       0
Bank Sta=4965.9,5085.9
XS Rating Curve= 0 ,0
Exp/Cntr=0.3,0.1

Type RM Length L Ch R = 1 ,22063   ,477,477,477
BEGIN DESCRIPTION:
MINE CREEK 41.0
END DESCRIPTION:
XS GIS Cut Line= 3
      3706849.61     10757510.18      3706149.61     10756510.19
      3705549.66     10756510.19
#Sta/Elev= 30
  3737.1  402.92    3781  400.53    3932  390.12    4039  376.17  4060.1  371.39
  4089.8  369.04  4095.9  367.44  4194.9  361.09  4247.6  358.05  4310.8  358.83
  4462.1  356.83    4721  358.69  4843.1  358.17  4914.6  359.85  4950.3  358.31
  4954.7     354  5004.7  353.51  5007.5  353.01  5010.7  353.51  5027.7  353.97
  5037.7  359.89  5147.7  358.27  5197.7  358.36  5237.7  360.14  5257.7  363.41
  5387.7  373.94  5427.7  379.44  5487.7  390.85  5547.7  398.08  5557.7  401.31
#Mann= 6 ,-1 , 0
  3737.1     .05       0    3781     .16       0    4039     .05       0
  4194.9     .16       0  5004.7     .07       0  5010.7     .16       0
Bank Sta=4914.6,5037.7
XS Rating Curve= 0 ,0
Exp/Cntr=0.3,0.1

Type RM Length L Ch R = 1 ,21586   ,473,473,473
BEGIN DESCRIPTION:
MINE CREEK 40.0
END DESCRIPTION:
XS GIS Cut Line= 3
      3707499.63     10757210.21      3706299.61     10756110.19
      3705699.62     10755860.19
#Sta/Elev= 30
  3361.1  410.12  3368.2  407.14  3431.7  404.78  3534.9  396.96  3767.8  374.81
  3783.4  373.65  3842.4  368.18  3928.7  363.97  4026.2  359.98  4047.7   361.3
  4316.6  355.89  4529.9  355.16  4762.4  357.04  4776.6  354.82  4798.2  357.03
    4961   358.7  4975.1  357.93  4981.9  355.38  4982.6  353.26  4985.4  352.76
  4988.6  353.26  5010.7  353.91  5027.5  356.04  5032.9  358.77  5172.2  356.55
  5227.3  356.77  5258.4  359.52  5269.9  360.47  5446.7  381.57    5639  393.32
#Mann= 11 ,-1 , 0
  3361.1     .05       0  3534.9     .12       0  3767.8     .16       0
  3783.4     .05       0  3928.7     .12       0  4529.9     .16       0
  4982.6     .07       0  4988.6     .16       0  5172.2     .12       0
  5258.4     .16       0  5269.9     .05       0
Bank Sta=4961,5032.9
XS Rating Curve= 0 ,0
Exp/Cntr=0.3,0.1

Type RM Length L Ch R = 1 ,21113   ,473,473,473
BEGIN DESCRIPTION:
MINE CREEK 39.0
END DESCRIPTION:
XS GIS Cut Line= 3
       3707599.6     10756460.18      3706399.61     10755660.19
      3705799.58      10755810.2
#Sta/Elev= 30
  3550.1  396.93  3646.5  393.78  3701.8  389.89    3789  381.09    3816  376.56
  3869.4  372.18  3954.2  362.87  4073.4  355.66    4127   353.2  4176.5  353.81
  4191.6  355.51  4228.9  354.23  4318.6   353.3  4344.9  353.33  4460.9  354.25
  4870.6  355.16  4969.8  357.59  5012.5  352.98  5015.2  352.48  5018.5  352.98
  5023.2  356.98  5033.5   357.5    5134   355.1  5241.5  354.94  5270.6  353.99
  5304.1  355.66  5344.5  361.76  5386.6  365.49  5476.8  377.26  5610.8   387.6
#Mann= 12 ,-1 , 0
  3550.1     .16       0  3646.5     .12       0  3869.4     .16       0
  4073.4     .12       0  4228.9     .07       0  4318.6     .12       0
  4344.9     .07       0  4460.9     .16       0  5012.5     .07       0
  5018.5     .16       0  5241.5     .12       0  5344.5     .05       0
Bank Sta=4969.8,5033.5
XS Rating Curve= 0 ,0
Exp/Cntr=0.3,0.1

Type RM Length L Ch R = 1 ,20640   ,461,461,461
BEGIN DESCRIPTION:
MINE CREEK 38.0
END DESCRIPTION:
XS GIS Cut Line= 4
      3708126.36     10755745.26      3706563.85     10755126.76
      3706140.67     10755256.97      3705554.77     10755745.22
#Sta/Elev= 30
    2990   397.3  3039.7  398.01  3210.7  385.85    3237  382.57  3266.7  374.71
  3477.6  358.82    3591  354.23    3713  353.49  3756.1  354.02  3942.1  353.14
  3944.9  352.64  3948.1  353.14  4027.6  353.79  4447.1  353.28  4641.5  353.77
  4699.5  354.18  4866.4  354.18  4901.5  354.03  4934.2   358.3  4988.8   353.6
  5010.1  353.47  5020.2  356.94  5088.7  354.93  5158.1  354.68  5363.4  353.71
  5471.1   358.8  5527.9  365.19  5713.3  388.24  5791.4  395.57  5875.9  399.44
#Mann= 15 ,-1 , 0
    2990     .05       0  3210.7     .16       0    3713     .05       0
  3756.1     .16       0  3942.1     .07       0  3948.1     .16       0
  4027.6     .05       0  4447.1     .16       0  4641.5     .05       0
  4699.5     .16       0  4866.4     .12       0  5088.7     .16       0
  5158.1     .12       0  5363.4     .16       0  5527.9     .05       0
Bank Sta=4934.2,5471.1
XS Rating Curve= 0 ,0
Exp/Cntr=0.3,0.1

Type RM Length L Ch R = 1 ,20179   ,1155,1155,1155
BEGIN DESCRIPTION:
MINE CREEK 37.0
END DESCRIPTION:
XS GIS Cut Line= 3
      3707399.62     10753610.18      3706199.61     10754810.19
      3705599.61     10755410.19
#Sta/Elev= 30
  3325.9  404.01    3374  399.29  3453.2  393.14  3566.3  387.86    3752  369.44
  3962.3  356.54  4054.7  354.52  4344.2  353.14  4372.4   353.4  4400.7  356.38
  4414.9  353.86  4450.2  353.36  4549.1   353.3  4595.3  353.08  4777.9  354.19
    4924  354.08  4938.1  356.83  5008.8  353.67  5037.1  355.96    5122   353.6
  5263.4  354.67  5359.4  352.48  5362.1  351.98  5365.4  352.48  5551.1  352.48
  5602.8  352.48  5645.2  356.31  5763.8  366.73  5800.8  369.01  5871.5  377.42
#Mann= 12 ,-1 , 0
  3325.9     .12       0    3374     .16       0    3752     .05       0
  4054.7     .12       0  4450.2     .07       0  4549.1     .05       0
  4595.3     .07       0  4777.9     .12       0  5359.4     .07       0
  5365.4     .12       0  5551.1     .16       0  5763.8     .05       0
Bank Sta=3962.3,5645.2
XS Rating Curve= 0 ,0
Exp/Cntr=0.3,0.1

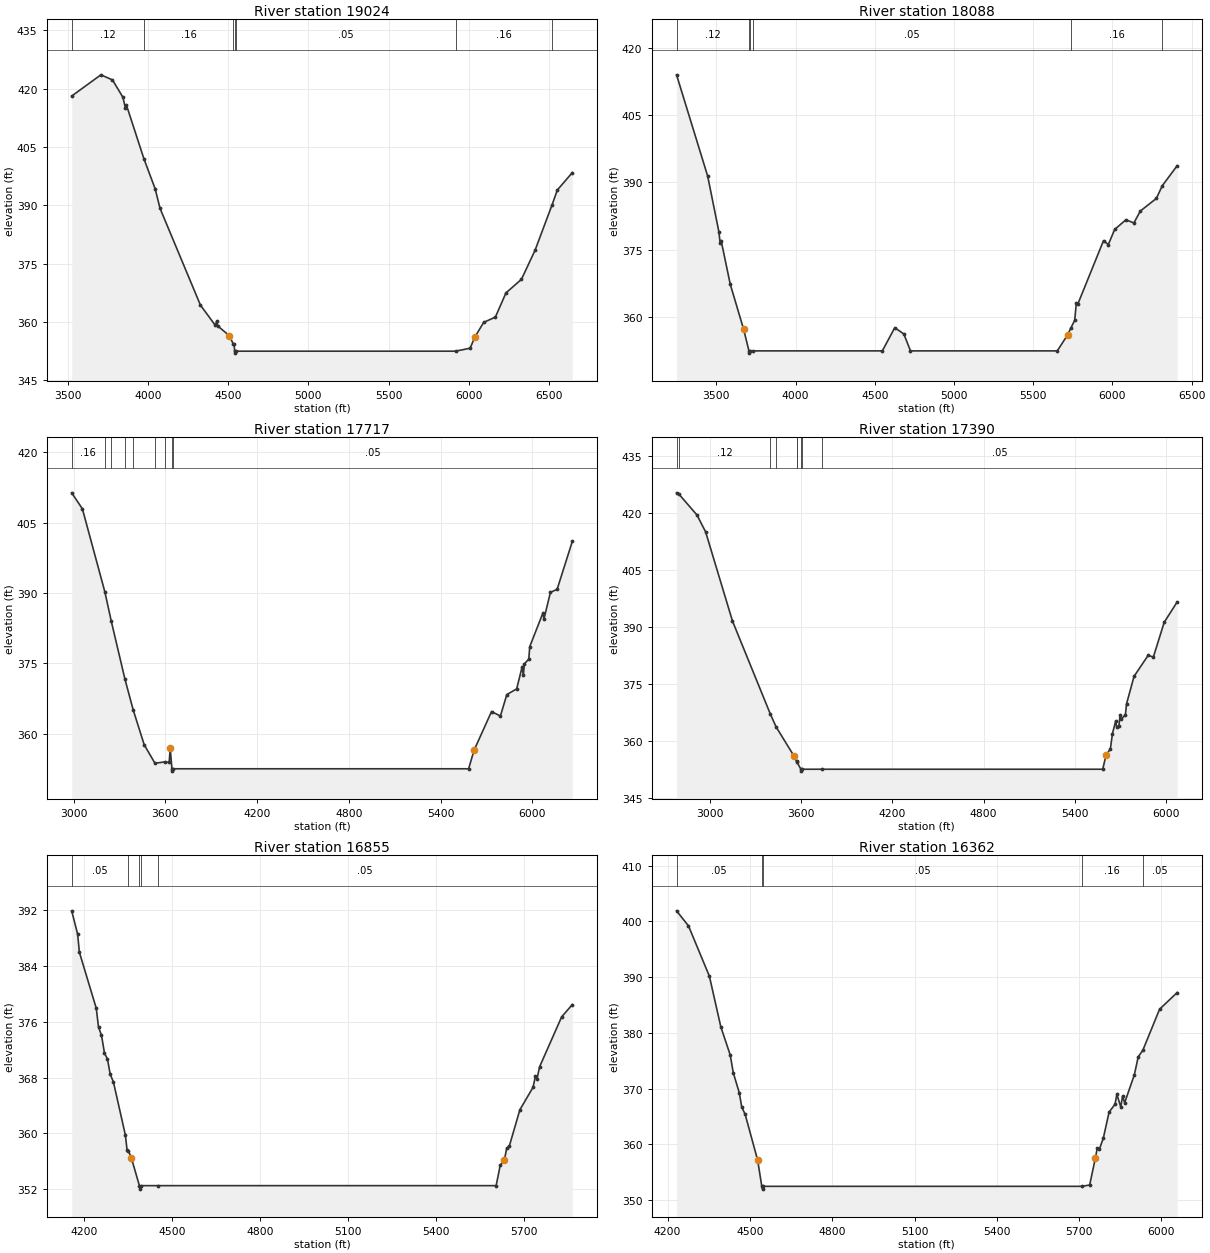
Type RM Length L Ch R = 1 ,19024   ,936,936,936
BEGIN DESCRIPTION:
MINE CREEK 36.0
END DESCRIPTION:
XS GIS Cut Line= 3
      3707030.45     10752967.46      3705901.96     10753727.02
      3705261.83      10755365.3
#Sta/Elev= 30
  3525.6  418.09  3707.4  423.55  3779.7  422.24    3845  417.75  3859.9  415.05
    3866  415.85  3976.4  401.86  4045.9   394.2  4075.9  389.22  4327.8  364.32
  4420.8   359.1  4429.8  360.28  4435.8  358.96  4507.8  356.47  4532.9  354.28
  4537.7   354.3  4540.8  352.48  4543.5  351.98  4546.8  352.48  5917.7  352.48
  6008.2  353.25  6038.1  356.15  6092.4  359.87  6165.8  361.26  6231.3  367.46
    6328  370.96  6412.9  378.45  6519.5  390.19  6551.4  393.91  6644.8   398.4
#Mann= 7 ,-1 , 0
  3525.6     .12       0  3976.4     .16       0  4532.9     .05       0
  4540.8    .033       0  4546.8     .05       0  5917.7     .16       0
  6519.5     .05       0
Bank Sta=4507.8,6038.1
XS Rating Curve= 0 ,0
Exp/Cntr=0.3,0.1

Type RM Length L Ch R = 1 ,18088   ,371,371,371
BEGIN DESCRIPTION:
MINE CREEK 34.0
END DESCRIPTION:
XS GIS Cut Line= 3
      3706328.19     10752722.32      3704869.84     10753894.21
      3705052.14      10755170.3
#Sta/Elev= 30
  3248.6  413.93  3445.2  391.37  3516.2  378.93  3523.6  376.46    3530  377.05
  3587.6  367.31  3672.4  357.25  3705.6  352.48  3708.4  351.98  3711.6  352.48
  3732.9  352.48  4547.6  352.48    4626  357.64  4683.6  356.24  4725.2  352.48
    5652  352.48  5717.7  356.08  5737.3  357.56  5761.9  359.28    5772  363.15
  5782.1  362.95  5943.7  377.02    5974  376.14  6014.4  379.53  6085.1  381.66
  6135.6  380.96  6176.1  383.61  6277.1  386.41  6314.7  389.24  6408.5   393.7
#Mann= 6 ,-1 , 0
  3248.6     .12       0  3705.6    .033       0  3711.6     .12       0
  3732.9     .05       0  5737.3     .16       0  6314.7     .05       0
Bank Sta=3672.4,5717.7
XS Rating Curve= 0 ,0
Exp/Cntr=0.3,0.1

Type RM Length L Ch R = 1 ,17717   ,327,327,327
BEGIN DESCRIPTION:
MINE CREEK 33.0
END DESCRIPTION:
XS GIS Cut Line= 3
      3706250.06     10752201.49      3704583.38     10753659.84
      3703945.74     10754505.69
#Sta/Elev= 30
  2987.2  411.34  3057.2  407.92  3204.3  390.18  3246.4  383.91  3335.5  371.59
  3388.9  365.09  3461.5  357.59  3531.5  353.67  3595.5  353.94  3624.8  353.84
  3631.4  356.82  3642.7  352.48  3645.4  351.98  3648.7  352.48  5583.1  352.48
  5618.4  356.41  5732.9  364.69  5790.9  363.73  5832.9  368.31  5897.4  369.52
  5932.8   374.2  5941.1  372.43  5947.4  374.85  5976.5  375.88  5982.8  378.53
  6068.1  385.63  6076.4  384.51  6118.1  390.12  6161.8  390.75  6261.1  400.97
#Mann= 9 ,-1 , 0
  2987.2     .16       0  3204.3     .12       0  3246.4     .16       0
  3335.5     .12       0  3388.9     .16       0  3531.5     .12       0
  3595.5     .05       0  3642.7    .033       0  3648.7     .05       0
Bank Sta=3631.4,5618.4
XS Rating Curve= 0 ,0
Exp/Cntr=0.3,0.1

Type RM Length L Ch R = 1 ,17390   ,535,535,535
BEGIN DESCRIPTION:
MINE CREEK 31.0
END DESCRIPTION:
XS GIS Cut Line= 3
      3706099.64     10751660.16      3704549.61     10753260.19
      3703749.63     10753960.17
#Sta/Elev= 30
  2782.2  425.31  2798.2  424.95  2916.6  419.46  2973.2  415.03    3150  391.51
  3398.4  367.06  3436.3  363.66  3553.1  356.04  3571.6  354.53  3571.8  354.51
  3599.7  352.48  3602.4  351.98  3605.7  352.48    3740  352.48  5583.7  352.48
  5605.5  356.18    5634  357.84  5647.7  361.88  5669.1   365.2  5675.7  363.59
    5690  363.78  5697.5  366.78  5704.2  365.63  5732.7  366.81  5740.3  369.71
  5789.6  376.95  5881.7  382.45  5916.8  382.07    5988  391.21  6072.9  396.55
#Mann= 9 ,-1 , 0
  2782.2     .16       0  2798.2     .12       0  3398.4     .16       0
  3436.3     .12       0  3571.6     .16       0  3571.8     .12       0
  3599.7    .033       0  3605.7     .12       0    3740     .05       0
Bank Sta=3553.1,5605.5
XS Rating Curve= 0 ,0
Exp/Cntr=0.3,0.1

Type RM Length L Ch R = 1 ,16855   ,493,493,493
BEGIN DESCRIPTION:
MINE CREEK 30.0
END DESCRIPTION:
XS GIS Cut Line= 3
      3704099.62     10752010.24      3704249.61     10752810.19
      3703849.62     10753610.17
#Sta/Elev= 30
    4157  391.93  4177.3  388.57  4183.2  385.99  4240.9  377.93  4248.5  375.23
  4258.7  374.06  4268.9   371.5    4279  370.66  4288.4  368.47  4299.4  367.36
  4340.1  359.76    4346  357.57    4350  357.51  4360.4   356.5    4388  352.48
  4390.7  351.98    4394  352.48  4450.4  352.48  5605.4  352.48  5619.4   355.4
  5633.3  356.12  5641.7  357.89  5650.1  358.12  5686.4  363.37  5731.2  366.59
  5739.5  368.16  5745.1  367.84  5753.5  369.52    5829  376.71  5865.3  378.47
#Mann= 5 ,-1 , 0
    4157     .05       0    4350     .16       0    4388    .033       0
    4394     .16       0  4450.4     .05       0
Bank Sta=4360.4,5633.3
XS Rating Curve= 0 ,0
Exp/Cntr=0.3,0.1

Type RM Length L Ch R = 1 ,16362   ,522,522,522
BEGIN DESCRIPTION:
MINE CREEK 29.0
END DESCRIPTION:
XS GIS Cut Line= 3
       3704099.6      10751910.2      3703799.61     10752610.19
       3703099.6      10753410.2
#Sta/Elev= 30
  4232.6  401.89  4276.1  399.19  4352.3  390.17    4394  381.08  4428.4  376.01
  4439.3  372.86  4461.1  369.29  4470.1  366.74  4482.8  365.37  4528.2  357.17
  4543.3  352.48    4546  351.98  4549.3  352.48    5710  352.48  5738.3  352.72
  5759.6  357.65  5766.3   359.4  5773.9  359.16  5788.1  361.11    5809  365.77
  5830.8  367.22  5837.5  368.96  5851.7  366.73  5858.3  368.66  5865.9  367.48
  5901.1  372.46  5915.3   375.7  5932.1  376.88  5993.1  384.24  6057.2  387.23
#Mann= 5 ,-1 , 0
  4232.6     .05       0  4543.3    .033       0  4549.3     .05       0
    5710     .16       0  5932.1     .05       0
Bank Sta=4528.2,5759.6
XS Rating Curve= 0 ,0
Exp/Cntr=0.3,0.1

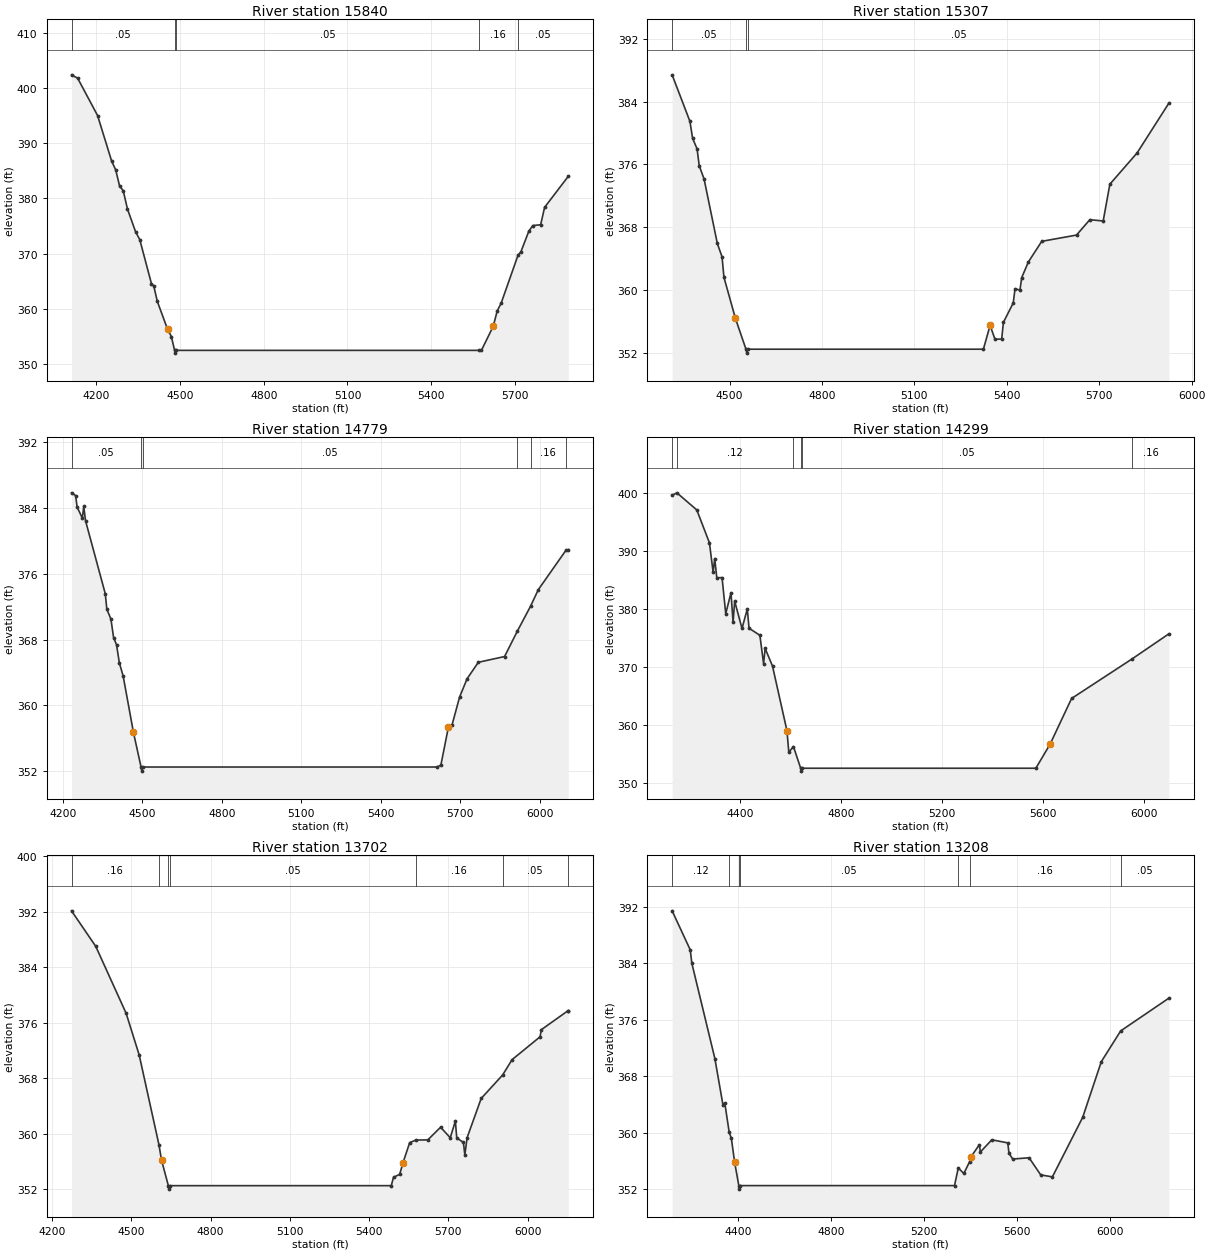
Type RM Length L Ch R = 1 ,15840   ,533,533,533
BEGIN DESCRIPTION:
MINE CREEK 28.0
END DESCRIPTION:
XS GIS Cut Line= 3
      3704049.59      10751860.2      3703349.61     10752360.19
      3702699.64     10753010.16
#Sta/Elev= 30
  4111.5  402.38  4133.6  401.76  4204.9  395.01  4255.3  386.75    4270  385.14
  4283.5  382.29    4297  381.36  4311.8   378.1  4341.3  373.92    4356  372.54
  4397.8  364.57  4406.4  364.11  4418.7  361.37  4455.6   356.3  4469.1  354.99
  4480.8  352.48  4483.6  351.98  4486.8  352.48  5569.4  352.48  5579.8  352.48
  5622.2  356.85  5636.4  359.63  5650.5  361.03  5711.2  369.75  5721.2  370.32
  5749.5  374.05  5763.7  375.08    5792  375.23  5806.1  378.38  5890.9     384
#Mann= 5 ,-1 , 0
  4111.5     .05       0  4480.8    .033       0  4486.8     .05       0
  5569.4     .16       0  5711.2     .05       0
Bank Sta=4455.6,5622.2
XS Rating Curve= 0 ,0
Exp/Cntr=0.3,0.1

Type RM Length L Ch R = 1 ,15307   ,528,528,528
BEGIN DESCRIPTION:
MINE CREEK 27.0
END DESCRIPTION:
XS GIS Cut Line= 3
      3703299.59     10751410.23      3702949.61     10752010.19
      3702499.59     10752810.23
#Sta/Elev= 30
  4313.6  387.41  4371.4  381.48  4380.1  379.32  4394.6  377.98  4401.6  375.83
  4417.3  374.15  4460.3  365.94  4475.6  364.24  4481.8  361.63    4519  356.41
  4553.3  352.48    4556  351.98  4559.3  352.48    5324  352.48  5345.7  355.52
  5361.6  353.74  5383.3  353.78    5389  355.91  5420.9  358.37  5426.6  360.18
  5442.6     360  5448.3  361.59    5470  363.59  5513.3  366.21  5626.2  367.01
  5669.5  368.97  5712.8   368.8  5734.5  373.49  5822.8  377.46  5926.1  383.81
#Mann= 3 ,-1 , 0
  4313.6     .05       0  4553.3    .033       0  4559.3     .05       0
Bank Sta=4519,5345.7
XS Rating Curve= 0 ,0
Exp/Cntr=0.3,0.1

Type RM Length L Ch R = 1 ,14779   ,480,480,480
BEGIN DESCRIPTION:
MINE CREEK 26.0
END DESCRIPTION:
XS GIS Cut Line= 3
      3703299.65     10751360.17      3702599.61     10751610.19
      3701799.62     10752410.18
#Sta/Elev= 30
  4232.3  385.86  4247.7  385.53  4253.6  384.12  4273.2  382.78  4278.5  384.21
  4285.4  382.44  4359.8  373.57  4365.6  371.69    4381   370.5  4391.1  368.24
  4402.2  367.37  4412.9  365.15  4427.2  363.56    4466   356.7  4494.8  352.48
  4497.6  351.98  4500.8  352.48    5612  352.48  5626.2  352.71  5654.5  357.31
  5668.6  357.63  5696.9     361  5725.2  363.23  5767.6  365.23  5866.6  365.93
  5915.1  369.04  5964.6  372.05  5993.9  374.07  6098.1  378.86    6107  378.94
#Mann= 6 ,-1 , 0
  4232.3     .05       0  4494.8    .033       0  4500.8     .05       0
  5915.1      .1       0  5964.6     .16       0  6098.1     .05       0
Bank Sta=4466,5654.5
XS Rating Curve= 0 ,0
Exp/Cntr=0.3,0.1

Type RM Length L Ch R = 1 ,14299   ,597,597,597
BEGIN DESCRIPTION:
MINE CREEK 25.0
END DESCRIPTION:
XS GIS Cut Line= 2
      3702723.07     10750646.55       3701540.3     10752219.97
#Sta/Elev= 30
  4131.9   399.6  4150.9  400.01  4229.7  397.05  4279.7  391.38  4294.3  386.32
  4300.6  388.67  4308.9  385.35  4329.7  385.38  4344.3  379.15  4365.1  382.78
  4373.4  377.66  4379.7  381.32  4408.8   376.6  4429.7  379.96  4436.7  376.64
  4479.7  375.42  4494.2  370.52  4500.5  373.15  4529.6  370.11  4586.8  358.97
  4594.2  355.26  4612.7  356.21  4641.2  352.48  4643.9  351.98  4647.2  352.48
  5573.1  352.48  5629.3  356.61  5714.7  364.52  5953.9  371.33  6100.3  375.68
#Mann= 6 ,-1 , 0
  4131.9     .05       0  4150.9     .12       0  4612.7     .05       0
  4641.2    .033       0  4647.2     .05       0  5953.9     .16       0
Bank Sta=4586.8,5629.3
XS Rating Curve= 0 ,0
Exp/Cntr=0.3,0.1

Type RM Length L Ch R = 1 ,13702   ,494,494,494
BEGIN DESCRIPTION:
MINE CREEK 24.0
END DESCRIPTION:
XS GIS Cut Line= 3
      3702249.64     10750560.16      3701699.61     10751010.19
      3701299.62     10752110.15
#Sta/Elev= 30
  4273.2  392.13  4365.1     387    4480  377.35  4529.5  371.33  4604.2   358.4
  4614.2  356.15  4639.9  352.48  4642.7  351.98  4645.9  352.48    5484  352.48
  5492.6  353.69  5515.9  354.11  5528.5  355.79  5553.8  358.69  5577.2  359.06
  5622.3  359.08  5670.9  360.91  5707.4  359.39  5726.7   361.8    5732  359.37
  5757.3  358.71  5762.6   356.9  5771.3  359.41  5824.5  365.06  5905.8  368.45
  5941.5  370.66  6047.3  373.95  6052.6  374.99  6152.6   377.7  6154.3   377.7
#Mann= 7 ,-1 , 0
  4273.2     .16       0  4604.2     .05       0  4639.9    .033       0
  4645.9     .05       0  5577.2     .16       0  5905.8     .05       0
  6152.6     .16       0
Bank Sta=4614.2,5528.5
XS Rating Curve= 0 ,0
Exp/Cntr=0.3,0.1

Type RM Length L Ch R = 1 ,13208   ,494,494,494
BEGIN DESCRIPTION:
MINE CREEK 23.0
END DESCRIPTION:
XS GIS Cut Line= 3
      3701849.62     10750160.17      3701249.61     10750810.19
      3701149.61     10752060.18
#Sta/Elev= 30
    4117  391.47    4195  385.93  4201.8  384.03    4301  370.51  4336.2  363.86
  4343.6  364.23  4362.6  360.06  4371.9   359.2  4386.1  355.79  4404.1  352.48
  4406.8  351.98  4410.1  352.48  5332.7  352.48  5348.8  354.99  5372.8   354.2
  5397.6  355.87  5402.9  356.53  5439.3  358.27  5444.3  357.26  5493.2  358.98
  5562.1  358.54  5567.2  357.05  5583.5  356.25  5653.7  356.43  5703.8     354
    5754  353.72  5884.4  362.16  5964.7  370.07    6048  374.43  6255.6  379.08
#Mann= 7 ,-1 , 0
    4117     .12       0  4362.6     .05       0  4404.1    .033       0
  4410.1     .05       0  5348.8      .1       0  5397.6     .16       0
    6048     .05       0
Bank Sta=4386.1,5402.9
XS Rating Curve= 0 ,0
Exp/Cntr=0.3,0.1