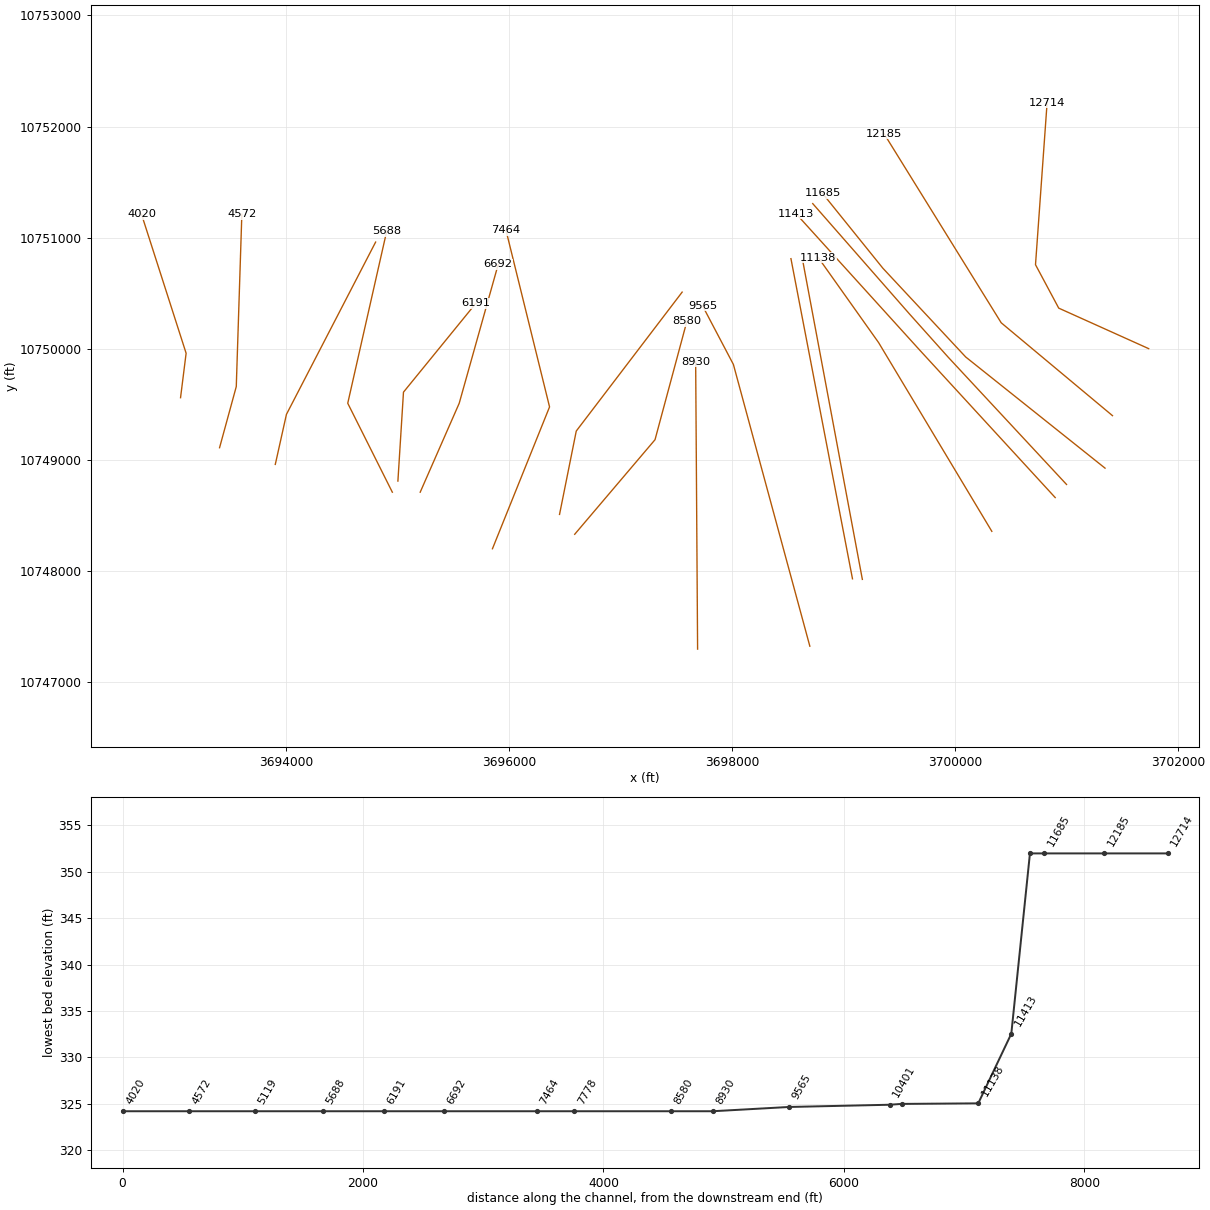
HEC-RAS study MINE CREEK.prj: MINE CREEK Base Level Engineering

--- MINE CREEK.g01 (geometry) --- (continued)

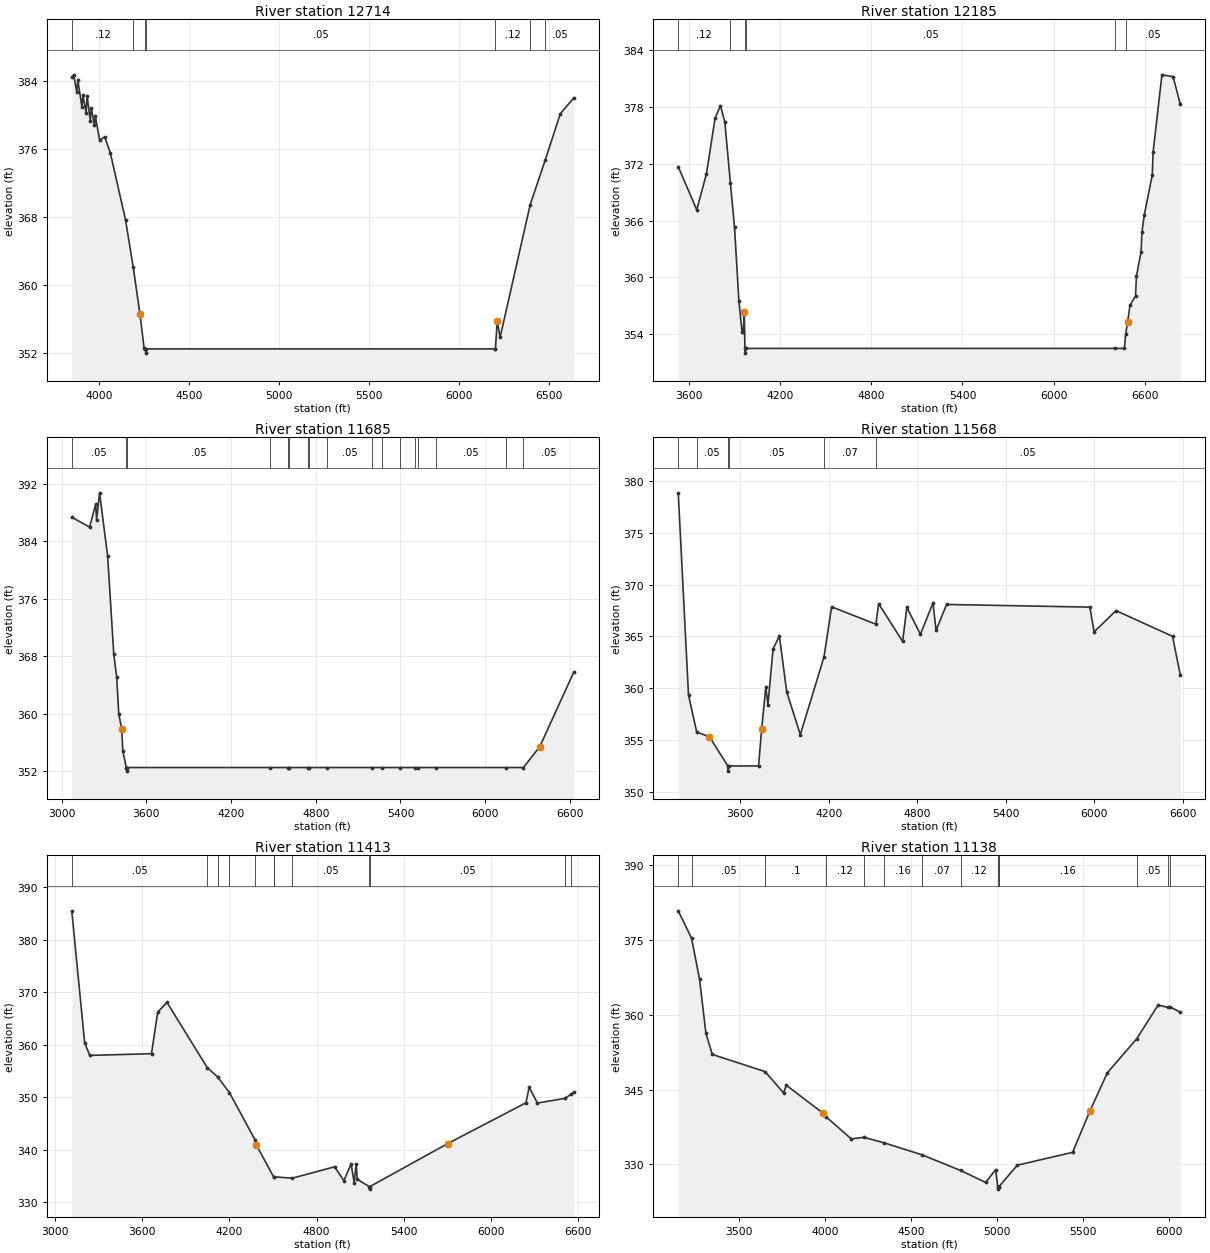
Type RM Length L Ch R = 1 ,12714   ,529,529,529
BEGIN DESCRIPTION:
MINE CREEK 22.0
END DESCRIPTION:
XS GIS Cut Line= 4
      3701735.17      10750001.5      3700927.91     10750366.07
      3700719.57     10750756.69      3700823.74       10752215.
#Sta/Elev= 30
  3848.6  384.43  3858.9  384.69  3876.5  382.66    3882  384.11  3905.1  380.92
  3910.6   382.3  3928.2   380.2  3933.7  382.25  3951.4  379.29  3956.8  380.82
  3974.5  378.77    3980   379.8  4003.1  377.02  4031.7  377.39  4063.2  375.49
  4147.3  367.65  4190.3  362.07  4227.8  356.54  4250.7  352.55  4257.7  352.48
  4260.4  351.98  4263.7  352.48  6199.5  352.48  6203.2  352.48  6213.2  355.75
  6229.2  353.84  6396.6  369.43  6480.1  374.68  6564.1  380.13  6639.1  381.99
#Mann= 7 ,-1 , 0
  3848.6     .12       0  4190.3     .05       0  4257.7    .033       0
  4263.7     .05       0  6199.5     .12       0  6396.6     .16       0
  6480.1     .05       0
Bank Sta=4227.8,6213.2
XS Rating Curve= 0 ,0
Exp/Cntr=0.3,0.1

Type RM Length L Ch R = 1 ,12185   ,500,500,500
BEGIN DESCRIPTION:
MINE CREEK 21.0
END DESCRIPTION:
XS GIS Cut Line= 3
      3701410.12     10749398.75      3700411.85     10750234.26
      3699360.15      10751936.5
#Sta/Elev= 30
  3530.2  371.69    3652  367.13  3715.8  370.95    3773  376.87  3808.2  378.15
  3836.8   376.4  3873.3  369.98  3900.6  365.27  3929.2  357.49    3950  354.22
  3957.8  354.24  3964.3  356.32  3969.1  352.48  3971.9  351.98  3975.1  352.48
  6401.7  352.48  6464.9  352.48  6473.1  353.97  6486.2  355.23  6501.6  357.03
  6538.3  358.02  6544.1  360.09  6574.9  362.72  6580.8  364.79  6596.2  366.61
  6648.2   370.8  6654.1  373.25    6712  381.41  6785.4  381.22  6832.9  378.29
#Mann= 6 ,-1 , 0
  3530.2     .12       0  3873.3     .05       0  3969.1    .033       0
  3975.1     .05       0  6401.7     .16       0  6473.1     .05       0
Bank Sta=3964.3,6486.2
XS Rating Curve= 0 ,0
Exp/Cntr=0.3,0.1

Type RM Length L Ch R = 1 ,11685   ,117,117,117
BEGIN DESCRIPTION:
MINE CREEK 20.0
END DESCRIPTION:
XS GIS Cut Line= 4
      3701343.36     10748926.53      3700093.34     10749926.55
      3699350.28     10750725.16      3698808.63     10751398.75
#Sta/Elev= 30
  3071.9  387.32  3198.1  385.95  3241.3  389.13  3247.7  386.94  3268.8  390.72
  3326.2  381.87  3369.4  368.24  3390.2  365.09  3404.6  359.95  3425.4  357.89
  3433.4   354.8  3457.9  352.48  3460.6  351.98  3463.9  352.48  4473.3  352.48
  4606.7  352.48  4612.5  352.48  4744.8  352.48  4749.9  352.48  4879.2  352.48
  5199.7  352.48  5266.9  352.48  5396.1  352.48  5502.9  352.48  5525.3  352.48
  5654.5  352.48  6148.6  352.48  6270.6  352.48  6385.9  355.37  6627.9  365.78
#Mann= 17 ,-1 , 0
  3071.9     .05       0  3457.9     .03       0  3463.9     .05       0
  4473.3     .07       0  4606.7     .05       0  4612.5     .07       0
  4744.8     .05       0  4749.9     .07       0  4879.2     .05       0
  5199.7     .16       0  5266.9     .05       0  5396.1     .07       0
  5502.9     .05       0  5525.3      .1       0  5654.5     .05       0
  6148.6      .1       0  6270.6     .05       0
Bank Sta=3425.4,6385.9
XS Rating Curve= 0 ,0
Exp/Cntr=0.3,0.1

Type RM Length L Ch R = 1 ,11568   ,155,155,155
BEGIN DESCRIPTION:
MINE CREEK 19.0
END DESCRIPTION:
XS GIS Cut Line= 4
      3700997.86     10748779.84      3699935.35     10749925.68
      3699588.13     10750314.57      3698721.17     10751306.37
#Sta/Elev= 30
    3181  378.86  3250.6  359.33  3306.2  355.75  3392.3   355.3  3516.8  352.48
  3519.6  351.98  3522.8  352.48  3725.1  352.48    3746  356.01  3774.4  360.14
  3788.6  358.39  3823.7   363.8  3866.2  365.03  3916.1  359.63    4008   355.5
  4168.6  363.02    4220  367.85  4519.8  366.17  4538.6  368.15  4701.3  364.51
  4729.7  367.79  4821.6   365.2  4906.9  368.22  4927.8  365.58  4998.9  368.08
  5969.5  367.82    5998  365.43    6147  367.48  6529.5     365  6582.3  361.27
#Mann= 6 ,-1 , 0
    3181     .07       0  3306.2     .05       0  3516.8     .03       0
  3522.8     .05       0  4168.6     .07       0  4519.8     .05       0
Bank Sta=3392.3,3746
XS Rating Curve= 0 ,0
Exp/Cntr=0.3,0.1

Type RM Length L Ch R = 1 ,11413   ,275,275,275
BEGIN DESCRIPTION:
Mapping XS 4ebacf3f
END DESCRIPTION:
XS GIS Cut Line= 3
      3700896.28      10748661.8      3699681.01     10749988.18
      3698570.88     10751216.26
#Sta/Elev= 30
  3115.9  385.52  3204.5  360.39  3239.7     358  3664.5  358.32  3707.1  366.22
  3770.6   368.1  4048.1  355.66  4119.6  353.91    4201  350.89  4376.3  341.95
  4386.6   340.9  4505.4  334.84    4507  334.89  4633.1  334.62  4924.3  336.79
  4987.9  334.15  5037.9  337.34  5058.8   333.8    5073  337.35  5079.8  334.41
  5161.9  333.04  5164.7  332.54  5167.9  333.04    5703  341.22    6241  348.98
  6262.7  351.95  6319.4  348.92  6508.5  349.82  6549.7  350.56  6570.3     351
#Mann= 12 ,-1 , 0
  3115.9     .05       0  4048.1     .12       0  4119.6     .07       0
    4201     .12       0  4376.3     .07       0  4505.4     .05       0
    4507     .07       0  4633.1     .05       0  5161.9     .03       0
  5167.9     .05       0  6508.5     .08       0  6549.7     .05       0
Bank Sta=4386.6,5703
XS Rating Curve= 0 ,0
Exp/Cntr=0.3,0.1

Type RM Length L Ch R = 1 ,11138   ,638,638,638
BEGIN DESCRIPTION:
Mapping XS fd7cd65d
END DESCRIPTION:
XS GIS Cut Line= 3
      3700327.71     10748357.97      3699312.09     10750055.89
      3698770.39     10750821.56
#Sta/Elev= 30
  3146.7  380.84    3224  375.34  3270.6   367.1  3307.6  356.28  3344.5  352.04
  3651.2   348.6  3758.8  344.32  3774.4  345.87  3986.4   340.3  4005.4  339.54
  4151.7  335.11  4225.1  335.42  4340.3  334.34  4563.6   331.9  4786.9  328.77
  4932.1  326.38  4990.4  328.93  5002.6  325.53  5005.4  325.03  5008.6  325.53
  5010.2  325.55  5116.5  329.83  5437.6  332.41  5538.6  340.75  5639.5  348.37
  5809.5  355.16  5933.7  361.92  5992.1  361.48  6001.8  361.61  6063.1  360.51
#Mann= 14 ,-1 , 0
  3146.7     .07       0    3224     .05       0  3651.2      .1       0
  4005.4     .12       0  4225.1     .05       0  4340.3     .16       0
  4563.6     .07       0  4786.9     .12       0  5002.6     .07       0
  5008.6     .12       0  5010.2     .16       0  5809.5     .05       0
  5992.1     .16       0  6001.8     .05       0
Bank Sta=3986.4,5538.6
XS Rating Curve= 0 ,0
Exp/Cntr=0.3,0.1

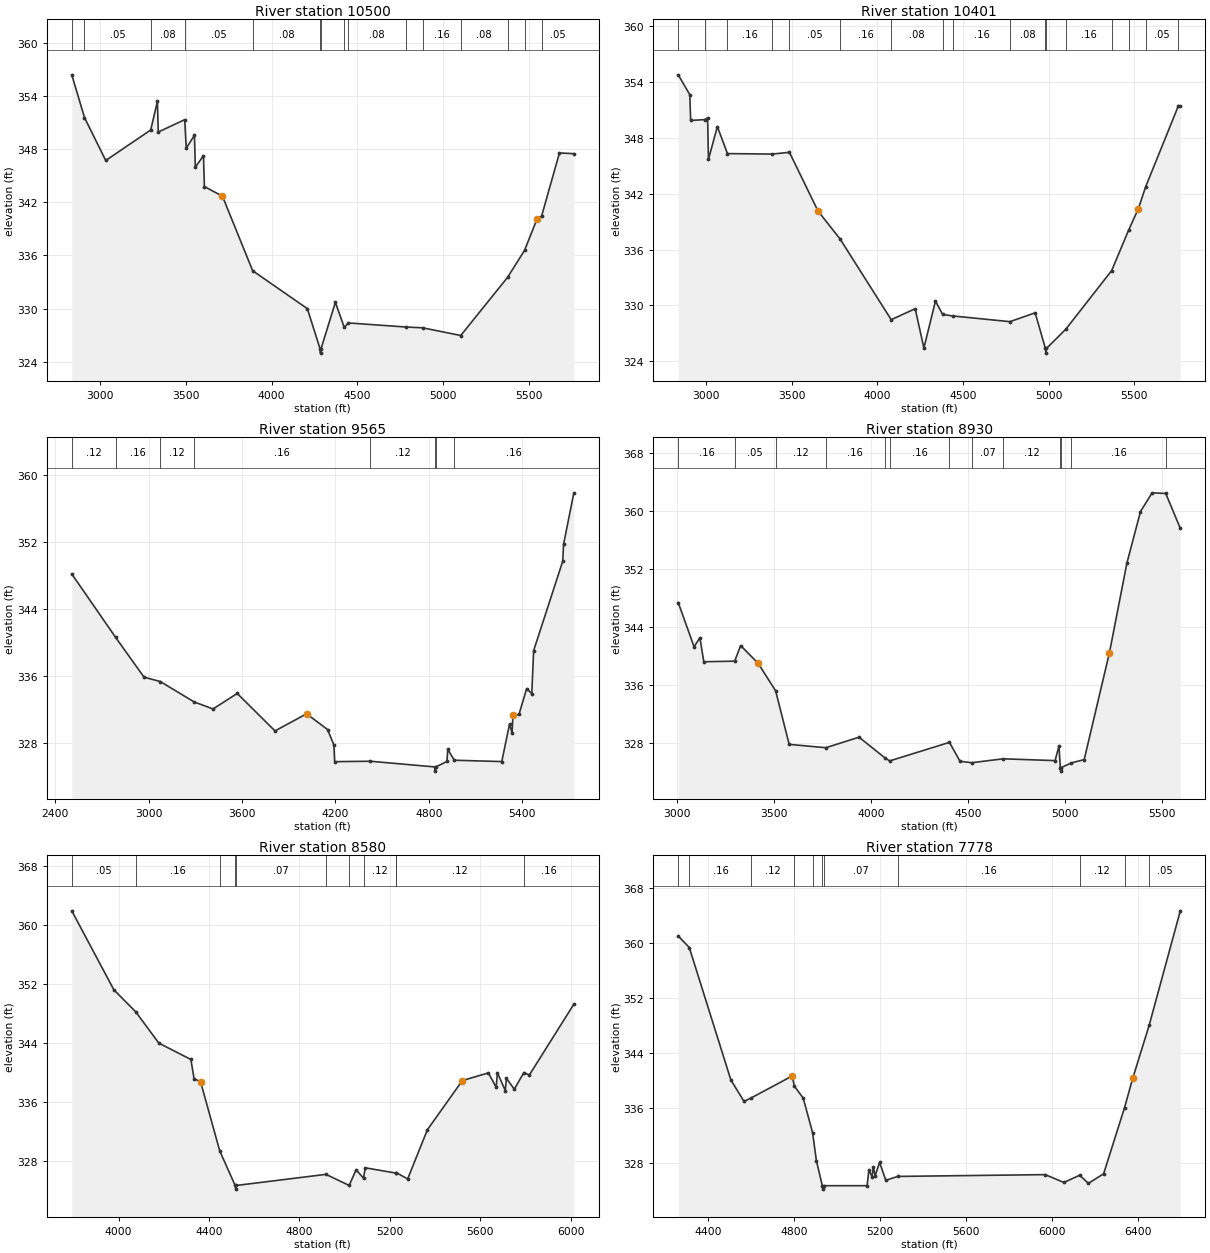
Type RM Length L Ch R = 1 ,10500   ,99,99,99
BEGIN DESCRIPTION:
MINE CREEK 18.0
END DESCRIPTION:
XS GIS Cut Line= 2
      3699166.26     10747925.67       3698629.8     10750800.64
#Sta/Elev= 30
  2835.7  356.39  2909.8  351.57  3033.6  346.72  3295.5  350.16  3334.5  353.39
  3339.6  349.93  3493.5  351.33  3502.7  348.11  3550.4  349.57  3555.4  345.97
    3603  347.26  3608.1  343.78  3713.5  342.68  3889.5  334.27  4208.1  329.99
  4281.8  325.47  4284.6  324.97  4287.8  325.47  4371.2   330.7    4423  327.87
  4446.2  328.38  4780.4  327.92  4879.4  327.83  5101.5  326.96  5374.4  333.53
  5473.4  336.58  5546.2  340.13  5572.4  340.44  5676.5  347.57  5760.3  347.49
#Mann= 15 ,-1 , 0
  2835.7     .08       0  2909.8     .05       0  3295.5     .08       0
  3493.5     .05       0  3889.5     .08       0  4281.8     .07       0
  4287.8     .08       0    4423     .05       0  4446.2     .08       0
  4780.4     .05       0  4879.4     .16       0  5101.5     .08       0
  5374.4     .05       0  5473.4      .1       0  5572.4     .05       0
Bank Sta=3713.5,5546.2
XS Rating Curve= 0 ,0
Exp/Cntr=0.3,0.1

Type RM Length L Ch R = 1 ,10401   ,836,836,836
BEGIN DESCRIPTION:
MINE CREEK 17.0
END DESCRIPTION:
XS GIS Cut Line= 2
       3699077.7     10747930.94      3698525.63      10750811.1
#Sta/Elev= 30
  2836.3  354.77  2903.8  352.64  2908.9  349.87  2990.4  349.96  3007.8  350.14
  3012.9  345.69  3064.9  349.21  3123.7  346.31  3386.7  346.26  3485.8  346.45
  3652.4  340.15  3782.3  337.12  4080.2  328.47  4220.3  329.65  4271.2  325.43
  4338.7  330.47  4380.9  329.03  4440.9  328.87  4773.7  328.26  4921.1  329.21
    4981  325.38  4983.7  324.88    4987  325.38  5099.6  327.44  5368.1  333.75
  5467.2   338.1  5523.6  340.38  5566.3  342.74  5758.3  351.47  5768.9  351.38
#Mann= 17 ,-1 , 0
  2836.3     .08       0  2990.4     .05       0  3123.7     .16       0
  3386.7     .08       0  3485.8     .05       0  3782.3     .16       0
  4080.2     .08       0  4380.9     .05       0  4440.9     .16       0
  4773.7     .08       0    4981     .07       0    4987     .08       0
  5099.6     .16       0  5368.1     .05       0  5467.2     .08       0
  5566.3     .05       0  5758.3     .16       0
Bank Sta=3652.4,5523.6
XS Rating Curve= 0 ,0
Exp/Cntr=0.3,0.1

Type RM Length L Ch R = 1 ,9565    ,635,635,635
BEGIN DESCRIPTION:
MINE CREEK 16.0
END DESCRIPTION:
XS GIS Cut Line= 3
      3698695.13     10747324.62      3698009.35     10749859.39
       3697731.6     10750388.86
#Sta/Elev= 30
  2506.8  348.17    2788  340.61  2970.9  335.85  3075.6  335.33  3292.2   332.9
  3413.8  332.06  3569.2  333.91  3811.7  329.44  4014.7  331.48  4149.4   329.6
  4189.6  327.78  4194.8  325.77  4424.4  325.82  4838.4  325.14  4841.2  324.64
  4844.4  325.14    4916   325.8  4921.1  327.24  4962.7  325.94  5267.8  325.78
  5317.5  330.23  5333.9  329.23  5339.6  331.29    5378   331.4  5427.8  334.49
  5460.6  333.89  5472.4  339.02  5659.1  349.68  5664.8  351.72  5730.6  357.85
#Mann= 8 ,-1 , 0
  2506.8     .12       0    2788     .16       0  3075.6     .12       0
  3292.2     .16       0  4424.4     .12       0  4838.4     .07       0
  4844.4     .12       0  4962.7     .16       0
Bank Sta=4014.7,5339.6
XS Rating Curve= 0 ,0
Exp/Cntr=0.3,0.1

Type RM Length L Ch R = 1 ,8930    ,350,350,350
BEGIN DESCRIPTION:
MINE CREEK 15.0
END DESCRIPTION:
XS GIS Cut Line= 2
      3697688.17      10747298.6      3697670.81     10749885.34
#Sta/Elev= 30
  3007.6  347.44  3089.2  341.33  3119.2  342.59  3139.2  339.27  3298.4  339.35
  3329.2   341.5  3419.2  339.06  3509.4  335.26  3579.2  327.87  3768.1  327.41
  3939.2  328.86  4071.1  326.04  4096.9  325.59    4405  328.15  4459.2  325.54
  4519.3  325.34  4681.6  325.88  4949.2  325.63  4969.2  327.65  4976.2  324.68
    4979  324.18  4982.2  324.68  5032.7  325.31  5099.2  325.77  5229.2  340.51
  5319.2  352.87  5389.2  359.99  5449.2  362.57  5519.4  362.48  5594.4  357.67
#Mann= 13 ,-1 , 0
  3007.6     .16       0  3298.4     .05       0  3509.4     .12       0
  3768.1     .16       0  4071.1     .12       0  4096.9     .16       0
    4405     .12       0  4519.3     .07       0  4681.6     .12       0
  4976.2     .07       0  4982.2     .12       0  5032.7     .16       0
  5519.4     .12       0
Bank Sta=3419.2,5229.2
XS Rating Curve= 0 ,0
Exp/Cntr=0.3,0.1

Type RM Length L Ch R = 1 ,8580    ,802,802,802
BEGIN DESCRIPTION:
MINE CREEK 14.0
END DESCRIPTION:
XS GIS Cut Line= 3
      3696585.76     10748331.63      3697306.23      10749182.3
      3697592.67     10750249.97
#Sta/Elev= 30
  3793.1  361.88  3979.1  351.19  4076.7  348.17    4178  343.96  4319.7  341.75
    4334  339.14  4362.5  338.74  4447.5  329.35  4515.5  324.68  4518.3  324.18
  4521.5  324.68  4917.1  326.18  5019.6  324.68  5050.6   326.8  5083.3  325.66
  5090.7  327.07  5225.3  326.36  5228.5  326.41  5278.4  325.56  5365.6  332.22
  5520.4  338.89  5635.2  339.92  5670.1  337.98  5675.2  339.96  5710.1  337.53
  5715.2  339.19  5750.1  337.72  5792.1  339.96  5816.8  339.65  6013.3  349.23
#Mann= 11 ,-1 , 0
  3793.1     .05       0  4076.7     .16       0  4447.5     .07       0
  4515.5     .07       0  4521.5     .07       0  4917.1     .12       0
  5019.6     .07       0  5083.3     .12       0  5225.3     .07       0
  5228.5     .12       0  5792.1     .16       0
Bank Sta=4362.5,5520.4
XS Rating Curve= 0 ,0
Exp/Cntr=0.3,0.1

Type RM Length L Ch R = 1 ,7778    ,314,314,314
BEGIN DESCRIPTION:
MINE CREEK 13.0
END DESCRIPTION:
XS GIS Cut Line= 3
       3696449.6     10748510.16      3696599.61     10749260.19
       3697549.6     10750510.18
#Sta/Elev= 30
  4262.1  361.02  4313.5  359.35  4506.9  340.07  4568.1  336.95  4602.8  337.48
  4792.4  340.66  4801.9  339.18  4843.4  337.42  4886.8  332.42  4904.6  328.32
  4932.2  324.68  4934.9  324.18  4938.2  324.68  5140.4  324.68  5148.6  326.96
  5163.2     326  5169.4  327.42  5177.7  326.11  5198.5  328.07  5227.6  325.46
  5282.7  326.03    5969  326.29  6055.3  325.15    6129   326.2  6169.6  325.02
  6240.4  326.42  6337.6  336.04  6375.6   340.3  6451.9     348    6597  364.69
#Mann= 11 ,-1 , 0
  4262.1     .05       0  4313.5     .16       0  4602.8     .12       0
  4801.9     .16       0  4886.8     .07       0  4932.2     .07       0
  4938.2     .07       0  5282.7     .16       0    6129     .12       0
  6337.6     .16       0  6451.9     .05       0
Bank Sta=4792.4,6375.6
XS Rating Curve= 0 ,0
Exp/Cntr=0.3,0.1

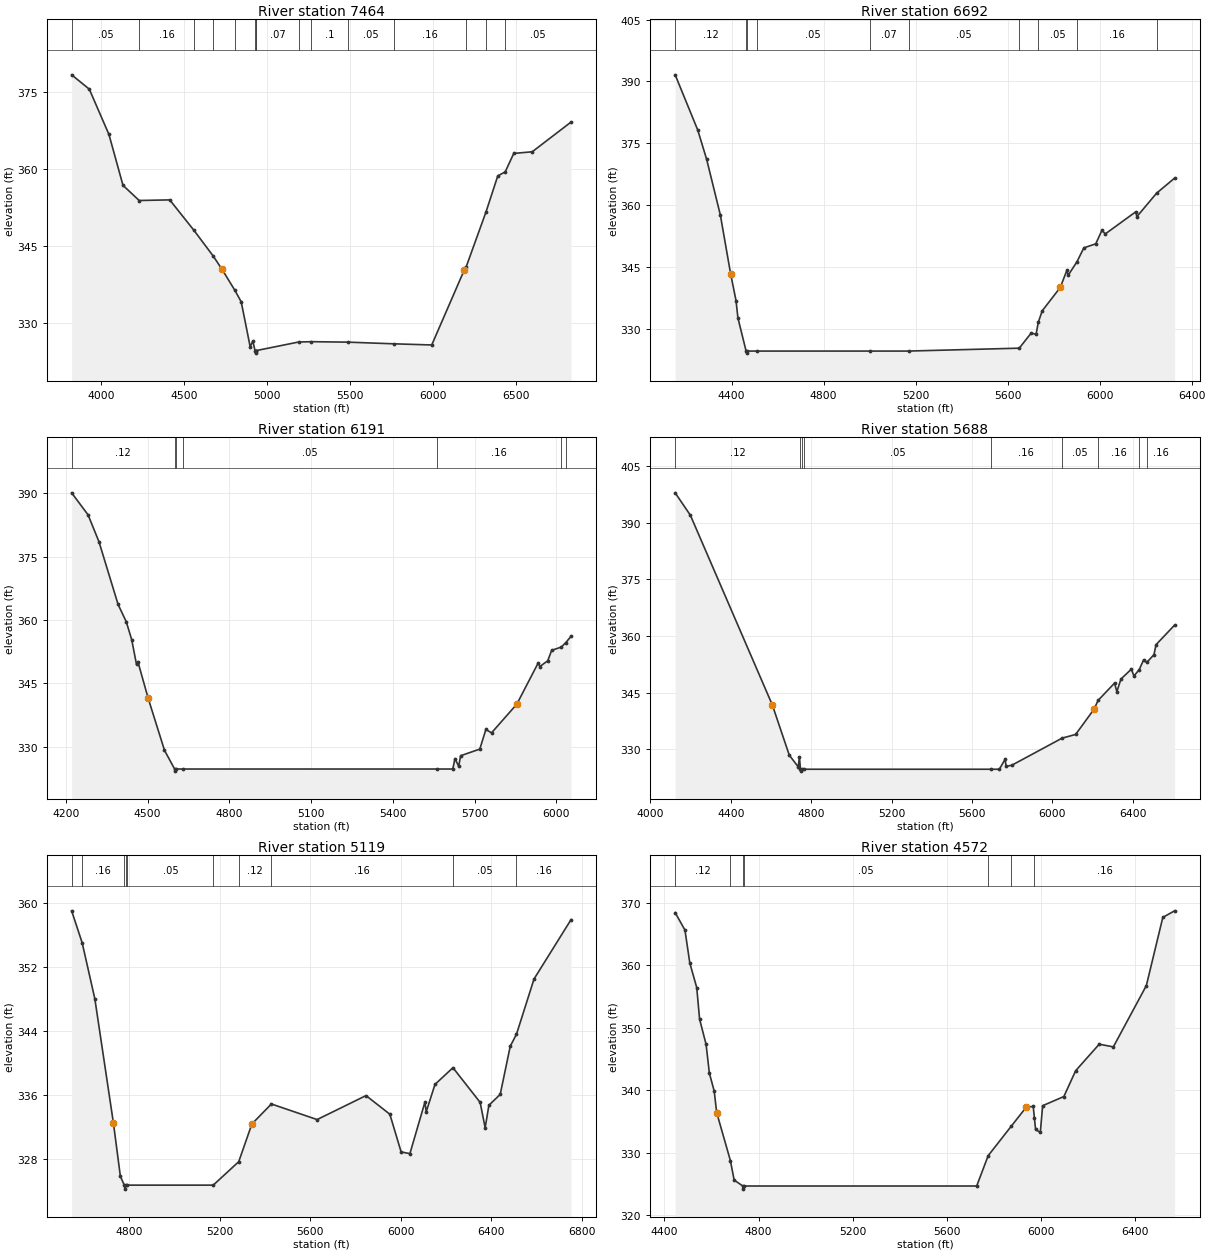
Type RM Length L Ch R = 1 ,7464    ,772,772,772
BEGIN DESCRIPTION:
MINE CREEK 12.0
END DESCRIPTION:
XS GIS Cut Line= 3
      3695847.91     10748201.44      3696360.05     10749477.44
      3695969.52     10751065.59
#Sta/Elev= 30
  3822.8  378.39  3929.2   375.6  4047.7  366.77  4132.3  356.87  4229.8  353.91
  4414.1  354.03  4560.8  348.07  4676.4  343.08  4729.4   340.5  4807.4  336.38
  4845.1  334.16    4899  325.43  4914.9  326.51  4928.3  324.68  4931.1  324.18
  4934.3  324.68  4936.5  324.68  5190.3  326.34  5268.3  326.41  5486.1  326.32
  5768.2  325.99  5993.5  325.77  6189.2  340.35  6199.6  340.86  6320.5  351.68
  6391.5   358.7  6436.4  359.49  6487.8  363.08  6599.2   363.4  6833.2  369.19
#Mann= 15 ,-1 , 0
  3822.8     .05       0  4229.8     .16       0  4560.8     .12       0
  4676.4     .16       0  4807.4     .12       0  4928.3     .07       0
  4934.3     .12       0  4936.5     .07       0  5190.3     .12       0
  5268.3      .1       0  5486.1     .05       0  5768.2     .16       0
  6199.6     .05       0  6320.5     .16       0  6436.4     .05       0
Bank Sta=4729.4,6189.2
XS Rating Curve= 0 ,0
Exp/Cntr=0.3,0.1

Type RM Length L Ch R = 1 ,6692    ,501,501,501
BEGIN DESCRIPTION:
MINE CREEK 11.0
END DESCRIPTION:
XS GIS Cut Line= 3
      3695199.63     10748710.23      3695549.61     10749510.19
       3695899.6     10750760.15
#Sta/Elev= 30
  4154.7  391.61  4252.9  378.22  4291.5  371.14  4351.1  357.65    4396  343.33
  4419.3  336.89  4427.5   332.7  4463.1  324.68  4465.9  324.18  4469.1  324.68
  4508.5  324.68  5001.1  324.68  5169.1  324.68  5650.6  325.38  5702.9  329.07
  5723.6  328.72  5733.5  331.66  5750.3  334.42    5829   340.1  5857.9  344.29
  5863.1  343.03  5901.1  346.28  5931.3  349.68  5983.2  350.67    6010  353.93
  6024.8  353.07  6156.8  358.41    6162  357.25  6247.4  362.92  6325.9  366.58
#Mann= 10 ,-1 , 0
  4154.7     .12       0  4463.1    .033       0  4469.1     .12       0
  4508.5     .05       0  5001.1     .07       0  5169.1     .05       0
  5650.6     .16       0  5733.5     .05       0  5901.1     .16       0
  6247.4     .05       0
Bank Sta=4396,5829
XS Rating Curve= 0 ,0
Exp/Cntr=0.3,0.1

Type RM Length L Ch R = 1 ,6191    ,503,503,503
BEGIN DESCRIPTION:
MINE CREEK 10.0
END DESCRIPTION:
XS GIS Cut Line= 3
      3694999.61     10748810.15      3695049.61     10749610.19
      3695699.62      10750410.2
#Sta/Elev= 30
  4221.3  390.12  4281.5  384.91  4321.5  378.55  4391.7  363.68  4421.7  359.58
  4441.8   355.3  4459.3  349.45  4464.3  350.13  4501.9  341.49    4562  329.11
  4599.1  324.68  4601.8  324.18  4605.1  324.68  4630.9  324.68  5562.4  324.68
  5619.8  324.68  5627.7  327.15  5641.4  325.34  5648.6  327.83  5718.9   329.4
  5741.2  334.05    5762  333.25  5854.7  340.05    5933  349.79  5939.5  348.97
  5968.2  350.33  5982.6   352.8    6018  353.58  6034.5  354.64  6053.7  356.13
#Mann= 7 ,-1 , 0
  4221.3     .12       0  4599.1    .033       0  4605.1     .12       0
  4630.9     .05       0  5562.4     .16       0    6018     .05       0
  6034.5     .16       0
Bank Sta=4501.9,5854.7
XS Rating Curve= 0 ,0
Exp/Cntr=0.3,0.1

Type RM Length L Ch R = 1 ,5688    ,569,569,569
BEGIN DESCRIPTION:
MINE CREEK 9.0
END DESCRIPTION:
XS GIS Cut Line= 3
       3694949.6      10748710.2      3694549.61     10749510.19
       3694899.6     10751060.15
#Sta/Elev= 30
  4123.8   397.9  4199.3  391.97  4607.3  341.66  4691.2  328.41  4735.9   325.3
  4741.5  327.99  4746.9  324.68  4749.6  324.18  4752.9  324.68  4766.2  324.68
  5692.2  324.68  5735.8  324.68  5764.4  327.31  5769.5  325.44  5797.3  325.73
  6047.9  332.92  6115.2   333.9  6207.4  340.64  6226.4  342.89  6308.5  347.49
  6320.2  345.24  6340.7  348.59    6392  351.18  6405.1  349.39  6431.3  351.06
  6453.5  353.68  6468.7  352.96  6504.7  355.04    6515  357.68  6607.2  362.86
#Mann= 9 ,-1 , 0
  4123.8     .12       0  4746.9    .033       0  4752.9     .12       0
  4766.2     .05       0  5692.2     .16       0  6047.9     .05       0
  6226.4     .16       0  6431.3     .05       0  6468.7     .16       0
Bank Sta=4607.3,6207.4
XS Rating Curve= 0 ,0
Exp/Cntr=0.3,0.1

Type RM Length L Ch R = 1 ,5119    ,547,547,547
BEGIN DESCRIPTION:
MINE CREEK 8.0
END DESCRIPTION:
XS GIS Cut Line= 3
       3693899.6     10748960.16      3693999.61     10749410.19
      3694799.61      10750960.2
#Sta/Elev= 30
    4547  358.99  4593.5  354.99  4649.5  347.98  4731.4  332.47  4762.2  325.78
  4779.6  324.68  4782.4  324.18  4785.6  324.68  4793.4  324.68  5172.3  324.68
  5284.8  327.61    5343  332.33  5429.1  334.83    5631  332.88  5846.9  335.88
  5952.1  333.55    6002  328.83  6040.7  328.62  6107.2  335.08  6112.8  333.86
  6151.5  337.28  6230.8  339.37  6350.9  335.03    6373  331.85  6389.5  334.67
  6439.5  336.03  6483.8  342.05  6511.4  343.56  6588.9  350.47  6752.3  357.89
#Mann= 10 ,-1 , 0
    4547     .05       0  4593.5     .16       0  4779.6    .033       0
  4785.6     .16       0  4793.4     .05       0  5172.3     .16       0
  5284.8     .12       0  5429.1     .16       0  6230.8     .05       0
  6511.4     .16       0
Bank Sta=4731.4,5343
XS Rating Curve= 0 ,0
Exp/Cntr=0.3,0.1

Type RM Length L Ch R = 1 ,4572    ,552,552,552
BEGIN DESCRIPTION:
MINE CREEK 7.0
END DESCRIPTION:
XS GIS Cut Line= 3
       3693399.6     10749110.15      3693549.61     10749660.19
      3693599.61     10751210.16
#Sta/Elev= 30
  4445.6  368.46  4487.1  365.67  4507.8  360.39  4537.2  356.45  4549.3   351.4
  4576.9  347.36  4590.7  342.77  4611.5  339.86  4621.8  336.45    4680  328.76
  4696.1  325.63  4732.9  324.68  4735.6  324.18  4738.9  324.68  5726.1  324.68
  5774.9  329.54  5873.1  334.27  5936.2  337.29  5966.2  337.42  5971.3  335.54
  5976.2  333.73  5996.2  333.26  6006.2  337.54  6096.3  339.01  6146.3  343.14
  6246.4  347.39  6306.4  346.96  6446.5  356.77  6516.5   367.7  6566.5  368.75
#Mann= 7 ,-1 , 0
  4445.6     .12       0    4680     .05       0  4732.9    .033       0
  4738.9     .05       0  5774.9     .16       0  5873.1     .12       0
  5971.3     .16       0
Bank Sta=4621.8,5936.2
XS Rating Curve= 0 ,0
Exp/Cntr=0.3,0.1

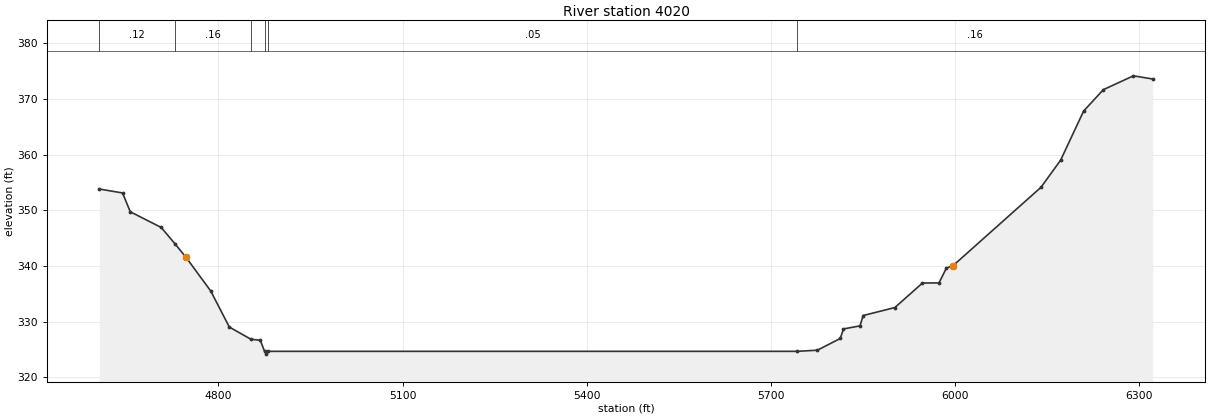
Type RM Length L Ch R = 1 ,4020    ,526,526,526
BEGIN DESCRIPTION:
MINE CREEK 6.0
END DESCRIPTION:
XS GIS Cut Line= 3
       3693049.6     10749560.15      3693099.61     10749960.19
      3692699.61     10751210.19
#Sta/Elev= 30
  4606.1  353.81  4643.9   353.1  4656.5  349.72  4706.9  346.91  4729.4  343.96
  4747.2  341.56  4787.5  335.51  4817.8  329.04  4853.1  326.84  4868.2  326.67
  4875.2  324.68    4878  324.18  4881.2  324.68  5741.8  324.68  5775.4  324.88
  5812.8  326.99    5818   328.7  5844.9  329.25  5850.2  331.11  5901.7  332.54
  5946.7  336.94  5973.6  336.96  5985.7  339.63  5996.2  340.03  6139.6  354.11
  6171.7  358.99  6209.2  367.81  6241.3  371.64  6290.2  374.12  6321.7  373.55
#Mann= 6 ,-1 , 0
  4606.1     .12       0  4729.4     .16       0  4853.1     .05       0
  4875.2    .033       0  4881.2     .05       0  5741.8     .16       0
Bank Sta=4747.2,5996.2
XS Rating Curve= 0 ,0
Exp/Cntr=0.3,0.1