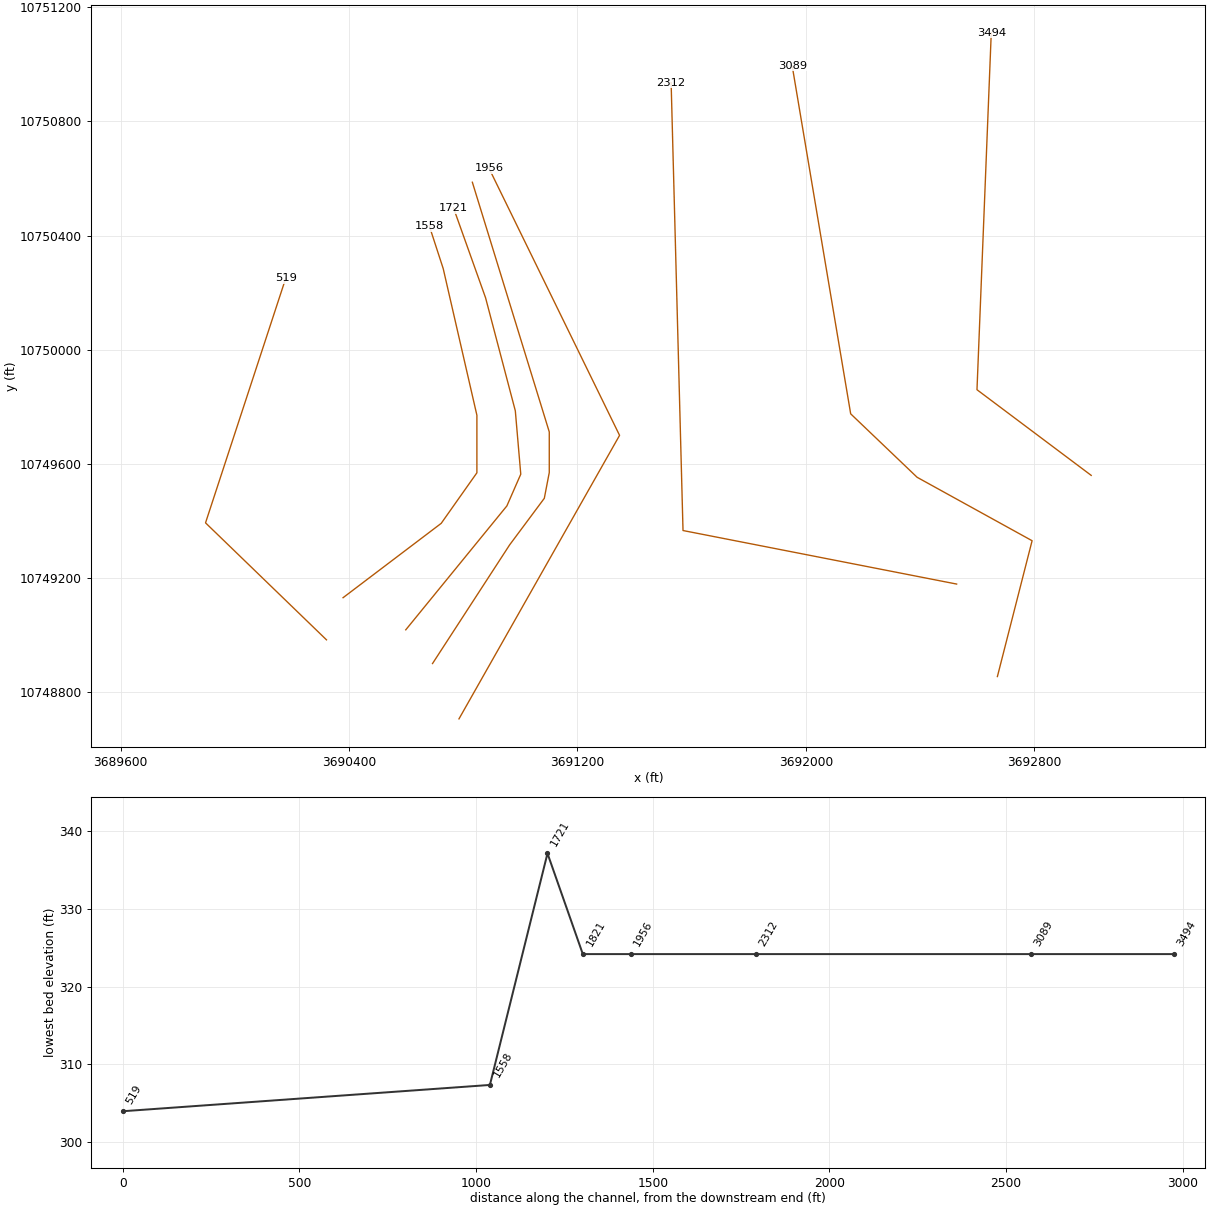
HEC-RAS study MINE CREEK.prj: MINE CREEK Base Level Engineering

--- MINE CREEK.g01 (geometry) --- (continued)

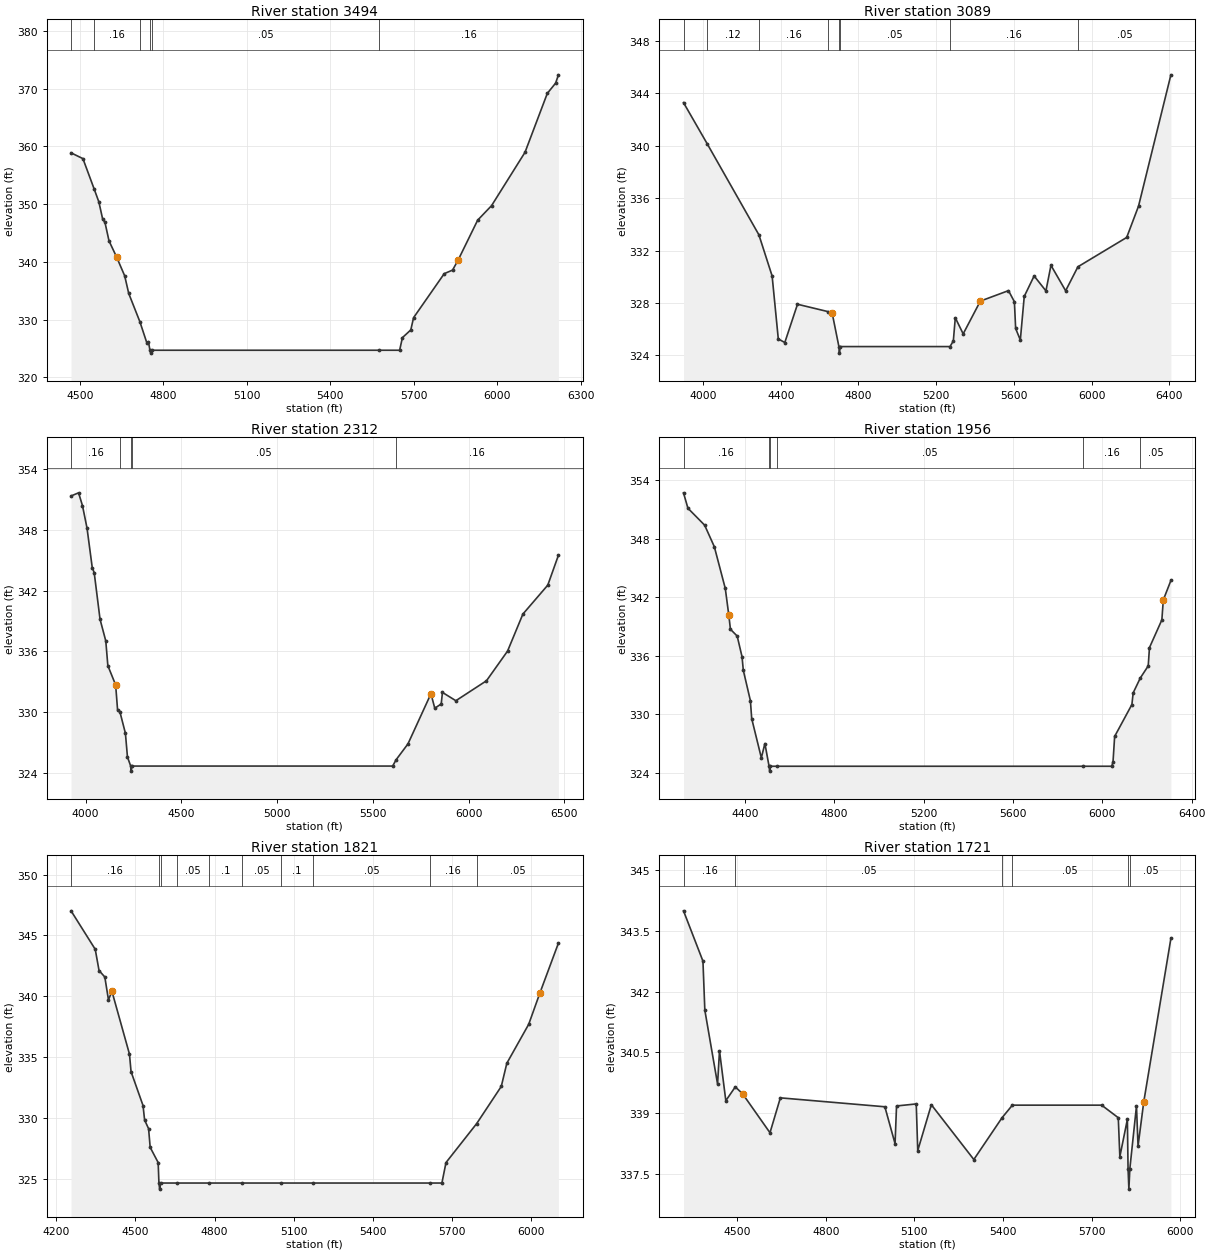
Type RM Length L Ch R = 1 ,3494    ,405,405,405
BEGIN DESCRIPTION:
MINE CREEK 5.0
END DESCRIPTION:
XS GIS Cut Line= 3
       3692999.6      10749560.2      3692599.61     10749860.19
      3692649.61      10751110.2
#Sta/Elev= 30
  4468.1  358.86  4510.8  357.86  4551.7  352.53  4568.1  350.36  4581.6  347.41
    4590  346.81  4604.5  343.62  4631.6  340.84  4660.8  337.57  4675.4  334.51
  4715.4  329.62    4740  326.02  4746.2  326.17  4751.5  324.68  4754.3  324.18
  4757.5  324.68  5575.7  324.68  5648.6  324.68  5658.6  326.86  5688.7   328.2
  5698.7  330.32  5808.8  337.94  5838.8  338.56  5858.8   340.3  5928.9   347.2
  5978.9  349.72    6099  358.95  6179.1  369.15  6209.1  370.94  6219.1  372.37
#Mann= 6 ,-1 , 0
  4468.1     .12       0  4551.7     .16       0  4715.4     .05       0
  4751.5    .033       0  4757.5     .05       0  5575.7     .16       0
Bank Sta=4631.6,5858.8
XS Rating Curve= 0 ,0
Exp/Cntr=0.3,0.1

Type RM Length L Ch R = 1 ,3089    ,777,777,777
BEGIN DESCRIPTION:
Mapping XS de168af9
END DESCRIPTION:
XS GIS Cut Line= 5
      3692671.11     10748855.56      3692792.64     10749331.28
      3692389.87      10749553.5      3692157.23     10749775.73
      3691952.36      10750994.5
#Sta/Elev= 30
  3899.4   343.3    4022  340.14  4287.4  333.21  4355.5  330.07  4387.3  325.26
  4420.8  324.99  4486.1  327.91  4642.7  327.35  4664.9  327.21  4699.2  324.68
    4702  324.18  4705.2  324.68  5271.1  324.68  5288.2  325.11  5298.3  326.88
  5338.9  325.65  5427.2  328.15  5572.1  328.95  5602.5   328.1  5608.9  326.06
    5633  325.18  5653.2  328.51    5704  330.07  5764.8  328.93  5790.7  330.88
  5866.2  328.94  5929.4  330.77  6180.5  333.01  6241.4   335.4    6408  345.42
#Mann= 8 ,-1 , 0
  3899.4     .16       0    4022     .12       0  4287.4     .16       0
  4642.7     .05       0  4699.2    .033       0  4705.2     .05       0
  5271.1     .16       0  5929.4     .05       0
Bank Sta=4664.9,5427.2
XS Rating Curve= 0 ,0
Exp/Cntr=0.3,0.1

Type RM Length L Ch R = 1 ,2312    ,356,356,356
BEGIN DESCRIPTION:
MINE CREEK 4.0
END DESCRIPTION:
XS GIS Cut Line= 3
      3692528.32     10749179.49      3691569.97     10749366.99
      3691528.32     10750935.81
#Sta/Elev= 30
  3923.7  351.34  3963.1  351.65  3983.5  350.38  4007.2  348.17  4034.5  344.27
  4044.7  343.77  4075.2  339.17  4105.2  337.03    4116  334.59  4156.7  332.69
  4166.9   330.2  4178.6  330.06  4207.7  327.92  4218.4  325.58  4235.3  324.68
    4238  324.18  4241.3  324.68  5603.7  324.68    5622  325.31  5683.7  326.87
  5803.7  331.82  5823.7  330.39  5857.3  330.81  5863.8  331.95  5933.8  331.13
  6093.8   333.1  6203.9  336.03  6283.9  339.68    6414  342.54  6469.6  345.49
#Mann= 5 ,-1 , 0
  3923.7     .16       0  4178.6     .05       0  4235.3    .033       0
  4241.3     .05       0    5622     .16       0
Bank Sta=4156.7,5803.7
XS Rating Curve= 0 ,0
Exp/Cntr=0.3,0.1

Type RM Length L Ch R = 1 ,1956    ,135,135,135
BEGIN DESCRIPTION:
MINE CREEK 3.0
END DESCRIPTION:
XS GIS Cut Line= 3
      3690785.26     10748707.29      3691347.75     10749700.32
      3690890.04     10750636.55
#Sta/Elev= 30
  4123.6  352.72  4143.4  351.14  4218.4   349.4  4261.7  347.19  4310.8  342.91
  4326.6  340.16  4333.8  338.73  4364.1  338.03  4385.8  335.91  4391.5  334.52
  4423.3   331.4  4429.1  329.57  4472.3  325.54  4488.2  327.01  4506.9  324.68
  4509.6  324.18  4512.9  324.68  4540.4  324.68  5915.2  324.68  6042.2  324.68
  6047.8  325.16    6055  327.74  6132.3  331.01  6137.9   332.2  6169.9  333.73
  6205.4  334.97    6211  336.85  6266.5  339.69    6273  341.74    6307  343.73
#Mann= 6 ,-1 , 0
  4123.6     .16       0  4506.9    .033       0  4512.9     .16       0
  4540.4     .05       0  5915.2     .16       0  6169.9     .05       0
Bank Sta=4326.6,6273
XS Rating Curve= 0 ,0
Exp/Cntr=0.3,0.1

Type RM Length L Ch R = 1 ,1821    ,100,100,100
BEGIN DESCRIPTION:
Mapping XS 4dcee2f5
END DESCRIPTION:
XS GIS Cut Line= 6
      3690692.65     10748901.17      3690962.62     10749316.64
      3691084.15     10749479.84      3691101.51     10749570.11
      3691101.51     10749712.48       3690832.1     10750586.91
#Sta/Elev= 30
  4255.6  347.02  4347.4  343.86  4361.8  342.12  4383.7  341.59  4397.5  339.72
  4410.7  340.41  4477.2  335.26  4483.2  333.82  4528.6  331.04  4534.6  329.85
  4549.7  329.14  4555.7  327.61    4586  326.36  4588.9  324.68  4591.7  324.18
  4594.9  324.68  4656.8  324.68    4778  324.68  4903.8  324.68  5050.6  324.68
  5172.8  324.68  5616.9  324.68    5662  324.68  5677.5  326.36  5793.9  329.56
  5887.2  332.61  5908.2  334.51  5991.2  337.71    6034   340.3  6103.9  344.37
#Mann= 10 ,-1 , 0
  4255.6     .16       0  4588.9    .033       0  4594.9     .16       0
  4656.8     .05       0    4778      .1       0  4903.8     .05       0
  5050.6      .1       0  5172.8     .05       0  5616.9     .16       0
  5793.9     .05       0
Bank Sta=4410.7,6034
XS Rating Curve= 0 ,0
Exp/Cntr=0.3,0.1

Type RM Length L Ch R = 1 ,1721    ,163,163,163
BEGIN DESCRIPTION:
Mapping XS a8c0d1e9
END DESCRIPTION:
XS GIS Cut Line= 6
      3690598.92     10749019.24      3690953.07     10749453.25
      3691001.68     10749564.36      3690982.59     10749786.26
      3690878.42     10750182.09      3690766.15     10750496.79
#Sta/Elev= 30
  4318.5  343.99  4384.3  342.75  4390.7  341.54  4433.8  339.72  4440.3  340.54
  4461.7  339.31  4493.8  339.65  4518.5  339.48  4611.2  338.52  4646.3  339.38
    5000  339.16  5034.5  338.25  5039.5  339.18  5106.2  339.23  5111.3  338.08
  5157.3  339.21  5301.1  337.86  5396.6  338.89  5431.6   339.2  5733.7   339.2
    5790  338.89  5795.3  337.93  5820.8  338.85  5823.1  337.63  5825.9  337.13
  5829.1  337.63  5851.6  339.18  5856.9  338.19  5876.2  339.28  5968.1  343.31
#Mann= 6 ,-1 , 0
  4318.5     .16       0  4493.8     .05       0  5396.6     .16       0
  5431.6     .05       0  5823.1     .03       0  5829.1     .05       0
Bank Sta=4518.5,5876.2
XS Rating Curve= 0 ,0
Exp/Cntr=0.3,0.1

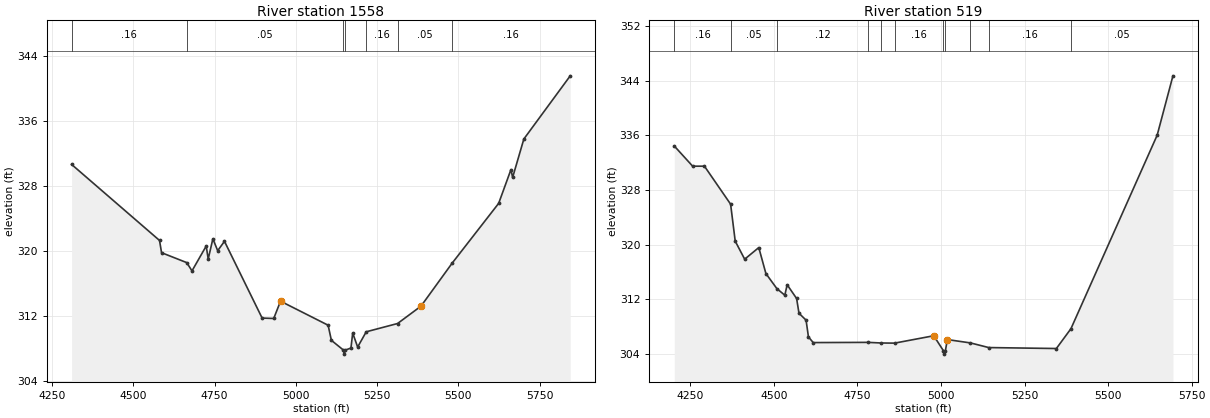
Type RM Length L Ch R = 1 ,1558    ,1039,1039,1039
BEGIN DESCRIPTION:
MINE CREEK 2.0
END DESCRIPTION:
XS GIS Cut Line= 6
      3690379.26     10749131.73      3690723.04     10749392.16
      3690848.04     10749569.25      3690848.04     10749770.64
      3690729.98     10750284.52      3690681.38      10750433.8
#Sta/Elev= 30
  4310.2  330.71  4580.6  321.35  4586.9  319.84  4664.3  318.62  4680.5   317.6
  4724.2  320.66  4730.4  319.06  4744.7  321.55  4759.5  320.09  4780.4  321.24
  4896.2  311.79  4931.9  311.74  4952.8  313.87  5099.2  310.91  5109.2  309.05
  5146.2  307.85  5148.9  307.35  5152.2  307.85  5169.4   308.1  5174.8  309.95
    5190  308.22  5216.4   310.1  5312.8  311.12  5384.9  313.26  5480.8  318.56
  5623.8  325.92  5661.5  330.07  5666.7  329.11  5701.2  333.84  5843.9  341.62
#Mann= 7 ,-1 , 0
  4310.2     .16       0  4664.3     .05       0  5146.2     .03       0
  5152.2     .05       0  5216.4     .16       0  5312.8     .05       0
  5480.8     .16       0
Bank Sta=4952.8,5384.9
XS Rating Curve= 0 ,0
Exp/Cntr=0.3,0.1

Type RM Length L Ch R = 1 ,519     ,0,0,0
BEGIN DESCRIPTION:
MINE CREEK 1.0
END DESCRIPTION:
XS GIS Cut Line= 3
      3690321.15     10748984.15      3689897.52      10749393.9
      3690178.78     10750251.58
#Sta/Elev= 30
    4202  334.42  4256.9  331.47  4292.2  331.47  4370.5  325.91  4384.3   320.5
  4412.6  317.86  4454.8  319.56  4476.1  315.76    4509  313.55  4532.7  312.59
  4539.7  314.12    4568  312.11  4575.1  309.95  4596.3  308.94  4603.4  306.49
  4617.6  305.66  4782.2  305.69    4821   305.6  4861.3  305.58  4978.4  306.66
  5007.2  304.47    5010  303.97  5013.2  304.47    5019   306.1  5088.1  305.61
  5142.9  304.93  5345.2  304.79  5388.8  307.69  5646.8     336    5694  344.69
#Mann= 11 ,-1 , 0
    4202     .16       0  4370.5     .05       0    4509     .12       0
  4782.2     .16       0    4821     .12       0  4861.3     .16       0
  5007.2     .07       0  5013.2     .16       0  5088.1     .12       0
  5142.9     .16       0  5388.8     .05       0
Bank Sta=4978.4,5019
XS Rating Curve= 0 ,0
Exp/Cntr=0.3,0.1

Chan Stop Cuts=-1
Use User Specified Reach Order=0
Composite Channel Slope=5