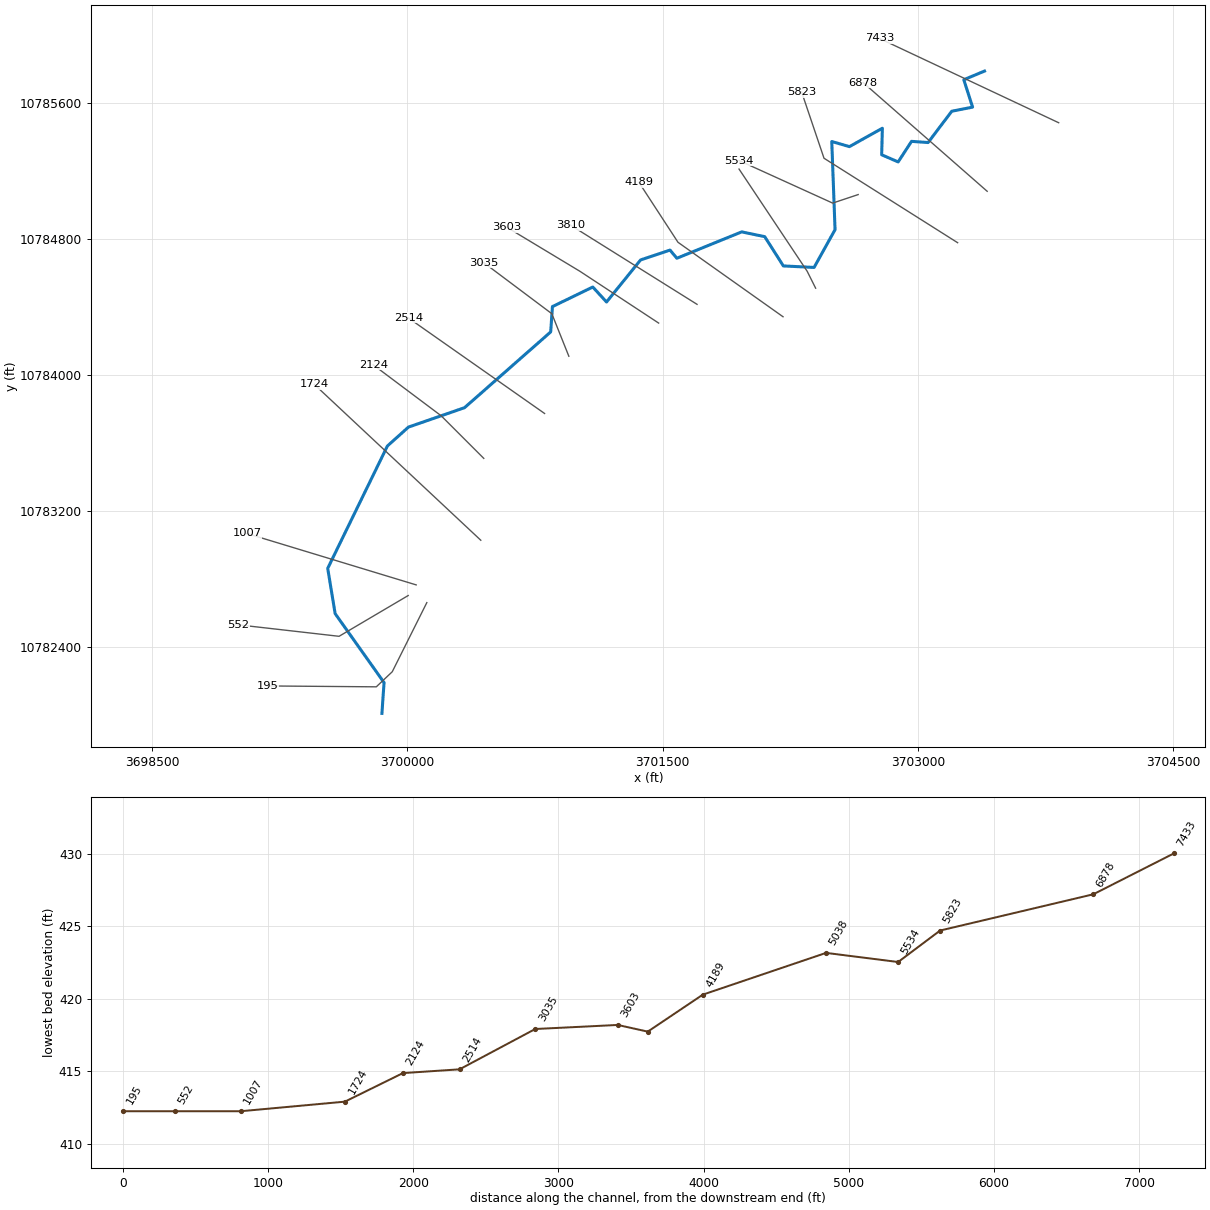
--- NORTH NICHOLS LAKE.prj (project) ---

Proj Title=NORTH NICHOLS LAKE Base Level Engineering
Current Plan=p01
Default Exp/Contr=0.3,0.1
English Units
Geom File=g01
Flow File=f01
Plan File=p01
BEGIN DESCRIPTION:
NORTH NICHOLS LAKE
END DESCRIPTION:

--- NORTH NICHOLS LAKE.p01 (plan) ---

Plan Title=Multiple Run
Short Identifier=Multiple
Geom File=g01
Flow File=f01
Subcritical Flow
K Sum by GR= 0
Std Step Tol= 0.01
Critical Tol= 0.01
Num of Std Step Trials= 20
Max Error Tol= 0.3
Flow Tol Ratio= 0.001
Split Flow NTrial= 30
Split Flow Tol= 0.02
Split Flow Ratio= 0.02
Log Output Level= 0
Friction Slope Method= 1
Unsteady Friction Slope Method= 2
Unsteady Bridges Friction Slope Method= 1
Parabolic Critical Depth
Global Vel Dist=  1 , 1 , 1
Global Log Level= 0
CheckData=True
Encroach Param= -1, 0, 0, 0
BEGIN DESCRIPTION:
Multiple Run
END DESCRIPTION:

--- NORTH NICHOLS LAKE.f01 (steady flow) ---

Flow Title=Multiple
Number of Profiles=7
Profile Names=10-year,25-year,50-year,1pct_min,100-year,1pct_plu,500-year
River Rch & RM= NORTH NICHOLS LA,Reach-1,7433
     637     864    1050     937    1267    1714    1848
River Rch & RM= NORTH NICHOLS LA,Reach-1,5823
     720     984    1203    1078    1457    1971    2145
River Rch & RM= NORTH NICHOLS LA,Reach-1,5534
    1193    1673    2080    1893    2560    3462    3888
Boundary for River Rch & Prof#=NORTH NICHOLS LA,Reach-1,1
Up Type=0
Dn Type=3
Dn Slope=0.005
Boundary for River Rch & Prof#=NORTH NICHOLS LA,Reach-1,2
Up Type=0
Dn Type=3
Dn Slope=0.005
Boundary for River Rch & Prof#=NORTH NICHOLS LA,Reach-1,3
Up Type=0
Dn Type=3
Dn Slope=0.005
Boundary for River Rch & Prof#=NORTH NICHOLS LA,Reach-1,4
Up Type=0
Dn Type=3
Dn Slope=0.005
Boundary for River Rch & Prof#=NORTH NICHOLS LA,Reach-1,5
Up Type=0
Dn Type=3
Dn Slope=0.005
Boundary for River Rch & Prof#=NORTH NICHOLS LA,Reach-1,6
Up Type=0
Dn Type=3
Dn Slope=0.005
Boundary for River Rch & Prof#=NORTH NICHOLS LA,Reach-1,7
Up Type=0
Dn Type=3
Dn Slope=0.005

--- NORTH NICHOLS LAKE.g01 (geometry) ---

Geom Title=Existing Conditions

River Reach=NORTH NICHOLS LA,Reach-1
Reach XY= 30
      3703392.00     10785786.00      3703270.25     10785735.00
      3703322.00     10785574.00      3703199.75     10785550.00
      3703060.50     10785366.00      3702963.25     10785373.00
      3702884.50     10785252.00      3702787.75     10785294.00
      3702791.75     10785450.00      3702598.25     10785342.00
      3702494.50     10785372.00      3702513.75     10784854.00
      3702390.50     10784632.00      3702210.00     10784641.00
      3702100.50     10784813.00      3701965.25     10784841.00
      3701584.25     10784686.00      3701544.00     10784734.00
      3701371.00     10784676.00      3701171.00     10784429.00
      3701090.25     10784517.00      3700853.25     10784402.00
      3700842.75     10784253.00      3700336.75     10783808.00
      3700007.25     10783694.00      3699883.50     10783583.00
      3699532.75     10782864.00      3699576.25     10782598.00
      3699863.83     10782192.57      3699851.21     10782011.79

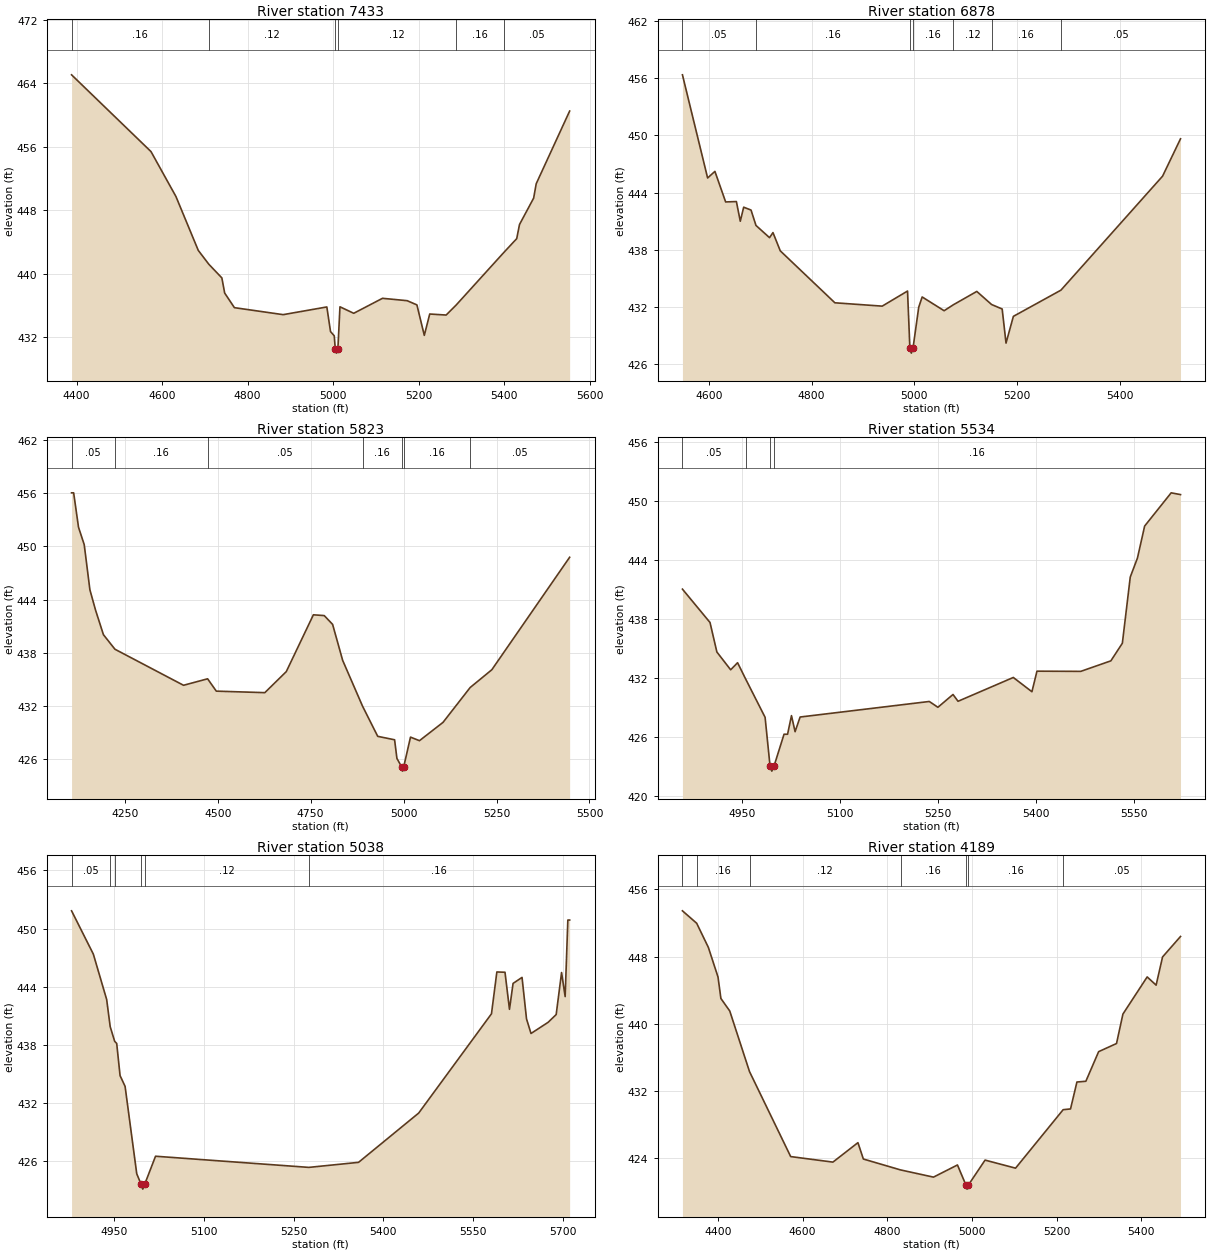
Type RM Length L Ch R = 1,7433,555,555,555
BEGIN DESCRIPTION:
UNT 008 IN CACR 3.0
END DESCRIPTION:
XS GIS Cut Line= 2
      3703827.81     10785482.29      3702773.43     10785978.26
#Sta/Elev= 30
  4388.1  465.09  4574.0  455.41  4632.3  449.75  4684.5  442.96  4709.1  441.22
  4739.7  439.49  4746.3  437.58  4769.1  435.74  4883.1  434.86  4985.3  435.83
  4993.9  432.73  5002.6  432.19  5005.1  430.51  5007.9  430.01  5011.1  430.51
  5016.0  435.85  5048.2  435.03  5115.5  436.92  5173.2  436.62  5196.0  436.09
  5213.3  432.25  5226.0  434.94  5264.4  434.81  5287.8  436.07  5399.2  442.69
  5429.5  444.44  5436.0  446.22  5469.1  449.55  5475.1  451.36  5553.3  460.52
#Mann=6,-1,0
  4388.1    0.16       0  4709.1    0.12       0  5005.1    0.07       0
  5011.1    0.12       0  5287.8    0.16       0  5399.2    0.05       0
Bank Sta=5005.1,5011.1
Exp/Cntr=0.3,0.1

Type RM Length L Ch R = 1,6878,1055,1055,1055
BEGIN DESCRIPTION:
UNT 008 IN CACR 2.0
END DESCRIPTION:
XS GIS Cut Line= 2
      3703407.64     10785079.54      3702678.53     10785718.38
#Sta/Elev= 30
  4548.6  456.33  4597.6  445.53  4611.8  446.22  4632.7  443.02  4653.6  443.06
  4661.2  441.00  4667.8  442.47  4682.1  442.17  4691.7  440.56  4718.1  439.28
  4724.8  439.81  4739.0  437.90  4845.3  432.46  4937.4  432.11  4986.7  433.69
  4991.3  427.69  4994.1  427.19  4997.3  427.69  5008.5  432.00  5015.2  433.07
  5057.9  431.63  5076.1  432.26  5121.5  433.65  5150.3  432.28  5170.9  431.81
  5178.4  428.24  5192.7  431.04  5285.2  433.78  5483.1  445.72  5518.0  449.63
#Mann=7,-1,0
  4548.6    0.05       0  4691.7    0.16       0  4991.3    0.07       0
  4997.3    0.16       0  5076.1    0.12       0  5150.3    0.16       0
  5285.2    0.05       0
Bank Sta=4991.3,4997.3
Exp/Cntr=0.3,0.1

Type RM Length L Ch R = 1,5823,289,289,289
BEGIN DESCRIPTION:
UNT 008 IN CACR 1.0
END DESCRIPTION:
XS GIS Cut Line= 3
      3703234.03     10784777.44      3702448.91     10785273.71
      3702317.39     10785662.87
#Sta/Elev= 30
  4107.0  456.04  4112.6  456.04  4125.7  452.16  4141.0  450.21  4156.3  445.12
  4171.4  442.84  4192.7  440.06  4223.7  438.42  4408.1  434.36  4472.9  435.09
  4496.3  433.70  4626.8  433.53  4684.5  435.90  4757.4  442.30  4786.6  442.21
  4809.1  441.22  4836.2  437.16  4889.7  432.00  4930.4  428.61  4975.8  428.22
  4982.1  426.12  4994.4  425.19  4997.1  424.69  5000.4  425.19  5018.6  428.52
  5042.7  428.12  5106.0  430.18  5179.1  434.11  5237.3  436.11  5446.6  448.78
#Mann=7,-1,0
  4107.0    0.05       0  4223.7    0.16       0  4472.9    0.05       0
  4889.7    0.16       0  4994.4    0.07       0  5000.4    0.16       0
  5179.1    0.05       0
Bank Sta=4994.4,5000.4
Exp/Cntr=0.3,0.1

Type RM Length L Ch R = 1,5534,496,496,496
BEGIN DESCRIPTION:
NORTH NICHOLS LAKE 12.0
END DESCRIPTION:
XS GIS Cut Line= 3
      3702649.64     10785060.20      3702499.61     10785010.19
      3701949.61     10785260.19
#Sta/Elev= 30
  4859.0  441.02  4901.2  437.63  4911.7  434.63  4932.8  432.82  4943.4  433.54
  4955.7  431.89  4985.5  427.99  4993.1  423.02  4995.8  422.52  4999.1  423.02
  5014.5  426.27  5019.9  426.27  5025.9  428.16  5031.4  426.53  5039.1  428.02
  5236.8  429.60  5250.0  429.01  5273.1  430.31  5280.8  429.62  5365.4  432.04
  5393.9  430.59  5401.6  432.68  5468.6  432.66  5514.7  433.73  5532.3  435.52
  5544.4  442.25  5555.4  444.18  5566.4  447.43  5607.0  450.81  5621.3  450.63
#Mann=4,-1,0
  4859.0    0.05       0  4955.7    0.16       0  4993.1    0.07       0
  4999.1    0.16       0
Bank Sta=4993.1,4999.1
Exp/Cntr=0.3,0.1

Type RM Length L Ch R = 1,5038,849,849,849
BEGIN DESCRIPTION:
NORTH NICHOLS LAKE 11.0
END DESCRIPTION:
XS GIS Cut Line= 3
      3702399.62     10784510.17      3702349.61     10784610.19
      3701949.63     10785210.16
#Sta/Elev= 30
  4878.8  451.83  4915.2  447.37  4937.5  442.69  4943.4  439.89  4950.9  438.38
  4954.3  438.16  4959.9  434.85  4968.3  433.74  4987.8  424.73  4995.1  423.65
  4997.9  423.15  5001.1  423.65  5019.2  426.54  5275.6  425.39  5358.7  425.91
  5459.3  430.99  5581.0  441.22  5590.0  445.53  5603.6  445.50  5611.1  441.68
  5617.1  444.35  5632.1  444.97  5639.6  440.69  5647.1  439.19  5675.7  440.34
  5689.2  441.14  5698.2  445.47  5704.2  442.99  5708.7  450.88  5711.7  450.88
#Mann=6,-1,0
  4878.8    0.05       0  4943.4    0.16       0  4950.9    0.12       0
  4995.1    0.07       0  5001.1    0.12       0  5275.6    0.16       0
Bank Sta=4995.1,5001.1
Exp/Cntr=0.3,0.1

Type RM Length L Ch R = 1,4189,379,379,379
BEGIN DESCRIPTION:
NORTH NICHOLS LAKE 10.0
END DESCRIPTION:
XS GIS Cut Line= 3
      3702208.11     10784342.32      3701590.95     10784779.80
      3701361.81     10785131.32
#Sta/Elev= 30
  4316.5  453.45  4350.1  451.97  4377.7  449.09  4400.5  445.56  4407.3  443.00
  4428.2  441.51  4474.9  434.28  4572.1  424.15  4671.8  423.49  4730.9  425.81
  4743.7  423.86  4831.5  422.56  4909.3  421.70  4965.9  423.15  4985.8  420.77
  4988.6  420.27  4991.8  420.77  5031.1  423.73  5103.1  422.77  5215.5  429.74
  5232.9  429.83  5248.0  433.04  5269.1  433.13  5299.3  436.66  5341.5  437.63
  5356.6  441.14  5413.9  445.57  5435.0  444.59  5450.2  447.95  5492.6  450.39
#Mann=7,-1,0
  4316.5    0.05       0  4350.1    0.16       0  4474.9    0.12       0
  4831.5    0.16       0  4985.8    0.07       0  4991.8    0.16       0
  5215.5    0.05       0
Bank Sta=4985.8,4991.8
Exp/Cntr=0.3,0.1

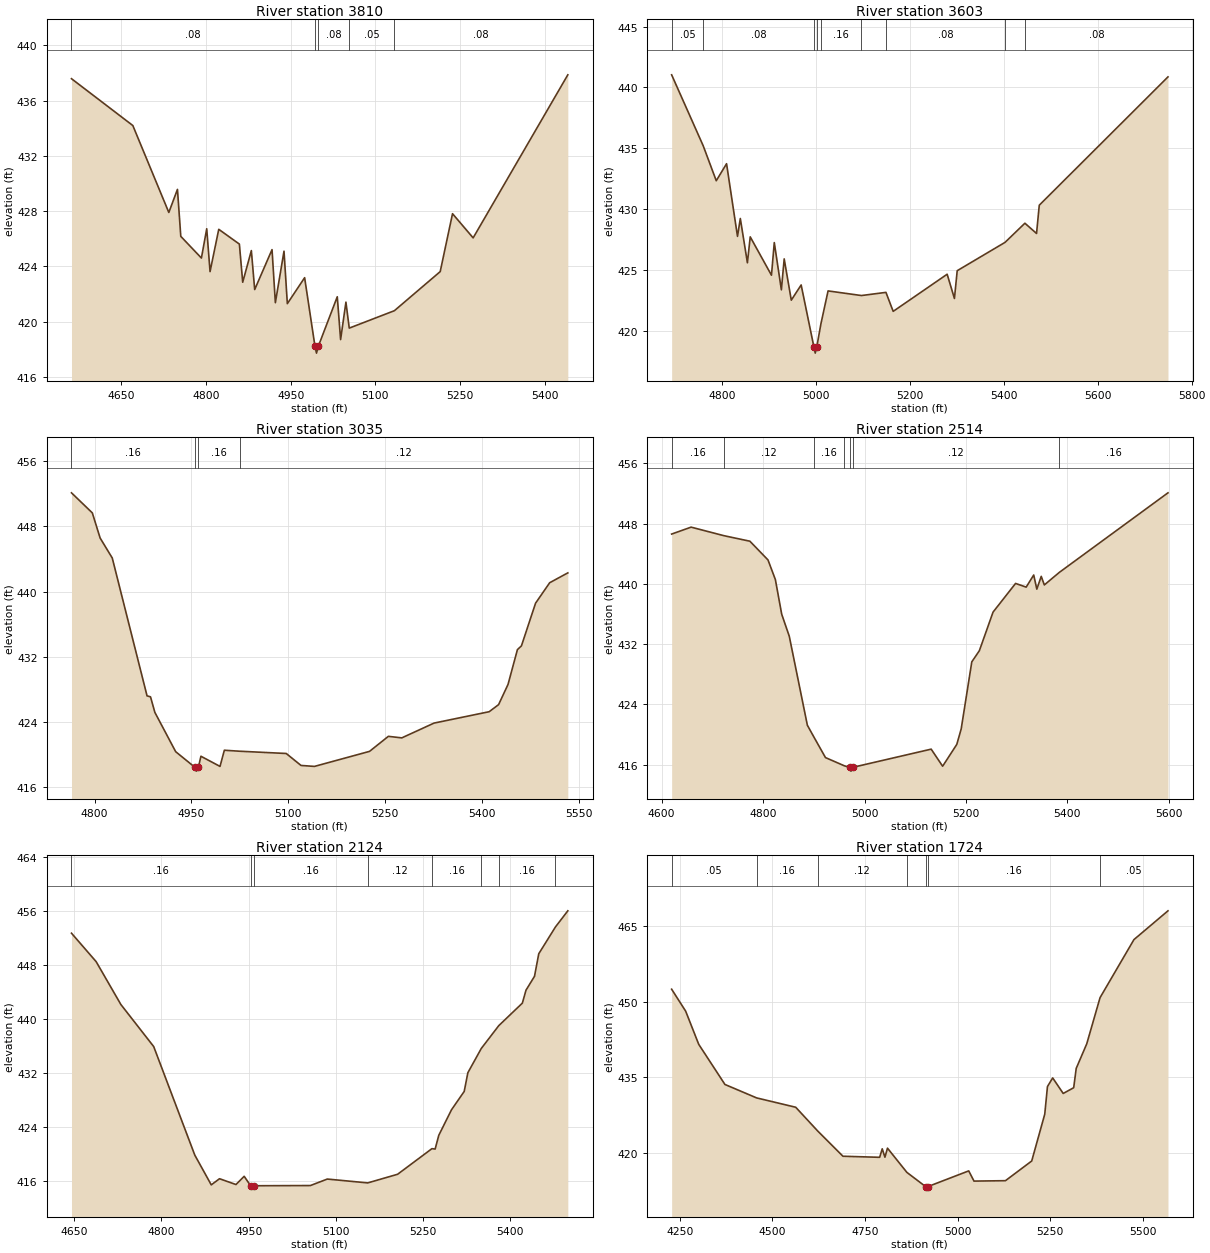
Type RM Length L Ch R = 1,3810,207,207,207
BEGIN DESCRIPTION:
NORTH NICHOLS LAKE 9.0
END DESCRIPTION:
XS GIS Cut Line= 2
      3701702.91     10784415.23      3700958.15     10784881.35
#Sta/Elev= 30
  4562.0  437.58  4670.6  434.19  4734.3  427.90  4749.6  429.57  4755.5  426.17
  4792.0  424.60  4801.4  426.72  4807.3  423.62  4822.7  426.68  4859.2  425.61
  4865.1  422.85  4880.4  425.14  4886.3  422.32  4917.0  425.21  4922.9  421.37
  4938.2  425.10  4944.1  421.30  4974.7  423.18  4993.0  418.22  4995.7  417.72
  4999.0  418.22  5032.5  421.80  5038.4  418.70  5047.8  421.41  5053.7  419.53
  5133.6  420.79  5214.7  423.62  5236.5  427.81  5273.0  426.06  5440.6  437.86
#Mann=5,-1,0
  4562.0    0.08       0  4993.0    0.07       0  4999.0    0.08       0
  5053.7    0.05       0  5133.6    0.08       0
Bank Sta=4993,4999
Exp/Cntr=0.3,0.1

Type RM Length L Ch R = 1,3603,568,568,568
BEGIN DESCRIPTION:
NORTH NICHOLS LAKE 8.0
END DESCRIPTION:
XS GIS Cut Line= 3
      3701477.25     10784305.14      3701015.43     10784608.97
      3700583.88     10784868.93
#Sta/Elev= 30
  4693.0  441.04  4760.1  435.22  4788.0  432.34  4809.9  433.74  4833.2  427.77
  4839.2  429.24  4854.3  425.60  4860.3  427.73  4905.5  424.58  4911.5  427.26
  4926.6  423.38  4932.6  425.92  4947.7  422.53  4968.7  423.78  4995.9  418.68
  4998.7  418.18  5001.9  418.68  5010.9  420.61  5026.0  423.29  5097.0  422.91
  5149.2  423.17  5164.6  421.61  5279.5  424.66  5295.0  422.67  5300.9  424.95
  5402.8  427.28  5445.0  428.85  5469.8  428.01  5475.6  430.33  5749.6  440.87
#Mann=9,-1,0
  4693.0    0.05       0  4760.1    0.08       0  4995.9    0.07       0
  5001.9    0.08       0  5010.9    0.16       0  5097.0    0.05       0
  5149.2    0.08       0  5402.8    0.16       0  5445.0    0.08       0
Bank Sta=4995.9,5001.9
Exp/Cntr=0.3,0.1

Type RM Length L Ch R = 1,3035,521,521,521
BEGIN DESCRIPTION:
NORTH NICHOLS LAKE 7.0
END DESCRIPTION:
XS GIS Cut Line= 3
      3700949.59     10784110.23      3700849.61     10784360.19
      3700449.62     10784660.18
#Sta/Elev= 30
  4764.2  452.14  4796.5  449.67  4808.6  446.58  4827.4  444.12  4881.3  427.16
  4886.7  427.04  4893.4  425.13  4925.7  420.29  4955.0  418.40  4957.8  417.90
  4961.0  418.40  4964.8  419.73  4994.4  418.48  5001.1  420.47  5024.6  420.35
  5097.0  420.07  5119.9  418.60  5140.7  418.48  5226.1  420.33  5255.3  422.18
  5276.1  421.99  5326.1  423.81  5411.5  425.21  5426.1  426.08  5440.7  428.56
  5455.3  432.85  5461.5  433.31  5483.4  438.56  5505.3  441.08  5533.4  442.29
#Mann=4,-1,0
  4764.2    0.16       0  4955.0    0.07       0  4961.0    0.16       0
  5024.6    0.12       0
Bank Sta=4955,4961
Exp/Cntr=0.3,0.1

Type RM Length L Ch R = 1,2514,390,390,390
BEGIN DESCRIPTION:
NORTH NICHOLS LAKE 6.0
END DESCRIPTION:
XS GIS Cut Line= 2
      3700807.08     10783773.91      3700005.87     10784335.80
#Sta/Elev= 30
  4619.7  446.62  4658.1  447.54  4722.5  446.41  4774.0  445.67  4809.7  443.18
  4824.2  440.58  4836.7  435.97  4851.6  433.05  4887.3  421.22  4900.2  419.65
  4923.0  416.92  4960.5  415.82  4970.6  415.62  4973.3  415.12  4976.6  415.62
  5131.4  418.04  5154.0  415.77  5181.9  418.67  5190.6  420.73  5211.5  429.64
  5226.4  431.12  5253.4  436.25  5297.8  440.06  5318.7  439.57  5333.6  441.18
  5339.7  439.30  5348.4  441.00  5354.5  439.86  5383.9  441.52  5598.3  452.10
#Mann=7,-1,0
  4619.7    0.16       0  4722.5    0.12       0  4900.2    0.16       0
  4960.5    0.12       0  4970.6    0.07       0  4976.6    0.12       0
  5383.9    0.16       0
Bank Sta=4970.6,4976.6
Exp/Cntr=0.3,0.1

Type RM Length L Ch R = 1,2124,400,400,400
BEGIN DESCRIPTION:
NORTH NICHOLS LAKE 5.0
END DESCRIPTION:
XS GIS Cut Line= 3
      3700449.62     10783510.18      3700199.61     10783760.19
      3699799.58     10784060.21
#Sta/Elev= 30
  4645.3  452.74  4687.7  448.53  4730.2  442.19  4786.7  435.96  4857.4  419.89
  4885.7  415.49  4899.9  416.40  4928.2  415.54  4942.3  416.76  4953.4  415.36
  4956.2  414.86  4959.4  415.36  5056.2  415.39  5085.3  416.35  5154.8  415.78
  5206.2  417.06  5265.2  420.85  5270.7  420.79  5277.0  422.83  5298.9  426.61
  5320.7  429.32  5327.0  432.09  5350.1  435.68  5380.1  439.05  5420.7  442.39
  5427.0  444.31  5441.6  446.36  5448.9  449.69  5477.6  453.66  5498.9  456.05
#Mann=8,-1,0
  4645.3    0.16       0  4953.4    0.07       0  4959.4    0.16       0
  5154.8    0.12       0  5265.2    0.16       0  5350.1    0.12       0
  5380.1    0.16       0  5477.6    0.05       0
Bank Sta=4953.4,4959.4
Exp/Cntr=0.3,0.1

Type RM Length L Ch R = 1,1724,717,717,717
BEGIN DESCRIPTION:
NORTH NICHOLS LAKE 4.0
END DESCRIPTION:
XS GIS Cut Line= 2
      3700432.09     10783029.11      3699454.08     10783944.69
#Sta/Elev= 30
  4228.3  452.47  4266.2  448.12  4301.4  441.56  4372.2  433.61  4457.7  430.95
  4563.2  429.10  4622.9  424.37  4690.7  419.40  4789.8  419.19  4796.7  420.87
  4804.0  419.21  4810.9  421.00  4863.3  416.20  4913.9  413.39  4916.6  412.89
  4919.9  413.39  5030.2  416.50  5044.4  414.48  5129.3  414.56  5200.2  418.46
  5235.4  427.73  5242.7  433.20  5256.8  434.91  5285.2  431.83  5313.5  432.97
  5320.3  436.79  5348.7  441.65  5384.7  450.81  5476.2  462.30  5568.0  467.99
#Mann=7,-1,0
  4228.3    0.05       0  4457.7    0.16       0  4622.9    0.12       0
  4863.3    0.16       0  4913.9    0.07       0  4919.9    0.16       0
  5384.7    0.05       0
Bank Sta=4913.9,4919.9
Exp/Cntr=0.3,0.1

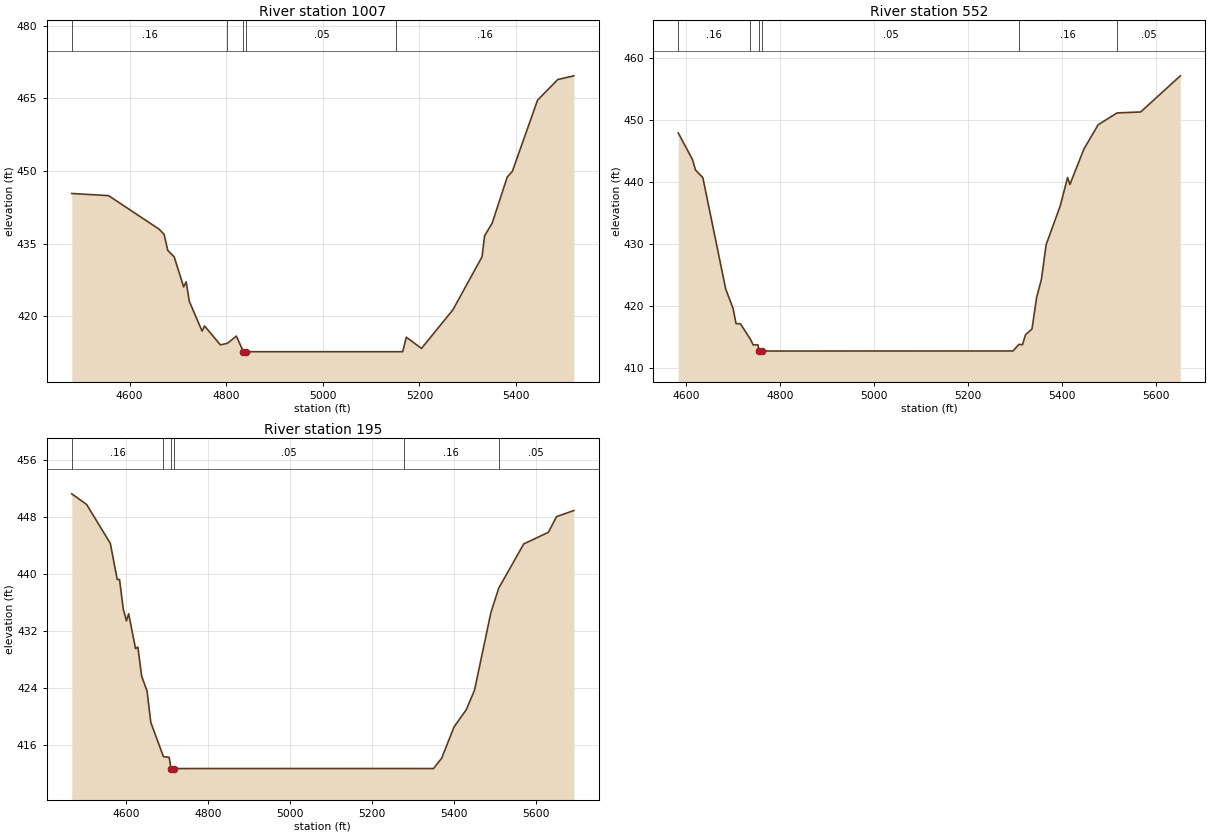
Type RM Length L Ch R = 1,1007,455,455,455
BEGIN DESCRIPTION:
NORTH NICHOLS LAKE 3.0
END DESCRIPTION:
XS GIS Cut Line= 2
      3700052.54     10782766.73      3699057.70     10783068.83
#Sta/Elev= 30
  4480.1  445.38  4556.3  444.94  4660.8  438.03  4671.3  436.94  4678.9  433.63
  4692.2  432.31  4711.8  426.09  4717.0  427.16  4723.5  423.13  4749.9  416.99
  4755.1  418.04  4788.0  414.13  4802.5  414.47  4820.9  415.95  4835.5  412.73
  4838.2  412.23  4841.5  412.73  5152.4  412.73  5165.4  412.73  5172.9  415.73
  5204.3  413.41  5269.3  421.37  5329.7  432.31  5335.0  436.65  5350.6  439.24
  5381.9  448.78  5392.4  449.93  5444.6  464.62  5486.5  468.90  5519.8  469.66
#Mann=5,-1,0
  4480.1    0.16       0  4802.5    0.05       0  4835.5   0.033       0
  4841.5    0.05       0  5152.4    0.16       0
Bank Sta=4835.5,4841.5
Exp/Cntr=0.3,0.1

Type RM Length L Ch R = 1,552,357,357,357
BEGIN DESCRIPTION:
NORTH NICHOLS LAKE 2.0
END DESCRIPTION:
XS GIS Cut Line= 3
      3700005.68     10782704.24      3699599.41     10782464.65
      3699005.71     10782532.35
#Sta/Elev= 30
  4583.2  447.97  4613.5  443.67  4620.0  441.98  4635.6  440.74  4684.3  422.75
  4700.0  419.61  4706.3  417.16  4715.6  417.14  4737.0  414.62  4742.9  413.71
  4752.7  413.76  4755.5  412.73  4758.3  412.23  4761.5  412.73  5296.2  412.74
  5308.6  413.81  5316.3  413.75  5322.9  415.38  5336.5  416.28  5346.5  421.43
  5356.6  424.30  5366.7  429.92  5396.9  436.22  5412.3  440.76  5417.3  439.64
  5447.2  445.38  5477.4  449.28  5517.8  451.20  5568.0  451.35  5652.4  457.19
#Mann=6,-1,0
  4583.2    0.16       0  4737.0    0.05       0  4755.5   0.033       0
  4761.5    0.05       0  5308.6    0.16       0  5517.8    0.05       0
Bank Sta=4755.5,4761.5
Exp/Cntr=0.3,0.1

Type RM Length L Ch R = 1,195,0,0,0
BEGIN DESCRIPTION:
NORTH NICHOLS LAKE 1.0
END DESCRIPTION:
XS GIS Cut Line= 4
      3700115.03     10782662.55      3699911.91     10782256.32
      3699818.16     10782167.78      3699177.52     10782172.98
#Sta/Elev= 30
  4467.8  451.28  4504.0  449.79  4561.8  444.33  4578.6  439.27  4584.2  439.26
  4593.4  435.11  4601.0  433.45  4606.5  434.45  4623.3  429.56  4628.9  429.78
  4638.1  425.71  4651.3  423.61  4660.5  419.20  4691.2  414.41  4705.2  414.31
  4709.8  412.73  4712.5  412.23  4715.8  412.73  5276.9  412.74  5349.5  412.73
  5369.5  414.19  5399.5  418.56  5429.5  421.00  5449.5  423.73  5489.5  434.64
  5508.4  438.03  5569.5  444.25  5629.5  445.88  5649.5  448.08  5691.6  448.94
#Mann=6,-1,0
  4467.8    0.16       0  4691.2    0.05       0  4709.8   0.033       0
  4715.8    0.05       0  5276.9    0.16       0  5508.4    0.05       0
Bank Sta=4709.8,4715.8
Exp/Cntr=0.3,0.1

Chan Stop Cuts=-1