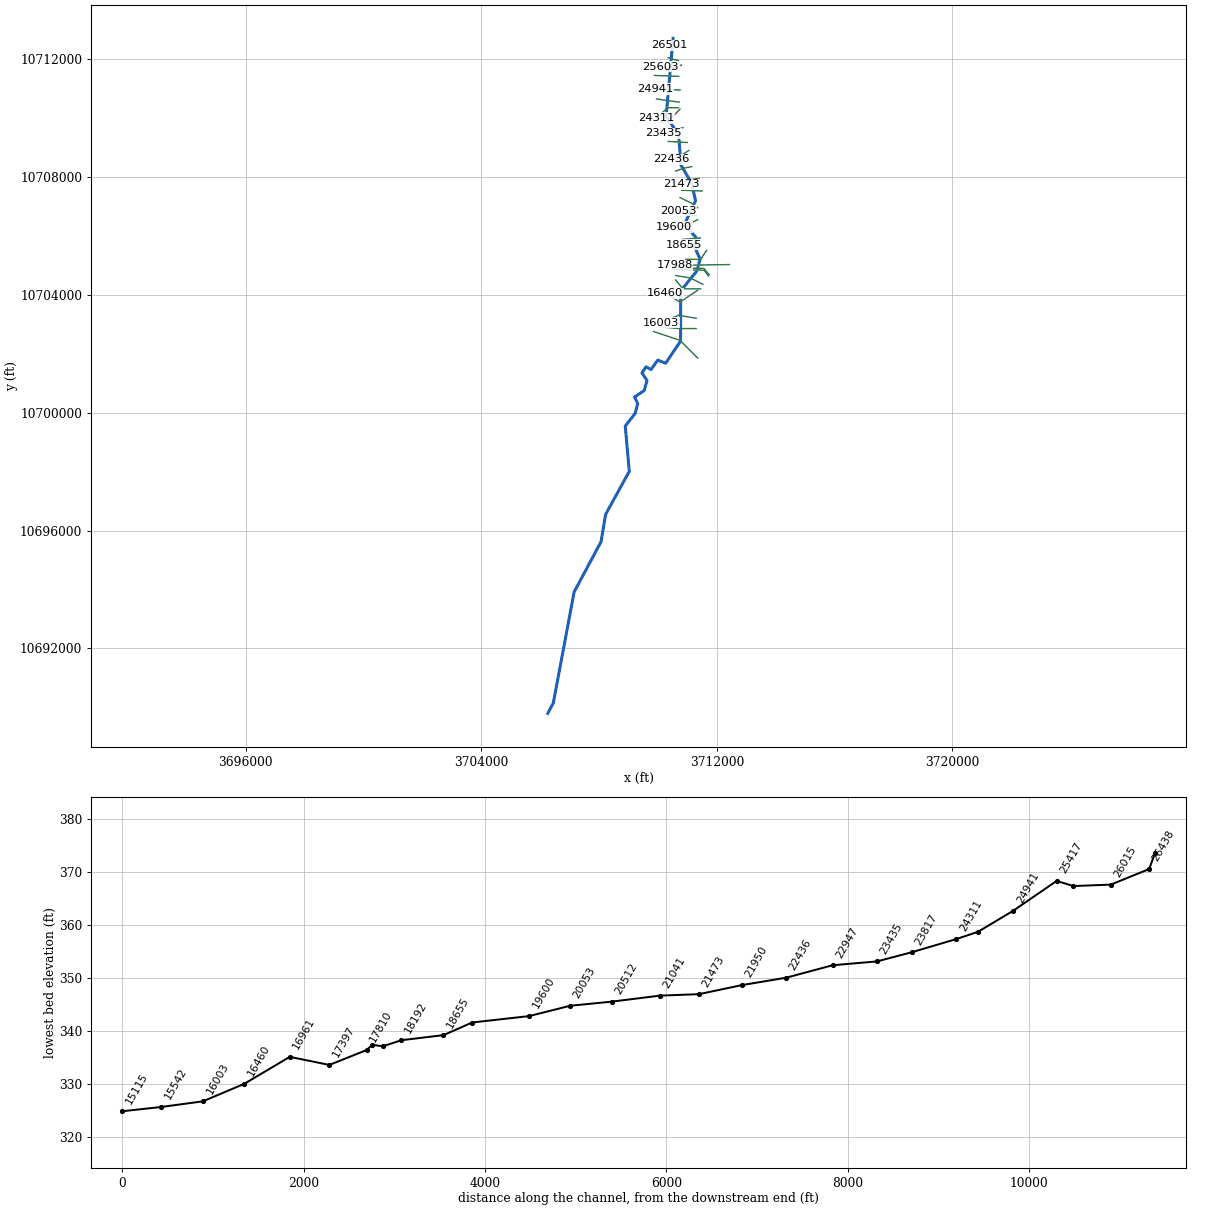
--- OTTER CREEK.prj (project) ---

Proj Title=OTTER CREEK Base Level Engineering
Current Plan=p01
Default Exp/Contr=0.3,0.1
English Units
Geom File=g01
Flow File=f01
Plan File=p01
Y Axis Title=Elevation
X Axis Title(PF)=Main Channel Distance
X Axis Title(XS)=Station
BEGIN DESCRIPTION:
OTTER CREEK
END DESCRIPTION:
DSS Export Rating Curves= 0
DSS Export Rating Curve Sorted= 0
DSS Export Volume Flow Curves= 0
DXF OffsetX= 0
DXF OffsetY= 0
DXF ScaleX= 1
DXF ScaleY= 10

--- OTTER CREEK.p01 (plan) ---

Plan Title=Multiple Run
Short Identifier=Multiple
Geom File=g01
Flow File=f01
Subcritical Flow
K Sum by GR= 0
Std Step Tol= 0.01
Critical Tol= 0.01
Num of Std Step Trials= 20
Max Error Tol= 0.3
Flow Tol Ratio= 0.001
Split Flow NTrial= 30
Split Flow Tol= 0.02
Split Flow Ratio= 0.02
Log Output Level= 0
Friction Slope Method= 1
Unsteady Friction Slope Method= 2
Unsteady Bridges Friction Slope Method= 1
Parabolic Critical Depth
Global Vel Dist=  1 , 1 , 1
Global Log Level= 0
CheckData=True
Encroach Param= -1, 0, 0, 0
BEGIN DESCRIPTION:
Multiple Run
END DESCRIPTION:

--- OTTER CREEK.f01 (steady flow) ---

Flow Title=Multiple
Program Version=4.10
Number of Profiles= 7
Profile Names=10-year,25-year,50-year,1pct_min,100-year,1pct_plu,500-year
River Rch & RM=OTTER CREEK,Reach-1         ,26501
     604     830    1020     922    1246    1686    1870
River Rch & RM=OTTER CREEK,Reach-1         ,25603
     636     875    1075     972    1314    1777    1971
River Rch & RM=OTTER CREEK,Reach-1         ,23817
     913    1279    1590    1452    1964    2656    3010
River Rch & RM=OTTER CREEK,Reach-1         ,20512
     915    1276    1583    1441    1949    2636    2969
River Rch & RM=OTTER CREEK,Reach-1         ,17869
    2140    3094    3931    3655    4944    6686    7859
River Rch & RM=OTTER CREEK,Reach-1         ,16460
    2728    3978    5082    4749    6422    8685   10309
River Rch & RM=OTTER CREEK,Reach-1         ,15542
    2728    3978    5082    4749    6422    8685   10309
River Rch & RM=OTTER CREEK,Reach-1         ,10952
    2704    3930    5010    4670    6315    8541   10089
River Rch & RM=OTTER CREEK,Reach-1         ,7316
    2770    4029    5138    4791    6479    8762   10357
River Rch & RM=OTTER CREEK,Reach-1         ,7002
    3203    4676    5979    5587    7555   10218   12128
River Rch & RM=OTTER CREEK,Reach-1         ,2666
    3221    4698    6003    5605    7580   10251   12148
Boundary for River Rch & Prof#=OTTER CREEK,Reach-1         , 1
Up Type= 0
Dn Type= 3
Dn Slope=0.00389
Boundary for River Rch & Prof#=OTTER CREEK,Reach-1         , 2
Up Type= 0
Dn Type= 3
Dn Slope=0.00389
Boundary for River Rch & Prof#=OTTER CREEK,Reach-1         , 3
Up Type= 0
Dn Type= 3
Dn Slope=0.00389
Boundary for River Rch & Prof#=OTTER CREEK,Reach-1         , 4
Up Type= 0
Dn Type= 3
Dn Slope=0.00389
Boundary for River Rch & Prof#=OTTER CREEK,Reach-1         , 5
Up Type= 0
Dn Type= 3
Dn Slope=0.00389
Boundary for River Rch & Prof#=OTTER CREEK,Reach-1         , 6
Up Type= 0
Dn Type= 3
Dn Slope=0.00389
Boundary for River Rch & Prof#=OTTER CREEK,Reach-1         , 7
Up Type= 0
Dn Type= 3
Dn Slope=0.00389
DSS Import GetInterval= 0
DSS Import GetPeak= 0
DSS Import FillOption= 0

--- OTTER CREEK.g01 (geometry) ---

Geom Title=Existing Conditions
Program Version=4.10

River Reach=OTTER CREEK     ,Reach-1
Reach XY= 30
       3710514.9     10712716.72       3710279.5       10710083.
        3710706.       10709419.      3710781.75       10708415.
        3711147.       10707789.      3711276.75       10707201.
       3710899.5       10706400.      3711287.25       10705959.
        3711231.       10705656.        3711436.       10705215.
      3711317.25       10704811.        3710773.       10704139.
        3710769.       10702437.      3710262.75       10701683.
      3709991.25       10701787.      3709765.75       10701468.
       3709596.5       10701563.      3709456.25       10701353.
        3709629.       10701100.        3709537.       10700761.
        3709205.       10700533.      3709315.25       10700314.
      3709222.75       10699972.      3708890.25       10699550.
      3709026.75       10698011.       3708223.5       10696549.
      3708069.25       10695625.       3707153.5       10693912.
       3706447.5       10690145.       3706260.5       10689791.

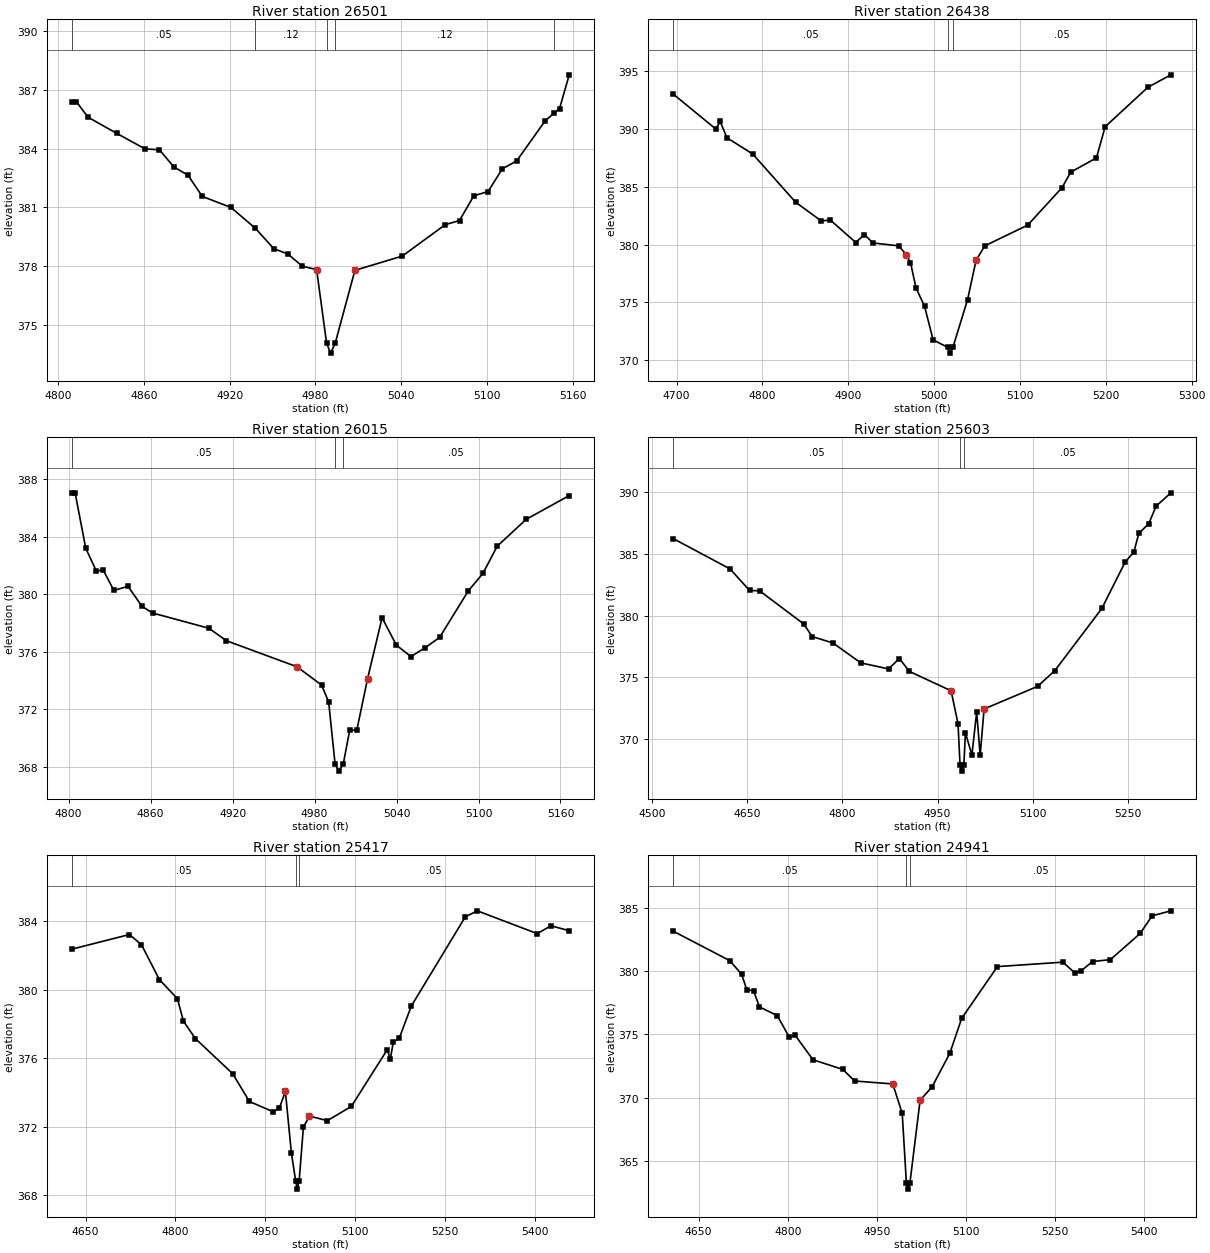
Type RM Length L Ch R = 1 ,26501   ,63,63,63
BEGIN DESCRIPTION:
OTTER CREEK 53.0
END DESCRIPTION:
XS GIS Cut Line= 3
      3710731.14     10712475.38      3710531.16     10712475.38
      3710382.84     10712475.38
#Sta/Elev= 30
  4809.3   386.4  4812.6   386.4  4820.8   385.6  4840.8  384.78  4860.8  383.98
  4870.8  383.94  4880.8  383.07  4890.8  382.64  4900.8  381.56  4920.8     381
    4938  379.93  4950.8   378.9  4960.8  378.62  4970.8     378  4980.8  377.83
  4987.8  374.07  4990.6  373.57  4993.8  374.07  5007.6  377.79  5040.8  378.52
  5070.8  380.12  5080.8  380.33  5090.8  381.59  5100.8  381.81  5110.8  382.97
  5120.8  383.37  5140.8  385.42  5146.9   385.8  5150.8  386.04  5157.6  387.76
#Mann= 5 ,-1 , 0
  4809.3     .05       0    4938     .12       0  4987.8     .07       0
  4993.8     .12       0  5146.9     .05       0
Bank Sta=4980.8,5007.6
XS Rating Curve= 0 ,0
Exp/Cntr=0.3,0.1

Type RM Length L Ch R = 1 ,26438   ,423,423,423
BEGIN DESCRIPTION:
Mapping XS 3a0e7a88
END DESCRIPTION:
XS GIS Cut Line= 2
       3710852.1     10712427.51      3710272.98     10712401.54
#Sta/Elev= 30
  4696.1  393.01  4745.8  389.98  4750.8  390.64  4758.7  389.23  4788.7  387.83
  4838.7  383.66  4868.8  382.03  4878.8  382.14  4908.8  380.18  4918.8  380.87
  4928.8  380.14  4958.9  379.89  4967.5  379.13  4972.5  378.45  4978.9  376.26
  4988.9  374.66  4998.9  371.76  5015.9  371.12  5018.7  370.62  5021.9  371.12
  5038.9  375.22  5048.9  378.64    5059  379.89    5109  381.68    5149  384.92
  5159.1  386.26  5189.1  387.49  5199.2  390.18  5249.1   393.6  5275.8  394.67
#Mann= 3 ,-1 , 0
  4696.1     .05       0  5015.9     .04       0  5021.9     .05       0
Bank Sta=4967.5,5048.9
XS Rating Curve= 0 ,0
Exp/Cntr=0.3,0.1

Type RM Length L Ch R = 1 ,26015   ,412,412,412
BEGIN DESCRIPTION:
OTTER CREEK 52.0
END DESCRIPTION:
XS GIS Cut Line= 3
      3710699.65     10711960.18      3710499.61     10712010.19
      3710349.62     10712060.18
#Sta/Elev= 30
  4802.1  387.04  4804.7  387.04  4812.5  383.18  4820.2  381.61  4825.3  381.66
  4833.1  380.25  4843.4  380.54  4853.7  379.14  4861.4  378.68  4902.6  377.62
  4915.5  376.75  4967.1  374.94  4985.1  373.67  4990.3  372.49    4995  368.18
  4997.7  367.68    5001  368.18  5005.7  370.53  5010.9  370.53  5018.8  374.12
  5029.4  378.35  5039.9  376.44  5050.5  375.65    5061  376.27  5071.5  376.98
  5092.6  380.23  5103.2  381.43  5113.7  383.33  5134.8  385.19  5166.4  386.85
#Mann= 3 ,-1 , 0
  4802.1     .05       0    4995     .03       0    5001     .05       0
Bank Sta=4967.1,5018.8
XS Rating Curve= 0 ,0
Exp/Cntr=0.3,0.1

Type RM Length L Ch R = 1 ,25603   ,186,186,186
BEGIN DESCRIPTION:
OTTER CREEK 51.0
END DESCRIPTION:
XS GIS Cut Line= 3
      3710799.57     10711810.17      3710349.61     10711610.19
      3710099.65     10711760.16
#Sta/Elev= 30
  4533.6  386.23  4623.2  383.77  4653.9  382.03  4669.7     382  4739.4  379.31
  4752.4   378.3  4785.2  377.78    4829  376.17  4872.8  375.68  4889.9  376.52
  4905.6  375.48  4971.3  373.91  4982.2  371.26  4985.4  367.91  4988.1  367.41
  4991.4  367.91  4993.9   370.5  5004.1  368.72  5011.6  372.19  5017.1   368.7
  5023.3  372.44  5107.6  374.27  5134.8  375.55  5208.7  380.57  5245.6  384.34
  5259.2  385.14    5267  386.65  5282.6  387.43  5294.2  388.85  5317.5  389.93
#Mann= 3 ,-1 , 0
  4533.6     .05       0  4985.4     .03       0  4991.4     .05       0
Bank Sta=4971.3,5023.3
XS Rating Curve= 0 ,0
Exp/Cntr=0.3,0.1

Type RM Length L Ch R = 1 ,25417   ,476,476,476
BEGIN DESCRIPTION:
Mapping XS 0474148b
END DESCRIPTION:
XS GIS Cut Line= 2
      3710706.13     10711425.18      3709876.32     10711456.43
#Sta/Elev= 30
  4626.7  382.35  4723.3  383.21  4743.3  382.62  4773.3  380.58  4803.3  379.47
  4813.4  378.16  4833.4  377.14  4895.5   375.1  4923.4  373.48  4963.5  372.87
  4973.5   373.1  4983.5  374.06  4993.5  370.48  5000.5  368.87  5003.2  368.37
  5006.5  368.87  5013.5  371.97  5023.5  372.63  5053.5  372.36  5093.5  373.19
  5153.5   376.5  5158.5  375.95  5163.6  376.94  5173.6  377.18  5193.6  379.04
  5283.7  384.24  5303.7  384.59  5403.8  383.26  5426.5  383.72  5457.1  383.43
#Mann= 3 ,-1 , 0
  4626.7     .05       0  5000.5     .03       0  5006.5     .05       0
Bank Sta=4983.5,5023.5
XS Rating Curve= 0 ,0
Exp/Cntr=0.3,0.1

Type RM Length L Ch R = 1 ,24941   ,391,391,391
BEGIN DESCRIPTION:
Mapping XS 9f63cd07
END DESCRIPTION:
XS GIS Cut Line= 2
      3710754.71     10710959.91      3709917.93     10710994.63
#Sta/Elev= 30
  4607.2  383.17  4702.4  380.84  4722.4  379.76    4731  378.54  4742.4  378.46
  4752.4  377.18  4782.4  376.49  4802.5  374.79  4812.5  374.93  4842.5     373
  4892.5  372.24  4912.6  371.32  4976.7  371.09  4992.6  368.76  4999.6  363.27
  5002.4  362.77  5005.6  363.27  5022.7   369.8  5042.7  370.85  5072.7  373.51
  5092.7  376.28  5152.8  380.37  5262.9  380.72  5282.9  379.88  5292.9  380.01
  5312.9  380.77  5342.9  380.92    5393  382.99    5413  384.38  5444.7  384.78
#Mann= 3 ,-1 , 0
  4607.2     .05       0  4999.6     .03       0  5005.6     .05       0
Bank Sta=4976.7,5022.7
XS Rating Curve= 0 ,0
Exp/Cntr=0.3,0.1

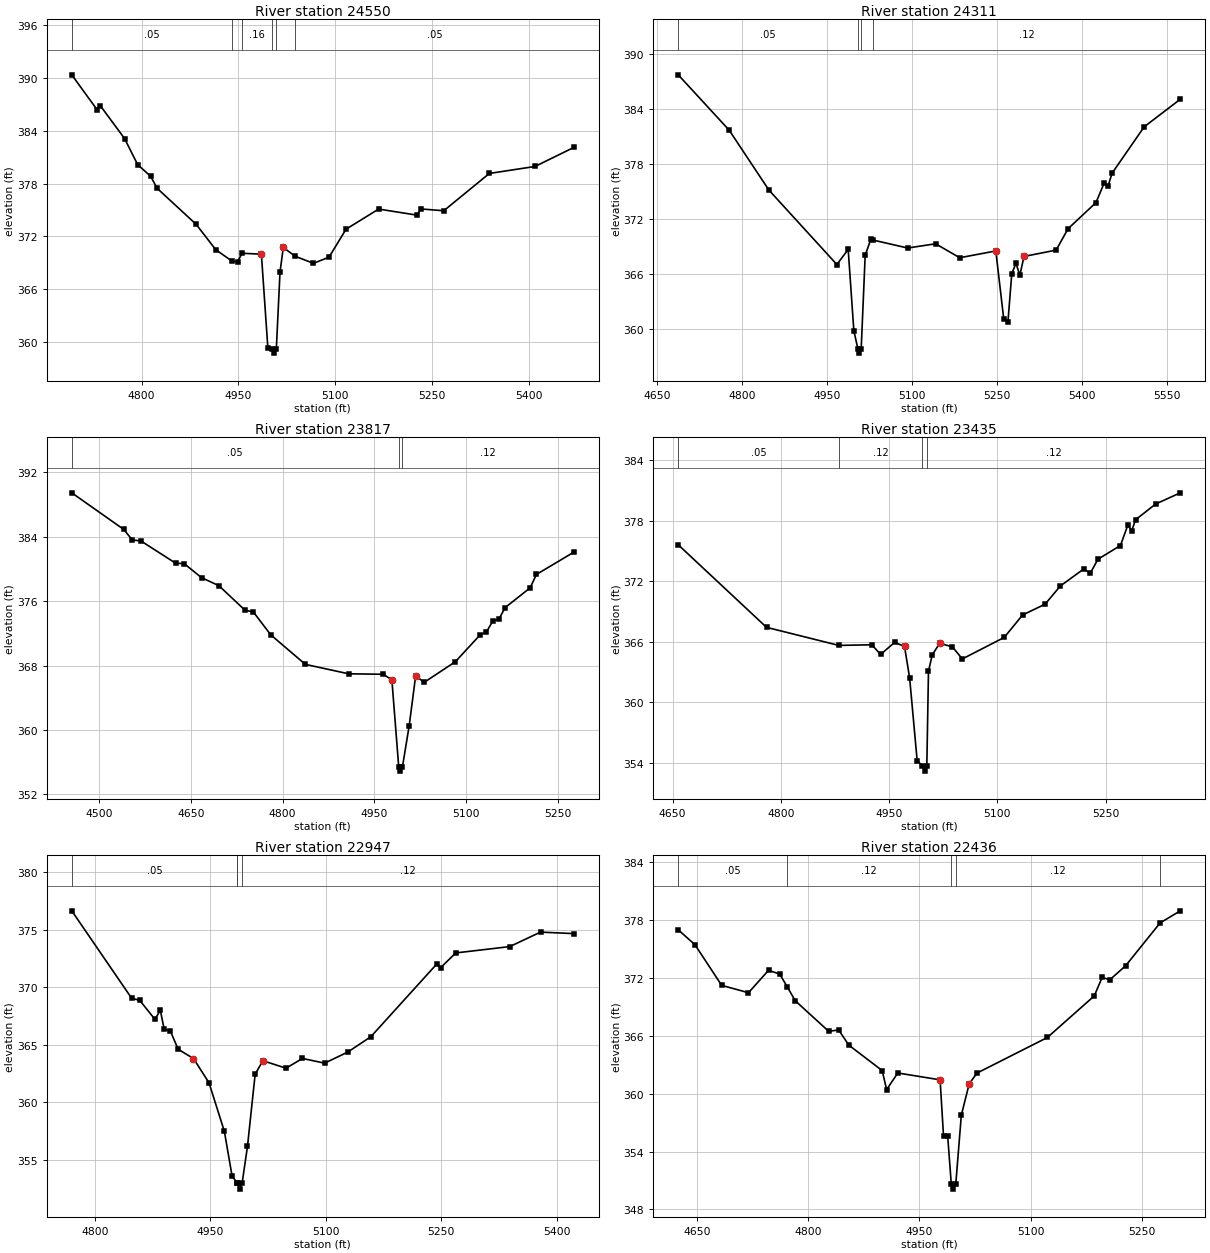
Type RM Length L Ch R = 1 ,24550   ,239,239,239
BEGIN DESCRIPTION:
OTTER CREEK 49.0
END DESCRIPTION:
XS GIS Cut Line= 2
      3710720.66      10710549.3      3709949.88     10710658.67
#Sta/Elev= 30
  4691.8  390.32    4731  386.37    4736  386.83  4773.7  383.09  4793.9  380.15
  4814.1  378.81  4824.2  377.45  4884.8  373.36  4915.1  370.49  4940.9  369.17
  4948.8  369.14  4955.9  370.09  4985.8  369.99  4995.9  359.31    5003  359.27
  5005.7  358.77    5009  359.27  5014.7  367.97  5019.8  370.75  5038.2  369.75
  5066.6  368.95  5090.7  369.65  5117.1  372.82  5167.6   375.1  5227.5  374.41
  5232.6  375.12  5268.6  374.91  5339.3  379.14    5410  379.93  5470.3  382.09
#Mann= 6 ,-1 , 0
  4691.8     .05       0  4940.9     .12       0  4955.9     .16       0
    5003     .07       0    5009     .16       0  5038.2     .05       0
Bank Sta=4985.8,5019.8
XS Rating Curve= 0 ,0
Exp/Cntr=0.3,0.1

Type RM Length L Ch R = 1 ,24311   ,494,494,494
BEGIN DESCRIPTION:
OTTER CREEK 48.0
END DESCRIPTION:
XS GIS Cut Line= 3
      3710699.57     10710360.19      3710331.41     10710360.47
      3709949.61     10710010.19
#Sta/Elev= 30
  4686.9  387.74  4776.9   381.7  4846.9  375.18  4966.9  367.06  4986.9   368.7
  4996.9  359.84  5003.9   357.9  5006.6   357.4  5009.9   357.9  5016.9  368.05
  5026.9  369.83  5031.2  369.72  5091.9  368.86  5141.3  369.32  5183.8   367.8
  5247.5  368.54  5261.5  361.12  5268.9   360.8  5275.7  366.06  5283.1   367.2
  5289.9  365.89  5297.3  367.94    5354  368.63    5375  370.96  5424.3  373.81
  5438.5   375.9  5445.9  375.67  5452.7  377.01  5509.4  382.07  5573.2  385.08
#Mann= 4 ,-1 , 0
  4686.9     .05       0  5003.9     .03       0  5009.9     .05       0
  5031.2     .12       0
Bank Sta=5247.5,5297.3
XS Rating Curve= 0 ,0
Exp/Cntr=0.3,0.1

Type RM Length L Ch R = 1 ,23817   ,382,382,382
BEGIN DESCRIPTION:
OTTER CREEK 47.0
END DESCRIPTION:
XS GIS Cut Line= 3
      3710749.57     10710310.15      3710349.61     10709910.19
       3710099.6     10709860.19
#Sta/Elev= 30
  4455.3  389.47  4540.1  384.93  4554.2  383.62  4568.4  383.49    4625  380.73
  4639.1  380.67  4667.4  378.93  4695.7  377.94  4738.1  374.91  4752.2  374.66
  4780.5  371.83  4837.1  368.16  4907.8  366.99  4964.4  366.93  4978.5  366.23
  4989.7   355.4  4992.4   354.9  4995.7   355.4  5006.8  360.55  5017.4  366.76
  5031.1  365.92  5082.1  368.48  5122.9  371.84  5133.1  372.19  5143.3  373.54
  5153.5   373.8  5163.7  375.22  5204.5  377.67  5214.7  379.33  5275.9   382.1
#Mann= 3 ,-1 , 0
  4455.3     .05       0  4989.7     .07       0  4995.7     .12       0
Bank Sta=4978.5,5017.4
XS Rating Curve= 0 ,0
Exp/Cntr=0.3,0.1

Type RM Length L Ch R = 1 ,23435   ,488,488,488
BEGIN DESCRIPTION:
Mapping XS 8246715e
END DESCRIPTION:
XS GIS Cut Line= 2
      3710856.83     10709683.86      3710190.18     10709485.95
#Sta/Elev= 30
  4657.9  375.61  4780.2  367.43  4880.2  365.64  4926.2   365.7  4938.1  364.74
  4957.5  365.93  4971.3  365.55  4978.4  362.41  4988.8  354.23  4996.2  353.68
    4999  353.18  5002.2  353.68  5004.5  363.08  5009.7   364.7  5020.1  365.85
  5037.7  365.49  5051.4   364.3  5109.4  366.43  5134.8  368.65  5166.1  369.73
    5187  371.52  5219.5  373.21  5228.7   372.8  5239.2  374.18  5270.4  375.54
  5280.7  377.58  5285.9  376.98  5291.3  378.09  5319.1  379.65  5353.3  380.76
#Mann= 4 ,-1 , 0
  4657.9     .05       0  4880.2     .12       0  4996.2     .07       0
  5002.2     .12       0
Bank Sta=4971.3,5020.1
XS Rating Curve= 0 ,0
Exp/Cntr=0.3,0.1

Type RM Length L Ch R = 1 ,22947   ,511,511,511
BEGIN DESCRIPTION:
Mapping XS 40b7543c
END DESCRIPTION:
XS GIS Cut Line= 2
      3710997.49     10709178.65      3710346.41     10709215.11
#Sta/Elev= 30
    4770  376.65    4848  369.03    4858  368.89    4878  367.22    4885  368.01
    4890  366.37  4898.1   366.2  4908.1  364.62  4928.1  363.81  4948.2  361.71
  4968.2  357.48  4978.2   353.6  4984.8     353  4985.2  352.96    4988  352.46
  4991.2  352.96  4998.2  356.17  5008.2  362.46  5018.3  363.62  5048.3  362.97
  5069.6  363.82  5098.4  363.41  5128.4  364.37  5158.5  365.71  5244.1  372.03
  5249.1  371.71  5268.7  372.99  5338.8  373.54  5378.8   374.8  5422.1  374.67
#Mann= 4 ,-1 , 0
    4770     .05       0  4984.8     .12       0  4985.2     .07       0
  4991.2     .12       0
Bank Sta=4928.1,5018.3
XS Rating Curve= 0 ,0
Exp/Cntr=0.3,0.1

Type RM Length L Ch R = 1 ,22436   ,486,486,486
BEGIN DESCRIPTION:
OTTER CREEK 44.0
END DESCRIPTION:
XS GIS Cut Line= 3
      3711049.61     10708910.19      3710749.61     10708710.19
       3710449.6     10708610.18
#Sta/Elev= 30
  4624.8  376.99  4647.3  375.45  4683.4  371.23  4719.5  370.47  4746.5  372.79
  4761.5  372.41  4771.9  371.06  4782.5  369.64  4827.6  366.47  4841.1  366.61
  4854.7  365.04  4899.7   362.4  4905.7  360.43  4920.8  362.15  4977.8  361.44
  4982.4  355.62    4988  355.62  4992.9  350.61  4995.7  350.11  4998.9  350.61
  5006.4  357.77    5017  361.02  5027.5  362.14  5122.4  365.83  5185.6  370.14
  5196.2  372.05  5206.7  371.82  5227.8  373.26  5274.4  377.71  5301.6  378.96
#Mann= 5 ,-1 , 0
  4624.8     .05       0  4771.9     .12       0  4992.9     .07       0
  4998.9     .12       0  5274.4     .05       0
Bank Sta=4977.8,5017
XS Rating Curve= 0 ,0
Exp/Cntr=0.3,0.1

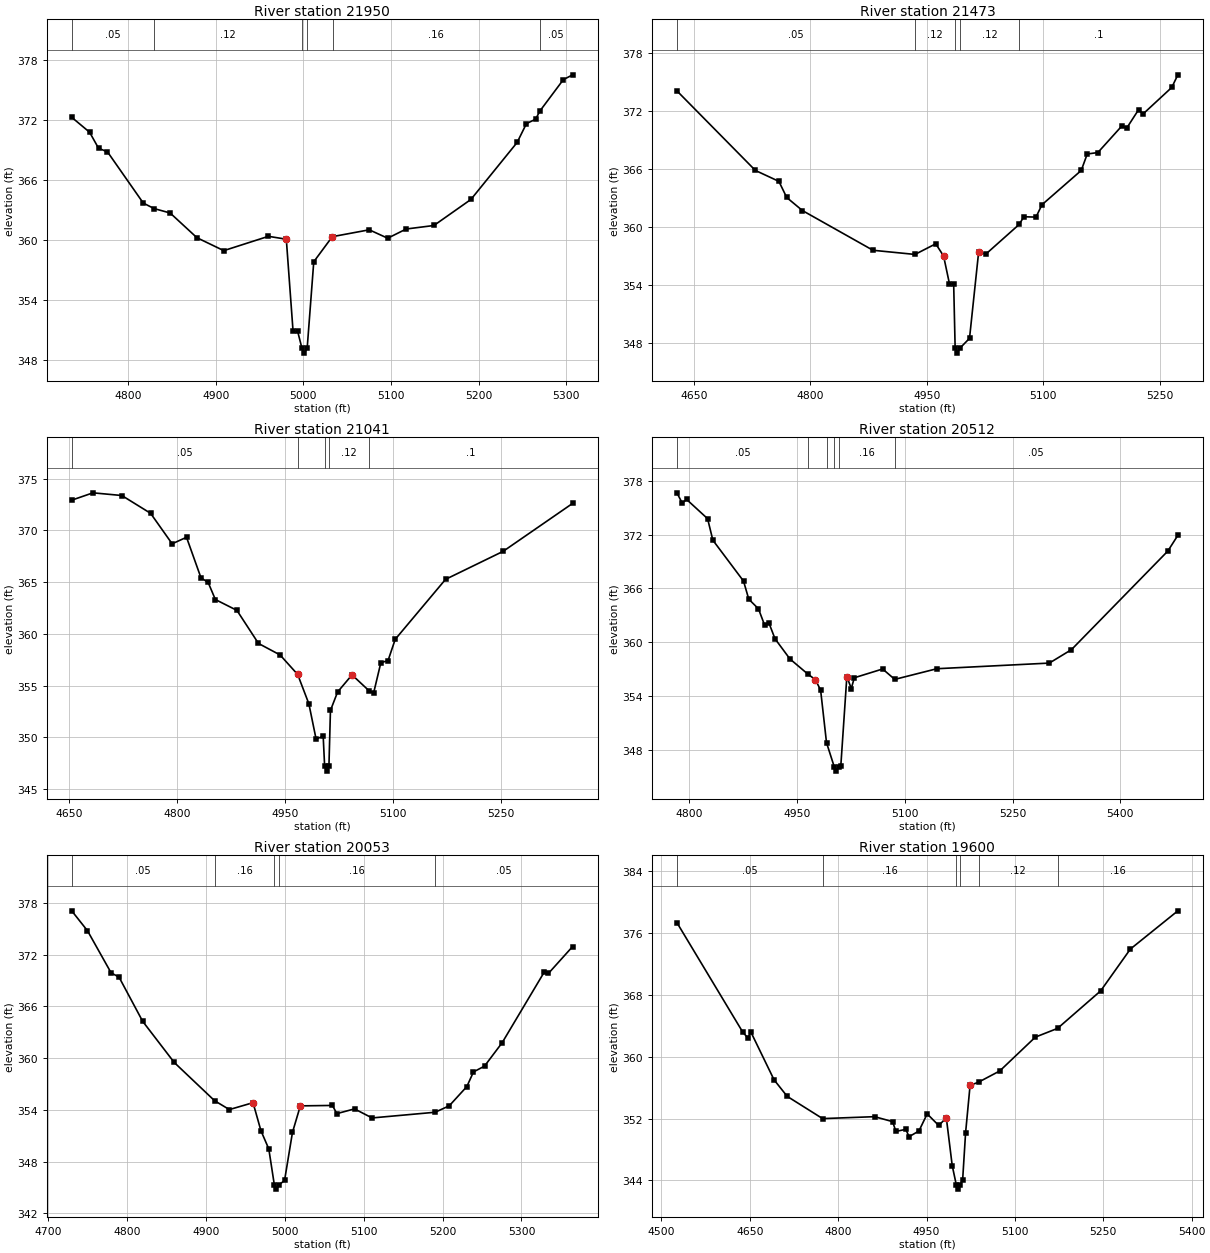
Type RM Length L Ch R = 1 ,21950   ,477,477,477
BEGIN DESCRIPTION:
OTTER CREEK 43.0
END DESCRIPTION:
XS GIS Cut Line= 3
      3711149.59     10708360.19      3710899.61     10708310.19
      3710599.57     10708210.18
#Sta/Elev= 30
  4735.9  372.26  4756.3  370.77  4766.5  369.17  4776.7  368.81  4817.5   363.7
  4829.8  363.15  4848.1  362.71  4878.7  360.24  4909.3  358.95  4960.2  360.38
  4980.6  360.09  4988.3   350.9  4993.5   350.9  4998.4  349.22  5001.1  348.72
  5004.4  349.22  5011.9  357.84    5033  360.34  5033.4  360.35  5075.2  361.03
  5096.2  360.19  5117.3  361.11  5148.9  361.46  5191.1  364.06  5243.8  369.75
  5254.4  371.63  5264.9  372.07  5269.6  372.87  5296.5  376.02  5307.1   376.5
#Mann= 6 ,-1 , 0
  4735.9     .05       0  4829.8     .12       0  4998.4     .07       0
  5004.4     .12       0  5033.4     .16       0  5269.6     .05       0
Bank Sta=4980.6,5033
XS Rating Curve= 0 ,0
Exp/Cntr=0.3,0.1

Type RM Length L Ch R = 1 ,21473   ,432,432,432
BEGIN DESCRIPTION:
OTTER CREEK 42.0
END DESCRIPTION:
XS GIS Cut Line= 3
      3711399.58     10707960.18      3711049.61     10707910.19
      3710799.58     10707760.17
#Sta/Elev= 30
  4628.2  374.13  4729.2   365.9  4759.5  364.77  4769.6   363.1  4789.8  361.75
  4880.7  357.64  4934.8  357.21  4961.5  358.31  4971.6  357.05  4979.2  354.16
  4984.6  354.16  4986.5   347.5  4989.2     347  4992.5   347.5    5005  348.53
  5016.7  357.42  5026.4  357.27  5068.9  360.31    5075  361.11  5090.6  361.07
  5098.3  362.35  5148.9   365.9  5156.6   367.6  5170.3  367.75  5201.4  370.52
  5207.2  370.25  5222.7  372.18  5228.6  371.75  5265.5  374.49  5273.3  375.79
#Mann= 5 ,-1 , 0
  4628.2     .05       0  4934.8     .12       0  4986.5     .07       0
  4992.5     .12       0  5068.9      .1       0
Bank Sta=4971.6,5016.7
XS Rating Curve= 0 ,0
Exp/Cntr=0.3,0.1

Type RM Length L Ch R = 1 ,21041   ,529,529,529
BEGIN DESCRIPTION:
Mapping XS 68dcb370
END DESCRIPTION:
XS GIS Cut Line= 2
      3711499.22     10707531.08      3710802.97     10707558.79
#Sta/Elev= 30
  4653.3  372.93  4682.9  373.64    4723  373.38    4763  371.66    4793  368.71
    4813  369.34  4833.1  365.42  4843.1  364.97  4853.1  363.32  4883.1  362.27
  4913.1  359.07  4943.1  357.96  4967.6  356.07  4983.2  353.23  4993.2  349.83
  5003.1  350.09  5005.1  347.22  5007.8  346.72  5011.1  347.22  5013.2  352.59
  5023.2  354.38  5043.2  356.03  5066.8   354.5  5073.2  354.26  5083.3  357.21
  5093.3  357.41  5103.3  359.47  5173.3  365.27  5253.4  367.98  5350.1  372.62
#Mann= 5 ,-1 , 0
  4653.3     .05       0  4967.6     .12       0  5005.1     .07       0
  5011.1     .12       0  5066.8      .1       0
Bank Sta=4967.6,5043.2
XS Rating Curve= 0 ,0
Exp/Cntr=0.3,0.1

Type RM Length L Ch R = 1 ,20512   ,459,459,459
BEGIN DESCRIPTION:
OTTER CREEK 40.0
END DESCRIPTION:
XS GIS Cut Line= 3
      3711349.61     10706960.18      3711149.61     10707110.19
      3710749.63     10707310.18
#Sta/Elev= 30
  4782.8  376.68  4790.1  375.54  4796.3  375.94  4825.5  373.79  4832.8  371.39
  4875.5  366.82  4882.8   364.8  4896.3  363.72  4904.7  361.93  4910.9  362.13
  4919.3  360.38  4940.1  358.12  4965.5   356.4  4975.5  355.81  4982.8  354.64
    4991  348.77  5001.7  346.09  5004.4  345.59  5007.7  346.09  5010.9  346.17
  5019.3  356.15  5025.5  354.82  5029.7  356.02  5069.1     357    5086  355.84
  5144.6  357.03  5301.1  357.66  5331.9  359.16    5466  370.17    5480  371.93
#Mann= 6 ,-1 , 0
  4782.8     .05       0  4965.5     .12       0    4991     .16       0
  5001.7     .07       0  5007.7     .16       0    5086     .05       0
Bank Sta=4975.5,5019.3
XS Rating Curve= 0 ,0
Exp/Cntr=0.3,0.1

Type RM Length L Ch R = 1 ,20053   ,453,453,453
BEGIN DESCRIPTION:
OTTER CREEK 39.0
END DESCRIPTION:
XS GIS Cut Line= 3
       3711299.6     10706710.19      3710999.61     10706710.19
      3710699.61     10706860.19
#Sta/Elev= 30
  4729.5   377.1  4749.5  374.79  4779.5   369.9  4789.5  369.41  4819.5  364.28
  4859.5  359.51  4910.7  355.07  4929.5  354.04  4959.5  354.84  4969.5  351.59
  4979.5  349.47  4986.5  345.31  4989.2  344.81  4992.5  345.31  4999.5  345.82
  5009.5  351.39  5019.5  354.47  5060.2  354.52  5065.8  353.57  5088.2  354.12
  5110.5  353.07  5190.5  353.73  5208.4  354.48  5230.7  356.71  5239.1  358.41
  5253.1  359.08  5275.5   361.8  5328.6  369.95  5334.2  369.84  5364.9  372.96
#Mann= 5 ,-1 , 0
  4729.5     .05       0  4910.7     .16       0  4986.5     .07       0
  4992.5     .16       0  5190.5     .05       0
Bank Sta=4959.5,5019.5
XS Rating Curve= 0 ,0
Exp/Cntr=0.3,0.1

Type RM Length L Ch R = 1 ,19600   ,628,628,628
BEGIN DESCRIPTION:
OTTER CREEK 38.0
END DESCRIPTION:
XS GIS Cut Line= 3
      3711349.58     10706560.17      3710949.61     10706360.19
       3710549.6     10706310.19
#Sta/Elev= 30
  4526.3  377.36  4638.1  363.18  4646.5  362.45    4652  363.17  4691.2  357.01
  4713.5  354.87  4773.6  351.99  4861.7  352.24  4892.4   351.6    4898  350.33
  4914.8   350.6  4920.4  349.65  4937.1  350.39  4951.1   352.6  4970.7   351.1
  4983.6  352.09  4993.6   345.9  5000.7  343.36  5003.5  342.86  5006.7  343.36
  5011.3  344.07  5016.3  350.16  5023.9  356.29  5038.3  356.71  5074.3  358.16
  5134.7  362.54  5172.4  363.67  5245.6  368.53    5296  373.94  5376.6  378.89
#Mann= 6 ,-1 , 0
  4526.3     .05       0  4773.6     .16       0  5000.7     .07       0
  5006.7     .16       0  5038.3     .12       0  5172.4     .16       0
Bank Sta=4983.6,5023.9
XS Rating Curve= 0 ,0
Exp/Cntr=0.3,0.1

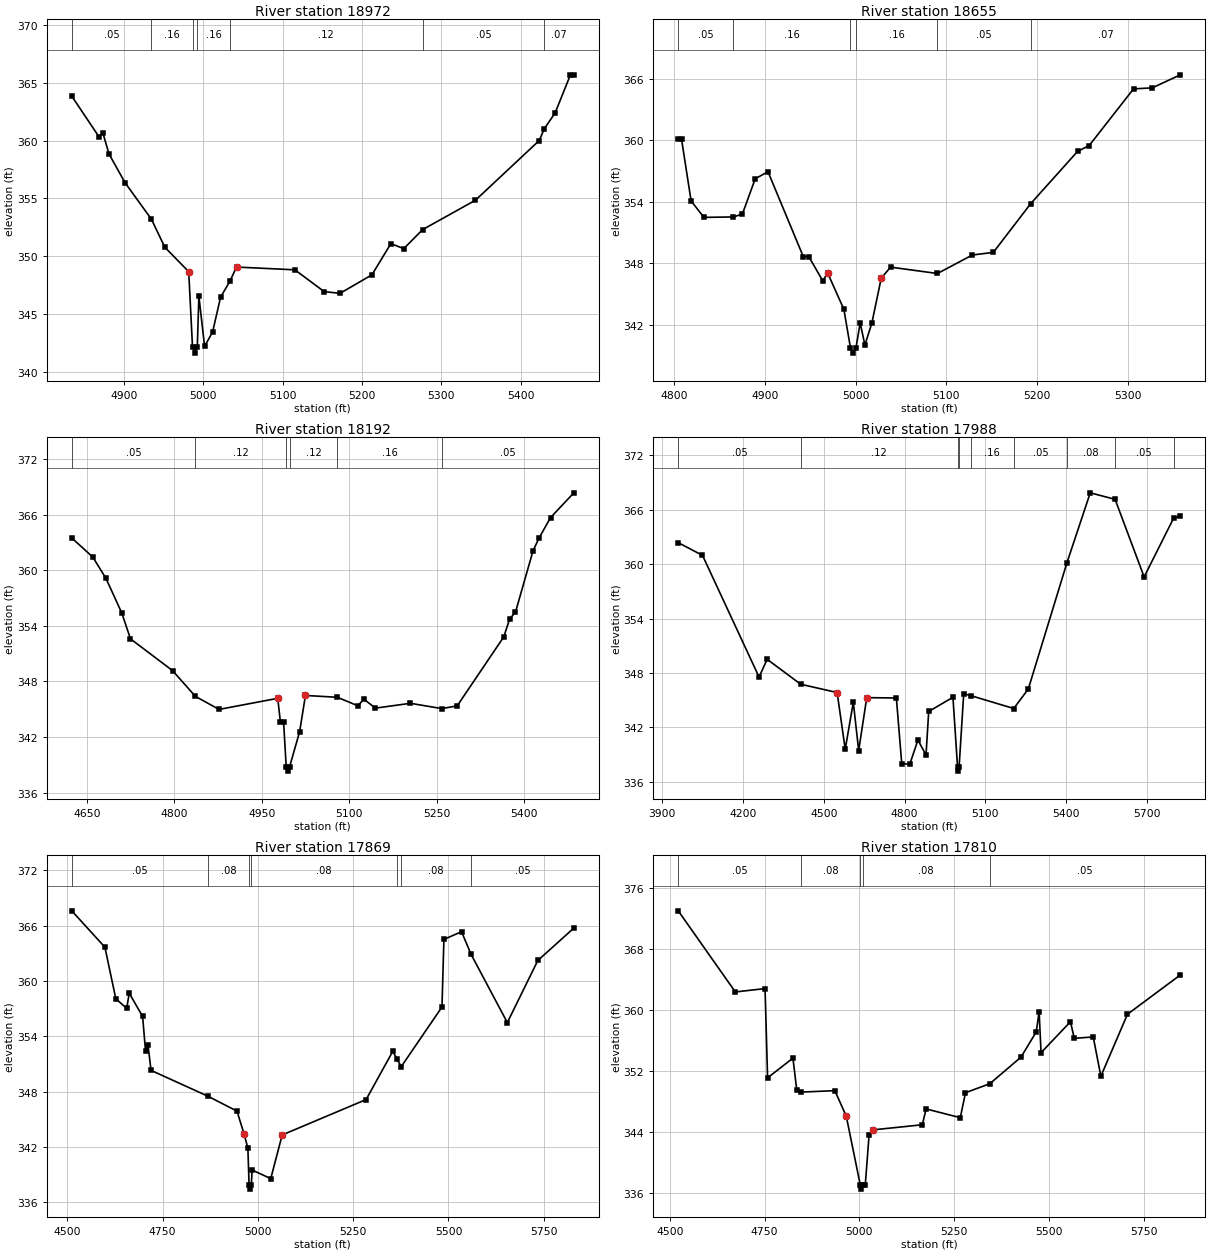
Type RM Length L Ch R = 1 ,18972   ,317,317,317
BEGIN DESCRIPTION:
OTTER CREEK 37.0
END DESCRIPTION:
XS GIS Cut Line= 2
      3711446.38     10705938.19      3710816.13      10705886.1
#Sta/Elev= 30
  4834.5  363.83  4868.6  360.34  4873.7  360.65  4881.4  358.84  4901.5  356.37
  4934.8  353.21  4951.7  350.79  4981.8  348.68  4986.6  342.15  4989.3  341.65
  4992.6  342.15  4994.6  346.56  5001.8  342.23  5011.9  343.48  5021.9  346.47
  5033.8  347.87    5042  349.08  5115.5  348.84  5152.4  346.96  5172.4  346.81
  5212.6  348.41  5236.4   351.1  5252.7  350.67  5276.4  352.31    5343  354.85
  5423.3     360  5429.7  361.02  5443.3  362.38  5462.6  365.67  5466.9  365.67
#Mann= 7 ,-1 , 0
  4834.5     .05       0  4934.8     .16       0  4986.6     .07       0
  4992.6     .16       0  5033.8     .12       0  5276.4     .05       0
  5429.7     .07       0
Bank Sta=4981.8,5042
XS Rating Curve= 0 ,0
Exp/Cntr=0.3,0.1

Type RM Length L Ch R = 1 ,18655   ,463,463,463
BEGIN DESCRIPTION:
OTTER CREEK 36.0
END DESCRIPTION:
XS GIS Cut Line= 3
      3711399.64     10705710.22      3711299.61     10705610.19
      3710899.59     10705710.19
#Sta/Elev= 30
  4804.4  360.13    4808  360.13  4818.6  354.09  4832.7  352.49  4865.3  352.53
  4875.2  352.82  4889.3  356.25  4903.4  356.94  4942.3  348.67  4948.4  348.67
  4963.9  346.29  4969.1  347.09  4987.1  343.53  4994.4  339.76  4997.2  339.26
  5000.4  339.76  5005.1   342.2  5010.3  340.04    5018   342.2  5028.3  346.56
  5038.6  347.64  5090.3  347.02  5128.8  348.82    5152  349.08  5193.3  353.84
  5244.8  358.91  5257.7  359.49  5306.6  365.01  5327.3  365.11  5358.2  366.38
#Mann= 6 ,-1 , 0
  4804.4     .05       0  4865.3     .16       0  4994.4     .07       0
  5000.4     .16       0  5090.3     .05       0  5193.3     .07       0
Bank Sta=4969.1,5028.3
XS Rating Curve= 0 ,0
Exp/Cntr=0.3,0.1

Type RM Length L Ch R = 1 ,18192   ,204,204,204
BEGIN DESCRIPTION:
OTTER CREEK 35.0
END DESCRIPTION:
XS GIS Cut Line= 3
       3711649.6     10705510.18      3711449.61     10705210.19
      3710949.66     10705210.19
#Sta/Elev= 30
  4624.4  363.51  4660.4  361.45    4683  359.14    4710  355.42    4725  352.61
  4797.2  349.17  4836.3  346.39  4876.8  344.98  4977.4  346.18  4981.9  343.66
  4987.4  343.66  4991.9  338.81  4994.7  338.31  4997.9  338.81  5014.9  342.57
  5024.9  346.49  5079.7  346.29  5114.9  345.37  5124.9  346.09  5144.9  345.12
  5204.9  345.64  5258.3  345.07  5284.9  345.36  5364.9  352.83  5374.9  354.76
  5384.9   355.5  5414.9  362.11  5424.9  363.46  5444.9  365.71  5484.9  368.39
#Mann= 6 ,-1 , 0
  4624.4     .05       0  4836.3     .12       0  4991.9     .07       0
  4997.9     .12       0  5079.7     .16       0  5258.3     .05       0
Bank Sta=4977.4,5024.9
XS Rating Curve= 0 ,0
Exp/Cntr=0.3,0.1

Type RM Length L Ch R = 1 ,17988   ,119,119,119
BEGIN DESCRIPTION:
Mapping XS fc8727b4
END DESCRIPTION:
XS GIS Cut Line= 2
      3712429.73     10705034.56      3710565.19     10705003.31
#Sta/Elev= 30
  3959.4  362.37  4049.5  360.97  4259.6  347.54  4289.6   349.5  4414.1  346.75
  4549.6  345.83  4579.6  339.57  4609.6  344.76  4629.6  339.43  4659.6  345.27
  4769.6  345.23  4789.6  337.96  4819.6  337.94  4849.6  340.59  4879.7  338.94
  4889.7  343.74  4979.7  345.31  4996.7  337.66  4999.4  337.16  5002.7  337.66
  5019.7   345.7  5046.2  345.49  5205.5  344.07  5259.7  346.23  5403.3  360.17
  5489.7  367.87    5582  367.15  5689.8  358.59  5798.9  365.05  5824.2  365.29
#Mann= 9 ,-1 , 0
  3959.4     .05       0  4414.1     .12       0  4996.7     .07       0
  5002.7     .12       0  5046.2     .16       0  5205.5     .05       0
  5403.3     .08       0    5582     .05       0  5798.9     .07       0
Bank Sta=4549.6,4659.6
XS Rating Curve= 0 ,0
Exp/Cntr=0.3,0.1

Type RM Length L Ch R = 1 ,17869   ,59,59,59
BEGIN DESCRIPTION:
Mapping XS 00d45b68
END DESCRIPTION:
XS GIS Cut Line= 5
      3711740.46     10704688.56      3711558.19     10704905.55
      3711411.49     10704903.81      3711115.48     10704914.23
      3710525.24     10704940.27
#Sta/Elev= 30
  4511.8   367.6  4598.7  363.66  4627.3  358.08  4655.9  357.02  4662.5  358.68
  4697.6  356.16  4705.4  352.37  4711.9  353.01  4719.7  350.31  4868.4  347.52
  4945.3  345.89  4963.8  343.41  4973.8  341.88  4976.9  337.94  4979.7  337.44
  4982.9  337.94  4984.9  339.51  5033.8  338.58  5063.8  343.31    5284  347.15
  5354.1  352.39  5364.1  351.57  5376.2  350.72    5483  357.18    5488   364.5
  5534.2  365.34  5559.5  362.87  5654.4  355.49  5734.4  362.22  5828.9  365.73
#Mann= 7 ,-1 , 0
  4511.8     .05       0  4868.4     .08       0  4976.9     .07       0
  4982.9     .08       0  5364.1     .05       0  5376.2     .08       0
  5559.5     .05       0
Bank Sta=4963.8,5063.8
XS Rating Curve= 0 ,0
Exp/Cntr=0.3,0.1

Type RM Length L Ch R = 1 ,17810   ,413,413,413
BEGIN DESCRIPTION:
OTTER CREEK 34.0
END DESCRIPTION:
XS GIS Cut Line= 5
      3711714.42     10704645.17      3711575.55      10704836.1
      3711388.92     10704853.47      3711263.05     10704844.78
      3710490.44     10704883.85
#Sta/Elev= 30
  4522.5     373    4673  362.35  4751.3  362.79    4758  351.07  4824.8  353.66
  4834.9  349.47  4847.2   349.2  4935.3  349.39  4965.4  346.03  5002.5  336.96
  5005.2  336.46  5008.5  336.96  5015.5  337.03  5025.5  343.57  5035.6  344.24
  5165.8  344.91  5175.8  346.99  5265.9  345.84  5279.6  349.12  5343.7   350.3
  5426.1   353.8  5466.1  357.11  5473.7  359.76  5478.7  354.37  5556.3  358.44
  5566.3  356.26  5616.3  356.44  5636.4  351.28  5706.5  359.42  5845.8  364.58
#Mann= 5 ,-1 , 0
  4522.5     .05       0  4847.2     .08       0  5002.5     .07       0
  5008.5     .08       0  5343.7     .05       0
Bank Sta=4965.4,5035.6
XS Rating Curve= 0 ,0
Exp/Cntr=0.3,0.1

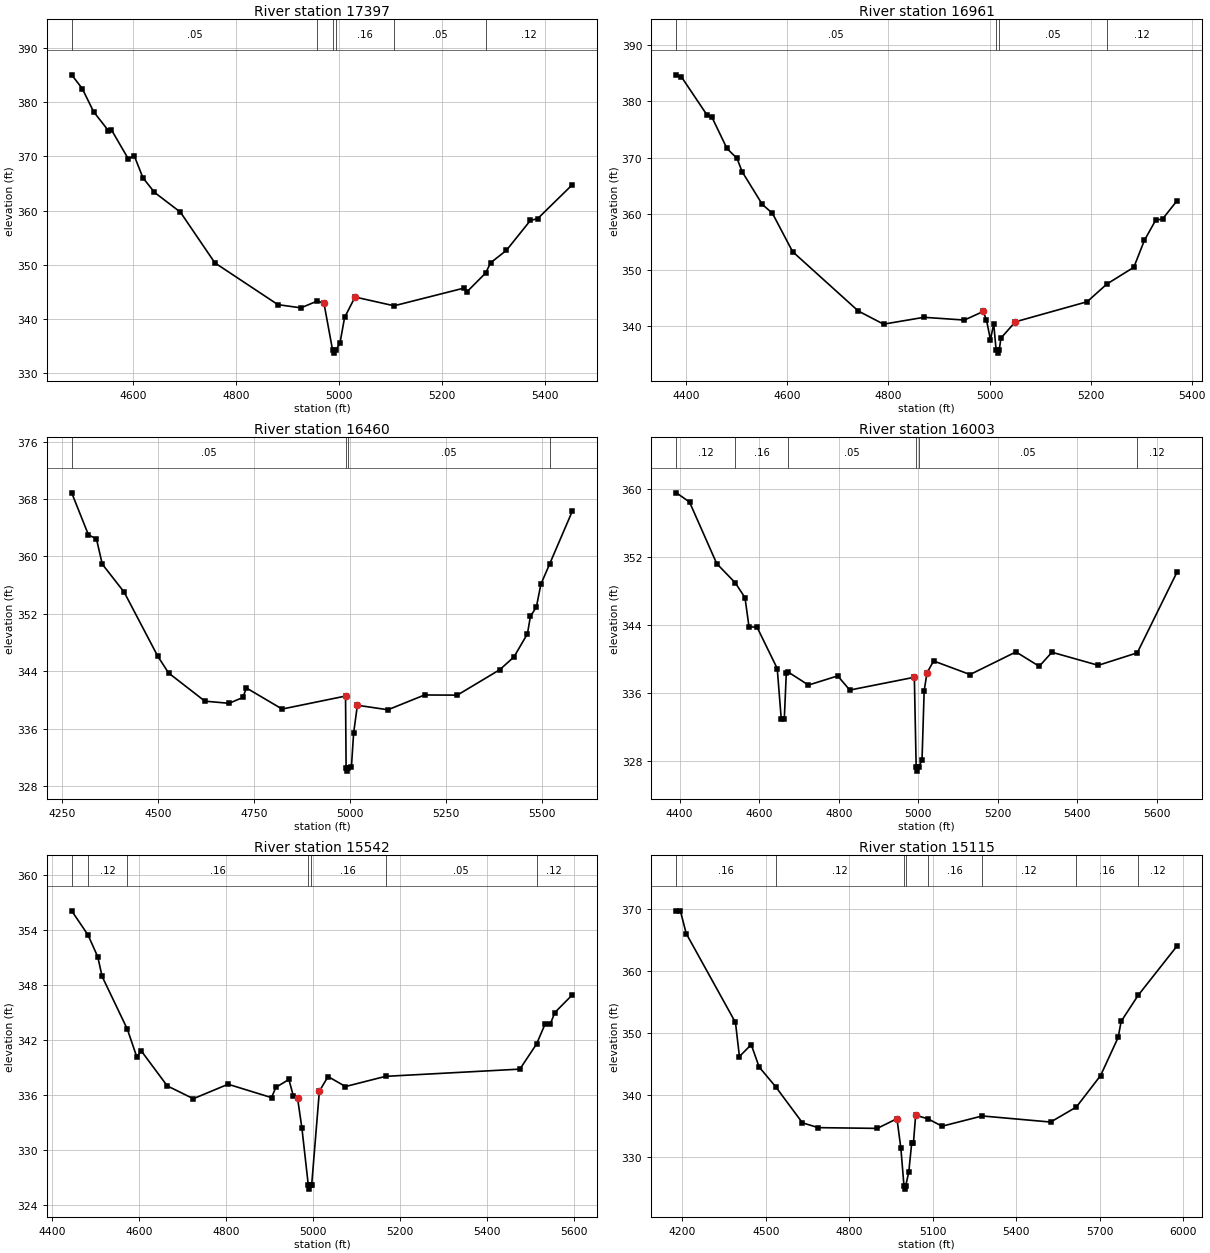
Type RM Length L Ch R = 1 ,17397   ,436,436,436
BEGIN DESCRIPTION:
OTTER CREEK 33.0
END DESCRIPTION:
XS GIS Cut Line= 3
      3711527.82     10704363.01      3711093.78     10704580.03
      3710613.32     10704657.94
#Sta/Elev= 30
  4480.3  385.08  4500.7  382.55    4523  378.24  4551.6  374.76  4557.2  374.96
  4590.1  369.57  4601.9  370.09  4618.7  366.04  4641.1  363.35  4691.4   359.7
  4758.4  350.32  4880.8   342.6  4925.5  342.01  4957.1  343.26  4970.2  342.88
  4987.1  334.14  4989.8  333.64  4993.1  334.14  5001.5  335.57  5010.3  340.23
  5030.6  344.01  5106.4  342.39    5243  345.68    5248  344.98  5284.2  348.44
    5294  350.35  5324.4  352.62  5371.3  358.18  5385.1  358.48  5452.3  364.74
#Mann= 6 ,-1 , 0
  4480.3     .05       0  4957.1     .16       0  4987.1     .07       0
  4993.1     .16       0  5106.4     .05       0  5284.2     .12       0
Bank Sta=4970.2,5030.6
XS Rating Curve= 0 ,0
Exp/Cntr=0.3,0.1

Type RM Length L Ch R = 1 ,16961   ,501,501,501
BEGIN DESCRIPTION:
OTTER CREEK 32.0
END DESCRIPTION:
XS GIS Cut Line= 3
      3711449.62     10704210.19      3710849.61     10704210.19
      3710599.62     10704510.17
#Sta/Elev= 30
  4380.3  384.74  4390.3  384.37  4440.3  377.66  4450.3  377.25  4480.3  371.63
  4500.3  369.85  4510.3   367.5  4550.3  361.66  4570.3  360.08  4610.3  353.24
  4740.3  342.67  4790.3  340.33  4870.3  341.55  4950.3  341.06  4987.5  342.59
    4994  341.05  5001.8  337.56  5008.3  340.38  5013.1  335.67  5015.9  335.17
  5019.1  335.67  5022.6  337.85  5051.2  340.75  5193.1  344.32  5232.3  347.48
  5285.6  350.46  5306.4  355.24  5328.5   358.8  5342.8   359.1  5370.8  362.28
#Mann= 4 ,-1 , 0
  4380.3     .05       0  5013.1     .03       0  5019.1     .05       0
  5232.3     .12       0
Bank Sta=4987.5,5051.2
XS Rating Curve= 0 ,0
Exp/Cntr=0.3,0.1

Type RM Length L Ch R = 1 ,16460   ,457,457,457
BEGIN DESCRIPTION:
OTTER CREEK 31.0
END DESCRIPTION:
XS GIS Cut Line= 3
      3711349.62      10704160.2      3710749.61     10703760.19
      3710249.63     10704060.18
#Sta/Elev= 30
  4274.5  368.86  4318.1  363.01  4339.1  362.43  4354.1  358.93  4411.2  355.02
  4498.4  346.13  4526.9  343.76  4621.6  339.83  4684.6  339.53  4720.7  340.35
  4729.7  341.67  4822.9  338.73  4988.1  340.54  4989.6  330.58  4992.4  330.08
  4995.6  330.58  5003.4  330.63  5009.2  335.39    5019  339.26  5098.6  338.63
  5193.9  340.69  5279.4  340.67  5390.2  344.22  5427.1     346  5462.1  349.21
  5469.9  351.65  5485.4  352.94  5497.1  356.11  5520.5  359.01  5578.7  366.26
#Mann= 4 ,-1 , 0
  4274.5     .05       0  4989.6     .03       0  4995.6     .05       0
  5520.5     .12       0
Bank Sta=4988.1,5019
XS Rating Curve= 0 ,0
Exp/Cntr=0.3,0.1

Type RM Length L Ch R = 1 ,16003   ,461,461,461
BEGIN DESCRIPTION:
OTTER CREEK 30.0
END DESCRIPTION:
XS GIS Cut Line= 3
      3711299.62     10703210.19      3710699.61     10703310.19
       3710099.6     10703060.19
#Sta/Elev= 30
  4391.9  359.59  4424.9   358.5  4493.3  351.24    4540  348.97  4564.3  347.23
  4574.4  343.79  4594.7  343.74  4645.4  338.87  4655.5   332.9  4663.1  332.86
  4668.2  338.33  4672.8  338.46  4723.9  336.92  4797.4     338  4827.8  336.33
  4990.1  337.84  4994.7  327.27  4997.4  326.77  5000.7  327.27  5009.4  328.06
  5014.8  336.24  5021.9  338.36  5038.6  339.76  5130.2  338.16  5245.6  340.83
  5304.1  339.13    5336  340.79  5452.5  339.25  5550.6  340.72  5650.2  350.21
#Mann= 6 ,-1 , 0
  4391.9     .12       0    4540     .16       0  4672.8     .05       0
  4994.7     .03       0  5000.7     .05       0  5550.6     .12       0
Bank Sta=4990.1,5021.9
XS Rating Curve= 0 ,0
Exp/Cntr=0.3,0.1

Type RM Length L Ch R = 1 ,15542   ,427,427,427
BEGIN DESCRIPTION:
OTTER CREEK 29.0
END DESCRIPTION:
XS GIS Cut Line= 3
      3711299.62     10702860.19      3710749.61     10702860.19
       3710149.6     10702910.19
#Sta/Elev= 30
  4444.4  356.08  4481.9  353.45  4504.4  351.06  4514.4  348.92  4572.5  343.16
  4594.4  340.11  4604.4   340.8  4664.4  336.97  4724.4  335.57  4804.4  337.15
  4904.4  335.69  4914.4  336.81  4944.4  337.67  4954.4  335.91  4964.4  335.61
  4974.4  332.35  4988.9   326.2  4991.7   325.7  4994.9   326.2  4996.9   326.2
  5014.5  336.38  5034.5  337.99  5074.7   336.9  5166.8  338.01  5476.1   338.8
  5514.5  341.54  5533.8  343.68  5546.3  343.73  5556.4  344.97  5596.5  346.89
#Mann= 7 ,-1 , 0
  4444.4     .16       0  4481.9     .12       0  4572.5     .16       0
  4988.9     .07       0  4994.9     .16       0  5166.8     .05       0
  5514.5     .12       0
Bank Sta=4964.4,5014.5
XS Rating Curve= 0 ,0
Exp/Cntr=0.3,0.1

Type RM Length L Ch R = 1 ,15115   ,442,442,442
BEGIN DESCRIPTION:
OTTER CREEK 28.0
END DESCRIPTION:
XS GIS Cut Line= 3
       3711349.6     10701860.19      3710749.61     10702460.19
      3709849.61     10702760.19
#Sta/Elev= 30
  4179.2   369.7  4193.3  369.71  4214.5  366.05  4391.3  351.73  4405.5  346.25
  4447.9  348.17  4476.2  344.57  4535.4   341.4  4631.7  335.58  4688.3   334.8
  4900.4  334.68  4971.2  336.24  4985.3  331.45  4996.4   325.4  4999.2   324.9
  5002.4   325.4  5013.6  327.64  5024.2  332.36  5030.4  332.36  5038.3  336.79
  5082.1  336.23  5133.1  335.03  5277.5  336.68  5523.1   335.7  5615.4  338.12
  5702.3  343.18  5765.6  349.33  5776.1   351.9    5837  356.09  5976.4  364.02
#Mann= 8 ,-1 , 0
  4179.2     .16       0  4535.4     .12       0  4996.4     .07       0
  5002.4     .12       0  5082.1     .16       0  5277.5     .12       0
  5615.4     .16       0    5837     .12       0
Bank Sta=4971.2,5038.3
XS Rating Curve= 0 ,0
Exp/Cntr=0.3,0.1