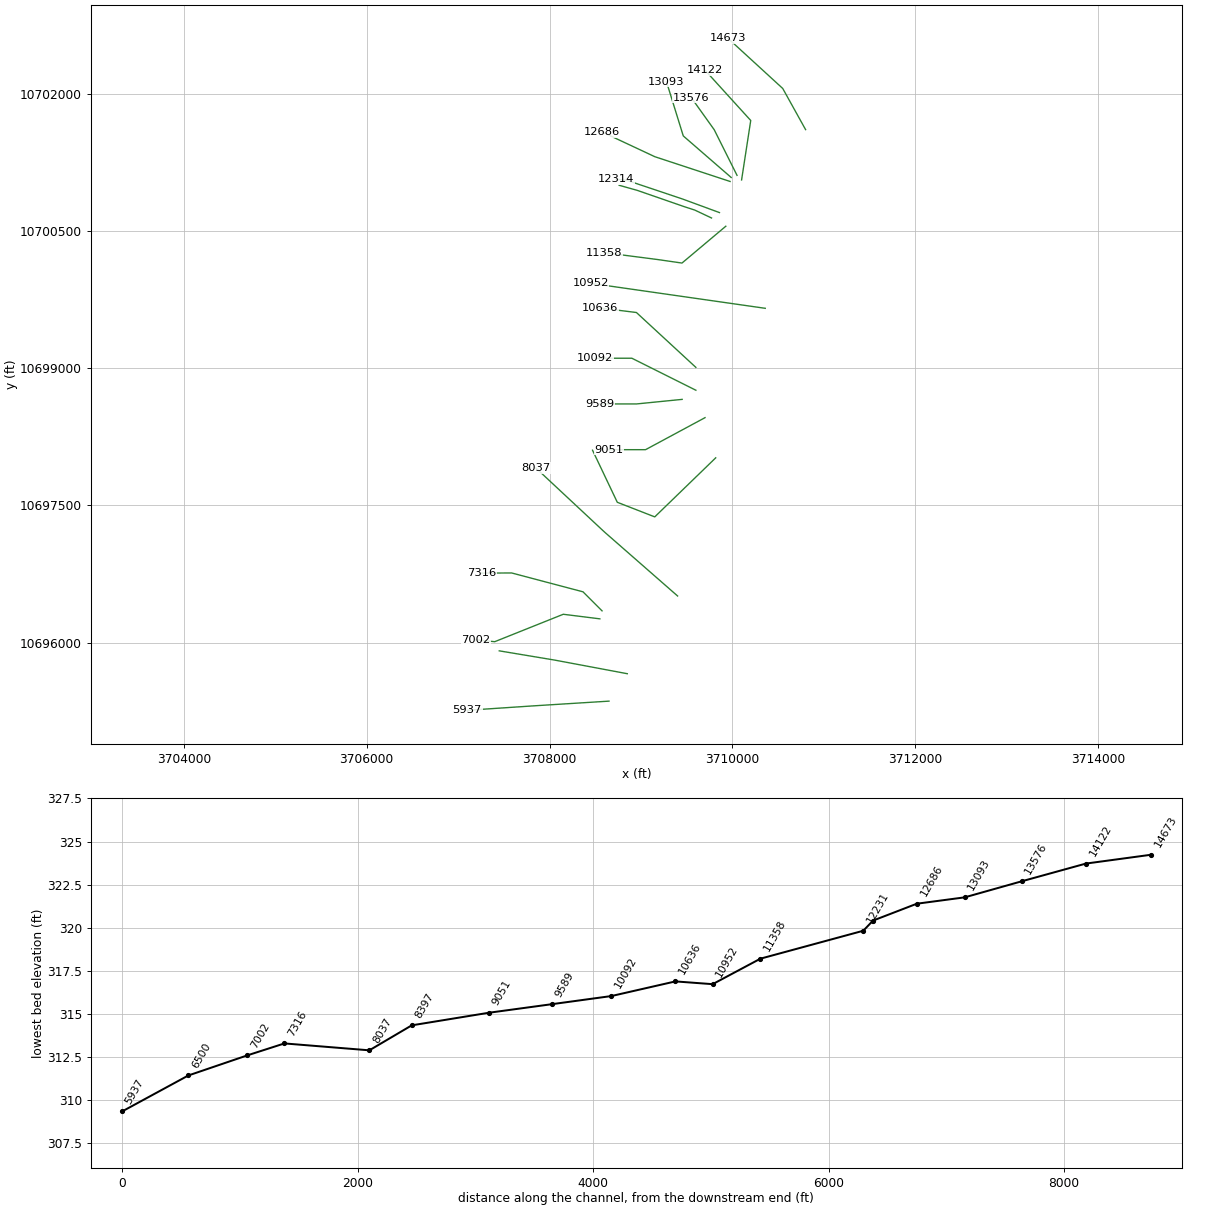
HEC-RAS study OTTER CREEK.prj: OTTER CREEK Base Level Engineering

--- OTTER CREEK.g01 (geometry) --- (continued)

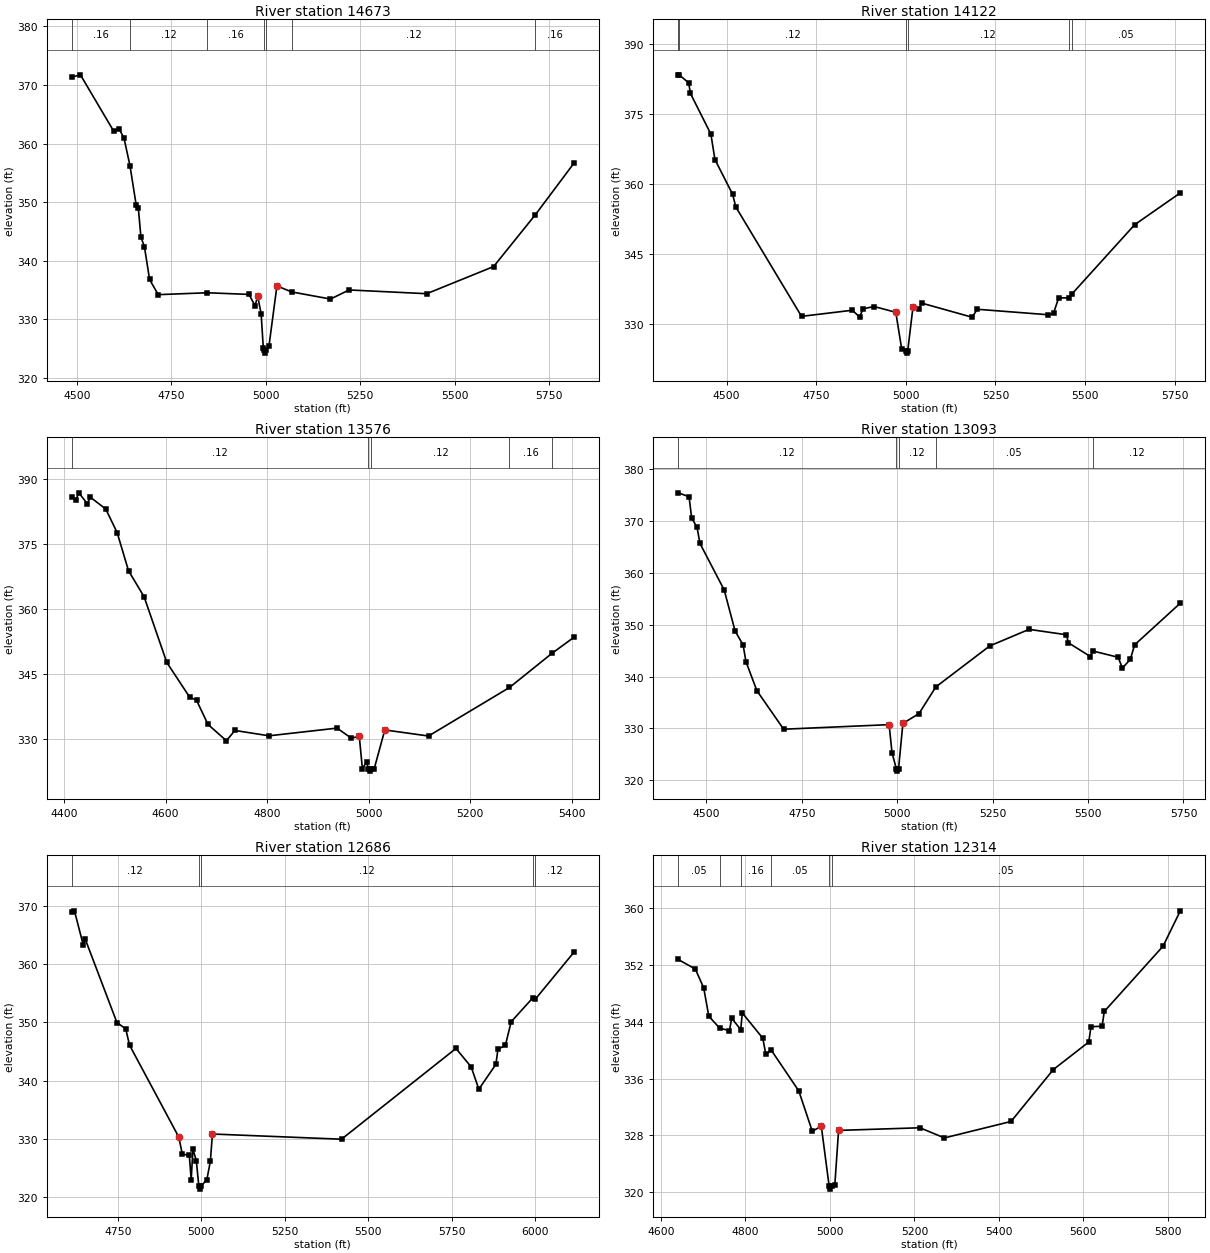
Type RM Length L Ch R = 1 ,14673   ,551,551,551
BEGIN DESCRIPTION:
OTTER CREEK 27.0
END DESCRIPTION:
XS GIS Cut Line= 3
      3710799.62     10701610.17      3710549.61     10702060.19
      3709949.64     10702610.16
#Sta/Elev= 30
  4486.8  371.33  4509.7  371.72  4597.8   362.1  4612.7  362.46  4625.2  360.87
  4640.8  356.23  4657.3  349.48    4663  348.95  4669.8  344.02    4679  342.42
  4692.7   336.8  4715.6  334.21  4845.6  334.53  4955.8  334.25  4971.9   332.3
  4978.7  333.96  4987.9  330.98  4993.6  325.17  4995.7  324.73  4998.5  324.23
  5001.7  324.73  5008.7  325.45  5029.7   335.7  5068.3  334.68  5171.5  333.46
  5220.8  335.01  5426.1  334.37  5603.1     339  5713.8  347.86  5815.5  356.62
#Mann= 7 ,-1 , 0
  4486.8     .16       0  4640.8     .12       0  4845.6     .16       0
  4995.7     .07       0  5001.7     .16       0  5068.3     .12       0
  5713.8     .16       0
Bank Sta=4978.7,5029.7
XS Rating Curve= 0 ,0
Exp/Cntr=0.3,0.1

Type RM Length L Ch R = 1 ,14122   ,546,546,546
BEGIN DESCRIPTION:
OTTER CREEK 26.0
END DESCRIPTION:
XS GIS Cut Line= 3
      3710099.61     10701060.19      3710199.61     10701710.19
      3709699.58     10702260.22
#Sta/Elev= 30
  4364.9  383.43  4367.7  383.42    4394  381.71    4399  379.43    4456  370.71
  4467.3  365.26  4516.7  357.79  4525.5  355.09  4708.9  331.61  4850.6  332.92
  4870.8  331.49  4880.9  333.23  4911.3  333.72    4972  332.48  4988.4  324.62
  4999.3  324.22  5002.1  323.72  5005.3  324.22    5020  333.66  5036.4   333.1
  5043.8  334.46  5185.1  331.42  5199.3  333.13  5397.9  331.95  5412.1  332.27
  5426.3  335.55  5454.5  335.59  5462.5  336.33  5638.5  351.27  5765.9   358.1
#Mann= 6 ,-1 , 0
  4364.9     .05       0  4367.7     .12       0  4999.3     .07       0
  5005.3     .12       0  5454.5     .16       0  5462.5     .05       0
Bank Sta=4972,5020
XS Rating Curve= 0 ,0
Exp/Cntr=0.3,0.1

Type RM Length L Ch R = 1 ,13576   ,483,483,483
BEGIN DESCRIPTION:
OTTER CREEK 25.0
END DESCRIPTION:
XS GIS Cut Line= 3
      3710049.59     10701110.22      3709799.61     10701610.19
      3709549.61     10701960.19
#Sta/Elev= 30
  4415.2  385.79  4423.5  385.26  4429.1  386.81  4445.9  384.29  4451.5  385.83
  4482.2  383.07  4504.6  377.64    4527  368.86  4557.7  362.86  4602.4  347.72
  4647.2  339.78  4661.1  338.99  4683.5  333.46  4719.8  329.69  4736.6  332.06
  4803.7  330.83  4937.8   332.6  4965.8   330.3  4981.6  330.69  4987.7  323.29
  4996.3  324.84  4999.4  323.19  5002.2  322.69  5005.4  323.19    5011  323.24
  5031.9  332.18    5118  330.78  5277.5  341.96    5361  349.81  5404.3  353.51
#Mann= 5 ,-1 , 0
  4415.2     .12       0  4999.4     .07       0  5005.4     .12       0
  5277.5     .16       0    5361     .05       0
Bank Sta=4981.6,5031.9
XS Rating Curve= 0 ,0
Exp/Cntr=0.3,0.1

Type RM Length L Ch R = 1 ,13093   ,407,407,407
BEGIN DESCRIPTION:
Mapping XS 26e8baf2
END DESCRIPTION:
XS GIS Cut Line= 3
      3709986.09     10701086.64      3709461.79      10701541.5
      3709277.77     10702135.22
#Sta/Elev= 30
    4426  375.41  4454.4  374.66  4461.1  370.57  4475.2  368.78  4482.9  365.66
  4546.5  356.67    4575  348.76  4595.9  346.11  4603.5  342.86    4632  337.28
  4702.2  329.84  4978.6  330.72  4986.2  325.31  4997.4  322.26  5000.2  321.76
  5003.4  322.26  5014.7  330.96  5056.8  332.84    5101  337.99  5242.4   345.9
  5345.4  349.09  5443.2  348.05  5448.4   346.5  5506.1  343.85  5512.3  344.92
  5578.8  343.71  5589.9  341.63  5610.8  343.31  5621.9   346.1  5741.7  354.14
#Mann= 5 ,-1 , 0
    4426     .12       0  4997.4     .07       0  5003.4     .12       0
    5101     .05       0  5512.3     .12       0
Bank Sta=4978.6,5014.7
XS Rating Curve= 0 ,0
Exp/Cntr=0.3,0.1

Type RM Length L Ch R = 1 ,12686   ,372,372,372
BEGIN DESCRIPTION:
Mapping XS 559b963f
END DESCRIPTION:
XS GIS Cut Line= 3
      3709973.95     10701043.23      3709151.02     10701314.07
      3708573.78     10701584.49
#Sta/Elev= 30
    4612  368.87    4620  369.11  4646.6  363.21  4651.8  364.34  4747.2  349.96
  4773.7  348.86    4785  346.08  4932.4  330.33  4943.2  327.38    4964   327.2
  4969.7  323.02  4974.9  328.24    4985  326.28  4992.6  321.89  4995.3  321.39
  4998.6  321.89  5016.6     323  5027.1  326.19  5033.3  330.84  5419.9  329.95
  5762.7  345.51  5808.3  342.35  5831.2  338.52  5882.3  342.79  5888.5   345.4
  5910.7  346.03    5928  350.08  5992.8  354.18  6000.3  353.95  6115.8  361.99
#Mann= 5 ,-1 , 0
    4612     .12       0  4992.6     .07       0  4998.6     .12       0
  5992.8     .16       0  6000.3     .12       0
Bank Sta=4932.4,5033.3
XS Rating Curve= 0 ,0
Exp/Cntr=0.3,0.1

Type RM Length L Ch R = 1 ,12314   ,83,83,83
BEGIN DESCRIPTION:
OTTER CREEK 23.0
END DESCRIPTION:
XS GIS Cut Line= 4
      3709857.56     10700703.04       3709451.3     10700852.35
      3708850.61     10701053.74      3708729.08     10701067.63
#Sta/Elev= 30
  4640.8  352.79  4681.3  351.44  4701.1  348.79  4713.2  344.79  4738.9  343.11
  4762.1  342.76  4767.4  344.52  4788.7  342.89  4792.5  345.25    4841  341.69
  4848.2   339.4    4861  340.01  4926.3  334.25  4958.2  328.56  4979.5  329.29
  4997.9  320.91  5000.6  320.41  5003.9  320.91  5011.5  320.96  5020.4  328.69
  5213.1  329.06  5270.9  327.63  5428.7  329.95  5528.9  337.27  5612.7  341.15
    5618  343.31  5644.3  343.38  5649.5  345.46  5788.7  354.67  5829.5  359.65
#Mann= 6 ,-1 , 0
  4640.8     .05       0  4738.9     .08       0  4788.7     .16       0
    4861     .05       0  4997.9     .04       0  5003.9     .05       0
Bank Sta=4979.5,5020.4
XS Rating Curve= 0 ,0
Exp/Cntr=0.3,0.1

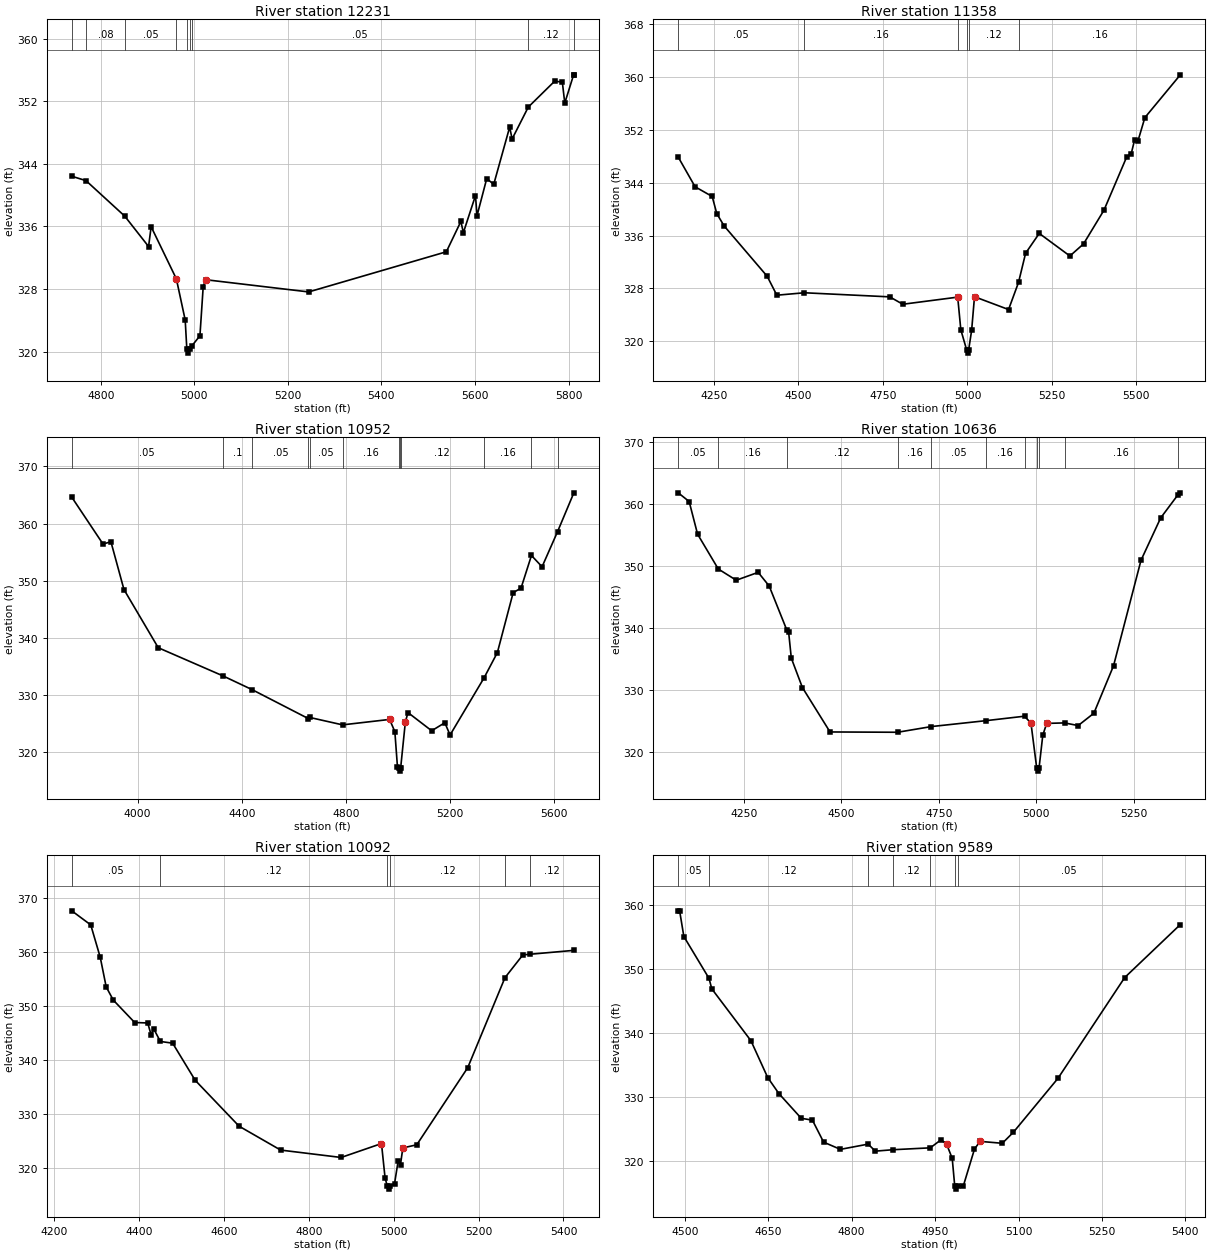
Type RM Length L Ch R = 1 ,12231   ,873,873,873
BEGIN DESCRIPTION:
OTTER CREEK 22.0
END DESCRIPTION:
XS GIS Cut Line= 5
      3709770.75     10700644.01      3709586.72     10700730.82
      3709479.08     10700765.54      3708958.24      10700946.1
      3708760.32     10701001.66
#Sta/Elev= 30
    4738  342.42  4768.4  341.86  4851.3  337.32  4902.2  333.44  4907.7  335.97
  4961.6  329.31  4980.5  324.05    4984  320.32  4986.7  319.82    4990  320.32
  4994.2   320.7    5012  322.04    5019  328.32  5024.3   329.2  5244.5  327.64
  5538.8  332.77  5569.9  336.65  5575.2  335.21  5601.1  339.95  5604.4  337.38
  5625.2  342.13  5640.1  341.38  5674.2   348.7  5679.4  347.18    5714  351.26
  5770.6  354.58  5786.8  354.44    5792  351.77  5810.9  355.38  5811.4  355.38
#Mann= 9 ,-1 , 0
    4738     .05       0  4768.4     .08       0  4851.3     .05       0
  4961.6     .16       0    4984     .04       0    4990     .16       0
  4994.2     .05       0    5714     .12       0  5810.9     .16       0
Bank Sta=4961.6,5024.3
XS Rating Curve= 0 ,0
Exp/Cntr=0.3,0.1

Type RM Length L Ch R = 1 ,11358   ,406,406,406
BEGIN DESCRIPTION:
OTTER CREEK 21.0
END DESCRIPTION:
XS GIS Cut Line= 4
      3709926.98     10700553.73      3709447.83     10700150.96
      3709183.94     10700189.15      3708595.54      10700265.3
#Sta/Elev= 30
  4144.1  347.88    4194  343.39  4244.6  341.92  4258.2  339.32  4279.8  337.47
  4407.3  329.84  4435.9  326.97  4517.3  327.34  4770.1  326.72  4808.7   325.6
  4971.2  326.68  4980.4  321.74  4997.6   318.7  5000.4   318.2  5003.6   318.7
  5012.4  321.64  5020.9  326.74  5121.7   324.8  5151.2  328.91  5172.1  333.32
  5212.5  336.33  5303.2  332.91  5343.6  334.74  5404.1  339.85  5471.4  347.92
  5484.7   348.4  5494.8   350.5  5504.9  350.37  5525.1  353.86    5630  360.34
#Mann= 6 ,-1 , 0
  4144.1     .05       0  4517.3     .16       0  4971.2     .12       0
  4997.6     .07       0  5003.6     .12       0  5151.2     .16       0
Bank Sta=4971.2,5020.9
XS Rating Curve= 0 ,0
Exp/Cntr=0.3,0.1

Type RM Length L Ch R = 1 ,10952   ,316,316,316
BEGIN DESCRIPTION:
Mapping XS 7563c81c
END DESCRIPTION:
XS GIS Cut Line= 2
      3710358.51     10699656.08      3708448.79     10699929.52
#Sta/Elev= 30
  3746.8  364.63  3866.9  356.43  3897.2  356.84  3947.4  348.47  4079.1   338.3
  4327.1  333.39  4440.2  330.96  4656.2   325.9  4660.8  326.11  4787.3  324.81
    4968  325.76  4988.2  323.63  4998.3  317.43  5003.9  317.22  5006.7  316.72
  5009.9  317.22  5010.5  317.26  5028.6  325.32  5038.7  326.96  5129.7  323.78
  5180.2  325.18  5200.4  323.04  5331.1  333.04  5382.2  337.46  5442.8  347.93
  5473.1  348.73  5513.1  354.43  5553.9  352.46  5613.6  358.62    5676  365.39
#Mann= 12 ,-1 , 0
  3746.8     .05       0  4327.1      .1       0  4440.2     .05       0
  4656.2     .16       0  4660.8     .05       0  4787.3     .16       0
  5003.9     .07       0  5009.9     .16       0  5010.5     .12       0
  5331.1     .16       0  5513.1     .12       0  5613.6     .16       0
Bank Sta=4968,5028.6
XS Rating Curve= 0 ,0
Exp/Cntr=0.3,0.1

Type RM Length L Ch R = 1 ,10636   ,544,544,544
BEGIN DESCRIPTION:
OTTER CREEK 20.0
END DESCRIPTION:
XS GIS Cut Line= 3
      3709599.59      10699010.2      3708949.61     10699610.19
      3708549.59     10699660.19
#Sta/Elev= 30
  4081.4  361.78  4109.4  360.38    4131  355.11  4184.1  349.49  4230.2  347.68
  4286.4  348.95  4314.7  346.74  4359.5   339.7  4364.6  339.27  4371.4  335.11
  4399.8  330.37  4470.7   323.2  4643.9  323.15  4730.8  324.07  4870.4  325.02
  4969.6  325.74  4986.1  324.61  5000.8  317.38  5003.5  316.88  5006.8  317.38
  5016.4  322.68  5026.4  324.58  5072.2  324.66  5107.1  324.23  5147.4  326.22
  5197.8  333.87  5268.3   350.9  5318.7  357.73  5363.3  361.48  5369.1  361.68
#Mann= 11 ,-1 , 0
  4081.4     .05       0  4184.1     .16       0  4359.5     .12       0
  4643.9     .16       0  4730.8     .05       0  4870.4     .16       0
  4969.6     .12       0  5000.8     .07       0  5006.8     .12       0
  5072.2     .16       0  5363.3     .12       0
Bank Sta=4986.1,5026.4
XS Rating Curve= 0 ,0
Exp/Cntr=0.3,0.1

Type RM Length L Ch R = 1 ,10092   ,503,503,503
BEGIN DESCRIPTION:
OTTER CREEK 19.0
END DESCRIPTION:
XS GIS Cut Line= 3
      3709599.62     10698760.18      3708899.61     10699110.19
      3708499.65     10699110.19
#Sta/Elev= 30
  4241.8  367.63  4286.5  365.02  4308.9     359  4322.9  353.52  4339.6  351.08
    4390  346.92  4420.7  346.84  4429.1  344.53  4434.7  345.77  4450.4  343.41
  4479.4  343.09  4532.5  336.21  4635.9   327.7  4733.8  323.27  4876.3   321.9
  4971.3  324.48  4979.7  318.15  4985.1  316.53  4987.9  316.03  4991.1  316.53
  5002.1  317.07  5010.5  321.21  5016.1  320.59  5021.6  323.67  5054.4  324.25
  5174.4  338.54  5262.2  355.24  5304.4  359.47  5321.5  359.58  5424.4   360.3
#Mann= 6 ,-1 , 0
  4241.8     .05       0  4450.4     .12       0  4985.1     .07       0
  4991.1     .12       0  5262.2     .16       0  5321.5     .12       0
Bank Sta=4971.3,5021.6
XS Rating Curve= 0 ,0
Exp/Cntr=0.3,0.1

Type RM Length L Ch R = 1 ,9589    ,538,538,538
BEGIN DESCRIPTION:
OTTER CREEK 18.0
END DESCRIPTION:
XS GIS Cut Line= 3
      3709449.63     10698660.19      3708949.61     10698610.19
      3708549.62     10698610.19
#Sta/Elev= 30
  4488.3  359.09  4490.8  359.09  4498.4  355.07  4543.6  348.53  4548.6  346.89
    4619  338.77  4649.1  333.02  4669.2  330.51  4709.4  326.64  4729.5  326.35
  4749.6  322.91  4779.8  321.78  4829.7   322.6  4842.6   321.5  4873.7  321.72
  4941.4  322.02  4960.7  323.28  4970.7  322.59  4980.8  320.37  4985.3  316.06
    4988  315.56  4991.3  316.06  5000.8  316.07  5020.8  321.82  5030.8  323.03
  5070.8  322.73  5090.8  324.46  5170.8  332.88  5290.8  348.65  5390.8  356.94
#Mann= 7 ,-1 , 0
  4488.3     .05       0  4543.6     .12       0  4829.7     .05       0
  4873.7     .12       0  4941.4     .05       0  4985.3     .03       0
  4991.3     .05       0
Bank Sta=4970.7,5030.8
XS Rating Curve= 0 ,0
Exp/Cntr=0.3,0.1

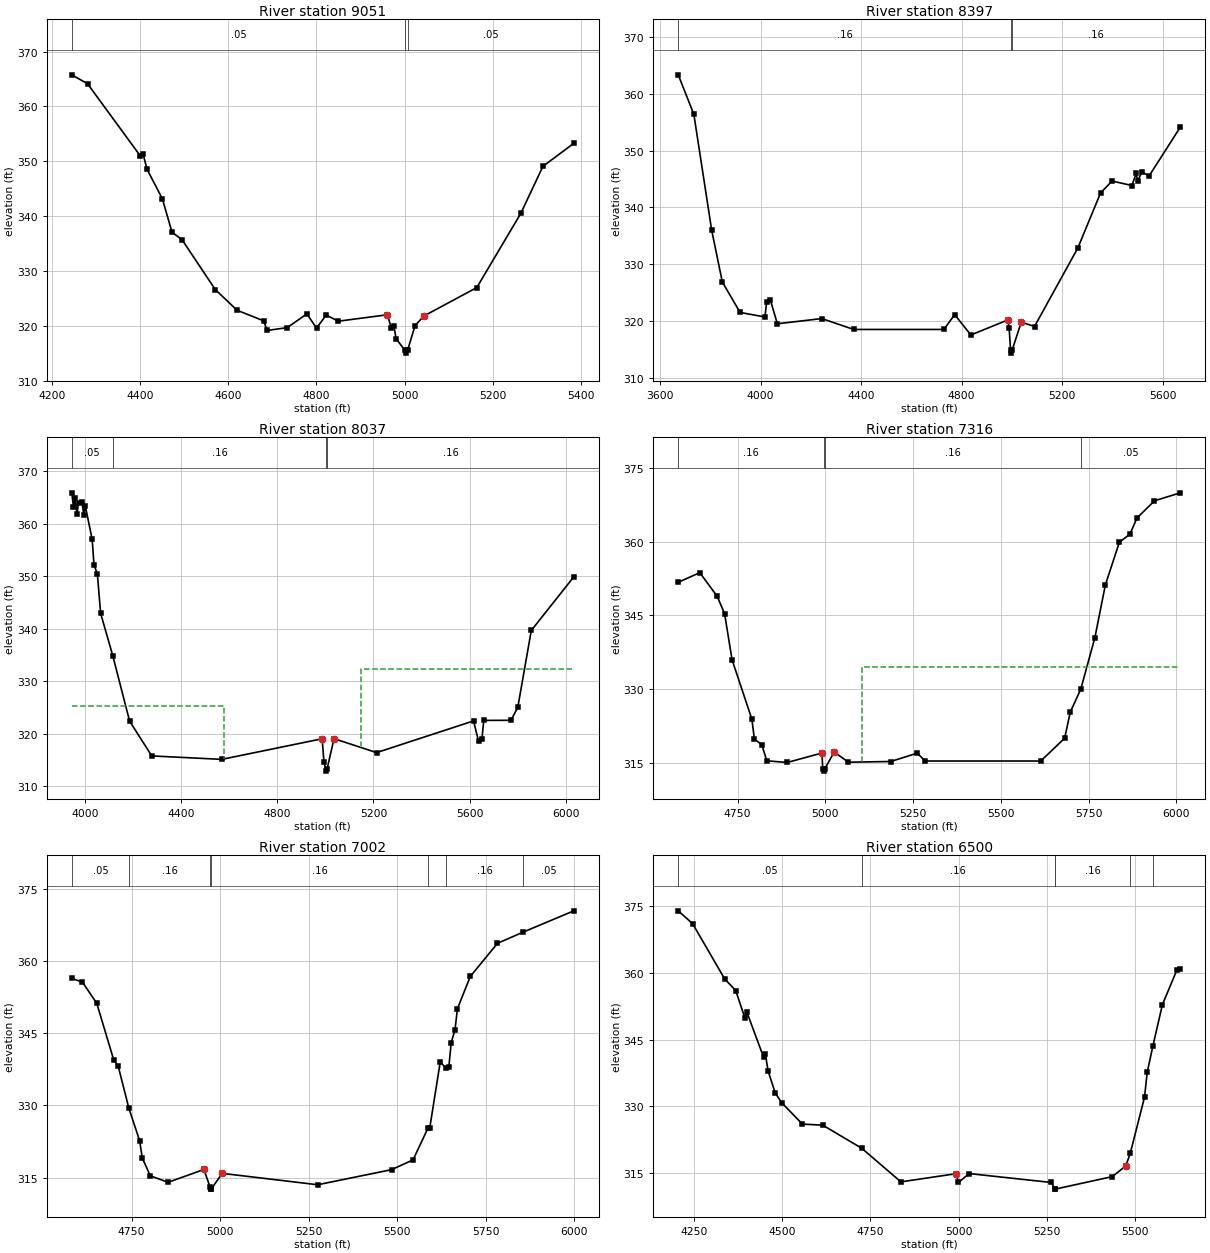
Type RM Length L Ch R = 1 ,9051    ,654,654,654
BEGIN DESCRIPTION:
OTTER CREEK 17.0
END DESCRIPTION:
XS GIS Cut Line= 3
      3709699.63      10698460.2      3709049.61     10698110.19
      3708649.57     10698110.19
#Sta/Elev= 30
  4245.2  365.77  4280.9  364.15    4401  350.95  4406.7  351.42  4415.6  348.59
  4450.5  343.21  4472.4   337.1  4495.1  335.74  4570.5  326.65    4620  322.87
  4680.1  320.95  4688.2  319.19  4733.6   319.7  4778.2  322.21  4800.1  319.62
    4822  321.99  4849.6  320.88  4960.8  322.05  4969.7  319.62  4975.4  319.99
  4980.6  317.69  5000.5  315.56  5003.2  315.06  5006.5  315.56  5023.5  320.07
  5043.5  321.82  5163.5  327.01  5263.5  340.56  5313.5  349.11  5383.5  353.29
#Mann= 3 ,-1 , 0
  4245.2     .05       0  5000.5     .03       0  5006.5     .05       0
Bank Sta=4960.8,5043.5
XS Rating Curve= 0 ,0
Exp/Cntr=0.3,0.1

Type RM Length L Ch R = 1 ,8397    ,360,360,360
BEGIN DESCRIPTION:
OTTER CREEK 16.0
END DESCRIPTION:
XS GIS Cut Line= 4
      3709816.71     10698021.01      3709150.04     10697375.17
      3708740.32     10697534.89      3708469.49     10698104.32
#Sta/Elev= 30
  3671.9  363.36  3734.1  356.39  3804.9  336.01  3847.3  326.88    3918   321.5
  4016.9   320.7    4024   323.4  4038.2  323.75  4066.5   319.5  4243.2  320.42
  4370.5   318.5  4729.4   318.5  4772.3  321.11  4836.7  317.53  4983.6  320.17
    4989  318.84  4994.7  314.83  4997.4  314.33  5000.7  314.83  5037.5   319.8
    5090  319.02  5262.2  332.83    5353  342.54  5398.5  344.65  5477.7  343.86
  5494.8  345.98  5500.4  344.65  5517.6  346.27  5545.8  345.52  5670.4  354.14
#Mann= 3 ,-1 , 0
  3671.9     .16       0  4994.7     .03       0  5000.7     .16       0
Bank Sta=4983.6,5037.5
XS Rating Curve= 0 ,0
Exp/Cntr=0.3,0.1

Type RM Length L Ch R = 1 ,8037    ,721,721,721
BEGIN DESCRIPTION:
OTTER CREEK 15.0
END DESCRIPTION:
XS GIS Cut Line= 3
      3709399.61     10696510.19      3708599.61     10697210.19
      3707849.63     10697910.17
#Sta/Elev= 30
  3945.1  365.93  3952.2  363.24  3958.9  365.03  3966.5   361.8  3973.1  364.04
  3987.3  364.24  3994.9  361.78  4001.6  363.39    4030  357.04  4037.6  352.17
  4051.4  350.52  4065.2  342.96  4115.5  334.91  4185.7  322.42  4277.8  315.78
  4569.1  315.12  4986.8  319.05  4994.4  314.56  5004.5  312.88  5007.8  313.38
  5036.2  319.07  5213.3  316.41  5616.6  322.45  5637.6  318.56  5651.8  319.06
  5659.1  322.55  5772.4  322.57  5800.8  325.04  5856.9  339.69    6034  349.93
#Mann= 4 ,-1 , 0
  3945.1     .05       0  4115.5     .16       0  5004.5     .07       0
  5007.8     .16       0
#XS Ineff= 2 , 0
         4577.27  325.32 5146.59           332.3
Permanent Ineff=
       F       F
Bank Sta=4986.8,5036.2
XS Rating Curve= 0 ,0
Exp/Cntr=0.3,0.1

Type RM Length L Ch R = 1 ,7316    ,314,314,314
BEGIN DESCRIPTION:
OTTER CREEK 14.0
END DESCRIPTION:
XS GIS Cut Line= 4
      3708573.65      10696347.4      3708365.32     10696555.73
      3707585.57      10696761.8      3707256.01     10696760.74
#Sta/Elev= 30
  4580.9  351.75  4642.3  353.71  4691.8   348.9    4713  345.35  4734.2  335.99
  4790.8  323.84  4797.9  319.81  4819.1  318.66  4833.2  315.38  4891.8  315.05
  4990.4  316.97  4992.6  313.78  4995.3  313.28  4998.6  313.78  5025.5  317.17
  5065.8   315.1  5186.5  315.24  5261.9  316.94  5284.8  315.34  5613.8  315.34
    5682  319.98    5698  325.29    5728  329.99    5768  340.42    5798   351.2
    5838  359.92    5868  361.55    5888  364.82    5938  368.35  6011.6  369.97
#Mann= 4 ,-1 , 0
  4580.9     .16       0  4995.3     .07       0  4998.6     .16       0
    5728     .05       0
#XS Ineff= 2 , 0
                         5105.68          334.44
Permanent Ineff=
       F       F
Bank Sta=4990.4,5025.5
XS Rating Curve= 0 ,0
Exp/Cntr=0.3,0.1

Type RM Length L Ch R = 1 ,7002    ,502,502,502
BEGIN DESCRIPTION:
OTTER CREEK 13.0
END DESCRIPTION:
XS GIS Cut Line= 4
      3708549.62     10696260.19      3708149.61     10696310.19
      3707399.61     10696010.19      3707194.53     10696030.69
#Sta/Elev= 30
  4581.3  356.45  4611.5  355.64  4651.9  351.24  4699.7  339.47  4712.3  338.18
  4742.6  329.38  4772.8  322.68  4780.3  319.07    4803  315.35  4853.4  314.01
  4954.2  316.68  4971.3  313.09  4974.1  312.59  4974.6  312.59    5006  315.87
  5275.2   313.5  5483.9  316.64  5544.5  318.68  5586.2  325.22  5591.6   325.3
  5621.2  339.04  5637.8  337.75  5645.5     338  5652.2  343.09    5663  345.77
  5669.7  350.13    5706  356.83  5782.8  363.73  5854.2  366.03  5998.3  370.49
#Mann= 7 ,-1 , 0
  4581.3     .05       0  4742.6     .16       0  4971.3     .07       0
  4974.6     .16       0  5586.2     .05       0  5637.8     .16       0
  5854.2     .05       0
Bank Sta=4954.2,5006
XS Rating Curve= 0 ,0
Exp/Cntr=0.3,0.1

Type RM Length L Ch R = 1 ,6500    ,563,563,563
BEGIN DESCRIPTION:
OTTER CREEK 12.0
END DESCRIPTION:
XS GIS Cut Line= 3
      3708849.59     10695660.19      3708049.61     10695810.19
      3707449.61     10695910.19
#Sta/Elev= 30
  4205.8  373.89  4246.5  371.01  4337.2  358.62  4368.6     356  4394.9  349.76
  4399.9  351.22  4447.4  341.06  4452.5  341.85  4460.1  338.01  4480.5  332.99
    4500  330.72  4557.6  326.02  4615.3  325.77  4725.5   320.6  4836.6  313.05
  4993.4  314.89  4999.4  312.91  5029.9  314.91    5263  312.91  5272.9  311.42
  5273.4  311.42  5435.4  314.23  5473.4  316.62  5486.1  319.43  5526.6  332.05
  5534.2  337.64  5550.4  343.58  5577.3  352.84  5617.9  360.52    5628   360.8
#Mann= 6 ,-1 , 0
  4205.8     .05       0  4725.5     .16       0  5272.9     .07       0
  5273.4     .16       0  5486.1     .05       0  5550.4     .16       0
Bank Sta=4993.4,5473.4
XS Rating Curve= 0 ,0
Exp/Cntr=0.3,0.1

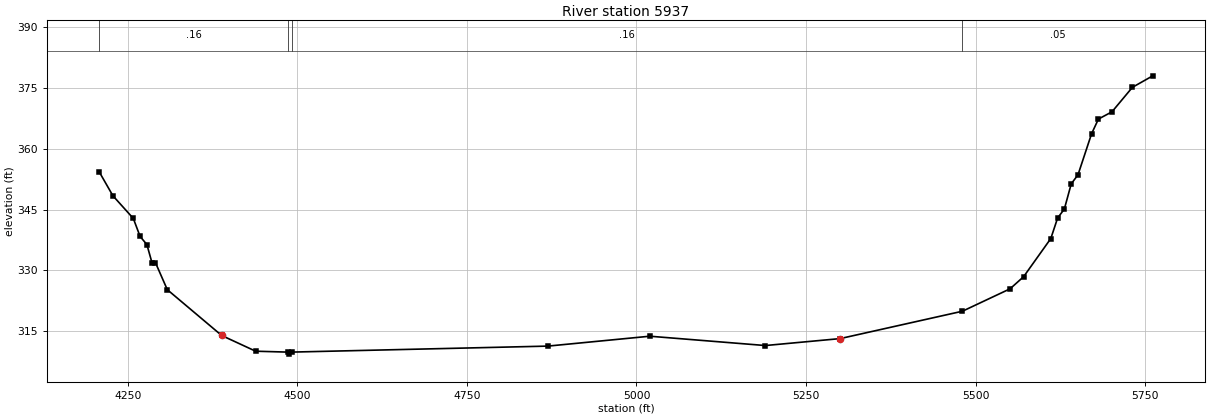
Type RM Length L Ch R = 1 ,5937    ,549,549,549
BEGIN DESCRIPTION:
OTTER CREEK 11.0
END DESCRIPTION:
XS GIS Cut Line= 3
      3708649.61     10695360.19      3707849.61     10695310.19
      3707099.64     10695260.19
#Sta/Elev= 30
    4208  354.27    4228  348.42  4258.1  342.82  4268.1  338.37  4278.1  336.38
  4285.7  331.84  4290.7  331.93  4308.2  325.24  4388.4  313.93  4438.5  310.05
  4485.5  309.83  4488.3  309.33  4491.5  309.83  4869.3  311.31  5019.6  313.75
    5190  311.45  5300.2  313.16  5480.6  319.92  5550.8  325.45  5570.8  328.44
  5610.9  337.86  5620.9  342.91  5630.9  345.16    5641  351.35    5651   353.6
    5671  363.72  5681.1  367.35  5701.1  369.14  5731.2  375.18  5761.2  378.02
#Mann= 4 ,-1 , 0
    4208     .16       0  4485.5     .03       0  4491.5     .16       0
  5480.6     .05       0
Bank Sta=4388.4,5300.2
XS Rating Curve= 0 ,0
Exp/Cntr=0.3,0.1