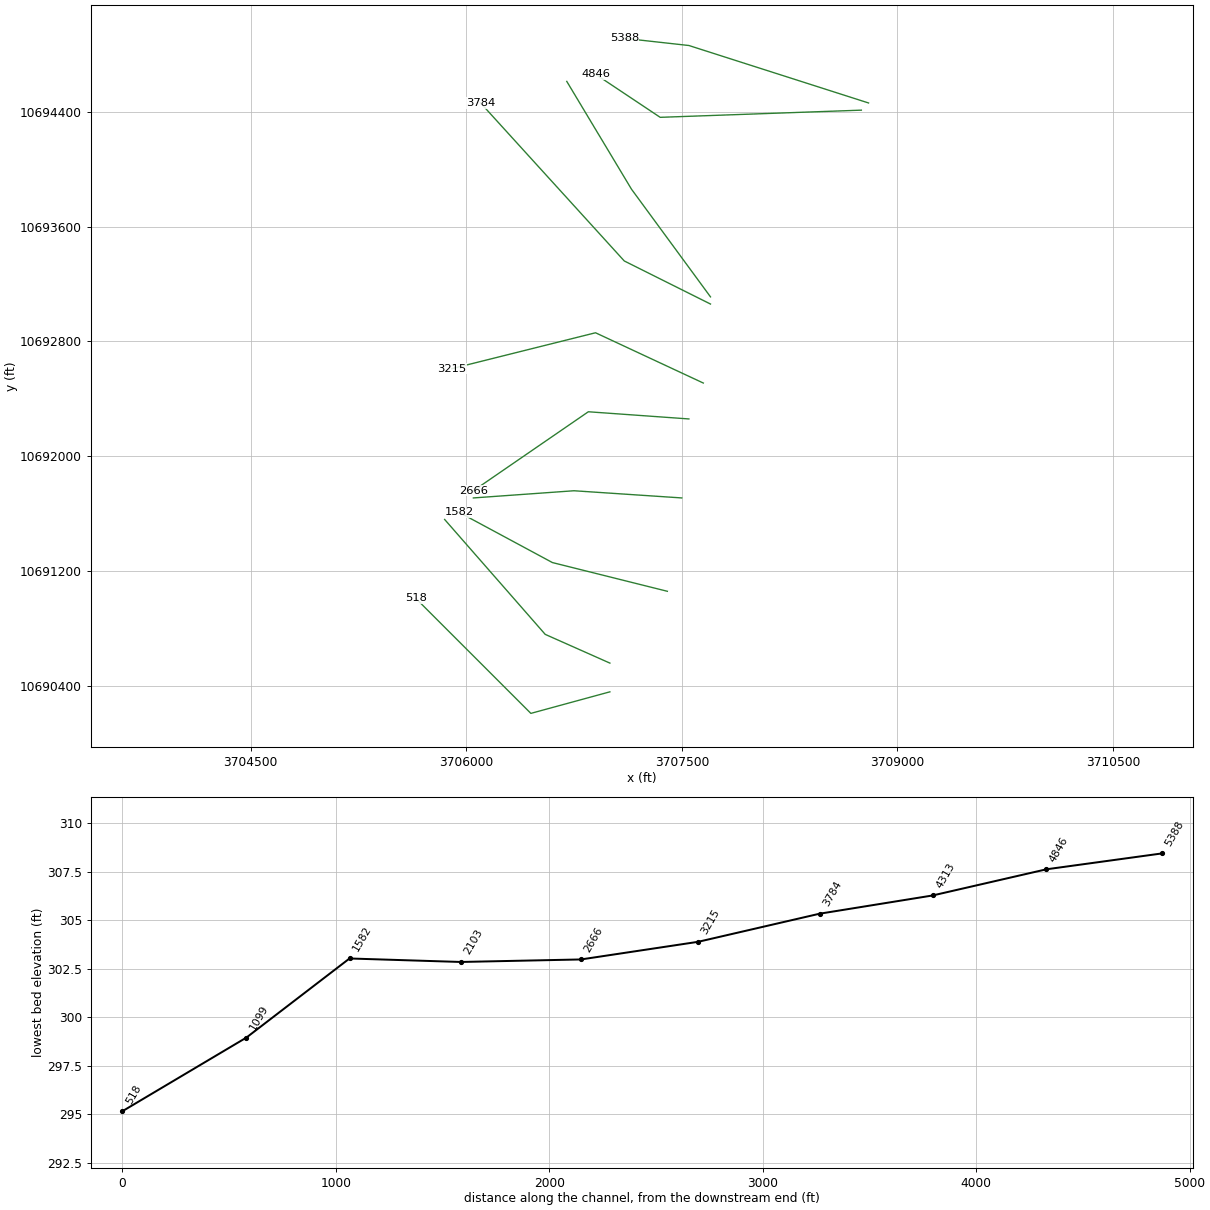
HEC-RAS study OTTER CREEK.prj: OTTER CREEK Base Level Engineering

--- OTTER CREEK.g01 (geometry) --- (continued)

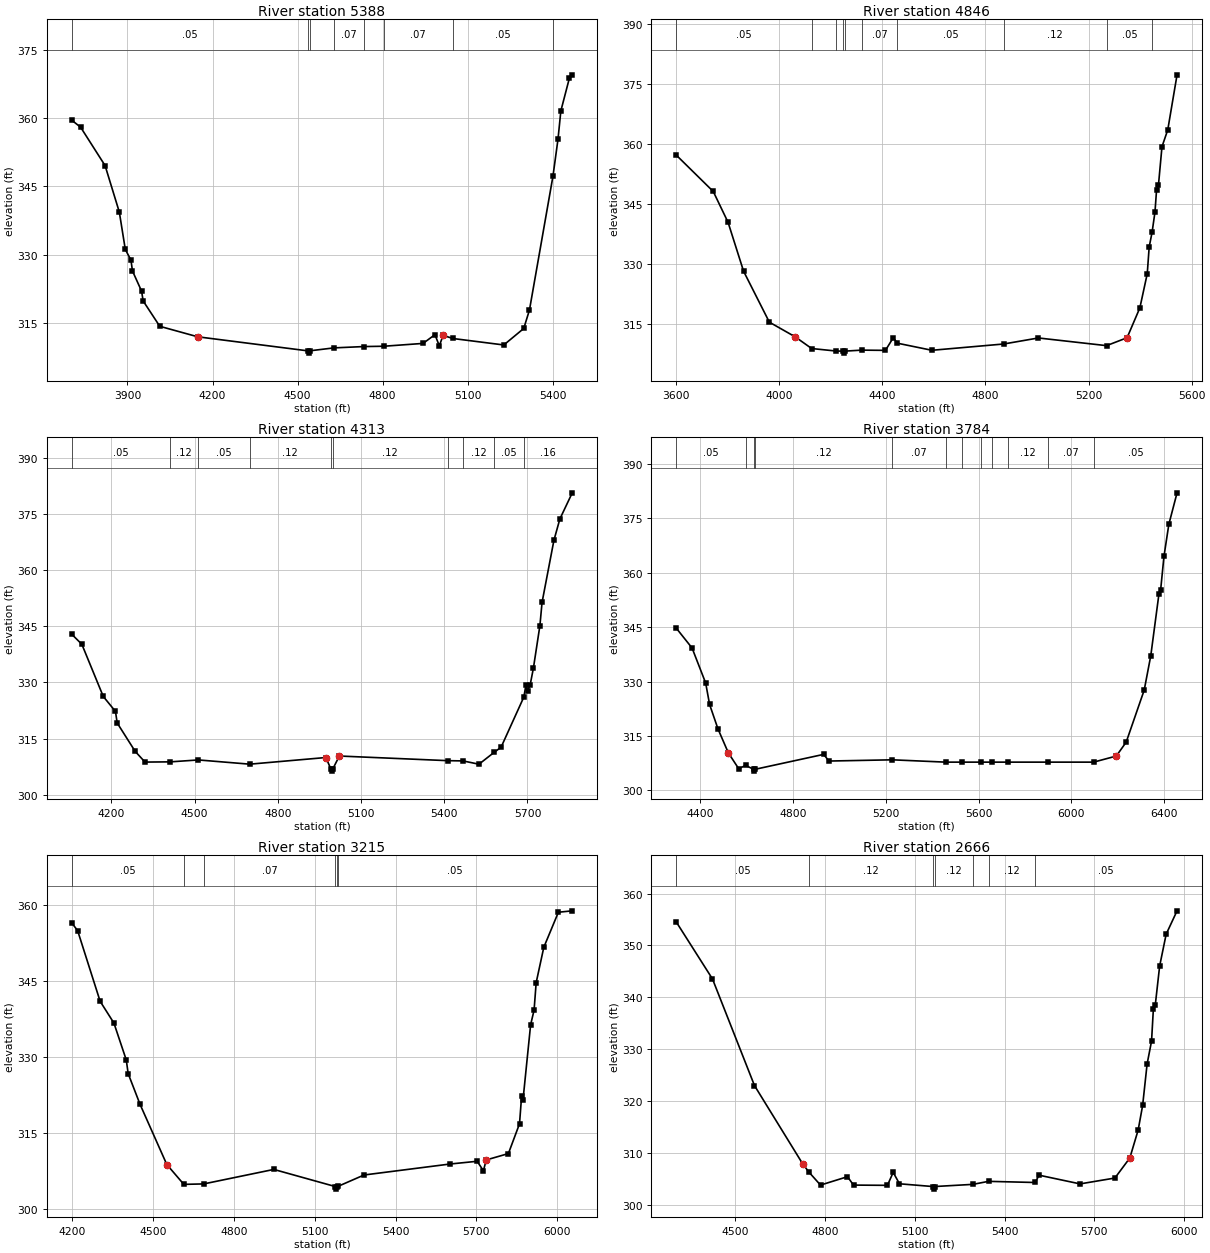
Type RM Length L Ch R = 1 ,5388    ,542,542,542
BEGIN DESCRIPTION:
OTTER CREEK 10.0
END DESCRIPTION:
XS GIS Cut Line= 3
      3708799.63     10694460.18      3707549.61     10694860.19
      3707099.64     10694910.19
#Sta/Elev= 30
  3703.4  359.54  3734.9  357.99  3821.2  349.57  3871.4  339.37  3892.4   331.2
  3912.4  328.84  3917.7  326.47  3949.8  322.05  3955.4  319.89  4014.1  314.33
    4148  312.03  4536.1  308.95  4538.9  308.45  4542.1  308.95  4628.2   309.6
  4733.4  309.89    4804  309.96  4942.4  310.58  4984.4   312.5  4999.8  310.05
  5013.2  312.35  5047.4  311.66  5227.2  310.24  5297.6  313.86  5317.7  317.91
  5400.7   347.3  5418.3  355.35  5428.4  361.57  5458.6  368.78  5468.6  369.48
#Mann= 8 ,-1 , 0
  3703.4     .05       0  4536.1     .07       0  4542.1     .05       0
  4628.2     .07       0  4733.4     .05       0    4804     .07       0
  5047.4     .05       0  5400.7     .16       0
Bank Sta=4148,5013.2
XS Rating Curve= 0 ,0
Exp/Cntr=0.3,0.1

Type RM Length L Ch R = 1 ,4846    ,533,533,533
BEGIN DESCRIPTION:
OTTER CREEK 9.0
END DESCRIPTION:
XS GIS Cut Line= 3
      3708749.63     10694410.19      3707349.61     10694360.19
      3706899.65     10694660.16
#Sta/Elev= 30
  3601.7  357.07  3744.3  348.04  3801.8  340.32  3861.9  328.11  3961.9  315.37
    4062  311.71    4126  308.78  4221.3  308.15  4249.1  308.13  4251.9  307.63
  4255.1  308.13  4320.2  308.38  4412.2  308.32  4442.3  311.45  4458.8  310.11
  4592.4  308.34  4870.7  309.91  5005.6  311.42  5269.9   309.5  5349.6  311.48
  5399.2  318.96  5427.8  327.49  5435.3  334.17  5446.6  337.86  5457.8  342.92
  5463.8  348.31  5471.3  349.66  5484.9  359.22  5507.4  363.46  5543.4   377.2
#Mann= 10 ,-1 , 0
  3601.7     .05       0    4126     .07       0  4221.3     .05       0
  4249.1     .07       0  4255.1     .05       0  4320.2     .07       0
  4458.8     .05       0  4870.7     .12       0  5269.9     .05       0
  5446.6     .16       0
Bank Sta=4062,5349.6
XS Rating Curve= 0 ,0
Exp/Cntr=0.3,0.1

Type RM Length L Ch R = 1 ,4313    ,529,529,529
BEGIN DESCRIPTION:
OTTER CREEK 8.0
END DESCRIPTION:
XS GIS Cut Line= 3
       3707699.6     10693110.21      3707149.61     10693860.19
       3706699.6     10694610.21
#Sta/Elev= 30
  4056.7   342.9  4093.3   340.2  4170.5  326.25  4214.5  322.25  4220.7  319.16
  4285.5  311.57    4321   308.7  4412.1  308.76  4513.5  309.27  4698.7  308.14
  4973.2  309.92  4991.5  306.78  4994.3  306.28  4997.5  306.78  5021.7  310.32
  5412.2  309.08  5467.7  309.01  5525.1  308.13  5579.4  311.28  5604.8  312.67
  5687.1  326.13  5694.2  329.27  5700.1  327.71  5709.8  329.41  5721.4  333.85
  5744.8  345.21  5752.5  351.39  5795.3     368  5816.7   373.7  5861.4   380.7
#Mann= 10 ,-1 , 0
  4056.7     .05       0  4412.1     .12       0  4513.5     .05       0
  4698.7     .12       0  4991.5     .07       0  4997.5     .12       0
  5412.2     .07       0  5467.7     .12       0  5579.4     .05       0
  5687.1     .16       0
Bank Sta=4973.2,5021.7
XS Rating Curve= 0 ,0
Exp/Cntr=0.3,0.1

Type RM Length L Ch R = 1 ,3784    ,569,569,569
BEGIN DESCRIPTION:
OTTER CREEK 7.0
END DESCRIPTION:
XS GIS Cut Line= 3
      3707699.61     10693060.19      3707099.61     10693360.19
      3706099.63     10694460.17
#Sta/Elev= 30
  4297.6  344.68  4364.7  339.29  4423.4  329.62  4440.2  323.73  4476.5  316.96
  4521.2  310.36  4565.9  305.99  4595.3  306.93    4630  305.84  4632.8  305.34
    4636  305.84  4932.1  309.96  4954.4  308.12  5227.7  308.46  5457.4  307.82
  5529.6  307.82  5611.1  307.82  5657.6  307.82  5724.5  307.82  5896.7  307.82
  6095.5  307.82  6193.2   309.5  6235.8  313.34  6313.5   327.7  6341.8  337.18
    6377  354.22  6384.4   355.4  6398.6  364.54  6419.6  373.39    6455  382.07
#Mann= 12 ,-1 , 0
  4297.6     .05       0  4595.3     .12       0    4630     .07       0
    4636     .12       0  5227.7     .07       0  5457.4     .16       0
  5529.6     .05       0  5611.1     .12       0  5657.6     .07       0
  5724.5     .12       0  5896.7     .07       0  6095.5     .05       0
Bank Sta=4521.2,6193.2
XS Rating Curve= 0 ,0
Exp/Cntr=0.3,0.1

Type RM Length L Ch R = 1 ,3215    ,549,549,549
BEGIN DESCRIPTION:
OTTER CREEK 6.0
END DESCRIPTION:
XS GIS Cut Line= 3
       3707649.6     10692510.19      3706899.61     10692860.19
      3705899.62     10692610.19
#Sta/Elev= 30
  4197.4  356.49  4219.5  354.93    4303  340.98  4354.2  336.68    4400   329.4
  4407.1   326.7  4451.2  320.63  4550.5  308.75  4613.7  304.83  4687.7  304.92
  4947.8  307.78  5176.6  304.39  5179.4  303.89  5182.6  304.39  5185.8  304.43
  5282.7  306.68  5602.3  308.85  5702.8  309.39    5726  307.51  5736.3  309.65
  5818.7  310.91    5860   316.8  5867.7  322.21  5872.8  321.42  5901.2  336.34
  5914.1  339.25  5921.8  344.66  5950.2  351.65  6004.3  358.57  6055.8  358.85
#Mann= 6 ,-1 , 0
  4197.4     .05       0  4613.7     .12       0  4687.7     .07       0
  5176.6     .07       0  5182.6     .07       0  5185.8     .05       0
Bank Sta=4550.5,5736.3
XS Rating Curve= 0 ,0
Exp/Cntr=0.3,0.1

Type RM Length L Ch R = 1 ,2666    ,563,563,563
BEGIN DESCRIPTION:
OTTER CREEK 5.0
END DESCRIPTION:
XS GIS Cut Line= 3
      3707549.59     10692260.19      3706849.61     10692310.19
       3706049.6     10691760.18
#Sta/Elev= 30
  4303.7  354.46    4424  343.53  4564.3  322.96  4724.8  307.91  4745.7   306.3
  4784.9  303.76  4875.1  305.38  4895.2  303.76  5008.5  303.71  5027.8  306.21
  5048.8  304.01  5160.2  303.48    5163  302.98  5166.2  303.48  5294.3   303.9
  5346.3  304.48  5502.2  304.26  5515.2  305.67  5652.2  303.99  5768.6  305.12
  5818.5  308.99  5846.4   314.4  5861.3  319.13  5876.2  327.11  5891.1  331.55
  5897.1  337.67  5903.5  338.49  5918.1  346.01  5939.9  352.17  5976.3  356.68
#Mann= 7 ,-1 , 0
  4303.7     .05       0  4745.7     .12       0  5160.2     .07       0
  5166.2     .12       0  5294.3     .07       0  5346.3     .12       0
  5502.2     .05       0
Bank Sta=4724.8,5818.5
XS Rating Curve= 0 ,0
Exp/Cntr=0.3,0.1

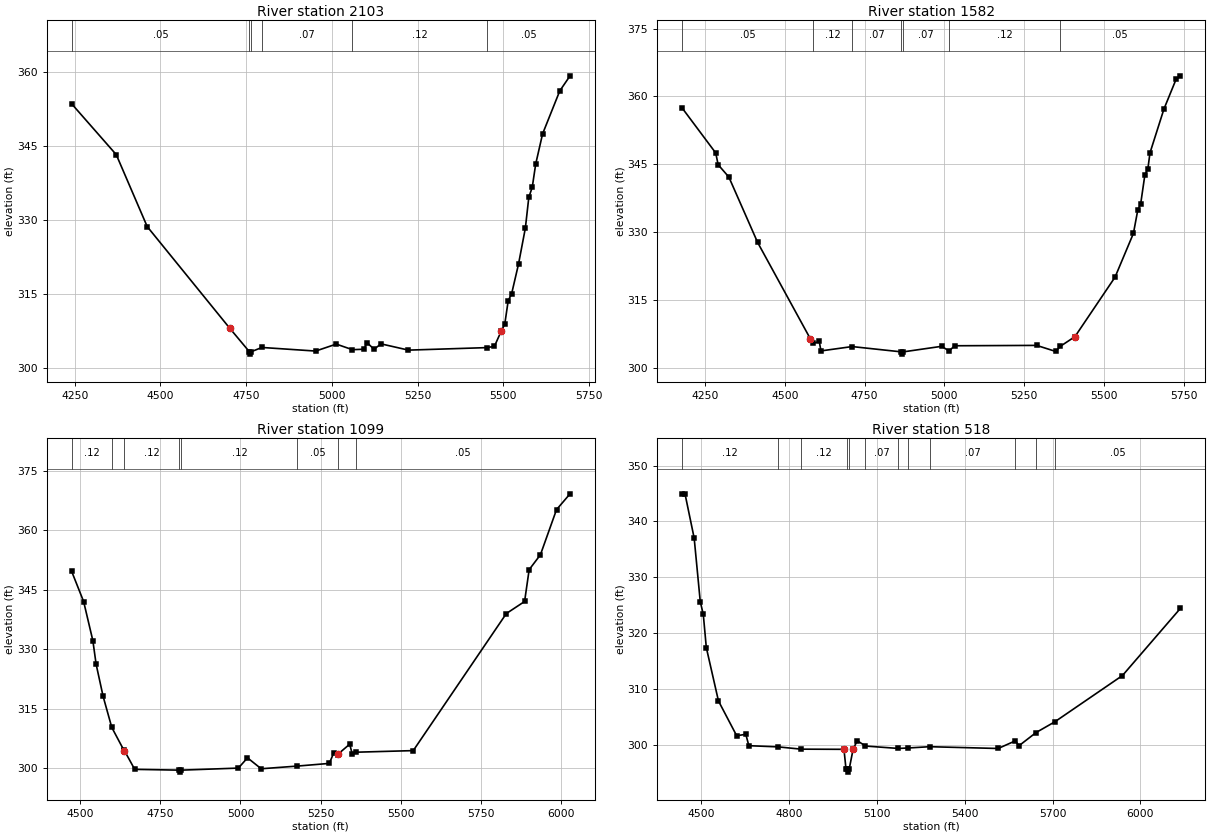
Type RM Length L Ch R = 1 ,2103    ,521,521,521
BEGIN DESCRIPTION:
OTTER CREEK 4.0
END DESCRIPTION:
XS GIS Cut Line= 3
      3707499.61     10691710.19      3706749.61     10691760.19
      3706049.66     10691710.19
#Sta/Elev= 30
  4240.9  353.53  4371.2  343.22  4461.4  328.66  4701.9   308.1  4759.1  303.35
  4761.8  302.85  4765.1  303.35  4795.8   304.2  4952.5  303.47  5012.6  304.88
  5059.8  303.75  5092.8  303.84  5102.8  305.15  5122.9  303.83  5142.9  304.93
  5223.2  303.66  5452.4  304.17  5473.8  304.43  5493.8  307.54  5503.9  308.91
  5513.9  313.65  5523.9  315.06    5544  321.07    5564  328.37    5574  334.57
  5584.1  336.65  5594.1  341.32  5614.1  347.41  5664.3  356.13  5694.3  359.18
#Mann= 6 ,-1 , 0
  4240.9     .05       0  4759.1     .07       0  4765.1     .05       0
  4795.8     .07       0  5059.8     .12       0  5452.4     .05       0
Bank Sta=4701.9,5493.8
XS Rating Curve= 0 ,0
Exp/Cntr=0.3,0.1

Type RM Length L Ch R = 1 ,1582    ,483,483,483
BEGIN DESCRIPTION:
OTTER CREEK 3.0
END DESCRIPTION:
XS GIS Cut Line= 3
      3707399.57      10691060.2      3706599.61     10691260.19
      3705949.63     10691610.18
#Sta/Elev= 30
  4177.5  357.49  4283.1  347.52  4290.8  344.91  4324.3  342.19  4414.5  327.73
  4579.5  306.46  4588.9  305.39  4607.8  305.83    4613  303.74  4710.8   304.7
  4865.1  303.53  4867.8  303.03  4871.1  303.53  4991.8  304.76  5014.8  303.72
  5032.1  304.88  5289.3  304.96  5349.3  303.62  5362.7  304.72  5409.3  306.89
  5535.1  320.05  5592.7  329.73  5606.5  334.93  5615.4  336.22  5628.4  342.56
  5638.1  344.05  5644.6  347.52  5688.4  357.23  5726.5  363.81  5740.3  364.57
#Mann= 7 ,-1 , 0
  4177.5     .05       0  4588.9     .12       0  4710.8     .07       0
  4865.1     .07       0  4871.1     .07       0  5014.8     .12       0
  5362.7     .05       0
Bank Sta=4579.5,5409.3
XS Rating Curve= 0 ,0
Exp/Cntr=0.3,0.1

Type RM Length L Ch R = 1 ,1099    ,581,581,581
BEGIN DESCRIPTION:
OTTER CREEK 2.0
END DESCRIPTION:
XS GIS Cut Line= 3
      3706999.57     10690560.21      3706549.61     10690760.19
      3705849.62     10691560.18
#Sta/Elev= 30
  4473.1  349.66  4510.7  341.99  4539.4  332.15  4549.7  326.16  4571.5  318.06
  4598.5  310.23  4635.9  304.53  4637.9  304.38    4670  299.65  4809.3  299.45
    4812  298.95  4815.3  299.45  4993.5  299.97    5022  302.56  5064.7   299.8
    5178  300.48  5277.3  301.15  5291.5  303.89    5304  303.25  5305.8  303.59
  5340.9     306  5348.5  303.64  5361.4  303.98  5539.2  304.38  5829.7  338.97
  5886.6  342.01  5900.9  350.05    5936   353.8  5986.3   365.2  6028.5  369.18
#Mann= 8 ,-1 , 0
  4473.1     .12       0  4598.5     .16       0  4635.9     .12       0
  4809.3     .07       0  4815.3     .12       0    5178     .05       0
    5304     .07       0  5361.4     .05       0
Bank Sta=4637.9,5305.8
XS Rating Curve= 0 ,0
Exp/Cntr=0.3,0.1

Type RM Length L Ch R = 1 ,518     ,0,0,0
BEGIN DESCRIPTION:
OTTER CREEK 1.0
END DESCRIPTION:
XS GIS Cut Line= 3
      3706999.63     10690360.19      3706449.61     10690210.19
      3705649.59      10691010.2
#Sta/Elev= 30
  4435.3  344.95  4445.7  344.89  4476.8  337.02  4497.5  325.68  4507.9  323.37
  4518.2  317.44  4559.7  307.88  4621.9  301.66    4653  301.92  4663.4  299.88
  4763.2  299.67  4841.9  299.26  4988.1  299.23    4995  295.71  4999.8  295.65
  5002.6  295.15  5005.8  295.65  5019.6  299.33  5033.7  300.77  5061.4  299.82
  5173.2  299.39    5207  299.47  5280.4   299.7  5514.5  299.38  5573.6  300.76
  5585.2  299.86  5643.7  302.23  5707.1  304.13  5938.8  312.44  6136.8  324.47
#Mann= 12 ,-1 , 0
  4435.3     .12       0  4763.2     .05       0  4841.9     .12       0
  4999.8     .07       0  5005.8     .12       0  5061.4     .07       0
  5173.2     .12       0    5207     .05       0  5280.4     .07       0
  5573.6     .12       0  5643.7     .07       0  5707.1     .05       0
Bank Sta=4988.1,5019.6
XS Rating Curve= 0 ,0
Exp/Cntr=0.3,0.1

Chan Stop Cuts=-1
Use User Specified Reach Order=0
Composite Channel Slope=5