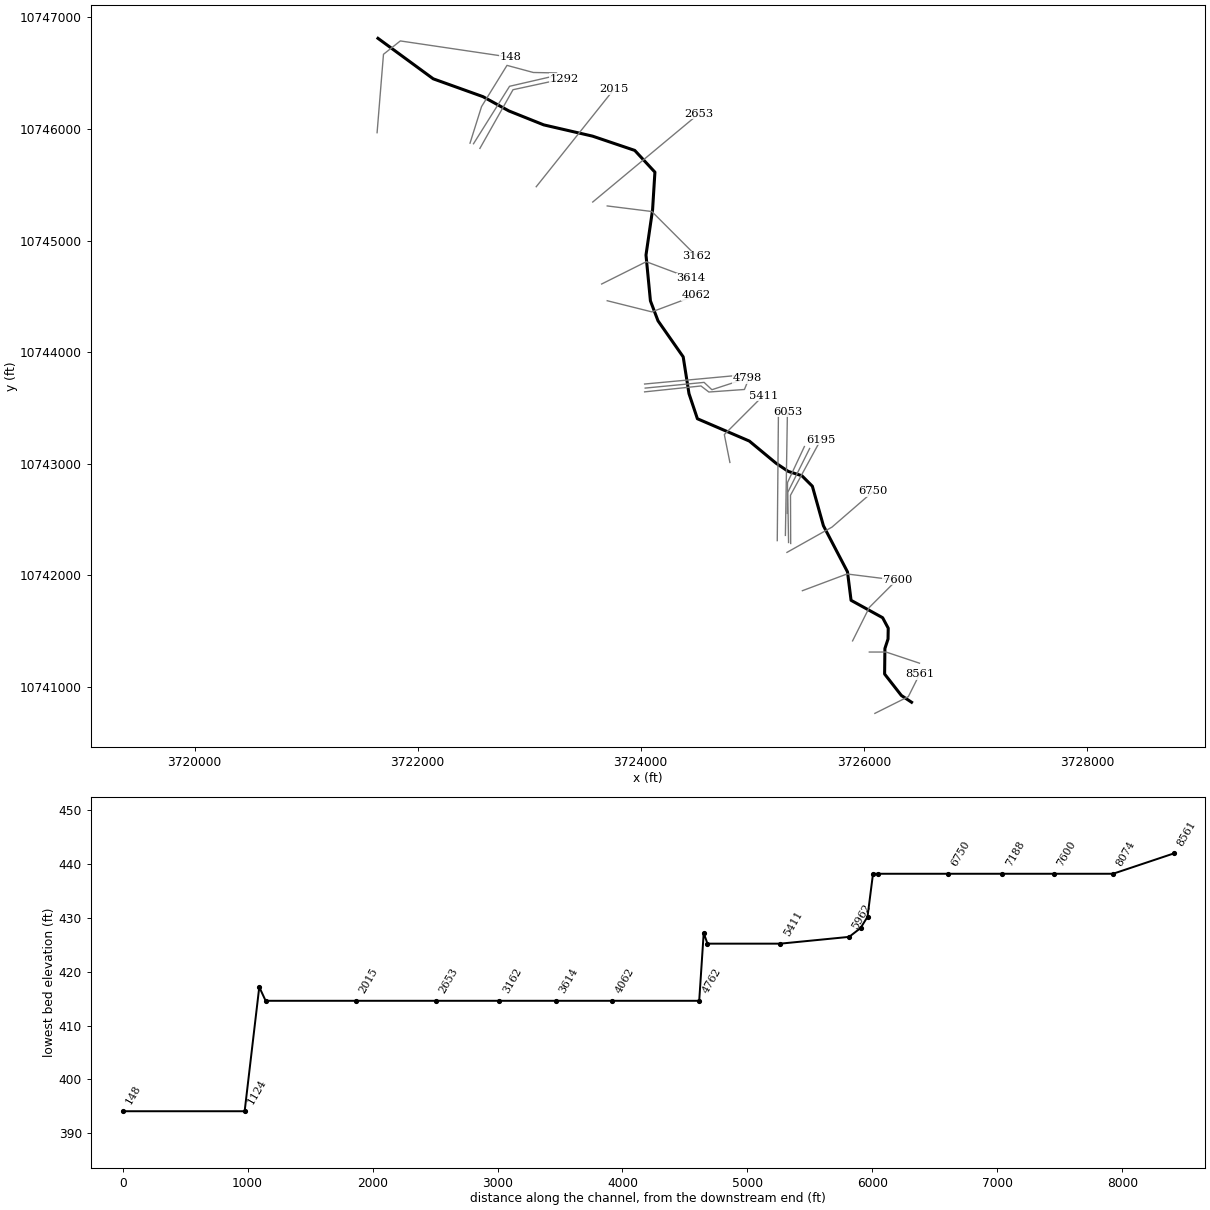
--- PALMER BRANCH.prj (project) ---

Proj Title=PALMER BRANCH Base Level Engineering
Current Plan=p01
Default Exp/Contr=0.3,0.1
English Units
Geom File=g01
Flow File=f01
Plan File=p01
BEGIN DESCRIPTION:
PALMER BRANCH
END DESCRIPTION:

--- PALMER BRANCH.p01 (plan) ---

Plan Title=Multiple Run
Short Identifier=Multiple
Geom File=g01
Flow File=f01
Subcritical Flow
K Sum by GR= 0
Std Step Tol= 0.01
Critical Tol= 0.01
Num of Std Step Trials= 20
Max Error Tol= 0.3
Flow Tol Ratio= 0.001
Split Flow NTrial= 30
Split Flow Tol= 0.02
Split Flow Ratio= 0.02
Log Output Level= 0
Friction Slope Method= 1
Unsteady Friction Slope Method= 2
Unsteady Bridges Friction Slope Method= 1
Parabolic Critical Depth
Global Vel Dist=  1 , 1 , 1
Global Log Level= 0
CheckData=True
Encroach Param= -1, 0, 0, 0
BEGIN DESCRIPTION:
Multiple Run
END DESCRIPTION:

--- PALMER BRANCH.f01 (steady flow) ---

Flow Title=Multiple
Number of Profiles=7
Profile Names=10-year,25-year,50-year,1pct_min,100-year,1pct_plu,500-year
River Rch & RM= PALMER BRANCH,Reach-1,8561
     778    1076    1327    1201    1624    2197    2438
River Rch & RM= PALMER BRANCH,Reach-1,7188
     922    1286    1594    1450    1961    2652    2971
River Rch & RM= PALMER BRANCH,Reach-1,6053
    1131    1589    1980    1807    2444    3305    3732
River Rch & RM= PALMER BRANCH,Reach-1,148
    2210    3197    4060    3768    5096    6891    8052
Boundary for River Rch & Prof#=PALMER BRANCH,Reach-1,1
Up Type=0
Dn Type=3
Dn Slope=0.005
Boundary for River Rch & Prof#=PALMER BRANCH,Reach-1,2
Up Type=0
Dn Type=3
Dn Slope=0.005
Boundary for River Rch & Prof#=PALMER BRANCH,Reach-1,3
Up Type=0
Dn Type=3
Dn Slope=0.005
Boundary for River Rch & Prof#=PALMER BRANCH,Reach-1,4
Up Type=0
Dn Type=3
Dn Slope=0.005
Boundary for River Rch & Prof#=PALMER BRANCH,Reach-1,5
Up Type=0
Dn Type=3
Dn Slope=0.005
Boundary for River Rch & Prof#=PALMER BRANCH,Reach-1,6
Up Type=0
Dn Type=3
Dn Slope=0.005
Boundary for River Rch & Prof#=PALMER BRANCH,Reach-1,7
Up Type=0
Dn Type=3
Dn Slope=0.005

--- PALMER BRANCH.g01 (geometry) ---

Geom Title=Existing Conditions

River Reach=PALMER BRANCH,Reach-1
Reach XY= 30
      3726428.50     10740860.00      3726336.75     10740921.00
      3726186.75     10741113.00      3726189.50     10741342.00
      3726217.50     10741427.00      3726219.25     10741524.00
      3726169.00     10741618.00      3725886.00     10741774.00
      3725854.00     10742029.00      3725638.00     10742443.00
      3725539.00     10742797.00      3725445.25     10742891.00
      3725322.75     10742930.00      3725213.50     10743003.00
      3724973.75     10743202.00      3724508.25     10743402.00
      3724432.75     10743627.00      3724380.75     10743957.00
      3724155.00     10744280.00      3724087.00     10744459.00
      3724047.25     10744870.00      3724106.25     10745276.00
      3724127.25     10745613.00      3723946.50     10745808.00
      3723568.00     10745936.00      3723130.50     10746037.00
      3722818.00     10746162.00      3722585.50     10746290.00
      3722139.50     10746450.00      3721644.00     10746813.00

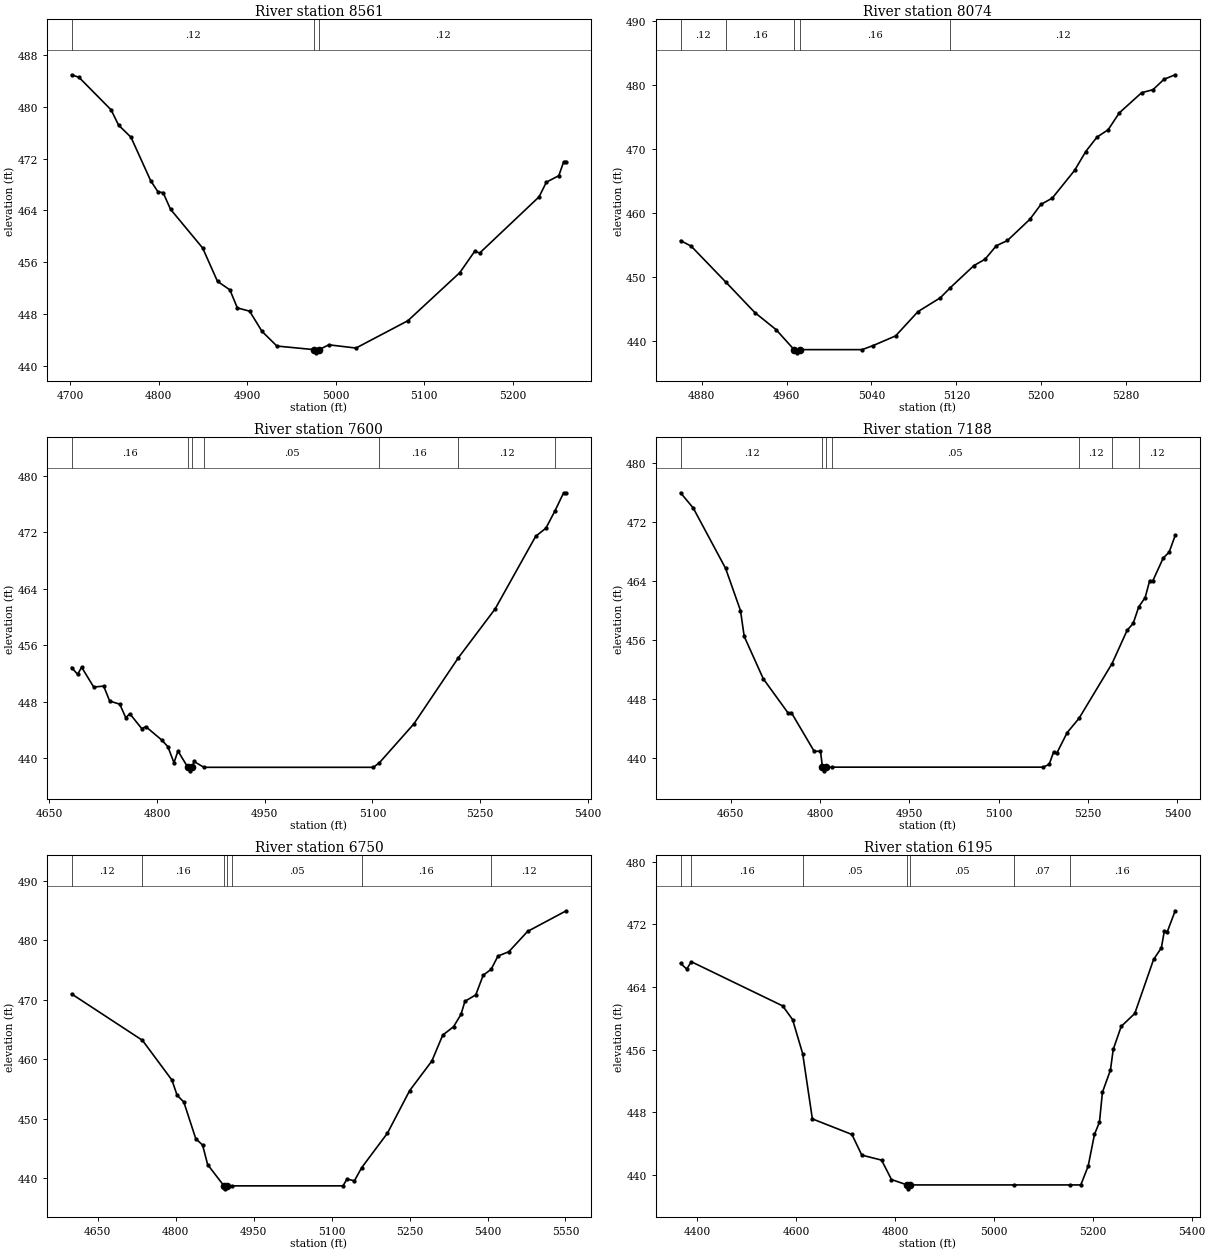
Type RM Length L Ch R = 1,8561,487,487,487
BEGIN DESCRIPTION:
PALMER BRANCH 16.0
END DESCRIPTION:
XS GIS Cut Line= 3
      3726099.63     10740760.20      3726399.61     10740910.19
      3726499.61     10741110.19
#Sta/Elev= 30
  4701.5  484.97  4709.9  484.57  4746.2  479.54  4754.6  477.18  4768.6  475.32
  4790.9  468.59  4799.3  466.84  4804.9  466.76  4813.3  464.18  4849.6  458.19
  4866.4  453.03  4880.4  451.72  4888.8  448.93  4902.7  448.42  4916.7  445.30
  4933.5  443.03  4975.2  442.48  4977.9  441.98  4981.2  442.48  4992.2  443.22
  5022.9  442.72  5081.6  446.95  5140.3  454.39  5157.1  457.69  5162.7  457.41
  5229.8  466.10  5238.1  468.37  5252.1  469.37  5257.7  471.54  5260.5  471.54
#Mann=3,-1,0
  4701.5    0.12       0  4975.2    0.07       0  4981.2    0.12       0
Bank Sta=4975.2,4981.2
Exp/Cntr=0.3,0.1

Type RM Length L Ch R = 1,8074,474,474,474
BEGIN DESCRIPTION:
PALMER BRANCH 15.0
END DESCRIPTION:
XS GIS Cut Line= 3
      3726049.60     10741310.19      3726199.61     10741310.19
      3726499.57     10741210.20
#Sta/Elev= 30
  4860.1  455.69  4870.1  454.83  4902.5  449.27  4930.1  444.48  4950.1  441.82
  4967.1  438.70  4969.9  438.20  4973.1  438.70  5031.2  438.70  5041.7  439.34
  5062.8  440.84  5083.9  444.63  5105.0  446.79  5114.3  448.35  5136.6  451.80
  5147.1  452.79  5157.7  454.89  5168.2  455.71  5189.3  459.01  5199.8  461.34
  5210.4  462.31  5231.5  466.64  5242.0  469.58  5252.6  471.83  5263.1  472.97
  5273.6  475.60  5294.7  478.75  5305.3  479.21  5315.8  480.84  5326.3  481.54
#Mann=5,-1,0
  4860.1    0.12       0  4902.5    0.16       0  4967.1    0.07       0
  4973.1    0.16       0  5114.3    0.12       0
Bank Sta=4967.1,4973.1
Exp/Cntr=0.3,0.1

Type RM Length L Ch R = 1,7600,412,412,412
BEGIN DESCRIPTION:
PALMER BRANCH 14.0
END DESCRIPTION:
XS GIS Cut Line= 3
      3725899.60     10741410.18      3726049.61     10741710.19
      3726299.63     10741960.21
#Sta/Elev= 30
  4681.0  452.85  4689.4  451.88  4695.0  452.89  4711.8  450.08  4725.7  450.21
  4734.1  448.09  4748.1  447.65  4756.5  445.73  4762.1  446.30  4778.8  444.18
  4784.4  444.47  4806.8  442.55  4815.2  441.61  4823.6  439.35  4829.2  441.01
  4842.9  438.70  4845.7  438.20  4848.9  438.70  4851.5  439.53  4865.3  438.70
  5101.3  438.70  5109.7  439.34  5157.8  444.86  5219.6  454.21  5271.0  461.16
  5327.5  471.46  5341.7  472.60  5354.4  475.07  5366.4  477.62  5370.0  477.62
#Mann=7,-1,0
  4681.0    0.16       0  4842.9   0.033       0  4848.9    0.16       0
  4865.3    0.05       0  5109.7    0.16       0  5219.6    0.12       0
  5354.4    0.05       0
Bank Sta=4842.9,4848.9
Exp/Cntr=0.3,0.1

Type RM Length L Ch R = 1,7188,438,438,438
BEGIN DESCRIPTION:
PALMER BRANCH 13.0
END DESCRIPTION:
XS GIS Cut Line= 3
      3725449.62     10741860.19      3725849.61     10742010.19
      3726249.61     10741960.19
#Sta/Elev= 30
  4565.9  475.94  4587.2  473.87  4641.5  465.68  4666.5  459.95  4672.7  456.46
  4704.7  450.70  4746.6  446.03  4751.9  446.10  4790.2  440.85  4800.8  440.86
  4804.1  438.70  4806.8  438.20  4810.1  438.70  4819.5  438.70  5174.5  438.70
  5184.6  439.07  5192.1  440.75  5197.2  440.56  5214.8  443.38  5234.8  445.33
  5290.2  452.76  5315.6  457.29  5325.7  458.21  5335.0  460.46  5345.8  461.72
  5353.4  464.03  5358.4  463.95  5376.0  467.07  5386.1  467.89  5396.2  470.15
#Mann=7,-1,0
  4565.9    0.12       0  4804.1   0.033       0  4810.1    0.12       0
  4819.5    0.05       0  5234.8    0.12       0  5290.2    0.16       0
  5335.0    0.12       0
Bank Sta=4804.1,4810.1
Exp/Cntr=0.3,0.1

Type RM Length L Ch R = 1,6750,555,555,555
BEGIN DESCRIPTION:
PALMER BRANCH 12.0
END DESCRIPTION:
XS GIS Cut Line= 3
      3725311.22     10742203.69      3725714.89     10742430.27
      3726084.65     10742750.56
#Sta/Elev= 30
  4599.4  470.95  4735.8  463.15  4792.5  456.48  4802.5  453.93  4815.4  452.79
  4838.4  446.63  4851.6  445.55  4861.3  442.27  4892.7  438.70  4895.5  438.20
  4898.7  438.70  4907.7  438.70  5121.9  438.70  5129.5  439.85  5143.8  439.55
  5157.7  441.75  5207.4  447.56  5250.1  454.70  5292.9  459.68  5313.8  464.03
  5334.6  465.44  5348.9  467.50  5356.5  469.71  5377.4  470.79  5391.6  474.08
  5407.0  475.09  5420.1  477.31  5441.0  478.04  5477.1  481.45  5551.5  484.92
#Mann=7,-1,0
  4599.4    0.12       0  4735.8    0.16       0  4892.7   0.033       0
  4898.7    0.16       0  4907.7    0.05       0  5157.7    0.16       0
  5407.0    0.12       0
Bank Sta=4892.7,4898.7
Exp/Cntr=0.3,0.1

Type RM Length L Ch R = 1,6195,42,42,42
BEGIN DESCRIPTION:
PALMER BRANCH 11.0
END DESCRIPTION:
XS GIS Cut Line= 3
      3725344.66     10742283.55      3725342.93     10742715.86
      3725614.88     10743214.74
#Sta/Elev= 30
  4366.1  467.02  4378.6  466.29  4387.8  467.23  4572.7  461.58  4592.7  459.83
  4613.1  455.48  4632.7  447.14  4712.7  445.15  4732.7  442.51  4772.7  441.87
  4792.7  439.39  4824.3  438.70  4827.1  438.20  4830.3  438.70  5040.9  438.70
  5153.1  438.70  5175.7  438.70  5190.6  441.11  5203.3  445.16  5213.4  446.72
  5219.4  450.54  5235.6  453.38  5241.3  456.03  5257.4  458.96  5284.9  460.62
  5322.9  467.52  5338.6  469.00  5344.7  471.18  5350.4  471.03  5366.6  473.74
#Mann=7,-1,0
  4366.1    0.12       0  4387.8    0.16       0  4613.1    0.05       0
  4824.3   0.033       0  4830.3    0.05       0  5040.9    0.07       0
  5153.1    0.16       0
Bank Sta=4824.3,4830.3
Exp/Cntr=0.3,0.1

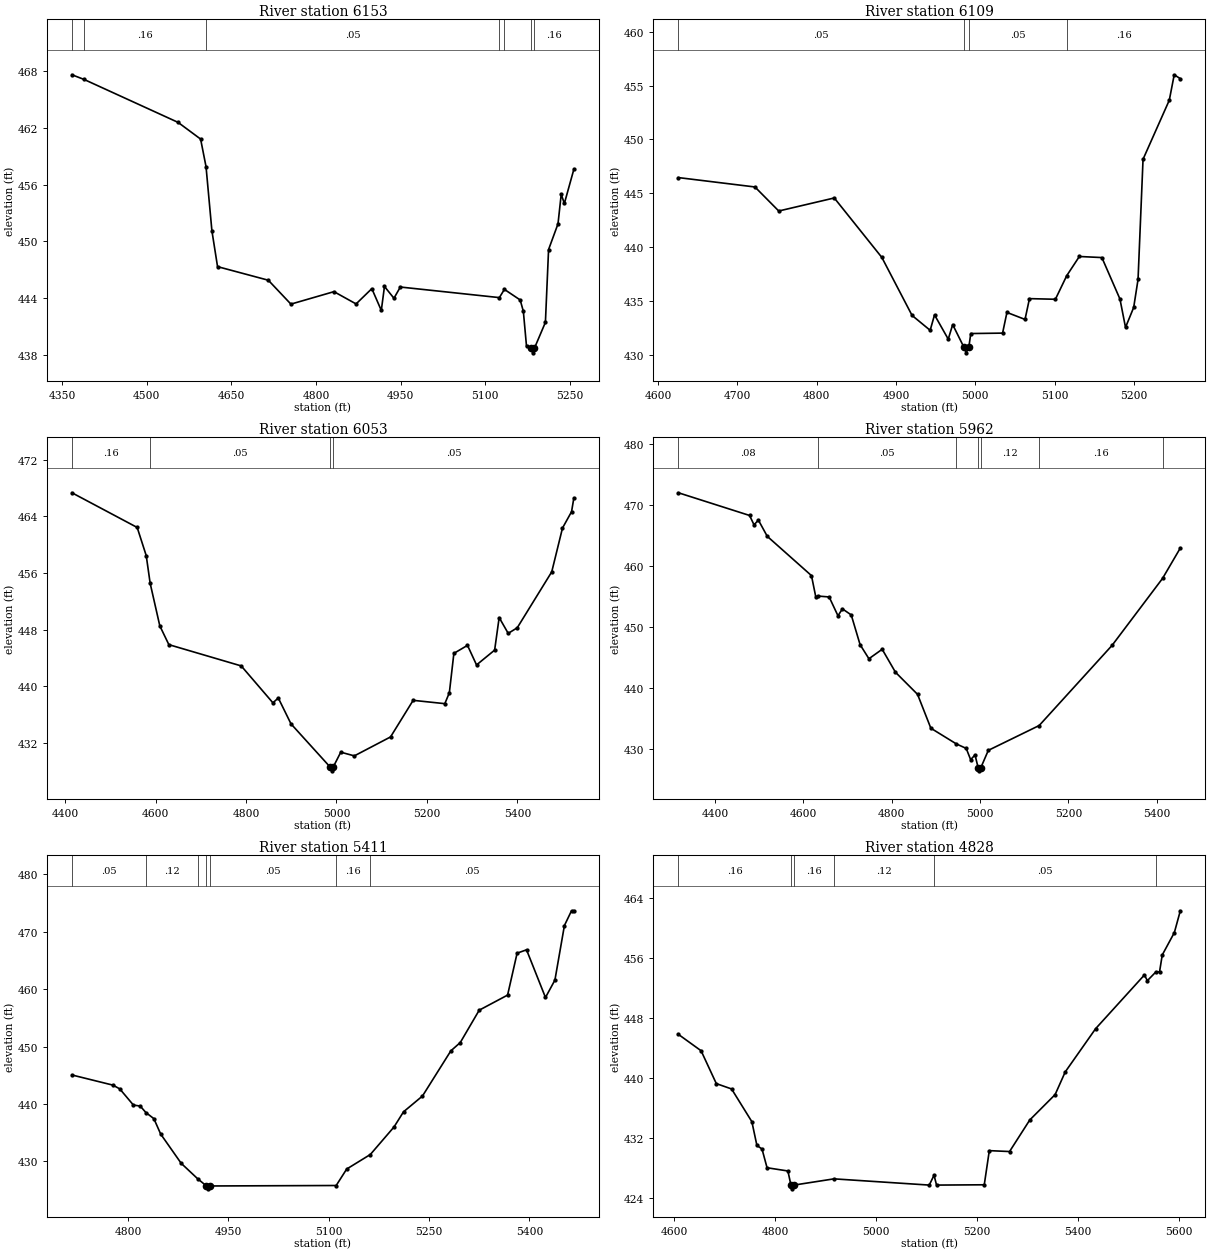
Type RM Length L Ch R = 1,6153,44,44,44
BEGIN DESCRIPTION:
Mapping XS 06f1582a
END DESCRIPTION:
XS GIS Cut Line= 3
      3725325.57     10742292.23      3725318.32     10742742.12
      3725514.56     10743135.32
#Sta/Elev= 30
  4367.5  467.65  4389.2  467.15  4555.5  462.61  4595.5  460.84  4605.1  457.92
  4615.5  451.13  4625.5  447.33  4715.5  445.89  4755.5  443.36  4831.8  444.68
  4871.0  443.38  4898.9  445.00  4915.7  442.69  4921.3  445.23  4938.1  443.98
  4949.4  445.17  5124.9  444.05  5133.8  444.92  5161.8  443.80  5167.4  442.60
  5173.0  438.90  5181.1  438.70  5183.9  438.20  5187.1  438.70  5206.5  441.43
  5212.1  449.14  5228.8  451.86  5234.5  454.99  5240.1  454.02  5256.9  457.64
#Mann=7,-1,0
  4367.5    0.12       0  4389.2    0.16       0  4605.1    0.05       0
  5124.9    0.07       0  5133.8    0.16       0  5181.1   0.033       0
  5187.1    0.16       0
Bank Sta=5181.1,5187.1
Exp/Cntr=0.3,0.1

Type RM Length L Ch R = 1,6109,56,56,56
BEGIN DESCRIPTION:
Mapping XS 3afe9371
END DESCRIPTION:
XS GIS Cut Line= 3
      3725313.54     10742553.74      3725316.11     10742829.81
      3725467.55     10743152.78
#Sta/Elev= 30
  4625.6  446.46  4722.1  445.59  4752.1  443.36  4822.1  444.57  4882.1  439.05
  4920.2  433.67  4943.0  432.29  4948.5  433.72  4965.8  431.47  4971.4  432.82
  4985.7  430.70  4988.4  430.20  4991.7  430.70  4994.2  431.99  5034.3  432.03
  5039.8  433.95  5062.6  433.30  5068.2  435.23  5100.9  435.17  5115.2  437.36
  5131.1  439.14  5159.5  439.04  5182.3  435.19  5189.3  432.56  5199.6  434.41
  5205.1  437.01  5211.4  448.16  5244.5  453.64  5250.7  456.00  5258.4  455.64
#Mann=4,-1,0
  4625.6    0.05       0  4985.7    0.04       0  4991.7    0.05       0
  5115.2    0.16       0
Bank Sta=4985.7,4991.7
Exp/Cntr=0.3,0.1

Type RM Length L Ch R = 1,6053,91,91,91
BEGIN DESCRIPTION:
Mapping XS 11bc655a
END DESCRIPTION:
XS GIS Cut Line= 2
      3725297.17     10742356.05      3725315.39     10743465.30
#Sta/Elev= 30
  4415.3  467.31  4559.5  462.42  4579.5  458.45  4588.2  454.54  4609.5  448.55
  4629.5  445.90  4789.5  442.90  4859.5  437.70  4871.4  438.38  4899.5  434.73
  4986.5  428.61  4989.3  428.11  4992.5  428.61  5009.5  430.74  5039.5  430.22
  5119.5  432.89  5169.5  438.05  5239.5  437.58  5249.5  439.12  5259.5  444.67
  5289.6  445.80  5309.6  443.04  5349.6  445.13  5359.6  449.72  5379.6  447.49
  5399.6  448.28  5475.8  456.16  5499.6  462.34  5519.6  464.64  5524.7  466.58
#Mann=4,-1,0
  4415.3    0.16       0  4588.2    0.05       0  4986.5    0.04       0
  4992.5    0.05       0
Bank Sta=4986.5,4992.5
Exp/Cntr=0.3,0.1

Type RM Length L Ch R = 1,5962,551,551,551
BEGIN DESCRIPTION:
PALMER BRANCH 10.0
END DESCRIPTION:
XS GIS Cut Line= 2
      3725224.25     10742309.16      3725234.67     10743444.61
#Sta/Elev= 30
  4317.5  472.07  4478.5  468.35  4488.5  466.82  4498.5  467.58  4518.5  464.93
  4618.5  458.49  4628.5  454.92  4632.5  455.14  4658.5  454.99  4678.5  451.90
  4688.5  453.04  4708.5  452.04  4728.5  447.17  4748.5  444.86  4778.5  446.41
  4808.5  442.65  4858.5  439.02  4888.6  433.47  4946.4  430.89  4968.6  430.16
  4978.6  428.32  4988.6  429.08  4995.6  426.98  4998.3  426.48  5001.6  426.98
  5018.6  429.84  5133.7  433.91  5298.6  447.05  5412.8  458.03  5453.0  463.01
#Mann=7,-1,0
  4317.5    0.08       0  4632.5    0.05       0  4946.4    0.12       0
  4995.6    0.07       0  5001.6    0.12       0  5133.7    0.16       0
  5412.8    0.05       0
Bank Sta=4995.6,5001.6
Exp/Cntr=0.3,0.1

Type RM Length L Ch R = 1,5411,583,583,583
BEGIN DESCRIPTION:
PALMER BRANCH 9.0
END DESCRIPTION:
XS GIS Cut Line= 3
      3724799.61     10743010.19      3724749.61     10743260.19
      3725099.59     10743610.17
#Sta/Elev= 30
  4716.4  445.06  4777.6  443.29  4787.8  442.64  4808.2  439.82  4818.4  439.64
  4827.0  438.50  4838.8  437.45  4849.0  434.76  4879.6  429.67  4904.2  426.98
  4917.4  425.72  4920.1  425.22  4923.4  425.72  5111.2  425.80  5126.9  428.67
  5162.2  431.20  5197.6  436.00  5211.8  438.64  5240.1  441.39  5282.5  449.26
  5296.6  450.71  5324.9  456.35  5367.3  458.98  5381.5  466.28  5395.6  466.87
  5423.9  458.56  5438.0  461.59  5452.2  471.10  5462.8  473.67  5466.3  473.67
#Mann=7,-1,0
  4716.4    0.05       0  4827.0    0.12       0  4904.2    0.05       0
  4917.4   0.033       0  4923.4    0.05       0  5111.2    0.16       0
  5162.2    0.05       0
Bank Sta=4917.4,4923.4
Exp/Cntr=0.3,0.1

Type RM Length L Ch R = 1,4828,30,30,30
BEGIN DESCRIPTION:
PALMER BRANCH 8.0
END DESCRIPTION:
XS GIS Cut Line= 5
      3724034.93     10743643.06      3724540.32     10743695.89
      3724610.85     10743641.64      3724929.86     10743664.43
      3724959.09     10743736.04
#Sta/Elev= 30
  4607.9  445.80  4652.8  443.62  4683.0  439.24  4713.2  438.53  4753.4  434.17
  4763.4  431.00  4773.5  430.53  4783.5  428.03  4824.8  427.60  4830.8  425.72
  4833.6  425.22  4836.8  425.72  4916.1  426.55  5104.8  425.72  5114.3  427.03
  5119.3  425.72  5213.8  425.76  5223.8  430.31  5263.9  430.19  5304.0  434.40
  5354.2  437.78  5374.2  440.80  5434.4  446.56  5531.1  453.72  5536.9  452.96
  5553.9  454.13  5561.0  454.12  5566.4  456.38  5590.4  459.37  5602.2  462.27
#Mann=6,-1,0
  4607.9    0.16       0  4830.8    0.07       0  4836.8    0.16       0
  4916.1    0.12       0  5114.3    0.05       0  5553.9    0.12       0
Bank Sta=4830.8,4836.8
Exp/Cntr=0.3,0.1

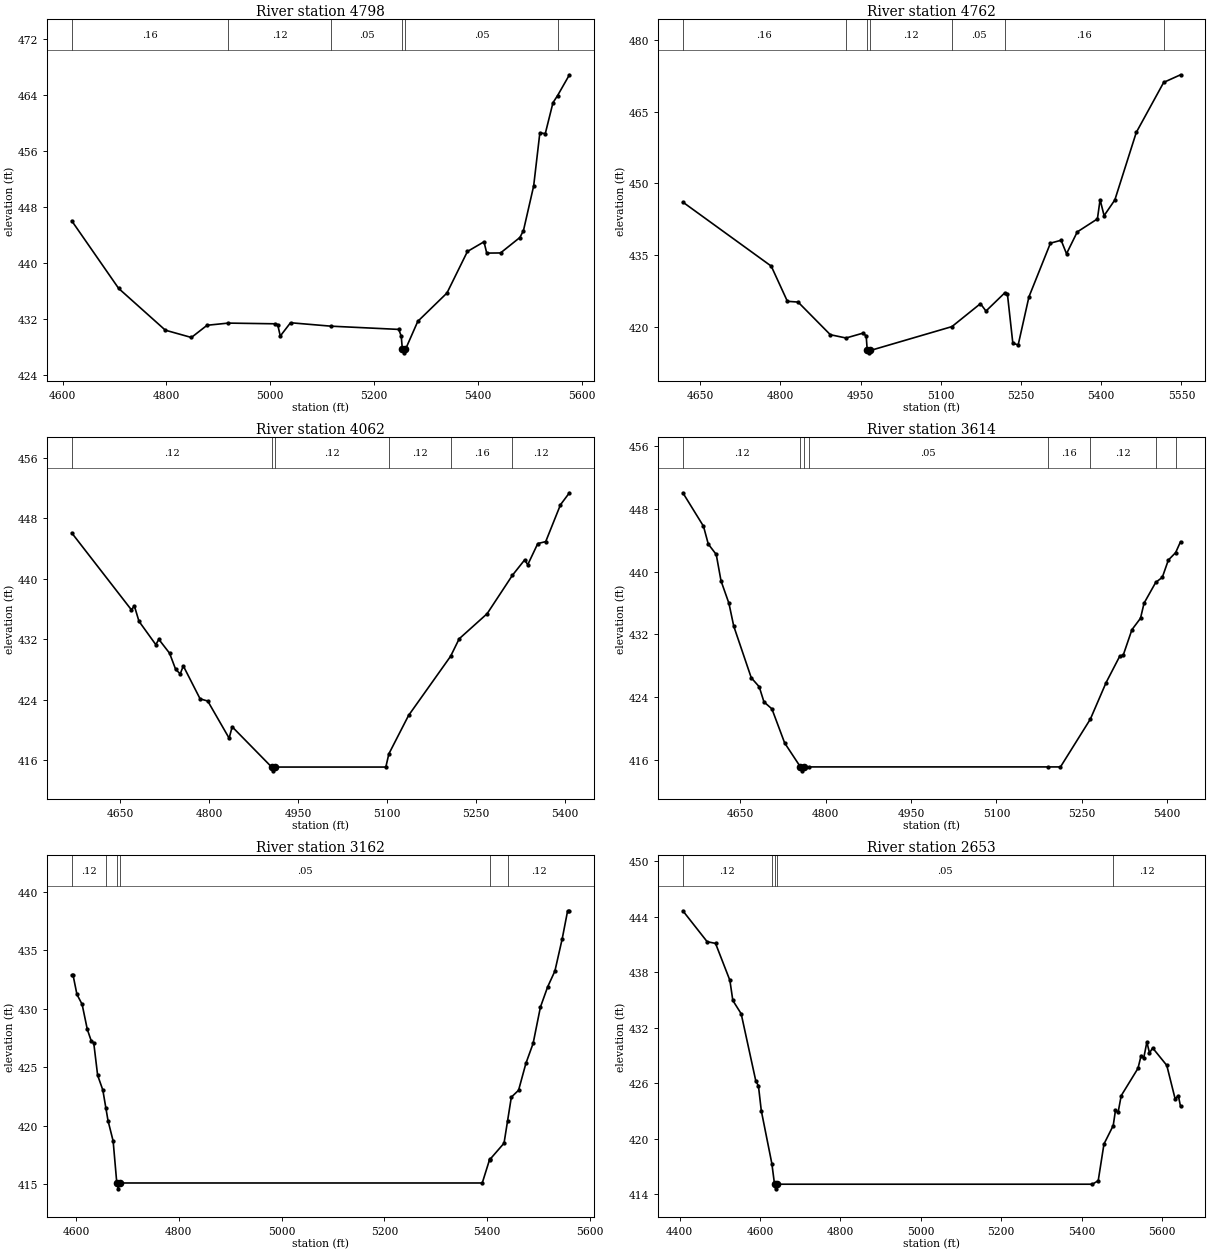
Type RM Length L Ch R = 1,4798,36,36,36
BEGIN DESCRIPTION:
Mapping XS f7476a7e
END DESCRIPTION:
XS GIS Cut Line= 4
      3724040.15     10743676.91      3724568.26     10743728.07
      3724637.98     10743662.26      3724953.83     10743765.33
#Sta/Elev= 30
  4617.6  446.03  4708.0  436.39  4797.9  430.44  4848.1  429.40  4878.3  431.14
  4919.1  431.45  5008.9  431.35  5014.3  431.24  5019.3  429.60  5039.0  431.50
  5117.2  431.01  5247.5  430.55  5252.3  429.59  5254.5  427.71  5257.3  427.21
  5260.5  427.71  5284.2  431.70  5340.4  435.74  5379.8  441.66  5411.7  443.04
  5417.0  441.43  5443.6  441.45  5480.8  443.65  5487.7  444.63  5507.4  451.00
  5519.3  458.56  5529.8  458.47  5544.6  462.87  5553.5  463.89  5576.3  466.85
#Mann=6,-1,0
  4617.6    0.16       0  4919.1    0.12       0  5117.2    0.05       0
  5254.5    0.07       0  5260.5    0.05       0  5553.5    0.12       0
Bank Sta=5254.5,5260.5
Exp/Cntr=0.3,0.1

Type RM Length L Ch R = 1,4762,700,700,700
BEGIN DESCRIPTION:
PALMER BRANCH 7.0
END DESCRIPTION:
XS GIS Cut Line= 2
      3724034.88     10743713.36      3724962.01     10743799.30
#Sta/Elev= 30
  4617.3  446.11  4782.7  432.73  4812.9  425.38  4832.9  425.22  4893.2  418.40
  4922.6  417.71  4953.5  418.70  4960.3  418.18  4962.3  415.11  4965.1  414.61
  4968.3  415.11  5120.7  420.09  5174.1  424.89  5184.4  423.34  5219.7  427.16
  5224.6  426.82  5234.7  416.59  5244.7  416.28  5264.8  426.31  5305.0  437.53
  5325.0  438.14  5335.1  435.32  5355.2  439.88  5392.9  442.60  5397.9  446.62
  5405.4  443.28  5425.5  446.56  5465.6  460.67  5516.9  471.13  5548.4  472.72
#Mann=7,-1,0
  4617.3    0.16       0  4922.6    0.12       0  4962.3    0.07       0
  4968.3    0.12       0  5120.7    0.05       0  5219.7    0.16       0
  5516.9    0.12       0
Bank Sta=4962.3,4968.3
Exp/Cntr=0.3,0.1

Type RM Length L Ch R = 1,4062,448,448,448
BEGIN DESCRIPTION:
PALMER BRANCH 6.0
END DESCRIPTION:
XS GIS Cut Line= 3
      3723699.58     10744460.20      3724099.61     10744360.19
      3724499.57     10744510.17
#Sta/Elev= 30
  4568.4  446.04  4668.9  435.89  4674.1  436.38  4681.8  434.37  4710.2  431.28
  4715.3  431.98  4733.4  430.15  4743.7  428.01  4751.4  427.42  4756.6  428.47
  4784.9  424.12  4797.8  423.83  4833.9  418.92  4839.0  420.43  4905.6  415.11
  4908.3  414.61  4911.6  415.11  5098.2  415.11  5103.3  416.85  5136.5  421.92
  5207.5  429.75  5221.9  432.05  5269.1  435.37  5311.7  440.44  5332.3  442.47
  5337.6  441.84  5354.5  444.63  5367.9  444.89  5392.8  449.76  5407.9  451.34
#Mann=6,-1,0
  4568.4    0.12       0  4905.6   0.033       0  4911.6    0.12       0
  5103.3    0.12       0  5207.5    0.16       0  5311.7    0.12       0
Bank Sta=4905.6,4911.6
Exp/Cntr=0.3,0.1

Type RM Length L Ch R = 1,3614,452,452,452
BEGIN DESCRIPTION:
PALMER BRANCH 5.0
END DESCRIPTION:
XS GIS Cut Line= 3
      3723649.62     10744610.19      3724049.61     10744810.19
      3724449.61     10744660.19
#Sta/Elev= 30
  4549.0  450.07  4585.3  445.80  4593.7  443.53  4607.7  442.20  4616.1  438.83
  4630.0  435.97  4638.4  433.07  4669.2  426.48  4683.2  425.33  4691.5  423.40
  4705.5  422.51  4727.9  418.16  4755.6  415.11  4758.4  414.61  4761.6  415.11
  4770.1  415.11  5189.8  415.11  5212.5  415.11  5265.0  421.21  5292.6  425.86
  5316.6  429.23  5322.8  429.38  5338.0  432.61  5353.1  434.07  5359.3  435.99
  5379.8  438.64  5391.4  439.29  5402.0  441.49  5414.8  442.44  5423.4  443.83
#Mann=8,-1,0
  4549.0    0.12       0  4755.6   0.033       0  4761.6    0.12       0
  4770.1    0.05       0  5189.8    0.16       0  5265.0    0.12       0
  5379.8    0.16       0  5414.8    0.12       0
Bank Sta=4755.6,4761.6
Exp/Cntr=0.3,0.1

Type RM Length L Ch R = 1,3162,509,509,509
BEGIN DESCRIPTION:
PALMER BRANCH 4.0
END DESCRIPTION:
XS GIS Cut Line= 3
      3723699.59     10745310.19      3724099.61     10745260.19
      3724499.59     10744860.20
#Sta/Elev= 30
  4591.5  432.88  4594.0  432.88  4601.6  431.22  4611.7  430.37  4621.8  428.23
  4629.3  427.27  4634.4  427.05  4641.9  424.31  4652.0  423.05  4657.8  421.55
  4662.1  420.44  4672.1  418.69  4679.2  415.11  4682.0  414.61  4685.2  415.11
  5390.6  415.11  5404.8  417.10  5406.1  417.15  5433.0  418.51  5439.9  420.42
  5447.2  422.44  5461.3  423.03  5475.5  425.32  5489.6  427.03  5503.8  430.13
  5517.9  431.86  5532.0  433.21  5546.2  435.96  5556.8  438.36  5560.3  438.36
#Mann=6,-1,0
  4591.5    0.12       0  4657.8    0.05       0  4679.2   0.033       0
  4685.2    0.05       0  5406.1    0.16       0  5439.9    0.12       0
Bank Sta=4679.2,4685.2
Exp/Cntr=0.3,0.1

Type RM Length L Ch R = 1,2653,638,638,638
BEGIN DESCRIPTION:
PALMER BRANCH 3.0
END DESCRIPTION:
XS GIS Cut Line= 2
      3723569.65     10745345.26      3724521.05     10746136.93
#Sta/Elev= 30
  4408.2  444.63  4468.7  441.29  4489.5  441.11  4525.2  437.12  4532.5  434.95
  4553.3  433.51  4589.7  426.25  4596.2  425.73  4603.3  423.05  4629.6  417.33
  4636.2  415.11  4639.0  414.61  4642.2  415.11  5426.8  415.11  5441.2  415.49
  5455.5  419.45  5478.5  421.44  5484.1  423.08  5490.6  422.86  5498.4  424.67
  5540.1  427.62  5547.9  429.00  5554.4  428.73  5562.2  430.46  5568.7  429.28
  5576.6  429.82  5611.7  427.94  5632.5  424.32  5640.4  424.67  5645.9  423.52
#Mann=5,-1,0
  4408.2    0.12       0  4629.6    0.05       0  4636.2   0.033       0
  4642.2    0.05       0  5478.5    0.12       0
Bank Sta=4636.2,4642.2
Exp/Cntr=0.3,0.1

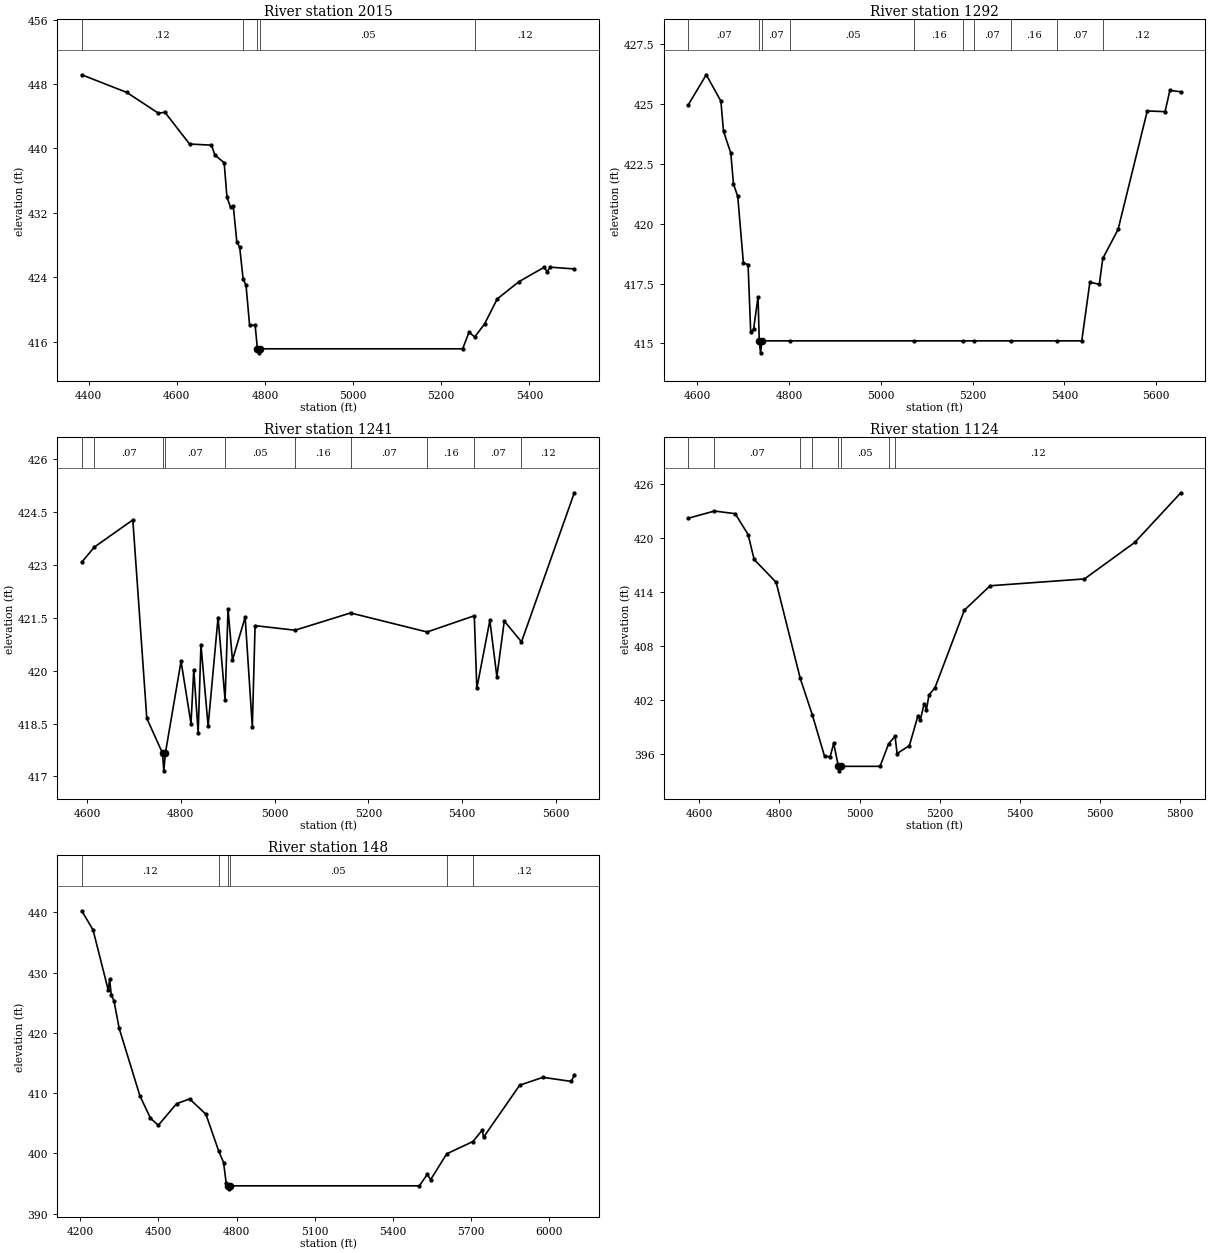
Type RM Length L Ch R = 1,2015,723,723,723
BEGIN DESCRIPTION:
Mapping XS abab85bf
END DESCRIPTION:
XS GIS Cut Line= 2
      3723063.15     10745482.48      3723760.17     10746356.35
#Sta/Elev= 30
  4384.2  449.14  4486.4  446.95  4558.4  444.36  4572.9  444.49  4628.9  440.54
  4678.5  440.40  4686.5  439.17  4707.4  438.22  4713.8  433.92  4721.8  432.71
  4728.2  432.79  4736.2  428.35  4742.6  427.75  4750.4  423.78  4757.0  423.02
  4765.0  418.10  4777.8  418.01  4782.8  415.11  4785.6  414.61  4788.8  415.11
  5248.6  415.11  5263.0  417.16  5276.0  416.59  5298.2  418.18  5327.1  421.31
  5376.7  423.46  5432.7  425.21  5440.8  424.70  5447.2  425.25  5502.0  425.03
#Mann=5,-1,0
  4384.2    0.12       0  4750.4    0.05       0  4782.8   0.033       0
  4788.8    0.05       0  5276.0    0.12       0
Bank Sta=4782.8,4788.8
Exp/Cntr=0.3,0.1

Type RM Length L Ch R = 1,1292,51,51,51
BEGIN DESCRIPTION:
Mapping XS 9371ee1e
END DESCRIPTION:
XS GIS Cut Line= 3
      3722557.93     10745826.22      3722854.81     10746352.26
      3723313.12     10746451.21
#Sta/Elev= 30
  4580.4  424.96  4619.7  426.22  4651.6  425.12  4657.3  423.86  4673.2  422.95
  4679.0  421.66  4688.3  421.14  4700.6  418.37  4710.8  418.29  4716.5  415.49
  4722.8  415.59  4732.5  416.95  4735.2  415.11  4737.9  414.61  4741.2  415.11
  4802.9  415.11  5073.2  415.11  5180.0  415.11  5203.3  415.11  5282.5  415.11
  5382.9  415.11  5437.6  415.11  5455.3  417.56  5475.8  417.47  5483.4  418.55
  5516.7  419.76  5580.3  424.71  5619.0  424.68  5629.6  425.57  5653.3  425.51
#Mann=10,-1,0
  4580.4    0.07       0  4735.2   0.033       0  4741.2    0.07       0
  4802.9    0.05       0  5073.2    0.16       0  5180.0    0.05       0
  5203.3    0.07       0  5282.5    0.16       0  5382.9    0.07       0
  5483.4    0.12       0
Bank Sta=4735.2,4741.2
Exp/Cntr=0.3,0.1

Type RM Length L Ch R = 1,1241,117,117,117
BEGIN DESCRIPTION:
Mapping XS 5f756027
END DESCRIPTION:
XS GIS Cut Line= 3
      3722500.63     10745867.86      3722823.86     10746383.01
      3723255.22     10746482.32
#Sta/Elev= 30
  4588.6  423.08  4615.6  423.51  4697.6  424.28  4727.4  418.65  4761.0  417.66
  4763.7  417.16  4767.0  417.66  4800.5  420.27  4821.7  418.50  4827.6  420.03
  4837.0  418.24  4842.9  420.74  4858.2  418.43  4879.4  421.51  4894.4  419.17
  4900.7  421.75  4910.1  420.30  4937.2  421.52  4952.5  418.41  4958.4  421.28
  5043.5  421.15  5162.1  421.64  5325.3  421.10  5426.0  421.56  5431.4  419.50
  5459.2  421.43  5474.2  419.83  5490.0  421.41  5526.7  420.82  5639.4  425.05
#Mann=10,-1,0
  4588.6    0.12       0  4615.6    0.07       0  4761.0    0.03       0
  4767.0    0.07       0  4894.4    0.05       0  5043.5    0.16       0
  5162.1    0.07       0  5325.3    0.16       0  5426.0    0.07       0
  5526.7    0.12       0
Bank Sta=4761,4767
Exp/Cntr=0.3,0.1

Type RM Length L Ch R = 1,1124,976,976,976
BEGIN DESCRIPTION:
PALMER BRANCH 2.0
END DESCRIPTION:
XS GIS Cut Line= 5
      3722469.40     10745873.13      3722572.56     10746200.72
      3722800.86     10746570.51      3723037.40     10746506.71
      3723244.74     10746502.81
#Sta/Elev= 30
  4572.0  422.16  4637.4  422.96  4689.3  422.67  4721.7  420.35  4736.7  417.58
  4791.7  415.04  4851.8  404.38  4882.2  400.30  4912.5  395.73  4926.6  395.67
  4935.4  397.15  4947.1  394.60  4949.8  394.10  4953.1  394.60  5051.3  394.60
  5072.7  397.12  5088.7  397.94  5093.8  396.02  5124.6  396.91  5145.9  400.22
  5151.8  399.74  5161.3  401.56  5167.2  400.91  5173.4  402.53  5188.4  403.33
  5261.8  411.95  5326.1  414.66  5561.8  415.42  5687.3  419.47  5802.4  424.99
#Mann=8,-1,0
  4572.0    0.12       0  4637.4    0.07       0  4851.8    0.12       0
  4882.2    0.05       0  4947.1   0.035       0  4953.1    0.05       0
  5072.7    0.16       0  5088.7    0.12       0
Bank Sta=4947.1,4953.1
Exp/Cntr=0.3,0.1

Type RM Length L Ch R = 1,148,0,0,0
BEGIN DESCRIPTION:
PALMER BRANCH 1.0
END DESCRIPTION:
XS GIS Cut Line= 4
      3721636.05     10745966.81      3721693.35     10746669.96
      3721844.39     10746789.76      3722828.78     10746643.92
#Sta/Elev= 30
  4205.1  440.26  4248.6  437.08  4307.1  427.07  4312.1  428.86  4318.9  426.20
  4328.9  425.35  4349.0  420.74  4428.9  409.52  4469.4  405.82  4499.5  404.66
  4569.7  408.23  4619.8  409.03  4682.5  406.48  4731.4  400.39  4750.3  398.47
  4760.3  395.06  4767.3  394.60  4770.1  394.10  4773.3  394.60  5502.9  394.60
  5533.2  396.49  5546.2  395.62  5608.0  399.91  5708.6  401.95  5744.6  403.84
  5749.6  402.67  5888.6  411.31  5978.0  412.61  6087.0  411.93  6098.5  413.01
#Mann=6,-1,0
  4205.1    0.12       0  4731.4    0.05       0  4767.3   0.033       0
  4773.3    0.05       0  5608.0    0.16       0  5708.6    0.12       0
Bank Sta=4767.3,4773.3
Exp/Cntr=0.3,0.1

Chan Stop Cuts=-1