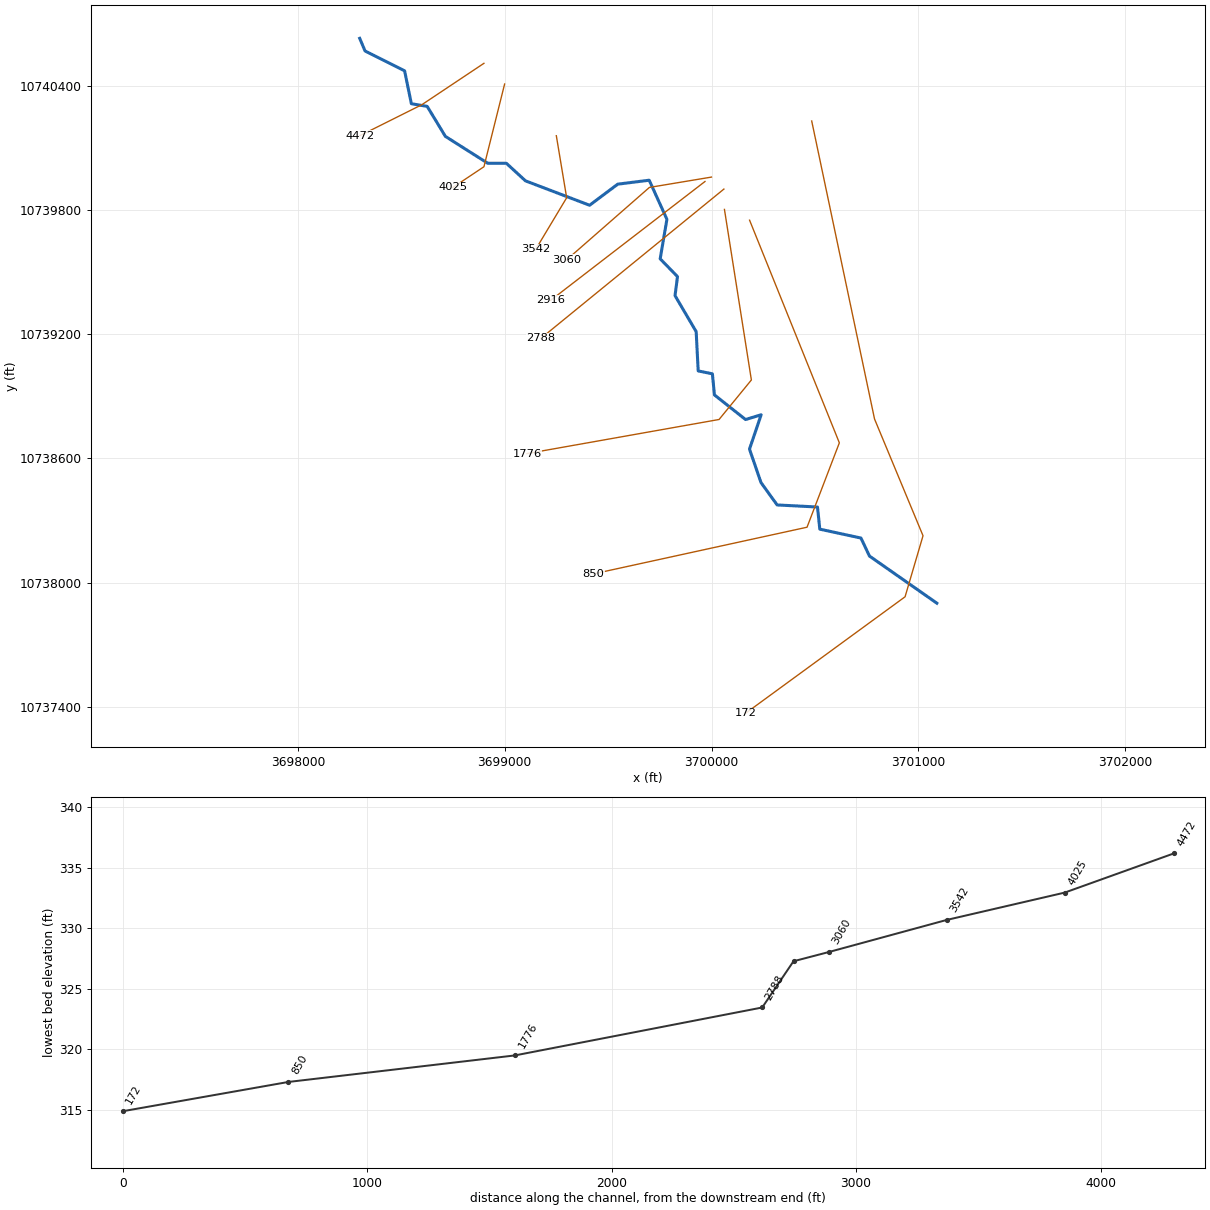
--- PICKLE BRANCH.prj (project) ---

Proj Title=PICKLE BRANCH Base Level Engineering
Current Plan=p01
Default Exp/Contr=0.3,0.1
English Units
Geom File=g01
Flow File=f01
Plan File=p01
Y Axis Title=Elevation
X Axis Title(PF)=Main Channel Distance
X Axis Title(XS)=Station
BEGIN DESCRIPTION:
PICKLE BRANCH
END DESCRIPTION:
DSS Export Rating Curves= 0
DSS Export Rating Curve Sorted= 0
DSS Export Volume Flow Curves= 0
DXF OffsetX= 0
DXF OffsetY= 0
DXF ScaleX= 1
DXF ScaleY= 10

--- PICKLE BRANCH.p01 (plan) ---

Plan Title=Multiple Run
Short Identifier=Multiple
Geom File=g01
Flow File=f01
Subcritical Flow
K Sum by GR= 0
Std Step Tol= 0.01
Critical Tol= 0.01
Num of Std Step Trials= 20
Max Error Tol= 0.3
Flow Tol Ratio= 0.001
Split Flow NTrial= 30
Split Flow Tol= 0.02
Split Flow Ratio= 0.02
Log Output Level= 0
Friction Slope Method= 1
Unsteady Friction Slope Method= 2
Unsteady Bridges Friction Slope Method= 1
Parabolic Critical Depth
Global Vel Dist=  1 , 1 , 1
Global Log Level= 0
CheckData=True
Encroach Param= -1, 0, 0, 0
BEGIN DESCRIPTION:
Multiple Run
END DESCRIPTION:

--- PICKLE BRANCH.f01 (steady flow) ---

Flow Title=Multiple
Number of Profiles=7
Profile Names=10-year,25-year,50-year,1pct_min,100-year,1pct_plu,500-year
River Rch & RM= PICKLE BRANCH,Reach-1,4472
     880    1229    1526    1390    1880    2542    2859
River Rch & RM= PICKLE BRANCH,Reach-1,3060
    1118    1565    1944    1768    2391    3234    3629
Boundary for River Rch & Prof#=PICKLE BRANCH,Reach-1,1
Up Type=0
Dn Type=3
Dn Slope=0.005
Boundary for River Rch & Prof#=PICKLE BRANCH,Reach-1,2
Up Type=0
Dn Type=3
Dn Slope=0.005
Boundary for River Rch & Prof#=PICKLE BRANCH,Reach-1,3
Up Type=0
Dn Type=3
Dn Slope=0.005
Boundary for River Rch & Prof#=PICKLE BRANCH,Reach-1,4
Up Type=0
Dn Type=3
Dn Slope=0.005
Boundary for River Rch & Prof#=PICKLE BRANCH,Reach-1,5
Up Type=0
Dn Type=3
Dn Slope=0.005
Boundary for River Rch & Prof#=PICKLE BRANCH,Reach-1,6
Up Type=0
Dn Type=3
Dn Slope=0.005
Boundary for River Rch & Prof#=PICKLE BRANCH,Reach-1,7
Up Type=0
Dn Type=3
Dn Slope=0.005

--- PICKLE BRANCH.g01 (geometry) ---

Geom Title=Existing Conditions
Program Version=4.10

River Reach=PICKLE BRANCH   ,Reach-1
Reach XY= 30
        3698299.       10740631.      3698324.75       10740570.
        3698516.       10740474.      3698548.75       10740315.
      3698625.25       10740302.      3698713.25       10740157.
        3698918.       10740027.        3699008.       10740027.
       3699100.5       10739942.       3699410.5       10739824.
      3699546.75       10739926.      3699698.75       10739945.
      3699784.25       10739756.      3699751.75       10739565.
       3699835.5       10739479.       3699823.5       10739387.
      3699925.75       10739213.       3699935.5       10739023.
      3700004.25       10739009.        3700014.       10738907.
       3700164.5       10738788.        3700240.       10738811.
       3700183.5       10738645.      3700239.25       10738483.
      3700317.25       10738375.      3700512.25       10738365.
       3700523.5       10738258.       3700722.5       10738215.
       3700763.5       10738128.       3701089.5       10737900.

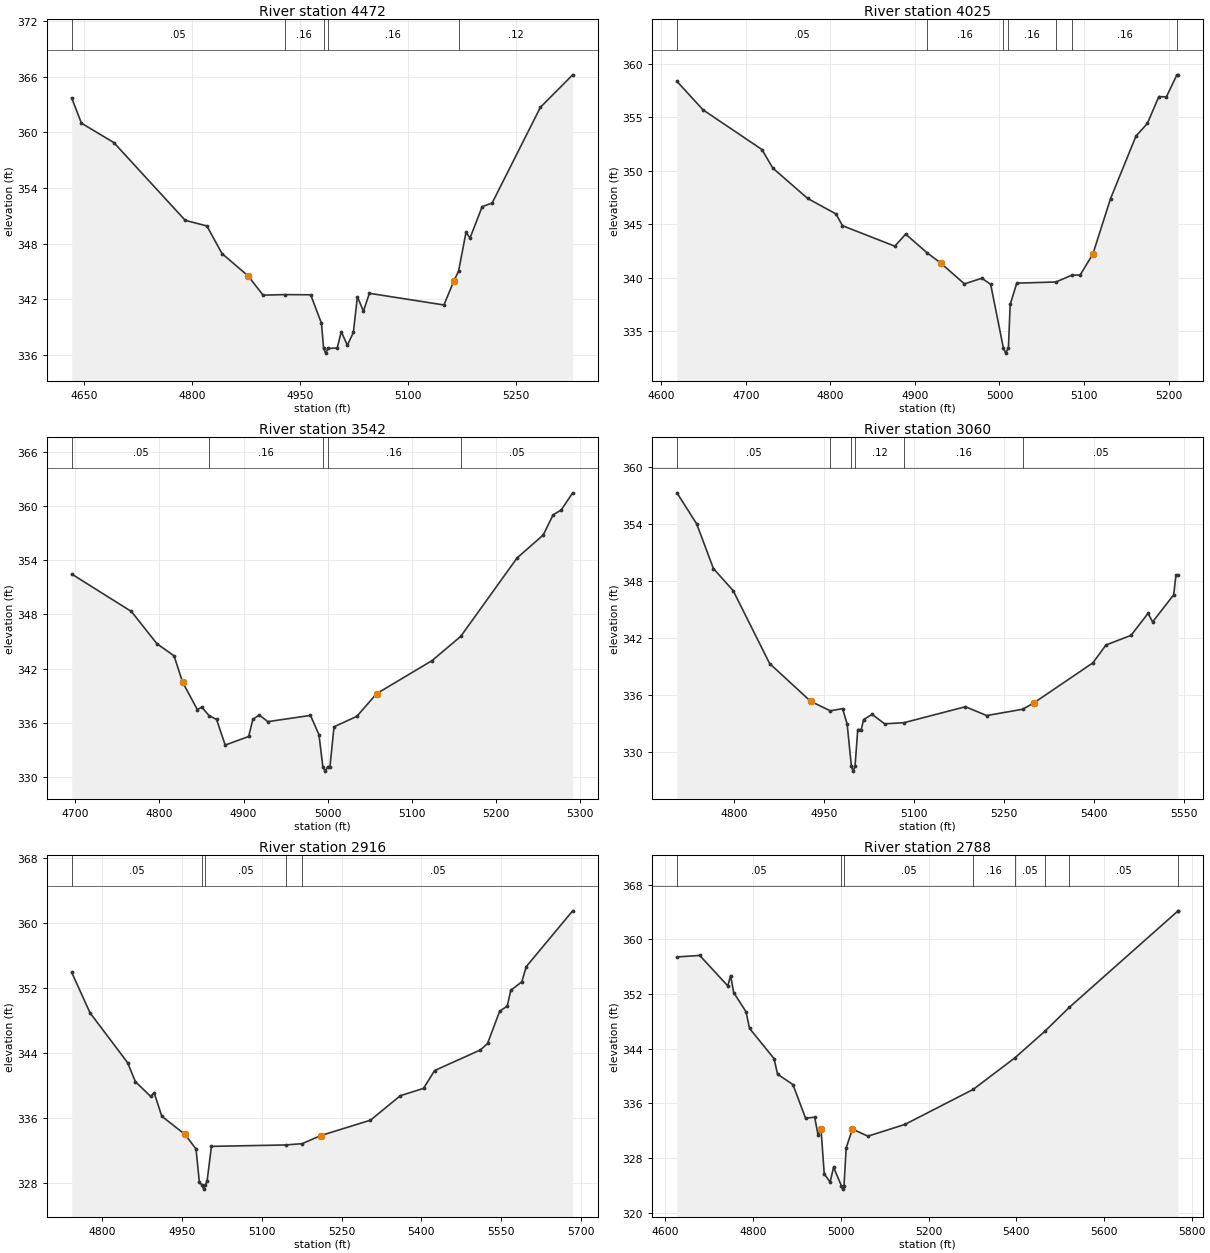
Type RM Length L Ch R = 1 ,4472    ,447,447,447
BEGIN DESCRIPTION:
PICKLE BRANCH 7.0
END DESCRIPTION:
XS GIS Cut Line= 3
       3698899.6     10740510.18      3698599.61     10740310.19
      3698299.57     10740160.17
#Sta/Elev= 30
  4632.7  363.72  4646.2     361  4691.3   358.9  4790.4  350.51  4820.5   349.9
  4841.5  346.92  4877.6  344.52  4898.6  342.43  4928.7  342.49  4964.7  342.47
  4979.7  339.39  4982.7  336.67  4985.5  336.17  4988.7  336.67  5001.6  336.73
  5007.2  338.49  5015.6  337.02    5024   338.4  5029.6  342.26    5038  340.71
  5046.3  342.63  5149.8  341.37  5163.7  343.97  5170.2  345.04  5180.5  349.21
  5186.1   348.6  5202.9  351.98  5216.8  352.38  5283.9  362.72  5328.7  366.22
#Mann= 5 ,-1 , 0
  4632.7     .05       0  4928.7     .16       0  4982.7     .07       0
  4988.7     .16       0  5170.2     .12       0
Bank Sta=4877.6,5163.7
XS Rating Curve= 0 ,0
Exp/Cntr=0.3,0.1

Type RM Length L Ch R = 1 ,4025    ,483,483,483
BEGIN DESCRIPTION:
PICKLE BRANCH 6.0
END DESCRIPTION:
XS GIS Cut Line= 3
       3698999.6     10740410.17      3698899.61     10740010.19
      3698749.58     10739910.17
#Sta/Elev= 30
  4618.5  358.37  4649.4   355.7    4719  351.99  4731.9  350.25  4773.1  347.41
  4806.6  345.96  4814.3  344.86  4876.2  342.94  4889.1  344.07  4914.1  342.34
  4930.3  341.38  4958.6  339.41  4979.2  339.94  4989.6  339.37  5004.6  333.43
  5007.3  332.93  5010.6  333.43  5012.7  337.49  5020.5  339.48  5066.8  339.59
  5085.7  340.23  5095.4  340.24  5110.4  342.18  5131.4  347.39  5161.5  353.25
    5175  354.43  5188.5  356.94  5197.5  356.92  5209.9  358.98  5211.1  358.98
#Mann= 7 ,-1 , 0
  4618.5     .05       0  4914.1     .16       0  5004.6     .07       0
  5010.6     .16       0  5066.8     .12       0  5085.7     .16       0
  5209.9     .12       0
Bank Sta=4930.3,5110.4
XS Rating Curve= 0 ,0
Exp/Cntr=0.3,0.1

Type RM Length L Ch R = 1 ,3542    ,482,482,482
BEGIN DESCRIPTION:
PICKLE BRANCH 5.0
END DESCRIPTION:
XS GIS Cut Line= 3
      3699249.61     10740160.19      3699299.61     10739860.19
       3699149.6     10739610.18
#Sta/Elev= 30
  4695.7  352.46  4766.7  348.32  4797.1  344.75  4817.4  343.42  4827.5  340.51
  4845.2  337.46  4850.3  337.76    4859  336.81    4868  336.38  4878.2  333.55
  4906.1   334.5  4911.1  336.39  4918.7  336.88  4928.9  336.14  4979.6  336.83
  4989.7  334.71  4994.3  331.17  4997.1  330.67  5000.3  331.17  5002.8  331.17
  5007.6  335.57  5034.8  336.73  5058.2  339.23  5124.2  342.89  5158.3  345.57
  5225.3  354.24  5256.4  356.78  5268.1     359  5277.8  359.55  5291.4  361.44
#Mann= 5 ,-1 , 0
  4695.7     .05       0    4859     .16       0  4994.3     .07       0
  5000.3     .16       0  5158.3     .05       0
Bank Sta=4827.5,5058.2
XS Rating Curve= 0 ,0
Exp/Cntr=0.3,0.1

Type RM Length L Ch R = 1 ,3060    ,144,144,144
BEGIN DESCRIPTION:
PICKLE BRANCH 4.0
END DESCRIPTION:
XS GIS Cut Line= 3
      3699999.61     10739960.19      3699699.61     10739910.19
      3699299.65     10739560.22
#Sta/Elev= 30
  4704.5  357.32  4737.5  354.04  4765.3  349.35  4798.3  347.02  4859.1  339.35
  4927.5  335.37  4960.3  334.37  4980.8   334.6  4988.4  332.97  4995.5  328.52
  4998.3  328.02  5001.5  328.52  5006.1   332.4    5012   332.4  5015.8  333.45
    5030     334  5050.9     333  5083.3  333.12  5185.7   334.8  5221.2  333.87
  5281.4  334.54  5299.5  335.19  5398.3  339.42  5420.1   341.3  5461.8  342.31
  5490.3  344.63  5497.9  343.73    5533  346.58  5536.8  348.62  5540.1  348.62
#Mann= 6 ,-1 , 0
  4704.5     .05       0  4960.3     .12       0  4995.5     .07       0
  5001.5     .12       0  5083.3     .16       0  5281.4     .05       0
Bank Sta=4927.5,5299.5
XS Rating Curve= 0 ,0
Exp/Cntr=0.3,0.1

Type RM Length L Ch R = 1 ,2916    ,128,128,128
BEGIN DESCRIPTION:
Mapping XS 03800a1a
END DESCRIPTION:
XS GIS Cut Line= 2
      3699968.38     10739938.87      3699222.17     10739364.27
#Sta/Elev= 30
  4742.8  353.91  4777.2  348.94  4847.9  342.81  4862.4  340.48  4891.4  338.65
  4897.7  339.13  4912.2  336.22  4955.7  333.99  4976.5   332.2  4982.8   328.1
    4988  327.76  4990.8  327.26    4994  327.76  4997.3  328.25  5005.5  332.52
  5144.8  332.69  5176.1  332.85  5211.2  333.85  5304.5  335.74  5360.6  338.75
  5404.2  339.65    5425  341.84  5511.1  344.37  5524.6  345.17  5547.3  349.13
  5561.6  349.77  5568.2   351.7    5589  352.75  5597.2  354.61  5684.6  361.48
#Mann= 5 ,-1 , 0
  4742.8     .05       0    4988     .04       0    4994     .05       0
  5144.8     .16       0  5176.1     .05       0
Bank Sta=4955.7,5211.2
XS Rating Curve= 0 ,0
Exp/Cntr=0.3,0.1

Type RM Length L Ch R = 1 ,2788    ,1012,1012,1012
BEGIN DESCRIPTION:
Mapping XS a3c502bd
END DESCRIPTION:
XS GIS Cut Line= 2
      3700059.86     10739902.24      3699174.54     10739180.09
#Sta/Elev= 30
  4626.2  357.43  4678.1  357.65  4742.2  353.19  4748.6  354.71  4755.6  352.21
  4783.8   349.4  4791.7  346.98  4847.7  342.54  4855.6  340.27  4890.8  338.74
  4919.5  333.83  4940.3  333.97  4948.2   331.3  4954.7  332.29  4962.1  325.67
  4975.5  324.47  4983.4  326.64  5001.2  323.94    5004  323.44  5007.2  323.94
  5012.1  329.48  5026.5  332.23  5061.7  331.19  5146.4  332.92  5302.1  338.05
  5396.9  342.66  5464.9  346.53  5520.7  350.03  5768.4  364.14  5768.7  364.18
#Mann= 8 ,-1 , 0
  4626.2     .05       0  5001.2     .04       0  5007.2     .05       0
  5302.1     .16       0  5396.9     .05       0  5464.9     .12       0
  5520.7     .05       0  5768.4     .08       0
Bank Sta=4954.7,5026.5
XS Rating Curve= 0 ,0
Exp/Cntr=0.3,0.1

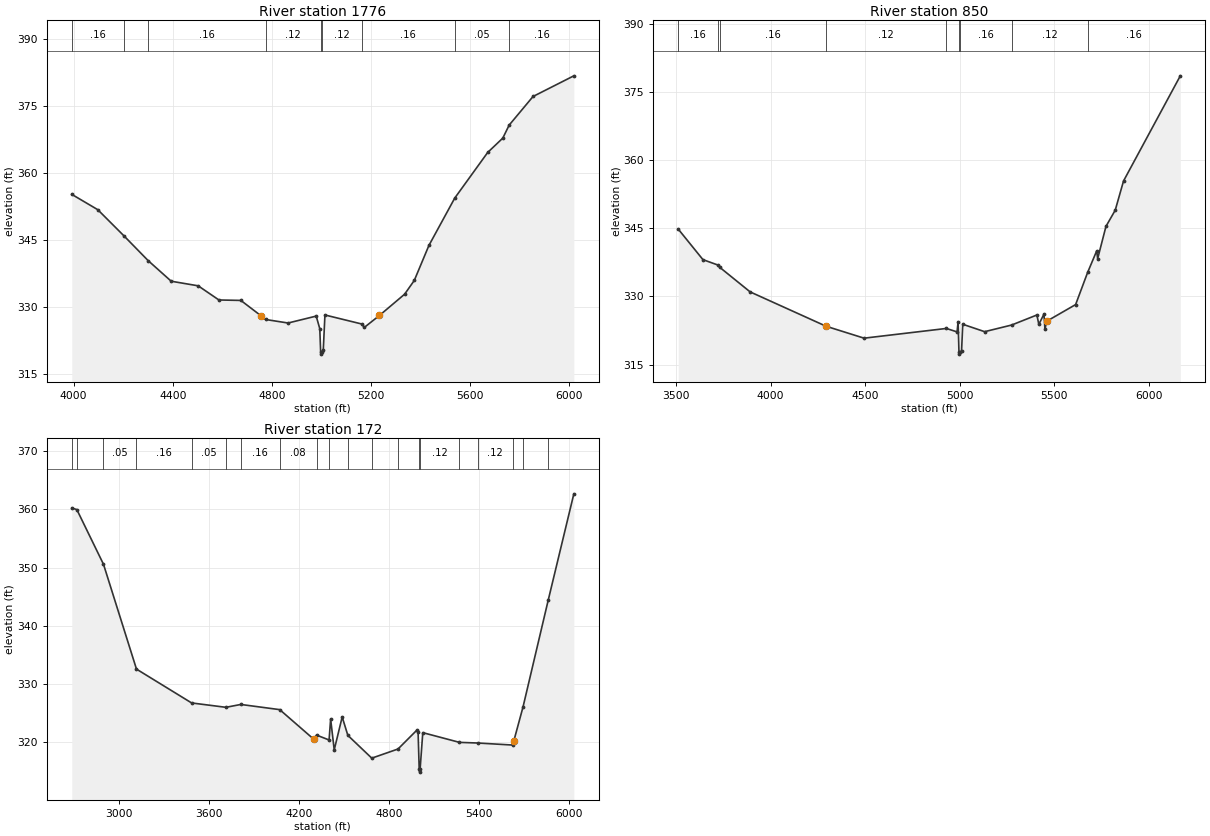
Type RM Length L Ch R = 1 ,1776    ,926,926,926
BEGIN DESCRIPTION:
PICKLE BRANCH 3.0
END DESCRIPTION:
XS GIS Cut Line= 4
      3700062.44     10739803.86      3700192.65     10738979.19
       3700036.4     10738788.21      3699107.57     10738623.28
#Sta/Elev= 30
  3992.7  355.27  4097.7  351.83  4203.4  345.96  4300.9  340.42  4393.8  335.81
  4502.6  334.78  4586.2  331.61  4674.7  331.51  4755.7  328.08  4774.3  327.24
  4865.1  326.45  4978.6     328    4993  325.17  4996.5  319.98  4999.2  319.48
  5002.5  319.98  5007.2  320.51  5013.8  328.25  5162.2  326.23  5172.6  325.46
  5233.6  328.14  5335.1   332.9  5374.2  335.99  5433.2  343.83  5537.3  354.43
  5670.3  364.66  5731.2  367.87  5756.8  370.78  5853.1  377.19  6017.7  381.82
#Mann= 9 ,-1 , 0
  3992.7     .16       0  4203.4     .12       0  4300.9     .16       0
  4774.3     .12       0  4996.5     .07       0  5002.5     .12       0
  5162.2     .16       0  5537.3     .05       0  5756.8     .16       0
Bank Sta=4755.7,5233.6
XS Rating Curve= 0 ,0
Exp/Cntr=0.3,0.1

Type RM Length L Ch R = 1 ,850     ,678,678,678
BEGIN DESCRIPTION:
PICKLE BRANCH 2.0
END DESCRIPTION:
XS GIS Cut Line= 4
      3700183.96     10739751.77        3700618.     10738675.37
      3700461.75     10738267.38      3699428.72     10738041.68
#Sta/Elev= 30
  3511.7   344.8  3642.3  338.08  3722.3  336.88  3730.6  336.41    3892  330.98
  4293.8  323.42  4494.6   320.8  4929.6  322.94  4986.2  322.18  4991.6  324.44
  4996.1  317.79  4998.9  317.29  5002.1  317.79  5009.8  317.89  5016.2  323.86
  5131.9  322.23  5274.5  323.69  5408.2   325.9  5418.5  323.83  5445.7  326.11
  5450.9  322.74  5459.4  324.51    5613  328.19  5676.4  335.25  5724.5  340.01
  5729.6   338.3  5773.5   345.4  5822.5  348.96  5866.4  355.39  6166.6  378.52
#Mann= 9 ,-1 , 0
  3511.7     .16       0  3722.3     .12       0  3730.6     .16       0
  4293.8     .12       0  4929.6     .16       0  4996.1     .07       0
  5002.1     .16       0  5274.5     .12       0  5676.4     .16       0
Bank Sta=4293.8,5459.4
XS Rating Curve= 0 ,0
Exp/Cntr=0.3,0.1

Type RM Length L Ch R = 1 ,172     ,0,0,0
BEGIN DESCRIPTION:
PICKLE BRANCH 1.0
END DESCRIPTION:
XS GIS Cut Line= 5
      3700484.32     10740231.35      3700788.14     10738790.38
      3701022.51     10738226.15      3700935.71     10737931.01
       3700163.9     10737367.33
#Sta/Elev= 30
  2685.8  360.23  2719.7  359.95  2897.3  350.56  3117.2  332.56  3484.8  326.75
  3713.4     326  3812.8  326.49  4072.2   325.6  4299.4  320.51  4317.4  321.23
  4401.2  320.39  4411.5  323.99  4435.4  318.69  4488.5  324.34  4526.3  321.18
  4685.7  317.27  4860.7  318.84  4984.1  322.02  4994.5  321.73  5001.9  315.37
  5004.7  314.87  5007.9  315.37  5025.8  321.65  5270.5  319.98  5391.6  319.87
  5624.7  319.52  5632.6  320.22    5694  326.06  5861.7  344.37  6032.8  362.66
#Mann= 20 ,-1 , 0
  2685.8     .08       0  2719.7     .16       0  2897.3     .05       0
  3117.2     .16       0  3484.8     .05       0  3713.4     .08       0
  3812.8     .16       0  4072.2     .08       0  4317.4     .12       0
  4401.2     .08       0  4526.3     .16       0  4685.7     .08       0
  4860.7     .12       0  5001.9     .07       0  5007.9     .12       0
  5270.5     .16       0  5391.6     .12       0  5624.7     .16       0
    5694     .12       0  5861.7     .16       0
Bank Sta=4299.4,5632.6
XS Rating Curve= 0 ,0
Exp/Cntr=0.3,0.1

Chan Stop Cuts=-1
Use User Specified Reach Order=0
Composite Channel Slope=5