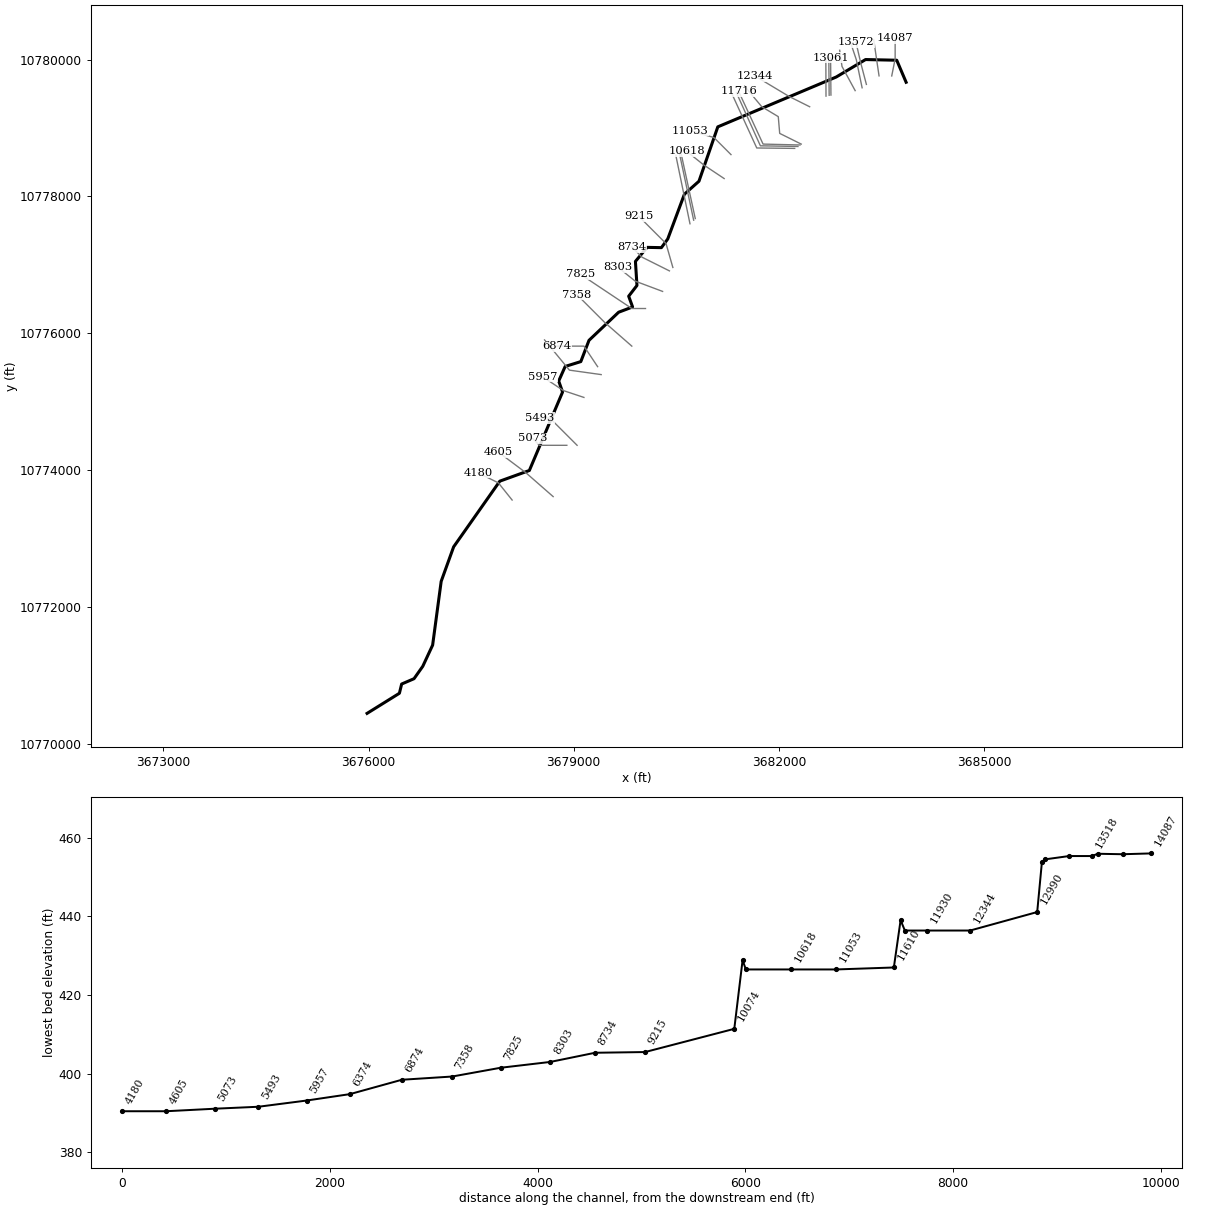
--- SHELTON MILL BRANCH.prj (project) ---

Proj Title=SHELTON MILL BRANCH Base Level Engineering
Current Plan=p01
Default Exp/Contr=0.3,0.1
English Units
Geom File=g01
Flow File=f01
Plan File=p01
Y Axis Title=Elevation
X Axis Title(PF)=Main Channel Distance
X Axis Title(XS)=Station
BEGIN DESCRIPTION:
SHELTON MILL BRANCH
END DESCRIPTION:
DSS Export Rating Curves= 0
DSS Export Rating Curve Sorted= 0
DSS Export Volume Flow Curves= 0
DXF OffsetX= 0
DXF OffsetY= 0
DXF ScaleX= 1
DXF ScaleY= 10

--- SHELTON MILL BRANCH.p01 (plan) ---

Plan Title=Multiple Run
Short Identifier=Multiple
Geom File=g01
Flow File=f01
Subcritical Flow
K Sum by GR= 0
Std Step Tol= 0.01
Critical Tol= 0.01
Num of Std Step Trials= 20
Max Error Tol= 0.3
Flow Tol Ratio= 0.001
Split Flow NTrial= 30
Split Flow Tol= 0.02
Split Flow Ratio= 0.02
Log Output Level= 0
Friction Slope Method= 1
Unsteady Friction Slope Method= 2
Unsteady Bridges Friction Slope Method= 1
Parabolic Critical Depth
Global Vel Dist=  1 , 1 , 1
Global Log Level= 0
CheckData=True
Encroach Param= -1, 0, 0, 0
BEGIN DESCRIPTION:
Multiple Run
END DESCRIPTION:

--- SHELTON MILL BRANCH.f01 (steady flow) ---

Flow Title=Multiple
Number of Profiles=7
Profile Names=10-year,25-year,50-year,1pct_min,100-year,1pct_plu,500-year
River Rch & RM= SHELTON MILL BRA,Reach-1,14087
     196     248     288     247     334     452     449
River Rch & RM= SHELTON MILL BRA,Reach-1,13297
     836    1166    1446    1316    1780    2408    2703
River Rch & RM= SHELTON MILL BRA,Reach-1,11053
    1041    1457    1808    1645    2225    3008    3375
River Rch & RM= SHELTON MILL BRA,Reach-1,3265
    1197    1686    2102    1918    2594    3509    3965
River Rch & RM= SHELTON MILL BRA,Reach-1,41
    2268    3275    4153    3846    5202    7035    8189
Boundary for River Rch & Prof#=SHELTON MILL BRA,Reach-1,1
Up Type=0
Dn Type=3
Dn Slope=0.005
Boundary for River Rch & Prof#=SHELTON MILL BRA,Reach-1,2
Up Type=0
Dn Type=3
Dn Slope=0.005
Boundary for River Rch & Prof#=SHELTON MILL BRA,Reach-1,3
Up Type=0
Dn Type=3
Dn Slope=0.005
Boundary for River Rch & Prof#=SHELTON MILL BRA,Reach-1,4
Up Type=0
Dn Type=3
Dn Slope=0.005
Boundary for River Rch & Prof#=SHELTON MILL BRA,Reach-1,5
Up Type=0
Dn Type=3
Dn Slope=0.005
Boundary for River Rch & Prof#=SHELTON MILL BRA,Reach-1,6
Up Type=0
Dn Type=3
Dn Slope=0.005
Boundary for River Rch & Prof#=SHELTON MILL BRA,Reach-1,7
Up Type=0
Dn Type=3
Dn Slope=0.005

--- SHELTON MILL BRANCH.g01 (geometry) ---

Geom Title=Existing Conditions
Program Version=4.10

River Reach=SHELTON MILL BRA,Reach-1
Reach XY= 30
        3683860.       10779668.      3683722.75       10779990.
        3683267.       10780000.       3682838.5       10779745.
      3681106.75       10779016.      3680831.25       10778221.
      3680618.75       10778032.        3680375.       10777377.
        3680282.       10777250.      3680072.75       10777254.
       3679902.5       10777049.      3679924.75       10776697.
      3679803.75       10776540.        3679861.       10776383.
        3679657.       10776306.      3679223.75       10775895.
        3679104.       10775584.       3678875.5       10775513.
      3678780.75       10775300.      3678837.25       10775139.
       3678351.5       10773992.      3677919.75       10773836.
      3677244.75       10772876.       3677062.5       10772371.
       3676937.5       10771439.      3676793.25       10771129.
       3676665.5       10770948.       3676484.5       10770870.
      3676451.75       10770735.        3675979.       10770441.

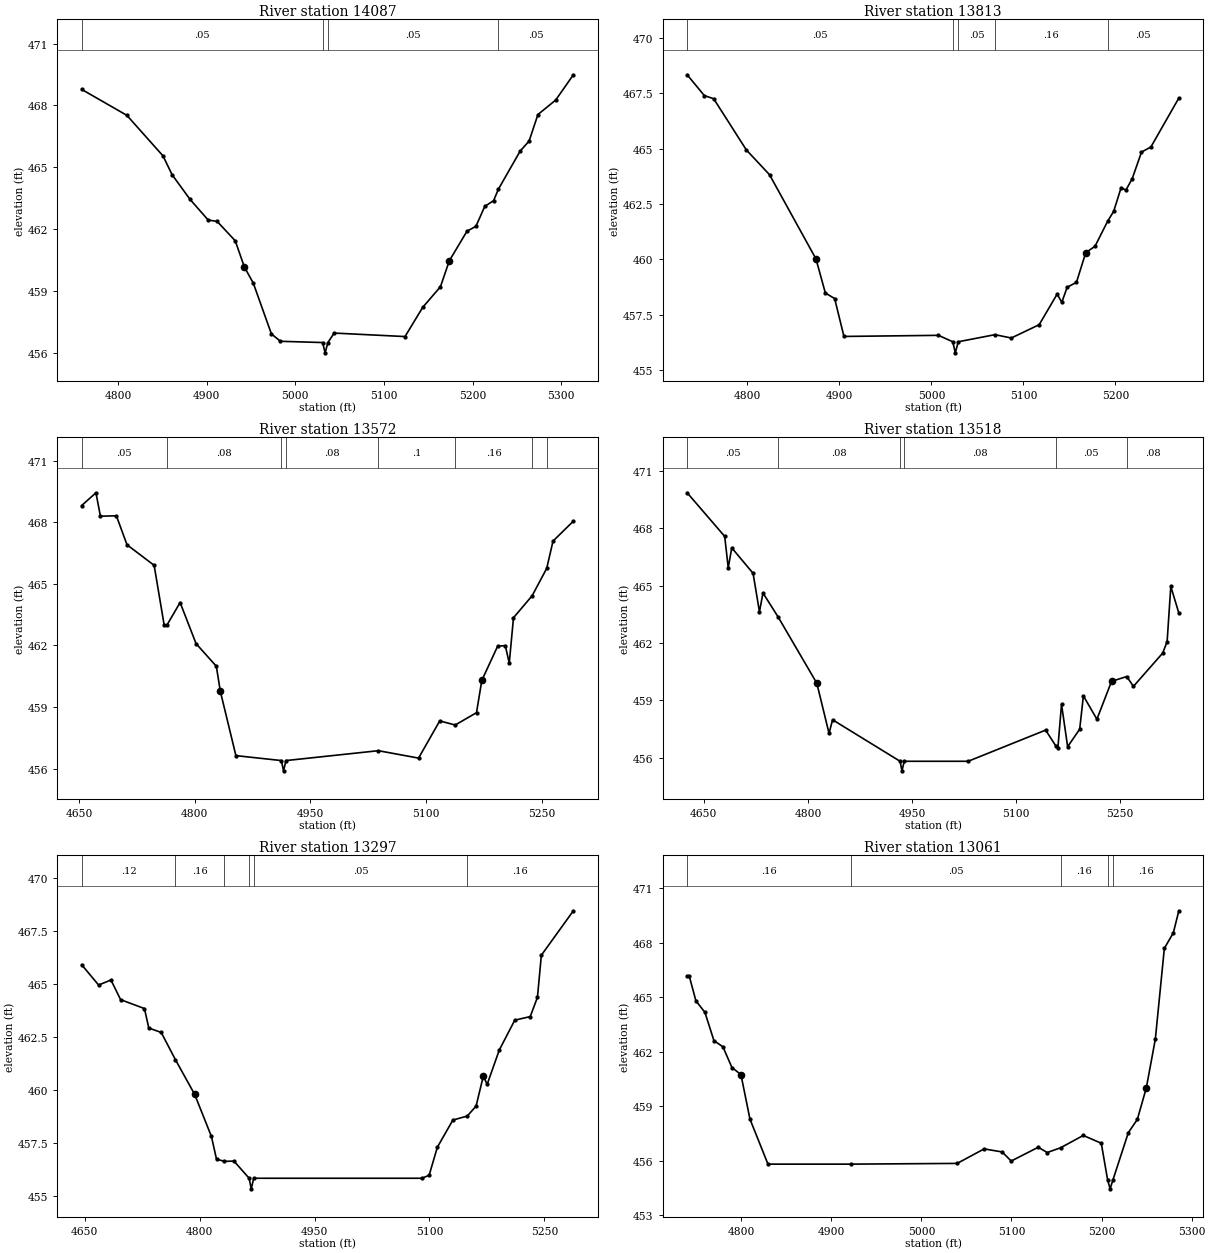
Type RM Length L Ch R = 1 ,14087   ,274,274,274
BEGIN DESCRIPTION:
SHELTON MILL BRANCH 31.0
END DESCRIPTION:
XS GIS Cut Line= 3
      3683649.61     10779760.22      3683699.61     10780010.19
      3683699.61     10780310.17
#Sta/Elev= 30
  4758.9  468.78  4809.9  467.52  4850.7  465.55  4860.9  464.64  4881.2  463.44
  4901.6  462.44  4911.8  462.37  4932.2  461.43  4942.4  460.17  4952.6  459.37
    4973  456.91  4983.2  456.55  5030.8  456.49  5033.6  455.99  5036.8  456.49
  5043.8  456.95  5123.8  456.78  5143.8   458.2  5163.8   459.2  5173.8  460.46
  5193.8   461.9  5203.8  462.13  5213.8   463.1  5223.8  463.38  5229.1  463.93
  5253.8  465.79  5263.8  466.27  5273.8  467.56  5293.8  468.26  5313.8  469.49
#Mann= 4 ,-1 , 0
  4758.9     .05       0  5030.8     .03       0  5036.8     .05       0
  5229.1     .05       0
Bank Sta=4942.4,5173.8
XS Rating Curve= 0 ,0
Exp/Cntr=0.3,0.1

Type RM Length L Ch R = 1 ,13813   ,241,241,241
BEGIN DESCRIPTION:
Mapping XS 42ce0f7e
END DESCRIPTION:
XS GIS Cut Line= 2
      3683464.03     10779761.65       3683385.9     10780290.31
#Sta/Elev= 30
  4734.5  468.33  4753.2  467.39  4763.3  467.25  4798.8  464.94    4824  463.82
  4874.5  460.02  4884.7  458.48  4894.8  458.23  4904.9  456.52  5007.6  456.57
  5023.2  456.28  5025.9  455.78  5029.2  456.28    5069   456.6  5086.8  456.45
  5117.1  457.05  5136.6  458.43  5141.7  458.06  5147.5  458.74  5157.6  458.96
  5167.7   460.3  5177.8  460.59  5191.5  461.72    5198  462.16  5206.2  463.24
  5211.3  463.12  5218.2  463.64  5228.3  464.84  5238.5  465.07  5268.9  467.28
#Mann= 5 ,-1 , 0
  4734.5     .05       0  5023.2    .035       0  5029.2     .05       0
    5069     .16       0  5191.5     .05       0
Bank Sta=4874.5,5167.7
XS Rating Curve= 0 ,0
Exp/Cntr=0.3,0.1

Type RM Length L Ch R = 1 ,13572   ,54,54,54
BEGIN DESCRIPTION:
SHELTON MILL BRANCH 30.0
END DESCRIPTION:
XS GIS Cut Line= 3
      3683279.13     10779636.66      3683198.39     10779943.98
      3683125.62     10780255.86
#Sta/Elev= 30
  4653.2  468.81  4671.7  469.43  4677.5  468.29  4698.2  468.31    4712   466.9
  4747.2   465.9  4760.2     463  4763.8  462.99  4780.9  464.09  4801.6  462.09
  4827.9  460.99  4833.1  459.77  4853.3  456.64  4912.3   456.4  4915.1   455.9
  4918.3   456.4  5038.2  456.88  5090.3  456.52  5117.8  458.33  5137.9  458.13
  5165.5  458.73  5172.4   460.3    5193  461.97  5202.9  461.99    5208  461.14
  5213.5  463.35  5237.7  464.42  5256.6  465.75  5264.8  467.08  5291.2  468.05
#Mann= 8 ,-1 , 0
  4653.2     .05       0  4763.8     .08       0  4912.3     .07       0
  4918.3     .08       0  5038.2      .1       0  5137.9     .16       0
  5237.7     .05       0  5256.6     .08       0
Bank Sta=4833.1,5172.4
XS Rating Curve= 0 ,0
Exp/Cntr=0.3,0.1

Type RM Length L Ch R = 1 ,13518   ,221,221,221
BEGIN DESCRIPTION:
Mapping XS d05c040d
END DESCRIPTION:
XS GIS Cut Line= 3
      3683216.63      10779587.2      3683130.69     10780001.27
      3683039.53     10780272.15
#Sta/Elev= 30
    4626  469.86  4680.1  467.58  4685.2  465.94  4690.3  466.98    4721  465.65
  4730.2  463.64  4735.3  464.62  4757.2  463.36  4812.9   459.9  4830.5  457.28
  4835.6  457.99  4932.9  455.82  4935.6  455.32  4938.9  455.82    5031  455.82
  5142.7  457.45  5157.4  456.62  5160.3   456.5  5165.6   458.8  5174.4  456.58
  5191.8   457.5  5197.1  459.24  5216.6  458.02  5237.7     460  5259.5  460.25
  5269.3  459.74  5311.5  461.48  5317.8  462.08  5323.1  464.96  5334.7  463.57
#Mann= 6 ,-1 , 0
    4626     .05       0  4757.2     .08       0  4932.9     .07       0
  4938.9     .08       0  5157.4     .05       0  5259.5     .08       0
Bank Sta=4812.9,5237.7
XS Rating Curve= 0 ,0
Exp/Cntr=0.3,0.1

Type RM Length L Ch R = 1 ,13297   ,236,236,236
BEGIN DESCRIPTION:
Mapping XS 0b91d642
END DESCRIPTION:
XS GIS Cut Line= 3
      3683115.05     10779545.57      3682922.35     10779899.71
      3682888.61     10780135.94
#Sta/Elev= 30
    4646  465.91  4668.1  464.95  4684.2  465.19  4696.8  464.26  4727.9  463.84
  4733.6  462.92  4749.8  462.71  4768.4  461.42  4793.5  459.78  4815.3   457.8
    4822  456.72  4832.4  456.62  4844.8  456.63  4864.6  455.82  4867.3  455.32
  4870.6  455.82  5090.1  455.82  5099.5  455.96  5110.3  457.29  5130.5  458.57
  5149.3  458.76  5160.8  459.23  5170.2  460.64  5175.3  460.26  5191.1  461.88
  5211.3  463.29  5231.5  463.46  5240.9  464.37    5246  466.36  5287.8  468.46
#Mann= 6 ,-1 , 0
    4646     .12       0  4768.4     .16       0  4832.4     .05       0
  4864.6    .033       0  4870.6     .05       0  5149.3     .16       0
Bank Sta=4793.5,5170.2
XS Rating Curve= 0 ,0
Exp/Cntr=0.3,0.1

Type RM Length L Ch R = 1 ,13061   ,26,26,26
BEGIN DESCRIPTION:
Mapping XS 602e0f5e
END DESCRIPTION:
XS GIS Cut Line= 2
      3682760.89     10779480.49       3682755.7     10780026.26
#Sta/Elev= 30
    4740  466.18  4742.3  466.18  4749.7  464.81  4759.7  464.18  4769.7  462.62
  4779.7  462.28  4789.7  461.14  4799.7  460.75  4809.7   458.3  4829.7  455.82
  4921.4  455.82  5039.7  455.86  5069.7  456.66  5089.7  456.49  5099.7  455.99
  5129.7  456.75  5139.7  456.46  5154.5  456.72  5179.7   457.4  5199.7  456.97
  5206.7  454.96  5209.5  454.46  5212.7  454.96  5229.7  457.55  5239.7  458.28
  5249.7  460.02  5259.7   462.7  5269.7   467.7  5279.7  468.56  5285.8  469.77
#Mann= 5 ,-1 , 0
    4740     .16       0  4921.4     .05       0  5154.5     .16       0
  5206.7    .033       0  5212.7     .16       0
Bank Sta=4799.7,5249.7
XS Rating Curve= 0 ,0
Exp/Cntr=0.3,0.1

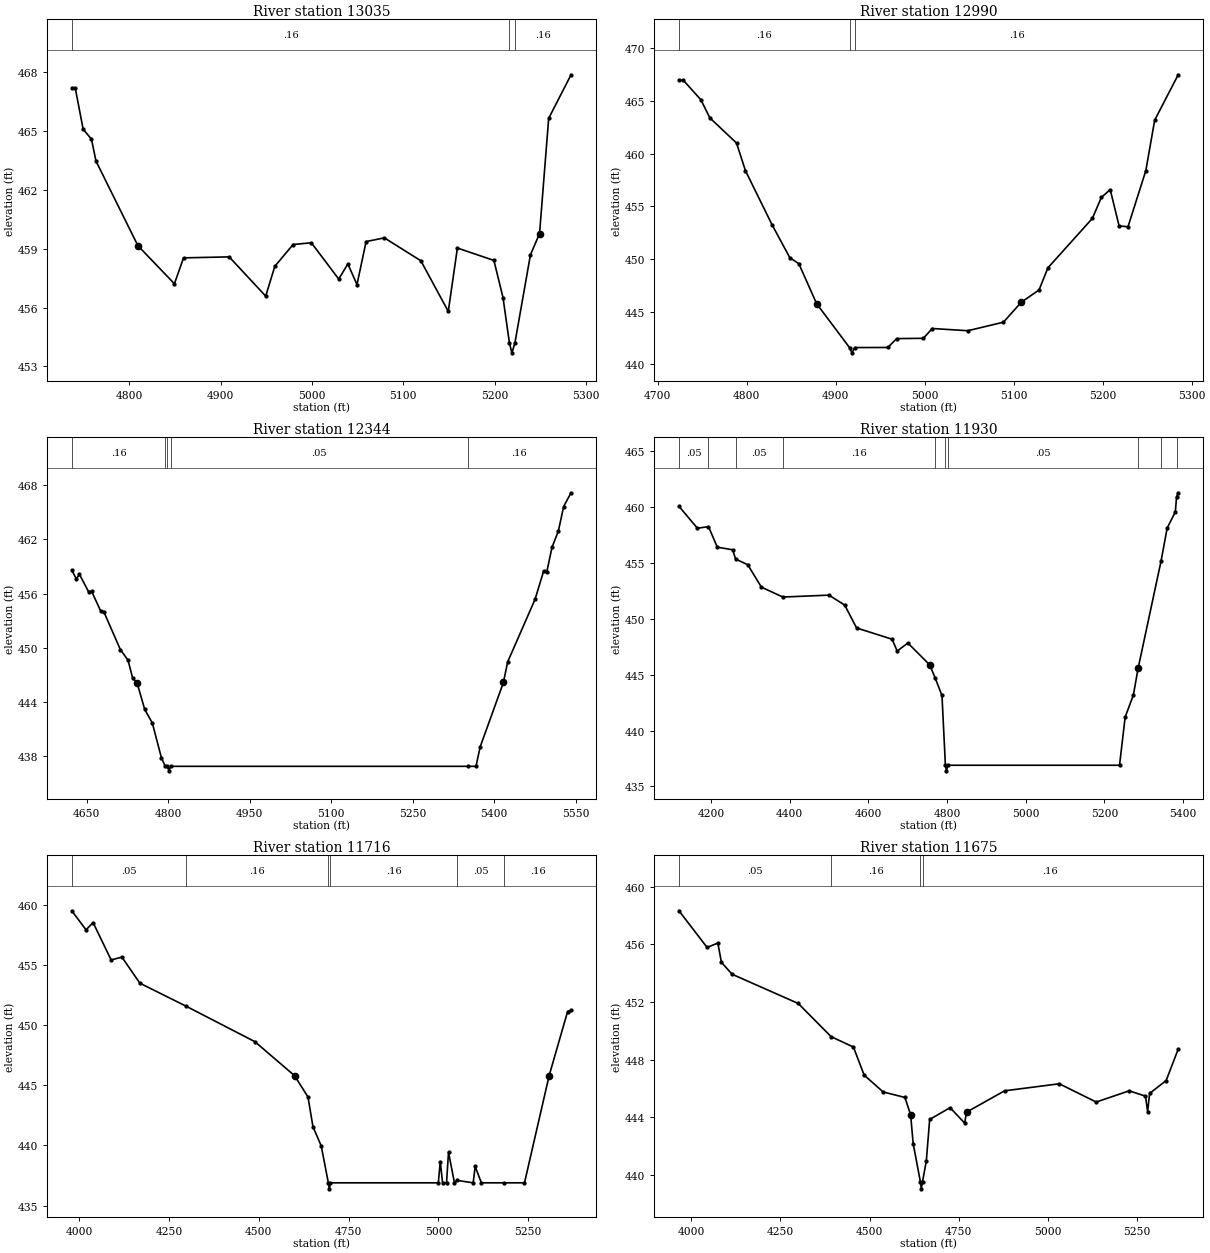
Type RM Length L Ch R = 1 ,13035   ,45,45,45
BEGIN DESCRIPTION:
SHELTON MILL BRANCH 29.0
END DESCRIPTION:
XS GIS Cut Line= 2
      3682734.85     10779477.83      3682729.64     10780024.71
#Sta/Elev= 30
  4736.9   467.2  4740.6   467.2  4749.3  465.09  4758.4  464.58  4763.4  463.46
  4809.3  459.15  4849.3  457.21  4859.3  458.53  4909.3  458.58  4949.3  456.58
  4959.3   458.1  4979.3  459.21  4999.3   459.3  5029.3  457.45  5039.3  458.22
  5049.3  457.17  5059.3  459.36  5079.3  459.55  5119.3  458.38  5149.3   455.8
  5159.3  459.03  5199.3   458.4  5209.3   456.5  5216.3  454.19    5219  453.69
  5222.3  454.19  5239.3  458.68  5249.3  459.77  5259.3  465.64  5283.8  467.86
#Mann= 3 ,-1 , 0
  4736.9     .16       0  5216.3     .07       0  5222.3     .16       0
Bank Sta=4809.3,5249.3
XS Rating Curve= 0 ,0
Exp/Cntr=0.3,0.1

Type RM Length L Ch R = 1 ,12990   ,646,646,646
BEGIN DESCRIPTION:
SHELTON MILL BRANCH 28.0
END DESCRIPTION:
XS GIS Cut Line= 2
      3682688.67     10779465.49      3682686.07     10780026.59
#Sta/Elev= 30
  4723.8  466.97  4728.7  466.97  4748.5  465.11  4758.5   463.4  4788.5  461.01
  4798.5  458.39  4828.5  453.24  4848.5  450.11  4858.5  449.56  4878.5  445.76
  4915.5  441.59  4918.2  441.09  4921.5  441.59  4958.5   441.6  4968.5  442.44
  4998.5  442.47  5008.5   443.4  5048.5  443.19  5088.5     444  5108.5  445.89
  5128.5  447.06  5138.5  449.16  5188.5  453.86  5198.5  455.84  5208.5  456.59
  5218.5  453.14  5228.5  453.06  5248.5  458.38  5258.5  463.18  5284.9  467.49
#Mann= 3 ,-1 , 0
  4723.8     .16       0  4915.5     .07       0  4921.5     .16       0
Bank Sta=4878.5,5108.5
XS Rating Curve= 0 ,0
Exp/Cntr=0.3,0.1

Type RM Length L Ch R = 1 ,12344   ,414,414,414
BEGIN DESCRIPTION:
SHELTON MILL BRANCH 27.0
END DESCRIPTION:
XS GIS Cut Line= 3
      3682449.59      10779310.2      3682149.61     10779460.19
       3681649.6      10779760.2
#Sta/Elev= 30
  4622.8  458.57  4631.2  457.62  4636.8  458.13  4653.5  456.22  4659.1  456.27
  4675.9  454.07  4681.5  454.01  4712.2  449.79  4726.2  448.64  4734.6  446.68
    4743   446.1  4756.9  443.18  4770.9  441.69  4787.7  437.82  4794.5  436.92
  4798.7  436.89  4801.4  436.39  4804.7  436.89    5351  436.89  5366.4  436.89
  5374.1  439.04  5416.9  446.17  5424.7  448.44  5475.2  455.38  5490.7  458.45
  5496.6  458.38  5506.3  461.12    5518  462.92  5527.7  465.63  5541.3  467.15
#Mann= 5 ,-1 , 0
  4622.8     .16       0  4794.5     .05       0  4798.7    .033       0
  4804.7     .05       0    5351     .16       0
Bank Sta=4743,5416.9
XS Rating Curve= 0 ,0
Exp/Cntr=0.3,0.1

Type RM Length L Ch R = 1 ,11930   ,214,214,214
BEGIN DESCRIPTION:
SHELTON MILL BRANCH 26.0
END DESCRIPTION:
XS GIS Cut Line= 5
      3682326.36     10778764.07      3682011.69     10778920.32
      3681990.81     10779165.47      3681749.61     10779310.19
      3681499.58     10779610.22
#Sta/Elev= 30
  4118.4  460.09  4165.4  458.12  4193.5  458.27  4215.8  456.43  4255.1  456.19
  4262.3  455.37  4293.4  454.85  4327.9  452.85  4382.4  451.96  4499.7  452.13
  4539.8  451.24    4570  449.19  4660.3  448.18  4673.2  447.12  4700.4  447.84
    4756  445.88  4769.8   444.7  4787.1  443.14  4795.8  436.89  4798.5  436.39
  4801.8  436.89  5238.5  436.89  5252.8  441.21  5273.7  443.18  5285.8  445.59
    5344  455.17  5359.6  458.14  5380.4  459.59  5383.4  460.91  5387.6   461.3
#Mann= 10 ,-1 , 0
  4118.4     .05       0  4193.5     .12       0  4262.3     .05       0
  4382.4     .16       0  4769.8     .05       0  4795.8    .033       0
  4801.8     .05       0  5285.8     .16       0    5344     .05       0
  5383.4     .16       0
Bank Sta=4756,5285.8
XS Rating Curve= 0 ,0
Exp/Cntr=0.3,0.1

Type RM Length L Ch R = 1 ,11716   ,41,41,41
BEGIN DESCRIPTION:
Mapping XS 7d9667e6
END DESCRIPTION:
XS GIS Cut Line= 3
      3682309.04     10778751.05      3681768.63     10778764.07
      3681410.92     10779534.63
#Sta/Elev= 30
  3979.2  459.51  4018.6  457.93  4038.6  458.52  4088.7  455.42  4118.7  455.66
  4168.7  453.49  4297.2  451.58  4488.8  448.63  4599.4   445.8  4636.8  444.03
  4650.7  441.55  4673.6  439.97  4693.5  436.89  4696.2  436.39  4699.5  436.89
  4999.7  436.89  5005.2  438.65  5011.6  436.89  5022.6  436.89  5028.1  439.43
  5044.7  436.89  5052.7  437.09  5096.8  436.89  5102.3  438.25  5119.7  436.89
  5183.3  436.89  5239.7  436.89  5308.4  445.81  5359.7  451.13  5369.3  451.24
#Mann= 6 ,-1 , 0
  3979.2     .05       0  4297.2     .16       0  4693.5     .07       0
  4699.5     .16       0  5052.7     .05       0  5183.3     .16       0
Bank Sta=4599.4,5308.4
XS Rating Curve= 0 ,0
Exp/Cntr=0.3,0.1

Type RM Length L Ch R = 1 ,11675   ,65,65,65
BEGIN DESCRIPTION:
Mapping XS 00b85733
END DESCRIPTION:
XS GIS Cut Line= 3
      3682278.61     10778729.35       3681729.4     10778738.93
      3681379.68     10779513.77
#Sta/Elev= 30
  3965.6  458.34  4044.6  455.79  4074.6   456.1  4084.6  454.76  4114.6  453.93
    4300   451.9  4391.9   449.6  4454.7  448.87  4484.7  446.92  4538.2  445.75
    4599  445.37    4615  444.16  4622.1  442.17  4642.3  439.52    4645  439.02
  4648.3  439.52  4658.9  440.94  4668.4  443.84  4725.6  444.66  4766.4  443.59
  4771.9  444.35  4878.3  445.83  5031.7  446.32  5135.2  445.05  5227.7  445.83
  5273.3  445.46  5279.4  444.38  5284.9  445.65  5331.2  446.54    5365  448.72
#Mann= 4 ,-1 , 0
  3965.6     .05       0  4391.9     .16       0  4642.3     .07       0
  4648.3     .16       0
Bank Sta=4615,4771.9
XS Rating Curve= 0 ,0
Exp/Cntr=0.3,0.1

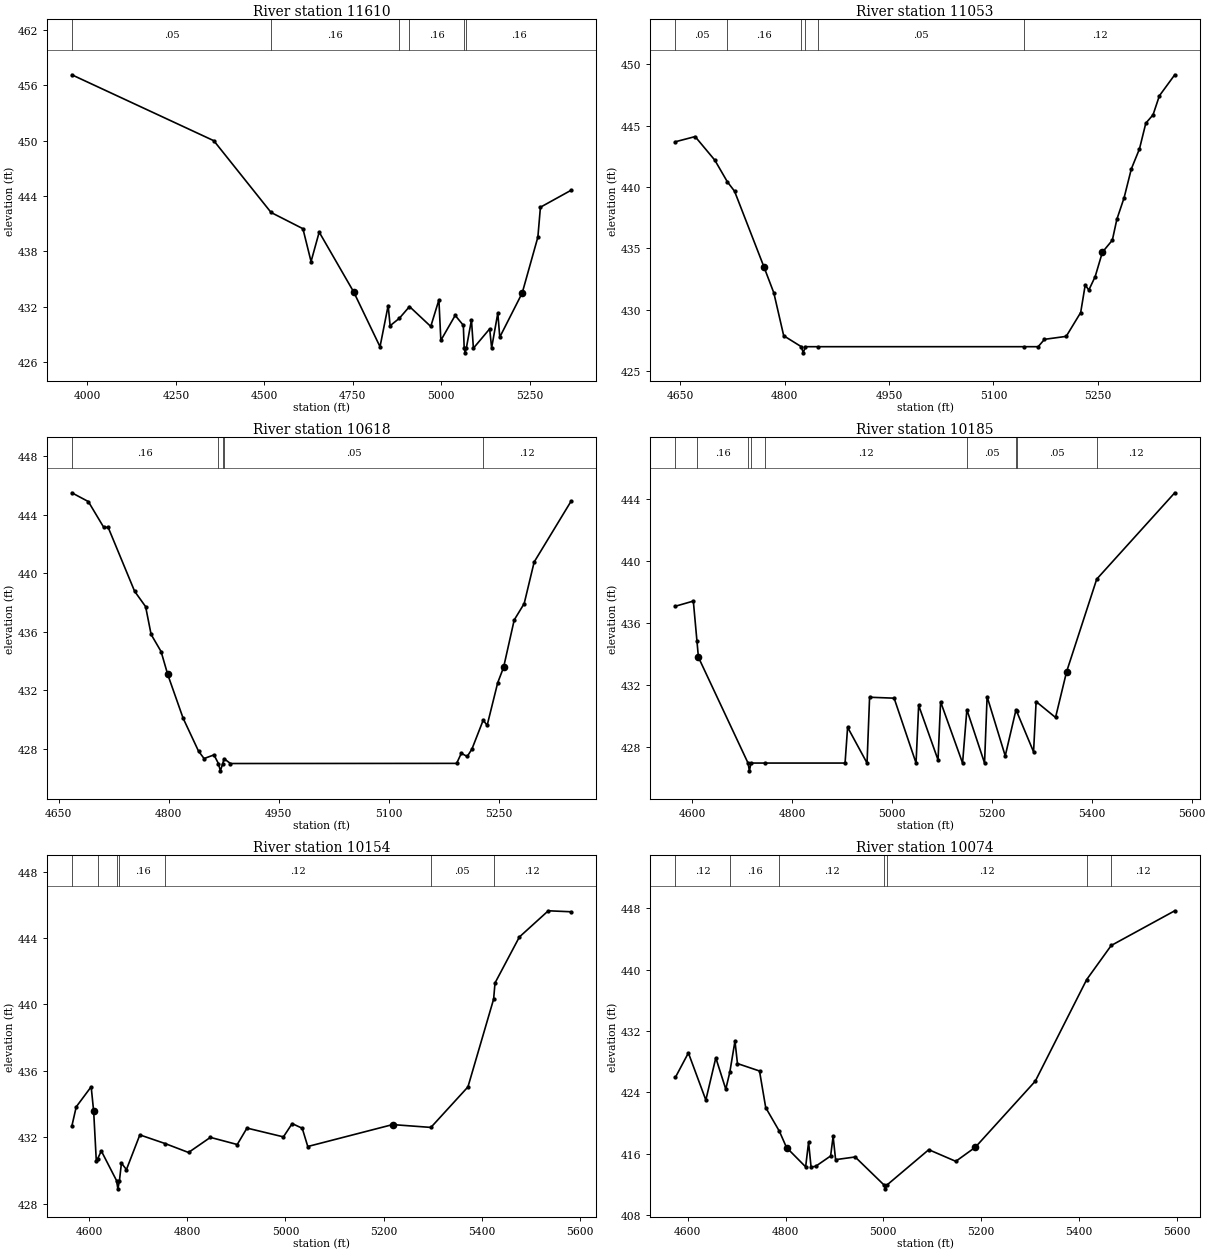
Type RM Length L Ch R = 1 ,11610   ,557,557,557
BEGIN DESCRIPTION:
SHELTON MILL BRANCH 25.0
END DESCRIPTION:
XS GIS Cut Line= 3
       3682230.9     10778701.14      3681676.35     10778707.12
      3681319.11     10779485.58
#Sta/Elev= 30
  3956.1  457.15  4357.4     450  4519.2  442.22  4609.2  440.46  4632.2   436.9
  4655.2  440.09  4752.6  433.61  4827.1  427.66  4850.1  432.13  4855.6  429.94
  4881.6  430.74  4910.4  432.02  4970.5  429.86  4993.5  432.74    4999  428.35
  5039.5  431.06  5062.5  429.99    5065   427.5  5067.7     427    5071   427.5
  5085.5  430.57    5091   427.5    5137   429.6  5142.5  427.53    5160  431.32
  5165.5   428.7  5228.9  433.49  5273.2  439.55  5280.4  442.79  5367.2  444.63
#Mann= 6 ,-1 , 0
  3956.1     .05       0  4519.2     .16       0  4881.6     .05       0
  4910.4     .16       0    5065     .07       0    5071     .16       0
Bank Sta=4752.6,5228.9
XS Rating Curve= 0 ,0
Exp/Cntr=0.3,0.1

Type RM Length L Ch R = 1 ,11053   ,435,435,435
BEGIN DESCRIPTION:
SHELTON MILL BRANCH 24.0
END DESCRIPTION:
XS GIS Cut Line= 3
      3681299.62     10778610.18      3681049.61     10778860.19
      3680699.59     10778960.19
#Sta/Elev= 30
  4642.9  443.68  4671.2   444.1  4699.5  442.18  4717.6  440.41  4727.8  439.66
  4770.2  433.48  4784.3  431.38  4798.5  427.89  4823.8     427  4826.5   426.5
  4829.8     427  4847.3     427  5144.2     427  5164.2     427  5173.3   427.6
  5204.5  427.84  5225.3  429.78  5231.8  432.02    5237  431.61  5246.1   432.7
  5256.5  434.69  5270.8  435.67  5277.3  437.37  5287.7  439.12  5298.1  441.47
  5309.8   443.1  5318.9  445.19  5329.3  445.87  5338.4  447.42  5360.5  449.13
#Mann= 6 ,-1 , 0
  4642.9     .05       0  4717.6     .16       0  4823.8    .033       0
  4829.8     .16       0  4847.3     .05       0  5144.2     .12       0
Bank Sta=4770.2,5256.5
XS Rating Curve= 0 ,0
Exp/Cntr=0.3,0.1

Type RM Length L Ch R = 1 ,10618   ,433,433,433
BEGIN DESCRIPTION:
SHELTON MILL BRANCH 23.0
END DESCRIPTION:
XS GIS Cut Line= 3
      3681199.59      10778260.2      3680899.61     10778460.19
       3680649.6     10778660.19
#Sta/Elev= 30
    4668   445.5  4690.5   444.9  4711.5  443.14  4717.6  443.13  4753.6  438.77
  4768.6  437.72  4776.1  435.82  4789.7  434.65  4798.7  433.09  4819.7   430.1
  4840.7  427.85  4848.3  427.34  4861.8  427.59  4867.8     427  4870.5   426.5
  4873.8     427  4875.5  427.33  4884.3     427  5192.6  427.01    5199   427.7
    5207  427.48  5213.4  427.98  5228.8  429.96  5234.2  429.61  5248.6  432.52
  5256.6  433.57  5271.1  436.81  5284.7  437.93  5298.3  440.77  5348.7  444.93
#Mann= 5 ,-1 , 0
    4668     .16       0  4867.8    .033       0  4873.8     .16       0
  4875.5     .05       0  5228.8     .12       0
Bank Sta=4798.7,5256.6
XS Rating Curve= 0 ,0
Exp/Cntr=0.3,0.1

Type RM Length L Ch R = 1 ,10185   ,31,31,31
BEGIN DESCRIPTION:
SHELTON MILL BRANCH 22.0
END DESCRIPTION:
XS GIS Cut Line= 2
      3680777.24     10777675.24      3680564.58     10778651.75
#Sta/Elev= 30
  4566.8  437.08  4602.6  437.41  4609.8  434.86  4612.8   433.8  4712.1     427
  4714.8   426.5  4718.1     427  4746.7     427  4906.3     427  4911.4   429.3
  4950.3     427  4955.4  431.23  5004.5  431.17  5048.4     427  5053.6  430.71
  5092.4   427.2  5097.5  430.94  5141.5     427  5150.1  430.43  5185.5     427
  5190.6  431.27  5226.9  427.46  5248.4  430.42  5249.8  430.32  5283.6  427.72
  5288.7  430.95  5327.6  429.93  5349.7  432.87    5410  438.82  5566.2  444.37
#Mann= 9 ,-1 , 0
  4566.8     .12       0  4609.8     .16       0  4712.1     .07       0
  4718.1     .16       0  4746.7     .12       0  5150.1     .05       0
  5248.4     .12       0  5249.8     .05       0    5410     .12       0
Bank Sta=4612.8,5349.7
XS Rating Curve= 0 ,0
Exp/Cntr=0.3,0.1

Type RM Length L Ch R = 1 ,10154   ,80,80,80
BEGIN DESCRIPTION:
Mapping XS 84fc7de5
END DESCRIPTION:
XS GIS Cut Line= 2
       3680753.8     10777651.38       3680542.1     10778645.69
#Sta/Elev= 30
  4565.2  432.66  4574.2  433.83  4604.6  435.04  4609.7  433.55  4615.1  430.54
  4617.7   430.7  4625.3  431.17  4656.2  429.39    4659  428.89  4662.2  429.39
  4666.2  430.44  4676.4  430.05  4703.7  432.14  4755.9  431.61  4802.8  431.08
  4847.3  431.99    4902  431.56  4921.8  432.55    4996  432.02  5013.8  432.82
  5034.3  432.54  5045.6  431.44  5218.3  432.76  5296.3  432.59  5371.7  435.03
    5424  440.32  5426.8  441.29  5476.4  444.06  5535.3  445.64  5581.8  445.58
#Mann= 7 ,-1 , 0
  4565.2     .12       0  4617.7     .16       0  4656.2     .07       0
  4662.2     .16       0  4755.9     .12       0  5296.3     .05       0
    5424     .12       0
Bank Sta=4609.7,5218.3
XS Rating Curve= 0 ,0
Exp/Cntr=0.3,0.1

Type RM Length L Ch R = 1 ,10074   ,859,859,859
BEGIN DESCRIPTION:
SHELTON MILL BRANCH 21.0
END DESCRIPTION:
XS GIS Cut Line= 2
      3680699.99     10777599.28      3680492.96     10778599.69
#Sta/Elev= 30
  4574.8  425.97  4601.3  429.15    4637     423  4657.4  428.51  4677.8  424.42
    4686  426.62  4696.6  430.69  4701.7  427.76  4746.8  426.79  4759.5  422.01
  4787.5  418.92  4802.1   416.8  4841.2  414.28  4847.2  417.49  4852.3  414.26
  4861.7  414.35  4892.3   415.7  4897.4  418.25  4902.5  415.22  4942.5  415.57
  5001.6  411.91  5004.4  411.41  5007.6  411.91  5093.1  416.52  5148.4     415
  5188.4  416.84    5311  425.46  5416.3  438.73  5466.4  443.17  5596.4   447.7
#Mann= 7 ,-1 , 0
  4574.8     .12       0    4686     .16       0  4787.5     .12       0
  5001.6     .07       0  5007.6     .12       0  5416.3     .05       0
  5466.4     .12       0
Bank Sta=4802.1,5188.4
XS Rating Curve= 0 ,0
Exp/Cntr=0.3,0.1

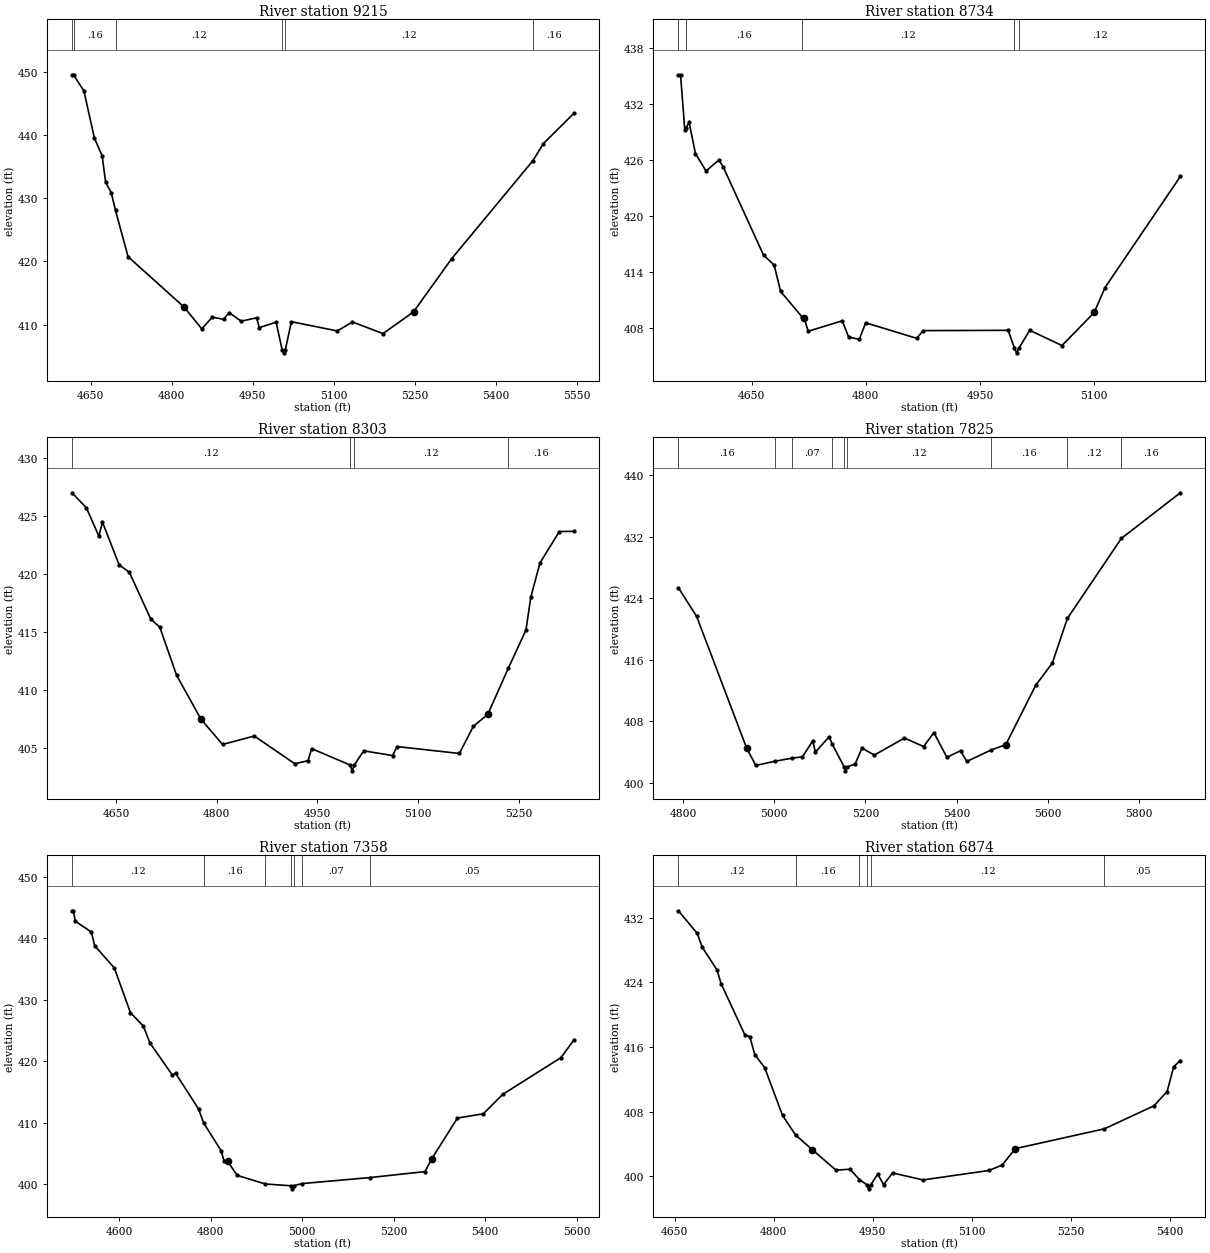
Type RM Length L Ch R = 1 ,9215    ,481,481,481
BEGIN DESCRIPTION:
SHELTON MILL BRANCH 20.0
END DESCRIPTION:
XS GIS Cut Line= 3
      3680449.62     10776960.16      3680349.61     10777310.19
      3679949.63     10777710.17
#Sta/Elev= 30
  4615.4  449.59  4618.4  449.56  4637.5  447.05    4657  439.54  4671.3  436.77
  4677.8  432.52  4688.2   430.9  4696.1  428.08  4719.4  420.75  4823.4  412.74
  4855.9  409.31  4875.4  411.17  4896.2  410.82  4906.6  411.89  4928.7  410.53
  4957.3  411.06  4962.5  409.51  4993.6  410.37  5004.7  406.01  5007.5  405.51
  5010.7  406.01  5021.9  410.45  5106.7  408.98    5135   410.4  5191.6  408.56
  5248.1     412  5318.8  420.44  5469.5     436  5488.6  438.68  5545.1  443.47
#Mann= 6 ,-1 , 0
  4615.4     .05       0  4618.4     .16       0  4696.1     .12       0
  5004.7     .07       0  5010.7     .12       0  5469.5     .16       0
Bank Sta=4823.4,5248.1
XS Rating Curve= 0 ,0
Exp/Cntr=0.3,0.1

Type RM Length L Ch R = 1 ,8734    ,431,431,431
BEGIN DESCRIPTION:
SHELTON MILL BRANCH 19.0
END DESCRIPTION:
XS GIS Cut Line= 3
      3680399.61     10776910.19      3679999.61     10777110.19
      3679849.64     10777260.16
#Sta/Elev= 30
  4553.9   435.1  4556.7   435.1  4562.3  429.17  4564.1  429.44  4567.9     430
  4576.3  426.66  4590.2   424.8    4607  425.97  4612.6  425.26  4665.7   415.8
  4679.7  414.72  4688.1  411.91  4716.3  409.18  4718.8  409.11  4724.4  407.64
  4769.1  408.76  4777.5  407.02  4791.5  406.77  4799.9  408.55    4867  406.88
  4875.3  407.71  4987.1  407.74  4995.3  405.83  4998.1  405.33  5001.3  405.83
  5015.3  407.75  5057.7  406.11  5100.1  409.65  5114.3  412.32  5213.2  424.21
#Mann= 5 ,-1 , 0
  4553.9     .05       0  4564.1     .16       0  4716.3     .12       0
  4995.3     .07       0  5001.3     .12       0
Bank Sta=4718.8,5100.1
XS Rating Curve= 0 ,0
Exp/Cntr=0.3,0.1

Type RM Length L Ch R = 1 ,8303    ,478,478,478
BEGIN DESCRIPTION:
SHELTON MILL BRANCH 18.0
END DESCRIPTION:
XS GIS Cut Line= 3
      3680299.62     10776610.18      3679899.61     10776760.19
      3679649.58     10776960.21
#Sta/Elev= 30
  4584.4  427.03  4605.8  425.74  4624.5  423.28  4629.8   424.5  4654.7   420.8
  4669.9  420.16  4701.9   416.1  4715.2  415.42  4740.2  411.26  4776.7  407.45
  4808.7  405.28  4855.9  406.01  4916.4  403.61    4936  403.88  4941.3  404.92
  4998.8   403.5  5001.6     403  5004.8   403.5  5018.8  404.73    5062  404.32
  5068.4   405.1  5161.3   404.5  5182.1  406.84  5203.7  407.89  5234.2  411.87
  5260.5  415.17  5267.7  418.01  5281.3  420.96  5310.2  423.68  5331.8   423.7
#Mann= 4 ,-1 , 0
  4584.4     .12       0  4998.8     .07       0  5004.8     .12       0
  5234.2     .16       0
Bank Sta=4776.7,5203.7
XS Rating Curve= 0 ,0
Exp/Cntr=0.3,0.1

Type RM Length L Ch R = 1 ,7825    ,467,467,467
BEGIN DESCRIPTION:
SHELTON MILL BRANCH 17.0
END DESCRIPTION:
XS GIS Cut Line= 3
      3680049.65     10776360.19      3679849.61     10776360.19
      3679099.63     10776860.17
#Sta/Elev= 30
  4789.5  425.34  4829.5  421.62  4939.5  404.43  4959.5  402.22  5000.6  402.76
  5038.6  403.17  5061.7  403.34  5084.2  405.41  5090.2  403.96  5120.2  405.95
  5126.9  405.01  5153.3  402.02    5156  401.52  5159.3  402.02  5177.3  402.41
  5192.4  404.48  5219.4  403.57  5285.5  405.79  5327.6  404.68  5350.1   406.5
  5378.6  403.28  5408.7  404.14  5422.2  402.74  5476.4  404.25  5507.8  404.92
  5573.9  412.69    5610  415.54  5643.1  421.36  5761.5  431.77  5890.9  437.71
#Mann= 9 ,-1 , 0
  4789.5     .16       0  5000.6     .12       0  5038.6     .07       0
  5126.9     .12       0  5153.3     .07       0  5159.3     .12       0
  5476.4     .16       0  5643.1     .12       0  5761.5     .16       0
Bank Sta=4939.5,5507.8
XS Rating Curve= 0 ,0
Exp/Cntr=0.3,0.1

Type RM Length L Ch R = 1 ,7358    ,484,484,484
BEGIN DESCRIPTION:
SHELTON MILL BRANCH 16.0
END DESCRIPTION:
XS GIS Cut Line= 3
      3679849.62     10775810.18      3679449.61     10776160.19
      3679049.62     10776560.18
#Sta/Elev= 30
  4496.5  444.47  4499.8  444.47  4503.6  442.79  4538.8  441.03  4546.3  438.79
  4589.1  435.19  4624.2  427.94  4652.7  425.72  4666.9     423  4716.2  417.76
  4722.9  418.09  4773.2  412.27  4784.6  409.97  4822.5   405.5  4829.2  403.79
  4836.8  403.76  4857.7  401.48  4919.3  400.08  4975.2  399.79  4977.9  399.29
  4981.2  399.79    4999  400.14  5147.6  401.12  5268.4  402.09  5282.6  404.12
  5339.2  410.79  5395.7  411.48  5438.1  414.63  5565.4  420.61  5593.7  423.46
#Mann= 7 ,-1 , 0
  4496.5     .12       0  4784.6     .16       0  4919.3     .05       0
  4975.2     .07       0  4981.2     .05       0    4999     .07       0
  5147.6     .05       0
Bank Sta=4836.8,5282.6
XS Rating Curve= 0 ,0
Exp/Cntr=0.3,0.1

Type RM Length L Ch R = 1 ,6874    ,500,500,500
BEGIN DESCRIPTION:
SHELTON MILL BRANCH 15.0
END DESCRIPTION:
XS GIS Cut Line= 3
      3679349.63     10775510.15      3679149.61     10775810.19
      3678749.61     10775810.19
#Sta/Elev= 30
  4655.6  432.84  4684.2  430.04  4691.7  428.33  4714.2  425.52  4720.2  423.85
  4756.3   417.5  4763.8  417.28  4771.3  415.07  4786.3  413.45  4813.4  407.54
  4833.2  405.12  4858.5  403.31  4894.5  400.77  4915.5   400.9  4929.9  399.62
  4941.1  398.97  4943.8  398.47  4947.1  398.97  4957.6   400.3  4966.6  398.99
  4980.1  400.44  5026.2  399.57  5126.2  400.74  5146.2  401.41  5166.2  403.44
  5301.2  405.89  5376.2  408.73  5396.2   410.5  5406.2  413.57  5416.2  414.33
#Mann= 6 ,-1 , 0
  4655.6     .12       0  4833.2     .16       0  4929.9     .12       0
  4941.1     .07       0  4947.1     .12       0  5301.2     .05       0
Bank Sta=4858.5,5166.2
XS Rating Curve= 0 ,0
Exp/Cntr=0.3,0.1

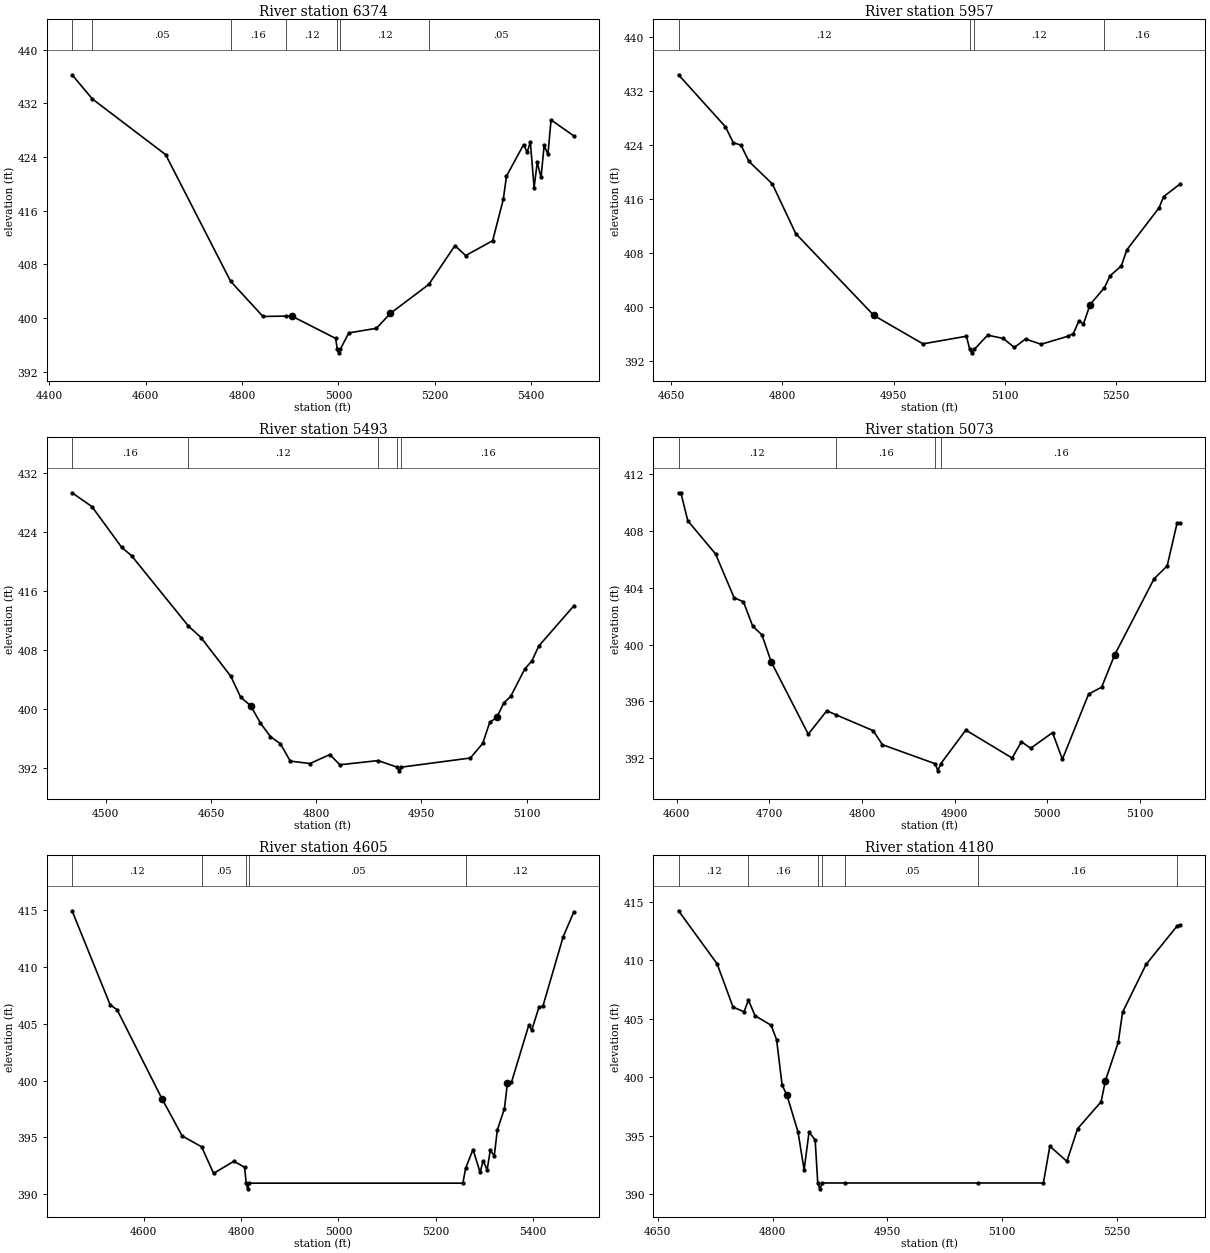
Type RM Length L Ch R = 1 ,6374    ,417,417,417
BEGIN DESCRIPTION:
SHELTON MILL BRANCH 14.0
END DESCRIPTION:
XS GIS Cut Line= 3
      3679401.87       10775394.      3678937.42      10775459.1
      3678573.72     10775900.73
#Sta/Elev= 30
  4447.4  436.27  4489.6  432.66  4641.5  424.37  4776.3  405.49  4843.5  400.24
  4890.8   400.3  4904.1  400.27  4994.3  396.97  4997.7  395.32  5000.5  394.82
  5003.7  395.32  5021.5  397.79  5078.9  398.48  5107.6  400.69  5187.4  405.01
  5241.8  410.81    5264  409.32    5320  411.54  5342.2  417.73  5348.7  421.16
  5384.2  425.85  5391.7  424.72  5398.2  426.27    5406  419.45  5412.5   423.2
  5420.4  420.96  5426.8  425.73  5434.7   424.4  5441.2  429.54  5488.5  427.15
#Mann= 7 ,-1 , 0
  4447.4     .16       0  4489.6     .05       0  4776.3     .16       0
  4890.8     .12       0  4997.7     .07       0  5003.7     .12       0
  5187.4     .05       0
Bank Sta=4904.1,5107.6
XS Rating Curve= 0 ,0
Exp/Cntr=0.3,0.1

Type RM Length L Ch R = 1 ,5957    ,464,464,464
BEGIN DESCRIPTION:
SHELTON MILL BRANCH 13.0
END DESCRIPTION:
XS GIS Cut Line= 3
       3679149.6     10775060.19      3678849.61     10775160.19
      3678549.59      10775360.2
#Sta/Elev= 30
  4659.9  434.35  4723.1  426.66  4733.7  424.31  4744.2  423.92  4754.8  421.54
  4786.4  418.19    4818  410.84  4923.4  398.72  4989.6  394.52  5048.2  395.65
  5052.7  393.69  5055.5  393.19  5058.7  393.69  5076.8  395.81  5097.8  395.32
  5112.8  393.99  5127.9  395.24  5148.9  394.46  5184.9  395.64  5192.5  396.05
    5200  397.94    5206  397.46    5215  400.34  5234.3  402.83    5242   404.6
  5257.1  406.05  5264.6  408.44  5308.1  414.67  5314.1  416.31  5336.7  418.21
#Mann= 4 ,-1 , 0
  4659.9     .12       0  5052.7     .07       0  5058.7     .12       0
  5234.3     .16       0
Bank Sta=4923.4,5215
XS Rating Curve= 0 ,0
Exp/Cntr=0.3,0.1

Type RM Length L Ch R = 1 ,5493    ,420,420,420
BEGIN DESCRIPTION:
SHELTON MILL BRANCH 12.0
END DESCRIPTION:
XS GIS Cut Line= 3
      3679049.63     10774360.17      3678649.61     10774760.19
      3678499.63     10774760.19
#Sta/Elev= 30
  4451.8  429.27  4480.1   427.4  4522.5  421.89  4536.7  420.74  4617.7  411.23
  4635.7  409.66  4678.1  404.43  4692.2  401.59  4706.4  400.44  4720.5  398.08
  4734.7  396.24  4748.8   395.3    4763  392.93  4791.2   392.6  4819.5  393.82
  4833.7  392.43  4888.3     393  4915.5  392.11  4918.3  391.61  4921.5  392.11
    5020  393.35  5037.5  395.33  5047.5  398.17  5057.5  398.84  5067.5   400.8
  5077.5   401.7  5097.5  405.41  5107.5  406.48  5117.5  408.52  5167.5  413.96
#Mann= 5 ,-1 , 0
  4451.8     .16       0  4617.7     .12       0  4888.3     .16       0
  4915.5     .07       0  4921.5     .16       0
Bank Sta=4706.4,5057.5
XS Rating Curve= 0 ,0
Exp/Cntr=0.3,0.1

Type RM Length L Ch R = 1 ,5073    ,468,468,468
BEGIN DESCRIPTION:
SHELTON MILL BRANCH 11.0
END DESCRIPTION:
XS GIS Cut Line= 3
      3678899.65     10774360.19      3678499.61     10774360.19
      3678399.58     10774460.22
#Sta/Elev= 30
  4602.1  410.68  4604.6  410.68  4612.1  408.71  4642.1  406.37  4662.1  403.29
  4672.1  403.01  4682.1   401.3  4692.1  400.68  4702.1  398.78  4742.1  393.69
  4762.1  395.34  4771.8  395.06  4812.1  393.94  4822.1  392.95  4879.1  391.61
  4881.9  391.11  4885.1  391.61  4912.1  393.98  4962.1  392.01  4972.1  393.16
  4982.1   392.7  5005.7   393.8  5016.3  391.92  5044.6  396.51  5058.7     397
  5072.8  399.28  5115.3  404.63  5129.4  405.53    5140  408.52  5143.6  408.52
#Mann= 4 ,-1 , 0
  4602.1     .12       0  4771.8     .16       0  4879.1     .07       0
  4885.1     .16       0
Bank Sta=4702.1,5072.8
XS Rating Curve= 0 ,0
Exp/Cntr=0.3,0.1

Type RM Length L Ch R = 1 ,4605    ,425,425,425
BEGIN DESCRIPTION:
SHELTON MILL BRANCH 10.0
END DESCRIPTION:
XS GIS Cut Line= 3
      3678699.58     10773610.22      3678299.61     10773960.19
      3677899.58     10774260.21
#Sta/Elev= 30
  4452.5  414.95  4530.8  406.67    4545  406.24  4637.1  398.42  4678.8  395.13
  4718.8  394.17  4743.4  391.83  4785.1   392.9    4807  392.37  4810.6  390.97
  4813.3  390.47  4816.6  390.97  5255.8  390.97  5261.6  392.29  5276.7  393.93
  5291.3  391.92  5297.5  392.94  5305.8  392.14  5312.1  393.85  5320.4  393.38
  5326.7  395.65  5341.3  397.54  5347.5  399.81  5355.8  399.86  5391.3  404.87
  5397.5  404.46  5412.1  406.44  5420.4  406.56  5462.1  412.67    5484  414.85
#Mann= 5 ,-1 , 0
  4452.5     .12       0  4718.8     .05       0  4810.6    .035       0
  4816.6     .05       0  5261.6     .12       0
Bank Sta=4637.1,5347.5
XS Rating Curve= 0 ,0
Exp/Cntr=0.3,0.1

Type RM Length L Ch R = 1 ,4180    ,486,486,486
BEGIN DESCRIPTION:
SHELTON MILL BRANCH 9.0
END DESCRIPTION:
XS GIS Cut Line= 3
      3678099.61     10773560.19      3677899.61     10773810.19
      3677599.58      10773960.2
#Sta/Elev= 30
  4677.2  414.23  4727.6   409.7  4748.4     406  4762.8   405.6  4768.5   406.6
  4777.2  405.26  4798.1  404.45  4805.3  403.22  4812.5  399.35  4818.9  398.46
  4833.3  395.33  4841.3  392.09  4847.7  395.32  4855.7  394.65  4859.1  390.97
  4861.8  390.47  4865.1  390.97    4895  390.97    5068  390.97  5153.9  390.97
  5162.3  394.11  5184.6  392.82  5198.6  395.61  5229.3  397.91  5234.9  399.71
  5251.7  402.99  5257.3  405.55    5288  409.64  5329.1  412.97  5332.8  412.98
#Mann= 7 ,-1 , 0
  4677.2     .12       0  4768.5     .16       0  4859.1    .033       0
  4865.1     .16       0    4895     .05       0    5068     .16       0
  5329.1     .05       0
Bank Sta=4818.9,5234.9
XS Rating Curve= 0 ,0
Exp/Cntr=0.3,0.1