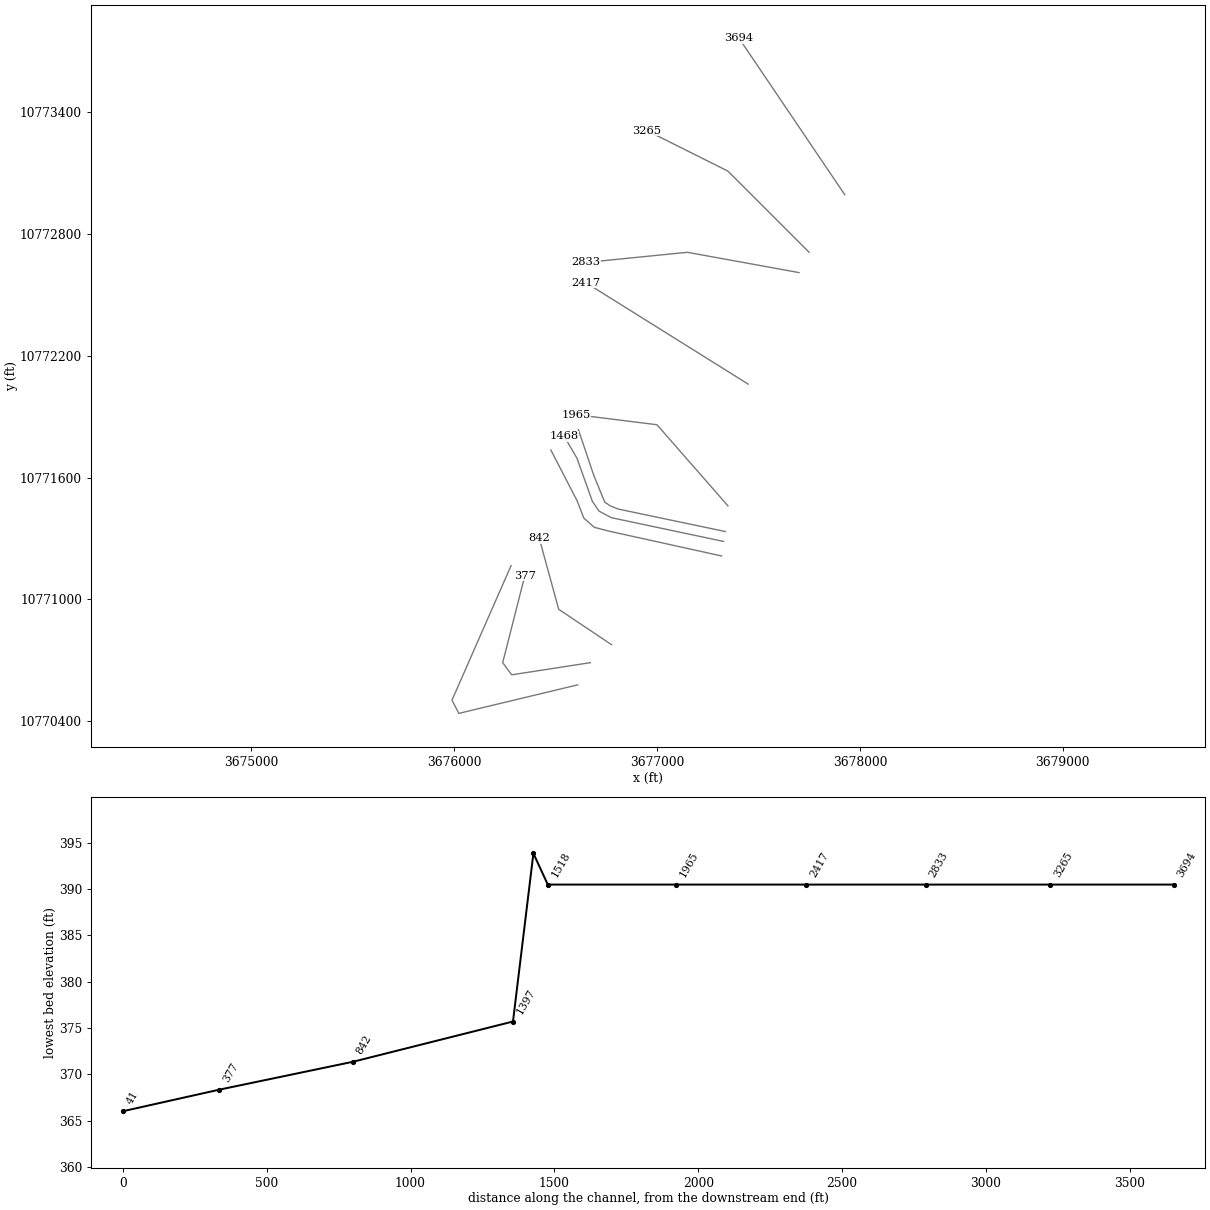
HEC-RAS study SHELTON MILL BRANCH.prj: SHELTON MILL BRANCH Base Level Engineering

--- SHELTON MILL BRANCH.g01 (geometry) --- (continued)

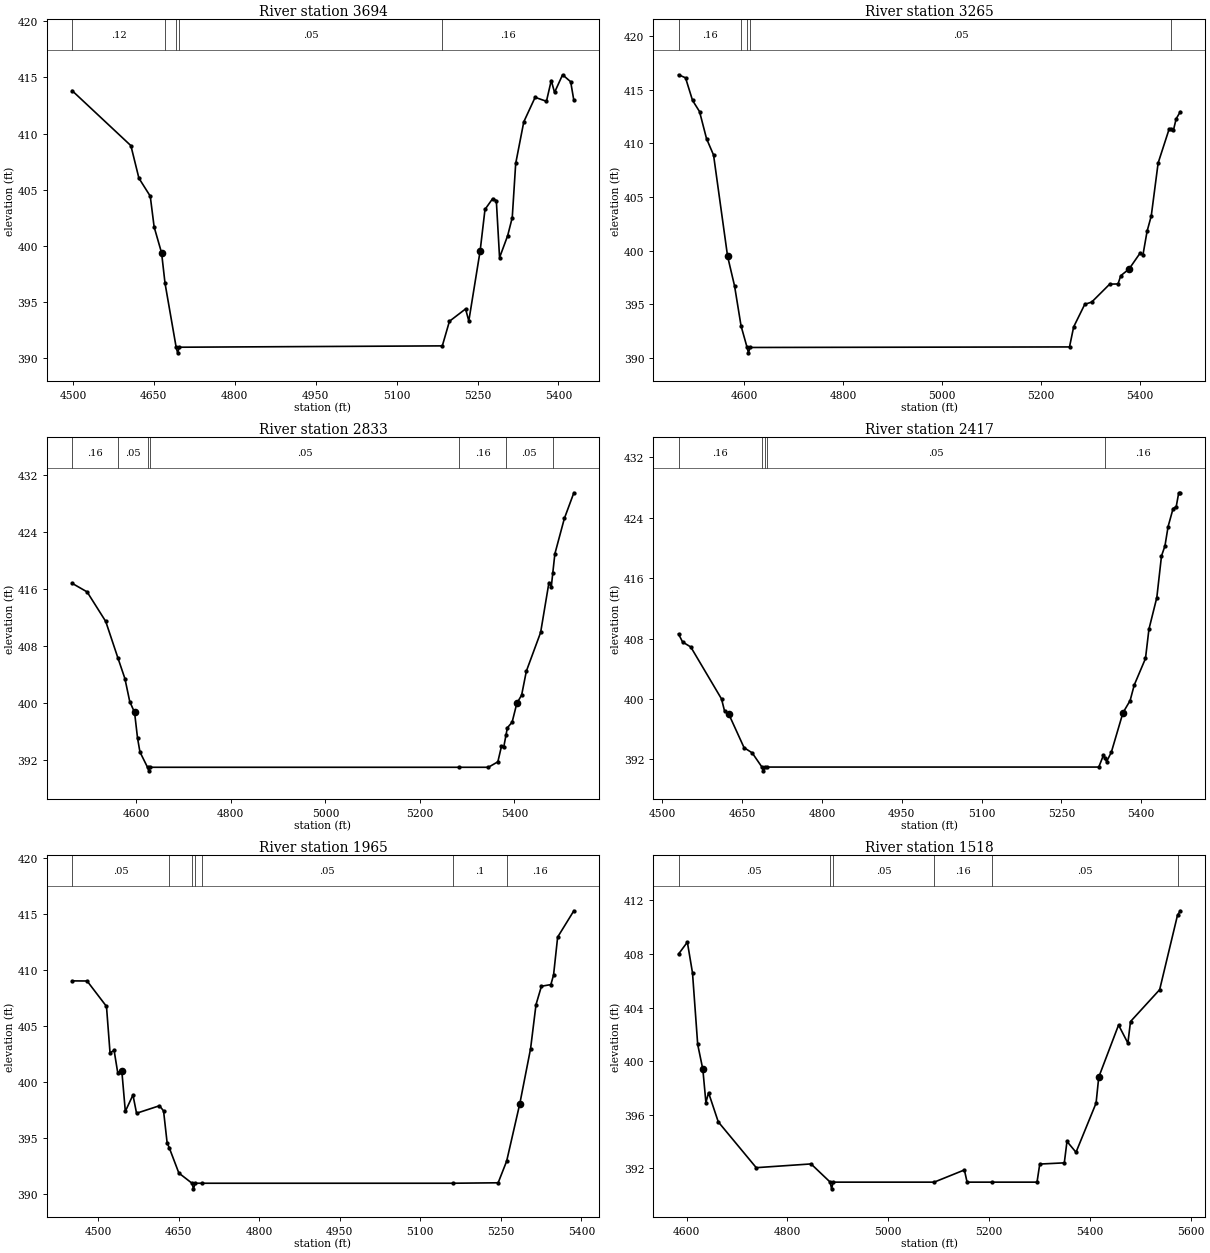
Type RM Length L Ch R = 1 ,3694    ,429,429,429
BEGIN DESCRIPTION:
SHELTON MILL BRANCH 8.0
END DESCRIPTION:
XS GIS Cut Line= 2
      3677925.13     10772994.19      3677404.46     10773764.78
#Sta/Elev= 30
  4498.5  413.82  4607.5  408.92  4622.4  406.02  4643.4  404.42  4650.6  401.68
  4664.4  399.37  4670.8  396.66  4691.4  390.97  4694.1  390.47  4697.4  390.97
  5184.7  391.09  5197.9  393.28  5227.8  394.38  5233.8  393.31  5254.8  399.55
  5263.8  403.24  5278.1  404.21  5284.8  404.03  5290.8  398.95  5305.8   400.9
  5314.3  402.51  5320.7  407.33  5335.7  411.04  5356.7  413.22  5377.7  412.87
  5386.6  414.72  5392.7  413.66  5407.6  415.23  5422.6  414.61  5428.5  412.94
#Mann= 5 ,-1 , 0
  4498.5     .12       0  4670.8     .05       0  4691.4    .033       0
  4697.4     .05       0  5184.7     .16       0
Bank Sta=4664.4,5254.8
XS Rating Curve= 0 ,0
Exp/Cntr=0.3,0.1

Type RM Length L Ch R = 1 ,3265    ,432,432,432
BEGIN DESCRIPTION:
SHELTON MILL BRANCH 7.0
END DESCRIPTION:
XS GIS Cut Line= 3
      3677749.58     10772710.22      3677349.61     10773110.19
      3676949.57     10773310.21
#Sta/Elev= 30
    4468  416.38  4482.1   416.1  4496.2     414  4510.4  412.95  4524.5  410.43
  4538.7   408.9    4567  399.47  4581.1   396.7  4594.2  392.98  4606.4  390.97
  4609.1  390.47  4612.4  390.97  5257.2  391.02  5265.6  392.89    5288  394.99
    5302   395.2  5338.3  396.87  5355.1  396.89  5360.7  397.66  5377.4  398.28
  5399.8  399.77  5405.4  399.58  5413.8   401.8  5422.2  403.22  5436.1  408.16
  5458.5  411.35  5462.1  411.29  5466.9   411.2  5472.5  412.28  5480.9  412.94
#Mann= 5 ,-1 , 0
    4468     .16       0  4594.2     .05       0  4606.4    .033       0
  4612.4     .05       0  5462.1     .16       0
Bank Sta=4567,5377.4
XS Rating Curve= 0 ,0
Exp/Cntr=0.3,0.1

Type RM Length L Ch R = 1 ,2833    ,416,416,416
BEGIN DESCRIPTION:
SHELTON MILL BRANCH 6.0
END DESCRIPTION:
XS GIS Cut Line= 3
      3677699.63     10772610.18      3677149.61     10772710.19
      3676649.64     10772660.19
#Sta/Elev= 30
  4464.1  416.83  4495.9  415.62  4535.3  411.47    4561  406.35  4575.9  403.43
  4586.1  400.21  4596.3  398.68  4602.6  395.07  4607.7  393.12  4623.7  390.97
  4626.5  390.47  4629.7  390.97  5282.8  390.97  5344.7  390.97  5364.8  391.74
  5372.4   393.9  5377.4  393.85  5381.9  395.45  5384.9  396.52    5395  397.31
    5405  399.97  5415.1  401.11  5425.1  404.48  5455.3  409.92  5472.9  416.93
  5477.9  416.36    5481  418.26  5485.4  420.96  5505.5  425.94  5525.6  429.55
#Mann= 7 ,-1 , 0
  4464.1     .16       0    4561     .05       0  4623.7    .033       0
  4629.7     .05       0  5282.8     .16       0  5381.9     .05       0
    5481     .16       0
Bank Sta=4596.3,5405
XS Rating Curve= 0 ,0
Exp/Cntr=0.3,0.1

Type RM Length L Ch R = 1 ,2417    ,452,452,452
BEGIN DESCRIPTION:
SHELTON MILL BRANCH 5.0
END DESCRIPTION:
XS GIS Cut Line= 3
      3677449.59      10772060.2      3677049.61     10772310.19
      3676649.59      10772560.2
#Sta/Elev= 30
  4530.3   408.6  4537.9  407.54  4553.3  406.88  4611.1     400    4617  398.35
  4624.6  398.01  4653.5  393.54  4668.8  392.85  4687.1  390.97  4689.8  390.47
  4693.1  390.97  4697.2  390.97  5320.4  390.97  5329.2  392.55  5331.7  392.19
  5335.1  391.69    5344  392.94  5365.8  398.16  5379.3  399.78    5387  401.83
  5408.2  405.36  5414.7  409.24  5429.5  413.43  5438.3  418.94  5444.8  420.27
  5450.7  422.83  5460.1  425.22    5466  425.48  5470.7  427.31  5473.7  427.31
#Mann= 5 ,-1 , 0
  4530.3     .16       0  4687.1    .033       0  4693.1     .16       0
  4697.2     .05       0  5331.7     .16       0
Bank Sta=4624.6,5365.8
XS Rating Curve= 0 ,0
Exp/Cntr=0.3,0.1

Type RM Length L Ch R = 1 ,1965    ,447,447,447
BEGIN DESCRIPTION:
SHELTON MILL BRANCH 4.0
END DESCRIPTION:
XS GIS Cut Line= 3
      3677349.62     10771460.17      3676999.61     10771860.19
      3676599.65     10771910.18
#Sta/Elev= 30
  4451.5  409.04  4479.5  409.03  4515.6  406.76  4522.2  402.62  4529.8  402.83
  4536.5  400.85  4544.1  401.03  4550.7  397.39  4564.9  398.85  4571.6  397.22
  4614.3  397.89  4621.9  397.43  4628.5   394.6  4632.4  394.15  4650.4  391.88
  4674.9  390.97  4677.6  390.47  4680.9  390.97  4693.1  390.97  5160.6  390.97
  5245.1  391.01  5260.9  392.94  5285.4  398.07  5305.5  402.99  5315.6  406.92
  5325.7  408.56  5343.3  408.71  5348.3  409.57  5355.9  412.95  5386.1   415.3
#Mann= 7 ,-1 , 0
  4451.5     .05       0  4632.4     .16       0  4674.9    .033       0
  4680.9     .16       0  4693.1     .05       0  5160.6      .1       0
  5260.9     .16       0
Bank Sta=4544.1,5285.4
XS Rating Curve= 0 ,0
Exp/Cntr=0.3,0.1

Type RM Length L Ch R = 1 ,1518    ,50,50,50
BEGIN DESCRIPTION:
Mapping XS fa67a865
END DESCRIPTION:
XS GIS Cut Line= 6
      3677336.76     10771333.81      3676809.38     10771444.49
      3676770.32     10771459.68      3676742.11     10771479.21
      3676687.85     10771611.59      3676612.25     10771836.25
#Sta/Elev= 30
    4584     408  4601.5  408.89  4611.7  406.59    4622  401.25  4632.2  399.39
  4638.3  396.91  4643.5  397.65  4662.8  395.47  4738.1  392.05  4846.8  392.33
  4884.8  390.97  4887.5  390.47  4890.8  390.97    5091  390.97  5150.9  391.88
  5156.3  390.97  5205.2  390.97    5295  390.97  5300.4  392.32  5349.1  392.41
  5354.4  394.01  5372.3   393.2  5412.1  396.87  5417.4  398.81  5456.7   402.7
  5475.2  401.35  5480.4  402.96  5538.2  405.34  5573.6   410.9  5579.2  411.23
#Mann= 6 ,-1 , 0
    4584     .05       0  4884.8     .03       0  4890.8     .05       0
    5091     .16       0  5205.2     .05       0  5573.6     .16       0
Bank Sta=4632.2,5417.4
XS Rating Curve= 0 ,0
Exp/Cntr=0.3,0.1

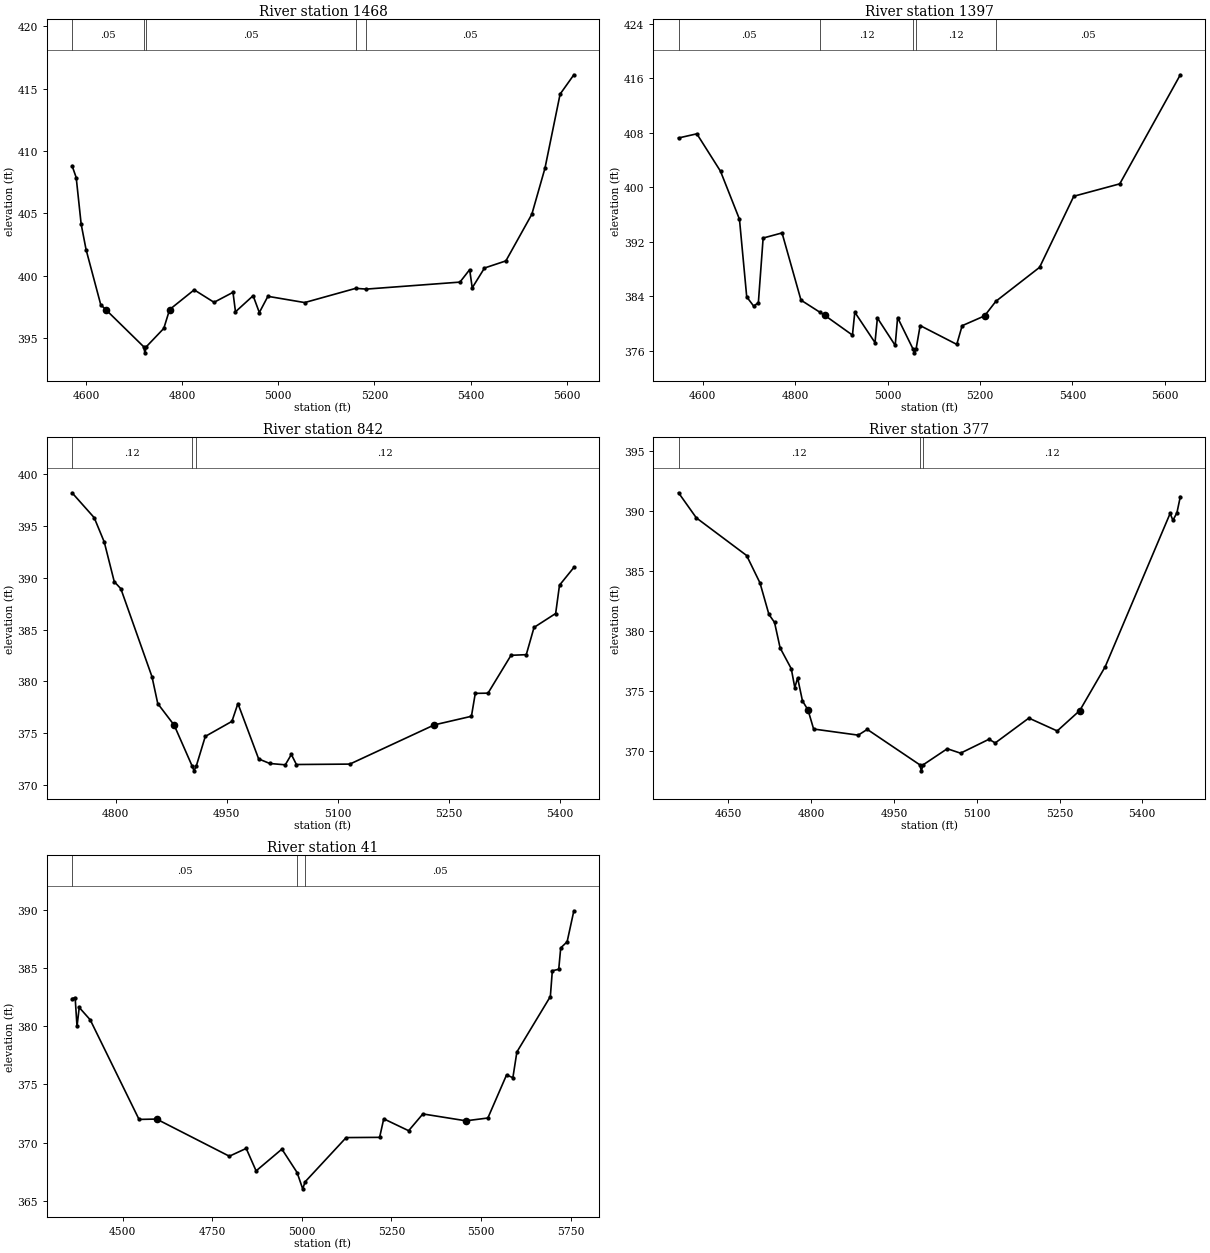
Type RM Length L Ch R = 1 ,1468    ,71,71,71
BEGIN DESCRIPTION:
Mapping XS 4aff4ff1
END DESCRIPTION:
XS GIS Cut Line= 6
      3677328.06     10771284.98      3676774.66     10771402.17
       3676713.9     10771434.73      3676681.34     10771482.47
      3676605.39     10771695.14      3676542.43     10771803.69
#Sta/Elev= 30
  4571.2  408.83  4579.8  407.88  4590.1  404.15  4600.3  402.11  4630.9  397.68
  4641.2   397.3  4719.9  394.33  4722.7  393.83  4725.9  394.33    4762  395.79
  4774.1   397.3  4825.2  398.88  4866.5  397.88  4905.9  398.68  4911.1  397.12
  4947.8  398.41  4960.7  397.06  4978.5  398.36    5055  397.86  5161.2     399
  5183.3  398.94    5378   399.5  5398.2   400.5  5403.5  399.04    5429  400.63
  5473.5   401.2  5527.5  404.94  5554.8  408.63  5586.3  414.57  5614.9  416.12
#Mann= 5 ,-1 , 0
  4571.2     .05       0  4719.9     .03       0  4725.9     .05       0
  5161.2     .12       0  5183.3     .05       0
Bank Sta=4641.2,4774.1
XS Rating Curve= 0 ,0
Exp/Cntr=0.3,0.1

Type RM Length L Ch R = 1 ,1397    ,555,555,555
BEGIN DESCRIPTION:
SHELTON MILL BRANCH 3.0
END DESCRIPTION:
XS GIS Cut Line= 6
      3677318.29     10771213.37      3676767.06      10771334.9
      3676691.11     10771354.43      3676639.03       10771400.
      3676606.47     10771484.64      3676476.58     10771735.76
#Sta/Elev= 30
  4547.9  407.23  4587.5  407.84  4638.7  402.35  4679.7  395.31  4695.4  383.92
  4710.4  382.57  4720.6  383.07  4730.9  392.55  4771.8   393.3  4812.8  383.44
  4853.6  381.67    4864  381.22  4924.1  378.31  4929.2  381.67  4972.9  377.21
  4978.1  380.82  5016.6   376.8  5021.8  380.88  5055.6  376.21  5058.3  375.71
  5061.6  376.21  5070.6  379.71  5149.8  376.95  5161.4  379.69  5209.9  381.13
  5234.5  383.28  5328.9  388.25  5402.9  398.68  5502.4   400.5  5633.4   416.5
#Mann= 5 ,-1 , 0
  4547.9     .05       0  4853.6     .12       0  5055.6     .07       0
  5061.6     .12       0  5234.5     .05       0
Bank Sta=4864,5209.9
XS Rating Curve= 0 ,0
Exp/Cntr=0.3,0.1

Type RM Length L Ch R = 1 ,842     ,465,465,465
BEGIN DESCRIPTION:
Mapping XS ca8ad6da
END DESCRIPTION:
XS GIS Cut Line= 3
      3676775.78     10770776.07      3676515.33     10770950.57
      3676418.98      10771302.1
#Sta/Elev= 30
  4741.1  398.19    4771  395.79  4784.6  393.44  4798.1  389.62    4807  388.94
  4849.1  380.45  4856.9  377.86  4879.1  375.78  4903.1  371.88  4905.9  371.38
  4909.1  371.88  4921.1   374.7  4957.1  376.15  4965.2  377.87  4993.2  372.53
  5008.2  372.09  5029.2  371.96  5037.4  372.96  5044.2  371.99  5116.4  372.03
  5230.5  375.81  5280.7  376.64  5285.9  378.85  5303.1  378.87  5334.2  382.52
  5354.8  382.58  5365.3  385.21  5394.5  386.55  5399.7  389.28  5419.1  390.99
#Mann= 3 ,-1 , 0
  4741.1     .12       0  4903.1     .07       0  4909.1     .12       0
Bank Sta=4879.1,5230.5
XS Rating Curve= 0 ,0
Exp/Cntr=0.3,0.1

Type RM Length L Ch R = 1 ,377     ,336,336,336
BEGIN DESCRIPTION:
SHELTON MILL BRANCH 2.0
END DESCRIPTION:
XS GIS Cut Line= 4
      3676671.54     10770687.54      3676283.56     10770627.65
      3676239.29     10770687.55       3676348.4     10771116.22
#Sta/Elev= 30
  4559.5  391.51  4591.8  389.42  4682.9  386.29  4707.1  384.01  4723.3  381.39
  4733.5  380.72  4743.6   378.6  4763.8  376.87  4770.2   375.3  4775.3   376.1
  4784.1  374.19  4794.2  373.43  4804.3  371.85  4885.2  371.34  4901.5  371.82
  4996.8  368.87  4999.5  368.37  5002.8  368.87  5046.5  370.21  5070.6  369.84
  5122.2     371  5133.4  370.69  5194.4  372.76  5245.8  371.69  5286.7  373.39
  5332.8  377.04  5450.4  389.79  5455.5  389.22  5462.7  389.84  5468.9  391.19
#Mann= 3 ,-1 , 0
  4559.5     .12       0  4996.8     .07       0  5002.8     .12       0
Bank Sta=4794.2,5286.7
XS Rating Curve= 0 ,0
Exp/Cntr=0.3,0.1

Type RM Length L Ch R = 1 ,41      ,0,0,0
BEGIN DESCRIPTION:
SHELTON MILL BRANCH 1.0
END DESCRIPTION:
XS GIS Cut Line= 4
      3676609.03     10770578.16      3676023.14     10770437.55
      3675989.29     10770502.65      3676280.63     10771165.98
#Sta/Elev= 30
  4358.9  382.37  4367.5  382.46  4372.7  379.98  4378.9  381.61  4409.5  380.55
  4545.8     372  4594.8  372.03  4797.8  368.84  4844.9  369.51  4872.5  367.58
  4944.5  369.45  4986.9  367.44  5002.5  366.04  5009.5  366.65  5123.8  370.44
  5217.2  370.46  5228.7  372.05  5298.2  371.03  5337.9  372.47  5458.1  371.88
  5519.3  372.12  5571.5  375.82  5589.1  375.58  5600.3  377.79  5693.7  382.55
  5699.2  384.76  5717.1  384.89  5722.6  386.72  5740.5  387.25  5759.3  389.91
#Mann= 3 ,-1 , 0
  4358.9     .05       0  4986.9     .03       0  5009.5     .05       0
Bank Sta=4594.8,5458.1
XS Rating Curve= 0 ,0
Exp/Cntr=0.3,0.1

Chan Stop Cuts=-1
Use User Specified Reach Order=0
Composite Channel Slope=5