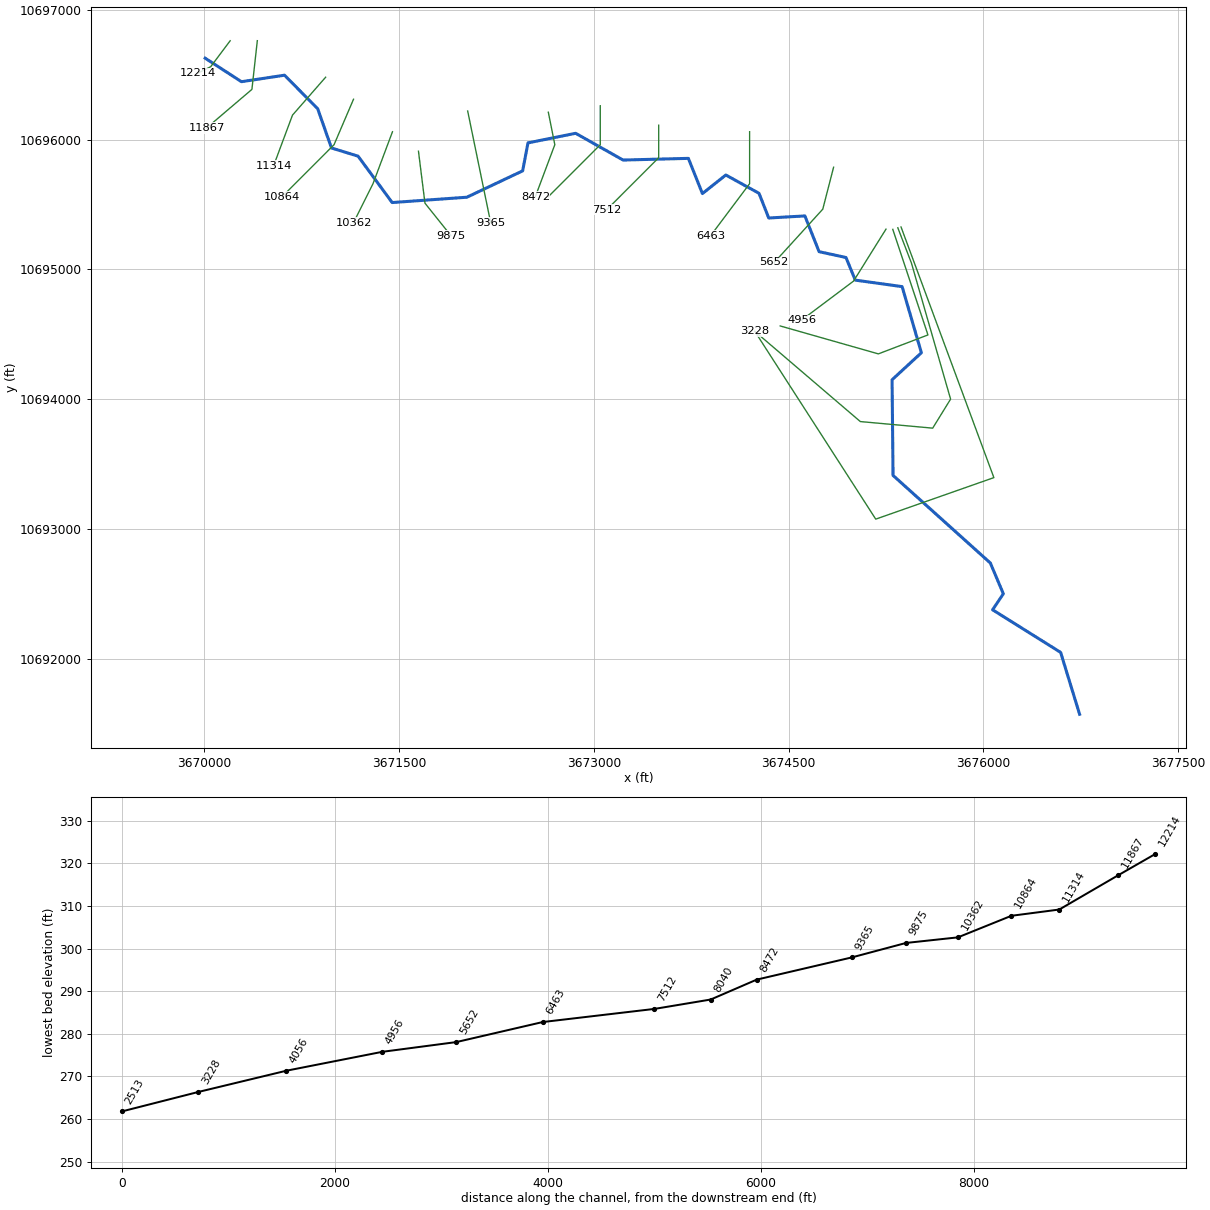
--- SHORT BRANCH.prj (project) ---

Proj Title=SHORT BRANCH Base Level Engineering
Current Plan=p01
Default Exp/Contr=0.3,0.1
English Units
Geom File=g01
Flow File=f01
Plan File=p01
Y Axis Title=Elevation
X Axis Title(PF)=Main Channel Distance
X Axis Title(XS)=Station
BEGIN DESCRIPTION:
SHORT BRANCH
END DESCRIPTION:
DSS Export Rating Curves= 0
DSS Export Rating Curve Sorted= 0
DSS Export Volume Flow Curves= 0
DXF OffsetX= 0
DXF OffsetY= 0
DXF ScaleX= 1
DXF ScaleY= 10

--- SHORT BRANCH.p01 (plan) ---

Plan Title=Multiple Run
Short Identifier=Multiple
Geom File=g01
Flow File=f01
Subcritical Flow
K Sum by GR= 0
Std Step Tol= 0.01
Critical Tol= 0.01
Num of Std Step Trials= 20
Max Error Tol= 0.3
Flow Tol Ratio= 0.001
Split Flow NTrial= 30
Split Flow Tol= 0.02
Split Flow Ratio= 0.02
Log Output Level= 0
Friction Slope Method= 1
Unsteady Friction Slope Method= 2
Unsteady Bridges Friction Slope Method= 1
Parabolic Critical Depth
Global Vel Dist=  1 , 1 , 1
Global Log Level= 0
CheckData=True
Encroach Param= -1, 0, 0, 0
BEGIN DESCRIPTION:
Multiple Run
END DESCRIPTION:

--- SHORT BRANCH.f01 (steady flow) ---

Flow Title=Multiple
Program Version=4.10
Number of Profiles= 7
Profile Names=10-year,25-year,50-year,1pct_min,100-year,1pct_plu,500-year
River Rch & RM=SHORT BRANCH,Reach-1         ,12214
     623     860    1060     960    1298    1756    1957
River Rch & RM=SHORT BRANCH,Reach-1         ,11314
     718     991    1220    1103    1491    2017    2240
Boundary for River Rch & Prof#=SHORT BRANCH,Reach-1         , 1
Up Type= 0
Dn Type= 3
Dn Slope=0.00934
Boundary for River Rch & Prof#=SHORT BRANCH,Reach-1         , 2
Up Type= 0
Dn Type= 3
Dn Slope=0.00934
Boundary for River Rch & Prof#=SHORT BRANCH,Reach-1         , 3
Up Type= 0
Dn Type= 3
Dn Slope=0.00934
Boundary for River Rch & Prof#=SHORT BRANCH,Reach-1         , 4
Up Type= 0
Dn Type= 3
Dn Slope=0.00934
Boundary for River Rch & Prof#=SHORT BRANCH,Reach-1         , 5
Up Type= 0
Dn Type= 3
Dn Slope=0.00934
Boundary for River Rch & Prof#=SHORT BRANCH,Reach-1         , 6
Up Type= 0
Dn Type= 3
Dn Slope=0.00934
Boundary for River Rch & Prof#=SHORT BRANCH,Reach-1         , 7
Up Type= 0
Dn Type= 3
Dn Slope=0.00934
DSS Import GetInterval= 0
DSS Import GetPeak= 0
DSS Import FillOption= 0

--- SHORT BRANCH.g01 (geometry) ---

Geom Title=Existing Conditions
Program Version=4.10

River Reach=SHORT BRANCH    ,Reach-1
Reach XY= 30
      3670007.38     10696625.85       3670286.5       10696445.
      3670618.25       10696495.       3670873.5       10696237.
      3670979.75       10695935.       3671184.5       10695872.
        3671447.       10695515.       3672022.5       10695556.
        3672452.       10695759.      3672492.75       10695974.
        3672860.       10696048.      3673225.25       10695842.
        3673728.       10695855.      3673836.25       10695584.
      3674016.25       10695727.        3674272.       10695586.
      3674346.75       10695396.      3674625.25       10695412.
       3674734.5       10695137.      3674941.75       10695092.
      3675013.25       10694918.      3675373.75       10694868.
      3675522.25       10694359.       3675296.5       10694151.
        3675304.       10693415.      3676053.25       10692741.
      3676153.25       10692504.       3676070.5       10692381.
       3676594.5       10692053.       3676740.5       10691577.

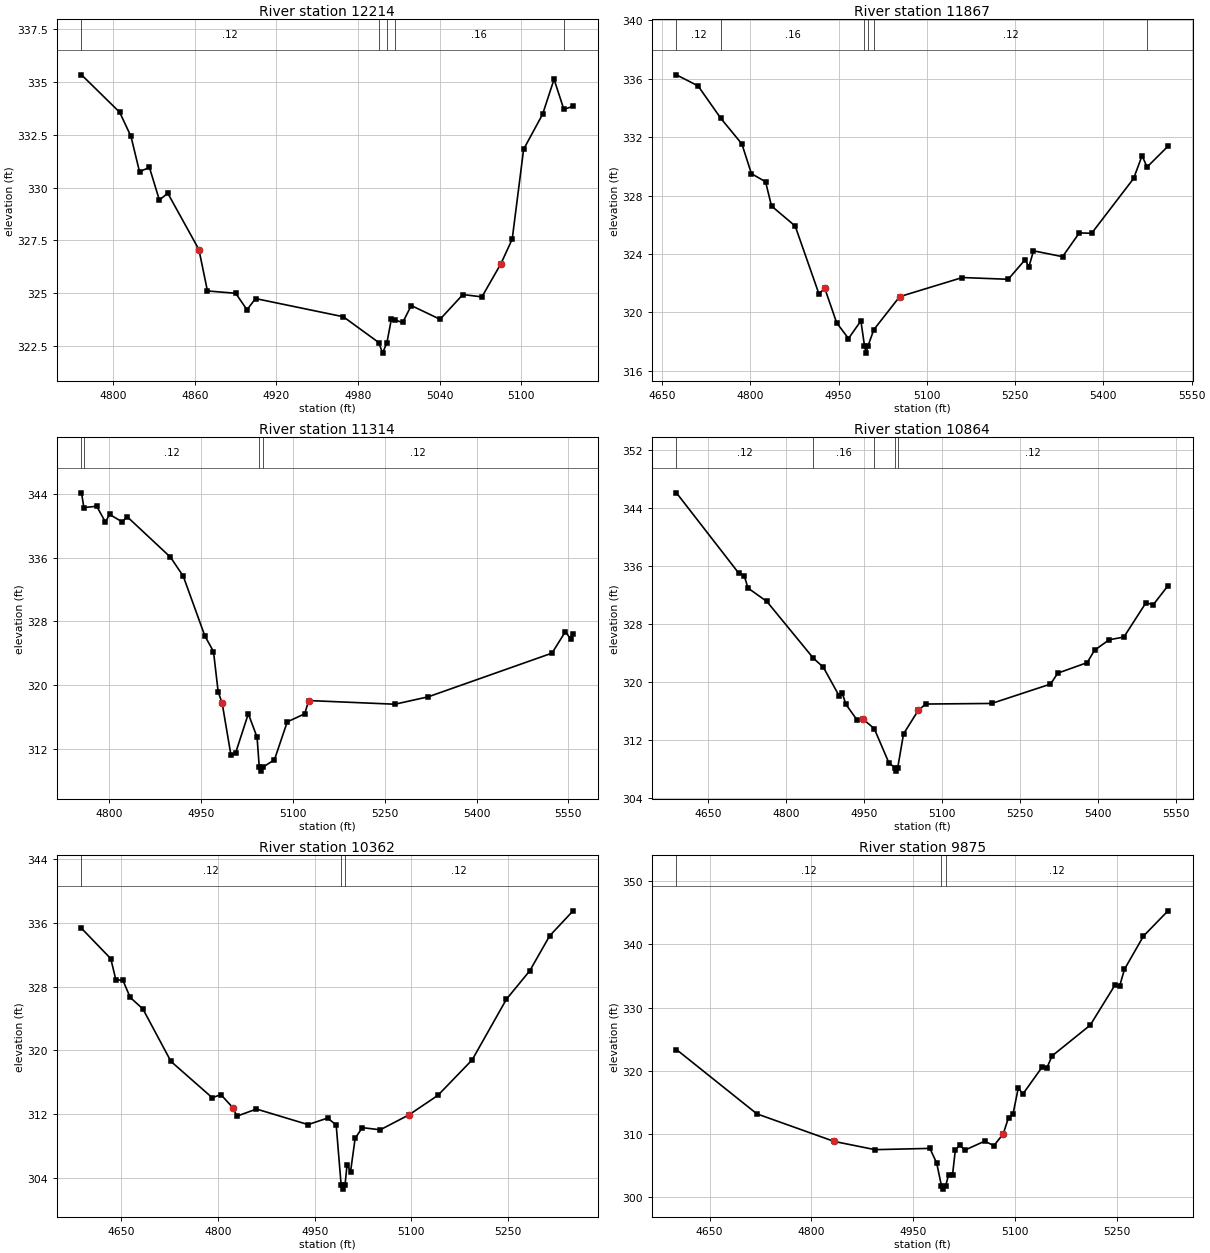
Type RM Length L Ch R = 1 ,12214   ,347,347,347
BEGIN DESCRIPTION:
SHORT BRANCH 24.0
END DESCRIPTION:
XS GIS Cut Line= 3
      3670199.59     10696760.16      3670049.61     10696560.19
      3669949.58     10696510.17
#Sta/Elev= 30
  4776.5  335.33  4804.6  333.56  4812.9  332.42  4819.2  330.75  4826.5  330.95
  4833.8  329.41    4840  329.73  4862.9  327.07  4869.2  325.11    4890     325
  4898.3  324.22  4904.6  324.75  4969.2  323.89  4995.3  322.67  4998.1  322.17
  5001.3  322.67  5004.6  323.79    5007  323.74  5012.9  323.62  5019.2  324.42
  5040.4  323.77  5057.2  324.94  5071.2  324.83  5085.2   326.4  5093.5  327.56
  5101.9  331.81  5115.9  333.47  5124.3  335.12  5131.5   333.7  5138.3  333.84
#Mann= 5 ,-1 , 0
  4776.5     .12       0  4995.3     .07       0  5001.3     .12       0
    5007     .16       0  5131.5     .05       0
Bank Sta=4862.9,5085.2
XS Rating Curve= 0 ,0
Exp/Cntr=0.3,0.1

Type RM Length L Ch R = 1 ,11867   ,553,553,553
BEGIN DESCRIPTION:
SHORT BRANCH 23.0
END DESCRIPTION:
XS GIS Cut Line= 3
      3670408.78      10696760.8      3670367.12     10696385.85
      3670018.17     10696088.98
#Sta/Elev= 30
  4674.4  336.27  4711.2  335.51    4750  333.28  4785.7  331.53  4801.8   329.5
  4825.9  328.94    4836  327.28  4876.2  325.91  4916.5  321.27  4926.6  321.63
  4946.7  319.28  4966.8   318.2  4987.9  319.41    4994   317.7  4996.7   317.2
    5000   317.7  5009.9  318.81  5053.8  321.07  5160.3  322.38  5238.3  322.26
  5266.9   323.6  5273.4  323.11  5281.2  324.21  5330.6  323.81  5359.1  325.44
    5380  325.41  5451.4  329.17  5465.7  330.73  5474.2  329.95  5509.8  331.38
#Mann= 6 ,-1 , 0
  4674.4     .12       0    4750     .16       0    4994     .07       0
    5000     .16       0  5009.9     .12       0  5474.2     .16       0
Bank Sta=4926.6,5053.8
XS Rating Curve= 0 ,0
Exp/Cntr=0.3,0.1

Type RM Length L Ch R = 1 ,11314   ,450,450,450
BEGIN DESCRIPTION:
SHORT BRANCH 22.0
END DESCRIPTION:
XS GIS Cut Line= 3
      3670934.82     10696479.59      3670679.62     10696187.93
      3670534.21     10695798.44
#Sta/Elev= 30
  4754.4  344.14  4758.3  342.29  4779.3  342.45  4793.5  340.46  4800.2  341.43
  4821.1  340.48  4828.7  341.16  4899.8  336.05  4920.7  333.66  4955.9  326.17
  4970.1  324.19  4977.7  319.15  4984.3  317.68  4998.6  311.17  5006.1  311.41
    5027  316.37  5041.3  313.42  5044.9  309.66  5047.7  309.16  5050.9  309.66
  5069.7  310.59  5090.6  315.35  5119.1  316.36  5125.7  318.03  5266.5  317.57
    5321   318.5  5523.2  323.99  5545.2   326.7  5553.5  325.77  5557.7  326.42
#Mann= 4 ,-1 , 0
  4754.4     .16       0  4758.3     .12       0  5044.9     .07       0
  5050.9     .12       0
Bank Sta=4984.3,5125.7
XS Rating Curve= 0 ,0
Exp/Cntr=0.3,0.1

Type RM Length L Ch R = 1 ,10864   ,502,502,502
BEGIN DESCRIPTION:
SHORT BRANCH 21.0
END DESCRIPTION:
XS GIS Cut Line= 3
       3671149.6     10696310.17      3670999.61     10695960.19
      3670599.58     10695560.15
#Sta/Elev= 30
  4588.5  346.06  4708.2  335.01    4719  334.64  4726.3  332.93  4762.6  331.08
  4852.3  323.25  4871.4  322.01  4902.2  318.02  4907.6  318.47  4914.9  316.89
  4936.6  314.71  4947.5  314.88  4969.4  313.55  4997.6  308.83  5008.7  308.19
  5011.4  307.69  5014.7  308.19  5025.8  312.83  5054.1  316.06  5068.3  316.94
  5195.5  317.02  5308.7  319.69  5322.8   321.2  5379.4  322.65  5393.5  324.36
  5421.8   325.8  5450.1  326.18  5492.5   330.9  5506.7  330.64    5535  333.26
#Mann= 5 ,-1 , 0
  4588.5     .12       0  4852.3     .16       0  4969.4     .12       0
  5008.7     .07       0  5014.7     .12       0
Bank Sta=4947.5,5054.1
XS Rating Curve= 0 ,0
Exp/Cntr=0.3,0.1

Type RM Length L Ch R = 1 ,10362   ,487,487,487
BEGIN DESCRIPTION:
SHORT BRANCH 20.0
END DESCRIPTION:
XS GIS Cut Line= 3
       3671449.6     10696060.16      3671299.61     10695660.19
       3671149.6     10695360.17
#Sta/Elev= 30
  4588.3  335.29  4633.7  331.49  4641.7  328.81  4652.4   328.8  4663.9  326.63
  4683.5   325.2  4727.1  318.62  4791.2  314.07  4804.5  314.47  4823.2  312.82
  4829.5  311.77  4859.7  312.66  4939.8  310.71  4970.1  311.53  4983.4  310.66
  4991.1  303.13  4993.9  302.63  4997.1  303.13  5000.3  305.71  5005.7  304.82
  5012.8  308.99  5023.9  310.33  5051.8  310.06  5096.5  311.94  5141.3  314.38
  5194.4  318.82  5247.5  326.41  5283.8  329.98  5314.5  334.34  5350.9  337.48
#Mann= 3 ,-1 , 0
  4588.3     .12       0  4991.1     .07       0  4997.1     .12       0
Bank Sta=4823.2,5096.5
XS Rating Curve= 0 ,0
Exp/Cntr=0.3,0.1

Type RM Length L Ch R = 1 ,9875    ,510,510,510
BEGIN DESCRIPTION:
SHORT BRANCH 19.0
END DESCRIPTION:
XS GIS Cut Line= 3
      3671649.61     10695910.18      3671699.61     10695510.19
      3671899.64     10695260.15
#Sta/Elev= 30
  4601.3  323.39  4719.7  313.22  4833.1  308.87  4893.5  307.56  4974.2  307.76
  4984.2  305.46  4991.3  301.82  4994.1  301.32  4997.3  301.82  5001.9  303.62
  5007.6  303.62  5011.6  307.44    5018  308.27    5026   307.5  5054.8   308.9
  5068.4   308.2    5082  310.02    5090  312.64  5096.4  313.13  5104.4  317.36
  5110.9  316.33  5139.7  320.66  5146.1  320.43  5154.1  322.39  5210.1  327.24
  5246.9  333.64  5253.3  333.37  5260.5  336.07  5288.5  341.33  5324.6  345.32
#Mann= 3 ,-1 , 0
  4601.3     .12       0  4991.3     .07       0  4997.3     .12       0
Bank Sta=4833.1,5082
XS Rating Curve= 0 ,0
Exp/Cntr=0.3,0.1

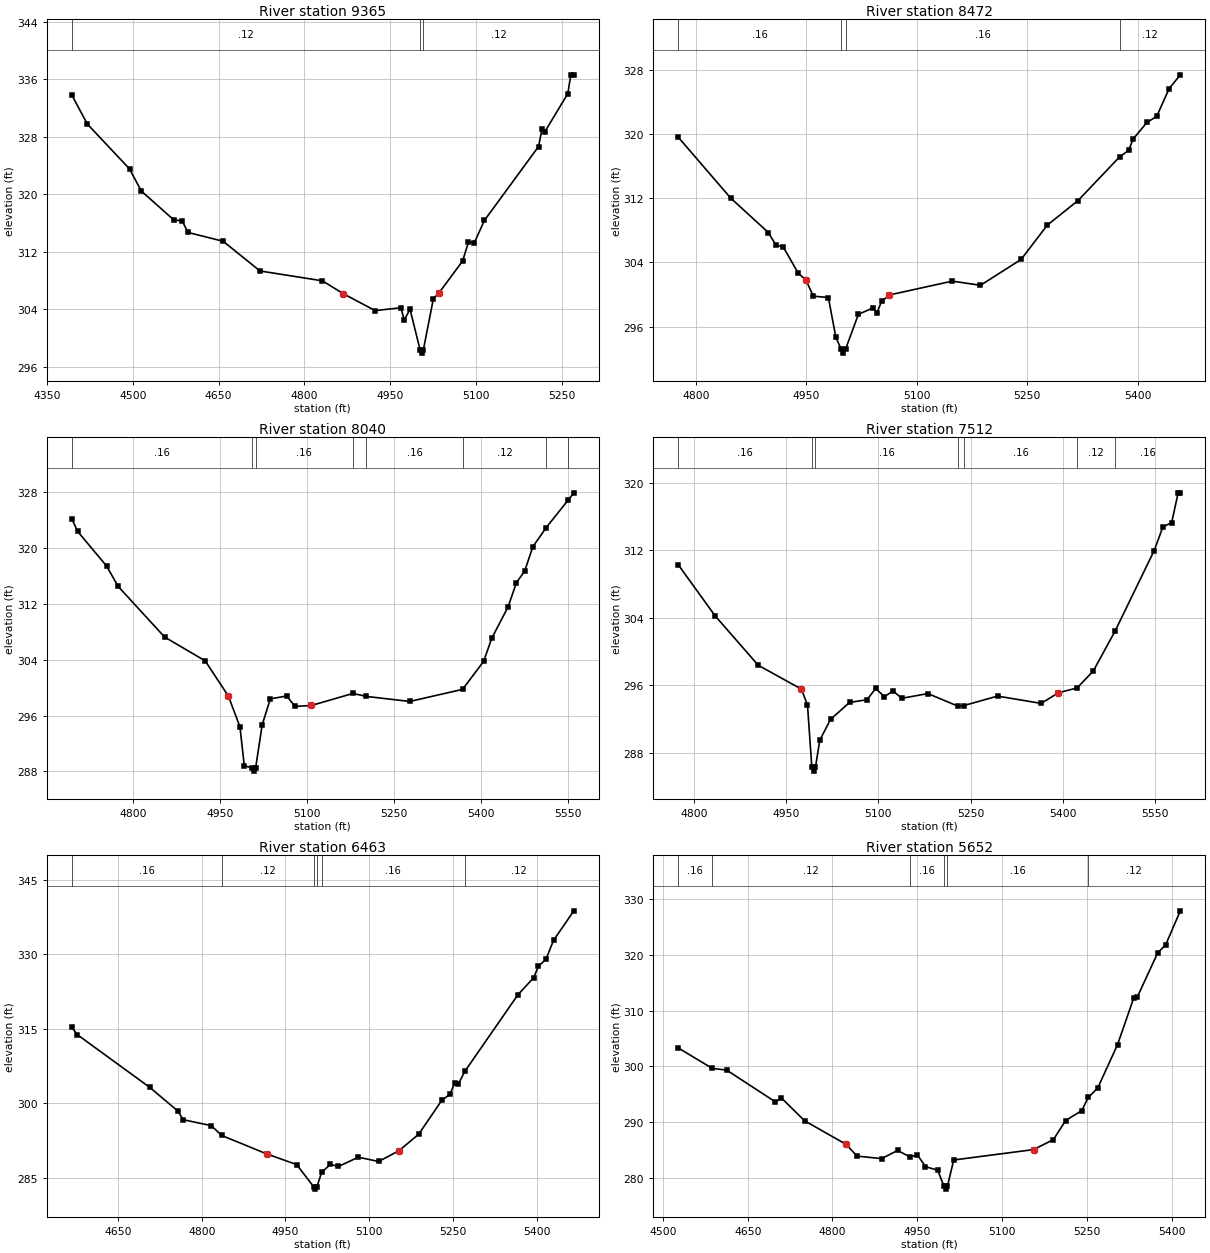
Type RM Length L Ch R = 1 ,9365    ,893,893,893
BEGIN DESCRIPTION:
SHORT BRANCH 18.0
END DESCRIPTION:
XS GIS Cut Line= 2
      3672028.57     10696219.22      3672205.67     10695359.77
#Sta/Elev= 30
  4393.3   333.8  4420.5  329.76  4494.4  323.51  4514.8  320.45  4571.4  316.45
  4586.3  316.29  4596.5  314.69  4657.8  313.47  4722.3  309.34  4831.3  307.97
  4868.1  306.17  4923.5  303.83  4968.7  304.23  4974.3  302.52  4984.5  304.02
  5001.9  298.42  5004.7  297.92  5007.9  298.42  5025.3  305.48  5035.5  306.33
  5076.4  310.73  5086.6  313.34  5096.8  313.25  5114.5  316.37  5209.1  326.63
  5215.1  329.05  5220.2   328.7  5260.2  333.98  5265.4  336.54  5270.8   336.6
#Mann= 3 ,-1 , 0
  4393.3     .12       0  5001.9     .07       0  5007.9     .12       0
Bank Sta=4868.1,5035.5
XS Rating Curve= 0 ,0
Exp/Cntr=0.3,0.1

Type RM Length L Ch R = 1 ,8472    ,432,432,432
BEGIN DESCRIPTION:
SHORT BRANCH 16.0
END DESCRIPTION:
XS GIS Cut Line= 3
      3672649.61      10696210.2      3672699.61     10695960.19
       3672549.6     10695560.16
#Sta/Elev= 30
  4775.9  319.58  4847.3  311.99  4898.3  307.72  4908.5  306.17  4918.7   305.9
  4939.1  302.64  4949.3  301.82  4959.5   299.8  4979.9  299.63  4990.1  294.66
  4997.3  293.21    5000  292.71  5003.3  293.21  5020.7  297.54  5040.7  298.34
    5046  297.75  5052.2  299.15  5062.9  299.95  5148.3  301.67  5186.6  301.15
  5241.8  304.37  5277.4  308.64  5319.2   311.7  5375.6  317.13  5387.8  317.93
    5394  319.35  5412.7  321.41    5426  322.17  5442.9  325.62  5458.1  327.34
#Mann= 4 ,-1 , 0
  4775.9     .16       0  4997.3     .07       0  5003.3     .16       0
  5375.6     .12       0
Bank Sta=4949.3,5062.9
XS Rating Curve= 0 ,0
Exp/Cntr=0.3,0.1

Type RM Length L Ch R = 1 ,8040    ,528,528,528
BEGIN DESCRIPTION:
SHORT BRANCH 15.0
END DESCRIPTION:
XS GIS Cut Line= 3
      3673049.61     10696260.16      3673049.61     10695960.19
      3672649.58     10695560.16
#Sta/Elev= 30
  4694.9  324.23  4704.9  322.42  4754.9  317.45  4774.9  314.52  4854.9  307.27
  4924.9  303.85  4964.9   298.8  4984.9  294.39  4992.4  288.77    5006  288.54
  5008.8  288.04    5012  288.54  5023.2  294.68  5037.3   298.4  5065.6  298.81
  5079.7  297.32    5108  297.45  5179.8  299.18  5202.9  298.75  5277.7  298.03
  5368.7  299.76    5405  303.77  5419.1  307.09  5447.4  311.63  5461.6  315.07
  5475.7   316.7  5489.9  320.21    5513  322.96  5550.7  326.89  5560.6  327.94
#Mann= 8 ,-1 , 0
  4694.9     .16       0    5006     .07       0    5012     .16       0
  5179.8     .12       0  5202.9     .16       0  5368.7     .12       0
    5513     .16       0  5550.7     .12       0
Bank Sta=4964.9,5108
XS Rating Curve= 0 ,0
Exp/Cntr=0.3,0.1

Type RM Length L Ch R = 1 ,7512    ,1049,1049,1049
BEGIN DESCRIPTION:
SHORT BRANCH 14.0
END DESCRIPTION:
XS GIS Cut Line= 3
      3673499.61     10696110.23      3673499.61     10695860.19
      3673099.63     10695460.21
#Sta/Elev= 30
  4774.8  310.27  4834.8  304.21  4904.8  298.37  4974.8  295.55  4984.8  293.68
  4991.8  286.34  4994.6  285.84  4997.8  286.34  5004.8   289.5  5022.3  291.97
  5053.1  293.97  5081.4  294.29  5095.6  295.62  5109.7  294.65  5123.8  295.33
    5138  294.46  5180.4  295.02  5228.8  293.54  5238.9   293.6  5293.5  294.72
  5364.3  293.86  5392.5  295.11  5422.9  295.69  5449.1  297.69  5484.2  302.37
  5548.1  311.95  5562.2  314.75  5576.4  315.25    5587  318.78  5590.5  318.78
#Mann= 7 ,-1 , 0
  4774.8     .16       0  4991.8     .07       0  4997.8     .16       0
  5228.8     .12       0  5238.9     .16       0  5422.9     .12       0
  5484.2     .16       0
Bank Sta=4974.8,5392.5
XS Rating Curve= 0 ,0
Exp/Cntr=0.3,0.1

Type RM Length L Ch R = 1 ,6463    ,811,811,811
BEGIN DESCRIPTION:
SHORT BRANCH 12.0
END DESCRIPTION:
XS GIS Cut Line= 3
      3674199.61     10696060.21      3674199.61     10695660.19
      3673899.62      10695260.2
#Sta/Elev= 30
  4566.9  315.31  4576.9  313.81  4706.9   303.2  4756.9  298.48  4766.9  296.71
  4816.9  295.53  4835.6  293.55  4916.9  289.82    4970   287.7  5000.4  283.26
  5003.1  282.76  5006.4  283.26  5014.9  286.15  5030.5  287.74    5045  287.31
  5080.5  289.18  5116.9  288.32  5153.4  290.48  5188.8  293.81  5230.5  300.66
    5245  301.83  5253.4  304.18  5259.6  303.84  5271.6  306.46  5366.9  321.88
    5395  325.29  5403.4  327.57  5416.9  328.98  5430.5  332.79  5466.9  338.72
#Mann= 6 ,-1 , 0
  4566.9     .16       0  4835.6     .12       0  5000.4     .07       0
  5006.4     .12       0  5014.9     .16       0  5271.6     .12       0
Bank Sta=4916.9,5153.4
XS Rating Curve= 0 ,0
Exp/Cntr=0.3,0.1

Type RM Length L Ch R = 1 ,5652    ,696,696,696
BEGIN DESCRIPTION:
SHORT BRANCH 10.0
END DESCRIPTION:
XS GIS Cut Line= 3
      3674846.28     10695786.88      3674762.95     10695463.97
      3674389.16     10695053.84
#Sta/Elev= 30
  4527.1  303.31  4587.6  299.64  4612.7  299.35  4699.2  293.65  4709.6  294.37
  4750.9  290.27  4823.2  286.12  4843.8  283.96  4886.9  283.52  4915.3  284.98
    4937  283.82  4950.4  284.18  4964.6  282.08  4986.2  281.44  4997.4  278.56
  5000.2  278.06  5003.4  278.56  5014.5  283.27  5155.8  285.13    5191  286.92
  5212.6  290.33  5240.9  292.08  5252.8  294.47  5269.3  296.13  5304.5  303.92
  5332.8  312.17  5339.6  312.46  5375.4  320.29  5389.6  321.75  5415.5  327.83
#Mann= 6 ,-1 , 0
  4527.1     .16       0  4587.6     .12       0    4937     .16       0
  4997.4     .07       0  5003.4     .16       0  5252.8     .12       0
Bank Sta=4823.2,5155.8
XS Rating Curve= 0 ,0
Exp/Cntr=0.3,0.1

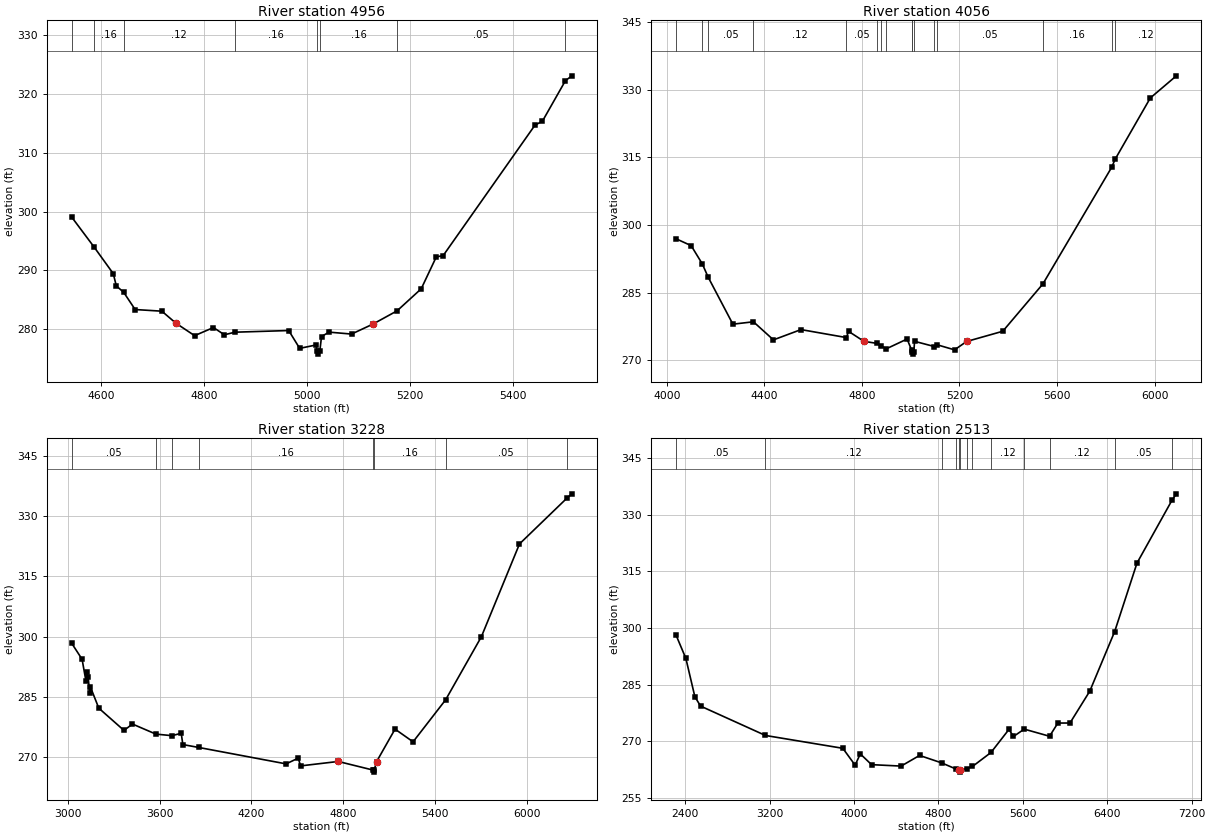
Type RM Length L Ch R = 1 ,4956    ,900,900,900
BEGIN DESCRIPTION:
SHORT BRANCH 9.0
END DESCRIPTION:
XS GIS Cut Line= 3
      3675249.63     10695310.23      3674999.61     10694910.19
      3674599.64     10694610.21
#Sta/Elev= 30
  4542.8  299.07  4586.3  293.98  4623.6  289.45  4629.5  287.37  4643.8  286.28
  4666.1  283.35    4718  283.07  4745.1  281.04  4781.6  278.91  4818.2  280.29
  4839.4  279.06    4860   279.5  4964.4  279.78  4985.7  276.75  5017.7  277.33
  5018.8  276.27  5021.6  275.77  5024.8  276.27  5028.1  278.76  5042.7  279.51
  5086.4  279.18  5128.1  280.88  5174.9  283.13  5221.8  286.88    5251  292.29
  5264.5  292.53  5442.7  314.69  5457.3  315.38    5502  322.27  5514.5  323.08
#Mann= 8 ,-1 , 0
  4542.8     .05       0  4586.3     .16       0  4643.8     .12       0
    4860     .16       0  5018.8     .07       0  5024.8     .16       0
  5174.9     .05       0    5502     .12       0
Bank Sta=4745.1,5128.1
XS Rating Curve= 0 ,0
Exp/Cntr=0.3,0.1

Type RM Length L Ch R = 1 ,4056    ,828,828,828
BEGIN DESCRIPTION:
Mapping XS 01118a91
END DESCRIPTION:
XS GIS Cut Line= 4
      3675301.95     10695308.71       3675572.8     10694496.17
      3675190.85     10694350.34      3674435.05     10694565.29
#Sta/Elev= 30
  4038.1  296.91  4099.8  295.39  4145.7  291.32  4169.2  288.43  4270.8  277.98
  4355.1  278.51  4437.1   274.5  4550.1  276.78  4736.4  275.01  4745.1  276.39
  4808.4  274.17  4859.9  273.74  4877.6  273.21  4899.6  272.51  4985.2  274.69
    5004  272.19  5006.9  271.84  5009.7  271.34  5012.9  271.84  5015.7  274.18
  5096.5  273.03  5108.4  273.41  5179.7  272.29  5229.1  274.14  5377.5  276.41
  5541.9   286.9  5823.8  312.74  5838.3  314.56  5982.4  328.13  6089.2  333.04
#Mann= 16 ,-1 , 0
  4038.1     .05       0  4145.7     .16       0  4169.2     .05       0
  4355.1     .12       0  4736.4     .05       0  4859.9      .1       0
  4877.6     .12       0  4899.6      .1       0    5004     .12       0
  5006.9     .07       0  5012.9     .12       0  5096.5     .08       0
  5108.4     .05       0  5541.9     .16       0  5823.8     .05       0
  5838.3     .12       0
Bank Sta=4808.4,5229.1
XS Rating Curve= 0 ,0
Exp/Cntr=0.3,0.1

Type RM Length L Ch R = 1 ,3228    ,715,715,715
BEGIN DESCRIPTION:
SHORT BRANCH 1.8
END DESCRIPTION:
XS GIS Cut Line= 6
      3675340.87     10695320.77      3675445.62     10695049.01
      3675747.12      10694002.2      3675609.39     10693778.83
      3675051.96      10693829.5      3674239.46     10694523.95
#Sta/Elev= 30
  3024.9  298.38    3093   294.4  3117.7   289.1    3123  291.35  3132.7  289.97
  3142.3  286.13  3147.6   287.5  3202.2  282.25    3367  276.72  3422.5   278.3
  3575.7   275.8  3680.8  275.41  3741.2  276.01    3752   273.2  3855.9  272.48
  4427.4   268.4  4506.6  269.83    4522   267.9  4768.1     269    4997  266.85
  4999.8  266.35    5003  266.85  5019.2  268.97  5139.7  277.04  5257.7  273.88
  5470.7  284.33  5704.5  300.01  5953.7  323.07  6263.4  334.43  6296.5  335.52
#Mann= 8 ,-1 , 0
  3024.9     .05       0  3575.7     .12       0  3680.8     .05       0
  3855.9     .16       0    4997     .07       0    5003     .16       0
  5470.7     .05       0  6263.4     .12       0
Bank Sta=4768.1,5019.2
XS Rating Curve= 0 ,0
Exp/Cntr=0.3,0.1

Type RM Length L Ch R = 1 ,2513    ,0,0,0
BEGIN DESCRIPTION:
SHORT BRANCH 1.0
END DESCRIPTION:
XS GIS Cut Line= 4
      3675365.61      10695326.8      3676080.45     10693398.04
      3675170.73     10693078.59      3674239.49     10694523.91
#Sta/Elev= 30
    2314  298.05  2406.4  291.92  2491.7  281.77  2545.8  279.29  3160.7  271.51
  3893.9  268.11  4010.1  263.65  4059.4  266.63  4166.1  263.78  4446.1   263.4
    4621  266.22    4830  264.25  4965.7  262.63    4997   262.3  4999.8   261.8
    5003   262.3  5069.2  262.74  5122.3   263.3  5297.8     267  5467.9  273.11
  5511.1  271.25  5613.1  273.19  5852.8   271.3  5931.6   274.8  6046.5  274.81
  6233.9  283.24  6470.1  299.05  6681.5  317.18  7013.3  333.83  7054.5  335.52
#Mann= 13 ,-1 , 0
    2314     .05       0  3160.7     .12       0    4830     .16       0
  4965.7     .05       0    4997    .033       0    5003     .05       0
  5069.2     .07       0  5122.3     .05       0  5297.8     .12       0
  5613.1     .05       0  5852.8     .12       0  6470.1     .05       0
  7013.3     .12       0
Bank Sta=4997,5003
XS Rating Curve= 0 ,0
Exp/Cntr=0.3,0.1

Chan Stop Cuts=-1
Use User Specified Reach Order=0
Composite Channel Slope=5