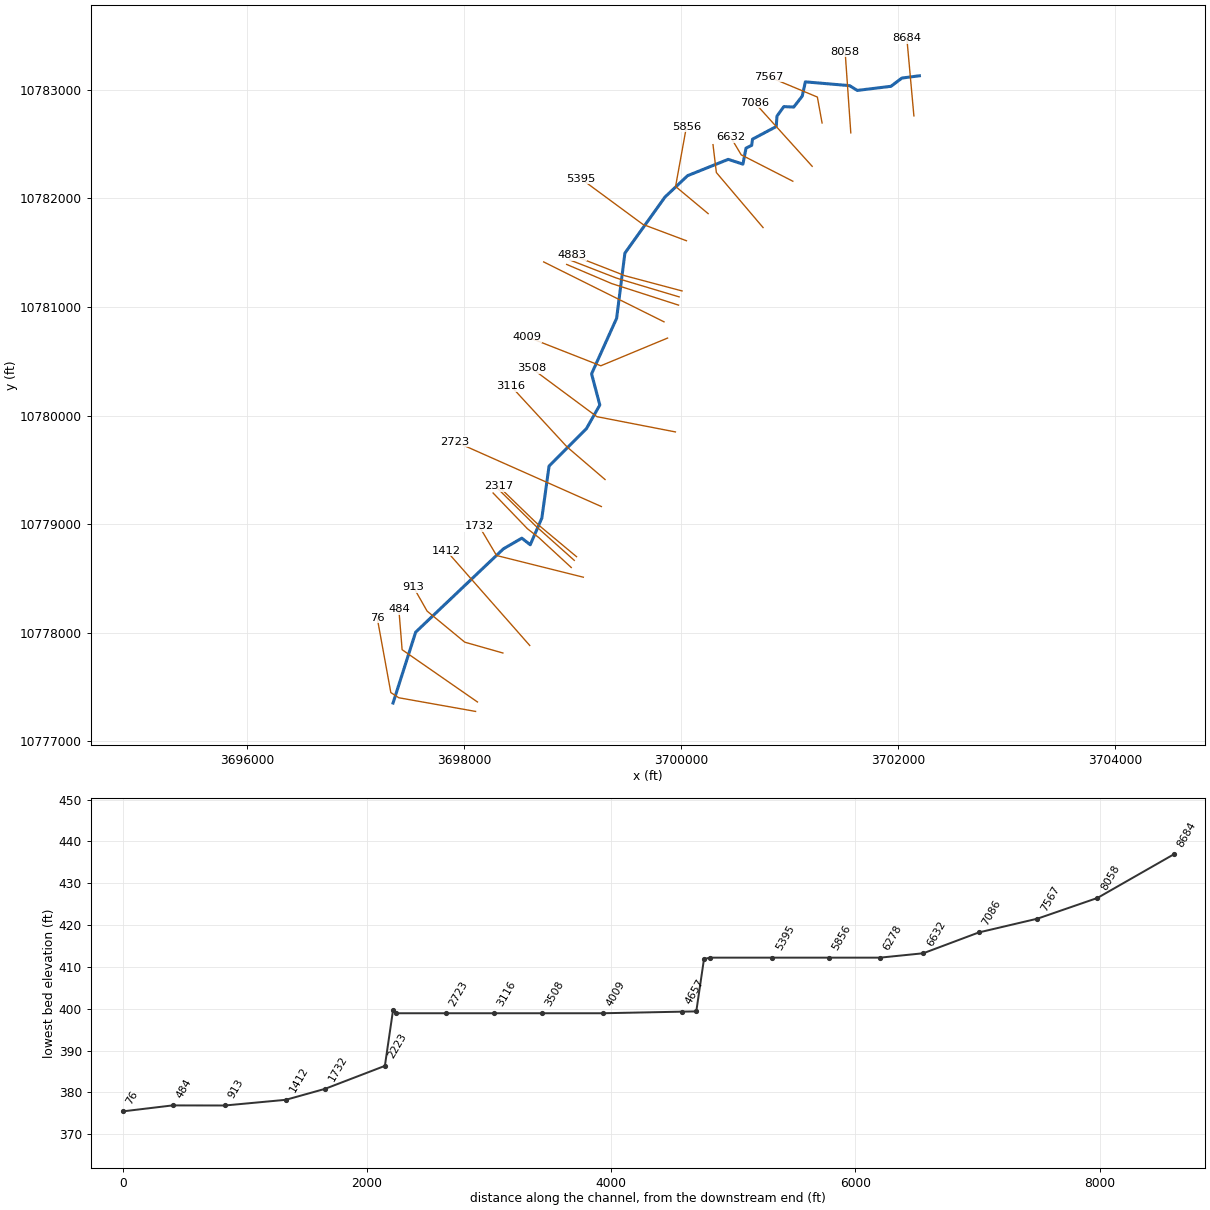
--- SOUTH NICHOLS LAKE.prj (project) ---

Proj Title=SOUTH NICHOLS LAKE Base Level Engineering
Current Plan=p01
Default Exp/Contr=0.3,0.1
English Units
Geom File=g01
Flow File=f01
Plan File=p01
BEGIN DESCRIPTION:
SOUTH NICHOLS LAKE
END DESCRIPTION:

--- SOUTH NICHOLS LAKE.p01 (plan) ---

Plan Title=Multiple Run
Short Identifier=Multiple
Geom File=g01
Flow File=f01
Subcritical Flow
K Sum by GR= 0
Std Step Tol= 0.01
Critical Tol= 0.01
Num of Std Step Trials= 20
Max Error Tol= 0.3
Flow Tol Ratio= 0.001
Split Flow NTrial= 30
Split Flow Tol= 0.02
Split Flow Ratio= 0.02
Log Output Level= 0
Friction Slope Method= 1
Unsteady Friction Slope Method= 2
Unsteady Bridges Friction Slope Method= 1
Parabolic Critical Depth
Global Vel Dist=  1 , 1 , 1
Global Log Level= 0
CheckData=True
Encroach Param= -1, 0, 0, 0
BEGIN DESCRIPTION:
Multiple Run
END DESCRIPTION:

--- SOUTH NICHOLS LAKE.f01 (steady flow) ---

Flow Title=Multiple
Number of Profiles=7
Profile Names=10-year,25-year,50-year,1pct_min,100-year,1pct_plu,500-year
River Rch & RM= SOUTH NICHOLS LA,Reach-1,8684
     339     445     530     464     628     849     881
River Rch & RM= SOUTH NICHOLS LA,Reach-1,5395
    1371    1936    2418    2209    2988    4041    4576
River Rch & RM= SOUTH NICHOLS LA,Reach-1,3508
    1482    2099    2626    2404    3251    4396    4996
Boundary for River Rch & Prof#=SOUTH NICHOLS LA,Reach-1,1
Up Type=0
Dn Type=3
Dn Slope=0.005
Boundary for River Rch & Prof#=SOUTH NICHOLS LA,Reach-1,2
Up Type=0
Dn Type=3
Dn Slope=0.005
Boundary for River Rch & Prof#=SOUTH NICHOLS LA,Reach-1,3
Up Type=0
Dn Type=3
Dn Slope=0.005
Boundary for River Rch & Prof#=SOUTH NICHOLS LA,Reach-1,4
Up Type=0
Dn Type=3
Dn Slope=0.005
Boundary for River Rch & Prof#=SOUTH NICHOLS LA,Reach-1,5
Up Type=0
Dn Type=3
Dn Slope=0.005
Boundary for River Rch & Prof#=SOUTH NICHOLS LA,Reach-1,6
Up Type=0
Dn Type=3
Dn Slope=0.005
Boundary for River Rch & Prof#=SOUTH NICHOLS LA,Reach-1,7
Up Type=0
Dn Type=3
Dn Slope=0.005

--- SOUTH NICHOLS LAKE.g01 (geometry) ---

Geom Title=Existing Conditions

River Reach=SOUTH NICHOLS LA,Reach-1
Reach XY= 30
      3702196.78     10783129.85      3702035.50     10783109.00
      3701934.75     10783033.00      3701624.50     10782995.00
      3701553.75     10783039.00      3701145.75     10783074.00
      3701116.75     10782942.00      3701038.75     10782842.00
      3700947.50     10782846.00      3700884.00     10782758.00
      3700877.25     10782662.00      3700658.75     10782546.00
      3700651.00     10782489.00      3700598.75     10782463.00
      3700570.25     10782316.00      3700435.00     10782360.00
      3700060.75     10782210.00      3699851.21     10782011.79
      3699482.50     10781496.00      3699406.25     10780896.00
      3699175.25     10780384.00      3699251.50     10780097.00
      3699127.25     10779878.00      3698783.50     10779534.00
      3698717.00     10779055.00      3698610.00     10778809.00
      3698532.50     10778870.00      3698363.25     10778772.00
      3697554.00     10778004.00      3697345.50     10777351.00

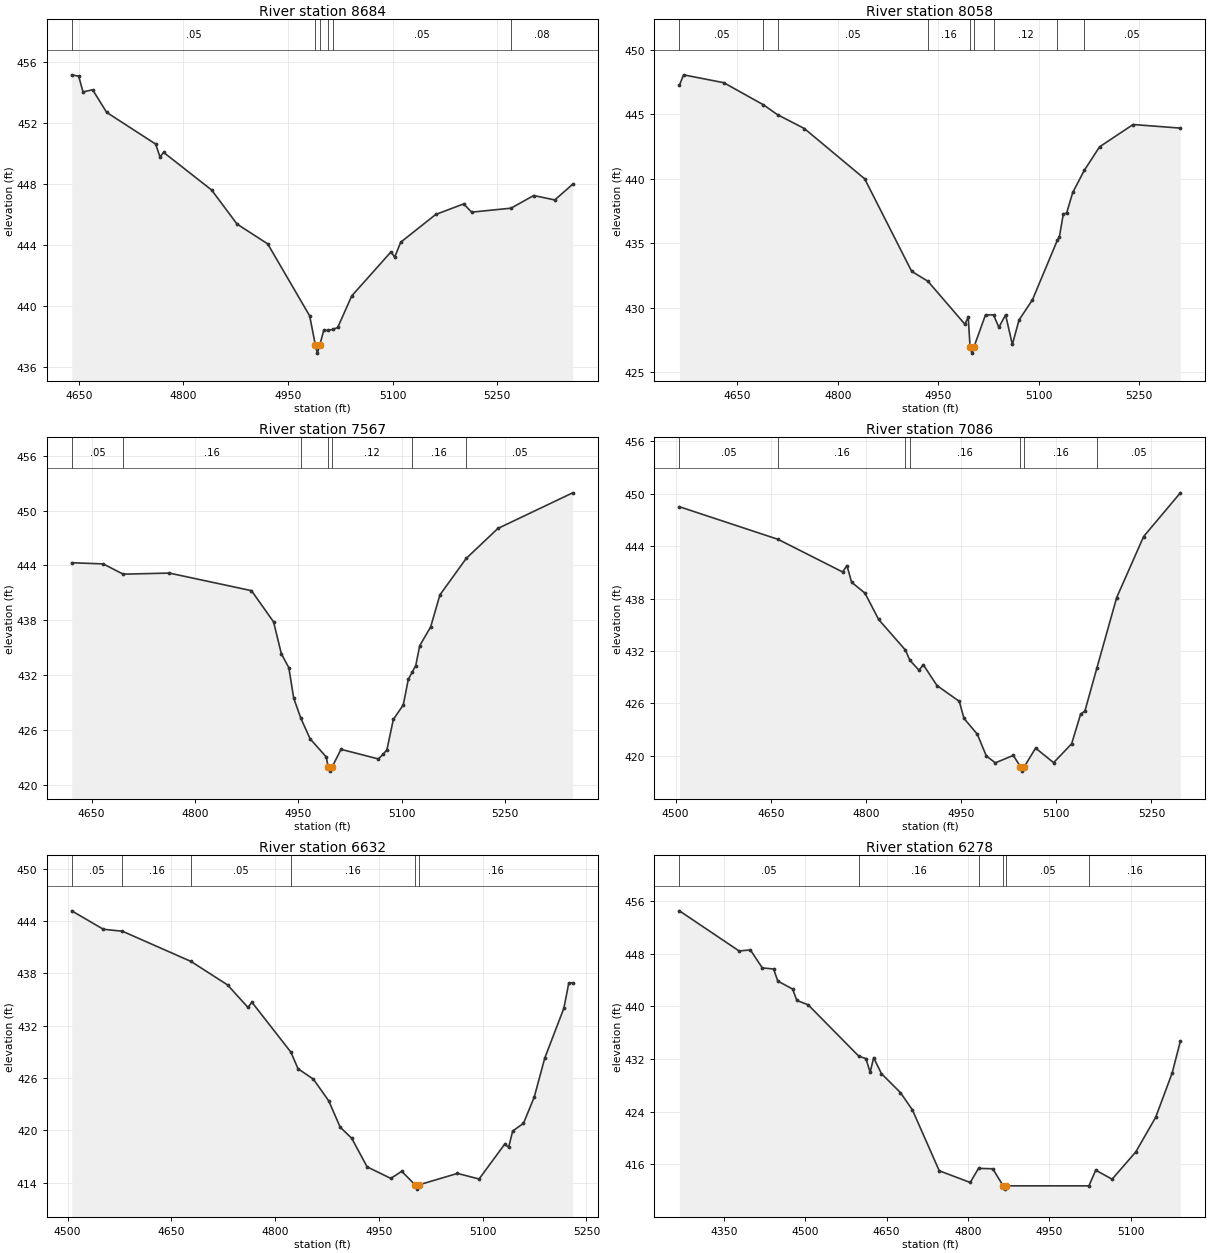
Type RM Length L Ch R = 1,8684,626,626,626
BEGIN DESCRIPTION:
SOUTH NICHOLS LAKE 19.0
END DESCRIPTION:
XS GIS Cut Line= 2
      3702146.19     10782760.27      3702081.14     10783475.82
#Sta/Elev= 30
  4639.7  455.18  4649.7  455.09  4655.9  454.06  4669.7  454.20  4689.8  452.72
  4760.1  450.64  4766.4  449.79  4771.4  450.10  4840.4  447.63  4876.8  445.40
  4920.8  444.10  4981.0  439.38  4989.3  437.44  4992.0  436.94  4995.3  437.44
  5001.1  438.43  5007.7  438.44  5014.0  438.49  5021.2  438.62  5041.3  440.69
  5097.7  443.58  5102.8  443.23  5111.6  444.21  5161.8  446.03  5201.9  446.72
  5213.2  446.18  5269.8  446.44  5302.3  447.27  5332.5  446.98  5358.2  448.01
#Mann=6,-1,0
  4639.7    0.05       0  4989.3    0.03       0  4995.3    0.05       0
  5007.7    0.12       0  5014.0    0.05       0  5269.8    0.08       0
Bank Sta=4989.3,4995.3
Exp/Cntr=0.3,0.1

Type RM Length L Ch R = 1,8058,491,491,491
BEGIN DESCRIPTION:
SOUTH NICHOLS LAKE 18.0
END DESCRIPTION:
XS GIS Cut Line= 2
      3701564.59     10782604.04      3701512.50     10783350.62
#Sta/Elev= 30
  4563.3  447.25  4569.5  448.07  4629.6  447.46  4688.7  445.75  4709.9  444.98
  4749.9  443.91  4840.1  440.01  4910.3  432.84  4934.6  432.07  4989.8  428.74
  4994.8  429.29  4997.5  427.00  5000.3  426.50  5003.5  427.00  5020.6  429.47
  5032.6  429.46  5040.6  428.50  5050.6  429.47  5060.7  427.17  5070.7  429.07
  5090.7  430.63  5128.0  435.26  5130.8  435.47  5136.8  437.28  5141.8  437.36
  5150.9  438.95  5168.1  440.66  5191.0  442.49  5241.1  444.22  5311.7  443.94
#Mann=9,-1,0
  4563.3    0.05       0  4688.7    0.16       0  4709.9    0.05       0
  4934.6    0.16       0  4997.5    0.07       0  5003.5    0.16       0
  5032.6    0.12       0  5128.0    0.16       0  5168.1    0.05       0
Bank Sta=4997.5,5003.5
Exp/Cntr=0.3,0.1

Type RM Length L Ch R = 1,7567,481,481,481
BEGIN DESCRIPTION:
SOUTH NICHOLS LAKE 17.0
END DESCRIPTION:
XS GIS Cut Line= 3
      3701299.84     10782695.15      3701256.43     10782933.91
      3700809.40     10783120.53
#Sta/Elev= 30
  4621.1  444.30  4666.9  444.17  4695.8  443.05  4762.8  443.17  4882.0  441.25
  4914.1  437.84  4925.4  434.35  4936.2  432.85  4943.3  429.52  4953.6  427.33
  4967.1  425.08  4990.4  423.11  4993.3  422.05  4996.1  421.55  4999.3  422.05
  5012.0  423.93  5066.2  422.88  5073.2  423.40  5078.6  423.89  5087.9  427.19
  5102.4  428.79  5109.6  431.57  5115.5  432.39  5120.4  433.07  5126.2  435.24
  5142.1  437.30  5155.5  440.79  5193.7  444.77  5239.6  448.04  5348.2  451.93
#Mann=7,-1,0
  4621.1    0.05       0  4695.8    0.16       0  4953.6    0.12       0
  4993.3    0.07       0  4999.3    0.12       0  5115.5    0.16       0
  5193.7    0.05       0
Bank Sta=4993.3,4999.3
Exp/Cntr=0.3,0.1

Type RM Length L Ch R = 1,7086,454,454,454
BEGIN DESCRIPTION:
SOUTH NICHOLS LAKE 16.0
END DESCRIPTION:
XS GIS Cut Line= 2
      3701208.66     10782295.92      3700679.18     10782881.82
#Sta/Elev= 30
  4506.0  448.52  4661.7  444.78  4763.3  441.05  4770.1  441.78  4777.5  439.87
  4798.5  438.63  4820.1  435.61  4862.4  432.10  4869.3  430.94  4883.7  429.80
  4890.4  430.44  4912.0  428.05  4947.2  426.24  4954.6  424.29  4975.6  422.48
  4989.8  419.99  5004.0  419.20  5032.4  420.05  5043.6  418.75  5046.3  418.25
  5049.6  418.75  5067.5  420.89  5095.9  419.22  5124.3  421.38  5138.5  424.78
  5145.2  425.13  5164.1  430.05  5195.3  438.12  5237.8  445.11  5295.7  450.11
#Mann=7,-1,0
  4506.0    0.05       0  4661.7    0.16       0  4862.4    0.12       0
  4869.3    0.16       0  5043.6    0.07       0  5049.6    0.16       0
  5164.1    0.05       0
Bank Sta=5043.6,5049.6
Exp/Cntr=0.3,0.1

Type RM Length L Ch R = 1,6632,354,354,354
BEGIN DESCRIPTION:
SOUTH NICHOLS LAKE 15.0
END DESCRIPTION:
XS GIS Cut Line= 3
      3701030.28     10782158.61      3700554.60     10782401.66
      3700457.40     10782564.83
#Sta/Elev= 30
  4506.0  445.16  4551.7  443.05  4579.4  442.82  4678.5  439.36  4731.3  436.67
  4760.8  434.09  4766.4  434.70  4822.9  428.96  4833.1  427.07  4855.3  425.88
  4877.5  423.39  4894.1  420.37  4910.7  419.11  4933.0  415.83  4967.2  414.51
  4983.0  415.32  5002.2  413.78  5005.0  413.28  5008.2  413.78  5063.6  415.08
  5094.8  414.44  5131.6  418.41  5137.6  418.09  5143.4  419.94  5159.0  420.82
  5174.6  423.84  5189.8  428.31  5217.4  434.01  5224.5  436.91  5230.1  436.91
#Mann=6,-1,0
  4506.0    0.05       0  4579.4    0.16       0  4678.5    0.05       0
  4822.9    0.16       0  5002.2    0.07       0  5008.2    0.16       0
Bank Sta=5002.2,5008.2
Exp/Cntr=0.3,0.1

Type RM Length L Ch R = 1,6278,422,422,422
BEGIN DESCRIPTION:
SOUTH NICHOLS LAKE 14.0
END DESCRIPTION:
XS GIS Cut Line= 3
      3700755.99     10781731.53      3700325.43     10782238.47
      3700294.62     10782495.22
#Sta/Elev= 30
  4267.8  454.49  4377.8  448.40  4398.7  448.55  4420.7  445.82  4441.5  445.66
  4449.2  443.83  4476.6  442.61  4484.4  440.88  4505.2  440.22  4598.7  432.41
  4611.7  432.05  4619.5  429.98  4626.0  432.19  4640.3  429.77  4675.4  426.89
  4697.5  424.25  4746.9  415.02  4804.0  413.24  4819.3  415.38  4845.7  415.32
  4864.7  412.73  4867.4  412.23  4870.7  412.73  5022.9  412.73  5035.4  415.11
  5065.6  413.74  5109.3  417.88  5146.1  423.16  5176.4  429.87  5191.5  434.70
#Mann=6,-1,0
  4267.8    0.05       0  4598.7    0.16       0  4819.3    0.05       0
  4864.7   0.033       0  4870.7    0.05       0  5022.9    0.16       0
Bank Sta=4864.7,4870.7
Exp/Cntr=0.3,0.1

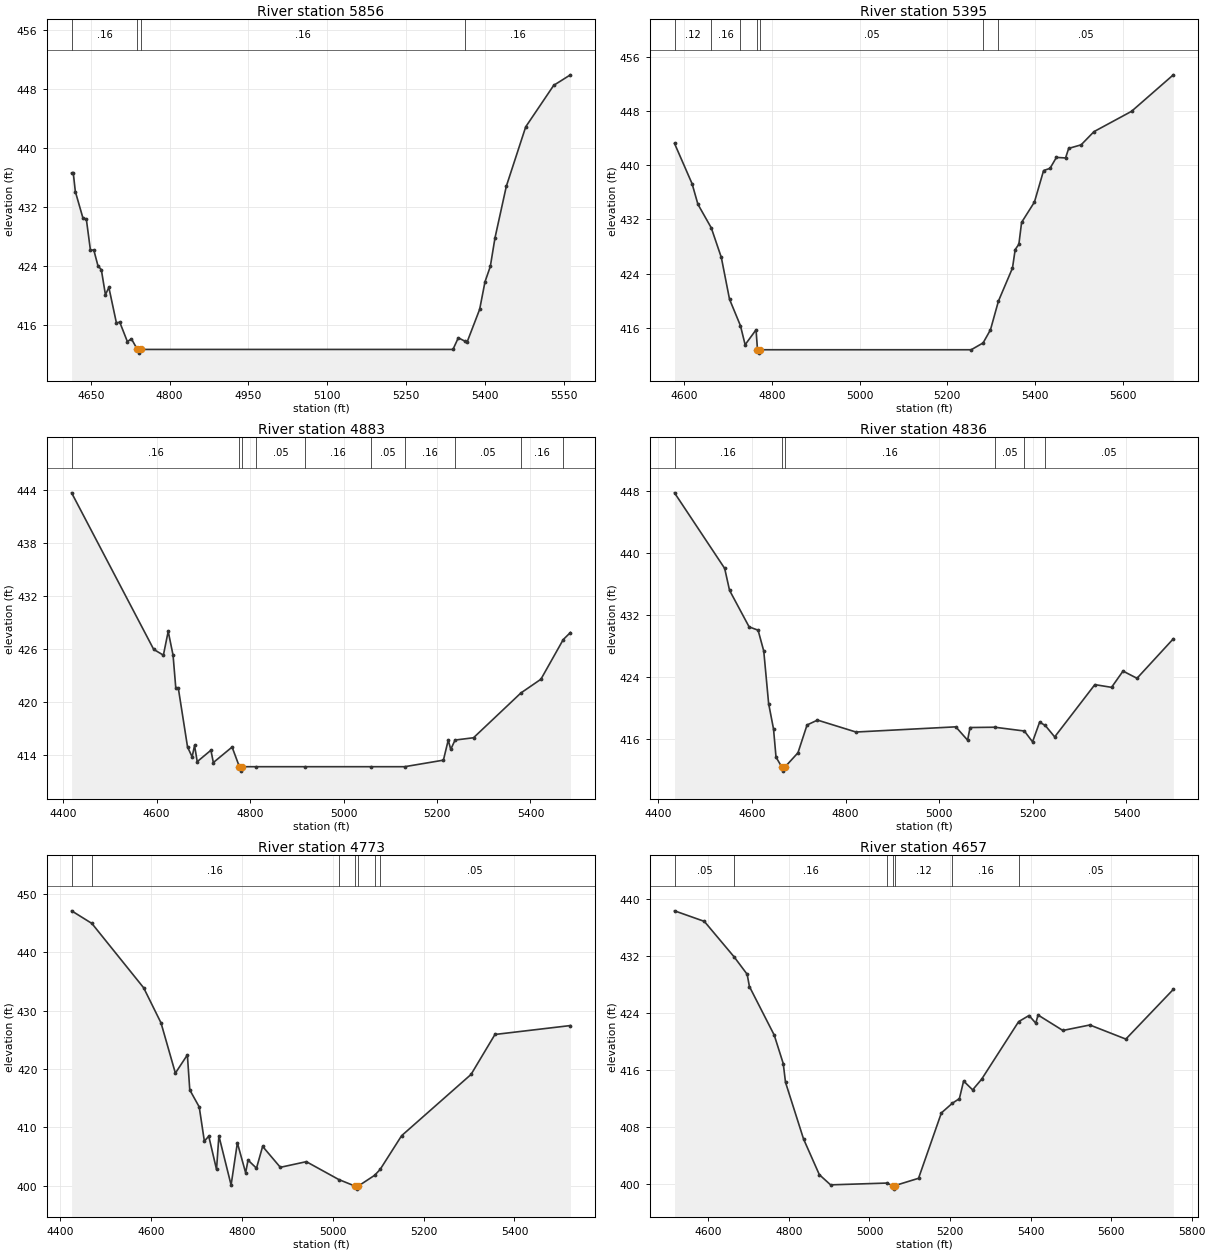
Type RM Length L Ch R = 1,5856,461,461,461
BEGIN DESCRIPTION:
SOUTH NICHOLS LAKE 13.0
END DESCRIPTION:
XS GIS Cut Line= 3
      3700249.59     10781860.20      3699949.61     10782110.19
      3700049.61     10782660.18
#Sta/Elev= 30
  4613.4  436.62  4616.6  436.62  4620.5  434.11  4634.9  430.54  4641.4  430.39
  4649.2  426.20  4655.7  426.18  4663.5  424.07  4670.0  423.52  4677.8  420.14
  4684.3  421.13  4698.6  416.35  4705.1  416.41  4719.5  413.80  4727.3  414.16
  4738.6  412.73  4741.3  412.23  4744.6  412.73  5339.3  412.73  5349.5  414.31
  5362.4  413.83  5366.0  413.69  5390.1  418.16  5400.3  421.90  5410.4  423.97
  5419.3  427.84  5440.9  434.84  5477.8  442.88  5531.1  448.50  5562.9  449.92
#Mann=4,-1,0
  4613.4    0.16       0  4738.6   0.033       0  4744.6    0.16       0
  5362.4    0.16       0
Bank Sta=4738.6,4744.6
Exp/Cntr=0.3,0.1

Type RM Length L Ch R = 1,5395,512,512,512
BEGIN DESCRIPTION:
SOUTH NICHOLS LAKE 12.0
END DESCRIPTION:
XS GIS Cut Line= 3
      3700049.64     10781610.18      3699649.61     10781760.19
      3699077.37     10782181.44
#Sta/Elev= 30
  4578.0  443.24  4618.1  437.28  4631.4  434.24  4661.9  430.75  4684.8  426.38
  4703.5  420.20  4728.4  416.29  4739.1  413.47  4764.0  415.68  4767.3  412.73
  4770.0  412.23  4773.3  412.73  5254.8  412.73  5281.9  413.74  5298.7  415.68
  5316.9  419.93  5348.9  424.81  5355.1  427.55  5363.5  428.33  5369.7  431.56
  5399.0  434.57  5419.9  439.23  5434.5  439.55  5449.1  441.17  5470.0  441.09
  5477.1  442.50  5505.5  443.03  5534.8  444.98  5620.4  447.98  5715.8  453.38
#Mann=7,-1,0
  4578.0    0.12       0  4661.9    0.16       0  4728.4    0.05       0
  4767.3   0.033       0  4773.3    0.05       0  5281.9    0.16       0
  5316.9    0.05       0
Bank Sta=4767.3,4773.3
Exp/Cntr=0.3,0.1

Type RM Length L Ch R = 1,4883,47,47,47
BEGIN DESCRIPTION:
Mapping XS 67583dee
END DESCRIPTION:
XS GIS Cut Line= 4
      3700009.41     10781147.68      3699480.72     10781288.32
      3699423.43     10781311.76      3698996.37     10781478.42
#Sta/Elev= 30
  4418.1  443.67  4593.8  425.98  4614.5  425.33  4624.8  428.02  4635.2  425.32
  4641.1  421.58  4646.3  421.65  4666.2  414.95  4676.0  413.84  4681.2  415.13
  4686.9  413.30  4716.2  414.59  4721.4  413.20  4761.5  414.95  4777.1  412.73
  4779.8  412.23  4783.1  412.73  4813.0  412.73  4916.5  412.73  5058.8  412.73
  5130.7  412.73  5213.7  413.47  5224.0  415.73  5229.4  414.69  5238.6  415.74
  5278.1  416.00  5379.5  421.06  5422.3  422.61  5470.2  427.10  5485.5  427.89
#Mann=10,-1,0
  4418.1    0.16       0  4777.1    0.07       0  4783.1    0.16       0
  4813.0    0.05       0  4916.5    0.16       0  5058.8    0.05       0
  5130.7    0.16       0  5238.6    0.05       0  5379.5    0.16       0
  5470.2    0.05       0
Bank Sta=4777.1,4783.1
Exp/Cntr=0.3,0.1

Type RM Length L Ch R = 1,4836,63,63,63
BEGIN DESCRIPTION:
Mapping XS dac8f2ef
END DESCRIPTION:
XS GIS Cut Line= 4
      3699982.33     10781092.99      3699451.03     10781251.86
      3699401.55     10781267.49      3698973.27     10781433.61
#Sta/Elev= 30
  4434.3  447.82  4541.5  438.06  4551.9  435.23  4593.7  430.51  4612.9  430.08
  4625.0  427.39  4635.4  420.61  4645.9  417.31  4651.2  413.69  4663.8  412.38
  4666.5  411.88  4669.8  412.38  4698.1  414.25  4717.5  417.84  4739.8  418.47
  4822.0  416.93  5035.3  417.60  5060.5  415.88  5065.8  417.51  5118.6  417.55
  5181.8  417.06  5199.3  415.66  5214.4  418.20  5226.4  417.78  5246.6  416.30
  5332.4  423.05  5368.1  422.70  5392.6  424.80  5422.5  423.87  5500.1  428.97
#Mann=6,-1,0
  4434.3    0.16       0  4663.8    0.07       0  4669.8    0.16       0
  5118.6    0.05       0  5181.8    0.16       0  5226.4    0.05       0
Bank Sta=4663.8,4669.8
Exp/Cntr=0.3,0.1

Type RM Length L Ch R = 1,4773,116,116,116
BEGIN DESCRIPTION:
SOUTH NICHOLS LAKE 11.0
END DESCRIPTION:
XS GIS Cut Line= 3
      3699977.07     10781016.97      3699362.49     10781214.88
      3698945.82     10781391.97
#Sta/Elev= 30
  4424.8  447.12  4469.4  444.96  4583.5  433.91  4621.7  427.89  4653.3  419.28
  4679.7  422.41  4685.0  416.40  4705.8  413.48  4717.1  407.62  4726.8  408.46
  4743.9  402.75  4749.1  408.52  4776.0  400.08  4789.8  407.32  4808.0  402.19
  4813.3  404.36  4831.9  402.97  4845.4  406.71  4884.4  403.12  4941.6  404.09
  5013.0  401.03  5049.5  399.88  5052.2  399.38  5055.5  399.88  5092.0  401.75
  5104.1  402.75  5151.5  408.55  5304.3  419.05  5357.0  425.91  5523.2  427.44
#Mann=7,-1,0
  4424.8    0.05       0  4469.4    0.16       0  5013.0    0.12       0
  5049.5    0.07       0  5055.5    0.12       0  5092.0    0.16       0
  5104.1    0.05       0
Bank Sta=5049.5,5055.5
Exp/Cntr=0.3,0.1

Type RM Length L Ch R = 1,4657,648,648,648
BEGIN DESCRIPTION:
SOUTH NICHOLS LAKE 10.0
END DESCRIPTION:
XS GIS Cut Line= 2
      3699842.84     10780863.16      3698734.05     10781414.95
#Sta/Elev= 30
  4516.0  438.40  4590.0  436.92  4664.5  431.90  4696.4  429.49  4702.0  427.77
  4763.6  420.95  4786.0  416.95  4791.6  414.32  4836.4  406.36  4875.6  401.35
  4903.5  399.92  5042.4  400.17  5057.3  399.82  5060.0  399.32  5063.3  399.82
  5121.9  400.84  5178.6  410.02  5206.2  411.40  5223.3  412.02  5233.8  414.50
  5256.2  413.26  5278.6  414.76  5370.4  422.84  5396.2  423.70  5413.0  422.62
  5418.6  423.77  5480.2  421.60  5547.2  422.37  5636.6  420.39  5754.5  427.37
#Mann=7,-1,0
  4516.0    0.05       0  4664.5    0.16       0  5042.4    0.12       0
  5057.3    0.07       0  5063.3    0.12       0  5206.2    0.16       0
  5370.4    0.05       0
Bank Sta=5057.3,5063.3
Exp/Cntr=0.3,0.1

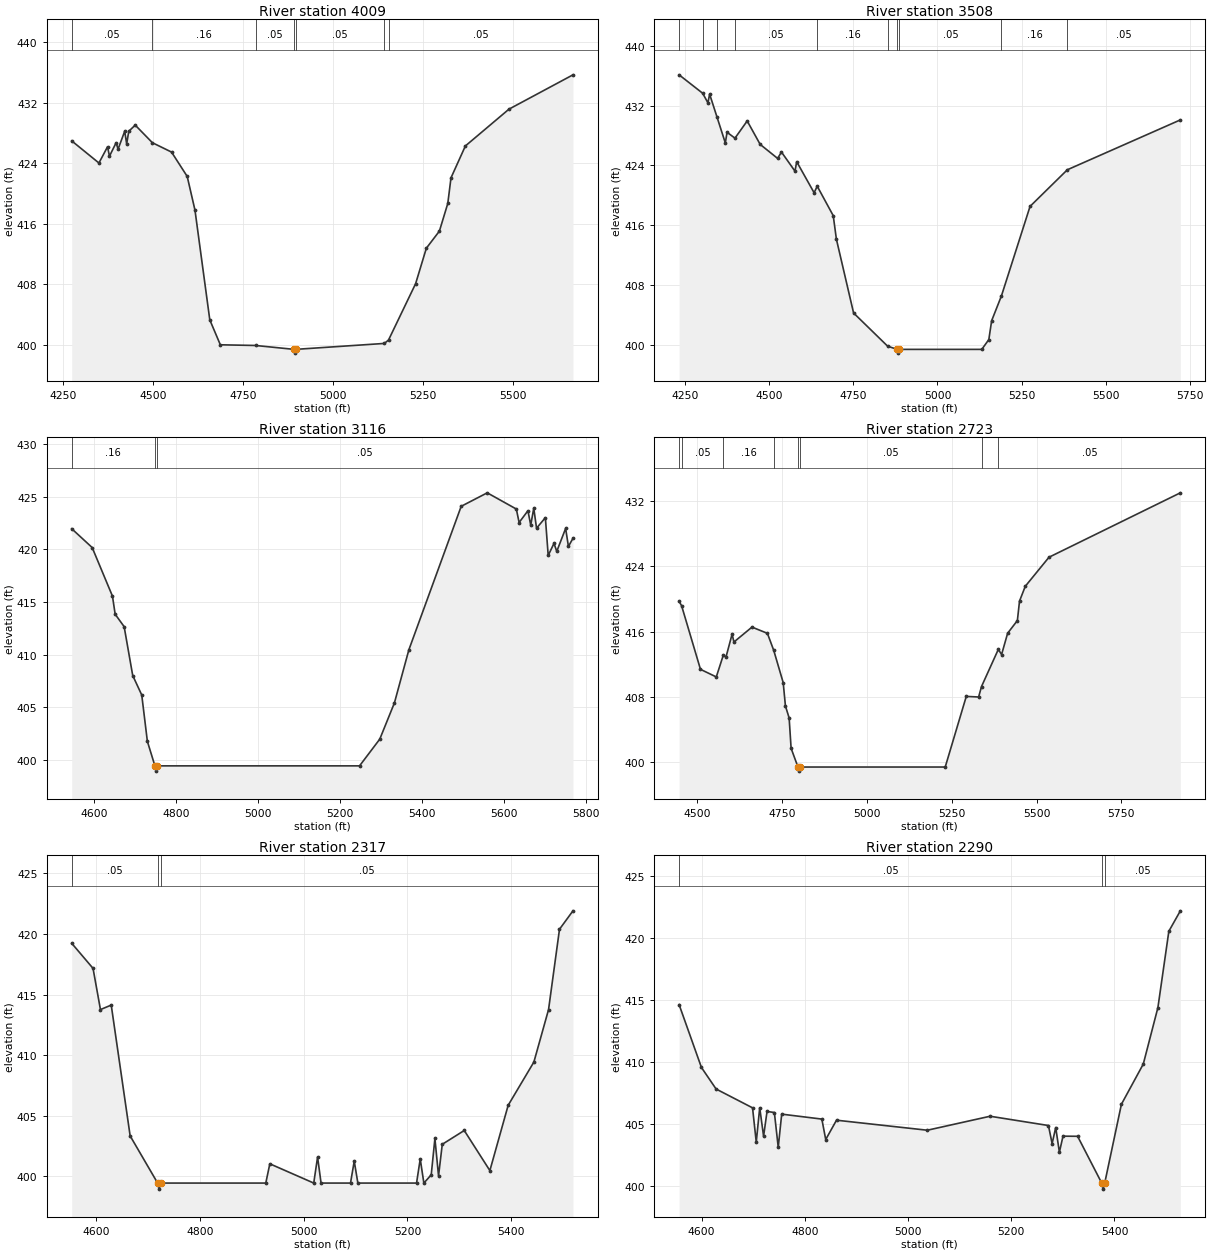
Type RM Length L Ch R = 1,4009,501,501,501
BEGIN DESCRIPTION:
SOUTH NICHOLS LAKE 9.0
END DESCRIPTION:
XS GIS Cut Line= 3
      3699875.96     10780713.56      3699260.51     10780458.14
      3698584.05     10780723.52
#Sta/Elev= 30
  4274.3  426.96  4349.9  424.04  4373.8  426.18  4379.2  424.94  4397.7  426.72
  4403.1  425.87  4421.6  428.24  4427.0  426.55  4432.8  428.23  4450.8  429.04
  4498.4  426.72  4551.7  425.48  4595.2  422.27  4616.8  417.82  4658.0  403.33
  4687.3  400.04  4785.1  399.95  4891.5  399.44  4894.3  398.94  4897.5  399.44
  5143.1  400.22  5154.7  400.67  5230.0  408.11  5259.8  412.79  5296.1  415.05
  5319.4  418.70  5328.3  422.08  5368.3  426.29  5489.5  431.15  5667.3  435.68
#Mann=7,-1,0
  4274.3    0.05       0  4498.4    0.16       0  4785.1    0.05       0
  4891.5   0.033       0  4897.5    0.05       0  5143.1    0.16       0
  5154.7    0.05       0
Bank Sta=4891.5,4897.5
Exp/Cntr=0.3,0.1

Type RM Length L Ch R = 1,3508,392,392,392
BEGIN DESCRIPTION:
SOUTH NICHOLS LAKE 8.0
END DESCRIPTION:
XS GIS Cut Line= 3
      3699947.97     10779848.77      3699224.05     10779989.39
      3698621.29     10780436.27
#Sta/Elev= 30
  4233.1  436.11  4303.0  433.65  4318.6  432.37  4323.7  433.53  4345.8  430.44
  4370.3  427.01  4375.4  428.44  4398.9  427.65  4435.2  429.95  4473.7  426.82
  4525.4  424.95  4537.0  425.79  4577.1  423.24  4582.1  424.51  4633.8  420.36
  4643.1  421.23  4690.6  417.30  4700.0  414.15  4751.0  404.30  4852.0  399.87
  4880.4  399.44  4883.1  398.94  4886.4  399.44  5131.5  399.44  5152.4  400.75
  5160.8  403.27  5189.9  406.59  5274.8  418.54  5385.5  423.43  5720.9  430.09
#Mann=10,-1,0
  4233.1    0.16       0  4303.0    0.12       0  4345.8    0.16       0
  4398.9    0.05       0  4643.1    0.16       0  4852.0    0.05       0
  4880.4   0.033       0  4886.4    0.05       0  5189.9    0.16       0
  5385.5    0.05       0
Bank Sta=4880.4,4886.4
Exp/Cntr=0.3,0.1

Type RM Length L Ch R = 1,3116,393,393,393
BEGIN DESCRIPTION:
SOUTH NICHOLS LAKE 7.0
END DESCRIPTION:
XS GIS Cut Line= 3
      3699299.60     10779410.20      3698949.61     10779710.19
      3698433.47     10780269.46
#Sta/Elev= 30
  4546.1  421.96  4596.0  420.17  4645.4  415.56  4652.0  413.84  4673.9  412.66
  4694.8  408.02  4716.8  406.17  4730.5  401.77  4748.9  399.44  4751.6  398.94
  4754.9  399.44  5247.8  399.44  5297.1  401.98  5332.8  405.42  5368.0  410.46
  5495.6  424.09  5559.1  425.37  5630.0  423.83  5636.8  422.55  5658.3  423.67
  5665.1  422.30  5672.5  423.91  5679.3  422.01  5700.8  423.01  5707.7  419.42
  5721.8  420.57  5728.6  419.81  5750.2  421.99  5757.0  420.28  5768.1  421.05
#Mann=3,-1,0
  4546.1    0.16       0  4748.9   0.033       0  4754.9    0.05       0
Bank Sta=4748.9,4754.9
Exp/Cntr=0.3,0.1

Type RM Length L Ch R = 1,2723,406,406,406
BEGIN DESCRIPTION:
SOUTH NICHOLS LAKE 6.0
END DESCRIPTION:
XS GIS Cut Line= 2
      3699265.74     10779161.25      3697916.74     10779760.23
#Sta/Elev= 30
  4447.5  419.68  4454.7  419.17  4510.4  411.38  4557.0  410.45  4577.5  413.09
  4585.7  412.90  4603.5  415.67  4609.0  414.72  4662.1  416.54  4707.5  415.78
  4726.2  413.69  4754.0  409.76  4760.6  406.90  4771.5  405.44  4777.3  401.73
  4797.5  399.44  4800.3  398.94  4803.5  399.44  5231.1  399.44  5293.1  408.07
  5329.5  408.00  5338.0  409.28  5387.5  413.82  5397.1  413.19  5414.9  415.79
  5443.6  417.34  5449.9  419.72  5466.9  421.53  5536.7  425.08  5923.5  432.95
#Mann=8,-1,0
  4447.5    0.16       0  4454.7    0.05       0  4577.5    0.16       0
  4726.2    0.05       0  4797.5   0.033       0  4803.5    0.05       0
  5338.0    0.16       0  5387.5    0.05       0
Bank Sta=4797.5,4803.5
Exp/Cntr=0.3,0.1

Type RM Length L Ch R = 1,2317,27,27,27
BEGIN DESCRIPTION:
Mapping XS 1baeb1f2
END DESCRIPTION:
XS GIS Cut Line= 4
      3699036.72     10778699.34      3698708.58     10778972.78
      3698646.08     10779030.07      3698319.29     10779346.49
#Sta/Elev= 30
  4552.5  419.23  4593.6  417.16  4607.9  413.76  4628.7  414.13  4665.2  403.33
  4718.2  399.44  4720.9  398.94  4724.2  399.44  4926.8  399.44  4934.6  401.03
  5019.3  399.44  5026.7  401.59  5033.4  399.44  5090.2  399.44  5097.4  401.25
  5104.4  399.44  5217.6  399.44  5224.7  401.43  5231.7  399.44  5245.9  400.12
  5253.0  403.12  5260.0  400.03  5267.2  402.64  5309.6  403.78  5359.0  400.47
  5394.3  405.86  5443.9  409.43  5472.2  413.76  5493.3  420.39  5519.3  421.91
#Mann=3,-1,0
  4552.5    0.05       0  4718.2    0.03       0  4724.2    0.05       0
Bank Sta=4718.2,4724.2
Exp/Cntr=0.3,0.1

Type RM Length L Ch R = 1,2290,67,67,67
BEGIN DESCRIPTION:
Mapping XS 43106c31
END DESCRIPTION:
XS GIS Cut Line= 4
      3699015.89     10778665.48      3698705.98     10778941.53
      3698656.50     10778985.80      3698307.51     10779329.58
#Sta/Elev= 30
  4556.4  414.63  4599.7  409.55  4628.1  407.81  4698.7  406.29  4705.9  403.52
  4712.6  406.30  4720.1  403.99  4726.8  406.00  4741.0  405.91  4748.5  403.10
  4755.2  405.78  4833.0  405.38  4840.5  403.73  4861.4  405.29  5037.4  404.48
  5159.0  405.61  5272.1  404.86  5279.2  403.40  5286.2  404.70  5293.3  402.70
  5300.3  404.00  5328.6  403.99  5375.2  400.22  5377.9  399.72  5381.2  400.22
  5413.5  406.58  5455.9  409.83  5484.2  414.39  5505.4  420.56  5527.7  422.21
#Mann=3,-1,0
  4556.4    0.05       0  5375.2    0.03       0  5381.2    0.05       0
Bank Sta=5375.2,5381.2
Exp/Cntr=0.3,0.1

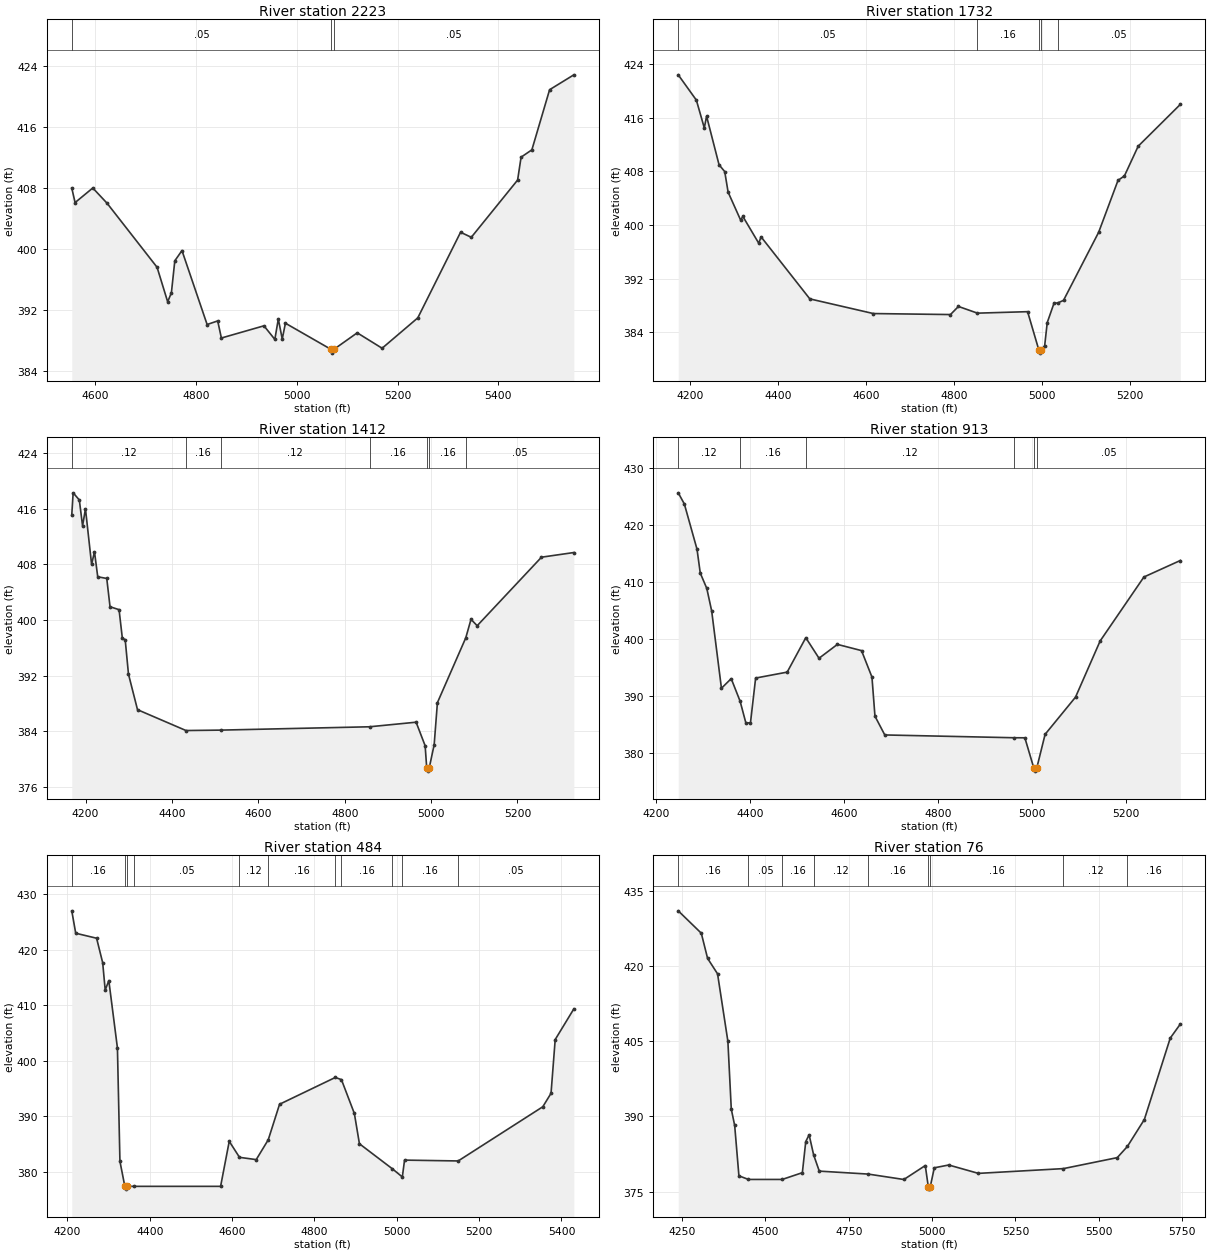
Type RM Length L Ch R = 1,2223,491,491,491
BEGIN DESCRIPTION:
SOUTH NICHOLS LAKE 5.0
END DESCRIPTION:
XS GIS Cut Line= 4
      3698988.12     10778599.50      3698688.62     10778875.56
      3698584.45     10778956.29      3698267.66     10779286.07
#Sta/Elev= 30
  4553.5  407.99  4560.1  406.09  4595.2  408.00  4623.6  406.00  4722.8  397.61
  4743.8  393.09  4751.2  394.26  4758.0  398.46  4772.2  399.80  4822.1  390.11
  4843.1  390.58  4850.4  388.34  4934.9  389.94  4956.5  388.16  4963.4  390.83
  4971.2  388.21  4977.5  390.28  5067.8  386.86  5070.5  386.36  5073.8  386.86
  5120.0  389.02  5169.4  387.00  5240.2  390.98  5325.1  402.20  5346.4  401.54
  5438.3  409.04  5445.2  412.04  5466.6  413.00  5501.8  420.88  5549.9  422.83
#Mann=3,-1,0
  4553.5    0.05       0  5067.8    0.03       0  5073.8    0.05       0
Bank Sta=5067.8,5073.8
Exp/Cntr=0.3,0.1

Type RM Length L Ch R = 1,1732,320,320,320
BEGIN DESCRIPTION:
SOUTH NICHOLS LAKE 4.0
END DESCRIPTION:
XS GIS Cut Line= 3
      3699099.56     10778510.20      3698299.61     10778710.19
      3698138.35     10778981.86
#Sta/Elev= 30
  4173.2  422.42  4214.4  418.64  4232.4  414.49  4237.6  416.24  4265.9  408.99
  4278.8  407.97  4286.5  404.90  4314.9  400.73  4320.0  401.27  4356.1  397.27
  4361.3  398.23  4472.1  388.96  4616.4  386.77  4791.6  386.62  4809.7  387.83
  4852.9  386.83  4966.8  387.05  4992.2  381.36  4994.9  380.86  4998.2  381.36
  5005.6  381.98  5011.4  385.42  5027.0  388.35  5034.9  388.34  5048.4  388.74
  5128.3  398.92  5172.2  406.66  5186.8  407.33  5218.0  411.76  5313.7  418.00
#Mann=5,-1,0
  4173.2    0.05       0  4852.9    0.16       0  4992.2    0.07       0
  4998.2    0.16       0  5034.9    0.05       0
Bank Sta=4992.2,4998.2
Exp/Cntr=0.3,0.1

Type RM Length L Ch R = 1,1412,499,499,499
BEGIN DESCRIPTION:
Mapping XS a3d4bb03
END DESCRIPTION:
XS GIS Cut Line= 2
      3698605.50     10777881.34      3697837.23     10778753.79
#Sta/Elev= 30
  4168.0  415.10  4171.2  418.29  4185.5  417.26  4193.0  413.53  4199.7  415.99
  4213.9  408.00  4220.6  409.81  4228.1  406.21  4249.0  405.97  4256.6  401.90
  4277.5  401.48  4285.1  397.37  4291.7  397.16  4299.3  392.20  4320.2  387.09
  4432.5  384.09  4512.4  384.15  4857.4  384.63  4965.3  385.29  4986.2  381.90
  4989.8  378.75  4992.6  378.25  4995.8  378.75  5007.1  382.06  5014.6  388.10
  5080.3  397.43  5092.4  400.09  5106.7  399.17  5255.6  409.03  5330.5  409.70
#Mann=7,-1,0
  4168.0    0.12       0  4432.5    0.16       0  4512.4    0.12       0
  4857.4    0.16       0  4989.8    0.07       0  4995.8    0.16       0
  5080.3    0.05       0
Bank Sta=4989.8,4995.8
Exp/Cntr=0.3,0.1

Type RM Length L Ch R = 1,913,429,429,429
BEGIN DESCRIPTION:
SOUTH NICHOLS LAKE 3.0
END DESCRIPTION:
XS GIS Cut Line= 4
      3698358.12     10777811.90      3698006.53     10777911.74
      3697659.31     10778198.19      3697534.02     10778418.54
#Sta/Elev= 30
  4247.4  425.66  4260.4  423.71  4287.4  415.77  4294.3  411.60  4308.2  408.91
  4318.6  404.96  4339.4  391.41  4360.2  393.10  4379.2  389.13  4391.4  385.34
  4401.2  385.35  4412.2  393.20  4479.4  394.24  4519.0  400.27  4547.2  396.67
  4586.3  399.10  4637.7  398.01  4659.9  393.37  4666.3  386.52  4687.2  383.23
  4962.5  382.74  4985.5  382.73  5004.7  377.39  5007.5  376.89  5010.7  377.39
  5028.6  383.34  5093.4  389.86  5145.8  399.70  5239.0  410.91  5316.5  413.80
#Mann=6,-1,0
  4247.4    0.12       0  4379.2    0.16       0  4519.0    0.12       0
  4962.5    0.16       0  5004.7    0.07       0  5010.7    0.05       0
Bank Sta=5004.7,5010.7
Exp/Cntr=0.3,0.1

Type RM Length L Ch R = 1,484,408,408,408
BEGIN DESCRIPTION:
SOUTH NICHOLS LAKE 2.0
END DESCRIPTION:
XS GIS Cut Line= 3
      3698123.71     10777360.53      3697429.27     10777842.29
      3697398.91     10778215.37
#Sta/Elev= 30
  4210.5  426.98  4220.1  422.95  4270.8  422.05  4285.6  417.64  4291.7  412.72
  4300.5  414.43  4321.4  402.31  4327.5  381.91  4339.4  377.41  4342.1  376.91
  4345.4  377.41  4362.0  377.41  4572.0  377.41  4593.0  385.51  4617.9  382.63
  4658.5  382.22  4687.7  385.78  4715.2  392.18  4850.6  397.00  4865.5  396.61
  4896.9  390.52  4909.2  385.07  4989.3  380.56  5013.4  379.10  5018.8  382.13
  5149.1  381.98  5354.6  391.73  5374.6  394.15  5384.7  403.82  5430.0  409.34
#Mann=11,-1,0
  4210.5    0.16       0  4339.4    0.07       0  4345.4    0.16       0
  4362.0    0.05       0  4617.9    0.12       0  4687.7    0.16       0
  4850.6    0.12       0  4865.5    0.16       0  4989.3    0.12       0
  5013.4    0.16       0  5149.1    0.05       0
Bank Sta=4339.4,4345.4
Exp/Cntr=0.3,0.1

Type RM Length L Ch R = 1,76,0,0,0
BEGIN DESCRIPTION:
SOUTH NICHOLS LAKE 1.0
END DESCRIPTION:
XS GIS Cut Line= 4
      3698106.35     10777273.72      3697398.89     10777399.58
      3697325.11     10777447.33      3697199.44     10778136.31
#Sta/Elev= 30
  4238.2  430.96  4307.4  426.50  4326.3  421.48  4356.2  418.40  4387.2  404.95
  4397.4  391.43  4407.6  388.17  4420.3  378.13  4448.9  377.41  4550.2  377.41
  4610.7  378.76  4620.9  384.96  4631.0  386.31  4644.6  382.29  4661.5  379.07
  4808.3  378.48  4915.4  377.40  4979.6  380.18  4988.6  375.98  4991.4  375.48
  4994.6  375.98  5006.7  379.73  5050.0  380.29  5139.0  378.62  5394.2  379.57
  5555.8  381.76  5586.1  383.98  5637.1  389.36  5714.8  405.59  5745.0  408.38
#Mann=9,-1,0
  4238.2    0.16       0  4448.9    0.05       0  4550.2    0.16       0
  4644.6    0.12       0  4808.3    0.16       0  4988.6    0.07       0
  4994.6    0.16       0  5394.2    0.12       0  5586.1    0.16       0
Bank Sta=4988.6,4994.6
Exp/Cntr=0.3,0.1

Chan Stop Cuts=-1