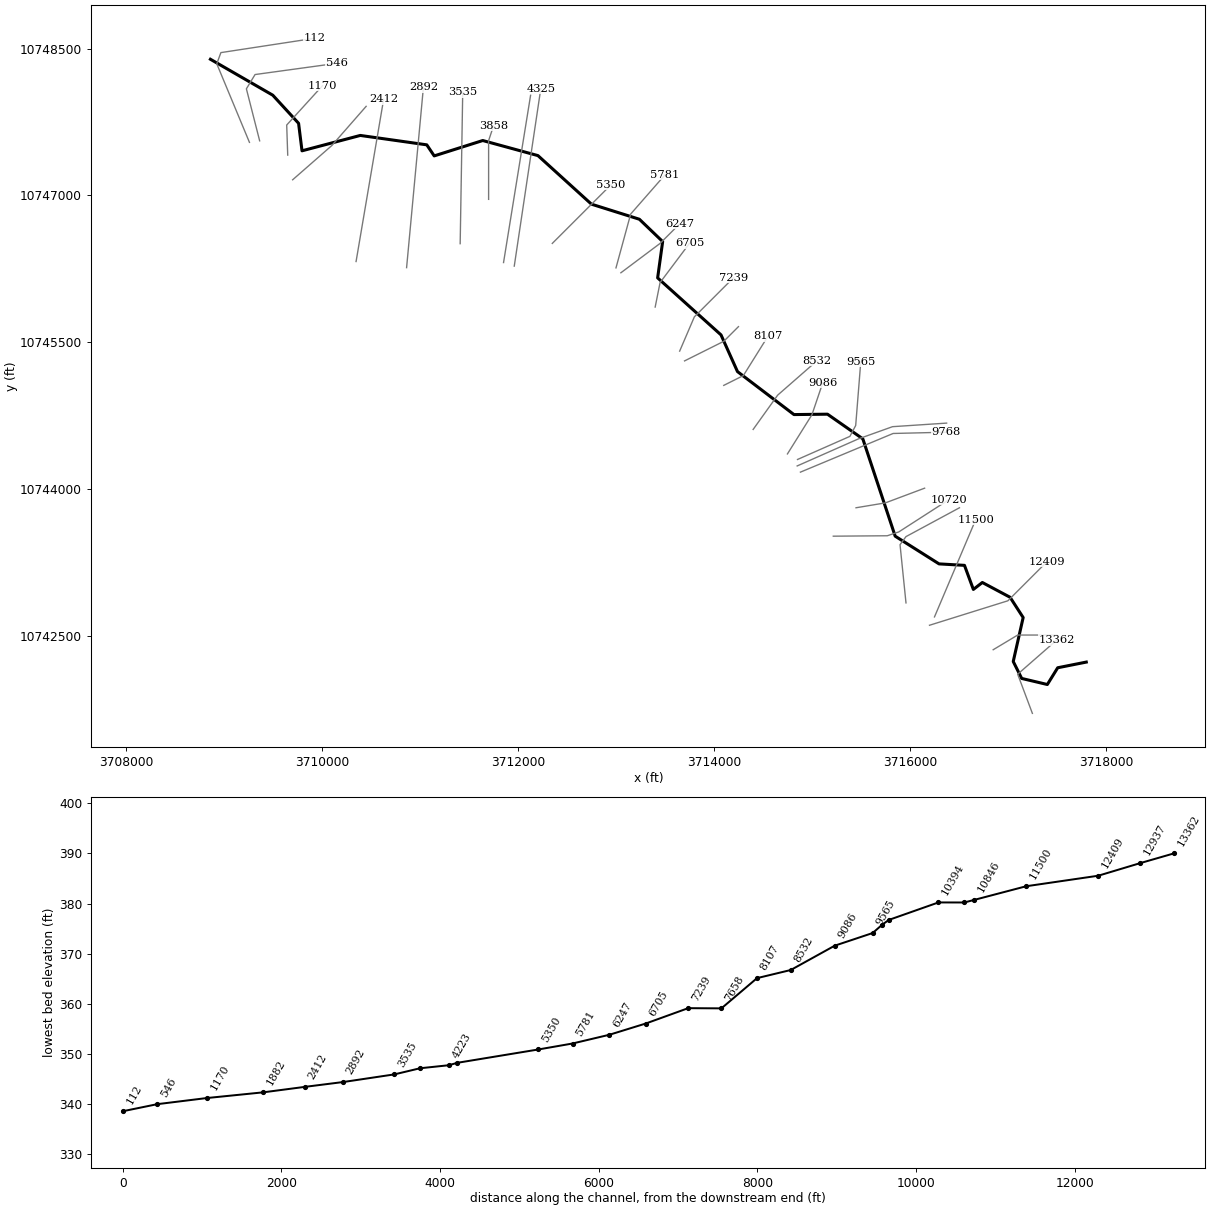
--- STRICKLAND BRANCH.prj (project) ---

Proj Title=STRICKLAND BRANCH Base Level Engineering
Current Plan=p01
Default Exp/Contr=0.3,0.1
English Units
Geom File=g01
Flow File=f01
Plan File=p01
Y Axis Title=Elevation
X Axis Title(PF)=Main Channel Distance
X Axis Title(XS)=Station
BEGIN DESCRIPTION:
STRICKLAND BRANCH
END DESCRIPTION:
DSS Export Rating Curves= 0
DSS Export Rating Curve Sorted= 0
DSS Export Volume Flow Curves= 0
DXF OffsetX= 0
DXF OffsetY= 0
DXF ScaleX= 1
DXF ScaleY= 10

--- STRICKLAND BRANCH.p01 (plan) ---

Plan Title=Multiple Run
Short Identifier=Multiple
Geom File=g01
Flow File=f01
Subcritical Flow
K Sum by GR= 0
Std Step Tol= 0.01
Critical Tol= 0.01
Num of Std Step Trials= 20
Max Error Tol= 0.3
Flow Tol Ratio= 0.001
Split Flow NTrial= 30
Split Flow Tol= 0.02
Split Flow Ratio= 0.02
Log Output Level= 0
Friction Slope Method= 1
Unsteady Friction Slope Method= 2
Unsteady Bridges Friction Slope Method= 1
Parabolic Critical Depth
Global Vel Dist=  1 , 1 , 1
Global Log Level= 0
CheckData=True
Encroach Param= -1, 0, 0, 0
BEGIN DESCRIPTION:
Multiple Run
END DESCRIPTION:

--- STRICKLAND BRANCH.f01 (steady flow) ---

Flow Title=Multiple
Program Version=4.10
Number of Profiles= 7
Profile Names=10-year,25-year,50-year,1pct_min,100-year,1pct_plu,500-year
River Rch & RM=STRICKLAND BRANC,Reach-1         ,13362
     901    1255    1556    1414    1913    2587    2897
River Rch & RM=STRICKLAND BRANC,Reach-1         ,10720
    1235    1751    2194    2015    2725    3685    4213
River Rch & RM=STRICKLAND BRANC,Reach-1         ,9565
    1477    2100    2637    2424    3278    4433    5076
River Rch & RM=STRICKLAND BRANC,Reach-1         ,1882
    1636    2335    2938    2705    3659    4948    5688
Boundary for River Rch & Prof#=STRICKLAND BRANC,Reach-1         , 1
Up Type= 0
Dn Type= 3
Dn Slope=0.00323
Boundary for River Rch & Prof#=STRICKLAND BRANC,Reach-1         , 2
Up Type= 0
Dn Type= 3
Dn Slope=0.00323
Boundary for River Rch & Prof#=STRICKLAND BRANC,Reach-1         , 3
Up Type= 0
Dn Type= 3
Dn Slope=0.00323
Boundary for River Rch & Prof#=STRICKLAND BRANC,Reach-1         , 4
Up Type= 0
Dn Type= 3
Dn Slope=0.00323
Boundary for River Rch & Prof#=STRICKLAND BRANC,Reach-1         , 5
Up Type= 0
Dn Type= 3
Dn Slope=0.00323
Boundary for River Rch & Prof#=STRICKLAND BRANC,Reach-1         , 6
Up Type= 0
Dn Type= 3
Dn Slope=0.00323
Boundary for River Rch & Prof#=STRICKLAND BRANC,Reach-1         , 7
Up Type= 0
Dn Type= 3
Dn Slope=0.00323
DSS Import GetInterval= 0
DSS Import GetPeak= 0
DSS Import FillOption= 0

--- STRICKLAND BRANCH.g01 (geometry) ---

Geom Title=Existing Conditions
Program Version=4.10

River Reach=STRICKLAND BRANC,Reach-1
Reach XY= 30
      3717799.75       10742234.        3717508.       10742176.
      3717402.25       10742005.       3717140.5       10742067.
      3717054.25       10742240.       3717155.5       10742689.
        3717022.       10742896.      3716738.75       10743047.
      3716647.25       10742976.       3716556.5       10743222.
      3716296.75       10743237.      3715849.25       10743520.
        3715519.       10744514.      3715158.25       10744766.
      3714816.25       10744762.      3714239.75       10745201.
       3714071.5       10745576.      3713424.75       10746158.
        3713476.       10746529.       3713238.5       10746757.
      3712749.25       10746911.      3712203.25       10747407.
      3711639.75       10747561.      3711144.25       10747404.
       3711068.5       10747517.      3710389.75       10747613.
        3709795.       10747456.        3709760.       10747737.
      3709496.75       10748024.      3708860.25       10748391.

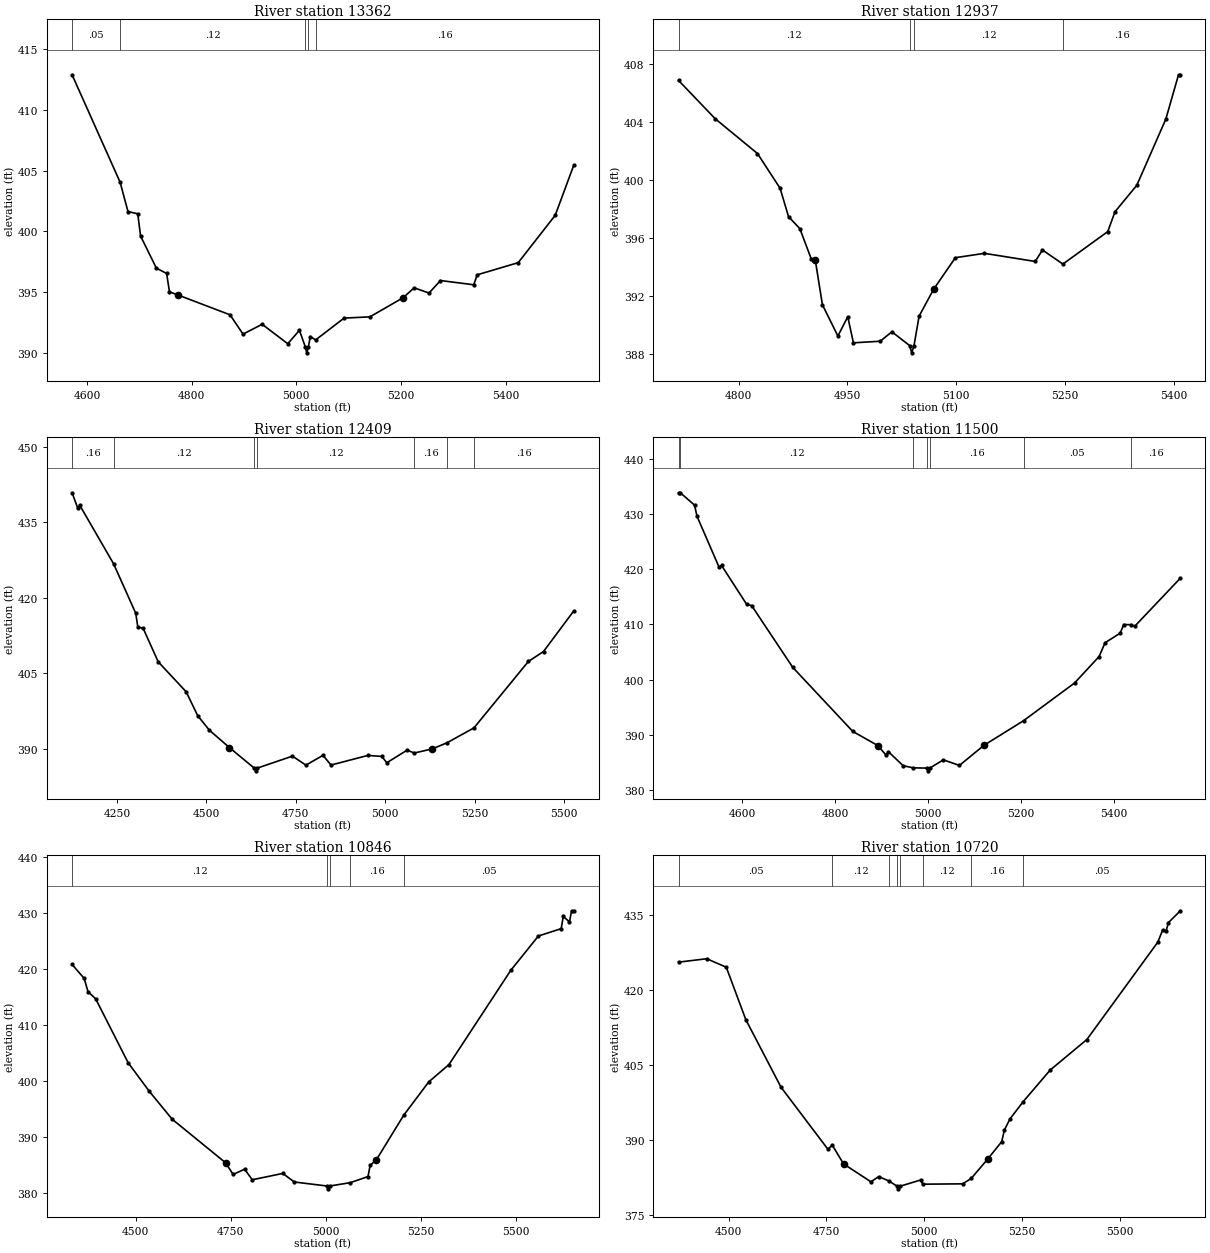
Type RM Length L Ch R = 1 ,13362   ,425,425,425
BEGIN DESCRIPTION:
STRICKLAND BRANCH 28.0
END DESCRIPTION:
XS GIS Cut Line= 3
      3717249.63     10741710.15      3717099.61     10742110.19
      3717499.64     10742460.22
#Sta/Elev= 30
  4571.5  412.89  4663.3  404.05  4678.3  401.64    4697  401.45  4702.4  399.62
  4732.6  396.98  4752.2  396.54  4757.6  395.03  4774.5  394.76  4873.3  393.14
  4898.2  391.55  4934.7  392.36  4983.6  390.76  5005.9  391.86  5017.1  390.51
  5019.9  390.01  5023.1  390.51  5026.7  391.35  5036.8  391.07  5091.3  392.87
  5140.6  392.97  5204.2  394.55  5225.1  395.36  5253.6  394.93  5275.4  395.96
    5339  395.61  5345.6  396.43    5424  397.43  5494.7  401.33  5530.3  405.47
#Mann= 5 ,-1 , 0
  4571.5     .05       0  4663.3     .12       0  5017.1     .07       0
  5023.1     .12       0  5036.8     .16       0
Bank Sta=4774.5,5204.2
XS Rating Curve= 0 ,0
Exp/Cntr=0.3,0.1

Type RM Length L Ch R = 1 ,12937   ,528,528,528
BEGIN DESCRIPTION:
STRICKLAND BRANCH 27.0
END DESCRIPTION:
XS GIS Cut Line= 3
      3716849.61     10742360.19      3717099.61     10742510.19
      3717499.56     10742510.19
#Sta/Elev= 30
  4717.3  406.85  4767.8  404.21  4826.1  401.81  4857.2  399.42  4868.9  397.46
  4884.5  396.63    4900  394.57  4905.8  394.45  4915.6  391.38  4936.9  389.23
  4950.5  390.56  4958.3  388.76  4995.2  388.87  5011.3  389.52  5035.8  388.57
  5038.6  388.07  5041.8  388.57  5048.8   390.6  5068.8  392.45  5098.8  394.63
  5138.8  394.93  5208.8  394.37  5218.8  395.16    5247  394.19  5308.8  396.43
  5318.8   397.8  5348.8  399.62  5388.8  404.18  5406.3  407.24  5408.8  407.24
#Mann= 4 ,-1 , 0
  4717.3     .12       0  5035.8     .07       0  5041.8     .12       0
    5247     .16       0
Bank Sta=4905.8,5068.8
XS Rating Curve= 0 ,0
Exp/Cntr=0.3,0.1

Type RM Length L Ch R = 1 ,12409   ,909,909,909
BEGIN DESCRIPTION:
STRICKLAND BRANCH 26.0
END DESCRIPTION:
XS GIS Cut Line= 3
      3716199.56     10742610.17      3716999.61     10742860.19
      3717399.62      10743260.2
#Sta/Elev= 30
    4124  440.91  4140.3  437.79  4145.5  438.43  4240.1  426.78  4302.2  416.92
  4307.9   414.2  4323.1   413.9    4365  407.26  4443.1  401.31  4475.5  396.54
    4508  393.66  4564.1   390.2  4634.4  386.06  4637.2  385.56  4640.4  386.06
  4740.6  388.49  4778.3  386.69    4826  388.65  4848.5  386.71  4951.7  388.63
  4990.5  388.43  5004.6  387.17  5061.2  389.67  5081.6  389.11  5131.9  389.93
  5172.9  391.14  5248.4  394.11  5400.6  407.33    5443  409.31  5527.9  417.42
#Mann= 7 ,-1 , 0
    4124     .16       0  4240.1     .12       0  4634.4     .07       0
  4640.4     .12       0  5081.6     .16       0  5172.9     .12       0
  5248.4     .16       0
Bank Sta=4564.1,5131.9
XS Rating Curve= 0 ,0
Exp/Cntr=0.3,0.1

Type RM Length L Ch R = 1 ,11500   ,654,654,654
BEGIN DESCRIPTION:
STRICKLAND BRANCH 25.0
END DESCRIPTION:
XS GIS Cut Line= 2
      3716250.43     10742695.32      3716671.43     10743689.23
#Sta/Elev= 30
  4463.5  433.82  4467.3  433.82  4497.9  431.59  4503.3  429.55  4550.7  420.34
  4556.1  420.65    4610  413.62  4620.8  413.38  4709.1  402.21  4838.3   390.6
  4892.3  388.03  4909.4  386.35  4914.8  386.94  4946.6  384.39  4968.5     384
  4997.9  383.96  5000.7  383.46  5003.9  383.96  5033.2  385.45  5067.7  384.44
  5120.5  388.08  5205.6  392.54  5315.4  399.37  5368.2  404.16    5381  406.66
  5413.6   408.4    5421  409.95  5436.9  409.93  5444.6  409.62  5542.9  418.35
#Mann= 7 ,-1 , 0
  4463.5     .16       0  4467.3     .12       0  4968.5     .16       0
  4997.9     .07       0  5003.9     .16       0  5205.6     .05       0
  5436.9     .16       0
Bank Sta=4892.3,5120.5
XS Rating Curve= 0 ,0
Exp/Cntr=0.3,0.1

Type RM Length L Ch R = 1 ,10846   ,126,126,126
BEGIN DESCRIPTION:
STRICKLAND BRANCH 24.0
END DESCRIPTION:
XS GIS Cut Line= 4
      3715959.61     10742838.46      3715898.85     10743433.12
      3715959.61     10743515.59      3716505.58     10743810.24
#Sta/Elev= 30
  4332.7  420.75  4364.6  418.27  4374.6   415.9  4394.7  414.64  4480.2  403.24
  4535.5  398.17  4595.8  393.18  4736.5   385.4  4756.6  383.31  4786.8  384.24
  4806.9  382.36  4887.3  383.49  4917.5  381.96  5004.6  381.24  5007.3  380.74
  5010.6  381.24  5065.4  381.85  5111.5  382.93  5117.2  384.94  5133.4   385.9
  5205.7  393.89  5271.5  399.82  5324.7  402.91  5487.4  419.72  5559.9  425.83
  5619.9  427.14  5625.5  429.31  5641.7  428.35  5647.4  430.33  5653.3   430.3
#Mann= 5 ,-1 , 0
  4332.7     .12       0  5004.6     .07       0  5010.6     .12       0
  5065.4     .16       0  5205.7     .05       0
Bank Sta=4736.5,5133.4
XS Rating Curve= 0 ,0
Exp/Cntr=0.3,0.1

Type RM Length L Ch R = 1 ,10720   ,326,326,326
BEGIN DESCRIPTION:
STRICKLAND BRANCH 23.0
END DESCRIPTION:
XS GIS Cut Line= 4
      3715217.43     10743519.93      3715768.64     10743524.27
      3715885.82     10743563.33      3716397.94     10743893.17
#Sta/Elev= 30
  4371.5  425.55  4443.7  426.23  4493.7  424.53  4543.7  414.04  4633.7  400.54
  4753.7  388.14  4764.8  388.97  4793.7  385.21  4863.7  381.63  4883.7  382.66
  4909.3  381.81  4931.3  380.72    4934  380.22  4937.3  380.72  4990.6  381.98
  4996.7  381.15  5098.3  381.22  5120.3  382.29  5162.1  386.13  5198.4  389.66
  5205.4  392.01  5219.6  394.21  5253.3  397.65  5322.5  403.98  5416.3  410.08
  5597.8  429.55  5609.8   431.9    5619  431.74  5624.9  433.45  5655.4  435.82
#Mann= 8 ,-1 , 0
  4371.5     .05       0  4764.8     .12       0  4909.3     .07       0
  4931.3     .07       0  4937.3     .07       0  4996.7     .12       0
  5120.3     .16       0  5253.3     .05       0
Bank Sta=4793.7,5162.1
XS Rating Curve= 0 ,0
Exp/Cntr=0.3,0.1

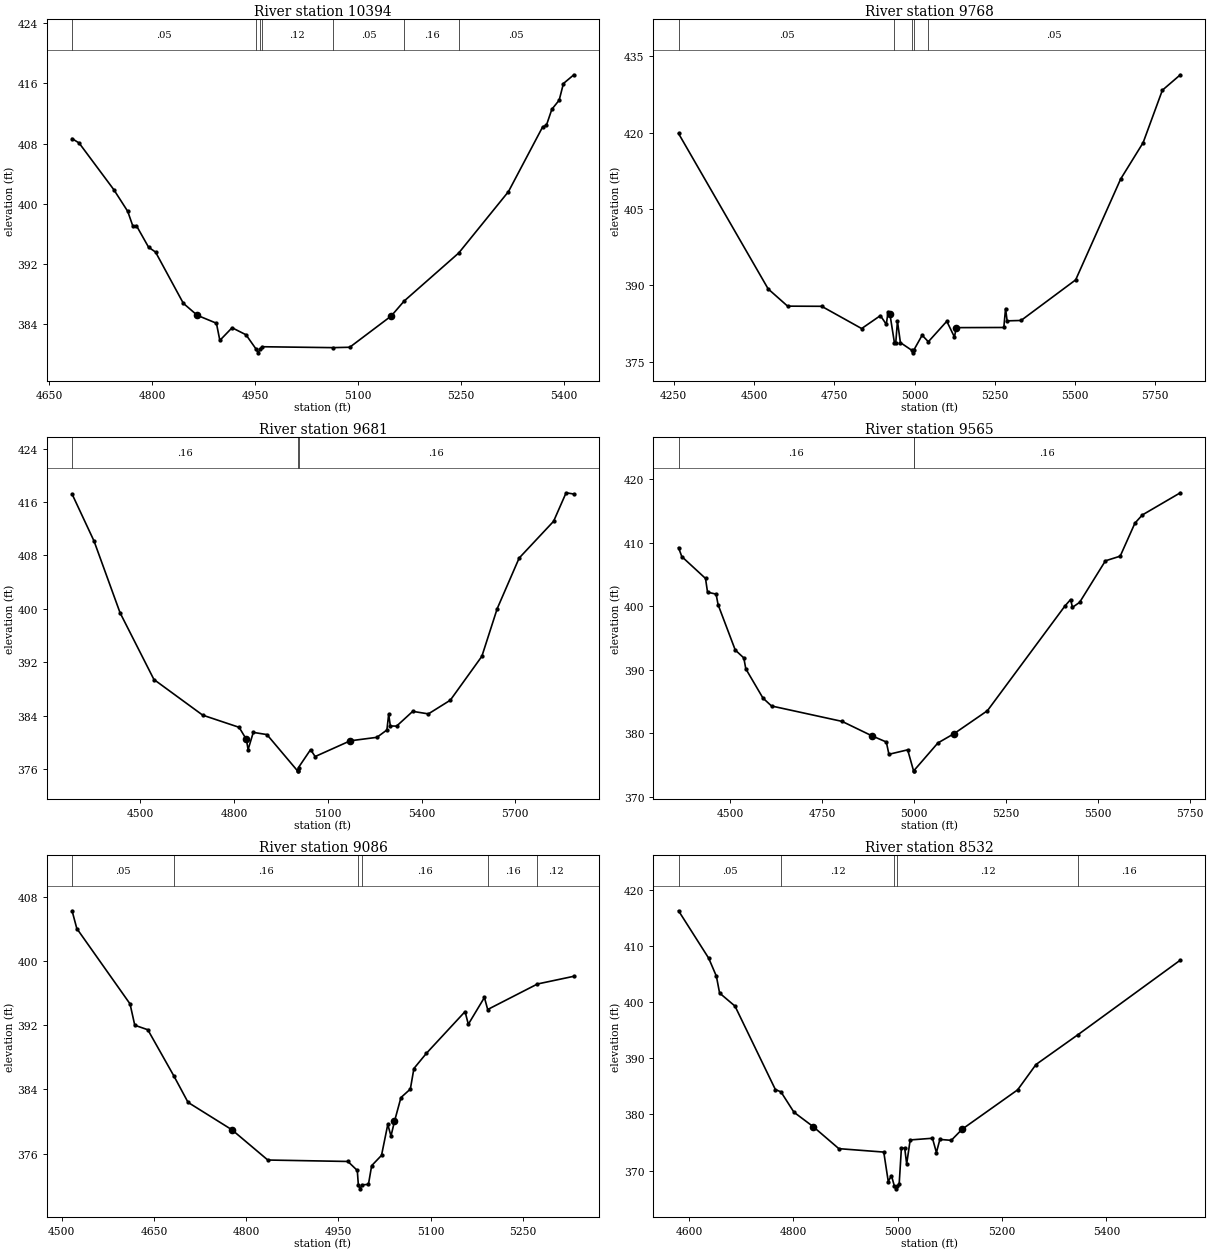
Type RM Length L Ch R = 1 ,10394   ,626,626,626
BEGIN DESCRIPTION:
STRICKLAND BRANCH 22.0
END DESCRIPTION:
XS GIS Cut Line= 3
       3715449.6     10743810.19      3715749.61     10743860.19
      3716149.65     10744010.21
#Sta/Elev= 30
  4683.1  408.66  4693.3  408.08  4743.9  401.89  4764.2  399.01  4771.8  397.02
  4776.9  397.11  4794.6  394.25  4804.8   393.6  4845.3   386.8  4865.6  385.21
  4893.5  384.16  4898.5  381.88  4916.3  383.56  4936.6  382.63  4951.3  380.73
  4954.1  380.23  4957.3  380.73    4960  381.04    5063  380.92  5087.8  380.97
  5148.3  385.12  5167.2  387.11  5246.7  393.48  5319.2  401.63  5369.1  410.23
  5374.4   410.4  5382.4  412.55  5393.1  413.76  5399.3  415.97  5414.5  417.13
#Mann= 7 ,-1 , 0
  4683.1     .05       0  4951.3     .07       0  4957.3     .05       0
    4960     .12       0    5063     .05       0  5167.2     .16       0
  5246.7     .05       0
Bank Sta=4865.6,5148.3
XS Rating Curve= 0 ,0
Exp/Cntr=0.3,0.1

Type RM Length L Ch R = 1 ,9768    ,87,87,87
BEGIN DESCRIPTION:
Mapping XS 6e698ec9
END DESCRIPTION:
XS GIS Cut Line= 3
      3714881.96       10744174.      3715828.17     10744568.97
      3716365.48     10744581.97
#Sta/Elev= 30
  4265.1  419.82  4544.3  389.29  4604.8  385.91  4710.9  385.88  4835.4  381.51
  4893.8  384.05  4912.2  382.34  4917.7  384.81  4923.6  384.29  4937.5   378.7
  4941.5  378.62  4946.9  382.96  4956.1  378.75  4991.5  377.24  4994.3  376.74
  4997.5  377.24  5023.8   380.2  5043.1  378.92  5100.6  382.94  5124.4  379.84
  5129.9  381.69  5278.2  381.72  5283.6  385.44  5288.5  383.02  5331.9   383.1
  5501.9  391.07    5642  410.87    5712  418.01    5772  428.32  5827.9  431.35
#Mann= 5 ,-1 , 0
  4265.1     .05       0  4937.5      .1       0  4991.5     .07       0
  4997.5      .1       0  5043.1     .05       0
Bank Sta=4923.6,5129.9
XS Rating Curve= 0 ,0
Exp/Cntr=0.3,0.1

Type RM Length L Ch R = 1 ,9681    ,116,116,116
BEGIN DESCRIPTION:
STRICKLAND BRANCH 21.0
END DESCRIPTION:
XS GIS Cut Line= 4
        3714849.     10744237.37      3715473.35     10744513.42
      3715822.31     10744638.42      3716374.38     10744674.88
#Sta/Elev= 30
    4281   417.2  4351.3  410.16  4434.7  399.41  4543.1  389.42  4699.3  384.08
  4815.8  382.26  4839.1  380.45  4844.6  378.92  4861.2   381.5  4904.9  381.17
  5002.8  375.74  5003.3  375.74    5006  376.24  5044.7  378.92  5059.2  377.88
  5171.6  380.24  5257.1  380.76    5289  381.86  5294.7  384.22    5300  382.46
  5320.1  382.44  5371.7  384.65  5421.8  384.27    5492  386.32    5593  392.89
  5642.3  400.05  5712.4  407.61  5822.7  413.12  5862.8  417.39  5887.6   417.2
#Mann= 3 ,-1 , 0
    4281     .16       0  5003.3     .07       0    5006     .16       0
Bank Sta=4839.1,5171.6
XS Rating Curve= 0 ,0
Exp/Cntr=0.3,0.1

Type RM Length L Ch R = 1 ,9565    ,479,479,479
BEGIN DESCRIPTION:
STRICKLAND BRANCH 20.0
END DESCRIPTION:
XS GIS Cut Line= 4
      3714852.44     10744303.33       3715387.2     10744539.46
      3715446.23     10744650.57      3715498.31     10745303.31
#Sta/Elev= 30
  4358.7   409.2  4367.6  407.79  4432.1  404.36  4437.6   402.2  4460.9   401.9
  4466.3  400.24    4513  393.11  4536.3  391.87  4541.7  390.16  4588.4  385.56
  4611.7  384.32  4803.6   381.9  4884.5  379.64    4924  378.66  4931.1  376.73
  4982.1  377.43  4998.1  374.13  4998.6  374.13  5064.3  378.51  5108.8  379.99
  5199.1  383.58  5409.8  400.02  5425.4  401.05  5430.4  399.82  5449.9   400.6
  5520.1  407.13  5560.3  407.86  5600.4  413.05  5620.4  414.33  5723.9  417.82
#Mann= 3 ,-1 , 0
  4358.7     .16       0  4998.1     .07       0  4998.6     .16       0
Bank Sta=4884.5,5108.8
XS Rating Curve= 0 ,0
Exp/Cntr=0.3,0.1

Type RM Length L Ch R = 1 ,9086    ,554,554,554
BEGIN DESCRIPTION:
STRICKLAND BRANCH 19.0
END DESCRIPTION:
XS GIS Cut Line= 3
      3714749.61      10744360.2      3714999.61     10744760.19
      3715110.02     10745086.63
#Sta/Elev= 30
  4516.7  406.24  4524.4  404.03    4611  394.64  4618.7  391.98  4639.9  391.42
  4682.4  385.65  4705.4  382.37  4776.7  378.96  4835.1  375.19  4965.4  375.01
  4980.7  373.89  4982.4   372.1  4985.2   371.6  4988.4   372.1  4998.8  372.15
  5004.1  374.49  5020.1  375.77  5030.3  379.62  5035.5  378.18  5041.2  380.01
  5051.7  382.97    5067  384.03  5072.8  386.59  5093.2  388.49    5156  393.68
  5161.3   392.1  5187.5  395.44  5192.8  393.94  5273.8  397.12    5333  398.08
#Mann= 6 ,-1 , 0
  4516.7     .05       0  4682.4     .16       0  4982.4     .07       0
  4988.4     .16       0  5192.8     .16       0  5273.8     .12       0
Bank Sta=4776.7,5041.2
XS Rating Curve= 0 ,0
Exp/Cntr=0.3,0.1

Type RM Length L Ch R = 1 ,8532    ,425,425,425
BEGIN DESCRIPTION:
STRICKLAND BRANCH 18.0
END DESCRIPTION:
XS GIS Cut Line= 3
       3714399.6     10744610.18      3714649.61     10744960.19
      3715049.59     10745310.17
#Sta/Elev= 30
  4580.1  416.22  4637.9  407.78  4652.6  404.59  4658.8  401.58  4688.3  399.26
  4765.7  384.41  4776.3  384.01  4801.3  380.38  4838.2  377.81  4887.3   373.9
  4973.4  373.29    4982  368.05  4988.1   369.1  4993.7  367.25  4996.5  366.75
  4999.7  367.25  5002.9  367.57  5007.2     374  5013.5     374  5017.3  371.18
    5024  375.45  5066.7  375.75  5074.3  373.21  5080.9  375.54  5102.8  375.38
  5123.6  377.36  5229.9  384.36  5265.1  388.87  5345.8  394.19  5541.7  407.44
#Mann= 5 ,-1 , 0
  4580.1     .05       0  4776.3     .12       0  4993.7     .07       0
  4999.7     .12       0  5345.8     .16       0
Bank Sta=4838.2,5123.6
XS Rating Curve= 0 ,0
Exp/Cntr=0.3,0.1

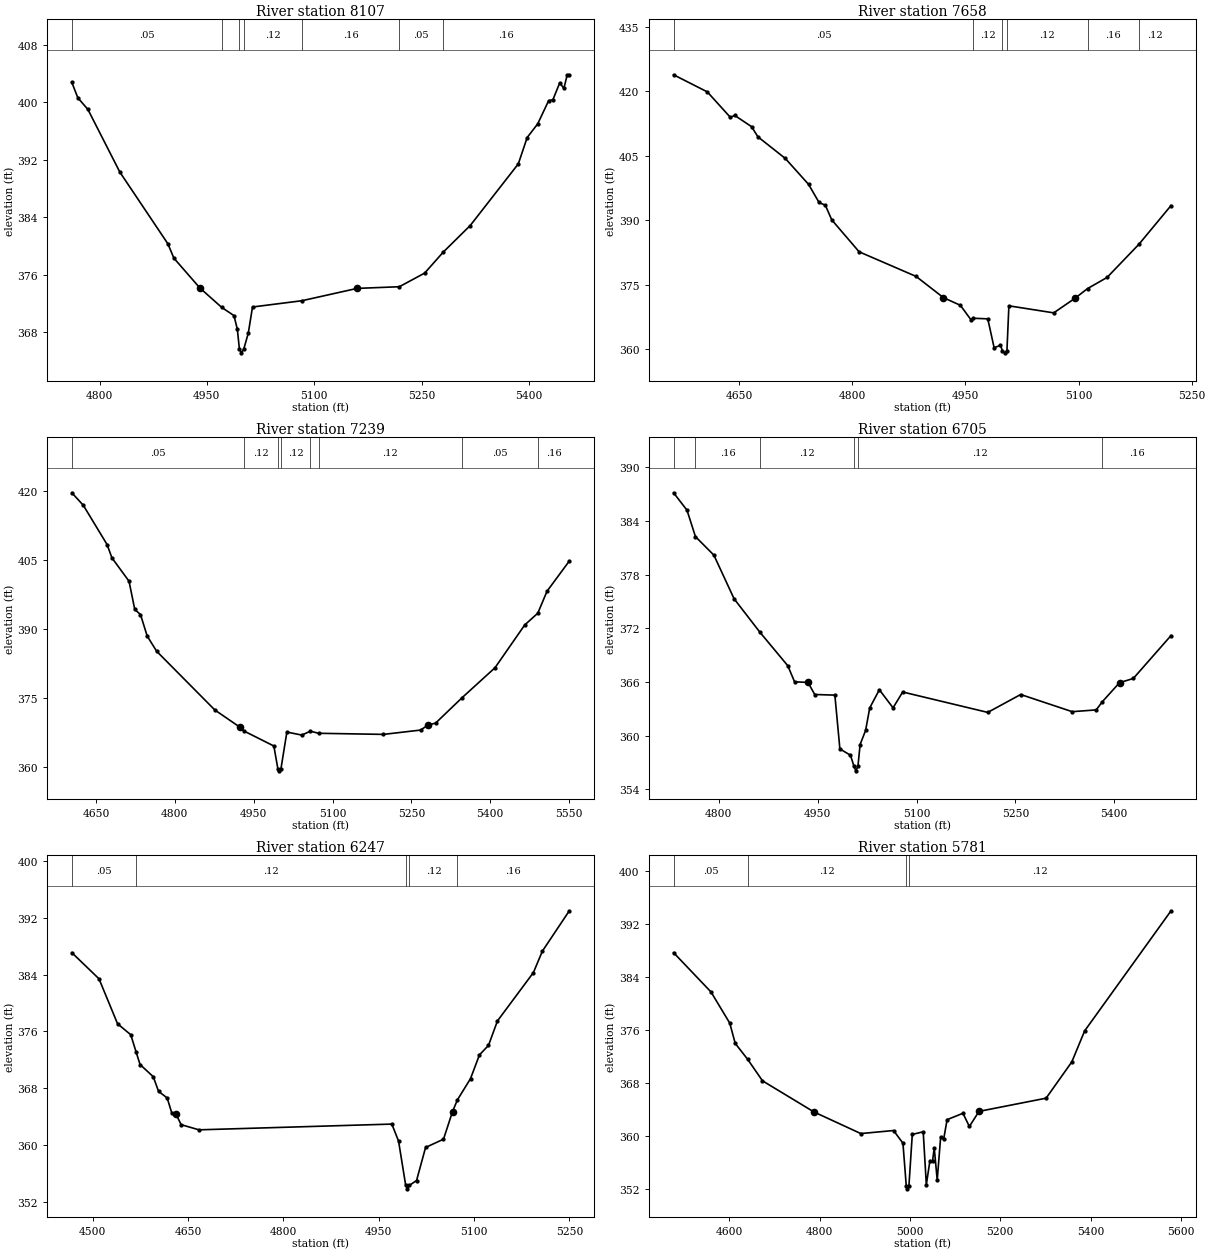
Type RM Length L Ch R = 1 ,8107    ,449,449,449
BEGIN DESCRIPTION:
STRICKLAND BRANCH 17.0
END DESCRIPTION:
XS GIS Cut Line= 3
      3714099.59     10745060.18      3714299.61     10745160.19
       3714549.6     10745560.17
#Sta/Elev= 30
  4761.3  402.76  4769.7  400.62  4783.7  399.01  4828.4  390.28  4895.5  380.31
  4903.9  378.31  4940.2  374.16  4970.7  371.46  4987.9  370.31  4992.6  368.41
  4995.5  365.63  4998.2  365.13  5001.5  365.63  5007.9  367.87  5013.8  371.51
  5082.7  372.38    5160   374.1    5219  374.33  5254.4  376.23  5280.5  379.16
  5318.1  382.85  5385.3  391.43  5397.7   395.1  5412.4     397  5427.7  400.23
  5433.6  400.35  5443.1  402.68    5449  401.95  5453.7  403.83  5456.6  403.83
#Mann= 7 ,-1 , 0
  4761.3     .05       0  4970.7     .12       0  4995.5     .07       0
  5001.5     .12       0  5082.7     .16       0    5219     .05       0
  5280.5     .16       0
Bank Sta=4940.2,5160
XS Rating Curve= 0 ,0
Exp/Cntr=0.3,0.1

Type RM Length L Ch R = 1 ,7658    ,419,419,419
BEGIN DESCRIPTION:
STRICKLAND BRANCH 16.0
END DESCRIPTION:
XS GIS Cut Line= 3
      3713699.63      10745310.2      3714099.61     10745510.19
      3714249.59     10745660.17
#Sta/Elev= 30
  4563.3  423.86    4608  419.88  4638.7  413.92  4644.3   414.4  4666.7  411.77
  4675.1  409.41  4711.4  404.37  4742.2  398.34  4756.1  394.12  4764.5  393.46
  4772.9  390.08  4809.2  382.63  4884.7   376.9    4921  371.95  4943.4  370.17
  4957.4  366.81  4960.5  367.15  4979.7  367.02  4988.1  360.31  4996.5  360.82
  4999.1   359.6  5001.9   359.1  5005.1   359.6  5007.7  370.05  5067.1  368.41
  5095.3  371.81  5111.9  374.06  5137.8  376.66    5180  384.38  5222.6  393.41
#Mann= 6 ,-1 , 0
  4563.3     .05       0  4960.5     .12       0  4999.1     .07       0
  5005.1     .12       0  5111.9     .16       0    5180     .12       0
Bank Sta=4921,5095.3
XS Rating Curve= 0 ,0
Exp/Cntr=0.3,0.1

Type RM Length L Ch R = 1 ,7239    ,534,534,534
BEGIN DESCRIPTION:
STRICKLAND BRANCH 15.0
END DESCRIPTION:
XS GIS Cut Line= 3
       3713649.6     10745410.17      3713799.61     10745760.19
      3714199.62      10746160.2
#Sta/Elev= 30
    4604  419.71  4625.8  416.98  4671.1  408.42  4680.2  405.54  4712.8  400.44
  4723.7  394.29  4734.6  393.19  4747.3  388.51  4765.4  385.18    4876   372.4
  4923.2  368.69  4931.4  367.82  4988.3  364.55  4995.9  359.64  4998.7  359.14
  5001.9  359.64  5013.1  367.59  5041.4  366.93  5057.9  367.78  5073.4  367.32
  5196.9  367.08  5267.6  368.02  5281.8  369.14  5295.9  369.52  5346.8  375.11
  5409.1   381.6  5465.6  390.91  5490.5  393.48  5508.1  398.27  5550.5  404.85
#Mann= 8 ,-1 , 0
    4604     .05       0  4931.4     .12       0  4995.9     .07       0
  5001.9     .12       0  5057.9     .16       0  5073.4     .12       0
  5346.8     .05       0  5490.5     .16       0
Bank Sta=4923.2,5281.8
XS Rating Curve= 0 ,0
Exp/Cntr=0.3,0.1

Type RM Length L Ch R = 1 ,6705    ,458,458,458
BEGIN DESCRIPTION:
STRICKLAND BRANCH 14.0
END DESCRIPTION:
XS GIS Cut Line= 3
      3713399.61     10745860.17      3713449.61     10746110.19
      3713749.63     10746510.21
#Sta/Elev= 30
  4731.3  387.15  4751.7   385.2  4764.5  382.25  4792.5  380.18  4823.1  375.31
  4862.2  371.58  4904.7  367.82  4914.9  366.03  4935.3  365.96  4945.5  364.61
  4976.1  364.54  4983.7  358.53  4999.8  357.82  5005.1  356.58  5007.9  356.08
  5011.1  356.58  5014.4  359.02  5022.7  360.59    5029  363.11  5043.6  365.14
  5064.4  363.12    5079  364.89  5208.1  362.61  5258.1  364.61  5336.3  362.69
  5372.7  362.89  5382.1  363.81  5408.1  365.93    5429   366.4  5486.3   371.2
#Mann= 6 ,-1 , 0
  4731.3     .12       0  4764.5     .16       0  4862.2     .12       0
  5005.1     .07       0  5011.1     .12       0  5382.1     .16       0
Bank Sta=4935.3,5408.1
XS Rating Curve= 0 ,0
Exp/Cntr=0.3,0.1

Type RM Length L Ch R = 1 ,6247    ,466,466,466
BEGIN DESCRIPTION:
STRICKLAND BRANCH 13.0
END DESCRIPTION:
XS GIS Cut Line= 3
      3713049.62     10746210.19      3713449.61     10746510.19
      3713649.59     10746710.16
#Sta/Elev= 30
  4467.2   387.1  4509.9  383.42  4539.1  377.09  4559.9  375.54  4568.1  373.17
  4574.5  371.35  4595.3  369.63  4603.6  367.57  4617.2  366.64  4624.5   364.5
  4630.7  364.44  4639.1  362.88  4667.2  362.15  4970.7  362.96  4981.3  360.56
  4992.5  354.34  4995.2  353.84  4998.5  354.34  5009.6  355.01  5023.8  359.67
    5052  360.83  5066.2  364.72  5073.9  366.37  5094.5  369.36  5108.6  372.71
  5122.8  374.04  5136.9  377.49  5193.5   384.3  5207.6  387.32    5250     393
#Mann= 5 ,-1 , 0
  4467.2     .05       0  4568.1     .12       0  4992.5     .07       0
  4998.5     .12       0  5073.9     .16       0
Bank Sta=4630.7,5066.2
XS Rating Curve= 0 ,0
Exp/Cntr=0.3,0.1

Type RM Length L Ch R = 1 ,5781    ,431,431,431
BEGIN DESCRIPTION:
STRICKLAND BRANCH 12.0
END DESCRIPTION:
XS GIS Cut Line= 3
      3712999.61     10746260.21      3713149.61     10746810.19
      3713499.63     10747210.21
#Sta/Elev= 30
  4476.5  387.73  4559.4   381.8  4600.9   377.1    4613  374.04  4640.5  371.64
  4673.4  368.39  4787.4  363.69  4891.1  360.43  4963.6  360.89  4984.4  358.98
  4991.7  352.59  4994.5  352.09  4997.7  352.59  5005.1   360.3  5029.3   360.7
  5036.2  352.72    5044  356.26  5049.9  356.26  5053.7  358.27  5060.3  353.41
  5067.9  359.89  5074.6  359.59  5082.2  362.53  5117.3  363.49  5131.5   361.5
  5152.9  363.78  5301.4  365.77  5358.4  371.25  5386.8  375.93  5578.1  394.05
#Mann= 4 ,-1 , 0
  4476.5     .05       0  4640.5     .12       0  4991.7     .07       0
  4997.7     .12       0
Bank Sta=4787.4,5152.9
XS Rating Curve= 0 ,0
Exp/Cntr=0.3,0.1

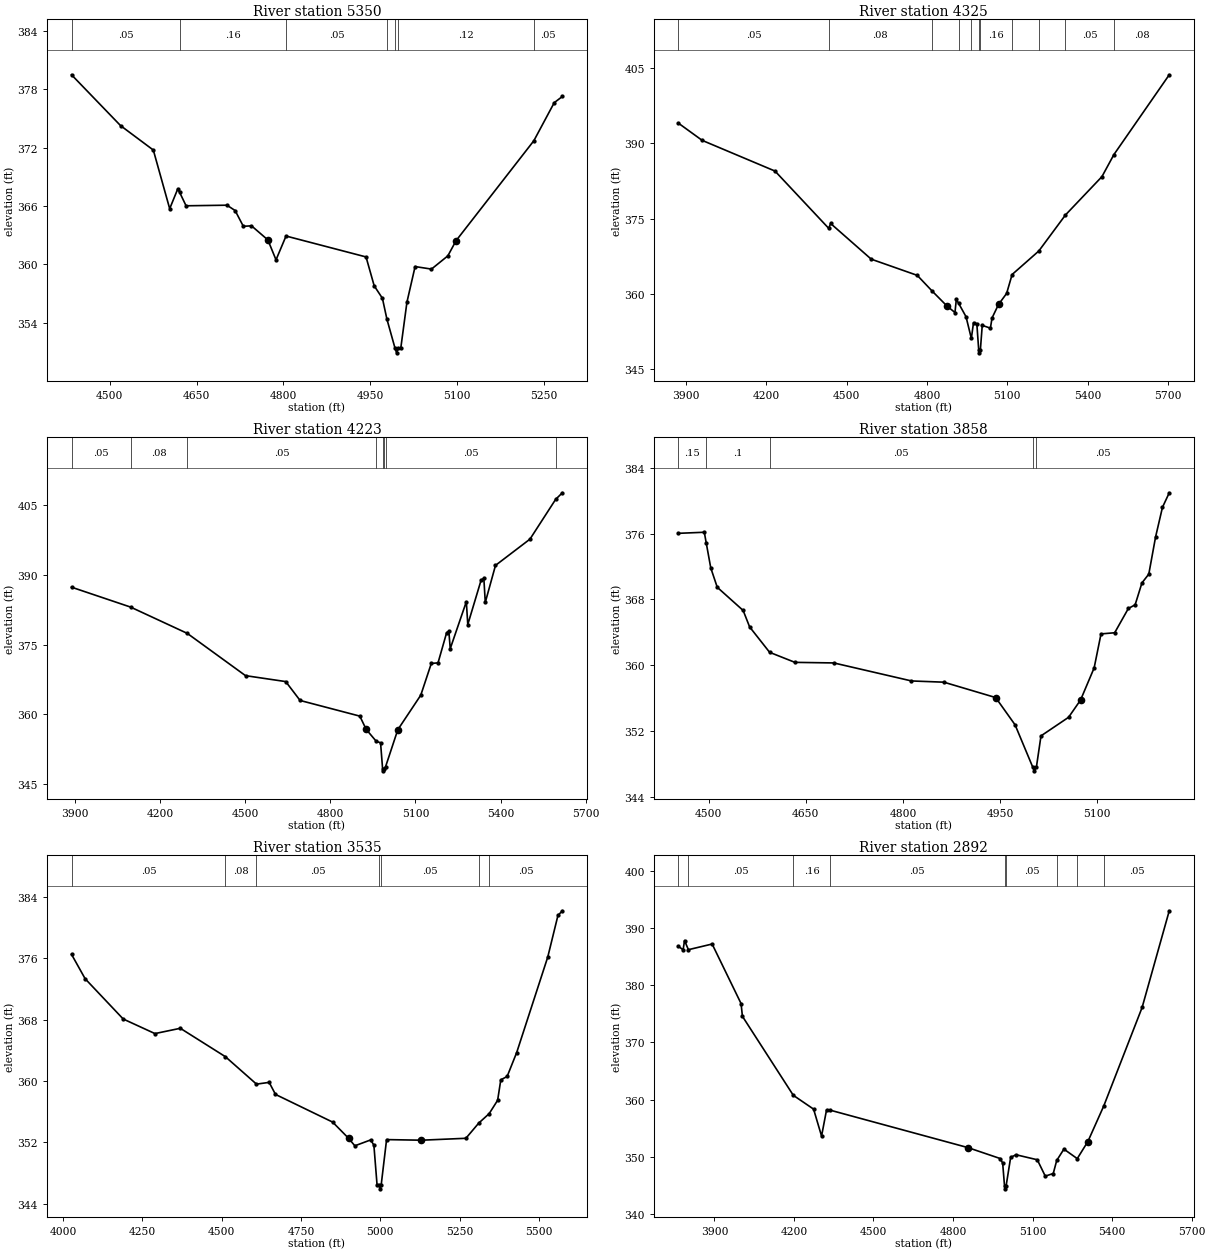
Type RM Length L Ch R = 1 ,5350    ,1025,1025,1025
BEGIN DESCRIPTION:
STRICKLAND BRANCH 11.0
END DESCRIPTION:
XS GIS Cut Line= 3
      3712349.63     10746510.21      3712749.61     10746910.19
      3712949.61     10747110.19
#Sta/Elev= 30
  4433.8  379.49  4518.6  374.26  4575.2  371.75  4603.5  365.72  4617.6  367.78
  4620.7   367.4  4631.8  366.02  4702.5  366.08  4716.6  365.53  4730.8  363.91
  4744.9  363.96  4773.2  362.51  4787.3  360.46  4804.6  362.91  4942.9  360.76
    4957  357.79  4971.2  356.51    4979  354.36  4992.9   351.4  4995.7   350.9
  4998.9   351.4    5003   351.4  5013.6  356.11  5027.7  359.77    5056  359.51
  5084.3  360.87  5098.5  362.43    5233  372.71  5268.2  376.62  5282.3  377.26
#Mann= 7 ,-1 , 0
  4433.8     .05       0  4620.7     .16       0  4804.6     .05       0
    4979     .12       0  4992.9     .07       0  4998.9     .12       0
    5233     .05       0
Bank Sta=4773.2,5098.5
XS Rating Curve= 0 ,0
Exp/Cntr=0.3,0.1

Type RM Length L Ch R = 1 ,4325    ,102,102,102
BEGIN DESCRIPTION:
STRICKLAND BRANCH 10.0
END DESCRIPTION:
XS GIS Cut Line= 2
      3711961.38     10746278.21      3712232.21     10748090.69
#Sta/Elev= 30
  3872.3  394.03    3961   390.6  4232.9  384.48  4433.6  373.05  4440.5  374.03
  4592.2  366.91  4764.1  363.68  4819.1  360.58  4875.3  357.55  4904.9  356.27
  4909.9  358.89  4918.8  358.08  4946.1  355.44    4966   351.1  4974.1  354.26
  4986.5  354.02  4993.6  348.73  4996.4  348.23  4999.6  348.73  5006.7  353.71
  5037.1  353.15  5043.3  355.19  5067.4  357.87  5097.7  360.08  5118.2  363.85
  5217.9  368.54  5317.5  375.73  5453.6  383.37  5498.3  387.77  5704.9  403.68
#Mann= 11 ,-1 , 0
  3872.3     .05       0  4433.6     .08       0  4819.1     .05       0
  4918.8     .08       0    4966     .16       0  4993.6     .07       0
  4999.6     .16       0  5118.2     .05       0  5217.9     .08       0
  5317.5     .05       0  5498.3     .08       0
Bank Sta=4875.3,5067.4
XS Rating Curve= 0 ,0
Exp/Cntr=0.3,0.1

Type RM Length L Ch R = 1 ,4223    ,365,365,365
BEGIN DESCRIPTION:
STRICKLAND BRANCH 9.0
END DESCRIPTION:
XS GIS Cut Line= 2
        3711852.     10746314.66      3712128.05     10748023.01
#Sta/Elev= 30
  3887.6  387.37  4095.7  383.08  4295.6  377.41    4501  368.29  4642.8  367.01
  4693.4  362.94    4904  359.56  4926.4   356.7  4962.2  354.11  4977.1  353.82
  4984.2  348.26    4987  347.76  4990.2  348.26    4995  348.69  5037.9  356.63
  5118.9  364.08    5156  370.92  5179.7  371.05  5210.1  377.57  5217.8  377.86
  5222.8  374.12  5279.5  384.24  5284.6  379.31  5331.6  388.89  5341.2   389.3
  5346.3  384.09  5382.3  392.07  5503.8  397.73  5594.5  406.32  5618.1  407.73
#Mann= 8 ,-1 , 0
  3887.6     .05       0  4095.7     .08       0  4295.6     .05       0
  4962.2     .08       0  4984.2     .04       0  4990.2     .08       0
    4995     .05       0  5594.5     .08       0
Bank Sta=4926.4,5037.9
XS Rating Curve= 0 ,0
Exp/Cntr=0.3,0.1

Type RM Length L Ch R = 1 ,3858    ,323,323,323
BEGIN DESCRIPTION:
STRICKLAND BRANCH 8.0
END DESCRIPTION:
XS GIS Cut Line= 3
      3711699.61     10746960.21      3711699.61     10747560.19
      3711749.61     10747710.19
#Sta/Elev= 30
  4453.2  376.03  4493.2  376.16  4496.1   374.9  4503.2  371.82  4513.2  369.47
  4553.2  366.65  4563.2  364.65  4594.1  361.56  4633.2  360.34  4693.2  360.27
  4813.2  358.08  4863.2  357.93  4943.2  356.06  4973.2  352.74  5000.2  347.65
  5002.9  347.15  5006.2  347.65  5013.2   351.4  5055.8  353.66  5074.3  355.76
  5095.3  359.67  5105.9   363.8    5127  363.94  5148.1  366.89  5158.6  367.34
  5169.1     370  5179.7  371.07  5190.2   375.6  5200.8  379.19  5211.3  380.96
#Mann= 5 ,-1 , 0
  4453.2     .15       0  4496.1      .1       0  4594.1     .05       0
  5000.2     .03       0  5006.2     .05       0
Bank Sta=4943.2,5074.3
XS Rating Curve= 0 ,0
Exp/Cntr=0.3,0.1

Type RM Length L Ch R = 1 ,3535    ,643,643,643
BEGIN DESCRIPTION:
STRICKLAND BRANCH 7.0
END DESCRIPTION:
XS GIS Cut Line= 2
      3711409.29     10746507.34      3711435.33     10748054.22
#Sta/Elev= 30
    4027   376.5  4069.9  373.32  4189.9  368.07  4289.9  366.17  4369.9  366.86
  4511.9  363.16    4610  359.58  4649.9  359.81  4669.9  358.24    4850  354.63
    4900  352.53    4920  351.54    4970  352.31    4980  351.62    4990  346.44
    4997  346.43  4999.7  345.93    5003  346.43    5020  352.35    5130  352.27
    5270  352.52  5310.7  354.51  5343.3  355.73    5370  357.47    5380  360.14
    5400  360.58  5430.1   363.7  5528.1  376.16  5560.1  381.57  5574.1  382.18
#Mann= 7 ,-1 , 0
    4027     .05       0  4511.9     .08       0    4610     .05       0
    4997     .03       0    5003     .05       0  5310.7     .12       0
  5343.3     .05       0
Bank Sta=4900,5130
XS Rating Curve= 0 ,0
Exp/Cntr=0.3,0.1

Type RM Length L Ch R = 1 ,2892    ,480,480,480
BEGIN DESCRIPTION:
STRICKLAND BRANCH 6.0
END DESCRIPTION:
XS GIS Cut Line= 2
      3710862.42     10746262.57      3711034.24     10748105.78
#Sta/Elev= 30
  3764.3  386.79    3782  386.18  3787.5   387.8    3802   386.2  3891.5  387.19
  4000.7  376.78  4005.7  374.56  4197.7  360.75  4274.1  358.34  4304.2  353.63
    4323   358.2  4335.7  358.17  4856.6  351.61  4977.6  349.71  4987.2  348.92
  4994.2  344.91    4997  344.41  5000.2  344.91  5017.3   349.9  5037.4  350.37
  5117.8  349.49  5147.9  346.63    5178  347.09  5191.1  349.37  5218.2  351.35
  5268.5  349.69  5308.6  352.68  5368.3  358.87  5513.1   376.1  5615.5     393
#Mann= 9 ,-1 , 0
  3764.3     .16       0    3802     .05       0  4197.7     .16       0
  4335.7     .05       0  4994.2     .03       0  5000.2     .05       0
  5191.1     .12       0  5268.5     .16       0  5368.3     .05       0
Bank Sta=4856.6,5308.6
XS Rating Curve= 0 ,0
Exp/Cntr=0.3,0.1

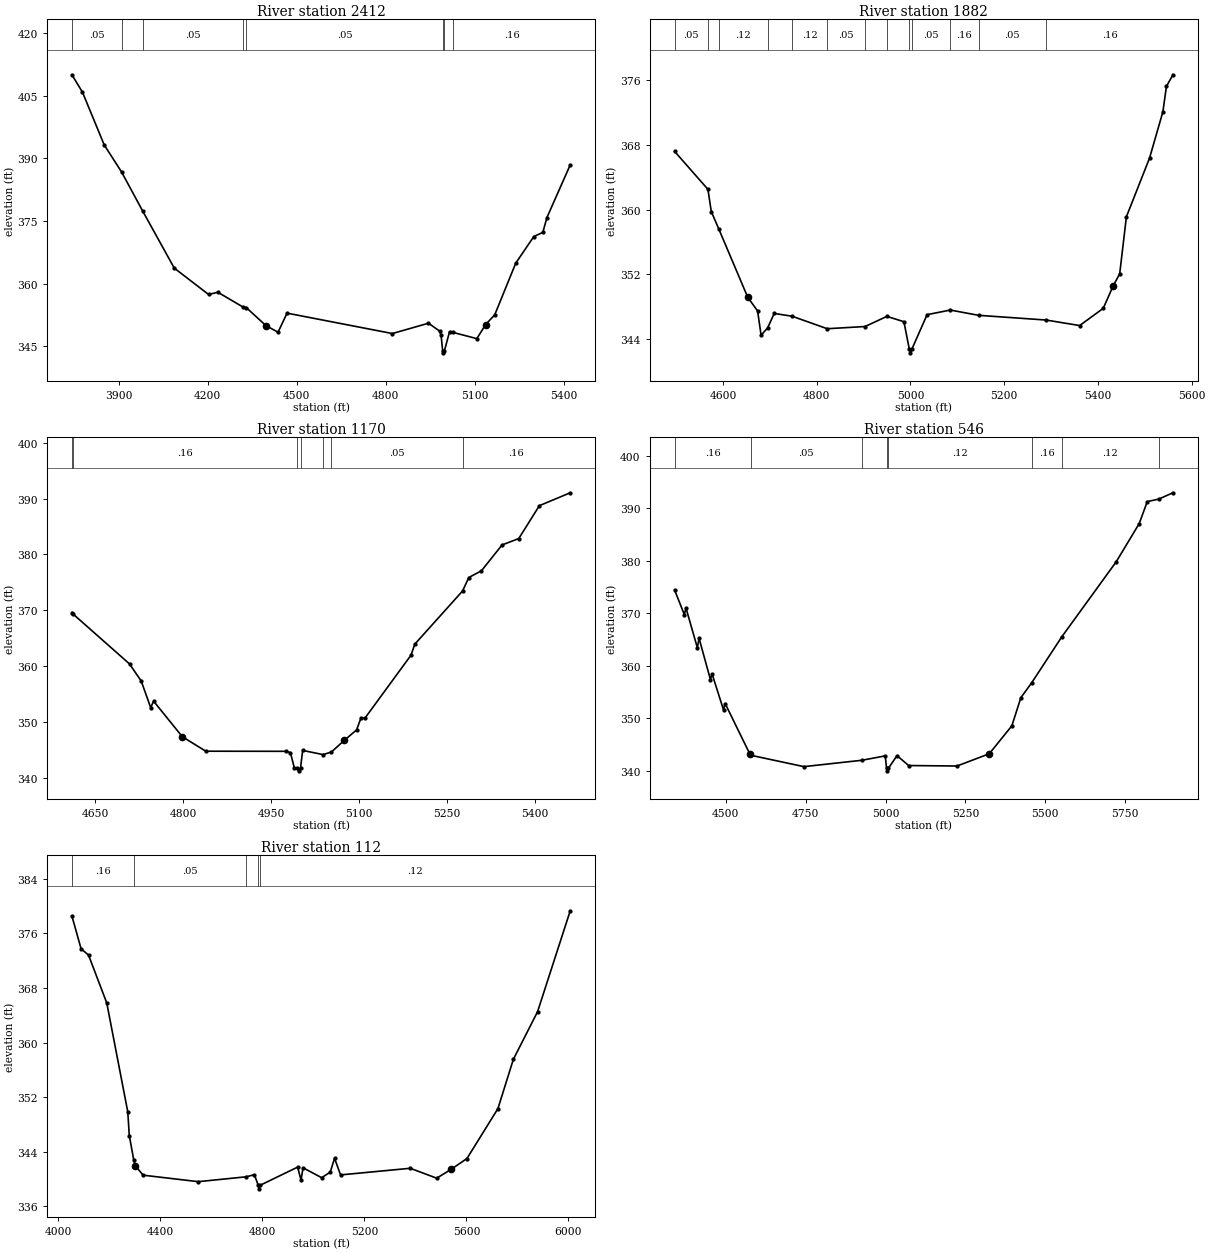
Type RM Length L Ch R = 1 ,2412    ,530,530,530
BEGIN DESCRIPTION:
STRICKLAND BRANCH 5.0
END DESCRIPTION:
XS GIS Cut Line= 2
       3710346.8     10746325.09      3710628.04     10747981.28
#Sta/Elev= 30
  3742.5     410  3778.1  405.84  3851.5   393.2  3909.8  386.76    3981   377.4
  4087.6  363.73  4203.2  357.42  4234.5  357.95  4319.2  354.42  4330.3  354.28
  4396.8  349.95  4437.4  348.39  4467.8  352.95  4822.8  348.07  4944.6  350.54
  4981.9  348.66    4987   347.7  4992.3  343.95    4995  343.45  4998.3  343.95
  5015.6  348.51  5027.2  348.34  5107.6  346.85  5137.3  350.23  5167.9  352.55
  5238.7  364.91  5299.6  371.29    5330  372.27  5343.7  375.81  5422.4  388.44
#Mann= 8 ,-1 , 0
  3742.5     .05       0  3909.8     .16       0    3981     .05       0
  4319.2     .16       0  4330.3     .05       0  4992.3     .03       0
  4998.3     .05       0  5027.2     .16       0
Bank Sta=4396.8,5137.3
XS Rating Curve= 0 ,0
Exp/Cntr=0.3,0.1

Type RM Length L Ch R = 1 ,1882    ,712,712,712
BEGIN DESCRIPTION:
STRICKLAND BRANCH 4.0
END DESCRIPTION:
XS GIS Cut Line= 3
      3709699.58     10747160.16      3710099.61     10747510.19
      3710449.64     10747910.22
#Sta/Elev= 30
  4496.9  367.16  4568.1  362.48  4575.2  359.75  4591.7  357.54  4653.1  349.18
    4674  347.51  4681.5  344.52  4695.4  345.42  4709.5   347.2  4747.5  346.86
  4822.6  345.32  4903.2  345.59  4949.9  346.84  4986.2  346.18  4997.5  342.85
  5000.2  342.35  5003.5  342.85  5035.6  347.05  5085.1  347.62  5145.4  346.97
  5289.3  346.39  5361.1  345.71  5411.4  347.83  5432.3  350.56  5446.5  352.09
  5460.8  359.11  5510.1  366.32  5538.6  372.03  5546.2  375.16    5560  376.59
#Mann= 13 ,-1 , 0
  4496.9     .05       0  4568.1     .16       0  4591.7     .12       0
  4695.4     .16       0  4747.5     .12       0  4822.6     .05       0
  4903.2     .12       0  4949.9     .05       0  4997.5     .03       0
  5003.5     .05       0  5085.1     .16       0  5145.4     .05       0
  5289.3     .16       0
Bank Sta=4653.1,5432.3
XS Rating Curve= 0 ,0
Exp/Cntr=0.3,0.1

Type RM Length L Ch R = 1 ,1170    ,624,624,624
BEGIN DESCRIPTION:
STRICKLAND BRANCH 3.0
END DESCRIPTION:
XS GIS Cut Line= 3
       3709649.2     10747412.08      3709638.78     10747719.36
       3710003.4     10748120.44
#Sta/Elev= 30
  4610.6  369.56  4612.5  369.33  4708.8  360.38  4728.8   357.3  4744.9  352.55
  4749.9   353.7  4798.8  347.33  4838.8  344.73  4975.7  344.71  4983.1  344.48
  4989.8  341.72  4994.3  341.71    4997  341.21  5000.3  341.71    5004  344.87
  5038.9  344.12    5053  344.59    5075  346.68  5095.9  348.55  5103.4  350.69
  5110.1  350.65  5188.5  361.92  5195.3  363.94  5276.6  373.46  5287.2  375.87
  5308.8  377.08  5343.9  381.71  5372.3  382.85  5407.5  388.75  5460.1  391.06
#Mann= 7 ,-1 , 0
  4610.6     .05       0  4612.5     .16       0  4994.3     .07       0
  5000.3     .16       0  5038.9     .12       0    5053     .05       0
  5276.6     .16       0
Bank Sta=4798.8,5075
XS Rating Curve= 0 ,0
Exp/Cntr=0.3,0.1

Type RM Length L Ch R = 1 ,546     ,434,434,434
BEGIN DESCRIPTION:
STRICKLAND BRANCH 2.0
END DESCRIPTION:
XS GIS Cut Line= 4
      3709362.75     10747557.88      3709227.32     10748089.16
      3709315.87     10748234.99      3710149.15     10748349.57
#Sta/Elev= 30
  4339.6  374.44  4370.2  369.74  4375.3  371.01    4411  363.41  4416.2  365.25
  4451.9  357.36  4457.1  358.44  4492.8   351.6    4498   352.8  4574.6  343.27
  4577.9  342.96  4744.5  340.79  4925.7     342  4999.2  342.84  5003.1  340.49
  5005.8  339.99  5009.1  340.49    5036  342.89  5072.3     341  5223.8  340.91
  5324.7  343.24  5395.4  348.56  5423.8  353.94  5457.8  356.78  5551.4  365.48
    5722  379.79  5794.1  387.07  5819.3  391.26  5855.3  391.74  5899.6  392.94
#Mann= 8 ,-1 , 0
  4339.6     .16       0  4577.9     .05       0  4925.7     .12       0
  5003.1     .07       0  5009.1     .12       0  5457.8     .16       0
  5551.4     .12       0  5855.3     .16       0
Bank Sta=4574.6,5324.7
XS Rating Curve= 0 ,0
Exp/Cntr=0.3,0.1

Type RM Length L Ch R = 1 ,112     ,0,0,0
BEGIN DESCRIPTION:
STRICKLAND BRANCH 1.0
END DESCRIPTION:
XS GIS Cut Line= 4
      3709258.56     10747542.31      3708925.24     10748344.36
      3708966.91     10748458.95      3709920.04     10748604.78
#Sta/Elev= 30
  4052.6  378.53  4088.6  373.73  4117.9   372.8  4189.4  365.79  4271.8  349.85
  4277.7  346.38  4294.9  342.87  4301.1  341.97  4331.9  340.58  4548.4  339.63
  4735.5  340.34  4768.4  340.65  4783.7  339.08  4786.4  338.58  4789.7  339.08
    4938  341.76  4951.3  339.85  4959.3  341.66  5032.4  340.21    5066  341.03
  5082.8  343.05  5106.5  340.62  5379.7  341.59  5483.5  340.14  5541.5  341.47
  5602.2  343.02  5723.6  350.32  5784.3  357.55  5879.1  364.51  6007.3  379.29
#Mann= 5 ,-1 , 0
  4052.6     .16       0  4294.9     .05       0  4735.5     .12       0
  4783.7     .07       0  4789.7     .12       0
Bank Sta=4301.1,5541.5
XS Rating Curve= 0 ,0
Exp/Cntr=0.3,0.1

Chan Stop Cuts=-1
Use User Specified Reach Order=0
Composite Channel Slope=5