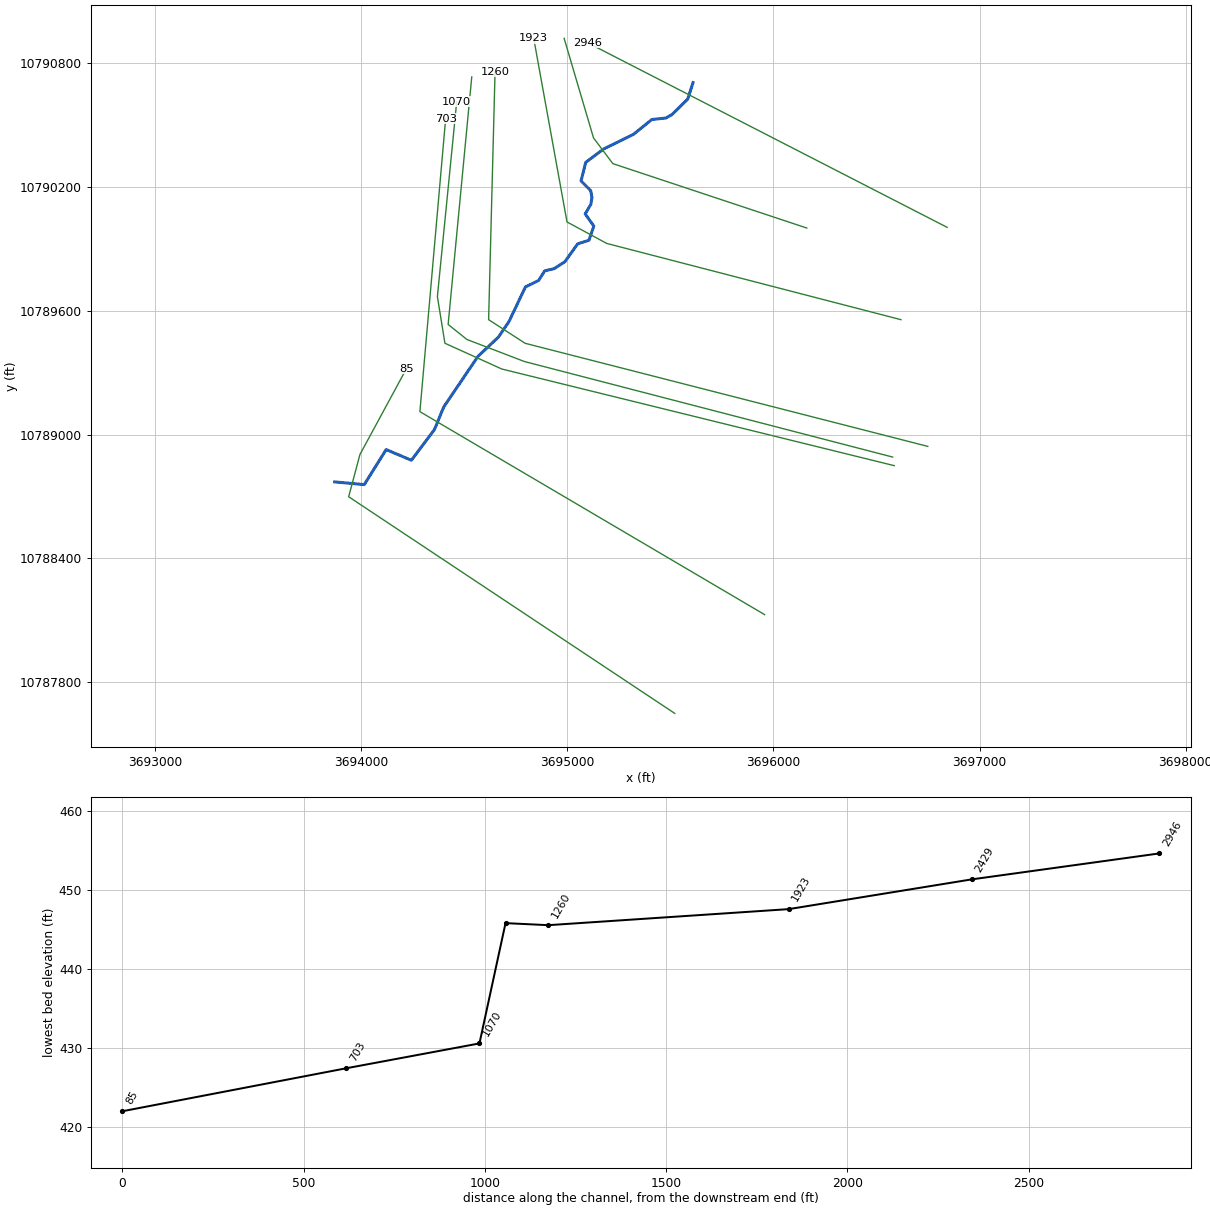
--- UNT 002 IN CACR.prj (project) ---

Proj Title=UNT 002 IN CACR Base Level Engineering
Current Plan=p01
Default Exp/Contr=0.3,0.1
English Units
Geom File=g01
Flow File=f01
Plan File=p01
BEGIN DESCRIPTION:
UNT 002 IN CACR
END DESCRIPTION:

--- UNT 002 IN CACR.p01 (plan) ---

Plan Title=Multiple Run
Short Identifier=Multiple
Geom File=g01
Flow File=f01
Subcritical Flow
K Sum by GR= 0
Std Step Tol= 0.01
Critical Tol= 0.01
Num of Std Step Trials= 20
Max Error Tol= 0.3
Flow Tol Ratio= 0.001
Split Flow NTrial= 30
Split Flow Tol= 0.02
Split Flow Ratio= 0.02
Log Output Level= 0
Friction Slope Method= 1
Unsteady Friction Slope Method= 2
Unsteady Bridges Friction Slope Method= 1
Parabolic Critical Depth
Global Vel Dist=  1 , 1 , 1
Global Log Level= 0
CheckData=True
Encroach Param= -1, 0, 0, 0
BEGIN DESCRIPTION:
Multiple Run
END DESCRIPTION:

--- UNT 002 IN CACR.f01 (steady flow) ---

Flow Title=Multiple
Number of Profiles=7
Profile Names=10-year,25-year,50-year,1pct_min,100-year,1pct_plu,500-year
River Rch & RM= UNT 002 IN CACR,Reach-1,2946
     590     804     983     882    1193    1613    1760
Boundary for River Rch & Prof#=UNT 002 IN CACR,Reach-1,1
Up Type=0
Dn Type=3
Dn Slope=0.005
Boundary for River Rch & Prof#=UNT 002 IN CACR,Reach-1,2
Up Type=0
Dn Type=3
Dn Slope=0.005
Boundary for River Rch & Prof#=UNT 002 IN CACR,Reach-1,3
Up Type=0
Dn Type=3
Dn Slope=0.005
Boundary for River Rch & Prof#=UNT 002 IN CACR,Reach-1,4
Up Type=0
Dn Type=3
Dn Slope=0.005
Boundary for River Rch & Prof#=UNT 002 IN CACR,Reach-1,5
Up Type=0
Dn Type=3
Dn Slope=0.005
Boundary for River Rch & Prof#=UNT 002 IN CACR,Reach-1,6
Up Type=0
Dn Type=3
Dn Slope=0.005
Boundary for River Rch & Prof#=UNT 002 IN CACR,Reach-1,7
Up Type=0
Dn Type=3
Dn Slope=0.005

--- UNT 002 IN CACR.g01 (geometry) ---

Geom Title=Existing Conditions

River Reach=UNT 002 IN CACR,Reach-1
Reach XY= 30
      3695610.54     10790706.96      3695584.75     10790627.00
      3695508.75     10790552.00      3695478.50     10790535.00
      3695410.75     10790528.00      3695321.75     10790456.00
      3695177.00     10790385.00      3695090.00     10790320.00
      3695067.25     10790230.00      3695114.00     10790183.00
      3695120.25     10790150.00      3695115.00     10790117.00
      3695087.25     10790070.00      3695129.25     10790011.00
      3695105.50     10789942.00      3695051.25     10789925.00
      3694988.94     10789838.20      3694936.86     10789804.35
      3694891.28     10789793.93      3694861.34     10789747.06
      3694797.53     10789715.81      3694718.67     10789549.72
      3694667.00     10789473.00      3694567.25     10789379.00
      3694401.50     10789134.00      3694356.25     10789024.00
      3694244.25     10788875.00      3694122.00     10788927.00
      3694015.75     10788757.00      3693872.50     10788770.00

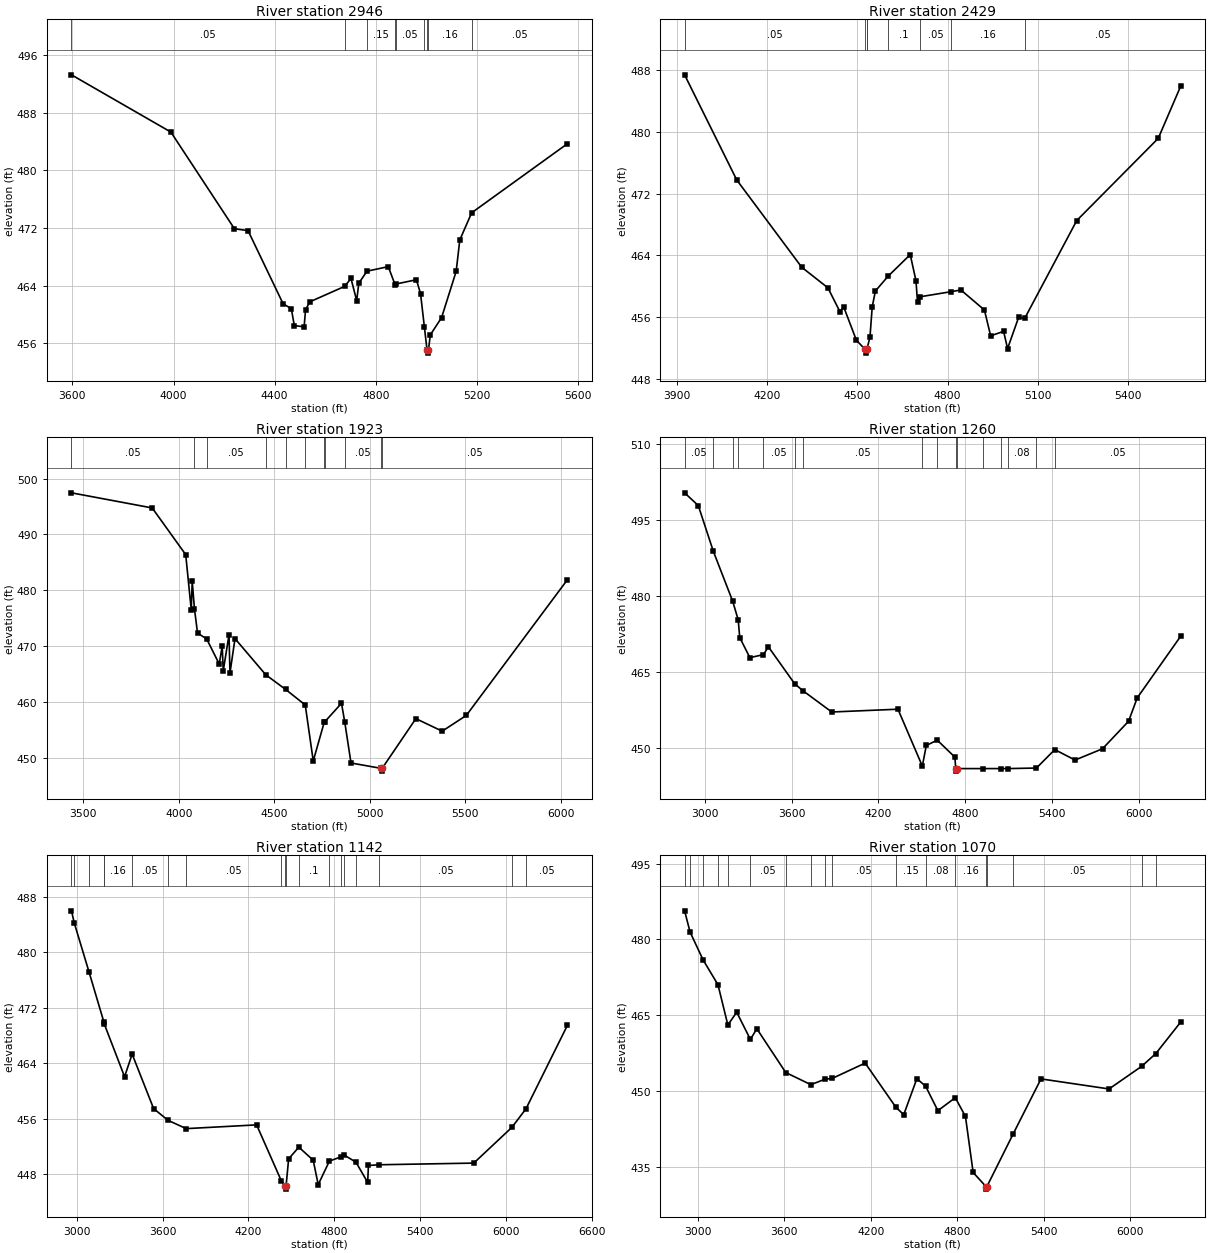
Type RM Length L Ch R = 1,2946,517,517,517
BEGIN DESCRIPTION:
UNT 002 IN CACR 6.0
END DESCRIPTION:
XS GIS Cut Line= 2
      3696842.89     10790004.91      3695098.04     10790900.78
#Sta/Elev= 30
  3596.5  493.27  3989.6  485.32  4240.9  471.89  4294.6  471.64  4433.4  461.47
  4465.8  460.80  4477.7  458.45  4516.5  458.27  4522.1  460.62  4538.7  461.74
  4676.7  463.89  4701.8  464.99  4724.3  461.91  4732.8  464.33  4765.0  466.00
  4849.3  466.63  4876.3  464.10  4878.5  464.21  4960.4  464.81  4976.8  462.90
  4992.1  458.23  5002.3  455.12  5005.1  454.62  5008.3  455.12  5015.6  457.16
  5060.0  459.55  5117.7  465.97  5132.1  470.34  5179.0  474.11  5557.9  483.71
#Mann=9,-1,0
  3596.5    0.05       0  4676.7     0.1       0  4765.0    0.15       0
  4876.3    0.08       0  4878.5    0.05       0  4992.1    0.16       0
  5002.3    0.07       0  5008.3    0.16       0  5179.0    0.05       0
Bank Sta=5002.3,5008.3
Exp/Cntr=0.3,0.1

Type RM Length L Ch R = 1,2429,506,506,506
BEGIN DESCRIPTION:
UNT 002 IN CACR 5.0
END DESCRIPTION:
XS GIS Cut Line= 4
      3696162.31     10790001.45      3695221.34     10790313.95
      3695127.59     10790438.95      3694985.22     10790921.63
#Sta/Elev= 30
  3924.6  487.39  4098.2  473.77  4314.6  462.46  4401.6  459.80  4441.3  456.73
  4454.3  457.31  4496.4  453.01  4525.1  451.84  4527.8  451.34  4531.1  451.84
  4531.8  451.93  4541.6  453.40  4549.1  457.34  4559.7  459.39  4602.6  461.33
  4675.6  464.10  4694.7  460.73  4699.9  457.91  4708.3  458.64  4810.3  459.29
  4844.2  459.52  4922.5  456.93  4943.3  453.58  4986.4  454.16  4999.6  451.93
  5036.4  455.97  5056.9  455.86  5230.0  468.52  5501.1  479.16  5575.6  485.90
#Mann=8,-1,0
  3924.6    0.05       0  4525.1    0.07       0  4531.1    0.05       0
  4531.8    0.15       0  4602.6     0.1       0  4708.3    0.05       0
  4810.3    0.16       0  5056.9    0.05       0
Bank Sta=4525.1,4531.1
Exp/Cntr=0.3,0.1

Type RM Length L Ch R = 1,1923,663,663,663
BEGIN DESCRIPTION:
UNT 002 IN CACR 4.0
END DESCRIPTION:
XS GIS Cut Line= 4
      3696618.95     10789557.00      3695191.82     10789926.80
      3694999.12     10790030.97      3694837.65     10790921.63
#Sta/Elev= 30
  3437.5  497.46  3860.4  494.75  4036.0  486.38  4065.0  476.49  4070.1  481.58
  4081.9  476.64  4098.0  472.31  4145.6  471.28  4211.6  466.77  4227.3  470.00
  4232.5  465.52  4262.8  472.01  4267.9  465.16  4294.2  471.32  4455.5  464.84
  4558.8  462.23  4662.2  459.43  4704.1  449.39  4761.8  456.36  4765.5  456.45
  4852.1  459.73  4868.8  456.45  4901.9  449.03  5059.1  448.07  5061.8  447.57
  5065.1  448.07  5241.8  456.98  5379.7  454.73  5506.1  457.56  6036.0  481.90
#Mann=11,-1,0
  3437.5    0.05       0  4081.9    0.08       0  4145.6    0.05       0
  4455.5    0.08       0  4558.8    0.05       0  4662.2     0.1       0
  4761.8    0.15       0  4765.5     0.1       0  4868.8    0.05       0
  5059.1    0.03       0  5065.1    0.05       0
Bank Sta=5059.1,5065.1
Exp/Cntr=0.3,0.1

Type RM Length L Ch R = 1,1260,118,118,118
BEGIN DESCRIPTION:
UNT 002 IN CACR 3.0
END DESCRIPTION:
XS GIS Cut Line= 4
      3696749.12     10788942.42      3694795.99     10789442.42
      3694618.91     10789557.01      3694650.16     10790760.17
#Sta/Elev= 30
  2859.8  500.33  2954.5  497.82  3058.9  488.79  3192.4  478.99  3230.5  475.33
  3241.2  471.83  3311.4  467.88  3405.5  468.48  3439.0  470.03  3621.0  462.74
  3678.2  461.37  3877.5  457.18  4335.4  457.73  4504.0  446.53  4531.5  450.59
  4607.2  451.64  4729.3  448.29  4735.0  446.04  4737.7  445.54  4741.0  446.04
  4923.9  446.04  5044.9  446.04  5097.2  446.04  5293.5  446.15  5420.0  449.78
  5560.2  447.72  5750.2  449.94  5930.3  455.35  5990.3  459.96  6290.4  472.08
#Mann=16,-1,0
  2859.8    0.05       0  3058.9    0.16       0  3192.4    0.12       0
  3230.5    0.16       0  3405.5    0.05       0  3621.0    0.16       0
  3678.2    0.05       0  4504.0    0.15       0  4607.2     0.1       0
  4735.0    0.07       0  4741.0     0.1       0  4923.9    0.08       0
  5044.9     0.1       0  5097.2    0.08       0  5293.5     0.1       0
  5420.0    0.05       0
Bank Sta=4735,4741
Exp/Cntr=0.3,0.1

Type RM Length L Ch R = 1,1142,72,72,72
BEGIN DESCRIPTION:
Mapping XS fcbb02d9
END DESCRIPTION:
XS GIS Cut Line= 5
      3696578.79     10788890.56      3694792.34     10789354.10
      3694513.69     10789460.87      3694422.55     10789533.78
      3694537.13     10790734.29
#Sta/Elev= 30
  2962.9  486.00  2982.3  484.26  3085.6  477.17  3189.0  469.97  3191.0  469.72
  3334.0  462.04  3387.0  465.30  3537.1  457.43  3638.3  455.73  3764.9  454.54
  4257.0  455.08  4428.9  447.03  4457.1  446.30  4459.8  445.80  4463.1  446.30
  4480.7  450.17  4551.9  451.86  4652.4  449.98  4687.4  446.45  4765.5  449.85
  4843.6  450.44  4869.3  450.72  4951.2  449.69  5033.1  446.77  5038.4  449.22
  5113.6  449.32  5774.6  449.56  6040.4  454.71  6139.2  457.39  6429.6  469.48
#Mann=19,-1,0
  2962.9    0.16       0  2982.3    0.12       0  3085.6    0.16       0
  3189.0    0.12       0  3191.0    0.16       0  3387.0    0.05       0
  3638.3    0.16       0  3764.9    0.05       0  4428.9    0.15       0
  4457.1    0.07       0  4463.1    0.15       0  4551.9     0.1       0
  4765.5    0.08       0  4843.6    0.16       0  4869.3    0.08       0
  4951.2    0.16       0  5113.6    0.05       0  6040.4    0.08       0
  6139.2    0.05       0
Bank Sta=4457.1,4463.1
Exp/Cntr=0.3,0.1

Type RM Length L Ch R = 1,1070,367,367,367
BEGIN DESCRIPTION:
Mapping XS 14c43a9f
END DESCRIPTION:
XS GIS Cut Line= 5
      3696586.58     10788848.90      3694682.96     10789317.64
      3694406.92     10789442.64      3694370.46     10789669.20
      3694464.21     10790614.48
#Sta/Elev= 30
  2907.4  485.67  2945.5  481.46  3036.1  475.94  3139.1  471.04  3207.6  463.07
  3269.1  465.60  3363.9  460.22  3408.9  462.32  3609.5  453.66  3783.8  451.26
  3882.3  452.34  3932.3  452.50  4160.7  455.53  4374.4  446.77  4428.5  445.32
  4519.5  452.44  4580.3  450.96  4665.4  446.11  4786.2  448.68  4856.8  444.97
  4910.2  433.88  4999.6  431.08  5002.3  430.58  5005.6  431.08  5189.5  441.59
  5381.1  452.40  5853.6  450.41  6078.9  454.87  6177.8  457.40  6350.3  463.63
#Mann=18,-1,0
  2907.4    0.16       0  2945.5    0.12       0  3036.1    0.16       0
  3139.1    0.12       0  3207.6    0.16       0  3363.9    0.05       0
  3609.5    0.16       0  3783.8    0.05       0  3882.3    0.16       0
  3932.3    0.05       0  4374.4    0.15       0  4580.3    0.08       0
  4786.2    0.16       0  4999.6    0.07       0  5005.6    0.16       0
  5189.5    0.05       0  6078.9    0.08       0  6177.8    0.05       0
Bank Sta=4999.6,5005.6
Exp/Cntr=0.3,0.1

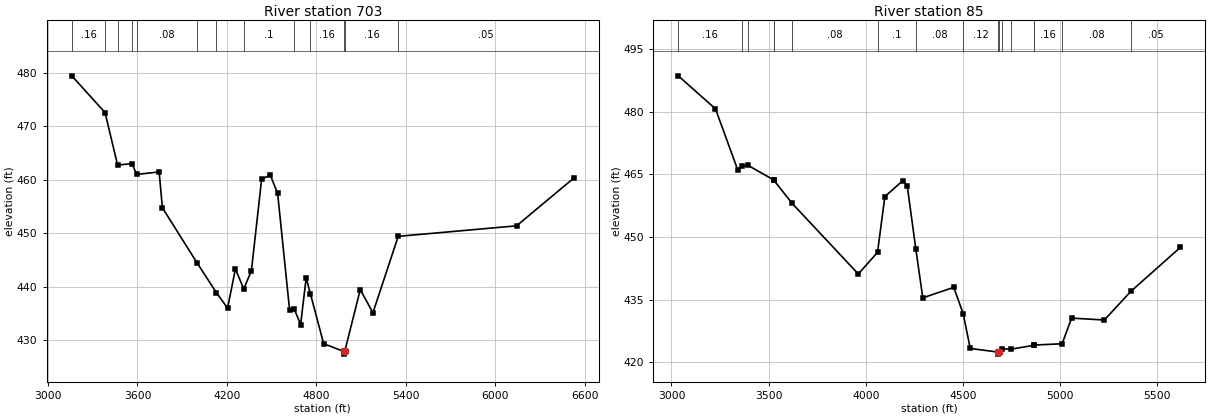
Type RM Length L Ch R = 1,703,618,618,618
BEGIN DESCRIPTION:
UNT 002 IN CACR 2.0
END DESCRIPTION:
XS GIS Cut Line= 3
      3695957.49     10788126.43      3694285.57     10789110.83
      3694410.58     10790532.75
#Sta/Elev= 30
  3159.2  479.45  3382.3  472.59  3466.6  462.77  3563.5  463.05  3594.0  461.02
  3745.4  461.49  3766.9  454.80  4000.8  444.44  4129.9  438.90  4204.2  436.05
  4256.9  443.36  4312.6  439.62  4364.2  443.04  4432.7  460.15  4491.2  460.90
  4540.0  457.46  4620.0  435.76  4651.0  435.92  4694.2  432.97  4731.3  441.66
  4759.9  438.73  4848.5  429.39  4984.1  427.94  4986.8  427.44  4990.1  427.94
  5094.1  439.50  5179.1  435.17  5348.8  449.45  6142.8  451.42  6526.8  460.35
#Mann=13,-1,0
  3159.2    0.16       0  3382.3    0.05       0  3466.6    0.15       0
  3563.5     0.1       0  3594.0    0.08       0  4000.8    0.16       0
  4129.9    0.08       0  4312.6     0.1       0  4651.0    0.08       0
  4759.9    0.16       0  4984.1    0.07       0  4990.1    0.16       0
  5348.8    0.05       0
Bank Sta=4984.1,4990.1
Exp/Cntr=0.3,0.1

Type RM Length L Ch R = 1,85,0,0,0
BEGIN DESCRIPTION:
UNT 002 IN CACR 1.0
END DESCRIPTION:
XS GIS Cut Line= 4
      3695521.69     10787647.29      3693940.09     10788698.14
      3693994.78     10788903.00      3694220.48     10789319.68
#Sta/Elev= 30
  3034.7  488.55  3226.5  480.65  3340.7  466.09  3360.6  466.96  3394.3  467.13
  3526.4  463.65  3527.9  463.52  3621.3  458.04  3961.7  441.16  4060.7  446.34
  4098.4  459.67  4191.6  463.51  4213.8  462.21  4257.9  447.11  4293.8  435.46
  4453.2  437.97  4501.9  431.63  4538.0  423.36  4679.0  422.50  4681.8  422.00
  4685.0  422.50  4699.4  423.28  4745.9  423.17  4866.7  424.12  4867.9  424.17
  5010.9  424.48  5059.9  430.61  5228.5  430.16  5364.7  437.00  5619.5  447.52
#Mann=17,-1,0
  3034.7    0.16       0  3360.6    0.05       0  3394.3    0.08       0
  3526.4     0.1       0  3527.9    0.15       0  3621.3    0.08       0
  4060.7     0.1       0  4257.9    0.08       0  4501.9    0.12       0
  4679.0    0.07       0  4685.0    0.12       0  4699.4    0.05       0
  4745.9    0.12       0  4866.7    0.05       0  4867.9    0.16       0
  5010.9    0.08       0  5364.7    0.05       0
Bank Sta=4679,4685
Exp/Cntr=0.3,0.1

Chan Stop Cuts=-1