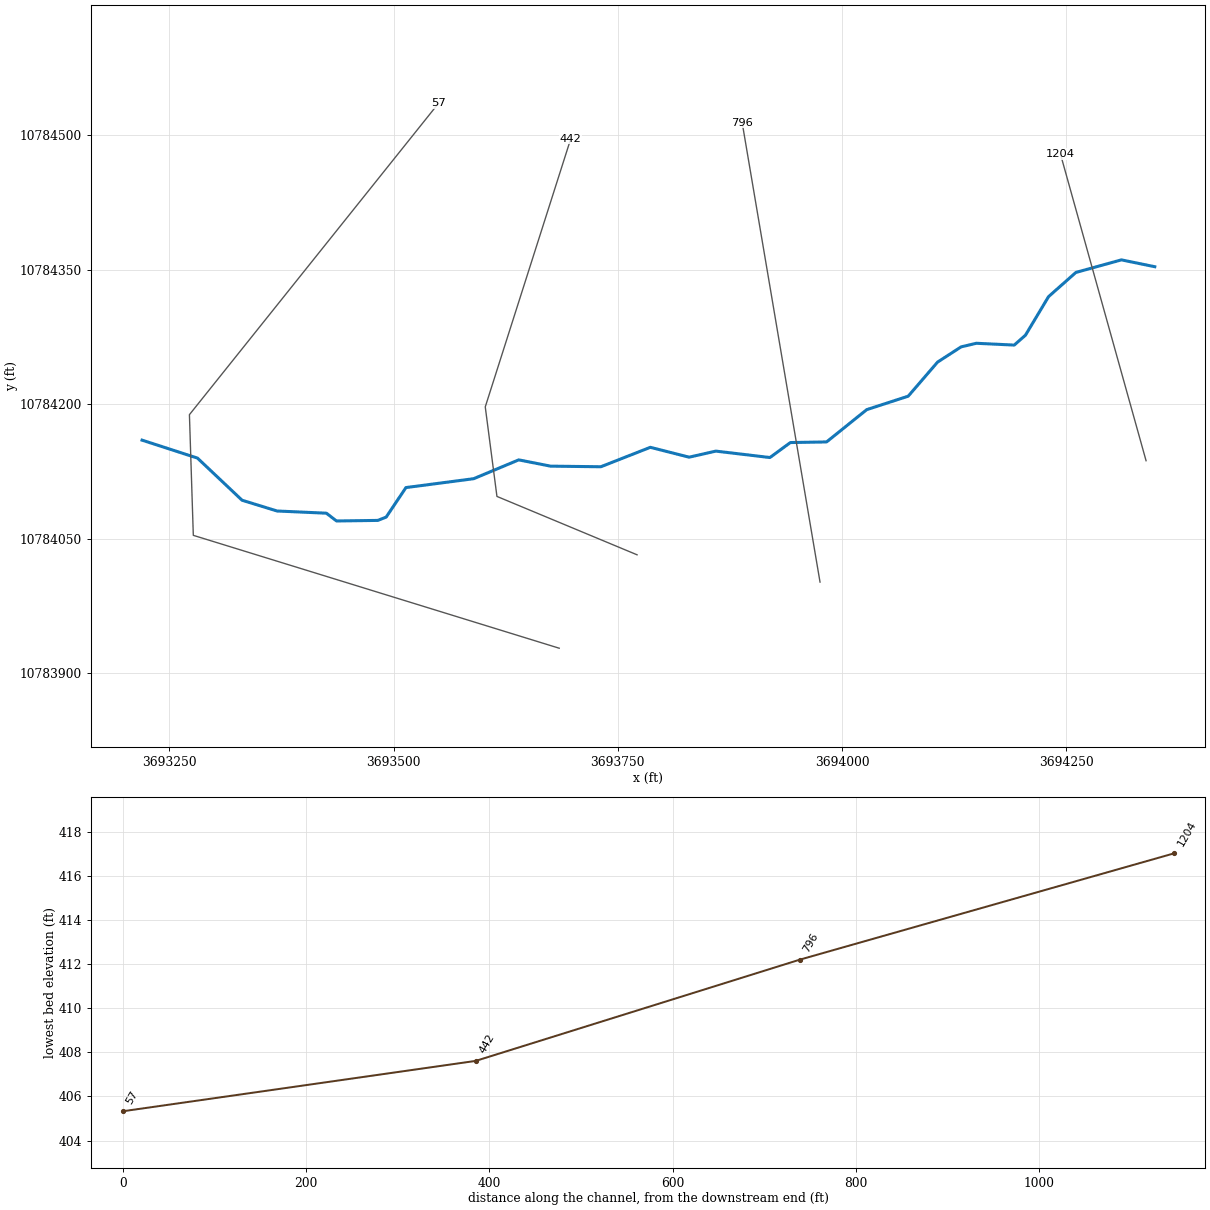
--- UNT 004 IN CACR.prj (project) ---

Proj Title=UNT 004 IN CACR Base Level Engineering
Current Plan=p01
Default Exp/Contr=0.3,0.1
English Units
Geom File=g01
Flow File=f01
Plan File=p01
Y Axis Title=Elevation
X Axis Title(PF)=Main Channel Distance
X Axis Title(XS)=Station
BEGIN DESCRIPTION:
UNT 004 IN CACR
END DESCRIPTION:
DSS Export Rating Curves= 0
DSS Export Rating Curve Sorted= 0
DSS Export Volume Flow Curves= 0
DXF OffsetX= 0
DXF OffsetY= 0
DXF ScaleX= 1
DXF ScaleY= 10

--- UNT 004 IN CACR.p01 (plan) ---

Plan Title=Multiple Run
Short Identifier=Multiple
Geom File=g01
Flow File=f01
Subcritical Flow
K Sum by GR= 0
Std Step Tol= 0.01
Critical Tol= 0.01
Num of Std Step Trials= 20
Max Error Tol= 0.3
Flow Tol Ratio= 0.001
Split Flow NTrial= 30
Split Flow Tol= 0.02
Split Flow Ratio= 0.02
Log Output Level= 0
Friction Slope Method= 1
Unsteady Friction Slope Method= 2
Unsteady Bridges Friction Slope Method= 1
Parabolic Critical Depth
Global Vel Dist=  1 , 1 , 1
Global Log Level= 0
CheckData=True
Encroach Param= -1, 0, 0, 0
BEGIN DESCRIPTION:
Multiple Run
END DESCRIPTION:

--- UNT 004 IN CACR.f01 (steady flow) ---

Flow Title=Multiple
Number of Profiles=7
Profile Names=10-year,25-year,50-year,1pct_min,100-year,1pct_plu,500-year
River Rch & RM= UNT 004 IN CACR,Reach-1,1204
     265     342     402     348     471     637     646
Boundary for River Rch & Prof#=UNT 004 IN CACR,Reach-1,1
Up Type=0
Dn Type=3
Dn Slope=0.005
Boundary for River Rch & Prof#=UNT 004 IN CACR,Reach-1,2
Up Type=0
Dn Type=3
Dn Slope=0.005
Boundary for River Rch & Prof#=UNT 004 IN CACR,Reach-1,3
Up Type=0
Dn Type=3
Dn Slope=0.005
Boundary for River Rch & Prof#=UNT 004 IN CACR,Reach-1,4
Up Type=0
Dn Type=3
Dn Slope=0.005
Boundary for River Rch & Prof#=UNT 004 IN CACR,Reach-1,5
Up Type=0
Dn Type=3
Dn Slope=0.005
Boundary for River Rch & Prof#=UNT 004 IN CACR,Reach-1,6
Up Type=0
Dn Type=3
Dn Slope=0.005
Boundary for River Rch & Prof#=UNT 004 IN CACR,Reach-1,7
Up Type=0
Dn Type=3
Dn Slope=0.005

--- UNT 004 IN CACR.g01 (geometry) ---

Geom Title=Existing Conditions
Program Version=4.10

River Reach=UNT 004 IN CACR ,Reach-1
Reach XY= 30
       3694348.7     10784353.37       3694311.5       10784361.
      3694260.75       10784347.      3694230.25       10784320.
       3694204.5       10784277.        3694192.       10784266.
      3694149.75       10784268.      3694132.75       10784264.
       3694106.5       10784247.      3694073.75       10784209.
       3694027.5       10784194.      3693982.75       10784158.
      3693942.39     10784157.32       3693919.6     10784140.61
      3693859.27     10784147.77       3693829.5       10784141.
      3693786.25       10784152.      3693731.07     10784130.33
        3693675.       10784131.       3693639.5       10784138.
      3693589.25       10784117.      3693513.73      10784107.1
      3693491.71      10784074.2      3693482.38     10784070.51
      3693436.32     10784069.86      3693425.04     10784078.54
        3693370.       10784081.        3693331.       10784093.
      3693281.25       10784140.       3693219.5       10784160.

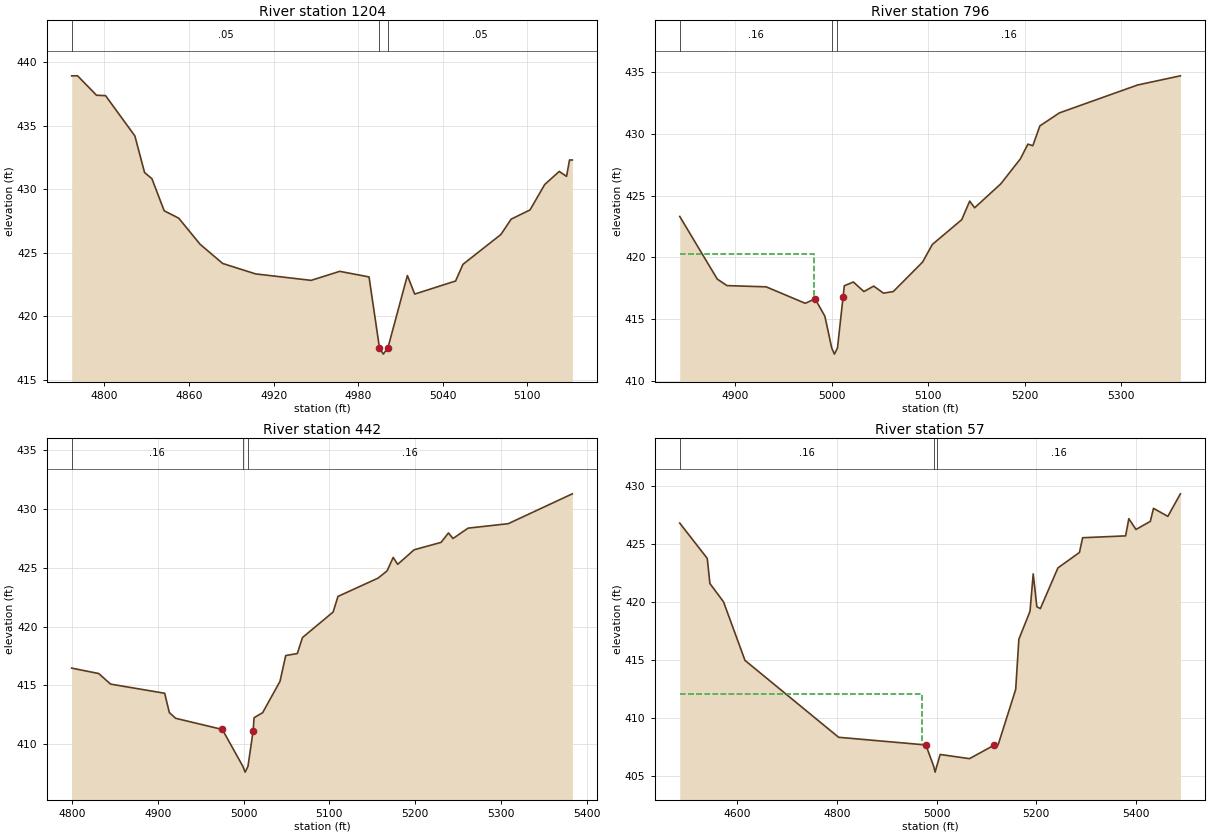
Type RM Length L Ch R = 1 ,1204    ,408,408,408
BEGIN DESCRIPTION:
UNT 004 IN CACR 2.0
END DESCRIPTION:
XS GIS Cut Line= 2
      3694338.99     10784137.05       3694243.5     10784479.07
#Sta/Elev= 30
  4776.8  438.93    4781  438.93  4794.4   437.4  4800.8  437.37  4821.6   434.2
  4828.5  431.31  4833.7  430.83  4842.4   428.3  4852.7  427.72  4867.9  425.66
  4883.9  424.15  4907.2  423.33  4946.6  422.82  4966.9  423.53  4987.7  423.09
  4995.1  417.51  4997.8  417.01  5001.1  417.51  5014.9   423.2  5020.1  421.74
  5049.1  422.77  5054.3  424.08  5081.2  426.43  5088.5  427.64  5101.9  428.37
  5112.3  430.37  5122.6   431.4  5127.8  431.01  5129.9   432.3  5131.9   432.3
#Mann= 3 ,-1 , 0
  4776.8     .05       0  4995.1     .03       0  5001.1     .05       0
Bank Sta=4995.1,5001.1
XS Rating Curve= 0 ,0
Exp/Cntr=0.3,0.1

Type RM Length L Ch R = 1 ,796     ,354,354,354
BEGIN DESCRIPTION:
Mapping XS 35a5c837
END DESCRIPTION:
XS GIS Cut Line= 2
      3693975.45     10784001.74      3693888.64     10784513.94
#Sta/Elev= 30
  4842.2  423.31  4881.2  418.25  4891.3  417.73  4931.9  417.63  4972.5   416.3
  4982.6  416.67  4992.8  415.26  4999.9   412.7  5002.7   412.2  5005.9   412.7
  5011.7  416.82    5013  417.72  5022.4  418.02  5033.3  417.25  5043.5  417.69
  5053.6  417.12  5063.8  417.25  5094.2  419.63  5104.3  421.05  5134.8  423.05
  5143.1  424.55  5148.2  424.01  5175.3  425.94  5195.6  427.95  5203.5  429.15
  5208.6  429.02  5215.9  430.62  5236.2  431.67  5317.3  433.92  5361.7  434.66
#Mann= 3 ,-1 , 0
  4842.2     .16       0  4999.9     .07       0  5005.9     .16       0
#XS Ineff= 2 , 0
         4981.02  420.29
Permanent Ineff=
       F       F
Bank Sta=4982.6,5011.7
XS Rating Curve= 0 ,0
Exp/Cntr=0.3,0.1

Type RM Length L Ch R = 1 ,442     ,385,385,385
BEGIN DESCRIPTION:
Mapping XS c522b105
END DESCRIPTION:
XS GIS Cut Line= 4
      3693771.45     10784032.15       3693615.2     10784097.25
      3693602.18     10784197.08      3693697.47     10784495.92
#Sta/Elev= 30
  4799.6  416.46  4831.1     416  4844.9   415.1    4908  414.32  4913.4  412.68
  4920.8  412.19  4975.2  411.24  4999.1  408.11  5001.8  407.61  5005.1  408.11
 5011.02  411.08  5012.2  412.24  5022.2  412.67  5042.4  415.33  5049.1  417.53
  5062.6   417.7  5068.6  419.06  5104.3  421.23    5110  422.56  5156.8  424.12
  5167.3  424.74  5174.4  425.88  5179.6  425.29  5198.8  426.53  5230.2  427.16
  5238.8  427.96  5244.1  427.49  5261.7  428.37  5308.5  428.75  5383.2  431.29
#Mann= 3 ,-1 , 0
  4799.6     .16       0  4999.1     .07       0  5005.1     .16       0
Bank Sta=4975.2,5011.02
XS Rating Curve= 0 ,0
Exp/Cntr=0.3,0.1

Type RM Length L Ch R = 1 ,57      ,0,0,0
BEGIN DESCRIPTION:
UNT 004 IN CACR 1.0
END DESCRIPTION:
XS GIS Cut Line= 4
      3693684.63     10783927.99      3693276.66     10784053.85
      3693272.32      10784188.4       3693549.9     10784535.37
#Sta/Elev= 30
    4484  426.77  4539.3  423.73  4544.6  421.57    4572  419.99  4615.1  414.95
  4803.2  408.33  4978.5  407.67  4994.3  405.83  4997.1  405.33  5000.3  405.83
  5007.3  406.85  5066.1  406.49  5115.8  407.65  5123.8  407.69    5159  412.45
  5165.4  416.77  5187.8  419.18  5194.2   422.4  5201.5  419.57  5208.6  419.41
  5243.8  422.91  5287.1  424.24  5293.5  425.51  5379.9  425.67  5386.3  427.15
  5400.7  426.22  5429.5  426.92  5435.9  428.04  5464.7  427.35  5489.9  429.29
#Mann= 3 ,-1 , 0
    4484     .16       0  4994.3     .07       0  5000.3     .16       0
#XS Ineff= 2 , 0
            4970  412.04
Permanent Ineff=
       F       F
Bank Sta=4978.5,5115.8
XS Rating Curve= 0 ,0
Exp/Cntr=0.3,0.1

Chan Stop Cuts=-1
Use User Specified Reach Order=0
Composite Channel Slope=5