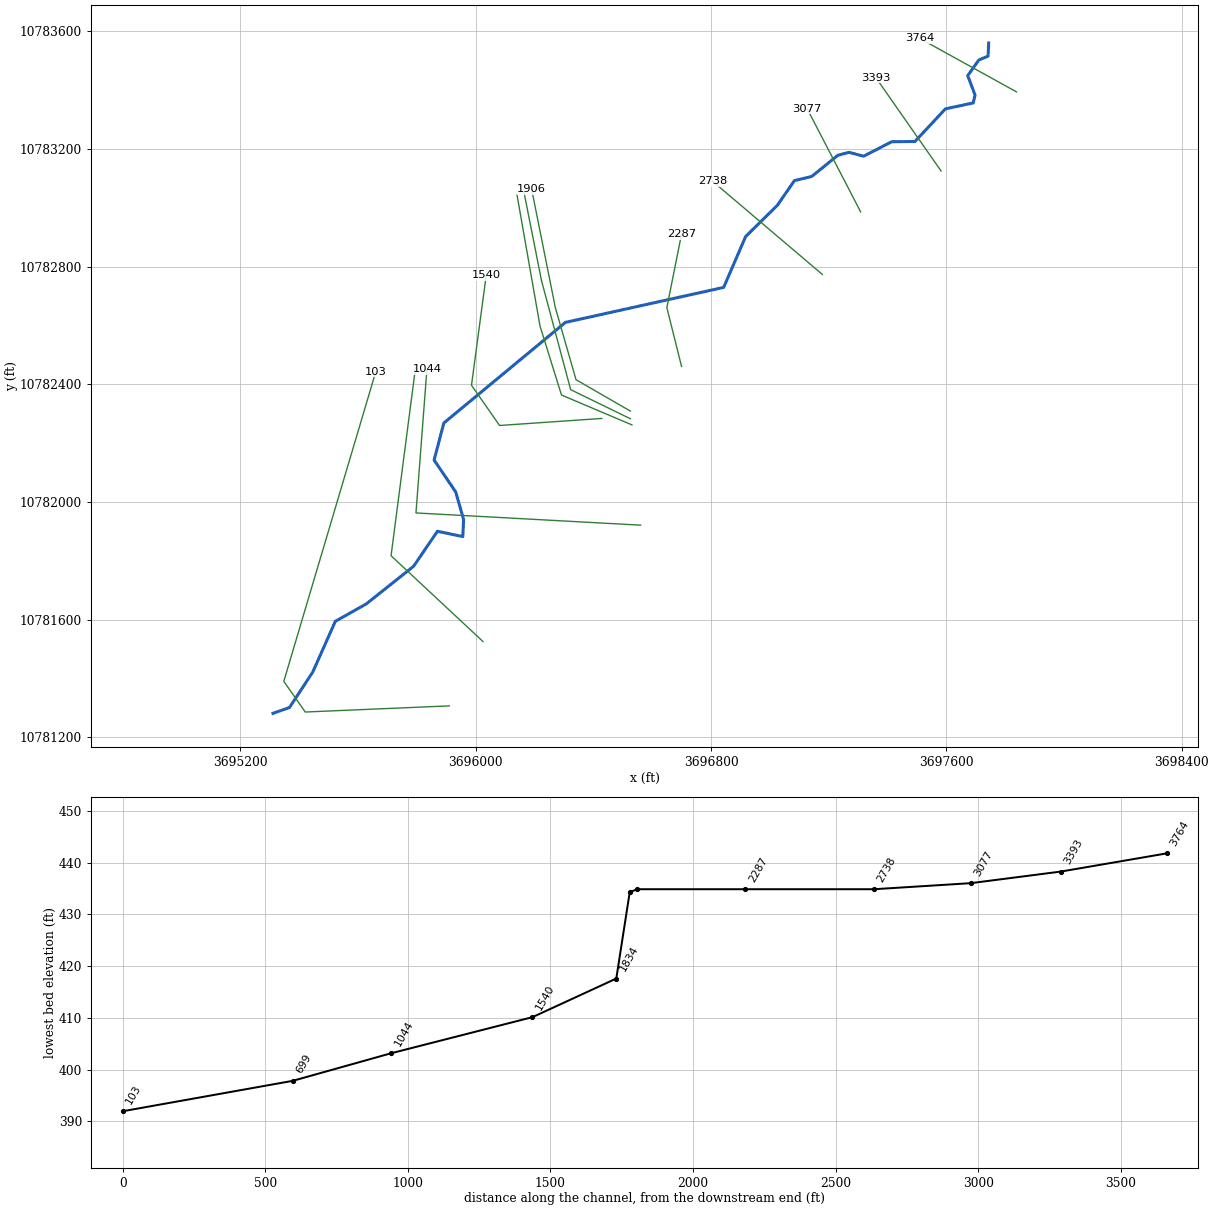
--- UNT 005 IN CACR.prj (project) ---

Proj Title=UNT 005 IN CACR Base Level Engineering
Current Plan=p01
Default Exp/Contr=0.3,0.1
English Units
Geom File=g01
Flow File=f01
Plan File=p01
Y Axis Title=Elevation
X Axis Title(PF)=Main Channel Distance
X Axis Title(XS)=Station
BEGIN DESCRIPTION:
UNT 005 IN CACR
END DESCRIPTION:
DSS Export Rating Curves= 0
DSS Export Rating Curve Sorted= 0
DSS Export Volume Flow Curves= 0
DXF OffsetX= 0
DXF OffsetY= 0
DXF ScaleX= 1
DXF ScaleY= 10

--- UNT 005 IN CACR.p01 (plan) ---

Plan Title=Multiple Run
Short Identifier=Multiple
Geom File=g01
Flow File=f01
Subcritical Flow
K Sum by GR= 0
Std Step Tol= 0.01
Critical Tol= 0.01
Num of Std Step Trials= 20
Max Error Tol= 0.3
Flow Tol Ratio= 0.001
Split Flow NTrial= 30
Split Flow Tol= 0.02
Split Flow Ratio= 0.02
Log Output Level= 0
Friction Slope Method= 1
Unsteady Friction Slope Method= 2
Unsteady Bridges Friction Slope Method= 1
Parabolic Critical Depth
Global Vel Dist=  1 , 1 , 1
Global Log Level= 0
CheckData=True
Encroach Param= -1, 0, 0, 0
BEGIN DESCRIPTION:
Multiple Run
END DESCRIPTION:

--- UNT 005 IN CACR.f01 (steady flow) ---

Flow Title=Multiple
Program Version=4.10
Number of Profiles= 7
Profile Names=10-year,25-year,50-year,1pct_min,100-year,1pct_plu,500-year
River Rch & RM=UNT 005 IN CACR,Reach-1         ,3764
     296     385     456     398     538     727     747
River Rch & RM=UNT 005 IN CACR,Reach-1         ,103
    2017    2885    3635    3345    4523    6117    7028
Boundary for River Rch & Prof#=UNT 005 IN CACR,Reach-1         , 1
Up Type= 0
Dn Type= 3
Dn Slope=0.00987
Boundary for River Rch & Prof#=UNT 005 IN CACR,Reach-1         , 2
Up Type= 0
Dn Type= 3
Dn Slope=0.00987
Boundary for River Rch & Prof#=UNT 005 IN CACR,Reach-1         , 3
Up Type= 0
Dn Type= 3
Dn Slope=0.00987
Boundary for River Rch & Prof#=UNT 005 IN CACR,Reach-1         , 4
Up Type= 0
Dn Type= 3
Dn Slope=0.00987
Boundary for River Rch & Prof#=UNT 005 IN CACR,Reach-1         , 5
Up Type= 0
Dn Type= 3
Dn Slope=0.00987
Boundary for River Rch & Prof#=UNT 005 IN CACR,Reach-1         , 6
Up Type= 0
Dn Type= 3
Dn Slope=0.00987
Boundary for River Rch & Prof#=UNT 005 IN CACR,Reach-1         , 7
Up Type= 0
Dn Type= 3
Dn Slope=0.00987
DSS Import GetInterval= 0
DSS Import GetPeak= 0
DSS Import FillOption= 0

--- UNT 005 IN CACR.g01 (geometry) ---

Geom Title=Existing Conditions
Program Version=4.10

River Reach=UNT 005 IN CACR ,Reach-1
Reach XY= 30
      3697743.58     10783559.67       3697741.5       10783515.
      3697710.25       10783502.      3697672.25       10783449.
      3697697.25       10783383.        3697691.       10783356.
      3697596.75       10783336.        3697493.       10783225.
      3697413.75       10783224.       3697318.5       10783175.
       3697268.5       10783188.      3697230.75       10783178.
        3697142.       10783106.      3697083.25       10783092.
      3697025.25       10783008.       3696917.5       10782902.
      3696842.75       10782729.      3696304.75       10782610.
       3695891.5       10782268.       3695858.5       10782142.
      3695931.75       10782034.      3695958.75       10781940.
        3695956.       10781882.      3695869.75       10781900.
      3695788.75       10781781.      3695627.75       10781653.
      3695522.75       10781594.      3695446.25       10781422.
        3695367.       10781301.       3695310.5       10781281.

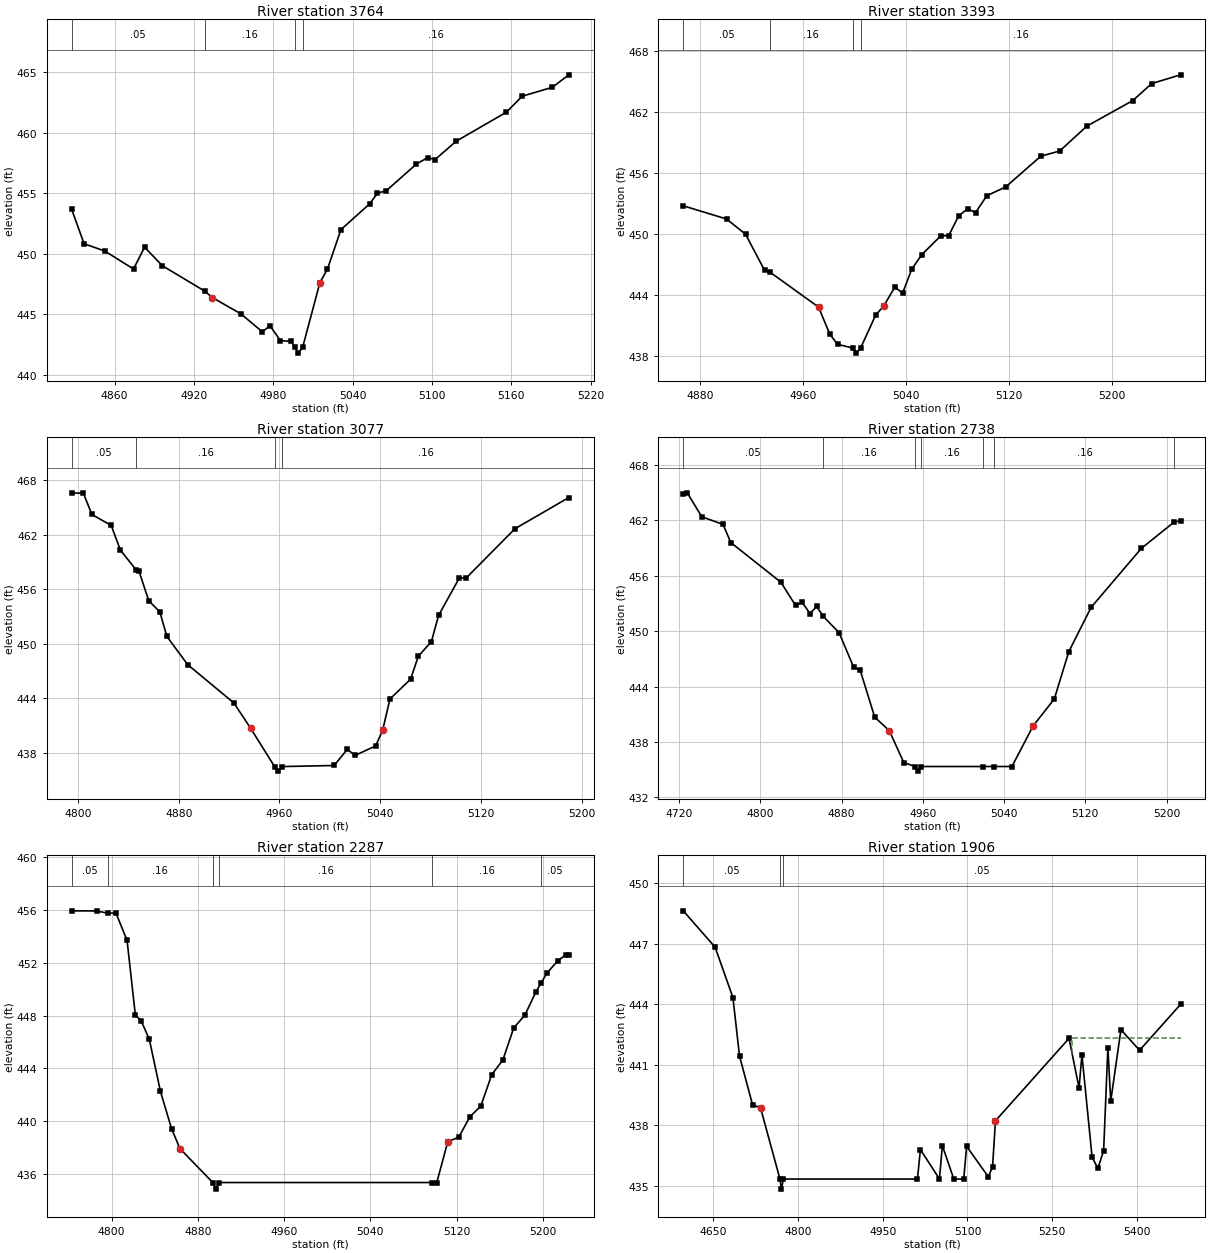
Type RM Length L Ch R = 1 ,3764    ,371,371,371
BEGIN DESCRIPTION:
UNT 005 IN CACR 7.0
END DESCRIPTION:
XS GIS Cut Line= 2
      3697837.89     10783393.73       3697508.8      10783575.6
#Sta/Elev= 30
  4827.5   453.7    4837  450.82  4852.6  450.22  4874.4  448.73  4882.7  450.54
  4896.2     449  4928.1  446.91    4934  446.37  4955.7  445.01  4971.8  443.53
  4977.5  444.04  4985.5   442.8  4993.6  442.74  4996.3  442.27    4999  441.77
  5002.3  442.27  5015.3   447.6    5021  448.72  5031.2  451.99  5053.1  454.14
  5058.8  455.01  5065.5  455.21  5088.3  457.42  5096.7  457.94  5102.4  457.79
  5118.4  459.31  5156.2   461.7  5168.3  463.03  5191.1  463.77  5203.5   464.8
#Mann= 4 ,-1 , 0
  4827.5     .05       0  4928.1     .16       0  4996.3     .07       0
  5002.3     .16       0
Bank Sta=4934,5015.3
XS Rating Curve= 0 ,0
Exp/Cntr=0.3,0.1

Type RM Length L Ch R = 1 ,3393    ,316,316,316
BEGIN DESCRIPTION:
Mapping XS f6585306
END DESCRIPTION:
XS GIS Cut Line= 2
      3697581.76     10783124.68      3697360.41     10783441.51
#Sta/Elev= 30
    4867  452.77  4900.6  451.47  4915.4  449.97  4930.2  446.41  4934.2  446.25
  4972.1   442.8  4980.8  440.15  4986.9  439.13  4998.8  438.76  5001.5  438.26
  5004.8  438.76  5016.6  442.02  5022.7  442.89  5031.4  444.75  5037.5  444.18
  5044.5  446.52  5052.4  447.96  5067.2  449.82  5073.3  449.83  5081.1   451.8
  5088.1  452.47  5094.2  452.11  5102.9  453.76  5117.7  454.64  5144.8  457.65
  5159.6  458.17  5180.6  460.61  5216.3  463.13  5231.1  464.81  5253.5  465.67
#Mann= 4 ,-1 , 0
    4867     .05       0  4934.2     .16       0  4998.8     .07       0
  5004.8     .16       0
Bank Sta=4972.1,5022.7
XS Rating Curve= 0 ,0
Exp/Cntr=0.3,0.1

Type RM Length L Ch R = 1 ,3077    ,339,339,339
BEGIN DESCRIPTION:
UNT 005 IN CACR 6.0
END DESCRIPTION:
XS GIS Cut Line= 2
      3697308.34     10782985.77       3697126.6     10783336.26
#Sta/Elev= 30
  4794.9  466.59  4804.3  466.54  4811.1  464.21  4826.4  463.01  4833.7   460.3
  4846.4  458.09  4848.5  457.97  4856.2  454.74    4865  453.51  4870.6  450.82
  4887.1  447.72  4923.8  443.51    4937  440.75  4956.1  436.52  4958.9  436.02
  4962.1  436.52  5003.4  436.64  5013.9  438.42  5019.9  437.74  5036.4  438.79
    5042  440.56  5047.7  443.94  5064.1  446.12  5070.2  448.64  5080.6  450.24
  5086.3  453.12  5102.8  457.24  5108.4  457.26    5147  462.65  5189.7  466.07
#Mann= 4 ,-1 , 0
  4794.9     .05       0  4846.4     .16       0  4956.1     .07       0
  4962.1     .16       0
Bank Sta=4937,5042
XS Rating Curve= 0 ,0
Exp/Cntr=0.3,0.1

Type RM Length L Ch R = 1 ,2738    ,451,451,451
BEGIN DESCRIPTION:
UNT 005 IN CACR 5.0
END DESCRIPTION:
XS GIS Cut Line= 2
      3697178.14     10782773.08      3696804.88     10783089.92
#Sta/Elev= 30
  4724.2  464.84  4728.1  464.95  4742.4  462.36  4763.3  461.54    4771  459.57
  4820.4  455.27  4834.7  452.77  4841.3   453.1    4849  451.89  4855.5  452.66
  4861.9   451.6  4877.6  449.82  4891.8  446.12  4898.4  445.75  4912.7  440.68
    4927  439.23  4941.3  435.78  4952.5  435.35  4955.3  434.85  4958.5  435.35
  5019.1  435.35  5030.5  435.35  5047.8  435.35  5068.6  439.73  5089.5  442.66
  5103.8  447.78  5125.8  452.57  5175.2  458.94  5207.8  461.82  5213.8  461.91
#Mann= 7 ,-1 , 0
  4724.2     .05       0  4861.9     .16       0  4952.5     .07       0
  4958.5     .16       0  5019.1     .05       0  5030.5     .16       0
  5207.8     .05       0
Bank Sta=4927,5068.6
XS Rating Curve= 0 ,0
Exp/Cntr=0.3,0.1

Type RM Length L Ch R = 1 ,2287    ,381,381,381
BEGIN DESCRIPTION:
UNT 005 IN CACR 4.0
END DESCRIPTION:
XS GIS Cut Line= 3
       3696699.6     10782460.23      3696649.61     10782660.19
      3696699.62     10782910.22
#Sta/Elev= 30
  4762.9  455.93  4786.1  455.92  4796.5  455.75  4804.1  455.76  4814.4  453.69
  4822.1  448.02  4827.3  447.62    4835  446.21  4845.3  442.27  4855.6  439.44
  4863.4  437.92  4893.9  435.35  4896.6  434.85  4899.9  435.35  5097.6  435.35
  5101.6  435.35  5111.8  438.45    5122  438.78  5132.2  440.32  5142.4  441.14
  5152.6  443.53  5162.8  444.62    5173  447.07  5183.2  448.02  5193.4  449.77
  5198.3  450.46  5203.6   451.2  5213.8  452.15  5221.4   452.6    5224   452.6
#Mann= 6 ,-1 , 0
  4762.9     .05       0  4796.5     .16       0  4893.9    .033       0
  4899.9     .16       0  5097.6     .16       0  5198.3     .05       0
Bank Sta=4863.4,5111.8
XS Rating Curve= 0 ,0
Exp/Cntr=0.3,0.1

Type RM Length L Ch R = 1 ,1906    ,25,25,25
BEGIN DESCRIPTION:
Mapping XS 368cdd3b
END DESCRIPTION:
XS GIS Cut Line= 4
      3696525.78     10782308.47      3696340.89     10782415.23
      3696270.58     10782660.02      3696189.86     10783063.64
#Sta/Elev= 30
  4597.2  448.62  4653.5  446.82    4685  444.33  4696.7  441.43  4719.8  439.02
  4733.9  438.87  4768.2  435.35  4770.9  434.85  4774.2  435.35  5011.5  435.35
  5016.7  436.81  5050.4  435.35  5055.6     437  5075.8  435.35  5093.4  435.35
  5098.5  436.97  5136.9  435.46  5144.4  435.96  5149.5  438.23  5279.7  442.31
  5297.4  439.86  5302.5  441.49  5320.5  436.43  5330.7  435.88  5340.9  436.75
  5348.4  441.84  5353.5  439.21  5371.5  442.74  5404.5  441.72    5477  443.99
#Mann= 3 ,-1 , 0
  4597.2     .05       0  4768.2     .03       0  4774.2     .05       0
#XS Ineff= 2 , 0
                         5285.17          442.34
Permanent Ineff=
       F       F
Bank Sta=4733.9,5149.5
XS Rating Curve= 0 ,0
Exp/Cntr=0.3,0.1

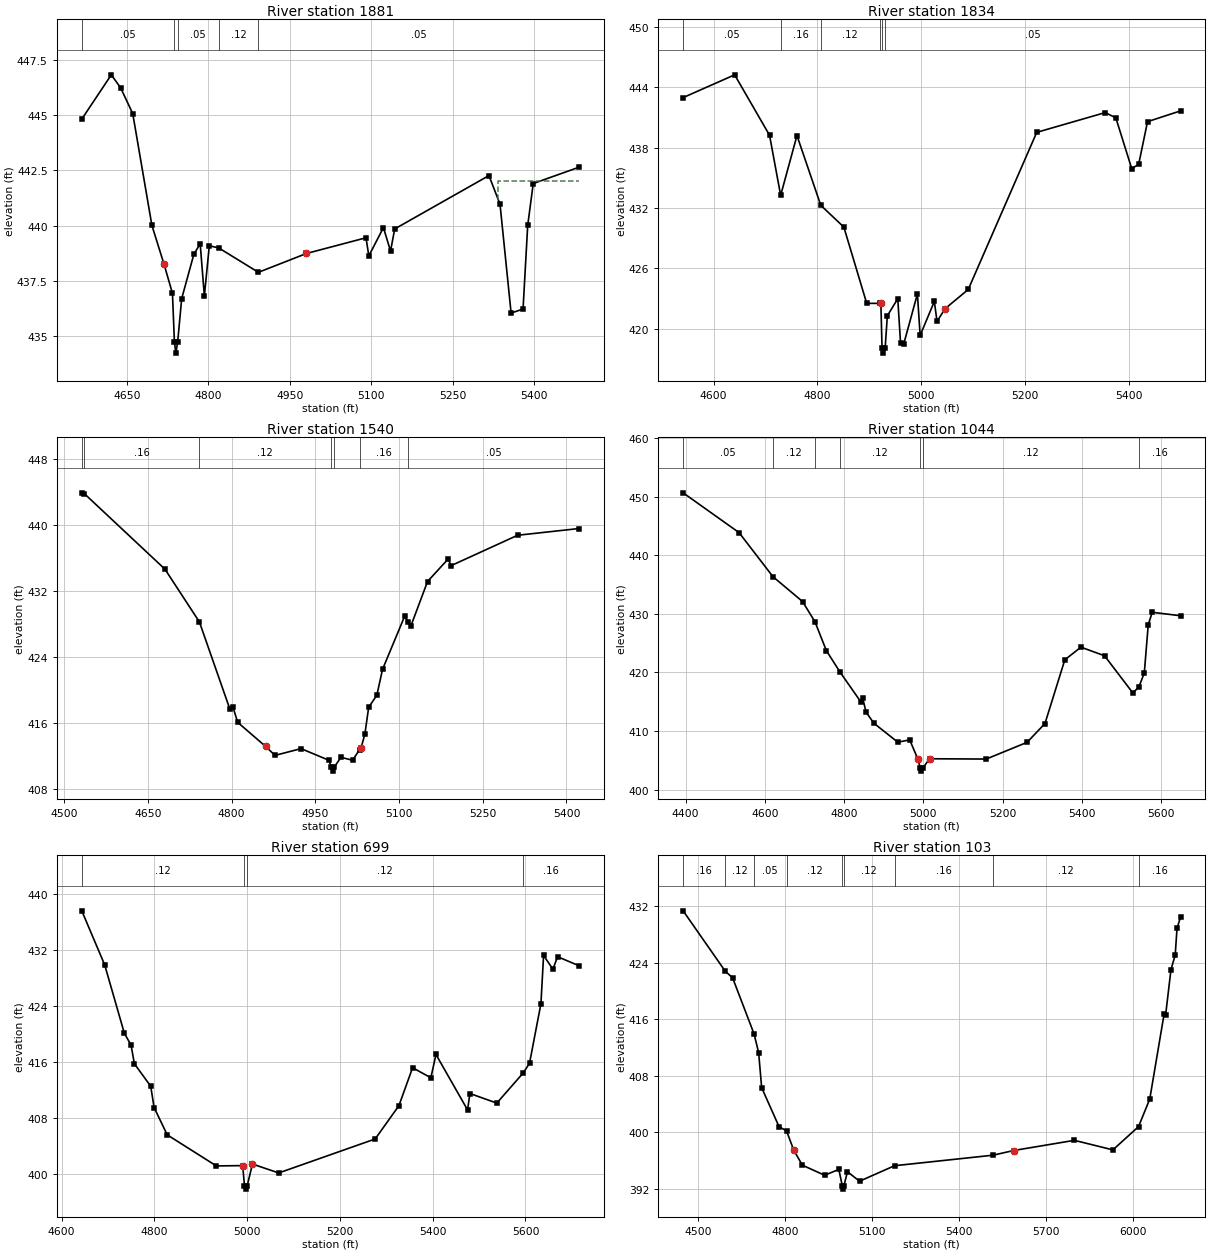
Type RM Length L Ch R = 1 ,1881    ,47,47,47
BEGIN DESCRIPTION:
Mapping XS 100bec36
END DESCRIPTION:
XS GIS Cut Line= 4
      3696525.76     10782282.43      3696322.66     10782381.38
       3696223.7     10782751.17      3696163.81     10783053.27
#Sta/Elev= 30
  4566.8  444.81  4621.2  446.81  4638.2  446.23  4660.7  445.06    4696  440.01
  4718.3  438.26  4733.9  436.94  4737.5  434.74  4740.2  434.24  4743.5  434.74
  4750.9   436.7  4773.4  438.71    4785  439.18  4792.7  436.82  4801.8  439.09
  4819.3  438.99  4892.3  437.89  4980.8  438.74  5090.6  439.45  5095.8  438.63
  5122.7  439.91  5135.8  438.85  5143.5  439.85  5317.2  442.26  5337.6  440.96
    5358  436.05    5380  436.23  5388.6  440.01  5398.8   441.9  5483.5  442.64
#Mann= 5 ,-1 , 0
  4566.8     .05       0  4737.5     .03       0  4743.5     .05       0
  4819.3     .12       0  4892.3     .05       0
#XS Ineff= 2 , 0
                         5334.23          442.02
Permanent Ineff=
       F       F
Bank Sta=4718.3,4980.8
XS Rating Curve= 0 ,0
Exp/Cntr=0.3,0.1

Type RM Length L Ch R = 1 ,1834    ,294,294,294
BEGIN DESCRIPTION:
UNT 005 IN CACR 3.0
END DESCRIPTION:
XS GIS Cut Line= 4
      3696530.97      10782261.6      3696291.41     10782363.15
       3696218.5     10782597.52      3696140.36     10783042.87
#Sta/Elev= 30
  4541.5  442.96  4640.7  445.22  4707.9  439.22  4729.3  433.25  4760.7  439.19
  4806.5  432.27    4851   430.1    4895  422.53  4919.9  422.53  4922.3  422.54
  4924.5  418.09  4927.3  417.59  4930.5  418.09  4934.7   421.3  4954.8  422.99
  4960.1  418.63  4966.2  418.48  4992.6  423.46  4997.9  419.35  5025.2  422.72
  5030.4  420.74  5045.9     422  5090.5  423.91  5222.4  439.51  5354.2  441.47
  5374.7  440.95  5405.2  435.92  5418.6  436.32  5435.7  440.57  5499.3  441.64
#Mann= 6 ,-1 , 0
  4541.5     .05       0  4729.3     .16       0  4806.5     .12       0
  4919.9     .05       0  4924.5     .03       0  4930.5     .05       0
Bank Sta=4922.3,5045.9
XS Rating Curve= 0 ,0
Exp/Cntr=0.3,0.1

Type RM Length L Ch R = 1 ,1540    ,496,496,496
BEGIN DESCRIPTION:
Mapping XS 52e42492
END DESCRIPTION:
XS GIS Cut Line= 4
      3696428.33     10782283.49      3696081.06     10782259.62
      3695985.58     10782396.34      3696035.49     10782769.57
#Sta/Elev= 30
  4531.4   443.9  4536.1  443.79  4680.5  434.63  4742.2  428.23    4797  417.61
    4802  417.97  4810.8  416.05  4860.9  413.12  4877.7  412.04  4924.3  412.86
  4974.9  411.43    4978  410.63  4980.7  410.13    4984  410.63  4995.8  411.81
  5016.7  411.45  5029.1  412.73  5031.6  412.88  5038.7  414.62  5045.5  417.87
  5060.2  419.35  5070.3  422.47    5110  428.93  5116.4  428.19  5120.8  427.68
    5151  433.14  5188.1  435.88  5193.1  435.06  5312.4  438.75  5422.8  439.57
#Mann= 7 ,-1 , 0
  4531.4     .05       0  4536.1     .16       0  4742.2     .12       0
    4978     .07       0    4984     .12       0  5029.1     .16       0
  5116.4     .05       0
Bank Sta=4860.9,5031.6
XS Rating Curve= 0 ,0
Exp/Cntr=0.3,0.1

Type RM Length L Ch R = 1 ,1044    ,345,345,345
BEGIN DESCRIPTION:
Mapping XS 9d177d81
END DESCRIPTION:
XS GIS Cut Line= 3
      3696560.62     10781920.79      3695796.78     10781962.31
      3695834.05     10782451.42
#Sta/Elev= 30
  4393.6  450.63  4534.8  443.84  4620.4  436.32  4695.1  432.08  4726.5  428.61
  4755.1  423.71  4789.9  420.02  4841.7  415.01  4846.7  415.67  4855.3  413.21
  4875.3  411.31  4935.4  408.09  4965.5  408.48  4985.5   405.3  4992.5  403.65
  4995.2  403.15  4998.5  403.65  5015.5  405.26  5158.6  405.21  5261.7  408.06
  5306.9  411.27    5357  422.14  5397.7   424.3  5457.3  422.83  5528.7  416.49
    5544  417.52  5557.6  419.89  5567.6  428.14  5577.7  430.25  5649.1  429.66
#Mann= 7 ,-1 , 0
  4393.6     .05       0  4620.4     .12       0  4726.5     .16       0
  4789.9     .12       0  4992.5     .07       0  4998.5     .12       0
    5544     .16       0
Bank Sta=4985.5,5015.5
XS Rating Curve= 0 ,0
Exp/Cntr=0.3,0.1

Type RM Length L Ch R = 1 ,699     ,596,596,596
BEGIN DESCRIPTION:
UNT 005 IN CACR 2.0
END DESCRIPTION:
XS GIS Cut Line= 3
      3696024.67     10781525.18      3695712.14     10781816.87
      3695795.32     10782456.38
#Sta/Elev= 30
  4643.5  437.55  4692.9  429.83  4735.4  420.04  4749.6  418.41  4756.9  415.72
  4792.1  412.51  4799.4  409.47  4827.7  405.57  4933.7  401.13  4990.4  401.18
  4994.2  398.32    4997  397.82  5000.2  398.32  5011.4   401.4  5068.1  400.13
    5276  404.98  5327.1  409.72  5356.7  415.15  5396.1  413.72  5407.1  417.04
  5475.2  409.13  5480.3  411.47  5538.2   410.1  5595.4  414.42  5608.8  415.79
  5633.4   424.3  5639.1  431.19  5659.2  429.21  5669.3     431  5715.9   429.7
#Mann= 4 ,-1 , 0
  4643.5     .12       0  4994.2     .07       0  5000.2     .12       0
  5595.4     .16       0
Bank Sta=4990.4,5011.4
XS Rating Curve= 0 ,0
Exp/Cntr=0.3,0.1

Type RM Length L Ch R = 1 ,103     ,0,0,0
BEGIN DESCRIPTION:
UNT 005 IN CACR 1.0
END DESCRIPTION:
XS GIS Cut Line= 4
      3695910.04     10781306.45      3695420.47     10781285.62
      3695347.55     10781389.79      3695660.06      10782441.9
#Sta/Elev= 30
  4449.7  431.31  4595.3  422.75  4620.3  421.83  4694.2   413.9    4710  411.26
  4720.4   406.3  4780.4  400.78  4806.1  400.19  4830.5  397.52  4860.5  395.34
  4937.6  393.91  4986.4  394.74  4998.2  392.45    5001  391.95  5004.2  392.45
  5016.1  394.41  5057.9  393.07  5178.4  395.26  5518.4  396.75  5588.9  397.41
  5798.4  398.85  5931.2   397.5  6019.5  400.79  6058.3  404.69  6107.7   416.7
  6112.9  416.55  6131.3  422.97  6146.1  425.08  6152.2  428.82  6164.4  430.44
#Mann= 9 ,-1 , 0
  4449.7     .16       0  4595.3     .12       0  4694.2     .05       0
  4806.1     .12       0  4998.2     .07       0  5004.2     .12       0
  5178.4     .16       0  5518.4     .12       0  6019.5     .16       0
Bank Sta=4830.5,5588.9
XS Rating Curve= 0 ,0
Exp/Cntr=0.3,0.1

Chan Stop Cuts=-1
Use User Specified Reach Order=0
Composite Channel Slope=5