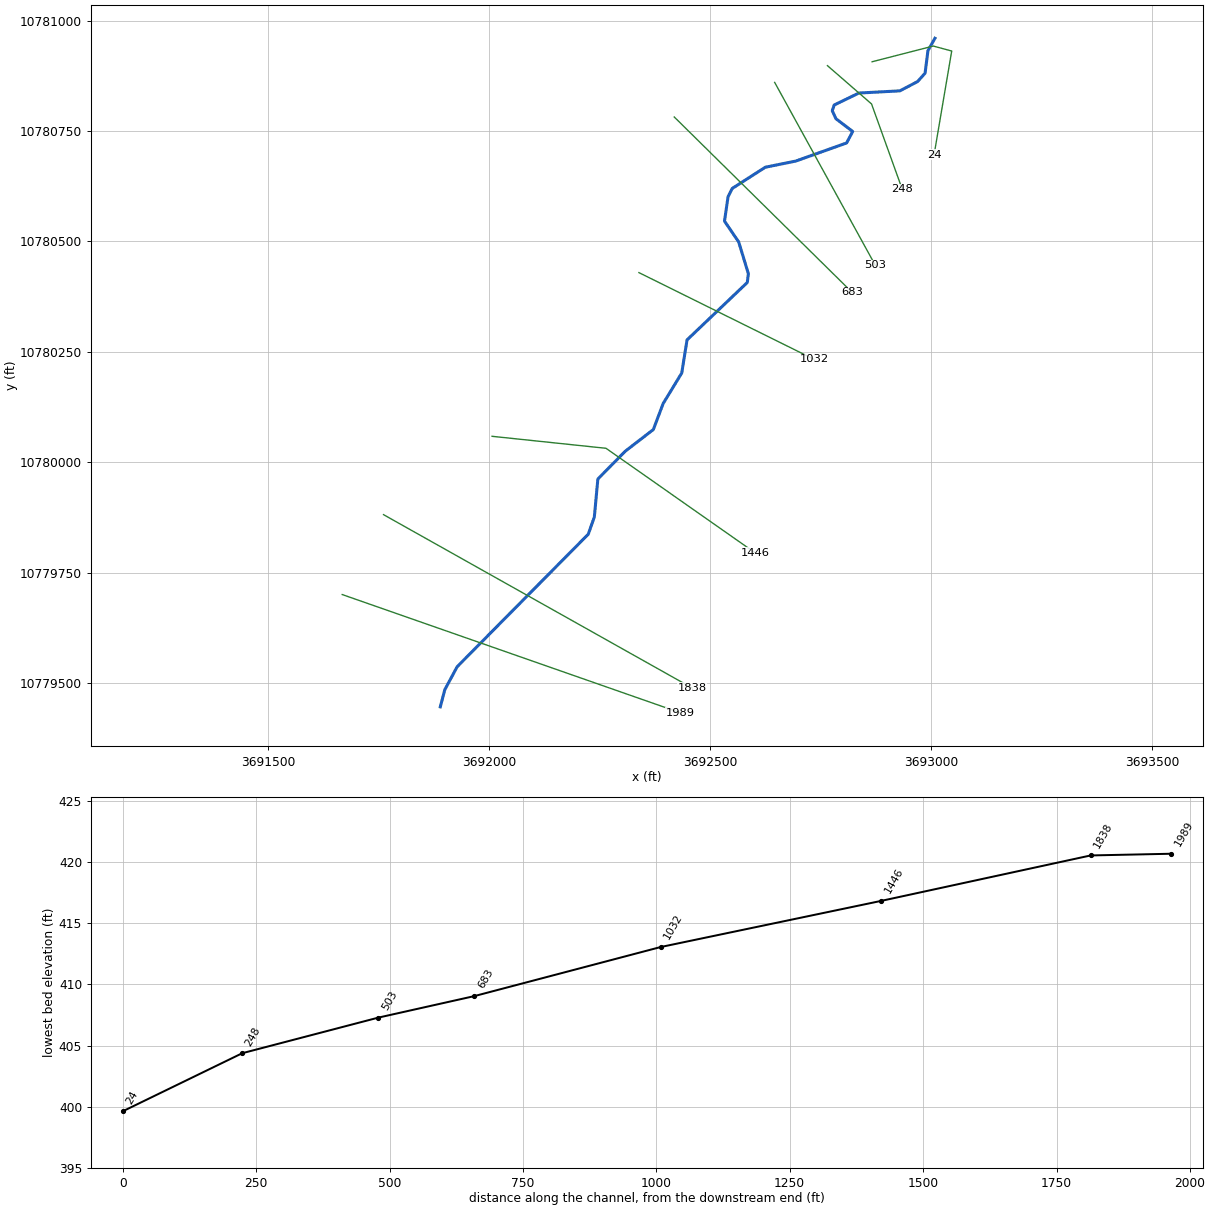
--- UNT 007 IN CACR.prj (project) ---

Proj Title=UNT 007 IN CACR Base Level Engineering
Current Plan=p01
Default Exp/Contr=0.3,0.1
English Units
Geom File=g01
Flow File=f01
Plan File=p01
Y Axis Title=Elevation
X Axis Title(PF)=Main Channel Distance
X Axis Title(XS)=Station
BEGIN DESCRIPTION:
UNT 007 IN CACR
END DESCRIPTION:
DSS Export Rating Curves= 0
DSS Export Rating Curve Sorted= 0
DSS Export Volume Flow Curves= 0
DXF OffsetX= 0
DXF OffsetY= 0
DXF ScaleX= 1
DXF ScaleY= 10

--- UNT 007 IN CACR.p01 (plan) ---

Plan Title=Multiple Run
Short Identifier=Multiple
Geom File=g01
Flow File=f01
Subcritical Flow
K Sum by GR= 0
Std Step Tol= 0.01
Critical Tol= 0.01
Num of Std Step Trials= 20
Max Error Tol= 0.3
Flow Tol Ratio= 0.001
Split Flow NTrial= 30
Split Flow Tol= 0.02
Split Flow Ratio= 0.02
Log Output Level= 0
Friction Slope Method= 1
Unsteady Friction Slope Method= 2
Unsteady Bridges Friction Slope Method= 1
Parabolic Critical Depth
Global Vel Dist=  1 , 1 , 1
Global Log Level= 0
CheckData=True
Encroach Param= -1, 0, 0, 0
BEGIN DESCRIPTION:
Multiple Run
END DESCRIPTION:

--- UNT 007 IN CACR.f01 (steady flow) ---

Flow Title=Multiple
Number of Profiles=7
Profile Names=10-year,25-year,50-year,1pct_min,100-year,1pct_plu,500-year
River Rch & RM= UNT 007 IN CACR,Reach-1,1989
     158     195     222     186     251     340     322
River Rch & RM= UNT 007 IN CACR,Reach-1,24
     966    1338    1649    1489    2013    2723    3010
Boundary for River Rch & Prof#=UNT 007 IN CACR,Reach-1,1
Up Type=0
Dn Type=3
Dn Slope=0.005
Boundary for River Rch & Prof#=UNT 007 IN CACR,Reach-1,2
Up Type=0
Dn Type=3
Dn Slope=0.005
Boundary for River Rch & Prof#=UNT 007 IN CACR,Reach-1,3
Up Type=0
Dn Type=3
Dn Slope=0.005
Boundary for River Rch & Prof#=UNT 007 IN CACR,Reach-1,4
Up Type=0
Dn Type=3
Dn Slope=0.005
Boundary for River Rch & Prof#=UNT 007 IN CACR,Reach-1,5
Up Type=0
Dn Type=3
Dn Slope=0.005
Boundary for River Rch & Prof#=UNT 007 IN CACR,Reach-1,6
Up Type=0
Dn Type=3
Dn Slope=0.005
Boundary for River Rch & Prof#=UNT 007 IN CACR,Reach-1,7
Up Type=0
Dn Type=3
Dn Slope=0.005

--- UNT 007 IN CACR.g01 (geometry) ---

Geom Title=Existing Conditions
Program Version=4.10

River Reach=UNT 007 IN CACR ,Reach-1
Reach XY= 30
       3691889.5       10779446.      3691899.75       10779485.
      3691927.75       10779537.      3692224.25       10779837.
        3692238.       10779876.        3692246.       10779962.
        3692308.       10780025.       3692371.5       10780074.
      3692393.75       10780133.      3692435.75       10780202.
      3692447.75       10780277.        3692584.       10780407.
       3692586.5       10780427.       3692564.5       10780499.
       3692532.5       10780546.       3692540.5       10780601.
        3692550.       10780620.      3692624.75       10780668.
      3692693.75       10780682.      3692808.75       10780723.
       3692822.5       10780749.       3692784.5       10780778.
      3692776.25       10780796.      3692780.75       10780809.
       3692836.5       10780836.      3692929.25       10780841.
      3692969.25       10780862.      3692986.25       10780881.
      3692992.75       10780932.       3693008.5       10780960.

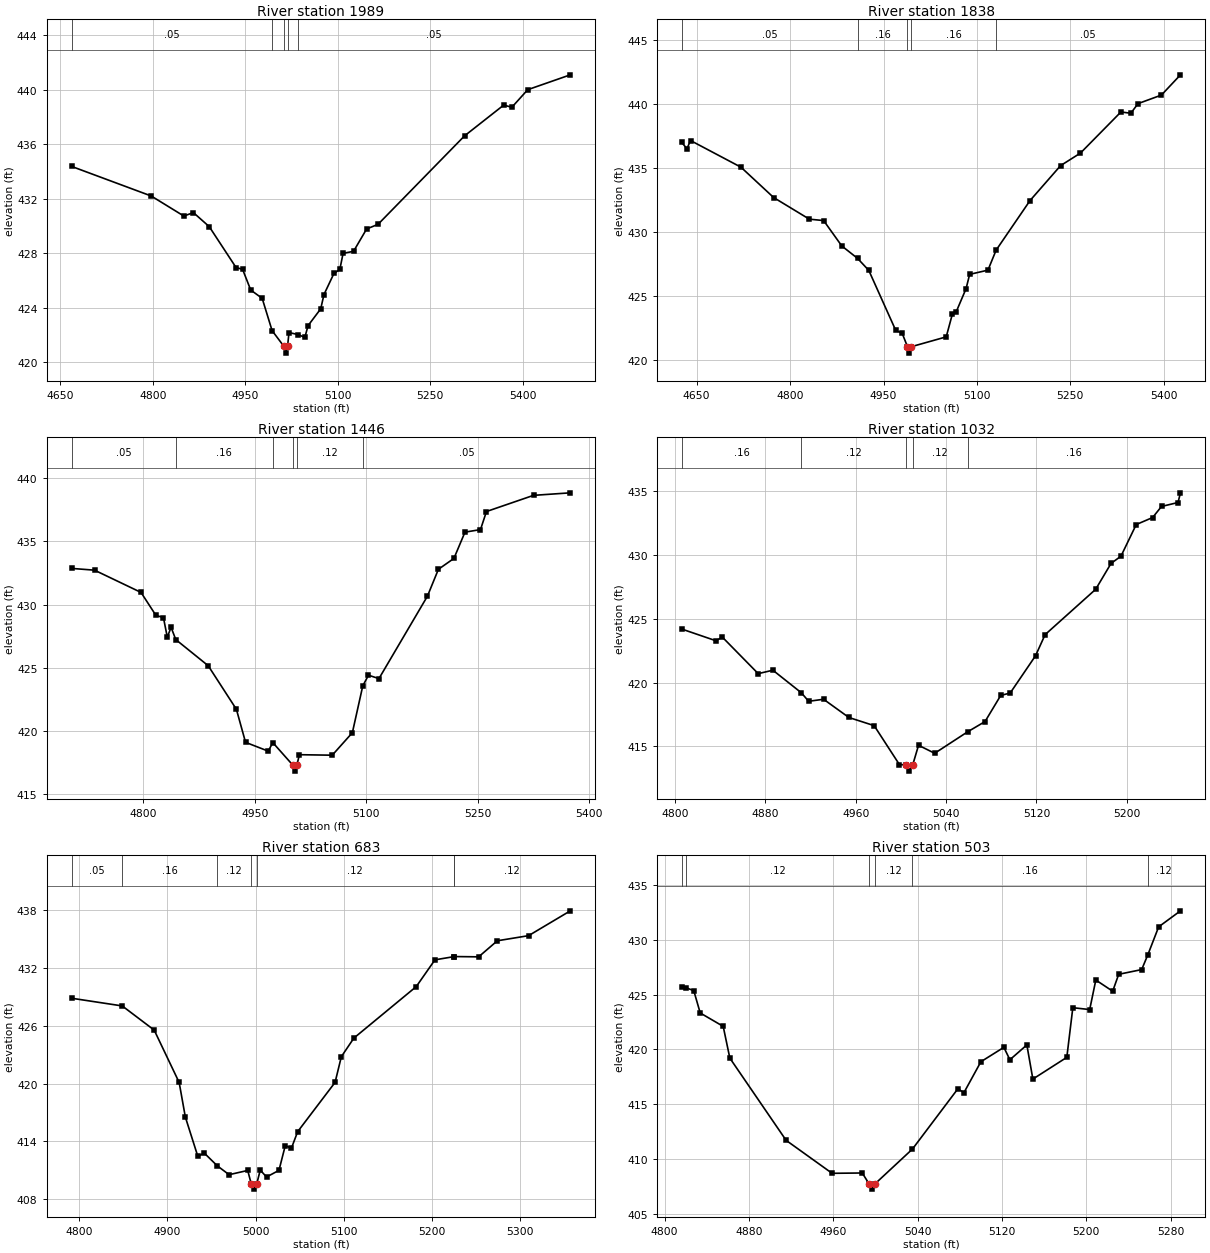
Type RM Length L Ch R = 1 ,1989    ,151,151,151
BEGIN DESCRIPTION:
UNT 007 IN CACR 4.0
END DESCRIPTION:
XS GIS Cut Line= 2
       3691667.7     10779700.36      3692431.66     10779432.98
#Sta/Elev= 30
  4668.2  434.38  4797.4  432.21  4850.3  430.74  4865.9  430.99  4891.6  429.96
  4935.1  426.96  4945.7  426.83  4958.9  425.31  4977.5   424.7  4993.6  422.33
  5012.7  421.18  5015.4  420.68  5018.7  421.18    5021  422.19  5035.9  422.04
  5046.7  421.83    5052   422.7  5072.5  423.93  5077.8  424.98    5094  426.53
  5103.5  426.82  5108.8     428  5125.8  428.15    5147  429.79  5165.5  430.13
  5305.9  436.62  5369.5  438.88  5382.7  438.72  5408.5  440.01  5477.6   441.1
#Mann= 5 ,-1 , 0
  4668.2     .05       0  4993.6     .16       0  5012.7     .07       0
  5018.7     .16       0  5035.9     .05       0
Bank Sta=5012.7,5018.7
XS Rating Curve= 0 ,0
Exp/Cntr=0.3,0.1

Type RM Length L Ch R = 1 ,1838    ,392,392,392
BEGIN DESCRIPTION:
Mapping XS 566d6b4b
END DESCRIPTION:
XS GIS Cut Line= 2
      3691761.05     10779881.34      3692459.02     10779488.95
#Sta/Elev= 30
  4626.1  436.99  4634.4   436.5  4640.2  437.14  4721.1  435.06  4773.6  432.69
  4830.9     431  4853.9  430.89    4883  428.91  4908.3  427.94  4926.4     427
  4969.7  422.31  4979.9   422.1  4988.5  421.04  4991.3  420.54  4994.5  421.04
  5050.7  421.81  5060.4  423.56  5066.6  423.75  5082.6  425.58  5088.3  426.69
  5117.7  427.02  5130.8  428.58  5185.2  432.45  5234.3  435.18  5266.2  436.16
  5331.2  439.37  5347.1  439.27  5358.6  440.02  5396.2  440.69  5426.8  442.27
#Mann= 5 ,-1 , 0
  4626.1     .05       0  4908.3     .16       0  4988.5     .07       0
  4994.5     .16       0  5130.8     .05       0
Bank Sta=4988.5,4994.5
XS Rating Curve= 0 ,0
Exp/Cntr=0.3,0.1

Type RM Length L Ch R = 1 ,1446    ,414,414,414
BEGIN DESCRIPTION:
UNT 007 IN CACR 3.0
END DESCRIPTION:
XS GIS Cut Line= 3
      3692006.62     10780058.71      3692264.47     10780031.58
      3692602.12     10779794.57
#Sta/Elev= 30
  4703.2  432.87  4734.1  432.73  4796.7  430.97  4816.8  429.15  4826.9  428.98
  4832.1  427.43  4837.2  428.21  4843.5  427.24  4887.2  425.17  4925.2  421.72
  4937.5  419.11  4968.1  418.41  4974.2  419.09  5000.8  417.33  5003.6  416.83
  5006.8  417.33    5010  418.13  5054.3  418.09  5081.4  419.87  5095.4  423.57
  5103.1  424.42  5117.2  424.15  5182.5  430.67  5197.3   432.8  5218.2  433.66
  5233.1  435.74    5254  435.94    5262  437.37  5325.4  438.65    5375  438.85
#Mann= 6 ,-1 , 0
  4703.2     .05       0  4843.5     .16       0  4974.2     .12       0
  5000.8     .07       0  5006.8     .12       0  5095.4     .05       0
Bank Sta=5000.8,5006.8
XS Rating Curve= 0 ,0
Exp/Cntr=0.3,0.1

Type RM Length L Ch R = 1 ,1032    ,349,349,349
BEGIN DESCRIPTION:
UNT 007 IN CACR 2.0
END DESCRIPTION:
XS GIS Cut Line= 2
      3692338.94     10780429.38       3692734.7     10780233.24
#Sta/Elev= 30
  4805.9   424.2  4836.2  423.28  4841.8  423.57  4873.6   420.7  4886.6  420.97
  4911.8   419.2  4918.3  418.53  4931.5  418.69  4953.9  417.26  4976.3  416.62
  4998.7  413.56  5004.5  413.55  5007.3  413.05  5010.5  413.55  5015.6  415.08
  5029.9  414.45    5059  416.13  5074.5  416.94  5088.4  418.99  5096.8  419.18
  5119.2   422.1  5127.7  423.76  5172.5  427.32  5186.1  429.35  5194.9  429.92
  5208.4   432.4  5222.9  432.95  5230.8  433.82  5245.4  434.13  5247.6  434.89
#Mann= 5 ,-1 , 0
  4805.9     .16       0  4911.8     .12       0  5004.5     .07       0
  5010.5     .12       0    5059     .16       0
Bank Sta=5004.5,5010.5
XS Rating Curve= 0 ,0
Exp/Cntr=0.3,0.1

Type RM Length L Ch R = 1 ,683     ,180,180,180
BEGIN DESCRIPTION:
Mapping XS eb5784aa
END DESCRIPTION:
XS GIS Cut Line= 2
      3692418.84     10780781.79      3692821.09     10780384.74
#Sta/Elev= 30
  4791.4  428.87  4848.8  428.07    4885  425.56  4913.3  420.12  4920.3  416.53
  4934.5  412.43  4941.6   412.8  4956.5  411.46  4969.9  410.54    4991  410.98
  4995.1  409.54  4997.9  409.04  5001.1  409.54  5005.2  411.02  5012.3   410.3
  5026.4  410.99  5033.5  413.54  5040.6  413.31  5047.6  415.01    5090  420.13
  5097.1   422.8  5111.3  424.73    5182  430.08  5203.2  432.86  5224.7  433.19
    5225   433.2  5252.7  433.17  5273.9  434.84  5309.3  435.37  5356.6  437.95
#Mann= 7 ,-1 , 0
  4791.4     .05       0  4848.8     .16       0  4956.5     .12       0
  4995.1     .07       0  5001.1     .12       0  5224.7     .16       0
    5225     .12       0
Bank Sta=4995.1,5001.1
XS Rating Curve= 0 ,0
Exp/Cntr=0.3,0.1

Type RM Length L Ch R = 1 ,503     ,255,255,255
BEGIN DESCRIPTION:
Mapping XS 76ed187f
END DESCRIPTION:
XS GIS Cut Line= 2
      3692645.95     10780860.19      3692873.82     10780445.69
#Sta/Elev= 30
  4816.3  425.66  4820.3  425.62  4827.7  425.35  4833.8  423.32  4855.6   422.1
  4861.9  419.21  4915.3  411.72  4958.9  408.72  4987.5  408.75  4993.8  407.78
  4996.5  407.28  4999.8  407.78  5035.1  410.93  5078.2  416.42  5083.9  416.06
    5100  418.88  5121.8  420.19  5127.5  419.06  5143.6  420.41  5149.3   417.3
  5181.5  419.28  5187.2   423.8  5203.2  423.63    5209  426.32    5225   425.3
  5230.7  426.84  5252.5  427.27  5258.4  428.63  5268.6  431.16  5289.3  432.62
#Mann= 6 ,-1 , 0
  4816.3     .16       0  4820.3     .12       0  4993.8     .07       0
  4999.8     .12       0  5035.1     .16       0  5258.4     .12       0
Bank Sta=4993.8,4999.8
XS Rating Curve= 0 ,0
Exp/Cntr=0.3,0.1

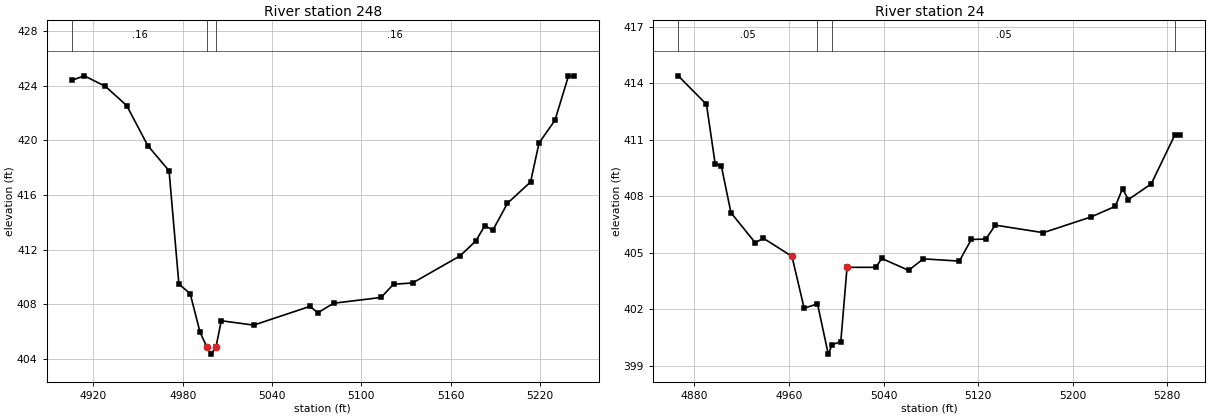
Type RM Length L Ch R = 1 ,248     ,224,224,224
BEGIN DESCRIPTION:
Mapping XS 3720dab3
END DESCRIPTION:
XS GIS Cut Line= 3
      3692765.34     10780898.12      3692865.16     10780811.32
      3692934.59     10780618.21
#Sta/Elev= 30
  4905.4  424.38  4913.8  424.71    4928  423.94  4942.3  422.54  4956.5  419.61
  4970.8  417.77  4977.4  409.49    4985  408.79  4991.6  405.98  4996.3  404.87
    4999  404.37  5002.3  404.87  5005.9  406.81  5027.7  406.49  5065.5  407.86
  5070.8  407.39  5081.4  408.09  5113.3  408.51  5121.7  409.48  5134.5  409.57
  5166.4  411.55    5177  412.64  5183.1  413.77  5188.4  413.42  5198.3   415.4
  5213.8  416.95  5219.5   419.8  5230.2  421.46  5239.2  424.67  5242.9  424.67
#Mann= 3 ,-1 , 0
  4905.4     .16       0  4996.3     .07       0  5002.3     .16       0
Bank Sta=4996.3,5002.3
XS Rating Curve= 0 ,0
Exp/Cntr=0.3,0.1

Type RM Length L Ch R = 1 ,24      ,0,0,0
BEGIN DESCRIPTION:
UNT 007 IN CACR 1.0
END DESCRIPTION:
XS GIS Cut Line= 4
      3692866.45     10780906.89      3693004.86     10780942.47
      3693046.53     10780931.18      3693006.59     10780695.92
#Sta/Elev= 30
  4866.3   414.4  4890.2  412.88  4897.5  409.74  4902.7  409.63  4910.9  407.13
  4931.5  405.53  4938.2  405.78  4962.5  404.81  4972.8  402.06  4984.1  402.29
  4993.2  399.62  4996.5  400.12  5003.8  400.28  5009.1  404.23  5033.4  404.23
  5038.5   404.7  5061.1  404.07  5073.7  404.68  5104.1  404.56  5114.2  405.71
  5126.5  405.73  5134.5  406.47  5175.1  406.07  5215.7  406.91    5236  407.47
  5242.1   408.4  5247.1  407.83  5266.4  408.66  5286.3  411.25    5291  411.25
#Mann= 4 ,-1 , 0
  4866.3     .05       0  4984.1     .03       0  4996.5     .05       0
  5286.3     .16       0
Bank Sta=4962.5,5009.1
XS Rating Curve= 0 ,0
Exp/Cntr=0.3,0.1

Chan Stop Cuts=-1
Use User Specified Reach Order=0
Composite Channel Slope=5