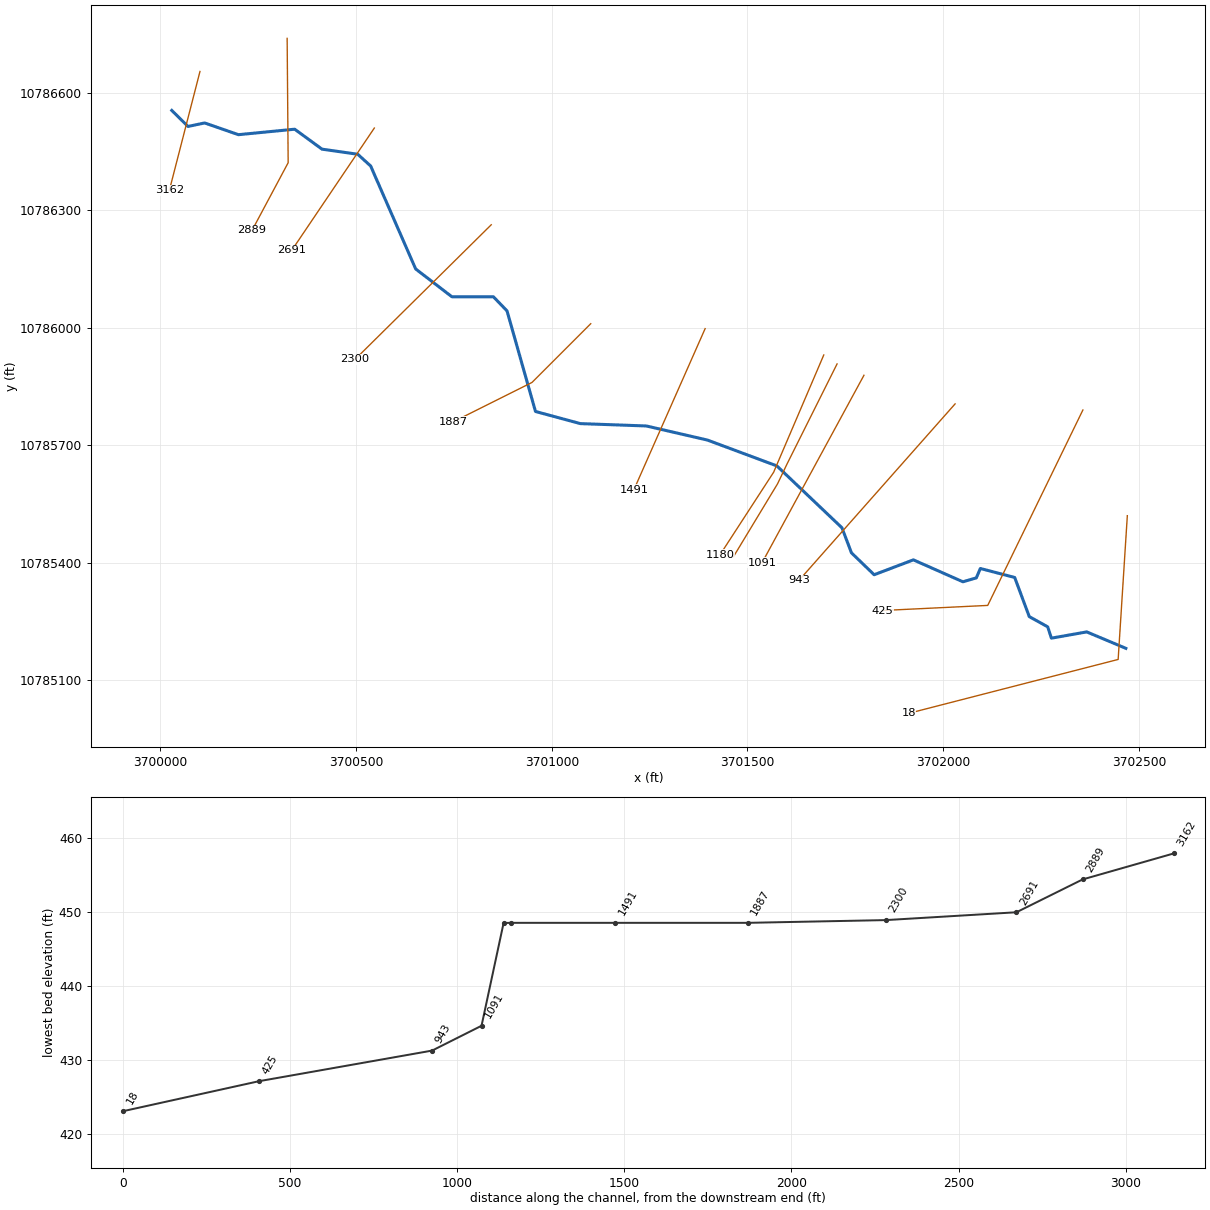
--- UNT 009 IN CACR.prj (project) ---

Proj Title=UNT 009 IN CACR Base Level Engineering
Current Plan=p01
Default Exp/Contr=0.3,0.1
English Units
Geom File=g01
Flow File=f01
Plan File=p01
BEGIN DESCRIPTION:
UNT 009 IN CACR
END DESCRIPTION:

--- UNT 009 IN CACR.p01 (plan) ---

Plan Title=Multiple Run
Short Identifier=Multiple
Geom File=g01
Flow File=f01
Subcritical Flow
K Sum by GR= 0
Std Step Tol= 0.01
Critical Tol= 0.01
Num of Std Step Trials= 20
Max Error Tol= 0.3
Flow Tol Ratio= 0.001
Split Flow NTrial= 30
Split Flow Tol= 0.02
Split Flow Ratio= 0.02
Log Output Level= 0
Friction Slope Method= 1
Unsteady Friction Slope Method= 2
Unsteady Bridges Friction Slope Method= 1
Parabolic Critical Depth
Global Vel Dist=  1 , 1 , 1
Global Log Level= 0
CheckData=True
Encroach Param= -1, 0, 0, 0
BEGIN DESCRIPTION:
Multiple Run
END DESCRIPTION:

--- UNT 009 IN CACR.f01 (steady flow) ---

Flow Title=Multiple
Number of Profiles=7
Profile Names=10-year,25-year,50-year,1pct_min,100-year,1pct_plu,500-year
River Rch & RM= UNT 009 IN CACR,Reach-1,3162
     614     833    1014     906    1226    1658    1792
Boundary for River Rch & Prof#=UNT 009 IN CACR,Reach-1,1
Up Type=0
Dn Type=3
Dn Slope=0.005
Boundary for River Rch & Prof#=UNT 009 IN CACR,Reach-1,2
Up Type=0
Dn Type=3
Dn Slope=0.005
Boundary for River Rch & Prof#=UNT 009 IN CACR,Reach-1,3
Up Type=0
Dn Type=3
Dn Slope=0.005
Boundary for River Rch & Prof#=UNT 009 IN CACR,Reach-1,4
Up Type=0
Dn Type=3
Dn Slope=0.005
Boundary for River Rch & Prof#=UNT 009 IN CACR,Reach-1,5
Up Type=0
Dn Type=3
Dn Slope=0.005
Boundary for River Rch & Prof#=UNT 009 IN CACR,Reach-1,6
Up Type=0
Dn Type=3
Dn Slope=0.005
Boundary for River Rch & Prof#=UNT 009 IN CACR,Reach-1,7
Up Type=0
Dn Type=3
Dn Slope=0.005

--- UNT 009 IN CACR.g01 (geometry) ---

Geom Title=Existing Conditions

River Reach=UNT 009 IN CACR,Reach-1
Reach XY= 30
      3700029.50     10786555.00      3700071.00     10786514.00
      3700113.50     10786523.00      3700199.75     10786493.00
      3700343.50     10786507.00      3700413.25     10786456.00
      3700504.50     10786443.00      3700537.50     10786413.00
      3700652.50     10786150.00      3700745.00     10786079.00
      3700851.00     10786079.00      3700885.75     10786043.00
      3700958.50     10785786.00      3701073.25     10785755.00
      3701241.50     10785749.00      3701397.75     10785713.00
      3701575.00     10785647.00      3701741.25     10785489.00
      3701765.50     10785425.00      3701823.50     10785369.00
      3701923.75     10785407.00      3702050.25     10785351.00
      3702084.50     10785361.00      3702094.75     10785385.00
      3702182.50     10785362.00      3702219.75     10785262.00
      3702266.75     10785236.00      3702276.25     10785207.00
      3702366.50     10785223.00      3702466.50     10785181.00

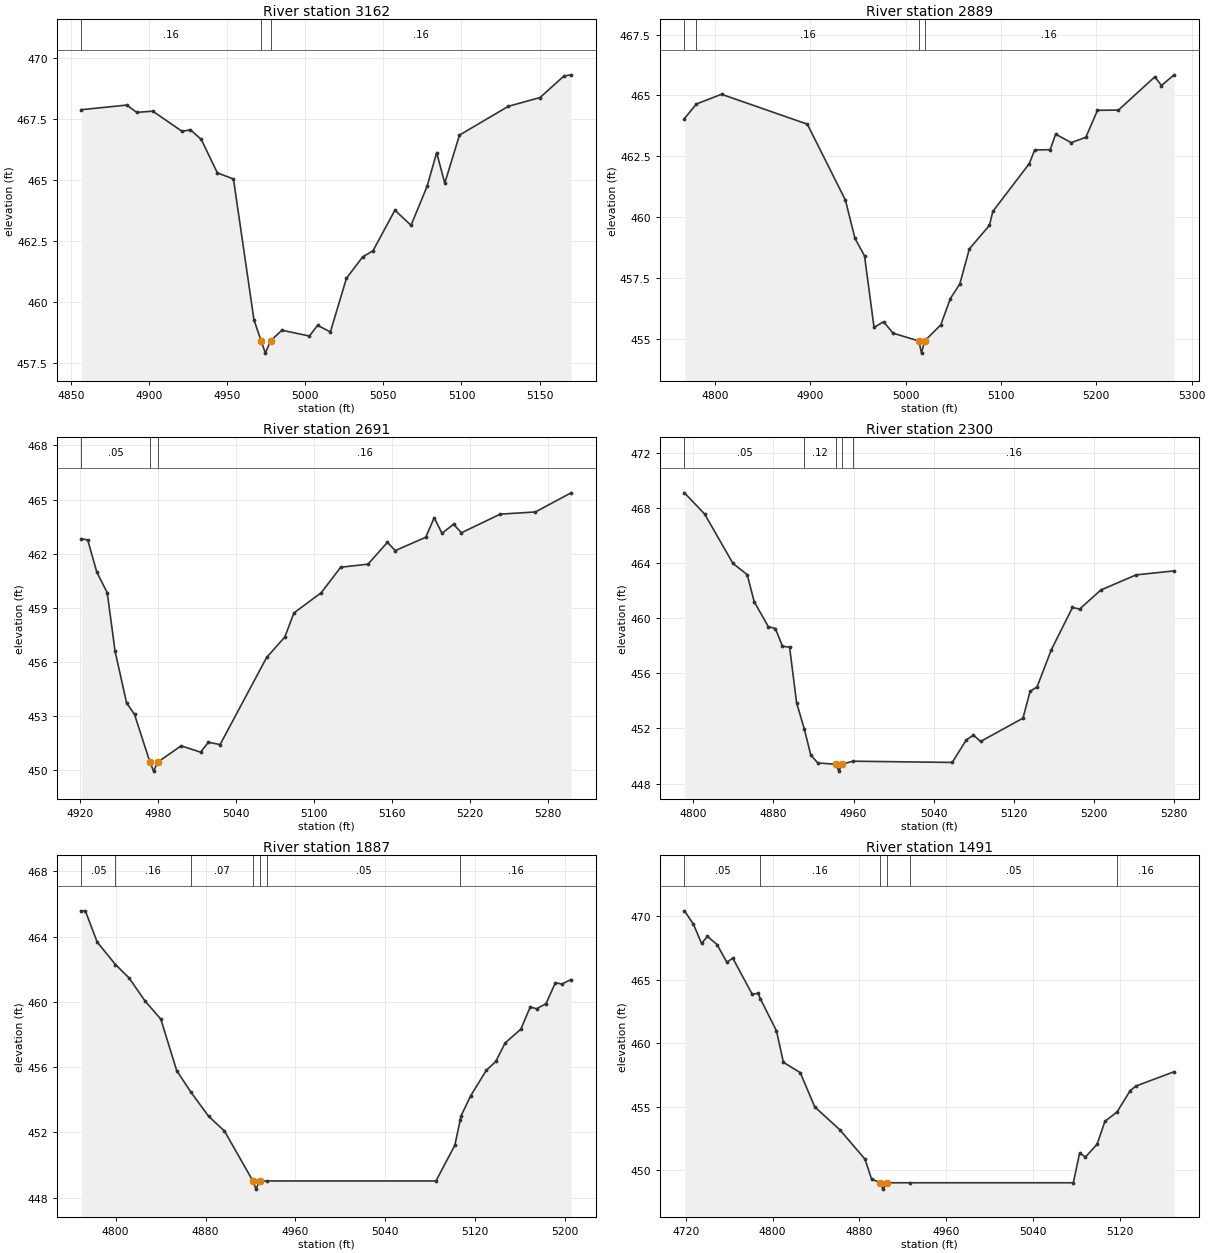
Type RM Length L Ch R = 1,3162,273,273,273
BEGIN DESCRIPTION:
UNT 009 IN CACR 4.0
END DESCRIPTION:
XS GIS Cut Line= 2
      3700101.52     10786654.44      3700023.39     10786351.04
#Sta/Elev= 30
  4856.8  467.90  4885.8  468.09  4892.2  467.79  4902.5  467.84  4921.3  467.01
  4926.5  467.08  4933.5  466.68  4943.8  465.31  4954.1  465.06  4967.2  459.29
  4971.8  458.42  4974.5  457.92  4977.8  458.42  4985.1  458.86  5002.7  458.62
  5007.9  459.06  5016.1  458.79  5026.4  460.99  5036.7  461.86  5043.4  462.12
  5057.4  463.78  5067.7  463.16  5078.0  464.76  5084.1  466.14  5089.3  464.89
  5098.7  466.86  5130.0  468.04  5150.3  468.40  5165.5  469.28  5170.1  469.33
#Mann=3,-1,0
  4856.8    0.16       0  4971.8    0.07       0  4977.8    0.16       0
Bank Sta=4971.8,4977.8
Exp/Cntr=0.3,0.1

Type RM Length L Ch R = 1,2889,198,198,198
BEGIN DESCRIPTION:
Mapping XS 16b7162b
END DESCRIPTION:
XS GIS Cut Line= 3
      3700324.19     10786739.09      3700326.79     10786421.40
      3700234.49     10786248.50
#Sta/Elev= 30
  4767.9  464.05  4780.4  464.65  4806.8  465.05  4896.8  463.82  4936.8  460.69
  4946.8  459.12  4956.8  458.40  4966.8  455.46  4976.8  455.69  4986.8  455.22
  5013.8  454.90  5016.6  454.40  5019.8  454.90  5036.8  455.56  5046.8  456.64
  5056.8  457.25  5066.8  458.69  5087.9  459.66  5091.4  460.23  5129.7  462.20
  5135.3  462.76  5151.6  462.77  5157.3  463.41  5173.6  463.06  5189.0  463.28
  5201.2  464.39  5223.2  464.40  5261.4  465.77  5268.3  465.41  5281.6  465.85
#Mann=4,-1,0
  4767.9    0.05       0  4780.4    0.16       0  5013.8    0.07       0
  5019.8    0.16       0
Bank Sta=5013.8,5019.8
Exp/Cntr=0.3,0.1

Type RM Length L Ch R = 1,2691,391,391,391
BEGIN DESCRIPTION:
Mapping XS a519ae36
END DESCRIPTION:
XS GIS Cut Line= 2
      3700546.86     10786509.96      3700335.88     10786197.41
#Sta/Elev= 30
  4920.7  462.83  4925.6  462.76  4932.5  460.99  4940.6  459.84  4946.6  456.61
  4955.5  453.74  4961.6  453.10  4973.5  450.46  4976.3  449.96  4979.5  450.46
  4997.5  451.36  5012.5  451.01  5018.5  451.56  5027.5  451.43  5063.4  456.26
  5077.3  457.38  5084.4  458.72  5105.4  459.84  5120.4  461.25  5141.4  461.42
  5156.4  462.63  5162.4  462.17  5185.9  462.91  5192.4  463.99  5198.4  463.13
  5207.3  463.63  5213.4  463.16  5243.3  464.19  5270.3  464.31  5297.8  465.37
#Mann=3,-1,0
  4920.7    0.05       0  4973.5    0.07       0  4979.5    0.16       0
Bank Sta=4973.5,4979.5
Exp/Cntr=0.3,0.1

Type RM Length L Ch R = 1,2300,413,413,413
BEGIN DESCRIPTION:
Mapping XS 43a2042f
END DESCRIPTION:
XS GIS Cut Line= 2
      3700845.48     10786262.90      3700497.35     10785918.78
#Sta/Elev= 30
  4791.0  469.08  4811.2  467.54  4839.5  463.96  4853.7  463.15  4860.7  461.19
  4874.8  459.38  4881.9  459.24  4889.0  457.96  4896.1  457.88  4903.1  453.86
  4910.8  451.96  4917.3  450.06  4924.4  449.49  4942.5  449.40  4945.3  448.90
  4948.5  449.40  4959.4  449.62  5058.7  449.53  5072.8  451.17  5079.9  451.51
  5087.0  451.05  5129.4  452.74  5136.5  454.68  5143.5  455.01  5157.7  457.69
  5178.9  460.77  5186.0  460.65  5207.2  462.03  5242.5  463.13  5280.5  463.42
#Mann=5,-1,0
  4791.0    0.05       0  4910.8    0.12       0  4942.5    0.07       0
  4948.5    0.12       0  4959.4    0.16       0
Bank Sta=4942.5,4948.5
Exp/Cntr=0.3,0.1

Type RM Length L Ch R = 1,1887,396,396,396
BEGIN DESCRIPTION:
UNT 009 IN CACR 3.0
END DESCRIPTION:
XS GIS Cut Line= 3
      3701099.61     10786010.19      3700949.61     10785860.19
      3700749.64     10785760.20
#Sta/Elev= 30
  4769.5  465.58  4773.0  465.58  4783.6  463.66  4799.8  462.29  4811.9  461.47
  4826.1  460.06  4840.2  458.94  4854.3  455.79  4867.1  454.46  4882.6  453.00
  4896.8  452.09  4922.1  449.03  4924.8  448.53  4928.1  449.03  4934.9  449.03
  5085.0  449.03  5101.8  451.22  5106.6  452.77  5107.4  453.03  5115.8  454.24
  5129.8  455.81  5138.2  456.35  5146.5  457.48  5160.5  458.33  5168.9  459.69
  5174.5  459.58  5182.9  459.89  5191.3  461.18  5196.9  461.09  5205.2  461.37
#Mann=7,-1,0
  4769.5    0.05       0  4799.8    0.16       0  4867.1    0.07       0
  4922.1   0.033       0  4928.1    0.07       0  4934.9    0.05       0
  5106.6    0.16       0
Bank Sta=4922.1,4928.1
Exp/Cntr=0.3,0.1

Type RM Length L Ch R = 1,1491,311,311,311
BEGIN DESCRIPTION:
Mapping XS dea71b60
END DESCRIPTION:
XS GIS Cut Line= 2
      3701391.81     10785997.65      3701209.53     10785585.35
#Sta/Elev= 30
  4718.9  470.41  4727.1  469.37  4734.6  467.85  4740.1  468.40  4748.9  467.76
  4757.9  466.37  4763.4  466.69  4781.2  463.86  4786.7  463.92  4788.7  463.51
  4803.6  460.98  4810.0  458.50  4825.5  457.69  4838.8  455.00  4862.0  453.19
  4885.1  450.89  4891.1  449.34  4899.0  449.03  4901.7  448.53  4905.0  449.03
  4926.5  449.03  5076.9  449.03  5082.7  451.36  5088.1  451.06  5098.8  452.06
  5106.0  453.86  5117.1  454.59  5129.3  456.28  5134.7  456.64  5169.7  457.76
#Mann=6,-1,0
  4718.9    0.05       0  4788.7    0.16       0  4899.0   0.033       0
  4905.0    0.16       0  4926.5    0.05       0  5117.1    0.16       0
Bank Sta=4899,4905
Exp/Cntr=0.3,0.1

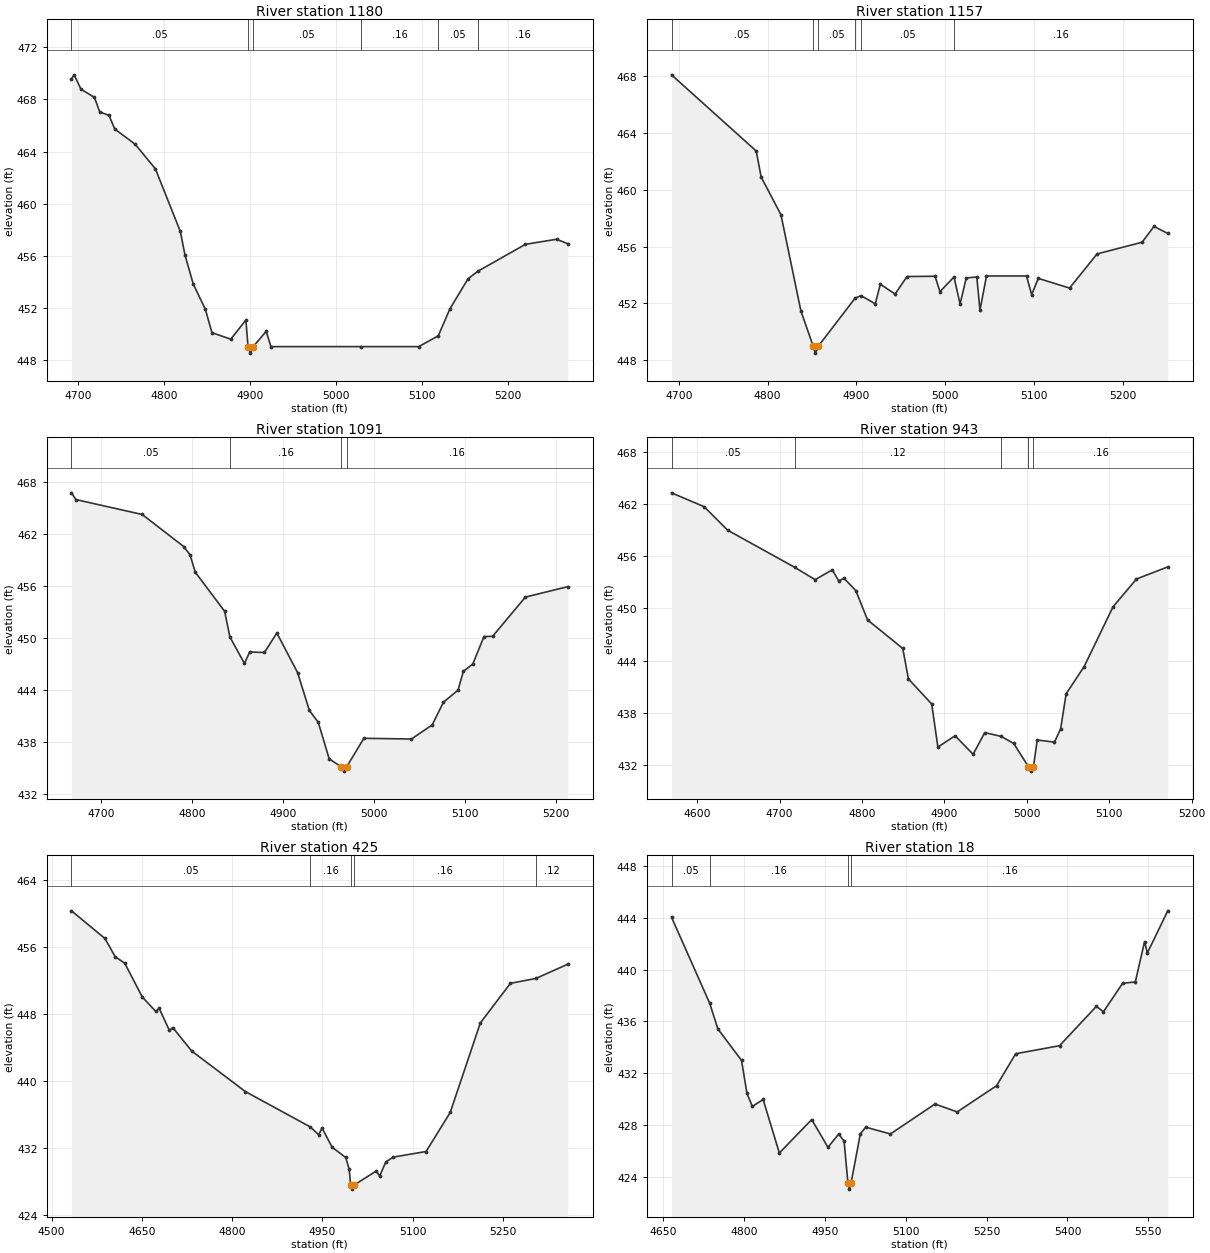
Type RM Length L Ch R = 1,1180,23,23,23
BEGIN DESCRIPTION:
Mapping XS d2151c78
END DESCRIPTION:
XS GIS Cut Line= 3
      3701694.84     10785930.34      3701566.80     10785630.86
      3701430.09     10785420.37
#Sta/Elev= 30
  4692.3  469.58  4695.4  469.89  4703.3  468.79  4719.0  468.16  4725.1  467.05
  4736.0  466.77  4742.6  465.73  4766.2  464.57  4789.8  462.68  4818.8  457.87
  4824.3  456.04  4833.9  453.82  4847.8  451.91  4855.6  450.10  4877.4  449.60
  4895.0  451.07  4897.5  449.03  4900.2  448.53  4903.5  449.03  4918.6  450.20
  4924.1  449.03  5029.1  449.03  5095.9  449.03  5118.6  449.86  5132.1  451.93
  5153.2  454.24  5164.5  454.81  5219.8  456.88  5256.0  457.27  5269.0  456.93
#Mann=6,-1,0
  4692.3    0.05       0  4897.5   0.035       0  4903.5    0.05       0
  5029.1    0.16       0  5118.6    0.05       0  5164.5    0.16       0
Bank Sta=4897.5,4903.5
Exp/Cntr=0.3,0.1

Type RM Length L Ch R = 1,1157,66,66,66
BEGIN DESCRIPTION:
Mapping XS 4a6c94ab
END DESCRIPTION:
XS GIS Cut Line= 4
      3701728.80     10785907.46      3701600.74     10785651.34
      3701576.87     10785601.43      3701464.42     10785415.46
#Sta/Elev= 30
  4691.7  468.06  4787.1  462.71  4792.7  460.88  4815.0  458.23  4837.4  451.49
  4851.2  449.01  4853.9  448.51  4857.2  449.01  4898.5  452.37  4905.2  452.55
  4921.3  451.97  4926.9  453.35  4943.6  452.66  4957.0  453.89  4988.6  453.91
  4994.1  452.83  5009.9  453.86  5016.8  451.96  5023.7  453.79  5035.6  453.86
  5039.2  451.52  5046.5  453.93  5091.6  453.93  5097.4  452.62  5104.9  453.76
  5140.1  453.08  5171.1  455.48  5221.8  456.30  5235.2  457.41  5250.7  456.92
#Mann=6,-1,0
  4691.7    0.05       0  4851.2   0.035       0  4857.2    0.05       0
  4898.5    0.16       0  4905.2    0.05       0  5009.9    0.16       0
Bank Sta=4851.2,4857.2
Exp/Cntr=0.3,0.1

Type RM Length L Ch R = 1,1091,148,148,148
BEGIN DESCRIPTION:
Mapping XS 96b663dc
END DESCRIPTION:
XS GIS Cut Line= 2
      3701797.46     10785878.48      3701537.07     10785399.37
#Sta/Elev= 30
  4667.6  466.75  4672.5  465.97  4745.3  464.25  4790.9  460.55  4797.9  459.59
  4803.6  457.59  4835.9  453.07  4841.7  450.10  4857.7  447.04  4863.4  448.37
  4879.6  448.31  4893.3  450.56  4916.1  445.98  4929.0  441.62  4938.8  440.25
  4950.8  436.03  4964.0  435.11  4966.8  434.61  4970.0  435.11  4988.9  438.40
  5041.2  438.32  5064.0  439.95  5076.3  442.56  5092.4  443.97  5098.2  446.12
  5108.6  446.98  5120.9  450.15  5130.4  450.18  5166.4  454.71  5212.9  455.91
#Mann=4,-1,0
  4667.6    0.05       0  4841.7    0.16       0  4964.0    0.07       0
  4970.0    0.16       0
Bank Sta=4964,4970
Exp/Cntr=0.3,0.1

Type RM Length L Ch R = 1,943,518,518,518
BEGIN DESCRIPTION:
Mapping XS 77c37749
END DESCRIPTION:
XS GIS Cut Line= 2
      3702030.29     10785805.42      3701631.48     10785354.60
#Sta/Elev= 30
  4569.0  463.33  4608.6  461.73  4637.0  459.03  4718.5  454.74  4743.2  453.32
  4764.1  454.46  4771.7  453.18  4778.3  453.48  4792.6  452.05  4806.8  448.68
  4849.5  445.39  4856.4  441.88  4884.6  438.99  4892.1  434.02  4913.0  435.33
  4934.8  433.19  4949.0  435.69  4968.9  435.25  4984.1  434.44  5002.0  431.75
  5004.8  431.25  5008.0  431.75  5012.6  434.84  5033.5  434.59  5041.0  436.13
  5047.7  440.17  5069.5  443.30  5104.6  450.20  5133.0  453.40  5170.9  454.79
#Mann=5,-1,0
  4569.0    0.05       0  4718.5    0.12       0  4968.9    0.16       0
  5002.0    0.07       0  5008.0    0.16       0
Bank Sta=5002,5008
Exp/Cntr=0.3,0.1

Type RM Length L Ch R = 1,425,407,407,407
BEGIN DESCRIPTION:
UNT 009 IN CACR 2.0
END DESCRIPTION:
XS GIS Cut Line= 3
      3702356.68     10785789.80      3702113.62     10785290.66
      3701844.61     10785277.65
#Sta/Elev= 30
  4533.0  460.32  4588.6  457.02  4605.6  454.85  4621.6  454.06  4650.6  450.04
  4673.2  448.31  4678.7  448.68  4695.7  446.05  4701.3  446.39  4732.8  443.59
  4821.8  438.76  4929.9  434.53  4943.7  433.60  4949.3  434.40  4966.2  432.10
  4988.6  430.89  4994.4  429.49  4996.9  427.61  4999.7  427.11  5002.9  427.61
  5039.4  429.27  5045.0  428.67  5055.3  430.35  5067.5  430.93  5122.2  431.60
  5162.3  436.26  5212.3  446.94  5262.4  451.67  5304.6  452.25  5357.5  453.95
#Mann=5,-1,0
  4533.0    0.05       0  4929.9    0.16       0  4996.9    0.07       0
  5002.9    0.16       0  5304.6    0.12       0
Bank Sta=4996.9,5002.9
Exp/Cntr=0.3,0.1

Type RM Length L Ch R = 1,18,0,0,0
BEGIN DESCRIPTION:
UNT 009 IN CACR 1.0
END DESCRIPTION:
XS GIS Cut Line= 3
      3702470.18     10785519.87      3702446.74     10785152.64
      3701911.34     10785014.90
#Sta/Elev= 30
  4665.3  444.04  4736.2  437.39  4751.4  435.41  4795.2  432.99  4805.3  430.44
  4815.3  429.43  4835.3  429.97  4865.4  425.84  4925.5  428.42  4955.6  426.28
  4975.6  427.30  4985.6  426.75  4992.6  423.55  4995.4  423.05  4998.6  423.55
  5015.7  427.32  5025.7  427.83  5071.6  427.31  5154.2  429.62  5195.5  429.01
  5268.4  431.03  5304.0  433.50  5385.4  434.12  5453.7  437.16  5466.8  436.74
  5502.4  438.94  5525.9  439.04  5543.1  442.15  5548.3  441.28  5586.1  444.53
#Mann=4,-1,0
  4665.3    0.05       0  4736.2    0.16       0  4992.6    0.07       0
  4998.6    0.16       0
Bank Sta=4992.6,4998.6
Exp/Cntr=0.3,0.1

Chan Stop Cuts=-1