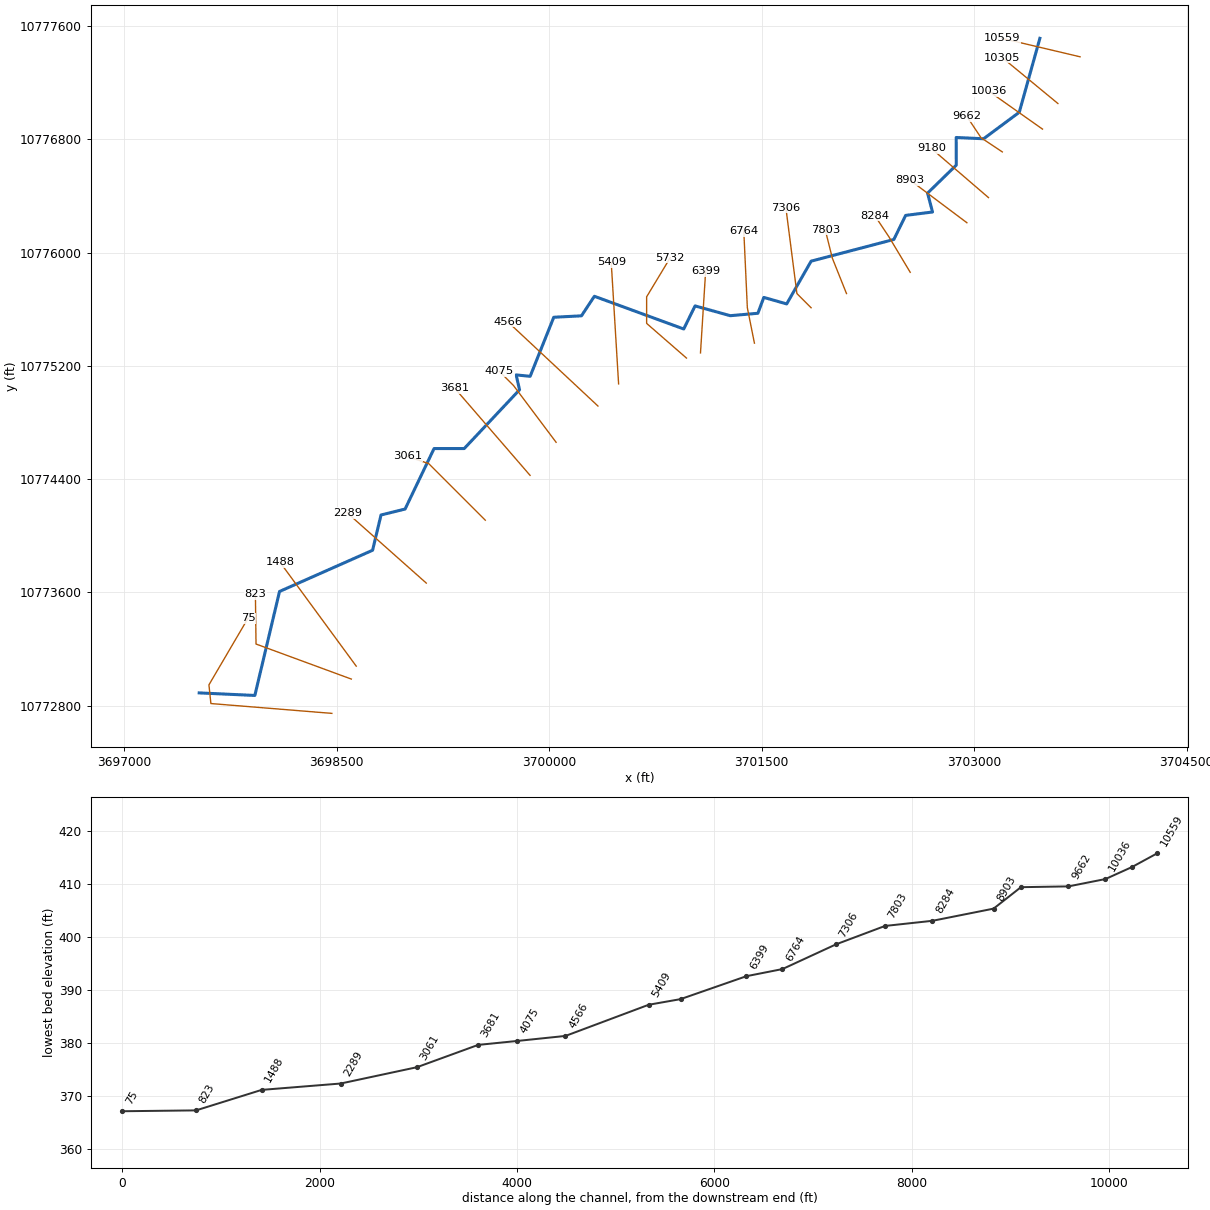
--- UNT 011 IN CACR.prj (project) ---

Proj Title=UNT 011 IN CACR Base Level Engineering
Current Plan=p01
Default Exp/Contr=0.3,0.1
English Units
Geom File=g01
Flow File=f01
Plan File=p01
Y Axis Title=Elevation
X Axis Title(PF)=Main Channel Distance
X Axis Title(XS)=Station
BEGIN DESCRIPTION:
UNT 011 IN CACR
END DESCRIPTION:
DSS Export Rating Curves= 0
DSS Export Rating Curve Sorted= 0
DSS Export Volume Flow Curves= 0
DXF OffsetX= 0
DXF OffsetY= 0
DXF ScaleX= 1
DXF ScaleY= 10

--- UNT 011 IN CACR.p01 (plan) ---

Plan Title=Multiple Run
Short Identifier=Multiple
Geom File=g01
Flow File=f01
Subcritical Flow
K Sum by GR= 0
Std Step Tol= 0.01
Critical Tol= 0.01
Num of Std Step Trials= 20
Max Error Tol= 0.3
Flow Tol Ratio= 0.001
Split Flow NTrial= 30
Split Flow Tol= 0.02
Split Flow Ratio= 0.02
Log Output Level= 0
Friction Slope Method= 1
Unsteady Friction Slope Method= 2
Unsteady Bridges Friction Slope Method= 1
Parabolic Critical Depth
Global Vel Dist=  1 , 1 , 1
Global Log Level= 0
CheckData=True
Encroach Param= -1, 0, 0, 0
BEGIN DESCRIPTION:
Multiple Run
END DESCRIPTION:

--- UNT 011 IN CACR.f01 (steady flow) ---

Flow Title=Multiple
Number of Profiles=7
Profile Names=10-year,25-year,50-year,1pct_min,100-year,1pct_plu,500-year
River Rch & RM= UNT 011 IN CACR,Reach-1,10559
     574     776     942     839    1135    1535    1651
River Rch & RM= UNT 011 IN CACR,Reach-1,9180
     702     958    1171    1049    1418    1918    2087
River Rch & RM= UNT 011 IN CACR,Reach-1,5409
     994    1384    1712    1552    2099    2838    3162
River Rch & RM= UNT 011 IN CACR,Reach-1,4075
    1096    1531    1899    1723    2331    3152    3522
Boundary for River Rch & Prof#=UNT 011 IN CACR,Reach-1,1
Up Type=0
Dn Type=3
Dn Slope=0.005
Boundary for River Rch & Prof#=UNT 011 IN CACR,Reach-1,2
Up Type=0
Dn Type=3
Dn Slope=0.005
Boundary for River Rch & Prof#=UNT 011 IN CACR,Reach-1,3
Up Type=0
Dn Type=3
Dn Slope=0.005
Boundary for River Rch & Prof#=UNT 011 IN CACR,Reach-1,4
Up Type=0
Dn Type=3
Dn Slope=0.005
Boundary for River Rch & Prof#=UNT 011 IN CACR,Reach-1,5
Up Type=0
Dn Type=3
Dn Slope=0.005
Boundary for River Rch & Prof#=UNT 011 IN CACR,Reach-1,6
Up Type=0
Dn Type=3
Dn Slope=0.005
Boundary for River Rch & Prof#=UNT 011 IN CACR,Reach-1,7
Up Type=0
Dn Type=3
Dn Slope=0.005

--- UNT 011 IN CACR.g01 (geometry) ---

Geom Title=Existing Conditions
Program Version=4.10

River Reach=UNT 011 IN CACR ,Reach-1
Reach XY= 30
      3703464.75       10777512.      3703319.25       10776990.
      3703067.75       10776803.        3702874.       10776812.
      3702874.75       10776617.      3702671.75       10776419.
        3702707.       10776286.      3702517.25       10776262.
      3702433.75       10776092.        3701850.       10775939.
      3701677.25       10775637.      3701515.75       10775683.
        3701474.       10775571.        3701279.       10775554.
       3701030.5       10775623.       3700950.5       10775460.
      3700319.75       10775691.       3700228.5       10775553.
        3700033.       10775543.      3699866.25       10775126.
      3699767.25       10775136.       3699791.5       10775031.
        3699401.       10774616.        3699188.       10774616.
       3698983.5       10774189.       3698813.5       10774147.
        3698754.       10773898.        3698097.       10773607.
      3697922.75       10772873.      3697529.75       10772891.

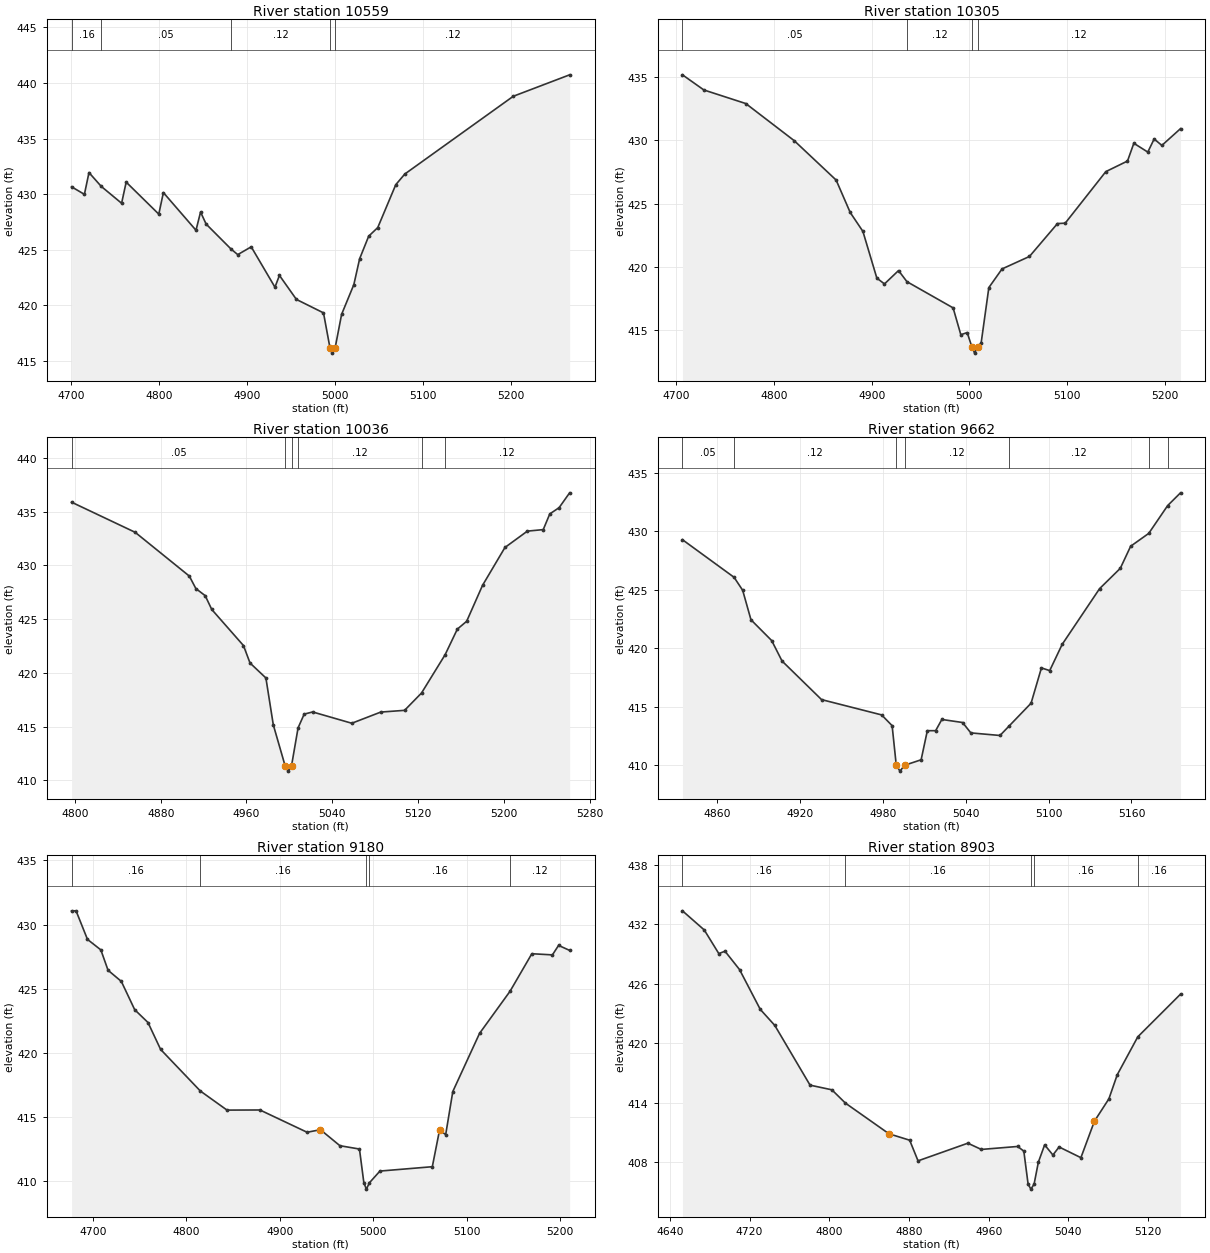
Type RM Length L Ch R = 1 ,10559   ,254,254,254
BEGIN DESCRIPTION:
UNT 011 IN CACR 19.0
END DESCRIPTION:
XS GIS Cut Line= 2
      3703748.47     10777381.73      3703197.24     10777511.94
#Sta/Elev= 30
  4700.6  430.66  4715.2  429.98  4720.4  431.94  4734.3   430.7  4757.5  429.18
  4762.7  431.08  4799.8   428.2    4805  430.14  4842.1  426.75  4847.3  428.39
  4853.6  427.31  4882.1  425.05  4889.6  424.56  4904.9  425.26  4931.9  421.63
    4937  422.69  4956.3  420.53  4987.1  419.32  4994.4   416.2  4997.2   415.7
  5000.4   416.2  5007.7  419.19  5021.6  421.86  5028.2  424.19  5038.5  426.22
  5048.8  426.99  5069.3  430.85  5079.6  431.81  5202.9   438.8    5267  440.73
#Mann= 5 ,-1 , 0
  4700.6     .16       0  4734.3     .05       0  4882.1     .12       0
  4994.4     .07       0  5000.4     .12       0
Bank Sta=4994.4,5000.4
XS Rating Curve= 0 ,0
Exp/Cntr=0.3,0.1

Type RM Length L Ch R = 1 ,10305   ,269,269,269
BEGIN DESCRIPTION:
Mapping XS 581d9bfc
END DESCRIPTION:
XS GIS Cut Line= 2
      3703592.21     10777051.89      3703198.58     10777376.31
#Sta/Elev= 30
  4706.2  435.21  4728.1  434.01  4771.1  432.93  4820.6  429.99  4863.6  426.86
    4878  424.29    4891  422.79  4905.3  419.08  4913.1  418.62  4927.5  419.68
  4936.1   418.8  4983.4  416.72  4991.3  414.59  4997.8  414.76  5002.6  413.63
  5005.4  413.13  5008.6  413.63  5012.1  413.93    5020  418.33  5033.5  419.81
  5061.6   420.8  5090.3  423.41  5098.2  423.44  5139.8  427.53    5162  428.37
  5168.5  429.78  5182.8  429.08  5189.3  430.12  5197.2  429.61  5216.3  430.94
#Mann= 4 ,-1 , 0
  4706.2     .05       0  4936.1     .12       0  5002.6     .07       0
  5008.6     .12       0
Bank Sta=5002.6,5008.6
XS Rating Curve= 0 ,0
Exp/Cntr=0.3,0.1

Type RM Length L Ch R = 1 ,10036   ,374,374,374
BEGIN DESCRIPTION:
Mapping XS 5aabfc2d
END DESCRIPTION:
XS GIS Cut Line= 2
      3703483.33     10776871.19      3703103.86      10777138.9
#Sta/Elev= 30
  4796.9  435.87  4856.2  433.07  4906.7     429  4912.8  427.84  4921.5  427.18
  4927.6   425.9  4957.2  422.54  4963.3  420.92  4978.1  419.53    4985  415.17
    4996  411.37  4998.8  410.87    5002  411.37  5008.1  414.89  5013.8  416.17
  5021.7  416.37  5058.2  415.32  5085.2  416.36  5107.4  416.52  5123.2  418.13
  5145.2  421.69  5156.6  424.07  5165.3   424.8  5180.1  428.14    5201  431.66
  5221.9  433.18  5236.7  433.32  5242.8  434.78  5251.5  435.36  5261.3  436.74
#Mann= 6 ,-1 , 0
  4796.9     .05       0    4996     .03       0    5002     .05       0
  5008.1     .12       0  5123.2     .16       0  5145.2     .12       0
Bank Sta=4996,5002
XS Rating Curve= 0 ,0
Exp/Cntr=0.3,0.1

Type RM Length L Ch R = 1 ,9662    ,482,482,482
BEGIN DESCRIPTION:
UNT 011 IN CACR 18.0
END DESCRIPTION:
XS GIS Cut Line= 3
      3703199.63     10776710.18      3703049.61     10776810.19
       3702949.6     10776960.21
#Sta/Elev= 30
  4834.9  429.29  4872.3  426.07  4878.5  424.96  4884.5  422.44  4899.5  420.66
    4907  418.91  4935.6  415.61  4979.1   414.3  4986.7  413.38  4989.7  409.99
  4992.4  409.49  4995.7  409.99  5007.7  410.46  5012.2  412.95  5018.2  412.95
  5022.7  413.91  5037.7  413.65  5043.7  412.76  5064.8  412.54  5071.4  413.35
  5087.3   415.3  5094.8  418.32  5100.8  418.09  5109.8  420.33  5136.9   425.1
  5151.9  426.84  5159.4  428.73  5172.5  429.83  5186.2  432.21  5195.5   433.3
#Mann= 7 ,-1 , 0
  4834.9     .05       0  4872.3     .12       0  4989.7     .07       0
  4995.7     .12       0  5071.4     .12       0  5172.5     .16       0
  5186.2     .05       0
Bank Sta=4989.7,4995.7
XS Rating Curve= 0 ,0
Exp/Cntr=0.3,0.1

Type RM Length L Ch R = 1 ,9180    ,277,277,277
BEGIN DESCRIPTION:
UNT 011 IN CACR 17.0
END DESCRIPTION:
XS GIS Cut Line= 2
      3703101.81     10776387.79      3702698.12     10776735.05
#Sta/Elev= 30
  4677.4  431.07  4682.2  431.07  4694.4  428.84  4708.7  428.02  4716.4  426.43
  4730.6  425.56  4744.9  423.35  4759.1  422.35  4772.6  420.25  4815.1     417
  4843.6  415.51  4878.8  415.52  4929.2  413.78  4943.5  413.98  4964.3  412.73
  4985.2  412.47  4989.9  409.84  4992.6  409.34  4995.9  409.84  5007.1  410.75
  5063.1  411.09  5070.8  413.94  5077.4   413.6    5085  416.96  5113.6   421.5
  5146.2  424.79  5169.5  427.72  5191.5  427.63  5198.1  428.37  5209.9  427.98
#Mann= 5 ,-1 , 0
  4677.4     .16       0  4815.1     .16       0  4992.6     .07       0
  4995.9     .16       0  5146.2     .12       0
Bank Sta=4943.5,5070.8
XS Rating Curve= 0 ,0
Exp/Cntr=0.3,0.1

Type RM Length L Ch R = 1 ,8903    ,619,619,619
BEGIN DESCRIPTION:
UNT 011 IN CACR 16.0
END DESCRIPTION:
XS GIS Cut Line= 3
      3702949.62     10776210.18      3702749.61     10776360.19
      3702549.62     10776510.18
#Sta/Elev= 30
  4652.6  433.35  4674.5  431.42  4689.1  429.04  4695.3  429.28  4709.9  427.43
  4730.7  423.42  4745.3   421.8  4780.7  415.78  4802.6  415.31  4816.2  413.97
  4859.9  410.88  4880.7  410.23  4889.1  408.15  4939.1  409.93  4952.6   409.3
  4989.1   409.6  4995.3  409.13  4999.6   405.8  5002.4   405.3  5005.6   405.8
  5009.9  408.02  5016.2  409.76  5024.5  408.74  5030.7  409.55  5052.6  408.47
  5066.2  412.15  5080.7   414.4  5089.1  416.83  5109.7  420.65  5152.6  424.95
#Mann= 5 ,-1 , 0
  4652.6     .16       0  4816.2     .16       0  5002.4     .07       0
  5005.6     .16       0  5109.7     .16       0
Bank Sta=4859.9,5066.2
XS Rating Curve= 0 ,0
Exp/Cntr=0.3,0.1

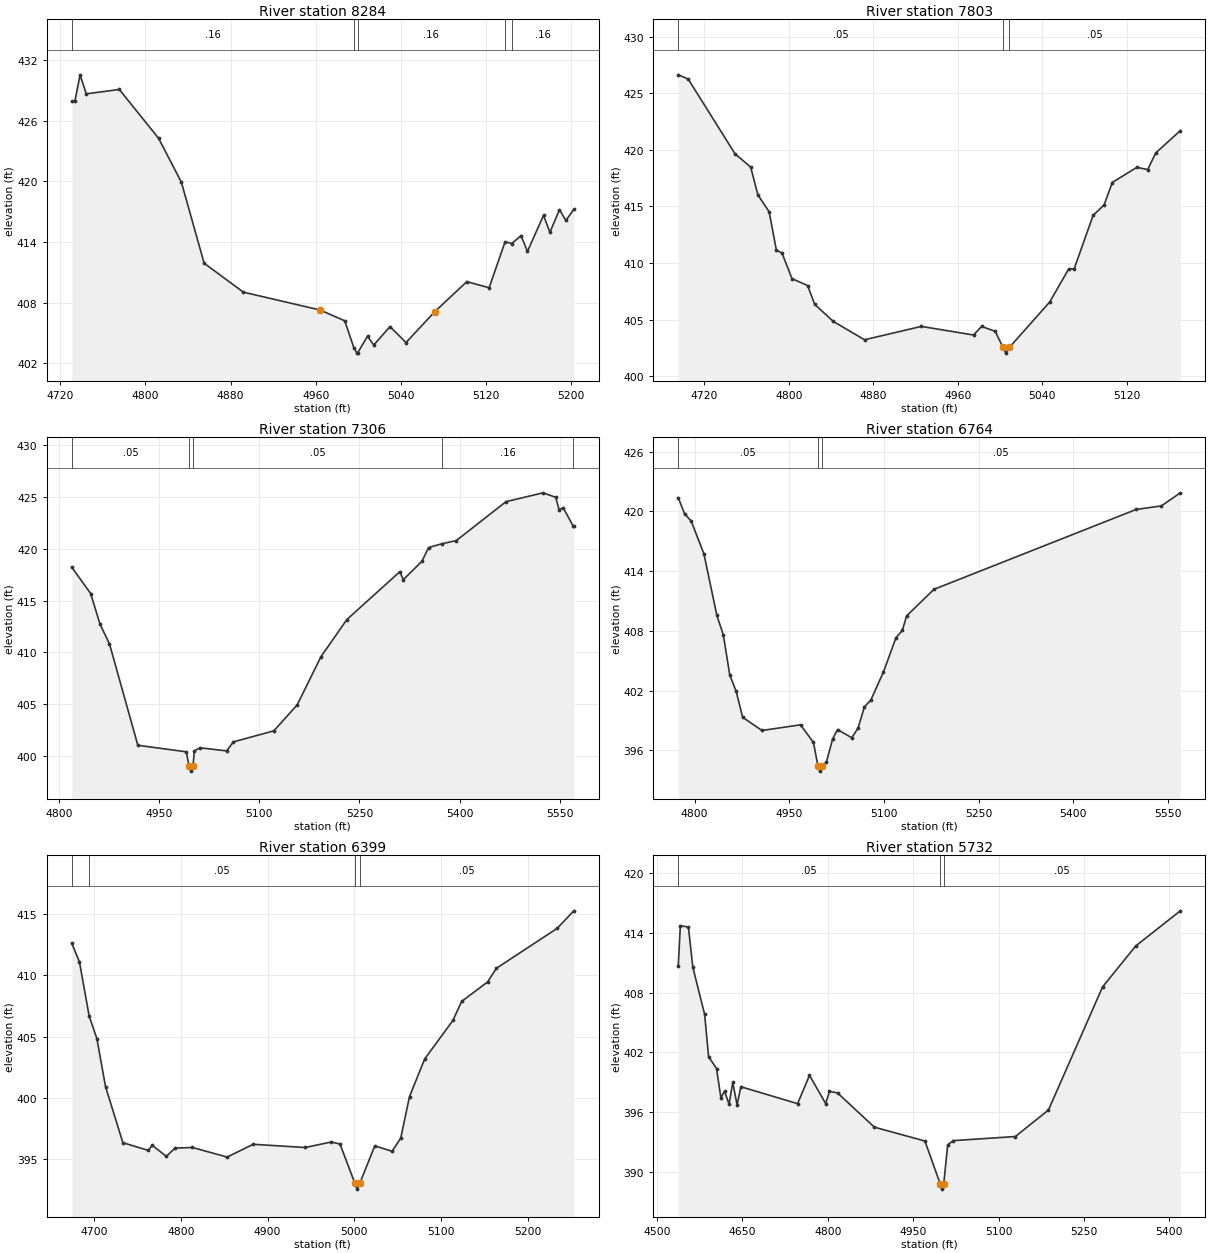
Type RM Length L Ch R = 1 ,8284    ,481,481,481
BEGIN DESCRIPTION:
UNT 011 IN CACR 15.0
END DESCRIPTION:
XS GIS Cut Line= 3
       3702549.6      10775860.2      3702399.61     10776110.19
      3702299.62     10776260.18
#Sta/Elev= 30
  4730.8  427.91  4733.7  427.91  4738.6  430.54  4744.4  428.66  4775.5  429.09
  4812.4  424.26  4833.8  419.92  4855.2   411.9  4892.1  409.04    4964  407.28
  4987.3  406.21    4996  403.51  4998.8  403.01  4999.3  403.01  5008.7  404.68
  5014.6  403.81  5029.8  405.63  5044.9  404.06  5071.9  407.11    5102  410.08
    5123  409.48    5138  414.03  5144.3  413.85    5153  414.64    5159  413.07
  5174.1  416.64  5180.1  414.96  5189.1   417.2  5195.1  416.13  5202.6  417.23
#Mann= 5 ,-1 , 0
  4730.8     .16       0    4996     .07       0  4999.3     .16       0
    5138     .12       0  5144.3     .16       0
Bank Sta=4964,5071.9
XS Rating Curve= 0 ,0
Exp/Cntr=0.3,0.1

Type RM Length L Ch R = 1 ,7803    ,497,497,497
BEGIN DESCRIPTION:
UNT 011 IN CACR 14.0
END DESCRIPTION:
XS GIS Cut Line= 3
       3702099.6      10775710.2      3701999.61     10775960.19
      3701949.61     10776160.19
#Sta/Elev= 30
  4695.3  426.62  4704.7  426.25  4749.1  419.64  4763.9  418.47  4770.7  416.02
  4781.4  414.52  4788.2  411.15  4793.6  410.87    4803  408.62  4817.8  408.01
  4824.5  406.35    4842  404.85  4871.7  403.22  4925.5   404.4  4974.9  403.64
  4982.6   404.4  4995.5  403.96  5002.8  402.54  5005.5  402.04  5008.8  402.54
    5047  406.55    5065  409.47  5070.2  409.49  5088.2  414.22  5098.5  415.12
  5106.3  417.11  5129.5  418.45  5139.8  418.25  5147.5  419.73  5170.7  421.69
#Mann= 3 ,-1 , 0
  4695.3     .05       0  5002.8     .03       0  5008.8     .05       0
Bank Sta=5002.8,5008.8
XS Rating Curve= 0 ,0
Exp/Cntr=0.3,0.1

Type RM Length L Ch R = 1 ,7306    ,542,542,542
BEGIN DESCRIPTION:
UNT 011 IN CACR 13.0
END DESCRIPTION:
XS GIS Cut Line= 3
      3701849.59      10775610.2      3701749.61     10775710.19
      3701671.64     10776315.99
#Sta/Elev= 30
  4819.1  418.21  4847.4  415.68  4861.5  412.71  4875.6  410.83  4918.1  401.06
  4990.7  400.43  4994.7  399.07  4997.5  398.57  5000.7  399.07  5002.8  400.51
  5010.9  400.82  5051.2  400.52  5061.3  401.39  5121.8  402.45  5156.7  404.94
  5192.4  409.59  5231.2  413.17  5310.7  417.79  5315.7  417.01  5343.6  418.78
  5353.7  420.11  5373.4  420.47  5395.2  420.78  5469.7  424.53  5525.1  425.38
  5544.1  424.95  5549.2  423.76  5555.4  423.94  5570.1   422.2  5571.3  422.16
#Mann= 5 ,-1 , 0
  4819.1     .05       0  4994.7     .03       0  5000.7     .05       0
  5373.4     .16       0  5570.1     .12       0
Bank Sta=4994.7,5000.7
XS Rating Curve= 0 ,0
Exp/Cntr=0.3,0.1

Type RM Length L Ch R = 1 ,6764    ,365,365,365
BEGIN DESCRIPTION:
UNT 011 IN CACR 12.0
END DESCRIPTION:
XS GIS Cut Line= 3
      3701449.61     10775360.19      3701399.61     10775610.19
      3701374.67     10776150.07
#Sta/Elev= 30
  4774.2  421.37  4784.4  419.74  4794.6  419.04    4815  415.71  4835.4  409.55
  4845.6  407.61  4855.8  403.58    4866  401.92  4876.2  399.33  4906.8     398
    4968  398.57  4988.4   396.8  4995.6  394.42  4998.3  393.92  5001.6  394.42
  5008.8   394.8  5018.9  397.17  5026.6  398.09  5049.2  397.27  5059.2  398.27
  5069.2  400.38  5079.2  401.04  5099.2  403.86  5119.2  407.32  5129.3  408.05
  5135.9   409.5  5179.3  412.17  5499.6  420.19  5539.7  420.55  5569.6  421.86
#Mann= 3 ,-1 , 0
  4774.2     .05       0  4995.6     .03       0  5001.6     .05       0
Bank Sta=4995.6,5001.6
XS Rating Curve= 0 ,0
Exp/Cntr=0.3,0.1

Type RM Length L Ch R = 1 ,6399    ,667,667,667
BEGIN DESCRIPTION:
UNT 011 IN CACR 11.0
END DESCRIPTION:
XS GIS Cut Line= 2
      3701068.82     10775291.29      3701105.28     10775869.44
#Sta/Elev= 30
  4674.1   412.6    4683  411.07  4694.2  406.66  4703.1  404.83  4713.1  400.91
  4733.1  396.36  4762.1  395.74  4767.1  396.14  4783.2  395.25  4793.2  395.92
  4813.3  395.97  4853.4  395.19  4883.4  396.23  4943.5  395.97  4973.6  396.42
  4983.6  396.25  5000.6  393.08  5003.4  392.58  5006.6  393.08  5023.7   396.1
  5043.7  395.66  5053.7  396.74  5063.8  400.12  5081.3  403.18  5113.9  406.32
  5123.9  407.86  5153.9  409.45    5164  410.56  5234.1  413.81  5253.4  415.24
#Mann= 4 ,-1 , 0
  4674.1      .1       0  4694.2     .05       0  5000.6     .03       0
  5006.6     .05       0
Bank Sta=5000.6,5006.6
XS Rating Curve= 0 ,0
Exp/Cntr=0.3,0.1

Type RM Length L Ch R = 1 ,5732    ,323,323,323
BEGIN DESCRIPTION:
UNT 011 IN CACR 10.0
END DESCRIPTION:
XS GIS Cut Line= 4
      3700969.83     10775254.88      3700688.61     10775499.65
      3700688.61     10775687.15      3700854.93     10775962.61
#Sta/Elev= 30
  4537.1  410.62  4540.8  414.71    4555  414.57  4562.7  410.54  4583.5   405.8
  4590.4  401.56  4604.4  400.37    4612  397.44  4618.6  398.08  4626.3  396.78
  4632.9  398.97  4640.5  396.71  4647.1  398.54  4746.8  396.84  4767.7  399.68
  4796.2  396.85  4802.8  398.08  4817.1  397.91  4881.7  394.48  4970.5  393.09
  4997.5  388.76  5000.2  388.26  5003.5  388.76  5010.5  392.71  5020.5  393.13
  5129.3  393.54  5187.5   396.2  5282.6  408.56  5340.8  412.67  5419.2   416.2
#Mann= 3 ,-1 , 0
  4537.1     .05       0  4997.5     .03       0  5003.5     .05       0
Bank Sta=4997.5,5003.5
XS Rating Curve= 0 ,0
Exp/Cntr=0.3,0.1

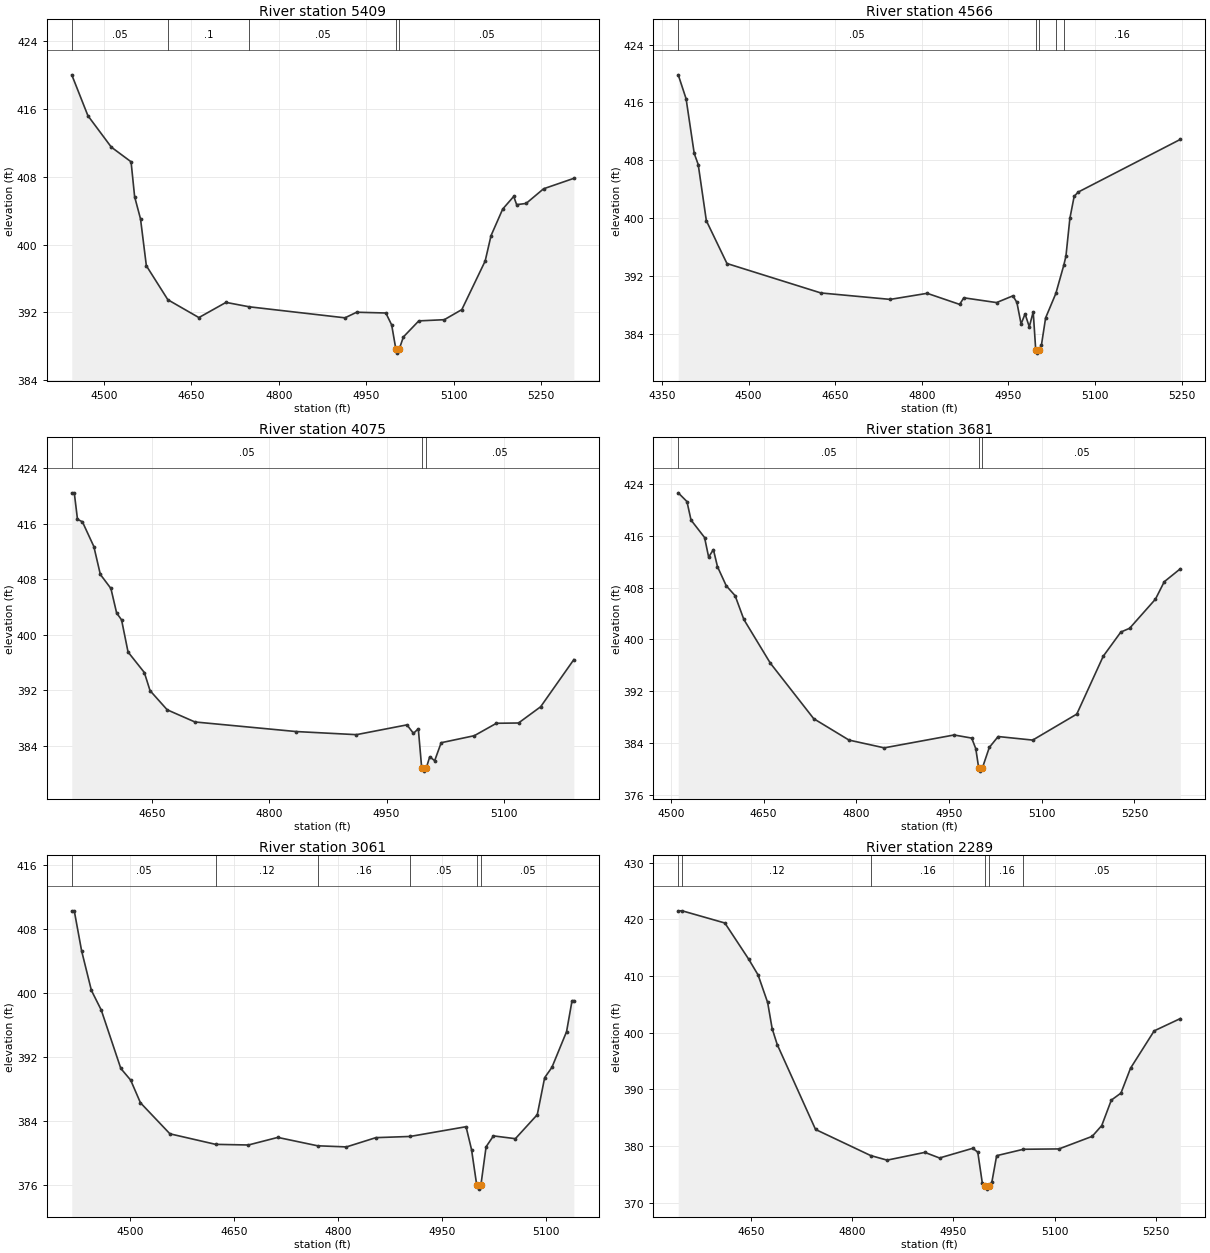
Type RM Length L Ch R = 1 ,5409    ,843,843,843
BEGIN DESCRIPTION:
UNT 011 IN CACR 9.0
END DESCRIPTION:
XS GIS Cut Line= 2
       3700490.7     10775072.54      3700438.61     10775931.97
#Sta/Elev= 30
  4444.8     420  4472.5  415.18  4512.6  411.48  4546.5  409.75  4552.6  405.63
  4562.7  403.02  4572.7   397.5  4609.6  393.49  4662.8  391.39  4709.3  393.18
  4749.1  392.66  4913.3  391.36  4933.3  392.02  4983.4  391.93  4993.4  390.52
  5000.5   387.7  5003.2   387.2  5006.5   387.7  5013.5  389.11  5039.9     391
  5083.6  391.14  5113.7  392.33  5153.7  398.05  5163.8  401.05  5183.8  404.18
  5202.7  405.67  5207.7   404.7  5223.9  404.84  5253.9  406.57  5305.8   407.8
#Mann= 5 ,-1 , 0
  4444.8     .05       0  4609.6      .1       0  4749.1     .05       0
  5000.5     .03       0  5006.5     .05       0
Bank Sta=5000.5,5006.5
XS Rating Curve= 0 ,0
Exp/Cntr=0.3,0.1

Type RM Length L Ch R = 1 ,4566    ,491,491,491
BEGIN DESCRIPTION:
UNT 011 IN CACR 8.0
END DESCRIPTION:
XS GIS Cut Line= 2
       3700344.9     10774916.28      3699709.44     10775510.07
#Sta/Elev= 30
    4378  419.81  4391.6   416.5  4405.7  408.94  4412.6  407.41  4426.7  399.64
  4462.4  393.72  4625.1  389.65  4745.2  388.76  4809.2   389.6  4865.4  388.07
  4872.7  388.98  4929.4  388.32  4957.7  389.25  4964.6  388.35  4971.9  385.36
  4978.8  386.76  4986.1  384.96  4992.9  387.04  4997.2  381.83    5000  381.33
  5003.2  381.83  5007.1  382.43  5014.4  386.21  5032.1  389.58  5045.9   393.5
  5049.6  394.75  5056.4  399.96  5063.8     403  5070.6  403.59  5247.7  410.88
#Mann= 5 ,-1 , 0
    4378     .05       0  4997.2     .03       0  5003.2     .05       0
  5032.1     .12       0  5045.9     .16       0
Bank Sta=4997.2,5003.2
XS Rating Curve= 0 ,0
Exp/Cntr=0.3,0.1

Type RM Length L Ch R = 1 ,4075    ,394,394,394
BEGIN DESCRIPTION:
UNT 011 IN CACR 7.0
END DESCRIPTION:
XS GIS Cut Line= 3
      3700049.62     10774660.17      3699749.61     10775060.19
      3699649.64     10775160.16
#Sta/Elev= 30
  4547.8  420.45    4551  420.45  4555.1  416.64  4561.4  416.28    4576  412.72
  4584.3   408.7  4597.8  406.68  4605.1  403.15  4611.4  402.16  4619.7  397.53
  4640.5  394.58  4647.8  391.97  4669.7  389.21  4705.1  387.46  4834.3  386.08
  4911.4  385.63    4976  387.04  4984.3  385.82  4990.5  386.48  4994.8  380.88
  4997.6  380.38  5000.8  380.88  5005.1  382.45  5011.4  381.88  5019.7  384.47
    5062  385.48  5090.3  387.27  5118.5  387.31  5146.8  389.65  5189.2  396.44
#Mann= 3 ,-1 , 0
  4547.8     .05       0  4994.8     .03       0  5000.8     .05       0
Bank Sta=4994.8,5000.8
XS Rating Curve= 0 ,0
Exp/Cntr=0.3,0.1

Type RM Length L Ch R = 1 ,3681    ,620,620,620
BEGIN DESCRIPTION:
UNT 011 IN CACR 6.0
END DESCRIPTION:
XS GIS Cut Line= 2
      3699865.72      10774426.7      3699334.52     10775041.23
#Sta/Elev= 30
    4512  422.68  4526.1  421.33  4532.7  418.47  4554.6  415.77  4561.2  412.74
  4568.9   413.9  4575.5  411.26  4589.7   408.3    4604  406.78  4618.2  403.09
    4661  396.34  4731.2  387.75  4788.3  384.44  4845.3  383.24  4958.3  385.23
  4986.8  384.75  4993.4  383.11  4998.1  380.14  5000.8  379.64  5004.1  380.14
  5015.3  383.31  5029.6  384.99  5085.5  384.44  5156.8  388.46  5199.6  397.41
  5228.1  401.15  5242.3  401.73  5284.1  406.24  5298.3  408.93  5324.3  410.93
#Mann= 3 ,-1 , 0
    4512     .05       0  4998.1     .03       0  5004.1     .05       0
Bank Sta=4998.1,5004.1
XS Rating Curve= 0 ,0
Exp/Cntr=0.3,0.1

Type RM Length L Ch R = 1 ,3061    ,772,772,772
BEGIN DESCRIPTION:
UNT 011 IN CACR 5.0
END DESCRIPTION:
XS GIS Cut Line= 3
      3699549.63     10774110.17      3699149.61     10774510.19
      3698999.64     10774560.18
#Sta/Elev= 30
  4416.1  410.31  4419.7  410.31  4430.3  405.29  4444.4  400.34  4458.6  397.88
  4486.8  390.56    4501   389.1  4515.1  386.26  4557.6  382.37  4623.5  381.05
  4670.7  380.97  4713.1  381.92  4770.5  380.87  4812.1  380.73  4854.5  381.89
  4903.9  382.04  4984.5  383.26  4992.4   380.4  4999.9  375.94  5002.6  375.44
  5005.9  375.94  5013.4  380.75    5024  382.11  5055.6  381.76  5087.2  384.77
  5097.8   389.4  5108.3   390.7  5129.4  395.17  5137.3  399.05  5139.9  399.05
#Mann= 6 ,-1 , 0
  4416.1     .05       0  4623.5     .12       0  4770.5     .16       0
  4903.9     .05       0  4999.9     .03       0  5005.9     .05       0
Bank Sta=4999.9,5005.9
XS Rating Curve= 0 ,0
Exp/Cntr=0.3,0.1

Type RM Length L Ch R = 1 ,2289    ,801,801,801
BEGIN DESCRIPTION:
UNT 011 IN CACR 4.0
END DESCRIPTION:
XS GIS Cut Line= 2
      3699133.02     10773666.34      3698575.77      10774161.1
#Sta/Elev= 30
  4541.5  421.52  4547.4  421.52  4610.7  419.37  4645.8  413.03    4660   410.2
  4674.2  405.33  4680.9  400.72  4688.4  397.91  4745.3  382.91  4827.1   378.3
  4851.5  377.49  4907.5  378.86  4929.3  377.87  4978.6  379.58  4986.1   378.9
  4992.8  373.45  4997.4  372.87  5000.1  372.37  5003.4  372.87  5007.1  373.67
  5014.1  378.28  5053.9  379.41  5106.6  379.47  5155.9  381.69  5170.1   383.6
  5184.3  388.09  5198.6  389.33  5212.8  393.72  5247.9  400.32  5286.7  402.49
#Mann= 6 ,-1 , 0
  4541.5     .16       0  4547.4     .12       0  4827.1     .16       0
  4997.4     .07       0  5003.4     .16       0  5053.9     .05       0
Bank Sta=4997.4,5003.4
XS Rating Curve= 0 ,0
Exp/Cntr=0.3,0.1

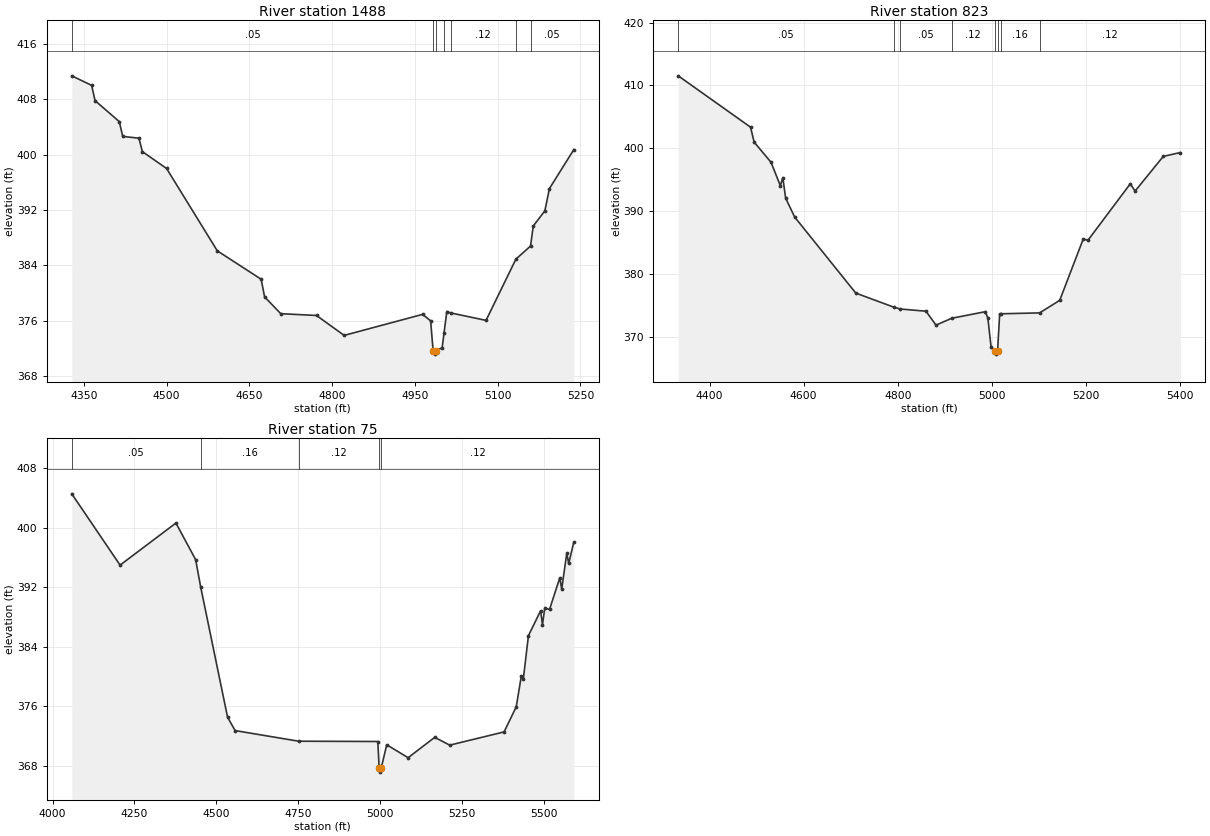
Type RM Length L Ch R = 1 ,1488    ,665,665,665
BEGIN DESCRIPTION:
UNT 011 IN CACR 3.0
END DESCRIPTION:
XS GIS Cut Line= 2
      3698638.55      10773079.8      3698100.34     10773813.33
#Sta/Elev= 30
  4328.3  411.42  4364.3  410.04  4370.5  407.83  4414.4   404.8  4420.6  402.66
    4450   402.4  4456.2  400.46  4500.1  398.02    4592  386.11  4671.5     382
  4677.7  379.45    4707  377.02  4771.8  376.76  4821.9  373.88    4964  376.92
  4978.6  375.98  4983.1  371.67  4985.9  371.17  4989.1  371.67  4999.5  372.11
    5003  374.29  5007.9  377.33  5014.9  377.13    5079  376.05  5133.1  384.91
  5159.6   386.8  5164.6   389.7  5185.5  391.89  5193.9  395.12  5238.1  400.76
#Mann= 7 ,-1 , 0
  4328.3     .05       0  4983.1     .03       0  4989.1     .05       0
    5003     .16       0  5014.9     .12       0  5133.1     .16       0
  5159.6     .05       0
Bank Sta=4983.1,4989.1
XS Rating Curve= 0 ,0
Exp/Cntr=0.3,0.1

Type RM Length L Ch R = 1 ,823     ,748,748,748
BEGIN DESCRIPTION:
UNT 011 IN CACR 2.0
END DESCRIPTION:
XS GIS Cut Line= 3
      3698603.84     10772988.65      3697931.09     10773236.05
      3697926.76     10773586.43
#Sta/Elev= 30
  4333.4  411.53  4487.1  403.37  4494.8  400.99  4530.6   397.8  4550.4  394.08
  4555.7  395.35  4561.7   392.1  4580.9  389.09  4710.8  377.01  4792.4  374.75
  4805.6  374.48    4860  374.13  4881.3  371.92  4914.8  373.01  4986.1  374.05
  4991.5  373.05  4998.5  368.37  5006.2  367.81  5008.9  367.31  5012.2  367.81
  5016.6  373.66  5019.2  373.72  5101.5  373.86  5144.3  375.86  5194.3  385.61
  5204.3   385.4  5294.4  394.39  5304.4  393.21  5364.4  398.73  5400.6  399.34
#Mann= 8 ,-1 , 0
  4333.4     .05       0  4792.4     .16       0  4805.6     .05       0
  4914.8     .12       0  5006.2     .07       0  5012.2     .12       0
  5019.2     .16       0  5101.5     .12       0
Bank Sta=5006.2,5012.2
XS Rating Curve= 0 ,0
Exp/Cntr=0.3,0.1

Type RM Length L Ch R = 1 ,75      ,0,0,0
BEGIN DESCRIPTION:
UNT 011 IN CACR 1.0
END DESCRIPTION:
XS GIS Cut Line= 4
      3698466.64     10772746.47      3697612.51     10772815.91
      3697598.62     10772947.85       3697873.7      10773416.7
#Sta/Elev= 30
  4058.5  404.59    4206     395  4376.6  400.66  4436.8  395.73  4452.4     392
  4534.2  374.55  4557.2  372.74  4751.3  371.31  4993.1  371.27  4997.2  367.65
  4999.9  367.15  5003.2  367.65  5020.3  370.83  5085.6  369.09  5166.8  371.83
  5212.7  370.78  5378.7  372.56  5415.8  375.94  5431.5  380.13  5437.3  379.62
    5453   385.5  5490.1  388.85  5495.9  386.99    5503  389.24  5517.4  389.03
  5548.8  393.29  5554.6  391.77  5570.2  396.62    5576  395.23  5591.7  398.11
#Mann= 5 ,-1 , 0
  4058.5     .05       0  4452.4     .16       0  4751.3     .12       0
  4997.2     .07       0  5003.2     .12       0
Bank Sta=4997.2,5003.2
XS Rating Curve= 0 ,0
Exp/Cntr=0.3,0.1

Chan Stop Cuts=-1
Use User Specified Reach Order=0
Composite Channel Slope=5