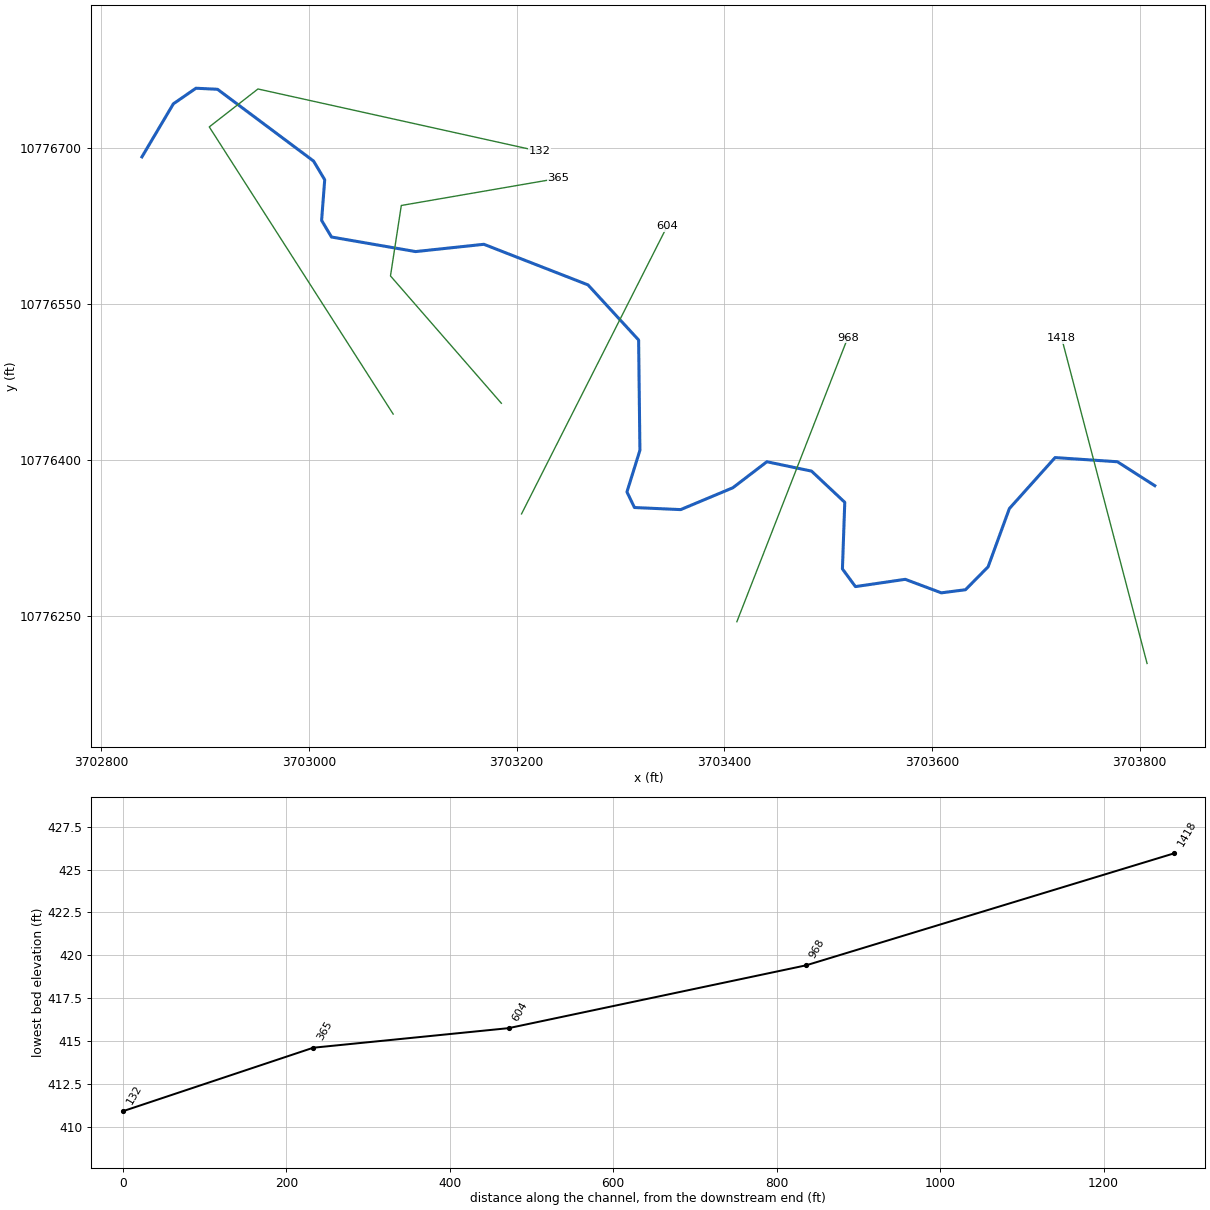
--- UNT 012 IN CACR.prj (project) ---

Proj Title=UNT 012 IN CACR Base Level Engineering
Current Plan=p01
Default Exp/Contr=0.3,0.1
English Units
Geom File=g01
Flow File=f01
Plan File=p01
Y Axis Title=Elevation
X Axis Title(PF)=Main Channel Distance
X Axis Title(XS)=Station
BEGIN DESCRIPTION:
UNT 012 IN CACR
END DESCRIPTION:
DSS Export Rating Curves= 0
DSS Export Rating Curve Sorted= 0
DSS Export Volume Flow Curves= 0
DXF OffsetX= 0
DXF OffsetY= 0
DXF ScaleX= 1
DXF ScaleY= 10

--- UNT 012 IN CACR.p01 (plan) ---

Plan Title=Multiple Run
Short Identifier=Multiple
Geom File=g01
Flow File=f01
Subcritical Flow
K Sum by GR= 0
Std Step Tol= 0.01
Critical Tol= 0.01
Num of Std Step Trials= 20
Max Error Tol= 0.3
Flow Tol Ratio= 0.001
Split Flow NTrial= 30
Split Flow Tol= 0.02
Split Flow Ratio= 0.02
Log Output Level= 0
Friction Slope Method= 1
Unsteady Friction Slope Method= 2
Unsteady Bridges Friction Slope Method= 1
Parabolic Critical Depth
Global Vel Dist=  1 , 1 , 1
Global Log Level= 0
CheckData=True
Encroach Param= -1, 0, 0, 0
BEGIN DESCRIPTION:
Multiple Run
END DESCRIPTION:

--- UNT 012 IN CACR.f01 (steady flow) ---

Flow Title=Multiple
Program Version=4.10
Number of Profiles= 7
Profile Names=10-year,25-year,50-year,1pct_min,100-year,1pct_plu,500-year
River Rch & RM=UNT 012 IN CACR,Reach-1         ,1418
     128     157     178     149     202     273     258
River Rch & RM=UNT 012 IN CACR,Reach-1         ,132
     128     157     178     149     202     273     258
Boundary for River Rch & Prof#=UNT 012 IN CACR,Reach-1         , 1
Up Type= 0
Dn Type= 3
Dn Slope=0.005
Boundary for River Rch & Prof#=UNT 012 IN CACR,Reach-1         , 2
Up Type= 0
Dn Type= 3
Dn Slope=0.005
Boundary for River Rch & Prof#=UNT 012 IN CACR,Reach-1         , 3
Up Type= 0
Dn Type= 3
Dn Slope=0.005
Boundary for River Rch & Prof#=UNT 012 IN CACR,Reach-1         , 4
Up Type= 0
Dn Type= 3
Dn Slope=0.005
Boundary for River Rch & Prof#=UNT 012 IN CACR,Reach-1         , 5
Up Type= 0
Dn Type= 3
Dn Slope=0.005
Boundary for River Rch & Prof#=UNT 012 IN CACR,Reach-1         , 6
Up Type= 0
Dn Type= 3
Dn Slope=0.005
Boundary for River Rch & Prof#=UNT 012 IN CACR,Reach-1         , 7
Up Type= 0
Dn Type= 3
Dn Slope=0.005
DSS Import GetInterval= 0
DSS Import GetPeak= 0
DSS Import FillOption= 0

--- UNT 012 IN CACR.g01 (geometry) ---

Geom Title=Existing Conditions
Program Version=4.10

River Reach=UNT 012 IN CACR ,Reach-1
Reach XY= 30
       3703814.5       10776375.       3703778.5       10776398.
       3703718.5       10776402.       3703674.5       10776353.
        3703654.       10776297.      3703632.25       10776275.
        3703609.       10776272.      3703574.25       10776285.
      3703526.25       10776278.      3703513.75       10776295.
        3703516.       10776359.        3703484.       10776389.
        3703441.       10776398.      3703408.25       10776373.
        3703358.       10776352.       3703313.5       10776354.
      3703306.25       10776369.      3703318.75       10776409.
       3703317.5       10776515.      3703268.75       10776568.
       3703168.5       10776607.      3703102.75       10776600.
      3703021.75       10776614.      3703012.25       10776630.
      3703015.25       10776669.       3703004.5       10776687.
        3702912.       10776756.      3702891.25       10776757.
       3702869.5       10776742.      3702839.25       10776691.

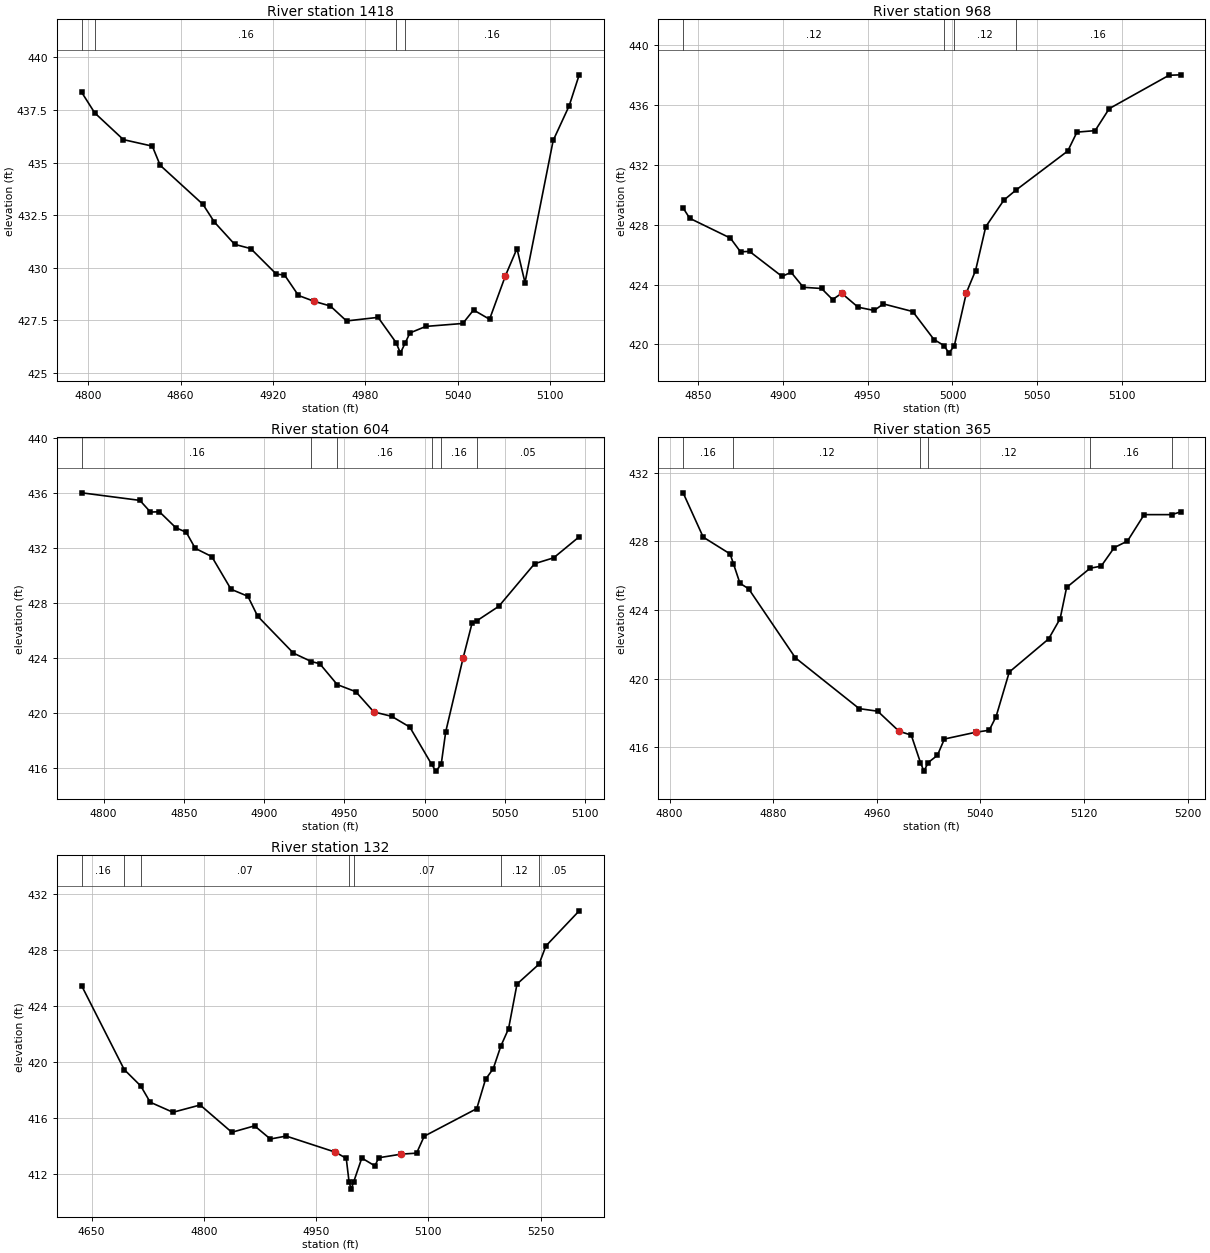
Type RM Length L Ch R = 1 ,1418    ,450,450,450
BEGIN DESCRIPTION:
UNT 012 IN CACR 2.0
END DESCRIPTION:
XS GIS Cut Line= 2
      3703807.08     10776204.11      3703724.93     10776516.49
#Sta/Elev= 30
  4795.8  438.33  4804.2  437.36  4822.8  436.09  4841.6  435.78  4846.7  434.87
  4874.5  433.01  4881.9  432.17  4895.1  431.11  4905.5  430.91  4922.2  429.69
  4927.4  429.66  4936.5  428.68  4946.8   428.4  4957.2  428.18  4967.7  427.47
  4988.2  427.64  4999.9  426.44  5002.7  425.94  5005.9  426.44  5008.9   426.9
  5019.2  427.21  5043.2  427.35  5050.2  427.99  5060.6  427.55  5070.9  429.62
  5078.4  430.91  5083.6  429.29  5101.9  436.05  5112.3   437.7  5118.8  439.17
#Mann= 4 ,-1 , 0
  4795.8     .05       0  4804.2     .16       0  4999.9     .07       0
  5005.9     .16       0
Bank Sta=4946.8,5070.9
XS Rating Curve= 0 ,0
Exp/Cntr=0.3,0.1

Type RM Length L Ch R = 1 ,968     ,364,364,364
BEGIN DESCRIPTION:
Mapping XS 4282e6bd
END DESCRIPTION:
XS GIS Cut Line= 2
      3703412.11     10776244.26      3703518.84     10776517.02
#Sta/Elev= 30
  4841.4  429.12  4845.3  428.43  4869.2  427.11  4875.2  426.19  4880.5  426.22
  4899.6  424.55    4905  424.82  4912.2  423.82  4922.9  423.74  4929.4     423
  4934.8  423.42  4944.4  422.49  4953.9  422.27  4959.3  422.71  4976.6   422.2
  4989.1  420.33  4995.1  419.92  4997.9  419.42  5001.1  419.92  5008.2  423.46
  5013.6  424.94  5019.6  427.87  5030.3  429.65  5037.2   430.3  5067.9  432.93
  5073.3  434.19    5084  434.29  5092.3  435.76  5127.5  437.99  5134.3  438.02
#Mann= 4 ,-1 , 0
  4841.4     .12       0  4995.1     .07       0  5001.1     .12       0
  5037.2     .16       0
Bank Sta=4934.8,5008.2
XS Rating Curve= 0 ,0
Exp/Cntr=0.3,0.1

Type RM Length L Ch R = 1 ,604     ,239,239,239
BEGIN DESCRIPTION:
Mapping XS bc197315
END DESCRIPTION:
XS GIS Cut Line= 2
      3703204.78      10776347.9        3703345.     10776624.38
#Sta/Elev= 30
  4786.4  436.02  4822.6  435.47  4829.2  434.62  4834.8  434.64    4845  433.48
  4851.5  433.15  4857.1  431.98  4867.4  431.38  4879.4     429  4889.9  428.49
    4896  427.04  4918.3  424.35  4929.4  423.74  4934.7  423.58  4945.6  422.06
  4957.2  421.54  4968.4  420.07  4979.5  419.75  4990.8  418.97  5004.4  416.26
  5007.1  415.76  5010.4  416.26  5013.2  418.62    5024  423.97  5029.6  426.52
  5032.8  426.72  5046.3  427.76  5068.6  430.86  5080.5  431.29  5096.4  432.82
#Mann= 6 ,-1 , 0
  4786.4     .16       0  4929.4     .12       0  4945.6     .16       0
  5004.4     .07       0  5010.4     .16       0  5032.8     .05       0
Bank Sta=4968.4,5024
XS Rating Curve= 0 ,0
Exp/Cntr=0.3,0.1

Type RM Length L Ch R = 1 ,365     ,233,233,233
BEGIN DESCRIPTION:
Mapping XS 5d0de585
END DESCRIPTION:
XS GIS Cut Line= 4
      3703185.34     10776454.21      3703078.57      10776576.6
      3703088.99     10776644.31      3703240.03     10776670.35
#Sta/Elev= 30
  4810.4  430.83  4825.9  428.25  4846.7  427.27  4849.3  426.69  4854.3  425.56
    4861  425.24  4897.1  421.22  4946.4  418.26  4960.7  418.11  4977.2  416.94
  4986.6  416.72  4993.7  415.12  4996.4  414.62  4999.7  415.12  5006.8  415.54
  5012.2  416.49  5036.7  416.89  5046.8     417  5052.1  417.79  5062.3  420.39
  5092.7  422.32  5101.6   423.5  5106.6  425.32  5124.8  426.44  5133.3  426.56
  5143.4  427.64  5153.6  428.02  5166.5  429.56  5187.9  429.56  5194.6  429.72
#Mann= 6 ,-1 , 0
  4810.4     .16       0  4849.3     .12       0  4993.7     .07       0
  4999.7     .12       0  5124.8     .16       0  5187.9     .05       0
Bank Sta=4977.2,5036.7
XS Rating Curve= 0 ,0
Exp/Cntr=0.3,0.1

Type RM Length L Ch R = 1 ,132     ,0,0,0
BEGIN DESCRIPTION:
UNT 012 IN CACR 1.0
END DESCRIPTION:
XS GIS Cut Line= 4
      3703081.16     10776443.82      3702904.09     10776719.83
      3702950.97     10776756.29      3703221.82     10776696.39
#Sta/Elev= 30
    4637  425.43  4693.7  419.46  4715.8  418.29  4728.4  417.13  4758.8  416.41
  4795.2  416.93  4837.5  414.98  4867.9  415.44    4889   414.5  4910.1  414.71
  4975.9  413.56  4990.4  413.12  4994.2  411.42    4997  410.92  5000.2  411.42
  5011.2  413.14  5028.7  412.58  5033.8  413.16  5063.9  413.42  5084.4  413.49
  5094.6   414.7  5164.8  416.67  5176.5  418.76  5186.8  419.52    5197  421.14
  5207.3  422.38  5218.6  425.57    5248  426.99  5257.2  428.29  5301.7   430.8
#Mann= 7 ,-1 , 0
    4637     .16       0  4693.7     .12       0  4715.8     .07       0
  4994.2     .05       0  5000.2     .07       0    5197     .12       0
    5248     .05       0
Bank Sta=4975.9,5063.9
XS Rating Curve= 0 ,0
Exp/Cntr=0.3,0.1

Chan Stop Cuts=-1
Use User Specified Reach Order=0
Composite Channel Slope=5