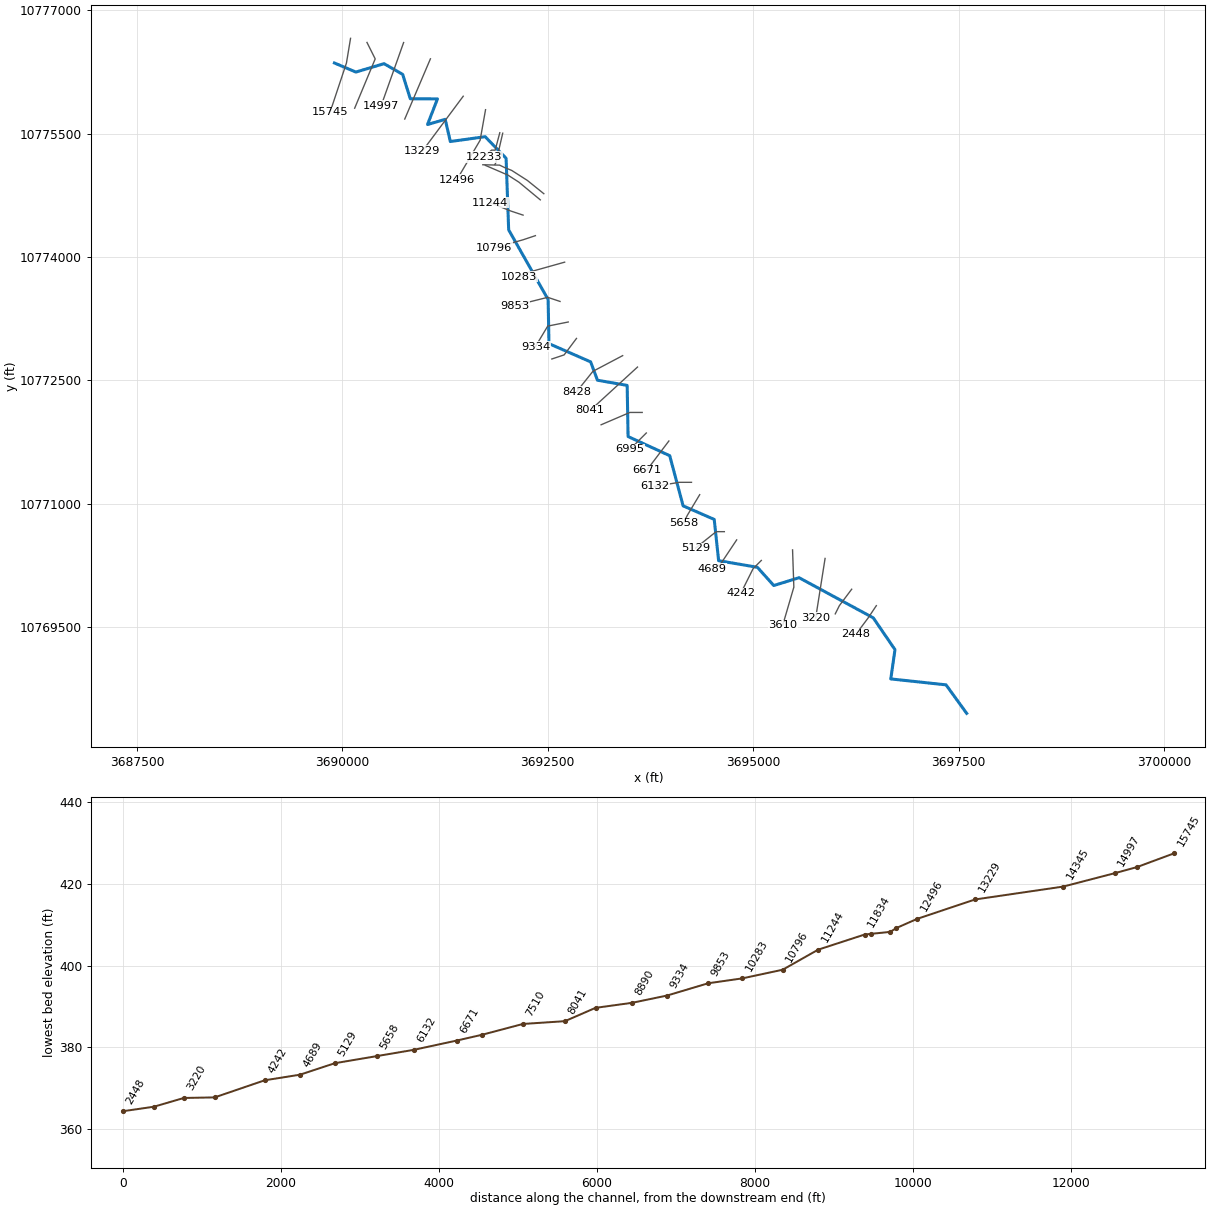
--- UNT 014 IN CACR.prj (project) ---

Proj Title=UNT 014 IN CACR Base Level Engineering
Current Plan=p01
Default Exp/Contr=0.3,0.1
English Units
Geom File=g01
Flow File=f01
Plan File=p01
BEGIN DESCRIPTION:
UNT 014 IN CACR
END DESCRIPTION:

--- UNT 014 IN CACR.p01 (plan) ---

Plan Title=Multiple Run
Short Identifier=Multiple
Geom File=g01
Flow File=f01
Subcritical Flow
K Sum by GR= 0
Std Step Tol= 0.01
Critical Tol= 0.01
Num of Std Step Trials= 20
Max Error Tol= 0.3
Flow Tol Ratio= 0.001
Split Flow NTrial= 30
Split Flow Tol= 0.02
Split Flow Ratio= 0.02
Log Output Level= 0
Friction Slope Method= 1
Unsteady Friction Slope Method= 2
Unsteady Bridges Friction Slope Method= 1
Parabolic Critical Depth
Global Vel Dist=  1 , 1 , 1
Global Log Level= 0
CheckData=True
Encroach Param= -1, 0, 0, 0
BEGIN DESCRIPTION:
Multiple Run
END DESCRIPTION:

--- UNT 014 IN CACR.f01 (steady flow) ---

Flow Title=Multiple
Number of Profiles=7
Profile Names=10-year,25-year,50-year,1pct_min,100-year,1pct_plu,500-year
River Rch & RM= UNT 014 IN CACR,Reach-1,15745
     627     850    1033     921    1246    1685    1814
River Rch & RM= UNT 014 IN CACR,Reach-1,14997
     757    1036    1267    1135    1535    2076    2260
River Rch & RM= UNT 014 IN CACR,Reach-1,11834
     891    1225    1503    1350    1826    2469    2702
River Rch & RM= UNT 014 IN CACR,Reach-1,3220
    1039    1440    1776    1603    2168    2931    3238
Boundary for River Rch & Prof#=UNT 014 IN CACR,Reach-1,1
Up Type=0
Dn Type=3
Dn Slope=0.005
Boundary for River Rch & Prof#=UNT 014 IN CACR,Reach-1,2
Up Type=0
Dn Type=3
Dn Slope=0.005
Boundary for River Rch & Prof#=UNT 014 IN CACR,Reach-1,3
Up Type=0
Dn Type=3
Dn Slope=0.005
Boundary for River Rch & Prof#=UNT 014 IN CACR,Reach-1,4
Up Type=0
Dn Type=3
Dn Slope=0.005
Boundary for River Rch & Prof#=UNT 014 IN CACR,Reach-1,5
Up Type=0
Dn Type=3
Dn Slope=0.005
Boundary for River Rch & Prof#=UNT 014 IN CACR,Reach-1,6
Up Type=0
Dn Type=3
Dn Slope=0.005
Boundary for River Rch & Prof#=UNT 014 IN CACR,Reach-1,7
Up Type=0
Dn Type=3
Dn Slope=0.005

--- UNT 014 IN CACR.g01 (geometry) ---

Geom Title=Existing Conditions

River Reach=UNT 014 IN CACR,Reach-1
Reach XY= 30
      3689903.66     10776360.19      3690164.00     10776250.00
      3690507.25     10776352.00      3690734.00     10776222.00
      3690826.75     10775925.00      3691157.50     10775924.00
      3691036.75     10775612.00      3691252.00     10775675.00
      3691314.00     10775405.00      3691738.00     10775464.00
      3691993.00     10775201.00      3692024.25     10774331.00
      3692504.50     10773483.00      3692514.75     10772947.00
      3693022.00     10772725.00      3693105.00     10772502.00
      3693466.75     10772439.00      3693477.75     10771817.00
      3693984.75     10771584.00      3694147.75     10770974.00
      3694526.25     10770809.00      3694580.00     10770307.00
      3695051.50     10770227.00      3695251.25     10770005.00
      3695559.50     10770100.00      3696462.00     10769612.00
      3696726.75     10769225.00      3696675.50     10768869.00
      3697348.00     10768797.00      3697599.50     10768450.00

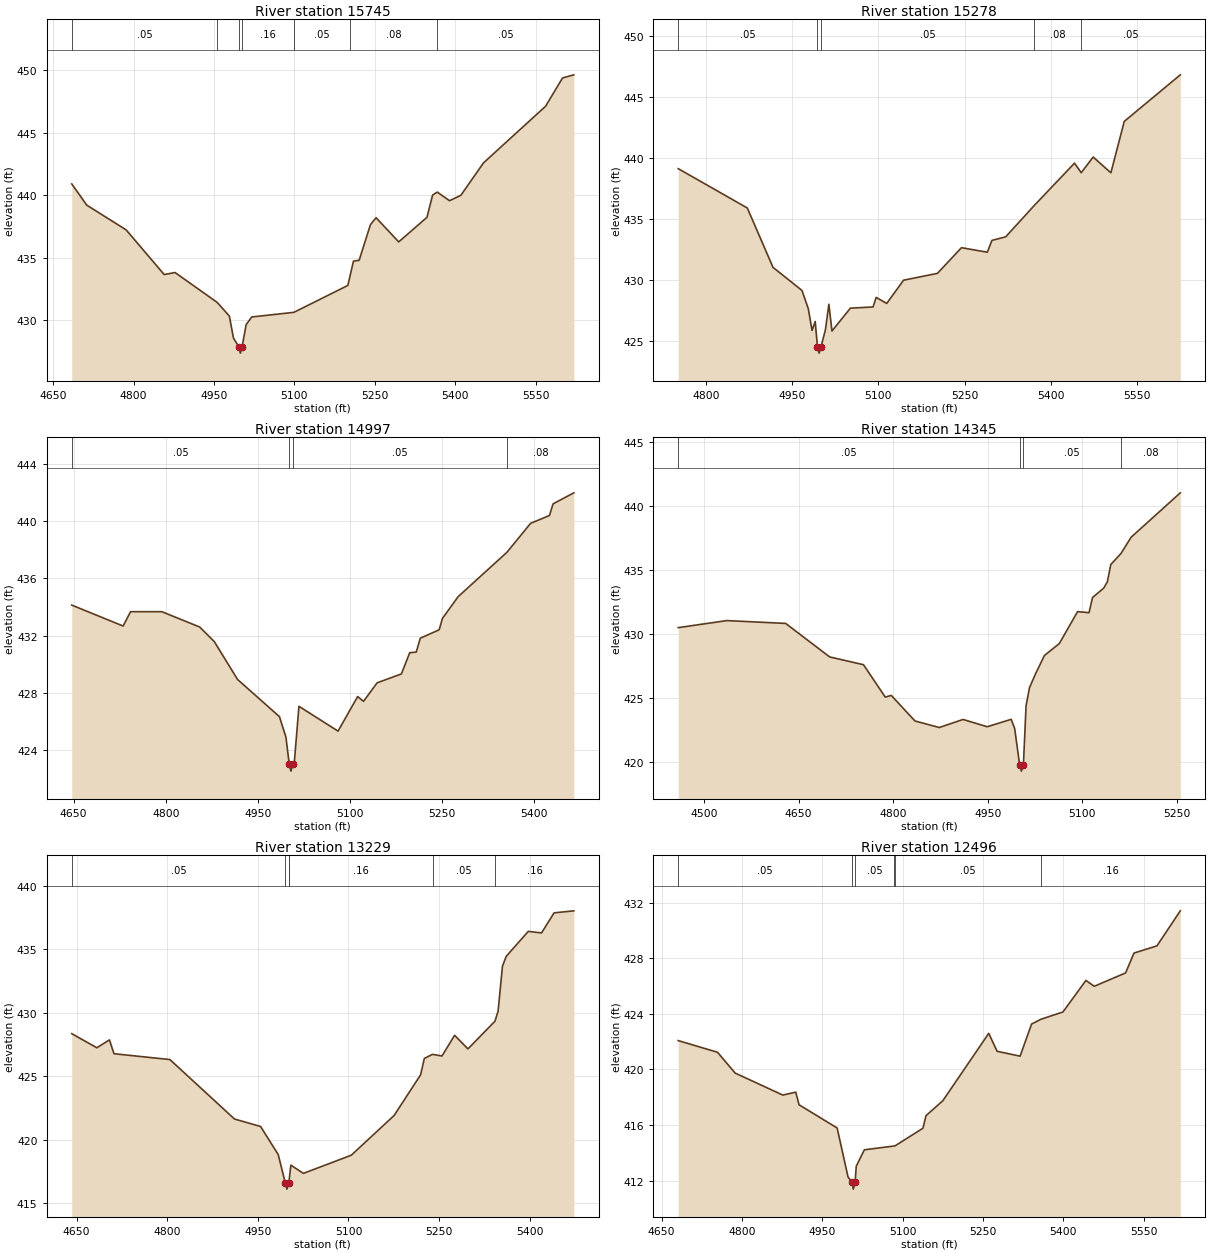
Type RM Length L Ch R = 1,15745,467,467,467
BEGIN DESCRIPTION:
UNT 014 IN CACR 32.0
END DESCRIPTION:
XS GIS Cut Line= 3
      3690099.61     10776660.22      3690049.61     10776360.19
      3689849.62     10775760.21
#Sta/Elev= 30
  4684.7  440.90  4712.6  439.21  4786.1  437.23  4857.1  433.66  4877.4  433.82
  4956.1  431.43  4978.7  430.34  4986.3  428.59  4996.4  427.88  4999.2  427.38
  5002.4  427.88  5010.0  429.66  5020.5  430.27  5099.1  430.64  5199.7  432.79
  5203.7  433.53  5210.2  434.73  5220.8  434.80  5241.9  437.65  5252.4  438.20
  5294.6  436.27  5347.3  438.23  5357.8  440.01  5366.5  440.25  5389.4  439.56
  5410.5  439.99  5452.7  442.58  5568.6  447.11  5600.2  449.37  5621.3  449.62
#Mann=7,-1,0
  4684.7    0.05       0  4956.1    0.16       0  4996.4    0.07       0
  5002.4    0.16       0  5099.1    0.05       0  5203.7    0.08       0
  5366.5    0.05       0
Bank Sta=4996.4,5002.4
Exp/Cntr=0.3,0.1

Type RM Length L Ch R = 1,15278,281,281,281
BEGIN DESCRIPTION:
UNT 014 IN CACR 31.0
END DESCRIPTION:
XS GIS Cut Line= 3
      3690299.59     10776610.22      3690399.61     10776410.19
      3690149.62     10775810.22
#Sta/Elev= 30
  4751.8  439.14  4872.0  435.92  4916.7  431.06  4967.1  429.17  4978.1  427.68
  4984.6  425.90  4990.1  426.63  4994.1  424.54  4996.9  424.04  5000.1  424.54
  5007.9  425.95  5013.9  428.04  5019.3  425.85  5051.3  427.72  5090.8  427.82
  5096.2  428.60  5114.6  428.11  5143.9  430.01  5202.9  430.57  5244.6  432.67
  5289.6  432.30  5297.7  433.27  5321.6  433.56  5371.6  436.14  5441.3  439.59
  5453.0  438.81  5473.8  440.09  5504.6  438.80  5527.9  443.01  5625.4  446.82
#Mann=5,-1,0
  4751.8    0.05       0  4994.1    0.03       0  5000.1    0.05       0
  5371.6    0.08       0  5453.0    0.05       0
Bank Sta=4994.1,5000.1
Exp/Cntr=0.3,0.1

Type RM Length L Ch R = 1,14997,652,652,652
BEGIN DESCRIPTION:
UNT 014 IN CACR 30.0
END DESCRIPTION:
XS GIS Cut Line= 2
      3690745.43     10776609.00      3690471.15     10775838.25
#Sta/Elev= 30
  4646.9  434.13  4730.6  432.67  4742.7  433.67  4793.7  433.67  4855.4  432.60
  4879.2  431.58  4917.1  428.94  4985.3  426.35  4995.9  424.92  5001.2  423.05
  5004.0  422.55  5007.2  423.05  5009.6  423.21  5017.1  427.07  5080.8  425.34
  5112.7  427.75  5122.3  427.42  5144.5  428.71  5184.0  429.33  5197.6  430.81
  5208.2  430.85  5214.8  431.82  5245.6  432.41  5250.9  433.20  5276.5  434.72
  5355.9  437.81  5394.5  439.83  5425.3  440.38  5431.1  441.19  5465.0  441.96
#Mann=4,-1,0
  4646.9    0.05       0  5001.2    0.03       0  5007.2    0.05       0
  5355.9    0.08       0
Bank Sta=5001.2,5007.2
Exp/Cntr=0.3,0.1

Type RM Length L Ch R = 1,14345,1116,1116,1116
BEGIN DESCRIPTION:
UNT 014 IN CACR 29.0
END DESCRIPTION:
XS GIS Cut Line= 2
      3691071.82     10776411.09      3690759.32     10775678.46
#Sta/Elev= 30
  4459.0  430.50  4536.1  431.05  4629.4  430.83  4699.2  428.21  4752.9  427.60
  4787.4  425.07  4797.0  425.20  4834.6  423.20  4873.1  422.69  4910.9  423.32
  4949.2  422.75  4987.2  423.33  4992.7  422.62  5000.6  419.78  5003.3  419.28
  5006.6  419.78  5010.8  424.39  5016.3  425.81  5025.3  426.83  5039.9  428.32
  5063.5  429.25  5092.5  431.75  5110.7  431.67  5116.2  432.85  5134.0  433.59
  5139.8  434.09  5145.2  435.43  5161.6  436.31  5177.5  437.57  5255.5  441.04
#Mann=4,-1,0
  4459.0    0.05       0  5000.6    0.03       0  5006.6    0.05       0
  5161.6    0.08       0
Bank Sta=5000.6,5006.6
Exp/Cntr=0.3,0.1

Type RM Length L Ch R = 1,13229,733,733,733
BEGIN DESCRIPTION:
UNT 014 IN CACR 28.0
END DESCRIPTION:
XS GIS Cut Line= 2
      3691471.12     10775956.23      3690974.62     10775289.61
#Sta/Elev= 30
  4641.9  428.37  4683.4  427.26  4704.3  427.88  4711.8  426.79  4804.4  426.33
  4911.3  421.65  4954.5  421.06  4983.7  418.85  4995.3  416.63  4998.1  416.13
  5001.3  416.63  5001.8  416.84  5004.6  418.02  5025.4  417.37  5104.7  418.80
  5175.6  421.93  5219.4  425.13  5225.6  426.42  5239.1  426.74  5254.8  426.61
  5275.7  428.24  5297.8  427.17  5342.5  429.35  5347.7  430.14  5354.9  433.68
  5361.2  434.46  5397.6  436.42  5419.6  436.30  5440.4  437.88  5473.1  438.04
#Mann=6,-1,0
  4641.9    0.05       0  4995.3    0.03       0  5001.3    0.05       0
  5001.8    0.16       0  5239.1    0.05       0  5342.5    0.16       0
Bank Sta=4995.3,5001.3
Exp/Cntr=0.3,0.1

Type RM Length L Ch R = 1,12496,263,263,263
BEGIN DESCRIPTION:
UNT 014 IN CACR 27.0
END DESCRIPTION:
XS GIS Cut Line= 3
      3691742.78     10775792.44      3691676.81     10775420.96
      3691392.07     10774938.29
#Sta/Elev= 30
  4681.0  422.08  4754.4  421.24  4787.4  419.74  4876.3  418.16  4900.5  418.37
  4906.7  417.46  4977.8  415.79  4998.1  412.27  5005.3  411.89  5008.0  411.39
  5011.3  411.89  5013.5  413.04  5028.6  414.22  5083.4  414.49  5086.1  414.51
  5138.0  415.77  5143.8  416.68  5175.1  417.75  5260.9  422.60  5276.6  421.31
  5319.5  420.96  5340.9  423.27  5358.7  423.62  5399.5  424.14  5442.4  426.41
  5458.0  425.99  5516.5  426.95  5532.2  428.38  5575.1  428.90  5618.7  431.42
#Mann=6,-1,0
  4681.0    0.05       0  5005.3    0.03       0  5011.3    0.05       0
  5083.4    0.16       0  5086.1    0.05       0  5358.7    0.16       0
Bank Sta=5005.3,5011.3
Exp/Cntr=0.3,0.1

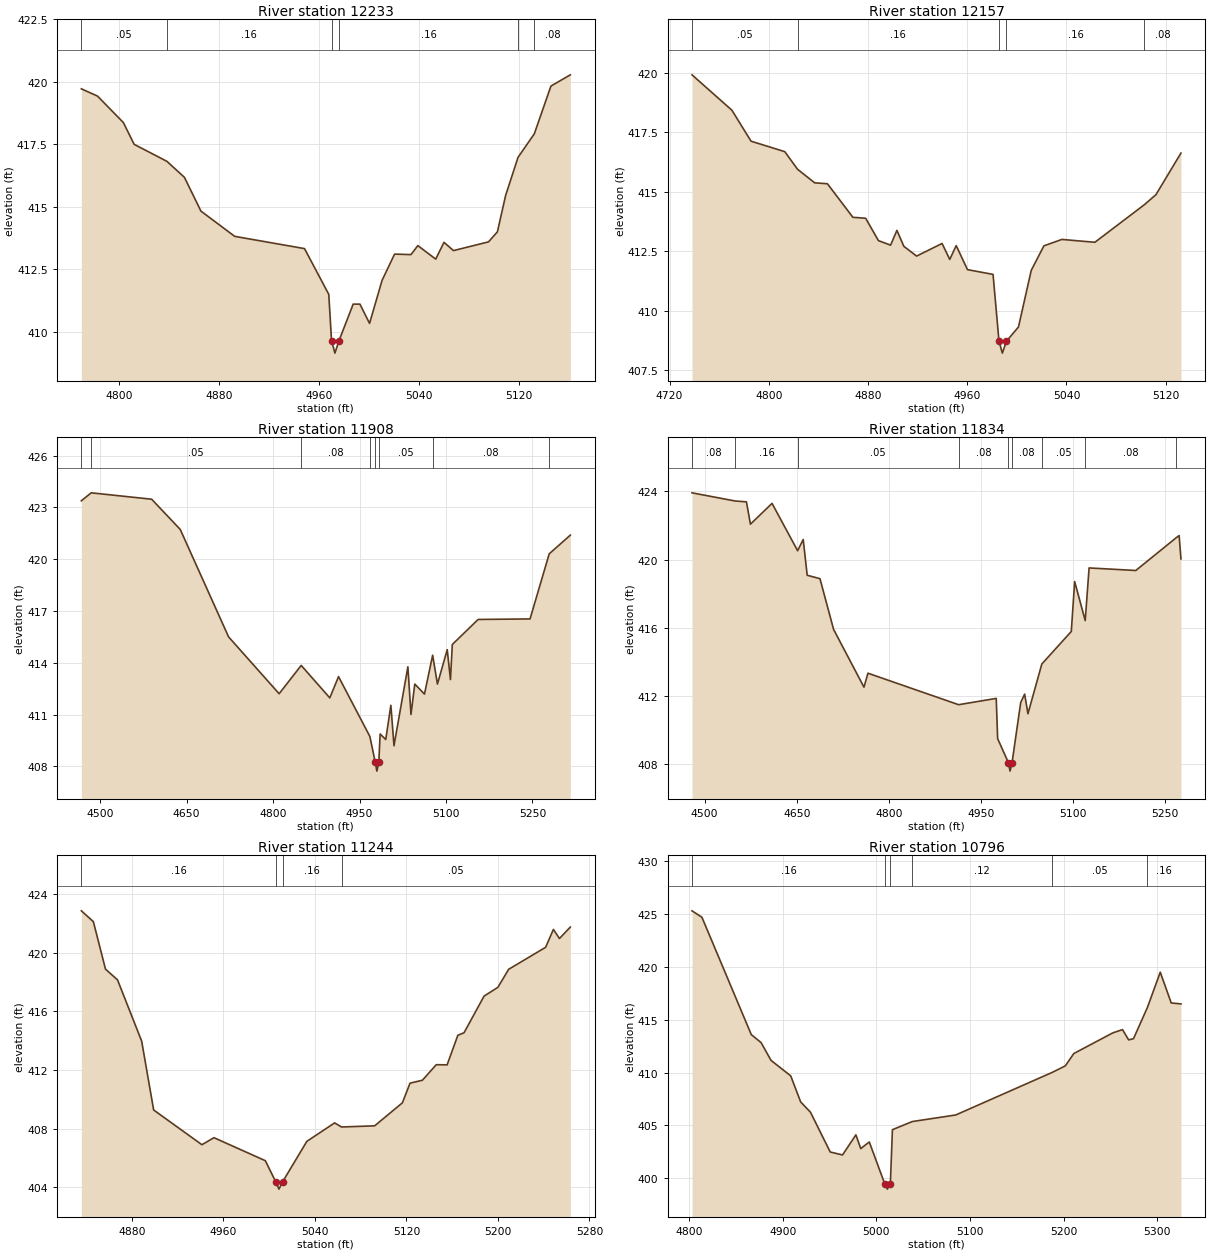
Type RM Length L Ch R = 1,12233,76,76,76
BEGIN DESCRIPTION:
Mapping XS 45363168
END DESCRIPTION:
XS GIS Cut Line= 4
      3691916.33     10775512.62      3691859.89     10775299.92
      3691816.49     10775300.78      3691720.11     10775217.43
#Sta/Elev= 30
  4770.0  419.72  4782.9  419.43  4803.6  418.37  4812.2  417.50  4838.4  416.82
  4852.4  416.18  4865.6  414.83  4892.6  413.82  4948.4  413.33  4967.8  411.50
  4970.0  409.65  4972.7  409.15  4976.0  409.65  4987.3  411.11  4992.7  411.11
  5000.4  410.34  5010.4  412.06  5020.4  413.11  5033.5  413.09  5039.0  413.45
  5053.3  412.91  5059.9  413.58  5067.5  413.25  5095.5  413.60  5102.6  414.00
  5109.2  415.46  5119.1  416.98  5132.1  417.92  5145.4  419.83  5160.9  420.28
#Mann=6,-1,0
  4770.0    0.05       0  4838.4    0.16       0  4970.0    0.07       0
  4976.0    0.16       0  5119.1    0.05       0  5132.1    0.08       0
Bank Sta=4970,4976
Exp/Cntr=0.3,0.1

Type RM Length L Ch R = 1,12157,249,249,249
BEGIN DESCRIPTION:
Mapping XS 5373a488
END DESCRIPTION:
XS GIS Cut Line= 3
      3691951.91     10775506.55      3691868.57     10775148.01
      3691856.56     10775124.84
#Sta/Elev= 30
  4738.1  419.92  4770.3  418.43  4785.7  417.13  4812.9  416.69  4823.2  415.95
  4837.0  415.38  4847.3  415.34  4867.8  413.93  4878.1  413.89  4888.4  412.95
  4898.2  412.76  4903.3  413.38  4908.9  412.71  4919.2  412.30  4939.7  412.83
  4945.9  412.16  4951.1  412.74  4960.2  411.73  4980.8  411.53  4985.6  408.72
  4988.3  408.22  4991.6  408.72  5001.3  409.32  5011.6  411.70  5021.8  412.73
  5036.3  413.00  5062.9  412.88  5102.8  414.46  5112.1  414.88  5132.3  416.63
#Mann=5,-1,0
  4738.1    0.05       0  4823.2    0.16       0  4985.6    0.07       0
  4991.6    0.16       0  5102.8    0.08       0
Bank Sta=4985.6,4991.6
Exp/Cntr=0.3,0.1

Type RM Length L Ch R = 1,11908,74,74,74
BEGIN DESCRIPTION:
UNT 014 IN CACR 26.0
END DESCRIPTION:
XS GIS Cut Line= 6
      3692452.12     10774770.62      3692251.60     10774932.08
      3692062.05     10775053.25      3691971.34     10775090.14
      3691914.14     10775118.06      3691709.69     10775122.70
#Sta/Elev= 30
  4467.3  423.38  4484.4  423.84  4589.3  423.47  4638.9  421.72  4722.8  415.50
  4810.5  412.21  4848.8  413.85  4898.4  411.97  4913.6  413.20  4967.9  409.74
  4977.4  408.23  4980.1  407.73  4983.4  408.23  4985.8  409.88  4995.5  409.56
  5004.4  411.54  5009.8  409.20  5033.9  413.77  5039.3  411.01  5045.9  412.77
  5062.7  412.19  5076.9  414.44  5085.2  412.77  5102.2  414.76  5107.8  413.03
  5111.0  415.06  5155.8  416.51  5245.9  416.54  5279.2  420.31  5315.8  421.39
#Mann=8,-1,0
  4467.3    0.08       0  4484.4    0.05       0  4848.8    0.08       0
  4967.9    0.05       0  4977.4    0.04       0  4983.4    0.05       0
  5076.9    0.08       0  5279.2    0.16       0
Bank Sta=4977.4,4983.4
Exp/Cntr=0.3,0.1

Type RM Length L Ch R = 1,11834,590,590,590
BEGIN DESCRIPTION:
UNT 014 IN CACR 25.0
END DESCRIPTION:
XS GIS Cut Line= 4
      3692409.28     10774695.61      3692148.86     10774910.89
      3692013.44     10774997.69      3691739.75     10775115.49
#Sta/Elev= 30
  4479.4  423.92  4549.7  423.44  4568.1  423.39  4574.6  422.08  4609.8  423.30
  4651.5  420.52  4660.6  421.18  4667.1  419.08  4687.9  418.88  4710.1  415.90
  4759.6  412.51  4766.1  413.33  4913.8  411.48  4975.1  411.85  4977.4  409.49
  4994.9  408.08  4997.6  407.58  5000.9  408.08  5015.0  411.61  5021.4  412.10
  5026.8  410.95  5049.4  413.87  5097.4  415.78  5102.9  418.71  5120.1  416.42
  5126.4  419.51  5202.5  419.36  5268.6  421.29  5273.1  421.41  5276.1  420.04
#Mann=9,-1,0
  4479.4    0.08       0  4549.7    0.16       0  4651.5    0.05       0
  4913.8    0.08       0  4994.9    0.07       0  5000.9    0.08       0
  5049.4    0.05       0  5120.1    0.08       0  5268.6    0.16       0
Bank Sta=4994.9,5000.9
Exp/Cntr=0.3,0.1

Type RM Length L Ch R = 1,11244,448,448,448
BEGIN DESCRIPTION:
UNT 014 IN CACR 24.0
END DESCRIPTION:
XS GIS Cut Line= 3
      3692199.60     10774510.19      3692049.61     10774560.19
      3691799.58     10774660.20
#Sta/Elev= 30
  4835.9  422.86  4846.4  422.12  4857.0  418.88  4867.5  418.15  4888.6  413.97
  4899.1  409.27  4941.3  406.90  4951.8  407.38  4996.7  405.81  5005.8  404.37
  5008.6  403.87  5011.8  404.37  5033.0  407.13  5057.3  408.39  5063.3  408.11
  5092.3  408.19  5116.5  409.76  5123.2  411.10  5134.0  411.30  5146.1  412.36
  5155.6  412.35  5165.0  414.37  5170.4  414.54  5187.9  417.04  5200.0  417.64
  5209.4  418.87  5241.7  420.37  5248.5  421.59  5253.8  420.97  5263.3  421.75
#Mann=4,-1,0
  4835.9    0.16       0  5005.8    0.07       0  5011.8    0.16       0
  5063.3    0.05       0
Bank Sta=5005.8,5011.8
Exp/Cntr=0.3,0.1

Type RM Length L Ch R = 1,10796,513,513,513
BEGIN DESCRIPTION:
UNT 014 IN CACR 23.0
END DESCRIPTION:
XS GIS Cut Line= 3
      3692349.64     10774260.20      3692199.61     10774210.19
      3691849.66     10774110.20
#Sta/Elev= 30
  4803.1  425.29  4813.7  424.68  4866.4  413.59  4876.9  412.83  4887.5  411.15
  4908.5  409.69  4919.1  407.23  4929.6  406.25  4950.7  402.49  4963.8  402.21
  4978.1  404.11  4983.3  402.81  4992.4  403.44  5008.9  399.48  5011.7  398.98
  5014.9  399.48  5017.1  404.60  5038.4  405.37  5084.7  405.99  5187.6  410.01
  5201.7  410.63  5210.8  411.80  5252.4  413.75  5262.8  414.06  5269.3  413.09
  5274.5  413.20  5289.4  416.16  5303.1  419.49  5314.8  416.58  5325.2  416.49
#Mann=6,-1,0
  4803.1    0.16       0  5008.9    0.07       0  5014.9    0.16       0
  5038.4    0.12       0  5187.6    0.05       0  5289.4    0.16       0
Bank Sta=5008.9,5014.9
Exp/Cntr=0.3,0.1

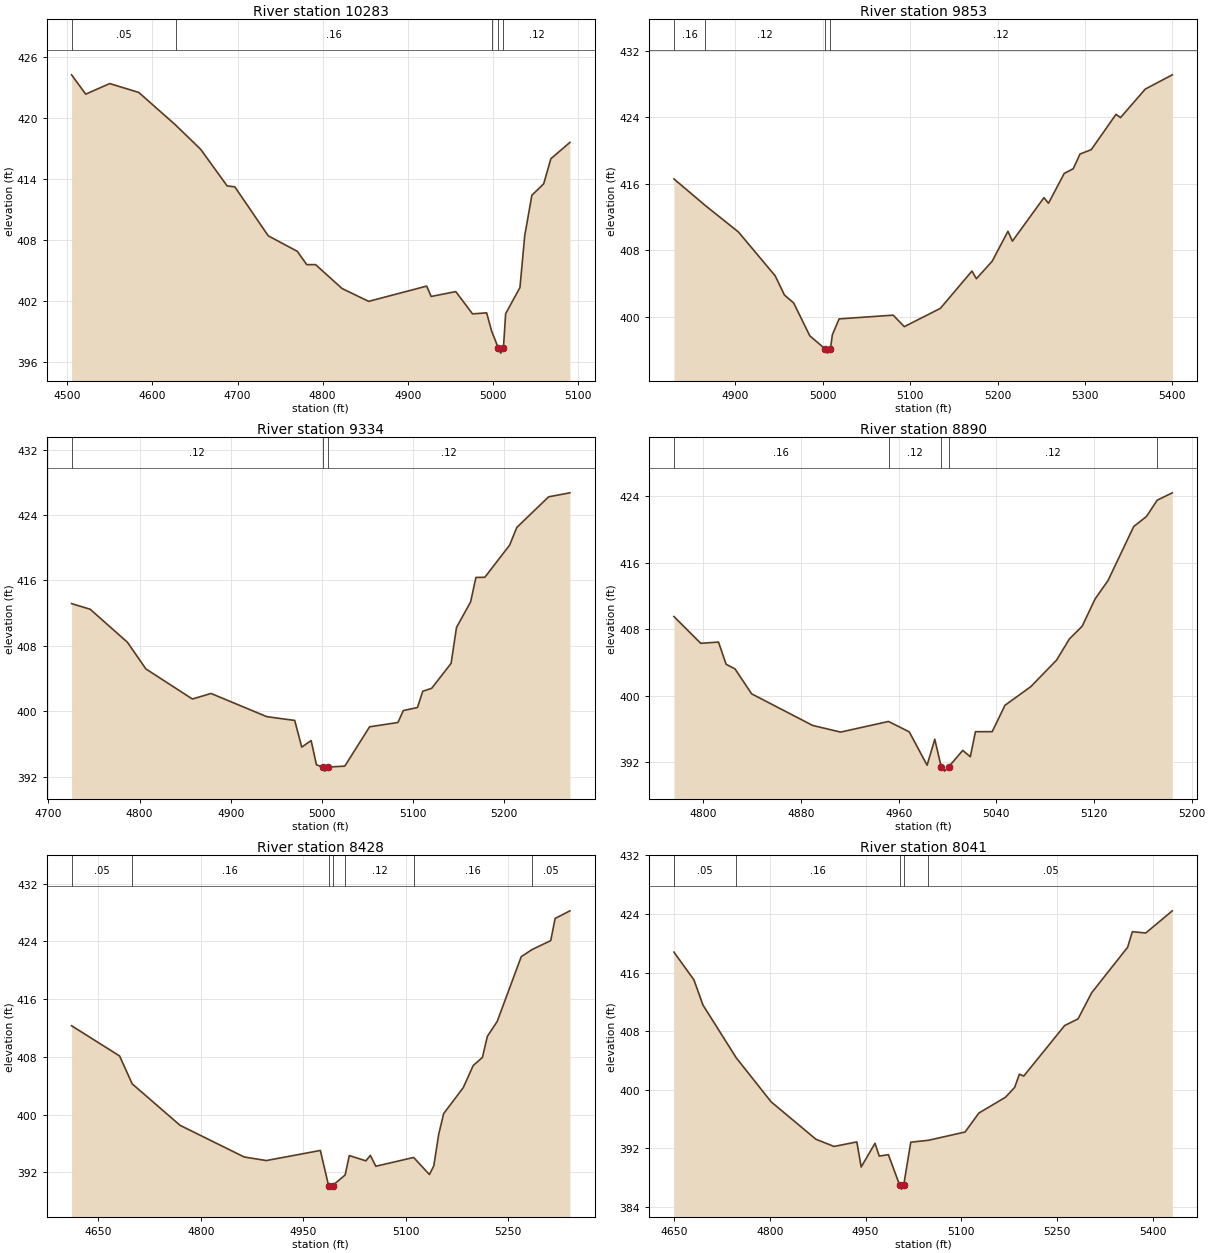
Type RM Length L Ch R = 1,10283,430,430,430
BEGIN DESCRIPTION:
UNT 014 IN CACR 22.0
END DESCRIPTION:
XS GIS Cut Line= 3
      3692705.56     10773937.89      3692249.61     10773810.19
      3692149.60     10773760.19
#Sta/Elev= 30
  4505.1  424.22  4521.7  422.32  4549.9  423.36  4584.0  422.49  4627.2  419.29
  4656.7  416.90  4687.8  413.30  4696.8  413.21  4736.1  408.39  4770.2  406.87
  4781.3  405.56  4791.7  405.56  4822.8  403.21  4854.0  401.95  4922.2  403.45
  4927.4  402.43  4956.3  402.91  4976.0  400.72  4992.6  400.82  4998.5  399.01
  5006.3  397.36  5009.1  396.86  5012.3  397.36  5014.9  400.74  5031.7  403.31
  5037.3  408.40  5045.7  412.38  5059.6  413.51  5068.0  415.97  5090.4  417.58
#Mann=5,-1,0
  4505.1    0.05       0  4627.2    0.16       0  4998.5    0.12       0
  5006.3    0.07       0  5012.3    0.12       0
Bank Sta=5006.3,5012.3
Exp/Cntr=0.3,0.1

Type RM Length L Ch R = 1,9853,519,519,519
BEGIN DESCRIPTION:
UNT 014 IN CACR 21.0
END DESCRIPTION:
XS GIS Cut Line= 3
      3692649.59     10773460.19      3692499.61     10773510.19
      3692099.61     10773410.19
#Sta/Elev= 30
  4829.6  416.59  4865.1  413.43  4903.4  410.22  4945.5  404.95  4956.1  402.64
  4966.6  401.70  4985.1  397.75  5002.7  396.17  5005.5  395.67  5008.7  396.17
  5010.9  397.86  5018.6  399.78  5080.5  400.23  5093.3  398.85  5134.6  401.05
  5170.7  405.53  5175.8  404.61  5193.8  406.70  5211.9  410.30  5217.0  409.12
  5253.1  414.34  5258.3  413.67  5276.3  417.25  5286.6  417.81  5294.4  419.58
  5307.2  420.10  5335.6  424.35  5340.7  423.95  5369.1  427.38  5400.0  429.09
#Mann=4,-1,0
  4829.6    0.16       0  4865.1    0.12       0  5002.7    0.07       0
  5008.7    0.12       0
Bank Sta=5002.7,5008.7
Exp/Cntr=0.3,0.1

Type RM Length L Ch R = 1,9334,444,444,444
BEGIN DESCRIPTION:
UNT 014 IN CACR 20.0
END DESCRIPTION:
XS GIS Cut Line= 3
      3692749.57     10773210.18      3692499.61     10773160.19
      3692349.59     10772910.16
#Sta/Elev= 30
  4725.5  413.17  4745.9  412.48  4786.7  408.45  4807.0  405.18  4858.0  401.50
  4878.4  402.18  4939.6  399.34  4970.2  398.88  4977.9  395.62  4988.2  396.42
  4994.0  393.46  5000.7  393.18  5003.5  392.68  5006.7  393.18  5025.1  393.29
  5052.3  398.10  5083.4  398.63  5089.3  400.09  5104.8  400.46  5110.6  402.45
  5120.4  402.81  5141.7  405.87  5147.6  410.25  5163.1  413.38  5168.9  416.37
  5178.7  416.39  5205.9  420.33  5213.7  422.48  5248.6  426.23  5272.0  426.72
#Mann=3,-1,0
  4725.5    0.12       0  5000.7    0.07       0  5006.7    0.12       0
Bank Sta=5000.7,5006.7
Exp/Cntr=0.3,0.1

Type RM Length L Ch R = 1,8890,462,462,462
BEGIN DESCRIPTION:
UNT 014 IN CACR 19.0
END DESCRIPTION:
XS GIS Cut Line= 3
      3692849.62     10773010.20      3692699.61     10772810.19
      3692549.64     10772760.20
#Sta/Elev= 30
  4776.0  409.51  4797.9  406.29  4812.5  406.44  4818.7  403.77  4826.0  403.21
  4839.6  400.21  4889.6  396.40  4912.5  395.60  4951.7  396.88  4968.7  395.63
  4983.3  391.61  4989.6  394.74  4994.9  391.40  4997.6  390.90  5000.9  391.40
  5012.5  393.40  5018.7  392.63  5022.9  395.65  5036.6  395.65  5047.1  398.83
  5068.2  401.07  5089.3  404.26  5099.8  406.81  5110.3  408.35  5120.9  411.64
  5131.4  413.83  5152.5  420.35  5163.0  421.57  5171.7  423.52  5184.1  424.41
#Mann=5,-1,0
  4776.0    0.16       0  4951.7    0.12       0  4994.9    0.07       0
  5000.9    0.12       0  5171.7    0.16       0
Bank Sta=4994.9,5000.9
Exp/Cntr=0.3,0.1

Type RM Length L Ch R = 1,8428,387,387,387
BEGIN DESCRIPTION:
UNT 014 IN CACR 18.0
END DESCRIPTION:
XS GIS Cut Line= 3
      3693411.82     10772801.00      3693049.61     10772610.19
      3692849.58     10772360.15
#Sta/Elev= 30
  4610.7  412.32  4681.0  408.13  4699.4  404.27  4769.6  398.51  4863.3  394.13
  4895.8  393.63  4974.9  395.03  4986.9  390.17  4989.6  389.67  4992.9  390.17
  5011.2  391.63  5017.3  394.32  5041.7  393.59  5048.1  394.35  5056.1  392.84
  5111.5  394.06  5134.6  391.69  5141.0  392.90  5148.2  397.27  5155.4  400.13
  5184.2  403.75  5198.6  406.79  5212.2  407.93  5219.4  410.85  5233.8  412.91
  5269.0  421.89  5284.8  422.88  5312.2  424.12  5318.6  427.19  5340.3  428.25
#Mann=7,-1,0
  4610.7    0.05       0  4699.4    0.16       0  4986.9    0.07       0
  4992.9    0.16       0  5011.2    0.12       0  5111.5    0.16       0
  5284.8    0.05       0
Bank Sta=4986.9,4992.9
Exp/Cntr=0.3,0.1

Type RM Length L Ch R = 1,8041,531,531,531
BEGIN DESCRIPTION:
UNT 014 IN CACR 17.0
END DESCRIPTION:
XS GIS Cut Line= 2
      3693592.38     10772662.10      3693016.44     10772134.75
#Sta/Elev= 30
  4649.7  418.79  4681.0  415.00  4695.2  411.56  4747.2  404.37  4801.9  398.35
  4872.2  393.23  4900.6  392.25  4936.3  392.87  4943.1  389.44  4964.7  392.68
  4971.5  390.93  4985.7  391.13  5003.6  386.92  5006.4  386.42  5009.6  386.92
  5020.8  392.83  5048.4  393.09  5105.9  394.22  5127.5  396.81  5169.4  398.98
  5183.6  400.32  5191.0  402.12  5197.8  401.86  5261.9  408.76  5282.9  409.67
  5304.3  413.25  5360.6  419.45  5368.0  421.58  5389.0  421.40  5430.6  424.43
#Mann=5,-1,0
  4649.7    0.05       0  4747.2    0.16       0  5003.6    0.07       0
  5009.6    0.16       0  5048.4    0.05       0
Bank Sta=5003.6,5009.6
Exp/Cntr=0.3,0.1

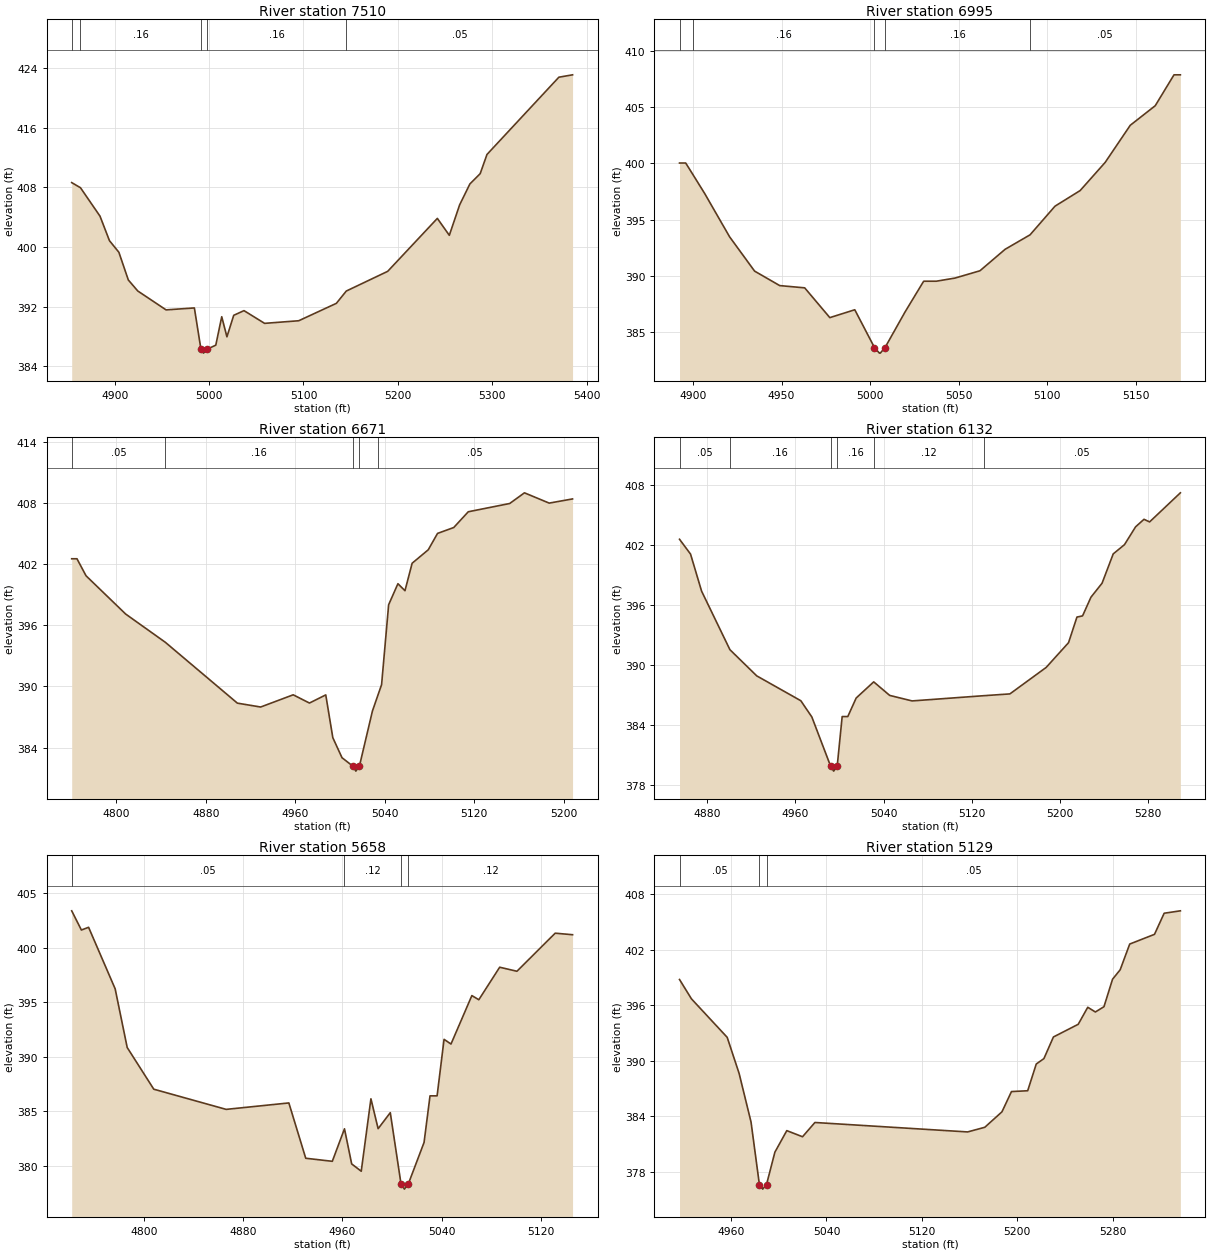
Type RM Length L Ch R = 1,7510,515,515,515
BEGIN DESCRIPTION:
UNT 014 IN CACR 16.0
END DESCRIPTION:
XS GIS Cut Line= 3
      3693649.59     10772110.19      3693499.61     10772110.19
      3693149.58     10771960.18
#Sta/Elev= 30
  4854.4  408.65  4863.7  407.96  4884.4  404.14  4894.4  400.85  4904.4  399.29
  4914.4  395.57  4924.4  394.09  4954.4  391.55  4984.4  391.81  4991.4  386.24
  4994.1  385.74  4997.4  386.24  5007.1  386.81  5013.4  390.63  5018.9  387.93
  5026.1  390.82  5037.0  391.45  5058.8  389.74  5095.0  390.09  5134.9  392.43
  5145.4  394.08  5189.3  396.73  5241.9  403.84  5254.6  401.57  5265.5  405.65
  5276.4  408.47  5287.3  409.85  5294.5  412.43  5370.7  422.81  5385.2  423.13
#Mann=5,-1,0
  4854.4    0.05       0  4863.7    0.16       0  4991.4    0.07       0
  4997.4    0.16       0  5145.4    0.05       0
Bank Sta=4991.4,4997.4
Exp/Cntr=0.3,0.1

Type RM Length L Ch R = 1,6995,324,324,324
BEGIN DESCRIPTION:
UNT 014 IN CACR 15.0
END DESCRIPTION:
XS GIS Cut Line= 3
      3693699.61     10771860.19      3693599.61     10771760.19
      3693499.57     10771660.15
#Sta/Elev= 28
  4892.4  400.03  4895.9  400.03  4899.9  399.02  4906.6  397.32  4920.7  393.46
  4934.8  390.41  4949.0  389.12  4963.1  388.92  4977.3  386.27  4991.4  386.97
  5002.5  383.61  5005.3  383.11  5005.8  383.11  5008.5  383.61  5019.7  386.75
  5030.3  389.51  5037.4  389.51  5048.0  389.79  5062.1  390.44  5076.3  392.35
  5090.4  393.64  5104.5  396.19  5118.7  397.58  5132.8  400.08  5147.0  403.39
  5161.1  405.13  5171.7  407.88  5175.3  407.88
#Mann=5,-1,0
  4892.4    0.05       0  4899.9    0.16       0  5002.5    0.07       0
  5008.5    0.16       0  5090.4    0.05       0
Bank Sta=5002.5,5008.5
Exp/Cntr=0.3,0.1

Type RM Length L Ch R = 1,6671,539,539,539
BEGIN DESCRIPTION:
UNT 014 IN CACR 14.0
END DESCRIPTION:
XS GIS Cut Line= 2
      3693974.32     10771762.79      3693704.04     10771405.88
#Sta/Elev= 30
  4760.1  402.55  4764.8  402.55  4772.9  400.88  4808.3  397.12  4843.8  394.34
  4908.2  388.36  4929.0  387.98  4958.1  389.18  4972.6  388.37  4987.2  389.17
  4993.5  384.97  5001.7  383.00  5011.3  382.18  5014.1  381.68  5017.3  382.18
  5028.9  387.58  5033.9  389.17  5037.1  390.18  5043.4  398.03  5051.7  400.10
  5058.0  399.41  5064.4  402.11  5078.8  403.43  5087.1  405.04  5101.6  405.62
  5114.6  407.17  5151.6  407.98  5164.8  409.03  5186.9  408.02  5207.8  408.43
#Mann=5,-1,0
  4760.1    0.05       0  4843.8    0.16       0  5011.3    0.07       0
  5017.3    0.16       0  5033.9    0.05       0
Bank Sta=5011.3,5017.3
Exp/Cntr=0.3,0.1

Type RM Length L Ch R = 1,6132,474,474,474
BEGIN DESCRIPTION:
UNT 014 IN CACR 13.0
END DESCRIPTION:
XS GIS Cut Line= 3
      3694249.64     10771260.19      3694099.61     10771260.19
      3693799.58     10771210.18
#Sta/Elev= 30
  4855.0  402.55  4865.0  401.07  4875.0  397.38  4900.7  391.54  4925.0  388.93
  4965.0  386.45  4975.0  384.83  4992.0  379.93  4994.8  379.43  4998.0  379.93
  5002.5  384.87  5007.6  384.87  5015.2  386.72  5031.1  388.33  5045.6  386.98
  5065.9  386.43  5130.8  386.95  5154.6  387.13  5187.5  389.77  5207.8  392.24
  5215.4  394.79  5220.5  394.91  5228.1  396.77  5238.2  398.17  5248.3  401.09
  5258.5  402.01  5268.6  403.79  5276.2  404.54  5281.3  404.28  5309.2  407.18
#Mann=6,-1,0
  4855.0    0.05       0  4900.7    0.16       0  4992.0    0.07       0
  4998.0    0.16       0  5031.1    0.12       0  5130.8    0.05       0
Bank Sta=4992,4998
Exp/Cntr=0.3,0.1

Type RM Length L Ch R = 1,5658,529,529,529
BEGIN DESCRIPTION:
UNT 014 IN CACR 12.0
END DESCRIPTION:
XS GIS Cut Line= 3
      3694349.61     10771110.19      3694199.61     10770860.19
      3694149.59     10770760.15
#Sta/Elev= 30
  4742.0  403.39  4749.8  401.63  4755.6  401.88  4777.0  396.24  4786.7  390.86
  4808.1  387.04  4866.4  385.19  4916.9  385.78  4930.5  380.71  4951.9  380.43
  4961.7  383.41  4967.5  380.19  4975.2  379.52  4983.0  386.16  4988.8  383.42
  4998.6  384.89  5007.2  378.38  5010.0  377.88  5013.2  378.38  5025.8  382.16
  5030.6  386.43  5036.3  386.43  5041.9  391.61  5047.5  391.18  5064.3  395.62
  5069.9  395.24  5086.7  398.22  5100.6  397.85  5131.4  401.34  5145.4  401.20
#Mann=4,-1,0
  4742.0    0.05       0  4961.7    0.12       0  5007.2    0.07       0
  5013.2    0.12       0
Bank Sta=5007.2,5013.2
Exp/Cntr=0.3,0.1

Type RM Length L Ch R = 1,5129,440,440,440
BEGIN DESCRIPTION:
UNT 014 IN CACR 11.0
END DESCRIPTION:
XS GIS Cut Line= 3
      3694649.61     10770660.19      3694549.61     10770660.19
      3694299.58     10770460.16
#Sta/Elev= 30
  4916.7  398.80  4926.7  396.71  4956.7  392.55  4966.7  388.65  4976.7  383.40
  4983.7  376.65  4986.5  376.15  4989.7  376.65  4996.7  380.14  5006.7  382.47
  5019.9  381.81  5030.3  383.35  5158.4  382.33  5172.8  382.83  5187.2  384.50
  5195.2  386.69  5208.8  386.78  5216.0  389.67  5222.4  390.25  5230.4  392.59
  5251.2  393.96  5259.2  395.80  5265.6  395.29  5272.8  395.86  5280.0  398.83
  5286.4  399.85  5294.4  402.63  5315.2  403.68  5323.3  405.96  5336.9  406.22
#Mann=3,-1,0
  4916.7    0.05       0  4983.7    0.03       0  4989.7    0.05       0
Bank Sta=4983.7,4989.7
Exp/Cntr=0.3,0.1

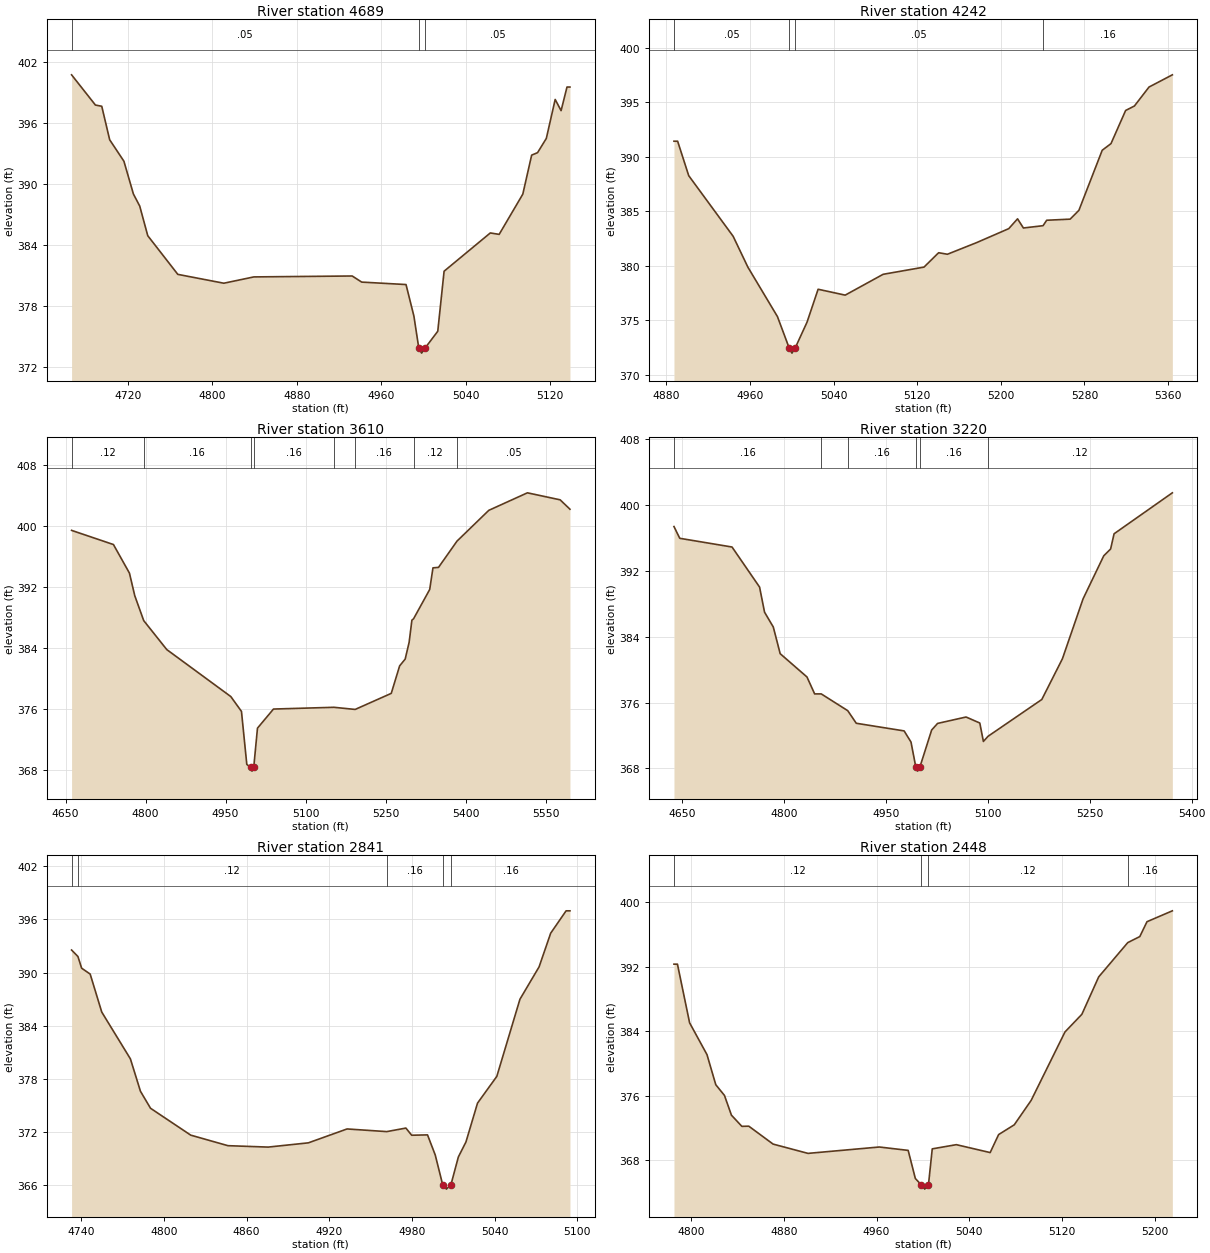
Type RM Length L Ch R = 1,4689,447,447,447
BEGIN DESCRIPTION:
UNT 014 IN CACR 10.0
END DESCRIPTION:
XS GIS Cut Line= 3
      3694799.63     10770560.23      3694599.61     10770260.19
      3694499.61     10770210.19
#Sta/Elev= 30
  4666.5  400.70  4689.1  397.73  4695.1  397.61  4702.6  394.32  4716.1  392.21
  4725.1  388.99  4731.1  387.80  4738.7  384.89  4767.2  381.09  4810.8  380.22
  4839.3  380.84  4932.5  380.93  4941.5  380.33  4983.5  380.09  4991.0  376.98
  4995.6  373.85  4998.3  373.35  5001.6  373.85  5013.6  375.50  5019.6  381.40
  5063.4  385.16  5071.8  385.02  5094.2  388.97  5102.6  392.81  5108.2  393.05
  5116.5  394.45  5124.9  398.28  5130.5  397.18  5136.1  399.50  5138.9  399.50
#Mann=3,-1,0
  4666.5    0.05       0  4995.6    0.03       0  5001.6    0.05       0
Bank Sta=4995.6,5001.6
Exp/Cntr=0.3,0.1

Type RM Length L Ch R = 1,4242,632,632,632
BEGIN DESCRIPTION:
UNT 014 IN CACR 9.0
END DESCRIPTION:
XS GIS Cut Line= 3
      3695099.61     10770310.19      3694999.61     10770210.19
      3694849.62     10769910.21
#Sta/Elev= 30
  4887.3  391.42  4890.8  391.42  4901.4  388.26  4943.9  382.70  4958.0  379.87
  4986.3  375.33  4997.4  372.48  5000.2  371.98  5003.4  372.48  5014.6  374.82
  5025.2  377.84  5051.1  377.30  5087.4  379.21  5126.5  379.87  5140.5  381.19
  5148.9  381.05  5176.9  382.12  5207.6  383.40  5216.0  384.30  5221.6  383.46
  5240.4  383.67  5243.9  384.17  5266.3  384.27  5274.7  385.08  5297.0  390.59
  5305.4  391.20  5319.4  394.24  5327.8  394.65  5341.8  396.39  5364.1  397.51
#Mann=4,-1,0
  4887.3    0.05       0  4997.4    0.03       0  5003.4    0.05       0
  5240.4    0.16       0
Bank Sta=4997.4,5003.4
Exp/Cntr=0.3,0.1

Type RM Length L Ch R = 1,3610,390,390,390
BEGIN DESCRIPTION:
UNT 014 IN CACR 8.0
END DESCRIPTION:
XS GIS Cut Line= 3
      3695479.96     10770438.60      3695495.58     10769985.52
      3695360.63     10769523.58
#Sta/Elev= 30
  4661.2  399.42  4739.7  397.56  4769.7  393.81  4779.7  390.84  4796.5  387.57
  4839.7  383.77  4959.8  377.60  4979.8  375.65  4989.8  368.69  4996.8  368.31
  4999.6  367.81  5002.8  368.31  5009.8  373.45  5039.8  375.96  5153.2  376.19
  5193.0  375.91  5260.7  378.02  5276.4  381.63  5286.8  382.52  5294.2  384.72
  5299.4  387.63  5302.5  387.81  5332.8  391.66  5338.9  394.50  5349.3  394.56
  5384.0  398.01  5443.6  402.05  5516.0  404.35  5577.4  403.43  5595.8  402.20
#Mann=8,-1,0
  4661.2    0.12       0  4796.5    0.16       0  4996.8    0.07       0
  5002.8    0.16       0  5153.2    0.05       0  5193.0    0.16       0
  5302.5    0.12       0  5384.0    0.05       0
Bank Sta=4996.8,5002.8
Exp/Cntr=0.3,0.1

Type RM Length L Ch R = 1,3220,379,379,379
BEGIN DESCRIPTION:
UNT 014 IN CACR 7.0
END DESCRIPTION:
XS GIS Cut Line= 2
      3695875.79     10770334.50      3695761.20     10769610.51
#Sta/Elev= 30
  4638.6  397.41  4647.1  395.98  4724.0  394.92  4764.5  390.05  4771.8  387.00
  4784.7  385.19  4794.8  381.95  4834.2  379.12  4845.5  377.06  4855.2  377.06
  4894.2  375.02  4906.7  373.49  4977.1  372.56  4987.2  371.21  4994.3  368.17
  4997.1  367.67  5000.3  368.17  5017.6  372.67  5026.3  373.47  5068.2  374.25
  5088.4  373.52  5093.7  371.28  5100.6  371.91  5179.6  376.38  5209.9  381.33
  5240.3  388.62  5270.7  393.85  5280.8  394.68  5285.9  396.53  5371.6  401.51
#Mann=6,-1,0
  4638.6    0.16       0  4855.2    0.12       0  4894.2    0.16       0
  4994.3    0.07       0  5000.3    0.16       0  5100.6    0.12       0
Bank Sta=4994.3,5000.3
Exp/Cntr=0.3,0.1

Type RM Length L Ch R = 1,2841,393,393,393
BEGIN DESCRIPTION:
UNT 014 IN CACR 6.0
END DESCRIPTION:
XS GIS Cut Line= 3
      3696199.61     10769960.19      3696049.61     10769760.19
      3695999.61     10769660.20
#Sta/Elev= 30
  4732.9  392.55  4737.5  391.82  4740.2  390.50  4746.4  389.83  4754.8  385.54
  4775.6  380.25  4782.9  376.59  4790.2  374.67  4819.4  371.63  4846.4  370.44
  4875.6  370.28  4904.8  370.76  4932.9  372.33  4961.7  372.03  4975.6  372.43
  4979.8  371.62  4991.3  371.66  4996.9  369.39  5002.3  366.03  5005.0  365.53
  5008.3  366.03  5013.7  369.17  5019.2  370.86  5027.6  375.25  5041.6  378.27
  5058.4  386.99  5072.3  390.65  5080.7  394.45  5091.9  396.98  5094.7  396.98
#Mann=5,-1,0
  4732.9    0.16       0  4737.5    0.12       0  4961.7    0.16       0
  5002.3    0.07       0  5008.3    0.16       0
Bank Sta=5002.3,5008.3
Exp/Cntr=0.3,0.1

Type RM Length L Ch R = 1,2448,729,729,729
BEGIN DESCRIPTION:
UNT 014 IN CACR 5.0
END DESCRIPTION:
XS GIS Cut Line= 3
      3696499.61     10769760.19      3696399.61     10769610.19
      3696249.60     10769410.17
#Sta/Elev= 30
  4785.1  392.31  4788.1  392.31  4798.6  385.04  4813.6  381.10  4821.2  377.37
  4828.7  376.04  4834.7  373.60  4843.7  372.21  4849.7  372.23  4870.7  370.01
  4900.8  368.86  4962.4  369.65  4987.3  369.23  4993.5  365.75  4998.8  364.93
  5001.6  364.43  5004.8  364.93  5008.1  369.42  5028.9  369.94  5058.1  368.96
  5065.4  371.19  5078.9  372.40  5093.5  375.43  5122.7  383.91  5137.3  386.10
  5151.8  390.73  5176.9  394.98  5187.3  395.73  5193.5  397.57  5215.4  398.92
#Mann=4,-1,0
  4785.1    0.12       0  4998.8    0.07       0  5004.8    0.12       0
  5176.9    0.16       0
Bank Sta=4998.8,5004.8
Exp/Cntr=0.3,0.1