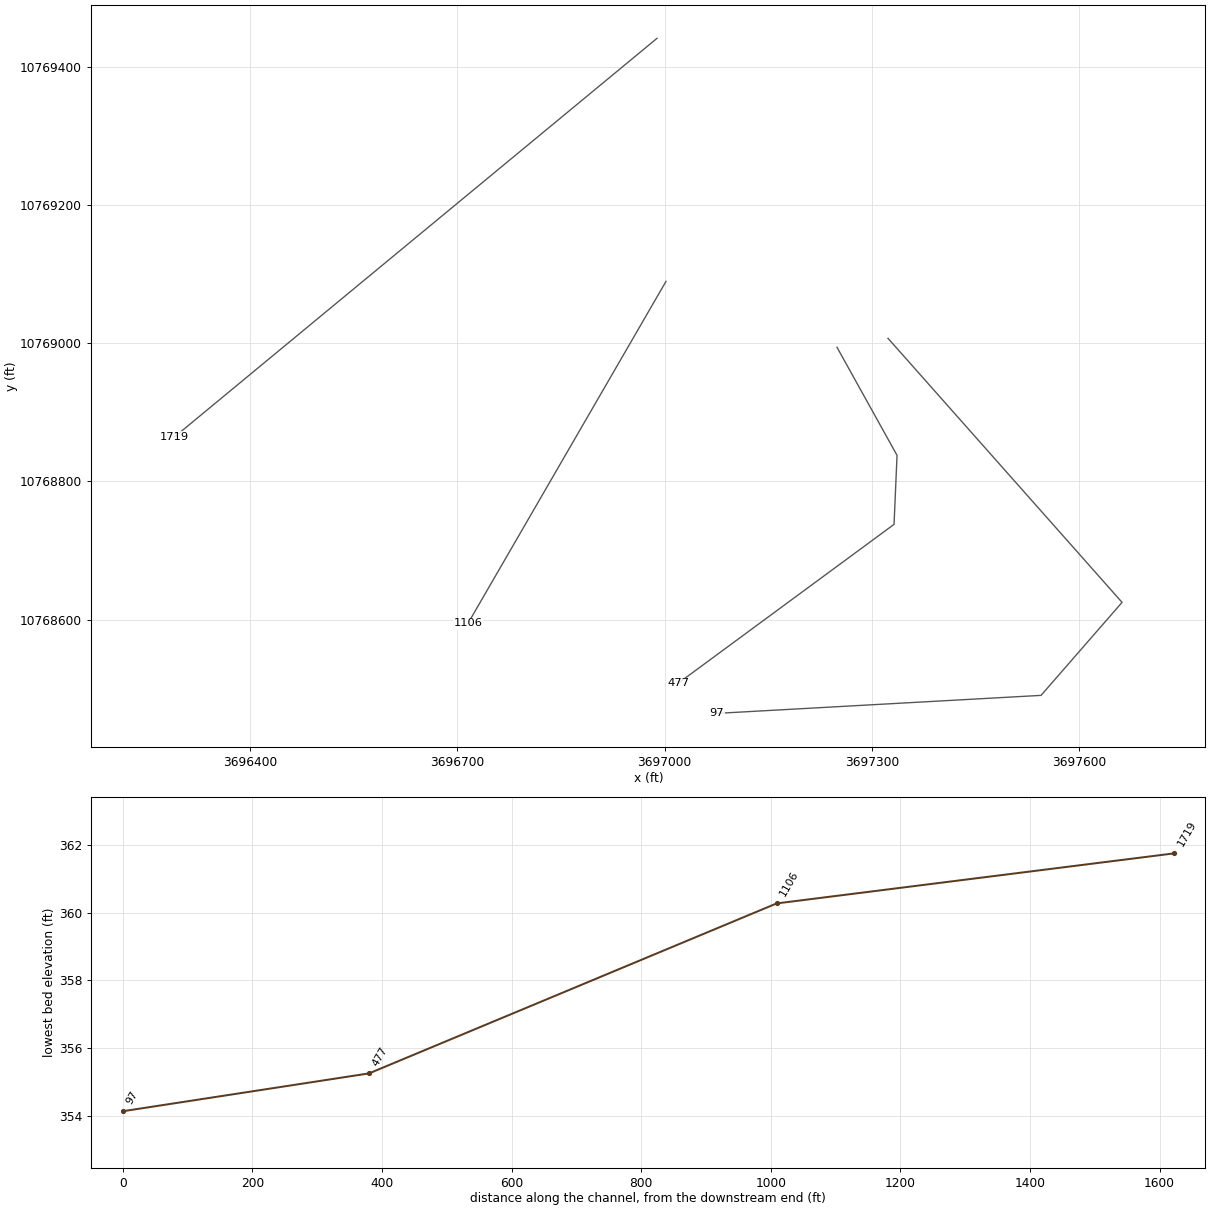
HEC-RAS study UNT 014 IN CACR.prj: UNT 014 IN CACR Base Level Engineering

--- UNT 014 IN CACR.g01 (geometry) --- (continued)

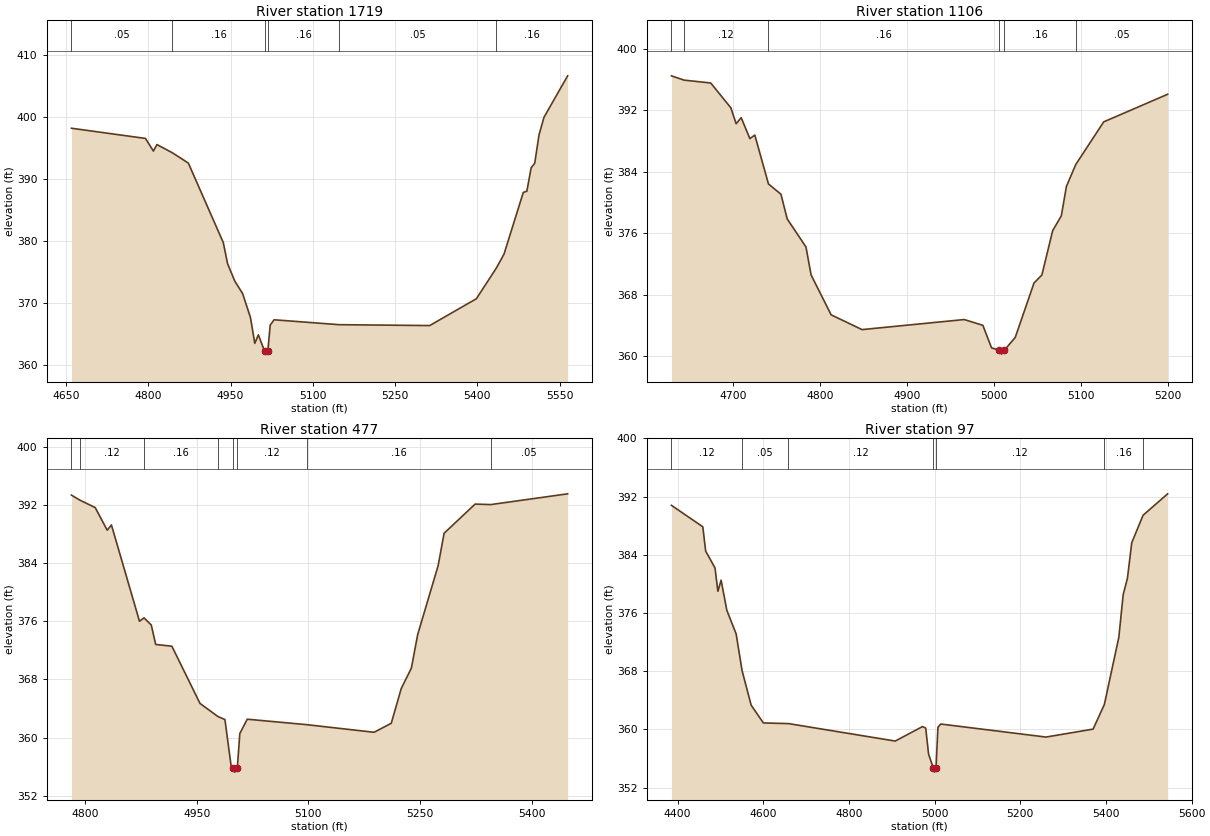
Type RM Length L Ch R = 1,1719,613,613,613
BEGIN DESCRIPTION:
UNT 014 IN CACR 4.0
END DESCRIPTION:
XS GIS Cut Line= 2
      3696989.08     10769440.90      3696291.28     10768864.46
#Sta/Elev= 30
  4659.7  398.13  4794.7  396.49  4809.1  394.46  4815.6  395.50  4843.6  394.19
  4872.9  392.52  4936.7  379.71  4944.4  376.33  4957.6  373.52  4971.9  371.51
  4986.2  367.66  4994.1  363.50  5000.6  364.86  5011.9  362.26  5014.7  361.76
  5017.9  362.26  5022.2  366.43  5029.2  367.29  5148.1  366.50  5313.2  366.36
  5398.3  370.68  5434.6  375.60  5448.7  377.86  5483.9  387.80  5490.4  387.99
  5498.2  391.76  5504.7  392.48  5512.6  397.07  5521.6  399.89  5564.8  406.57
#Mann=6,-1,0
  4659.7    0.05       0  4843.6    0.16       0  5011.9    0.07       0
  5017.9    0.16       0  5148.1    0.05       0  5434.6    0.16       0
Bank Sta=5011.9,5017.9
Exp/Cntr=0.3,0.1

Type RM Length L Ch R = 1,1106,629,629,629
BEGIN DESCRIPTION:
UNT 014 IN CACR 3.0
END DESCRIPTION:
XS GIS Cut Line= 2
      3697002.12     10769089.34      3696715.83     10768594.84
#Sta/Elev= 30
  4628.7  396.49  4643.2  395.93  4673.9  395.56  4697.1  392.33  4703.2  390.26
  4709.0  391.05  4719.0  388.32  4724.7  388.78  4740.4  382.43  4754.8  381.08
  4762.0  377.87  4783.6  374.23  4789.5  370.59  4812.6  365.39  4848.2  363.47
  4965.8  364.78  4987.3  364.03  4997.3  361.10  5006.0  360.78  5008.8  360.28
  5012.0  360.78  5024.6  362.45  5046.2  369.53  5055.3  370.58  5067.7  376.34
  5077.7  378.28  5083.5  382.09  5094.3  384.95  5126.5  390.50  5200.1  394.09
#Mann=6,-1,0
  4628.7    0.05       0  4643.2    0.12       0  4740.4    0.16       0
  5006.0    0.07       0  5012.0    0.16       0  5094.3    0.05       0
Bank Sta=5006,5012
Exp/Cntr=0.3,0.1

Type RM Length L Ch R = 1,477,380,380,380
BEGIN DESCRIPTION:
UNT 014 IN CACR 2.0
END DESCRIPTION:
XS GIS Cut Line= 4
      3697249.52     10768993.88      3697336.33     10768837.62
      3697331.99     10768737.80      3697019.50     10768507.77
#Sta/Elev= 30
  4781.8  393.35  4793.3  392.65  4813.7  391.64  4829.8  388.53  4835.5  389.25
  4873.2  376.00  4879.3  376.47  4889.0  375.49  4895.0  372.81  4916.7  372.57
  4954.5  364.70  4978.7  362.89  4988.0  362.48  4996.6  355.88  4998.6  355.75
  5001.4  355.25  5004.6  355.75  5008.0  360.56  5018.0  362.53  5097.7  361.78
  5188.4  360.73  5211.5  361.97  5224.9  366.75  5238.5  369.55  5247.0  374.17
  5274.5  383.66  5282.5  388.11  5324.2  392.12  5345.2  392.05  5448.5  393.53
#Mann=8,-1,0
  4781.8    0.16       0  4793.3    0.12       0  4879.3    0.16       0
  4978.7    0.12       0  4998.6    0.07       0  5004.6    0.12       0
  5097.7    0.16       0  5345.2    0.05       0
Bank Sta=4998.6,5004.6
Exp/Cntr=0.3,0.1

Type RM Length L Ch R = 1,97,0,0,0
BEGIN DESCRIPTION:
UNT 014 IN CACR 1.0
END DESCRIPTION:
XS GIS Cut Line= 4
      3697323.29     10769006.91      3697661.85     10768624.95
      3697544.66     10768490.40      3697075.92     10768464.36
#Sta/Elev= 30
  4385.6  390.80  4458.8  387.85  4465.5  384.50  4487.3  382.19  4494.0  378.98
  4501.5  380.51  4514.9  376.37  4536.6  373.13  4550.4  368.10  4571.7  363.33
  4600.2  360.89  4658.8  360.80  4908.0  358.40  4971.6  360.39  4979.2  360.18
  4985.8  356.63  4997.1  354.63  4999.8  354.13  5003.1  354.63  5007.7  360.29
  5014.3  360.74  5259.8  358.95  5369.9  360.04  5396.2  363.43  5430.0  372.67
  5440.1  378.52  5450.1  380.78  5460.1  385.65  5486.5  389.43  5543.9  392.38
#Mann=7,-1,0
  4385.6    0.12       0  4550.4    0.05       0  4658.8    0.12       0
  4997.1    0.07       0  5003.1    0.12       0  5396.2    0.16       0
  5486.5    0.05       0
Bank Sta=4997.1,5003.1
Exp/Cntr=0.3,0.1

Chan Stop Cuts=-1