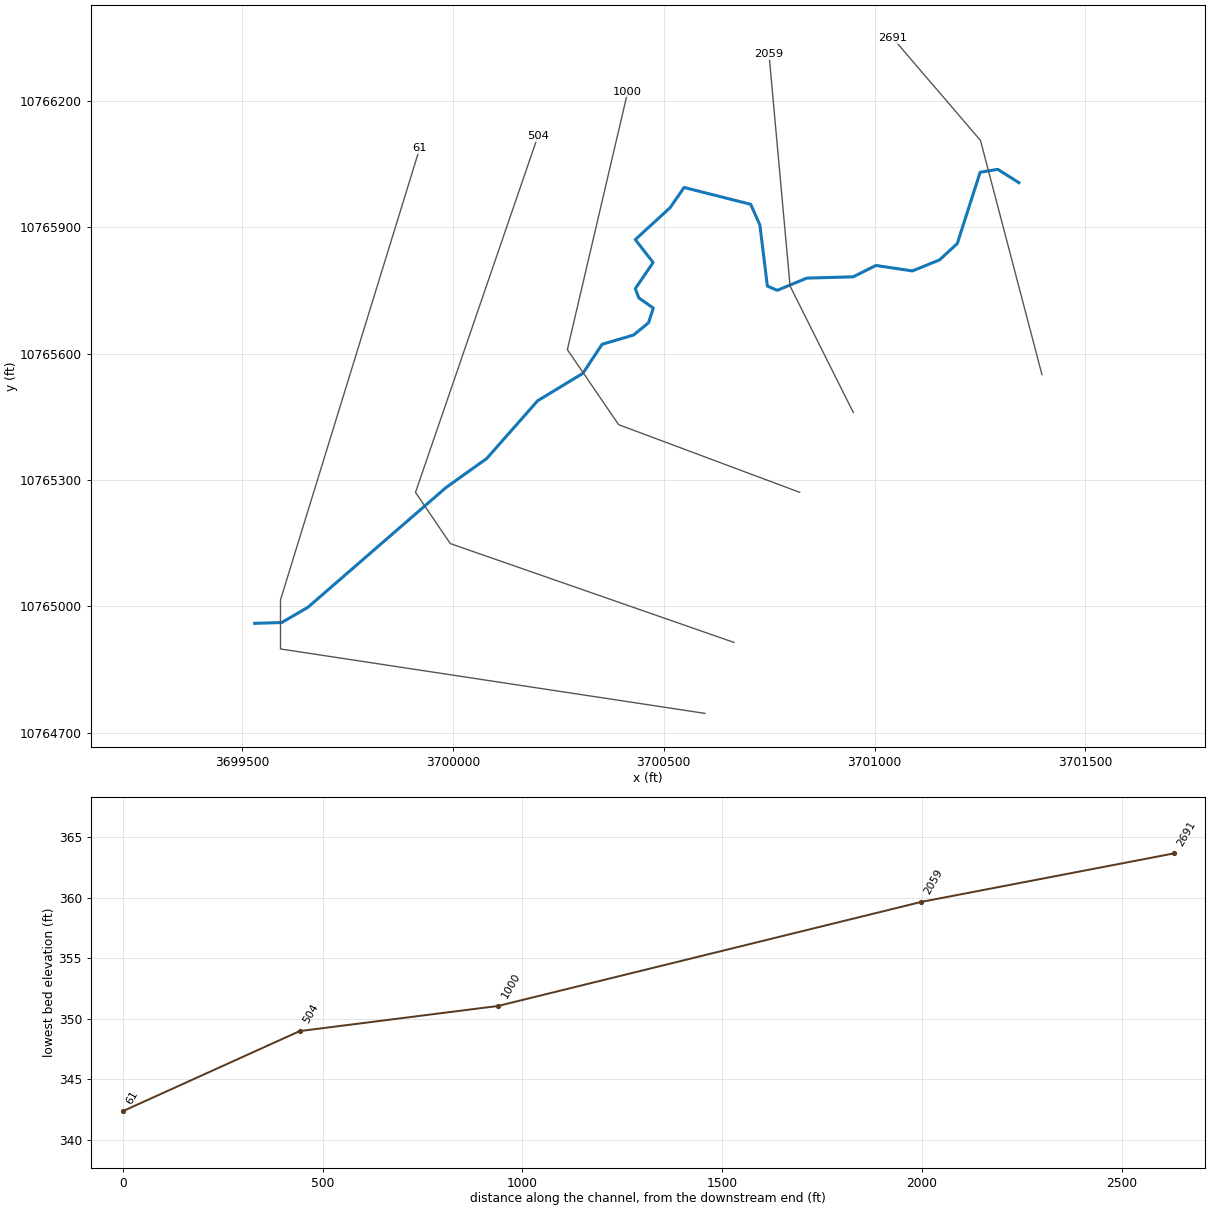
--- UNT 015 IN CACR.prj (project) ---

Proj Title=UNT 015 IN CACR Base Level Engineering
Current Plan=p01
Default Exp/Contr=0.3,0.1
English Units
Geom File=g01
Flow File=f01
Plan File=p01
BEGIN DESCRIPTION:
UNT 015 IN CACR
END DESCRIPTION:

--- UNT 015 IN CACR.p01 (plan) ---

Plan Title=Multiple Run
Short Identifier=Multiple
Geom File=g01
Flow File=f01
Subcritical Flow
K Sum by GR= 0
Std Step Tol= 0.01
Critical Tol= 0.01
Num of Std Step Trials= 20
Max Error Tol= 0.3
Flow Tol Ratio= 0.001
Split Flow NTrial= 30
Split Flow Tol= 0.02
Split Flow Ratio= 0.02
Log Output Level= 0
Friction Slope Method= 1
Unsteady Friction Slope Method= 2
Unsteady Bridges Friction Slope Method= 1
Parabolic Critical Depth
Global Vel Dist=  1 , 1 , 1
Global Log Level= 0
CheckData=True
Encroach Param= -1, 0, 0, 0
BEGIN DESCRIPTION:
Multiple Run
END DESCRIPTION:

--- UNT 015 IN CACR.f01 (steady flow) ---

Flow Title=Multiple
Number of Profiles=7
Profile Names=10-year,25-year,50-year,1pct_min,100-year,1pct_plu,500-year
River Rch & RM= UNT 015 IN CACR,Reach-1,2691
     660     900    1100     986    1334    1804    1964
Boundary for River Rch & Prof#=UNT 015 IN CACR,Reach-1,1
Up Type=0
Dn Type=3
Dn Slope=0.005
Boundary for River Rch & Prof#=UNT 015 IN CACR,Reach-1,2
Up Type=0
Dn Type=3
Dn Slope=0.005
Boundary for River Rch & Prof#=UNT 015 IN CACR,Reach-1,3
Up Type=0
Dn Type=3
Dn Slope=0.005
Boundary for River Rch & Prof#=UNT 015 IN CACR,Reach-1,4
Up Type=0
Dn Type=3
Dn Slope=0.005
Boundary for River Rch & Prof#=UNT 015 IN CACR,Reach-1,5
Up Type=0
Dn Type=3
Dn Slope=0.005
Boundary for River Rch & Prof#=UNT 015 IN CACR,Reach-1,6
Up Type=0
Dn Type=3
Dn Slope=0.005
Boundary for River Rch & Prof#=UNT 015 IN CACR,Reach-1,7
Up Type=0
Dn Type=3
Dn Slope=0.005

--- UNT 015 IN CACR.g01 (geometry) ---

Geom Title=Existing Conditions

River Reach=UNT 015 IN CACR,Reach-1
Reach XY= 30
      3701342.49     10766005.29      3701292.25     10766037.00
      3701250.50     10766030.00      3701196.25     10765861.00
      3701154.00     10765822.00      3701089.50     10765796.00
      3701003.25     10765809.00      3700949.25     10765782.00
      3700839.50     10765779.00      3700769.25     10765750.00
      3700745.75     10765760.00      3700728.00     10765905.00
      3700706.25     10765954.00      3700548.25     10765994.00
      3700515.00     10765946.00      3700432.44     10765870.39
      3700474.75     10765816.00      3700432.50     10765754.00
      3700440.75     10765732.00      3700475.25     10765708.00
      3700463.75     10765673.00      3700428.50     10765644.00
      3700353.75     10765622.00      3700308.00     10765553.00
      3700200.75     10765488.00      3700080.00     10765351.00
      3699983.25     10765282.00      3699655.75     10764998.00
      3699593.75     10764962.00      3699529.50     10764960.00

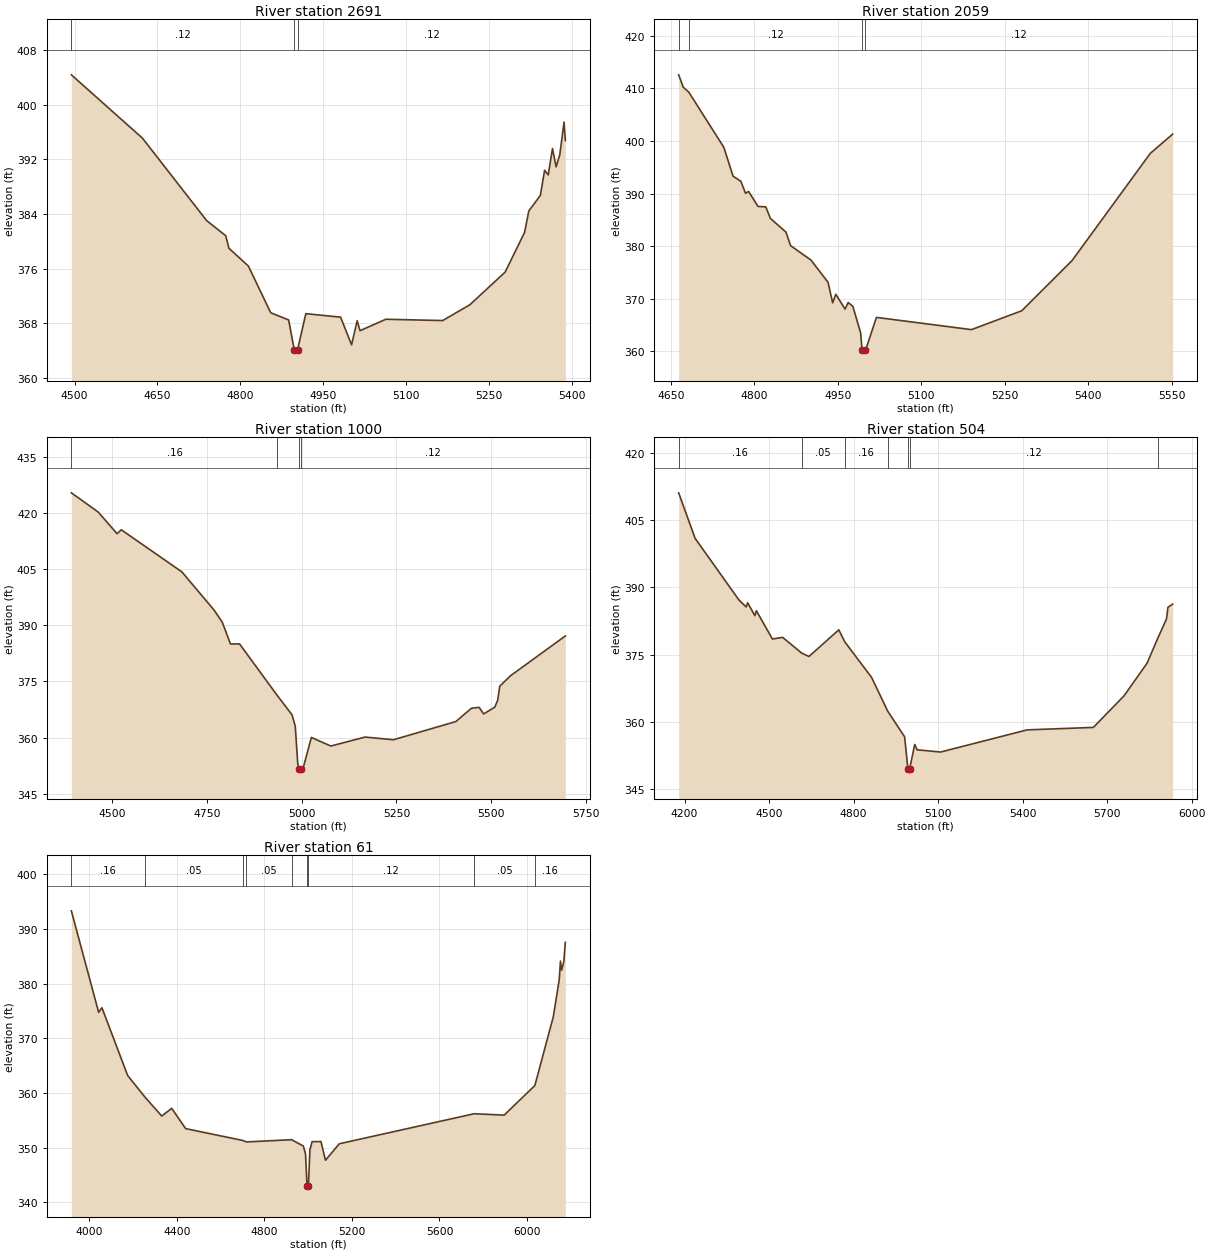
Type RM Length L Ch R = 1,2691,632,632,632
BEGIN DESCRIPTION:
UNT 015 IN CACR 5.0
END DESCRIPTION:
XS GIS Cut Line= 3
      3701397.08     10765550.12      3701251.25     10766105.69
      3701043.77     10766347.75
#Sta/Elev= 30
  4494.3  404.40  4622.9  395.12  4738.8  383.06  4773.5  380.83  4779.2  379.00
  4814.4  376.39  4854.8  369.55  4887.2  368.50  4897.3  364.14  4900.1  363.64
  4903.3  364.14  4918.3  369.42  4981.1  368.91  5001.0  364.86  5011.1  368.38
  5016.3  366.93  5063.0  368.60  5165.7  368.41  5215.0  370.73  5278.7  375.51
  5313.8  381.32  5321.5  384.46  5342.4  386.75  5350.0  390.42  5356.6  389.74
  5364.3  393.61  5370.9  390.92  5377.5  392.70  5385.2  397.48  5387.5  394.78
#Mann=3,-1,0
  4494.3    0.12       0  4897.3    0.07       0  4903.3    0.12       0
Bank Sta=4897.3,4903.3
Exp/Cntr=0.3,0.1

Type RM Length L Ch R = 1,2059,1059,1059,1059
BEGIN DESCRIPTION:
UNT 015 IN CACR 4.0
END DESCRIPTION:
XS GIS Cut Line= 3
      3700949.59     10765460.23      3700799.61     10765760.19
      3700749.61     10766310.16
#Sta/Elev= 30
  4664.2  412.59  4672.5  410.22  4682.3  409.31  4745.2  398.83  4762.0  393.30
  4776.0  392.33  4784.3  390.05  4789.9  390.40  4806.7  387.55  4820.7  387.47
  4829.1  385.26  4857.0  382.67  4865.4  380.08  4901.7  377.37  4932.5  373.14
  4940.9  369.22  4946.5  370.84  4963.2  368.02  4968.8  369.28  4977.2  368.53
  4991.2  363.50  4993.8  360.14  4996.5  359.64  4999.8  360.14  5019.6  366.44
  5190.3  364.11  5280.7  367.70  5371.1  377.25  5511.7  397.65  5551.8  401.30
#Mann=4,-1,0
  4664.2    0.16       0  4682.3    0.12       0  4993.8    0.07       0
  4999.8    0.12       0
Bank Sta=4993.8,4999.8
Exp/Cntr=0.3,0.1

Type RM Length L Ch R = 1,1000,496,496,496
BEGIN DESCRIPTION:
UNT 015 IN CACR 3.0
END DESCRIPTION:
XS GIS Cut Line= 4
      3700822.53     10765270.78      3700392.88     10765431.36
      3700271.36     10765609.31      3700414.59     10766221.31
#Sta/Elev= 30
  4392.7  425.37  4463.8  420.21  4513.3  414.45  4524.4  415.50  4684.1  404.27
  4769.5  394.01  4790.8  390.80  4812.2  385.03  4836.3  385.02  4936.2  371.19
  4974.8  366.08  4983.2  363.02  4989.7  353.13  4992.7  351.56  4995.5  351.06
  4998.7  351.56  5004.6  352.09  5025.6  360.05  5077.0  357.76  5167.1  360.15
  5242.4  359.44  5406.7  364.30  5447.8  367.85  5468.3  368.08  5479.9  366.32
  5509.4  368.15  5517.2  370.03  5522.4  373.72  5550.5  376.50  5695.4  387.15
#Mann=4,-1,0
  4392.7    0.16       0  4936.2    0.12       0  4992.7    0.07       0
  4998.7    0.12       0
Bank Sta=4992.7,4998.7
Exp/Cntr=0.3,0.1

Type RM Length L Ch R = 1,504,443,443,443
BEGIN DESCRIPTION:
UNT 015 IN CACR 2.0
END DESCRIPTION:
XS GIS Cut Line= 4
      3700666.32     10764914.87      3699993.58     10765149.24
      3699911.11     10765270.77      3700201.59     10766116.19
#Sta/Elev= 30
  4179.3  411.13  4237.6  400.97  4393.0  387.22  4418.8  385.65  4424.1  386.57
  4449.8  383.71  4455.1  384.80  4512.0  378.49  4548.4  378.85  4616.5  375.32
  4641.8  374.59  4747.7  380.54  4768.8  377.87  4864.1  369.90  4921.1  362.40
  4981.2  356.65  4993.1  349.49  4995.9  348.99  4999.1  349.49  5017.1  354.94
  5025.8  353.75  5108.8  353.25  5416.0  358.20  5651.2  358.75  5759.7  365.78
  5841.6  373.07  5879.9  378.68  5910.7  382.96  5915.9  385.57  5932.5  386.27
#Mann=7,-1,0
  4179.3    0.16       0  4616.5    0.05       0  4768.8    0.16       0
  4921.1    0.12       0  4993.1    0.07       0  4999.1    0.12       0
  5879.9    0.16       0
Bank Sta=4993.1,4999.1
Exp/Cntr=0.3,0.1

Type RM Length L Ch R = 1,61,0,0,0
BEGIN DESCRIPTION:
UNT 015 IN CACR 1.0
END DESCRIPTION:
XS GIS Cut Line= 4
      3700597.71     10764746.47      3699590.80     10764899.24
      3699590.80     10765015.56      3699921.03     10766086.87
#Sta/Elev= 30
  3918.9  393.33  4043.5  374.75  4058.6  375.58  4176.0  363.18  4256.9  359.14
  4331.7  355.76  4377.1  357.17  4440.8  353.46  4702.9  351.28  4718.6  351.02
  4924.7  351.43  4978.3  350.27  4988.3  348.83  4995.3  342.88  4998.0  342.38
  5001.3  342.88  5008.3  349.60  5018.3  351.07  5058.7  351.09  5079.4  347.67
  5142.2  350.68  5758.3  356.18  5895.6  355.93  6035.6  361.35  6119.8  373.94
  6146.8  380.70  6152.5  384.13  6157.7  382.46  6167.7  383.99  6174.7  387.56
#Mann=9,-1,0
  3918.9    0.16       0  4256.9    0.05       0  4702.9    0.16       0
  4718.6    0.05       0  4924.7    0.12       0  4995.3    0.07       0
  5001.3    0.12       0  5758.3    0.05       0  6035.6    0.16       0
Bank Sta=4995.3,5001.3
Exp/Cntr=0.3,0.1

Chan Stop Cuts=-1