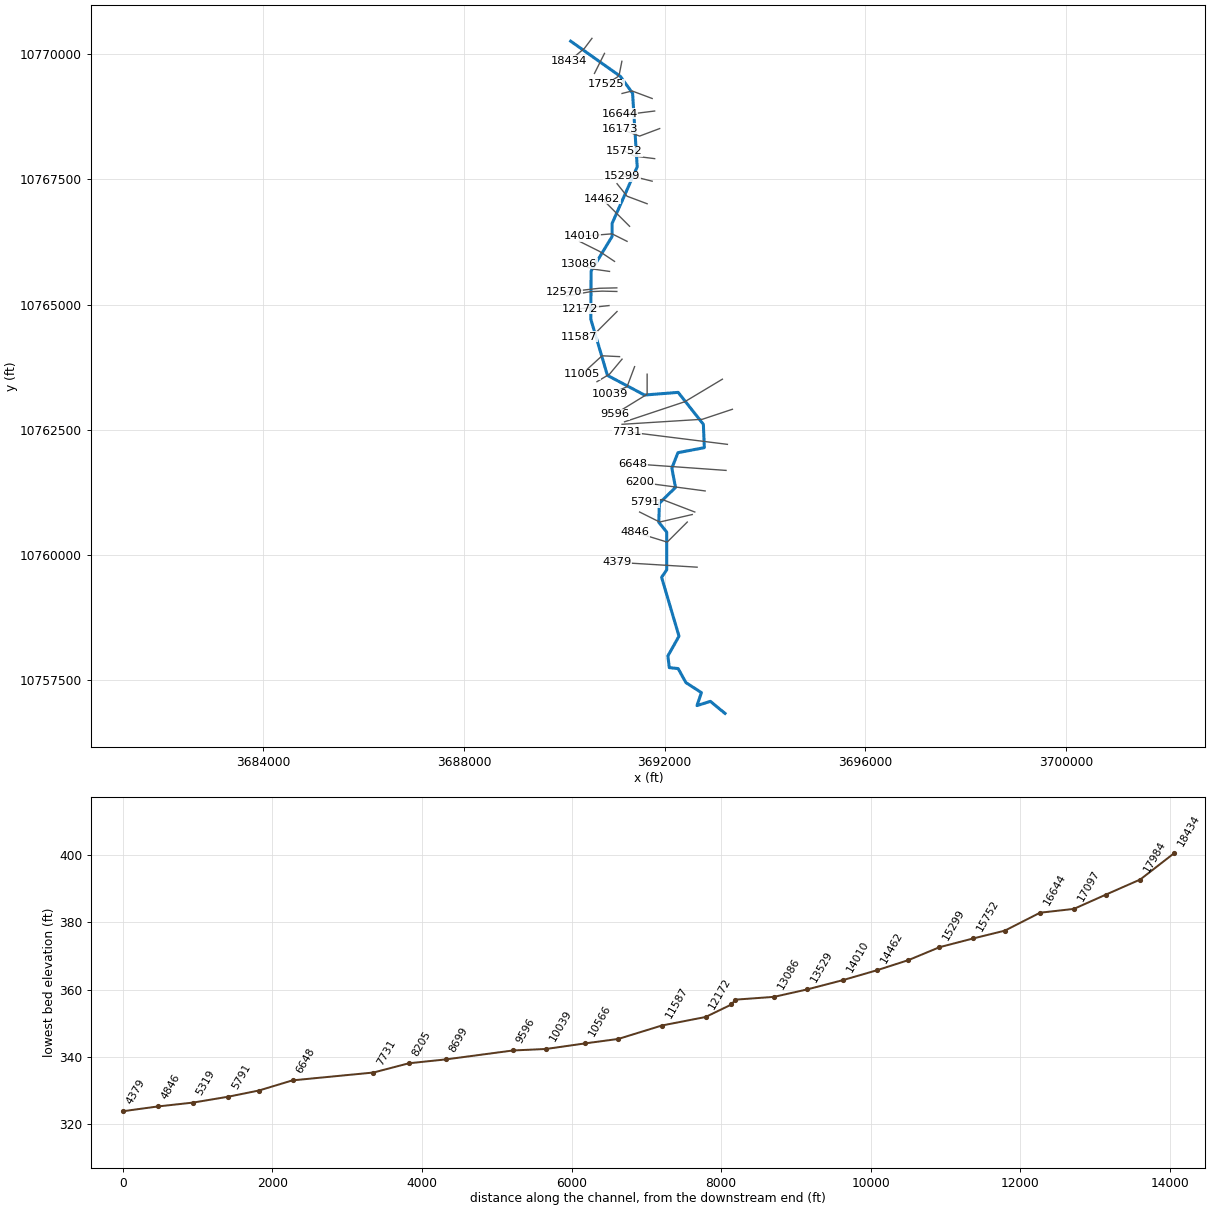
--- UNT 016 IN CACR.prj (project) ---

Proj Title=UNT 016 IN CACR Base Level Engineering
Current Plan=p01
Default Exp/Contr=0.3,0.1
English Units
Geom File=g01
Flow File=f01
Plan File=p01
Y Axis Title=Elevation
X Axis Title(PF)=Main Channel Distance
X Axis Title(XS)=Station
BEGIN DESCRIPTION:
UNT 016 IN CACR
END DESCRIPTION:
DSS Export Rating Curves= 0
DSS Export Rating Curve Sorted= 0
DSS Export Volume Flow Curves= 0
DXF OffsetX= 0
DXF OffsetY= 0
DXF ScaleX= 1
DXF ScaleY= 10

--- UNT 016 IN CACR.p01 (plan) ---

Plan Title=Multiple Run
Short Identifier=Multiple
Geom File=g01
Flow File=f01
Subcritical Flow
K Sum by GR= 0
Std Step Tol= 0.01
Critical Tol= 0.01
Num of Std Step Trials= 20
Max Error Tol= 0.3
Flow Tol Ratio= 0.001
Split Flow NTrial= 30
Split Flow Tol= 0.02
Split Flow Ratio= 0.02
Log Output Level= 0
Friction Slope Method= 1
Unsteady Friction Slope Method= 2
Unsteady Bridges Friction Slope Method= 1
Parabolic Critical Depth
Global Vel Dist=  1 , 1 , 1
Global Log Level= 0
CheckData=True
Encroach Param= -1, 0, 0, 0
BEGIN DESCRIPTION:
Multiple Run
END DESCRIPTION:

--- UNT 016 IN CACR.f01 (steady flow) ---

Flow Title=Multiple
Program Version=4.10
Number of Profiles= 7
Profile Names=10-year,25-year,50-year,1pct_min,100-year,1pct_plu,500-year
River Rch & RM=UNT 016 IN CACR,Reach-1         ,18434
     753    1044    1289    1169    1580    2137    2381
River Rch & RM=UNT 016 IN CACR,Reach-1         ,16644
     990    1387    1724    1571    2124    2873    3234
River Rch & RM=UNT 016 IN CACR,Reach-1         ,12172
    1228    1736    2170    1987    2687    3634    4131
River Rch & RM=UNT 016 IN CACR,Reach-1         ,8205
    1461    2077    2607    2394    3238    4379    5009
River Rch & RM=UNT 016 IN CACR,Reach-1         ,3658
    1674    2390    3006    2765    3739    5057    5805
Boundary for River Rch & Prof#=UNT 016 IN CACR,Reach-1         , 1
Up Type= 0
Dn Type= 3
Dn Slope=0.0001
Boundary for River Rch & Prof#=UNT 016 IN CACR,Reach-1         , 2
Up Type= 0
Dn Type= 3
Dn Slope=0.0001
Boundary for River Rch & Prof#=UNT 016 IN CACR,Reach-1         , 3
Up Type= 0
Dn Type= 3
Dn Slope=0.0001
Boundary for River Rch & Prof#=UNT 016 IN CACR,Reach-1         , 4
Up Type= 0
Dn Type= 3
Dn Slope=0.0001
Boundary for River Rch & Prof#=UNT 016 IN CACR,Reach-1         , 5
Up Type= 0
Dn Type= 3
Dn Slope=0.0001
Boundary for River Rch & Prof#=UNT 016 IN CACR,Reach-1         , 6
Up Type= 0
Dn Type= 3
Dn Slope=0.0001
Boundary for River Rch & Prof#=UNT 016 IN CACR,Reach-1         , 7
Up Type= 0
Dn Type= 3
Dn Slope=0.0001
DSS Import GetInterval= 0
DSS Import GetPeak= 0
DSS Import FillOption= 0

--- UNT 016 IN CACR.g01 (geometry) ---

Geom Title=Existing Conditions
Program Version=4.10

River Reach=UNT 016 IN CACR ,Reach-1
Reach XY= 30
      3690125.56     10770253.39      3691115.25       10769552.
      3691359.25       10769215.      3691451.75       10767747.
      3690951.75       10766619.        3690950.       10766355.
       3690532.5       10765669.        3690527.       10764706.
        3690858.       10763586.       3691596.5       10763194.
       3692268.5       10763247.      3692770.75       10762609.
        3692790.       10762144.      3692263.75       10762044.
      3692142.25       10761735.      3692214.75       10761351.
        3691894.       10761035.       3691881.5       10760656.
       3692039.5       10760460.       3692039.5       10759707.
        3691938.       10759557.      3692284.75       10758383.
       3692063.5       10757989.      3692090.75       10757756.
       3692267.5       10757737.      3692423.25       10757456.
      3692731.75       10757257.        3692643.       10756998.
      3692909.75       10757083.      3693201.75       10756843.

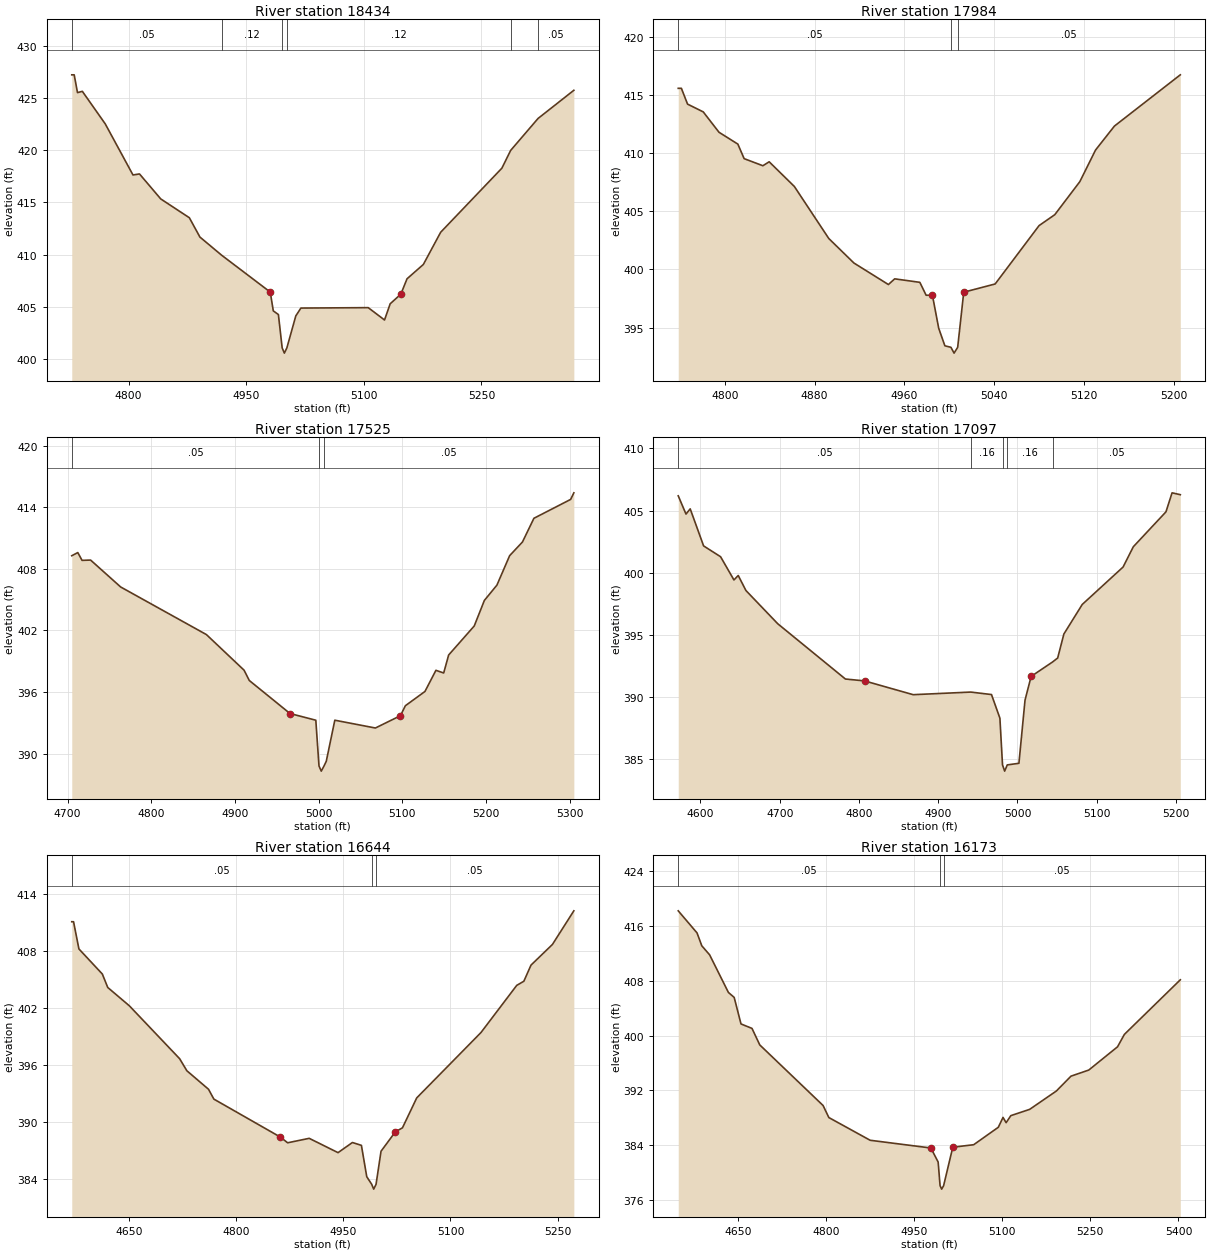
Type RM Length L Ch R = 1 ,18434   ,450,450,450
BEGIN DESCRIPTION:
UNT 016 IN CACR 38.0
END DESCRIPTION:
XS GIS Cut Line= 3
      3690549.59     10770310.16      3690399.61     10770110.19
       3690099.6     10769860.18
#Sta/Elev= 30
  4727.4   427.2  4730.5   427.2  4734.7   425.5  4740.9  425.62  4770.1  422.51
  4805.5  417.62  4813.8  417.72  4840.9  415.33  4877.4  413.53  4890.9  411.68
  4918.7  409.94  4980.6  406.42  4984.5  404.62    4991  404.27  4995.8  401.08
  4998.6  400.58  5001.8  401.08  5013.2  404.14  5019.7  404.89  5105.6  404.93
  5126.4  403.75  5133.6   405.3  5147.2  406.22  5155.1  407.69  5175.9  409.06
    5198  412.14  5276.1  418.27  5287.3  419.97  5322.3  423.03  5367.9  425.72
#Mann= 6 ,-1 , 0
  4727.4     .05       0  4918.7     .12       0  4995.8     .07       0
  5001.8     .12       0  5287.3     .16       0  5322.3     .05       0
Bank Sta=4980.6,5147.2
XS Rating Curve= 0 ,0
Exp/Cntr=0.3,0.1

Type RM Length L Ch R = 1 ,17984   ,459,459,459
BEGIN DESCRIPTION:
UNT 016 IN CACR 37.0
END DESCRIPTION:
XS GIS Cut Line= 3
      3690799.59     10770010.15      3690699.61     10769810.19
       3690599.6     10769610.16
#Sta/Elev= 30
  4758.5  415.58  4761.3  415.58  4766.8  414.22  4780.8  413.55  4794.8   411.8
  4811.6  410.78  4817.2  409.53  4833.9  408.92  4839.5  409.26  4861.9  407.14
  4892.6  402.66    4915  400.55  4945.7   398.7  4951.3  399.19  4973.7  398.89
  4979.3  397.78  4984.9  397.78  4990.5  394.94    4996  393.43  5001.4   393.3
  5004.2   392.8  5007.4   393.3  5012.8  398.04  5040.8  398.75  5079.9  403.77
  5093.9  404.71  5116.2  407.55  5130.2  410.27    5147  412.33  5205.7  416.74
#Mann= 3 ,-1 , 0
  4758.5     .05       0  5001.4     .03       0  5007.4     .05       0
Bank Sta=4984.9,5012.8
XS Rating Curve= 0 ,0
Exp/Cntr=0.3,0.1

Type RM Length L Ch R = 1 ,17525   ,428,428,428
BEGIN DESCRIPTION:
UNT 016 IN CACR 36.0
END DESCRIPTION:
XS GIS Cut Line= 4
        3691146.     10769852.22      3691096.52     10769602.23
      3691062.67     10769542.33      3690829.27     10769394.52
#Sta/Elev= 30
    4705  409.28  4712.2  409.59  4717.3  408.83  4727.5  408.86  4763.4  406.24
  4865.9   401.6  4910.9  398.13  4917.1  397.13  4965.8  393.91  4996.6  393.26
  5000.4   388.8  5003.1   388.3  5006.4   388.8  5009.1  389.26  5019.3  393.26
  5067.8   392.5  5097.7   393.7  5103.6  394.67    5127  396.06  5140.1  398.12
  5149.4  397.86  5155.3  399.61  5185.9  402.44    5198  404.93    5213  406.42
  5228.2  409.29  5243.5  410.62  5257.2  412.93  5301.1  414.77  5304.9  415.41
#Mann= 3 ,-1 , 0
    4705     .05       0  5000.4     .03       0  5006.4     .05       0
Bank Sta=4965.8,5097.7
XS Rating Curve= 0 ,0
Exp/Cntr=0.3,0.1

Type RM Length L Ch R = 1 ,17097   ,453,453,453
BEGIN DESCRIPTION:
UNT 016 IN CACR 35.0
END DESCRIPTION:
XS GIS Cut Line= 3
      3691749.61     10769110.19      3691349.61     10769260.19
      3691149.57     10769210.18
#Sta/Elev= 30
    4572  406.19  4581.8  404.72  4587.1  405.14    4604  402.16  4625.4  401.29
  4642.3  399.42  4647.7  399.78  4657.4  398.57  4697.5   395.9  4782.9  391.45
    4807   391.3  4868.4  390.19  4941.1   390.4  4967.2   390.2  4977.8   388.3
  4981.1  384.54  4983.8  384.04  4987.1  384.54  5001.8  384.67  5009.5  389.75
  5017.2  391.66  5044.2  392.82  5050.7  393.14  5058.5  395.07  5081.7  397.45
  5133.2  400.46  5146.1  402.09  5187.3   404.9    5195  406.43  5205.4  406.28
#Mann= 5 ,-1 , 0
    4572     .05       0  4941.1     .16       0  4981.1     .07       0
  4987.1     .16       0  5044.2     .05       0
Bank Sta=4807,5017.2
XS Rating Curve= 0 ,0
Exp/Cntr=0.3,0.1

Type RM Length L Ch R = 1 ,16644   ,471,471,471
BEGIN DESCRIPTION:
UNT 016 IN CACR 34.0
END DESCRIPTION:
XS GIS Cut Line= 3
      3691799.58     10768860.19      3691399.61     10768810.19
      3691099.59     10768810.19
#Sta/Elev= 30
  4569.7  411.12  4572.2  411.12  4579.7  408.25  4612.5   405.6  4620.1  404.18
  4650.3  402.25  4720.8  396.66  4730.9  395.39  4761.2  393.44  4768.7   392.4
  4861.9  388.39    4872  387.79  4902.2  388.26  4942.6  386.75  4962.7  387.82
  4975.3  387.52  4982.8  384.21  4989.8   383.4  4992.5   382.9  4995.8   383.4
  5002.8   386.9  5022.8  388.94  5032.8  389.37  5052.8  392.53  5142.8  399.43
  5192.8   404.4  5202.8  404.84  5212.8  406.54  5242.8  408.72  5272.8  412.27
#Mann= 3 ,-1 , 0
  4569.7     .05       0  4989.8     .03       0  4995.8     .05       0
Bank Sta=4861.9,5022.8
XS Rating Curve= 0 ,0
Exp/Cntr=0.3,0.1

Type RM Length L Ch R = 1 ,16173   ,421,421,421
BEGIN DESCRIPTION:
UNT 016 IN CACR 33.0
END DESCRIPTION:
XS GIS Cut Line= 3
      3691899.61     10768510.19      3691499.61     10768360.19
      3691099.61     10768510.19
#Sta/Elev= 30
  4548.7  418.22  4580.7  414.99  4588.8  413.11  4602.1  411.79  4634.1  406.29
  4643.9  405.57  4655.5  401.69  4674.2  401.04  4687.5  398.62  4795.2  389.77
    4805  388.01  4875.3  384.69  4978.6  383.56    4991  381.51  4994.3  378.05
    4997  377.55  5000.3  378.05  5015.9  383.67  5051.5  384.04  5093.4  386.59
  5101.4  388.03  5106.7  387.26  5114.7  388.29  5146.8  389.21  5192.2  391.89
  5217.1  394.06  5247.3  394.95  5296.3  398.35  5307.9  400.16  5403.1  408.14
#Mann= 3 ,-1 , 0
  4548.7     .05       0  4994.3     .03       0  5000.3     .05       0
Bank Sta=4978.6,5015.9
XS Rating Curve= 0 ,0
Exp/Cntr=0.3,0.1

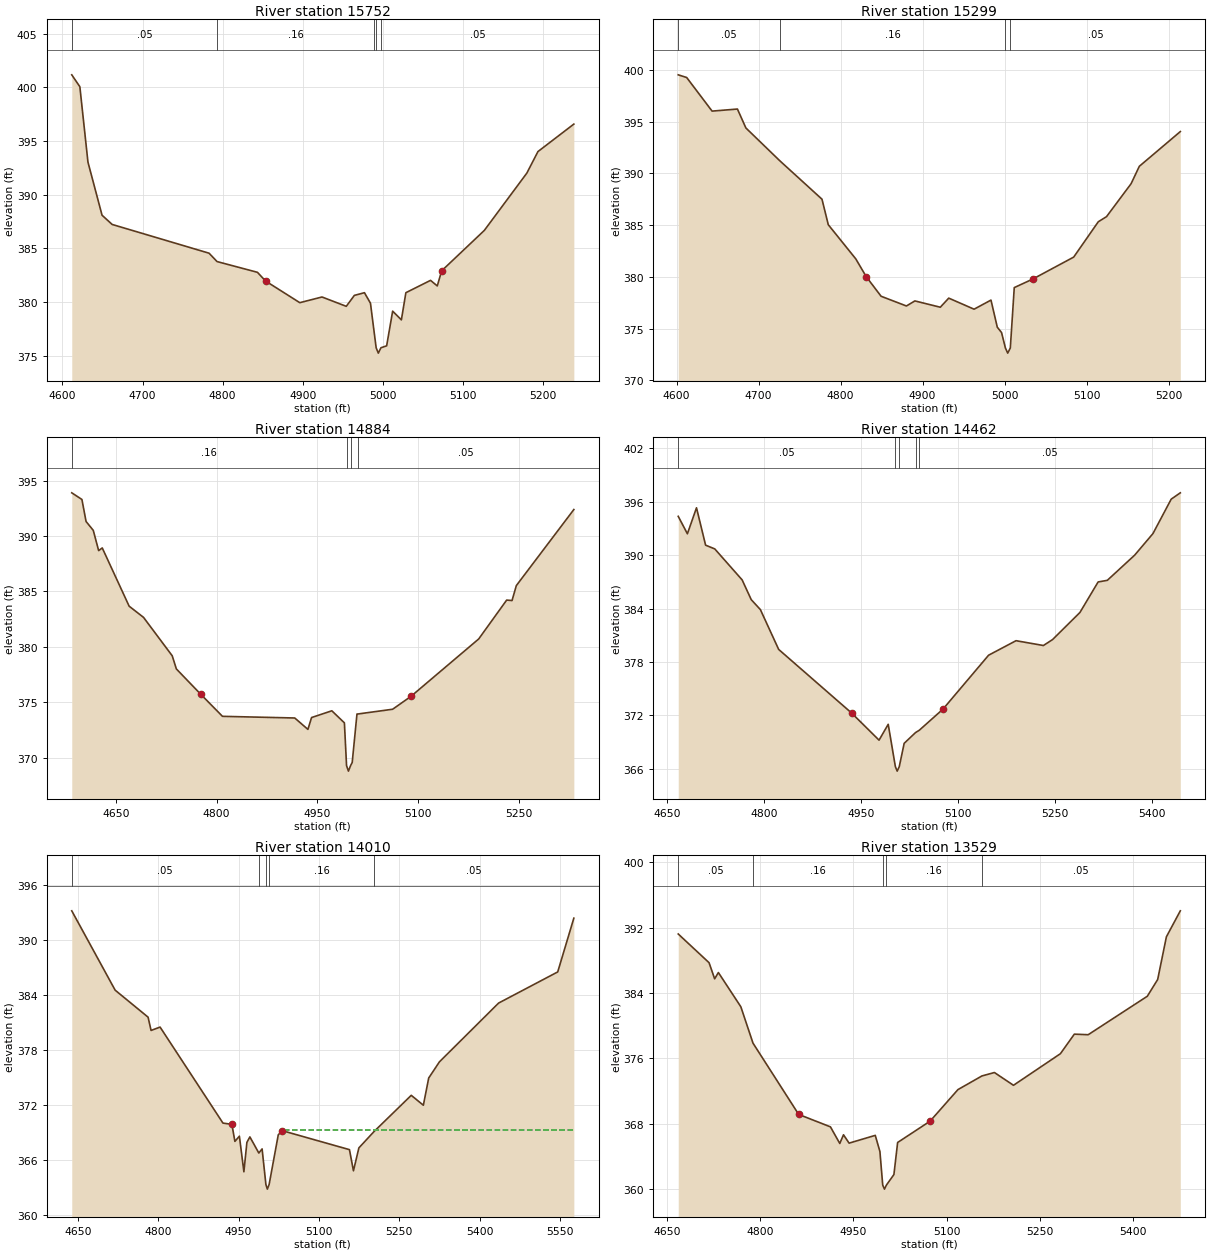
Type RM Length L Ch R = 1 ,15752   ,453,453,453
BEGIN DESCRIPTION:
UNT 016 IN CACR 32.0
END DESCRIPTION:
XS GIS Cut Line= 3
      3691799.64     10767910.18      3691399.61     10767960.19
      3691199.57     10768060.21
#Sta/Elev= 30
  4611.7  401.17  4621.8  400.06  4631.9  393.04  4649.5  388.09  4662.1  387.23
  4783.1  384.55  4793.1  383.77  4843.5  382.77  4853.6  381.96  4896.4  379.94
  4924.1  380.47  4954.4   379.6  4964.5  380.62  4977.1  380.87  4984.6  379.89
  4988.7  377.49  4991.7  375.74  4994.4  375.24  4997.7  375.74  5004.8  375.92
  5012.3  379.15  5023.2  378.34  5028.8  380.87  5059.6  382.02    5068   381.5
  5073.5  382.91  5126.7  386.67  5179.8  392.01  5193.7  394.02  5238.5  396.58
#Mann= 5 ,-1 , 0
  4611.7     .05       0  4793.1     .16       0  4988.7     .05       0
  4991.7     .03       0  4997.7     .05       0
Bank Sta=4853.6,5073.5
XS Rating Curve= 0 ,0
Exp/Cntr=0.3,0.1

Type RM Length L Ch R = 1 ,15299   ,415,415,415
BEGIN DESCRIPTION:
UNT 016 IN CACR 31.0
END DESCRIPTION:
XS GIS Cut Line= 3
      3691749.63     10767460.18      3691349.61     10767560.19
      3691149.64     10767560.19
#Sta/Elev= 30
    4602  399.54  4612.3  399.28  4643.3  396.03  4674.2  396.23  4684.5   394.4
  4726.1  391.21  4777.3  387.51    4785  385.04  4818.5  381.74  4831.4     380
  4849.4  378.12  4880.3  377.18  4890.6  377.67  4921.6  377.06  4931.9  377.94
  4962.8  376.87  4983.4  377.75  4991.1  375.13  4996.3  374.61    5001  373.12
  5003.8  372.62    5007  373.12  5011.8  378.96  5034.3  379.78  5084.3  381.91
  5114.3  385.33  5124.3  385.82  5154.3  389.01  5164.3  390.69  5214.3  394.05
#Mann= 4 ,-1 , 0
    4602     .05       0  4726.1     .16       0    5001     .07       0
    5007     .05       0
Bank Sta=4831.4,5034.3
XS Rating Curve= 0 ,0
Exp/Cntr=0.3,0.1

Type RM Length L Ch R = 1 ,14884   ,422,422,422
BEGIN DESCRIPTION:
UNT 016 IN CACR 30.0
END DESCRIPTION:
XS GIS Cut Line= 3
      3691649.58      10767010.2      3691249.61     10767160.19
      3691049.63     10767410.17
#Sta/Elev= 30
  4584.4  393.91  4599.5  393.31  4605.7  391.32  4616.4  390.52  4624.4  388.69
  4629.8  388.93  4669.8  383.67  4691.2  382.66  4733.9  379.19  4740.1     378
  4776.6   375.7  4808.7  373.72  4916.3  373.57  4935.9  372.54  4941.3  373.61
  4971.5  374.22  4990.2  373.13  4993.4  369.27  4996.2  368.77  4999.4  369.27
  5001.8  369.55  5008.9  373.93  5010.1  373.93    5062  374.36  5089.2  375.52
  5190.1  380.71  5231.7  384.22  5239.7  384.18  5246.1  385.53  5331.7   392.4
#Mann= 4 ,-1 , 0
  4584.4     .16       0  4993.4     .07       0  4999.4     .16       0
  5010.1     .05       0
Bank Sta=4776.6,5089.2
XS Rating Curve= 0 ,0
Exp/Cntr=0.3,0.1

Type RM Length L Ch R = 1 ,14462   ,452,452,452
BEGIN DESCRIPTION:
UNT 016 IN CACR 29.0
END DESCRIPTION:
XS GIS Cut Line= 3
      3691299.62     10766560.18      3691049.61     10766810.19
      3690749.63     10767110.17
#Sta/Elev= 30
  4666.7  394.36  4680.9   392.4    4695  395.32  4709.1  391.12  4723.3   390.7
  4765.7  387.22  4779.8     385    4794  383.88  4822.3  379.41  4935.4  372.26
  4977.8  369.22    4992     371  5003.1  366.24  5005.9  365.74  5009.1  366.24
  5016.7  368.86  5034.3  370.07  5040.1  370.33  5076.8   372.7  5147.5  378.76
    5190  380.39  5232.4  379.85  5246.5  380.51    5289  383.56  5317.2  386.99
  5331.4  387.17  5373.8     390  5402.1  392.42  5430.4  396.29  5444.5     397
#Mann= 5 ,-1 , 0
  4666.7     .05       0  5003.1     .03       0  5009.1     .05       0
  5034.3     .16       0  5040.1     .05       0
Bank Sta=4935.4,5076.8
XS Rating Curve= 0 ,0
Exp/Cntr=0.3,0.1

Type RM Length L Ch R = 1 ,14010   ,481,481,481
BEGIN DESCRIPTION:
UNT 016 IN CACR 28.0
END DESCRIPTION:
XS GIS Cut Line= 3
      3691249.58      10766260.2      3690949.61     10766410.19
      3690349.57     10766360.19
#Sta/Elev= 30
  4638.6   393.2  4719.6  384.54  4781.1  381.59  4786.7  380.14  4803.5  380.51
  4920.9  370.03  4937.6  369.89  4943.2  368.03  4951.6   368.6    4960  364.71
  4965.6  367.92  4971.2  368.52  4987.9  366.76    4994  367.21  5001.1  363.32
  5003.8  362.82  5007.1  363.32  5024.2  368.75  5031.7   369.2  5157.1  367.13
  5164.6  364.82  5174.7  367.32  5202.9   369.1  5272.5  373.06  5295.1  371.98
  5305.1  374.95  5325.2  376.72  5435.6  383.13    5546  386.53  5576.1   392.4
#Mann= 5 ,-1 , 0
  4638.6     .05       0  4987.9     .16       0  5001.1     .07       0
  5007.1     .16       0  5202.9     .05       0
#XS Ineff= 2 , 0
                         5039.29          369.24
Permanent Ineff=
       F       F
Bank Sta=4937.6,5031.7
XS Rating Curve= 0 ,0
Exp/Cntr=0.3,0.1

Type RM Length L Ch R = 1 ,13529   ,443,443,443
BEGIN DESCRIPTION:
UNT 016 IN CACR 27.0
END DESCRIPTION:
XS GIS Cut Line= 3
      3690999.61     10765860.19      3690699.61     10766060.19
      3690299.58      10766260.2
#Sta/Elev= 30
  4668.3  391.21  4717.9   387.7  4726.9  385.73  4732.9   386.5    4769  382.32
  4788.6  377.87  4862.1  369.16  4913.2  367.64  4928.2  365.61  4934.2  366.67
  4943.2  365.65  4985.3   366.6  4992.8  364.62  4997.3  360.53  5000.1  360.03
  5003.3  360.53  5015.3  361.81  5021.3  365.73  5073.6  368.34  5118.3  372.19
  5156.9  373.86    5177  374.28  5207.7  372.72  5283.2  376.58  5305.6  378.97
  5327.9   378.9    5423   383.6  5439.7  385.65  5453.7  390.86  5476.1  394.04
#Mann= 5 ,-1 , 0
  4668.3     .05       0  4788.6     .16       0  4997.3     .07       0
  5003.3     .16       0  5156.9     .05       0
Bank Sta=4862.1,5073.6
XS Rating Curve= 0 ,0
Exp/Cntr=0.3,0.1

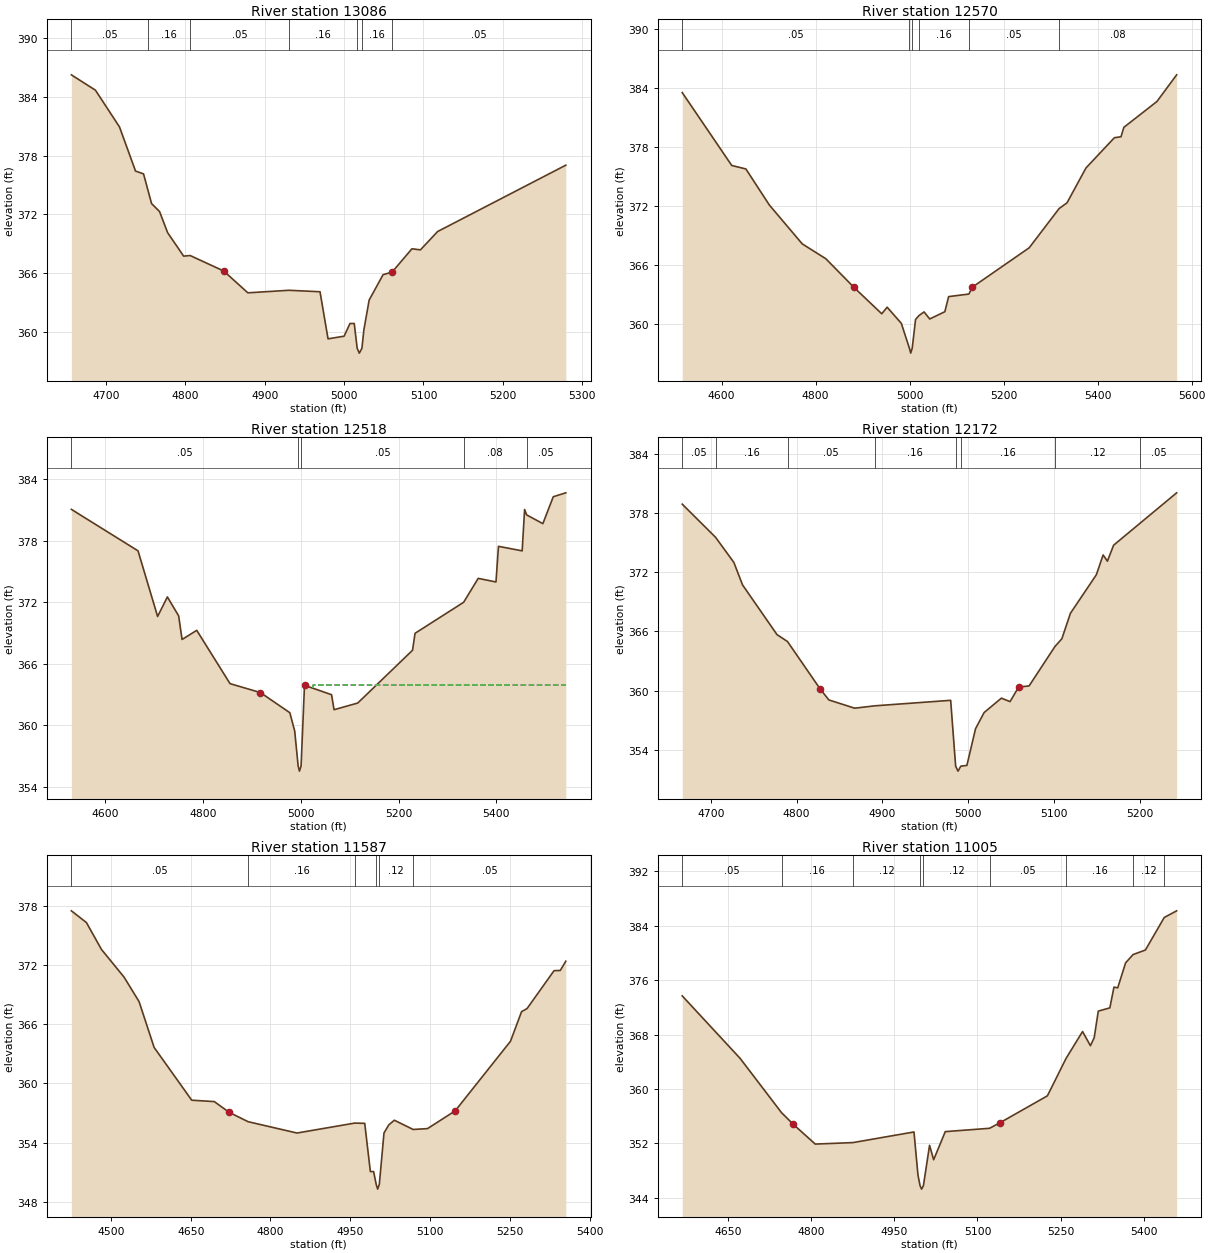
Type RM Length L Ch R = 1 ,13086   ,516,516,516
BEGIN DESCRIPTION:
UNT 016 IN CACR 26.0
END DESCRIPTION:
XS GIS Cut Line= 3
      3690899.63     10765660.19      3690549.61     10765710.19
      3690299.64     10765810.18
#Sta/Elev= 30
  4656.5  386.25  4686.8  384.68  4717.1  380.93  4737.3  376.42  4747.4  376.13
  4752.4  374.63  4757.5   373.1  4767.6  372.28  4777.7  370.13  4797.9  367.73
  4806.1  367.79  4848.4  366.21  4878.8  363.98  4930.4  364.24  4969.7  364.09
  4979.8  359.28    5000  359.55  5007.5  360.85  5012.8  360.85  5016.5  358.32
  5019.2  357.82  5022.5  358.32  5024.9  360.18  5031.6  363.24  5049.1  365.83
  5060.5   366.1  5085.5  368.48  5096.2  368.37  5117.8  370.24  5279.3  377.02
#Mann= 7 ,-1 , 0
  4656.5     .05       0  4752.4     .16       0  4806.1     .05       0
  4930.4     .16       0  5016.5     .07       0  5022.5     .16       0
  5060.5     .05       0
Bank Sta=4848.4,5060.5
XS Rating Curve= 0 ,0
Exp/Cntr=0.3,0.1

Type RM Length L Ch R = 1 ,12570   ,52,52,52
BEGIN DESCRIPTION:
Mapping XS 1c44a775
END DESCRIPTION:
XS GIS Cut Line= 4
      3691044.99     10765331.83      3690696.06     10765324.02
      3690487.72     10765300.58      3689998.14     10765240.68
#Sta/Elev= 30
  4516.2  383.54  4621.6  376.11  4651.6  375.76  4701.6  372.08  4771.6  368.12
  4821.7  366.61  4881.8  363.68  4940.7     361  4952.2  361.67  4982.4  360.02
  4999.5  357.49  5002.3  356.99  5005.5  357.49  5012.6  360.42  5020.2  360.83
  5030.7  361.19  5042.8  360.47  5074.9  361.21    5083  362.75  5126.1  363.01
  5133.4  363.71  5254.3  367.72    5318  371.72  5334.9  372.31  5375.2  375.86
  5435.6  378.94  5449.7  379.04  5455.8     380  5526.1  382.63  5568.1  385.35
#Mann= 6 ,-1 , 0
  4516.2     .05       0  4999.5     .03       0  5005.5     .05       0
  5020.2     .16       0  5126.1     .05       0    5318     .08       0
Bank Sta=4881.8,5133.4
XS Rating Curve= 0 ,0
Exp/Cntr=0.3,0.1

Type RM Length L Ch R = 1 ,12518   ,346,346,346
BEGIN DESCRIPTION:
UNT 016 IN CACR 25.0
END DESCRIPTION:
XS GIS Cut Line= 4
      3691045.74     10765259.95      3690757.52      10765266.9
      3690521.41     10765256.48      3690043.43     10765169.89
#Sta/Elev= 30
  4531.5  381.04  4667.7     377  4707.7  370.61  4727.7  372.51  4750.7  370.67
  4757.7  368.37  4787.7  369.26  4855.7  364.07  4917.8   363.2  4977.9  361.24
  4987.9  359.45  4994.9  356.05  4997.6  355.55  5000.9  356.05  5007.9  363.91
  5063.2  362.99  5068.3  361.53  5116.7  362.18  5228.7  367.32  5233.8  368.97
  5333.1  371.99  5362.9  374.32  5399.2  373.97  5404.3  377.44  5452.7     377
  5457.7  381.03  5461.9   380.5    5495  379.65  5516.3  382.27  5541.9  382.65
#Mann= 5 ,-1 , 0
  4531.5     .05       0  4994.9     .04       0  5000.9     .05       0
  5333.1     .08       0  5461.9     .05       0
#XS Ineff= 2 , 0
                         5024.53          363.97
Permanent Ineff=
       F       F
Bank Sta=4917.8,5007.9
XS Rating Curve= 0 ,0
Exp/Cntr=0.3,0.1

Type RM Length L Ch R = 1 ,12172   ,585,585,585
BEGIN DESCRIPTION:
UNT 016 IN CACR 24.0
END DESCRIPTION:
XS GIS Cut Line= 2
      3690889.45      10764978.7      3690316.55     10764916.21
#Sta/Elev= 30
  4666.8  378.93  4705.7  375.56    4727  373.01  4737.1  370.73  4777.3  365.68
  4789.5  364.98  4827.6  360.16  4837.7  359.05  4867.8  358.21  4891.1  358.45
  4979.7  359.01  4985.5  352.32  4988.3  351.82  4991.5  352.32  4998.6   352.4
  5008.7  356.13  5018.7  357.77  5038.8  359.23  5048.9  358.88    5059  360.36
  5071.1  360.47  5101.2  364.47  5109.3  365.26  5119.3  367.85  5149.5  371.76
  5157.4  373.77  5162.4  373.14  5169.6  374.76  5200.4  376.99  5243.1  380.08
#Mann= 8 ,-1 , 0
  4666.8     .05       0  4705.7     .16       0  4789.5     .05       0
  4891.1     .16       0  4985.5     .07       0  4991.5     .16       0
  5101.2     .12       0  5200.4     .05       0
Bank Sta=4827.6,5059
XS Rating Curve= 0 ,0
Exp/Cntr=0.3,0.1

Type RM Length L Ch R = 1 ,11587   ,582,582,582
BEGIN DESCRIPTION:
UNT 016 IN CACR 23.0
END DESCRIPTION:
XS GIS Cut Line= 3
      3691049.64     10764860.22      3690649.61     10764460.19
      3690299.64      10764360.2
#Sta/Elev= 30
  4425.6  377.51  4453.9  376.32  4482.2  373.59  4524.6  370.79  4552.9   368.3
  4581.2  363.65  4651.9   358.3  4694.3  358.16  4722.6  357.06  4757.9  356.12
  4849.9  354.97  4958.4  355.98  4977.2  355.95  4987.8  351.06  4993.9  351.06
  4998.7  349.78  5001.5  349.28  5004.7  349.78  5013.4  354.97  5022.5   355.8
  5032.9  356.27  5068.3  355.33  5095.3  355.42  5147.3  357.22  5251.3  364.28
  5272.1  367.28  5282.5   367.6  5333.2  371.44  5344.9  371.46  5355.3   372.4
#Mann= 6 ,-1 , 0
  4425.6     .05       0  4757.9     .16       0  4958.4     .12       0
  4998.7     .07       0  5004.7     .12       0  5068.3     .05       0
Bank Sta=4722.6,5147.3
XS Rating Curve= 0 ,0
Exp/Cntr=0.3,0.1

Type RM Length L Ch R = 1 ,11005   ,439,439,439
BEGIN DESCRIPTION:
UNT 016 IN CACR 22.0
END DESCRIPTION:
XS GIS Cut Line= 3
      3691099.56     10763960.19      3690750.57     10763976.97
      3690349.61     10763610.19
#Sta/Elev= 30
  4566.9  373.68  4671.5  364.49  4746.2  356.52  4767.1  354.83  4807.1   351.9
  4875.2  352.12  4985.4  353.68  4992.6  347.34  4996.4  345.78  4999.1  345.28
  5002.4  345.78  5013.5  351.72  5020.9   349.6  5041.9  353.73  5121.9  354.22
  5141.2  355.06  5226.3  358.99    5260  364.49  5289.8  368.44    5304  366.36
  5310.8  367.53  5318.2  371.44  5339.1  371.92  5346.5  374.97  5353.3  374.86
  5367.5  378.53    5381  379.75  5403.3  380.42  5437.3   385.2  5459.7  386.18
#Mann= 9 ,-1 , 0
  4566.9     .05       0  4746.2     .16       0  4875.2     .12       0
  4996.4     .07       0  5002.4     .12       0  5121.9     .05       0
    5260     .16       0    5381     .12       0  5437.3     .16       0
Bank Sta=4767.1,5141.2
XS Rating Curve= 0 ,0
Exp/Cntr=0.3,0.1

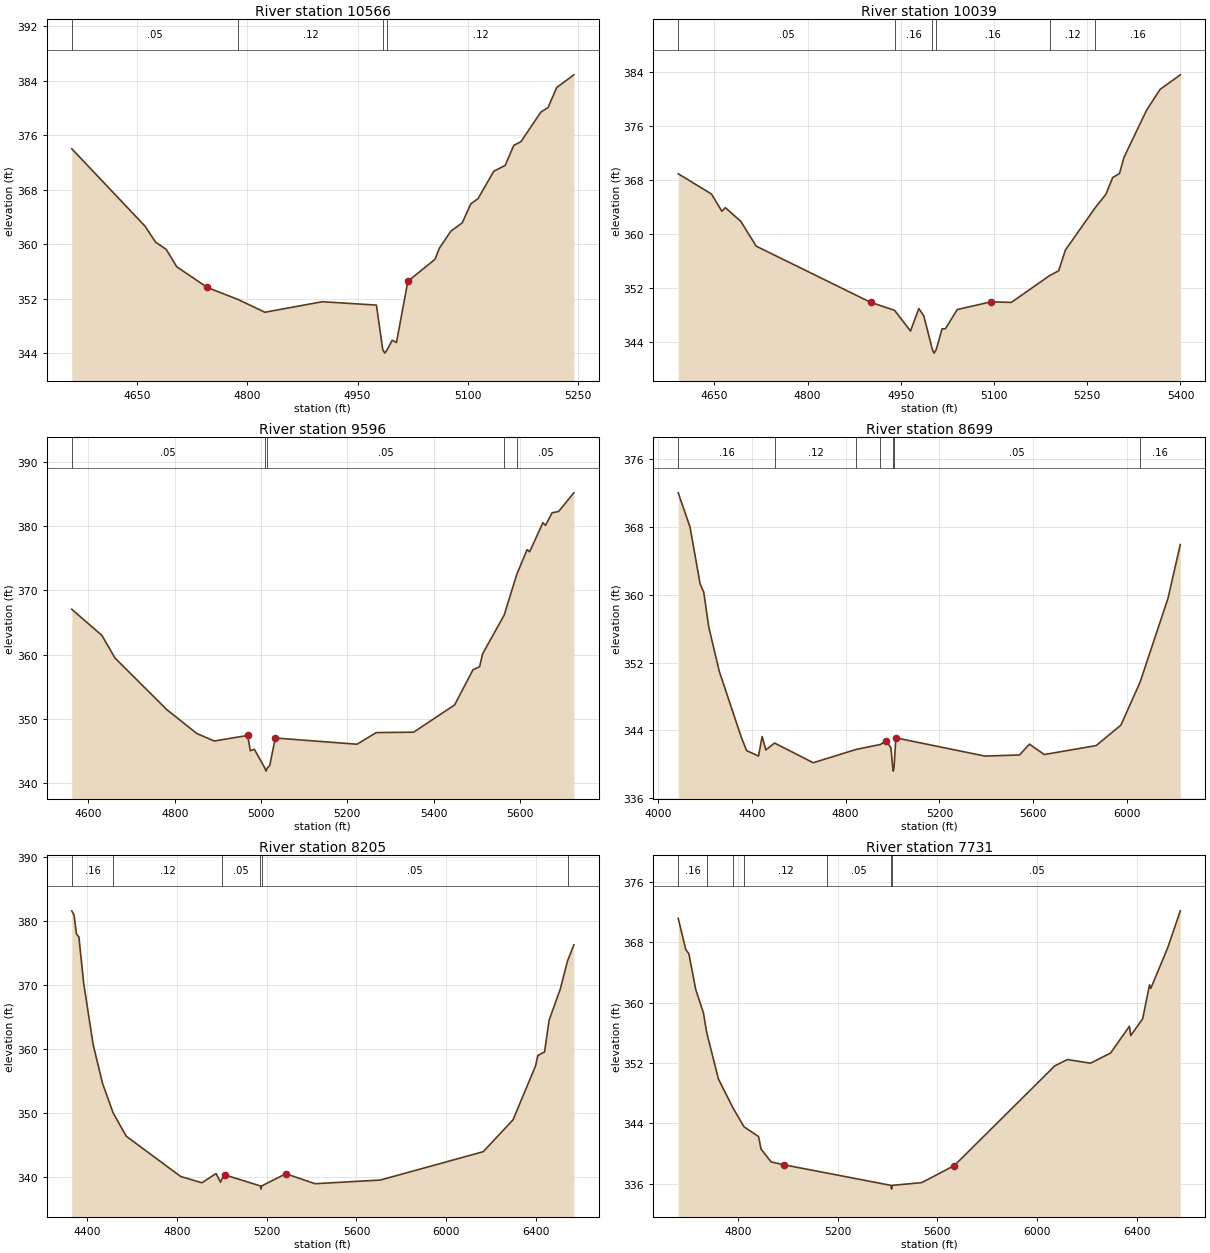
Type RM Length L Ch R = 1 ,10566   ,527,527,527
BEGIN DESCRIPTION:
UNT 016 IN CACR 21.0
END DESCRIPTION:
XS GIS Cut Line= 3
      3691149.63     10763910.22      3690899.61     10763610.19
      3690649.61     10763460.19
#Sta/Elev= 30
  4561.8  374.02  4661.4  362.63  4675.7  360.28  4690.1  359.23  4704.4  356.67
    4746  353.62  4788.1  351.84  4824.1  349.98  4902.2  351.53  4975.7  351.03
  4984.3  344.47  4987.1  343.97  4990.3  344.47  4997.1  345.87  5002.9  345.53
  5018.4  354.53  5055.4  357.78  5061.2  359.39  5076.7  361.89  5092.3  363.14
    5104  365.93  5113.7  366.68  5135.1  370.71  5150.6  371.57  5162.3  374.52
    5172  375.06  5199.2  379.42  5208.9  380.08  5220.6  383.02  5243.9  384.89
#Mann= 4 ,-1 , 0
  4561.8     .05       0  4788.1     .12       0  4984.3     .07       0
  4990.3     .12       0
Bank Sta=4746,5018.4
XS Rating Curve= 0 ,0
Exp/Cntr=0.3,0.1

Type RM Length L Ch R = 1 ,10039   ,443,443,443
BEGIN DESCRIPTION:
UNT 016 IN CACR 20.0
END DESCRIPTION:
XS GIS Cut Line= 3
      3691399.62     10763760.22      3691249.61     10763360.19
      3690899.62      10763210.2
#Sta/Elev= 30
  4591.7  368.92  4645.1  365.92    4662  363.35  4667.4  363.89  4692.3  361.87
  4717.2  358.17  4901.4  349.83  4939.8  348.65  4965.5  345.58  4978.9  348.91
  4986.9  347.82  5000.8  342.79  5003.5  342.29  5006.8  342.79  5016.3   345.9
  5021.6   345.9  5040.7  348.76  5095.1  349.91  5127.7  349.82  5189.2  353.79
  5203.9  354.51  5214.8   357.6    5263  363.91    5280  365.88  5290.9  368.36
  5301.8  368.95  5309.1  371.37  5345.3  378.34  5367.1  381.45  5399.7  383.61
#Mann= 6 ,-1 , 0
  4591.7     .05       0  4939.8     .16       0  5000.8     .07       0
  5006.8     .16       0  5189.2     .12       0    5263     .16       0
Bank Sta=4901.4,5095.1
XS Rating Curve= 0 ,0
Exp/Cntr=0.3,0.1

Type RM Length L Ch R = 1 ,9596    ,897,897,897
BEGIN DESCRIPTION:
UNT 016 IN CACR 19.0
END DESCRIPTION:
XS GIS Cut Line= 3
      3691649.61     10763610.17      3691649.61     10763210.19
      3690999.61     10762810.19
#Sta/Elev= 30
  4561.5  367.05  4631.5  362.97  4661.5  359.47  4781.5  351.43  4851.5  347.69
  4891.5  346.53  4969.2   347.4  4975.1  345.01  4984.6  345.23  5008.7  342.34
  5011.5  341.84  5014.7  342.34  5020.2  342.73    5033     347  5222.4  346.03
  5266.8  347.84  5353.7  347.91  5448.4  352.15    5491  357.62  5506.4  358.11
  5513.3  360.11  5563.3  366.14  5592.5  372.49  5616.5  376.35  5622.3     376
  5653.1  380.55    5659  380.11  5674.4  382.08  5689.5  382.29  5724.7  385.19
#Mann= 5 ,-1 , 0
  4561.5     .05       0  5008.7     .03       0  5014.7     .05       0
  5563.3     .16       0  5592.5     .05       0
Bank Sta=4969.2,5033
XS Rating Curve= 0 ,0
Exp/Cntr=0.3,0.1

Type RM Length L Ch R = 1 ,8699    ,494,494,494
BEGIN DESCRIPTION:
UNT 016 IN CACR 18.0
END DESCRIPTION:
XS GIS Cut Line= 3
      3693149.58     10763510.17      3692399.61     10763060.19
      3691199.63      10762660.2
#Sta/Elev= 30
  4086.7  372.06  4137.2  367.99    4180  361.29  4195.5  360.32  4216.9  356.19
  4261.6  350.97  4354.9  343.22  4378.2   341.6  4428.8  340.96  4444.3  343.27
  4459.9  341.68  4497.1   342.5    4662  340.17  4845.4  341.75  4948.4  342.33
  4971.9  342.76  4992.9  341.95  5000.5  339.68  5003.2  339.18  5006.5  339.68
    5014  343.11  5393.5  340.96  5541.1  341.09  5583.2  342.37  5646.5  341.14
  5867.8   342.2  5973.2  344.62  6055.1  349.71  6173.5  359.58  6226.2  365.95
#Mann= 7 ,-1 , 0
  4086.7     .16       0  4497.1     .12       0  4845.4     .07       0
  4948.4     .05       0  5000.5     .03       0  5006.5     .05       0
  6055.1     .16       0
Bank Sta=4971.9,5014
XS Rating Curve= 0 ,0
Exp/Cntr=0.3,0.1

Type RM Length L Ch R = 1 ,8205    ,474,474,474
BEGIN DESCRIPTION:
UNT 016 IN CACR 17.0
END DESCRIPTION:
XS GIS Cut Line= 3
       3693349.6     10762910.19      3692749.61     10762710.19
      3691149.58     10762610.19
#Sta/Elev= 30
  4332.4  381.58  4342.9  380.87  4353.5  377.94    4364  377.51  4385.1  370.36
  4427.3  360.69  4469.4  354.58  4516.6  349.96  4574.8  346.32  4817.3  340.01
  4912.1  339.02  4974.9  340.47  4994.9   339.1    5001  339.63  5014.9  340.25
  5172.3  338.53    5175  338.03  5178.3  338.53  5285.5  340.44  5415.7  338.88
  5706.3  339.45  6164.7  343.89  6297.4  348.89  6397.6  357.32  6407.7  358.94
  6437.7  359.51  6457.8  364.46  6507.8  369.35    6540  373.75    6568  376.26
#Mann= 6 ,-1 , 0
  4332.4     .16       0  4516.6     .12       0    5001     .05       0
  5172.3     .07       0  5178.3     .05       0    6540     .16       0
Bank Sta=5014.9,5285.5
XS Rating Curve= 0 ,0
Exp/Cntr=0.3,0.1

Type RM Length L Ch R = 1 ,7731    ,1083,1083,1083
BEGIN DESCRIPTION:
UNT 016 IN CACR 16.0
END DESCRIPTION:
XS GIS Cut Line= 3
      3693249.63     10762210.19      3692849.61     10762260.19
      3691249.59     10762460.19
#Sta/Elev= 30
    4560  371.15  4590.3  367.02  4602.8  366.45  4630.6  361.68  4660.8  358.67
  4674.3  356.03  4721.3  349.87  4780.5  345.99  4824.2  343.53  4882.5  342.23
  4892.6  340.57  4932.9  338.88  4983.3   338.5  5158.8  337.39  5413.6  335.77
  5416.4  335.27  5419.6  335.77  5537.6  336.13  5668.6   338.4  6071.7  351.61
  6122.1  352.44  6215.3  351.96  6295.9  353.31  6371.5  356.86  6376.5  355.62
  6424.4  357.83  6452.1  362.35  6457.2  361.88  6525.2  367.27  6575.6  372.15
#Mann= 7 ,-1 , 0
    4560     .16       0  4674.3     .12       0  4780.5     .16       0
  4824.2     .12       0  5158.8     .05       0  5413.6     .07       0
  5419.6     .05       0
Bank Sta=4983.3,5668.6
XS Rating Curve= 0 ,0
Exp/Cntr=0.3,0.1

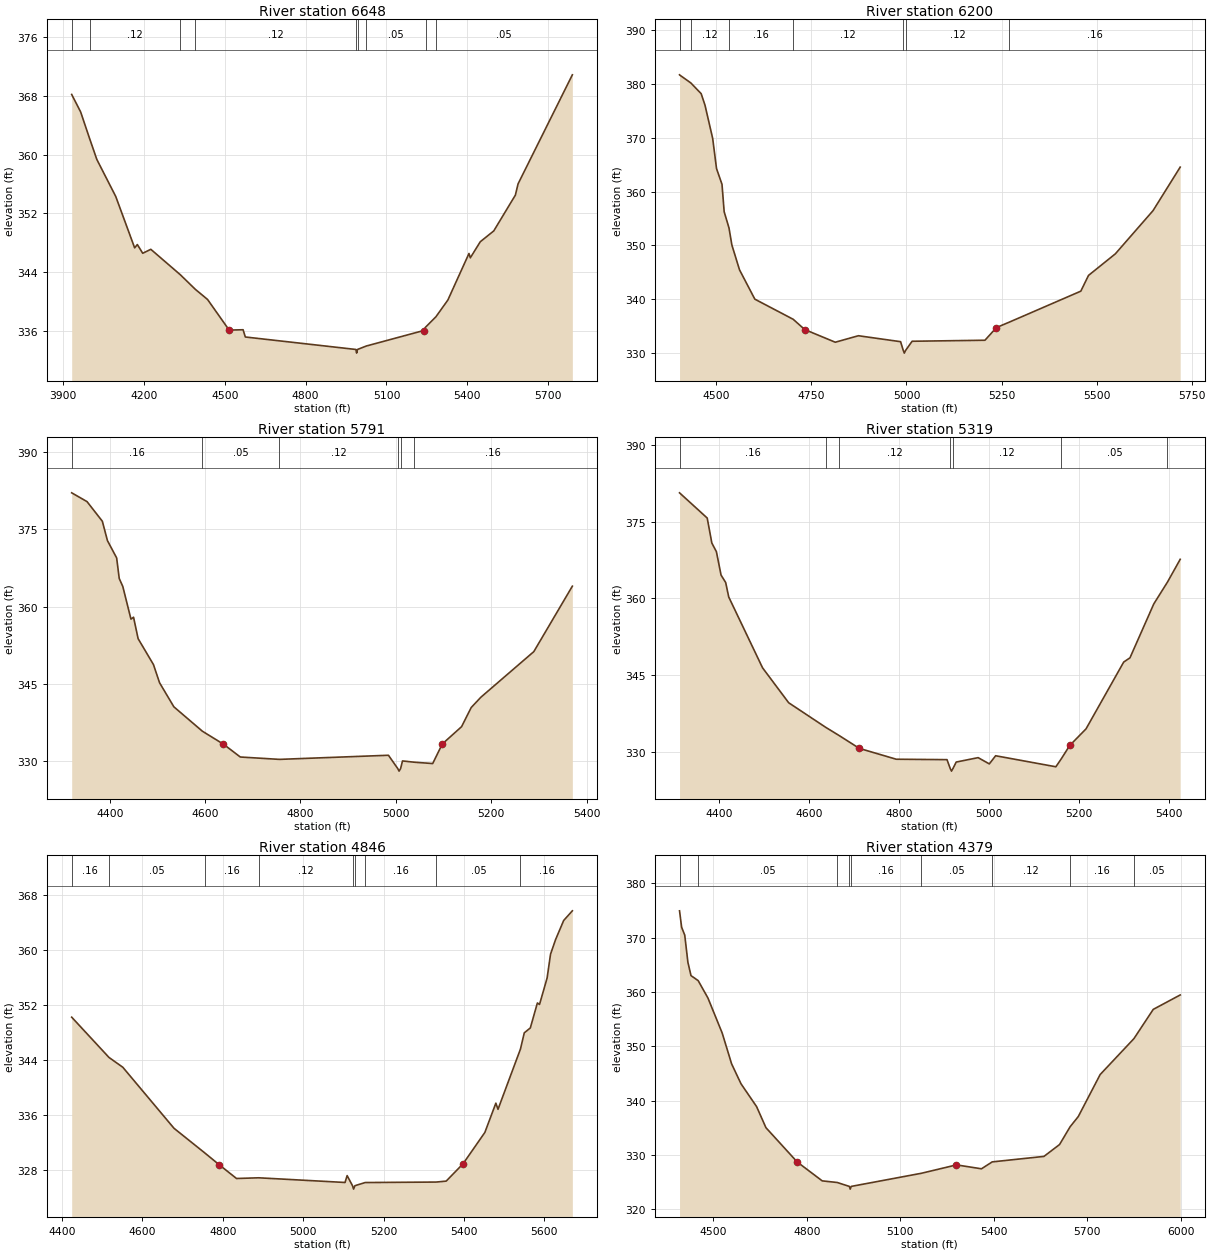
Type RM Length L Ch R = 1 ,6648    ,448,448,448
BEGIN DESCRIPTION:
UNT 016 IN CACR 14.0
END DESCRIPTION:
XS GIS Cut Line= 2
      3693222.69     10761690.27      3691368.58     10761822.21
#Sta/Elev= 30
  3931.4  368.21  3964.6  365.83  3997.5  362.24  4024.7  359.35  4094.9   354.3
  4165.1  347.29  4175.1  347.74  4195.1  346.55  4225.2  347.09  4334.5  343.63
  4390.5  341.63  4435.8  340.25    4516  336.07  4567.7  336.12  4576.1  335.13
  4986.5  333.43  4989.3  332.93  4992.5  333.43  5025.3   333.9  5237.8  336.01
    5245  336.46  5283.7  337.89    5328  340.17  5406.4  346.52  5411.4  345.93
  5448.3  348.12  5498.4   349.6  5578.6  354.48  5588.7  356.02  5790.2  370.89
#Mann= 9 ,-1 , 0
  3931.4     .16       0  3997.5     .12       0  4334.5     .16       0
  4390.5     .12       0  4986.5     .07       0  4992.5     .12       0
  5025.3     .05       0    5245     .16       0  5283.7     .05       0
Bank Sta=4516,5237.8
XS Rating Curve= 0 ,0
Exp/Cntr=0.3,0.1

Type RM Length L Ch R = 1 ,6200    ,409,409,409
BEGIN DESCRIPTION:
UNT 016 IN CACR 13.0
END DESCRIPTION:
XS GIS Cut Line= 2
      3692806.03     10761280.55      3691500.52     10761454.15
#Sta/Elev= 30
    4403  381.74  4403.3  381.71  4432.7  380.23  4459.9  378.23    4470  376.08
  4490.2  369.89  4500.3  364.28  4514.7  361.35  4520.4  356.24  4533.1  353.23
  4540.6  350.07  4560.8  345.42  4601.1  339.96    4702  336.21  4732.3   334.3
  4812.7  331.94  4873.5  333.15  4984.5  332.04  4991.6  330.41  4994.3  329.91
  4997.6  330.41  5014.8  332.12  5206.4  332.31  5236.7  334.67  5270.4  335.68
  5458.6  341.45  5478.8  344.38  5549.4   348.4  5648.6  356.45    5720  364.55
#Mann= 8 ,-1 , 0
    4403     .05       0  4403.3     .16       0  4432.7     .12       0
  4533.1     .16       0    4702     .12       0  4991.6     .07       0
  4997.6     .12       0  5270.4     .16       0
Bank Sta=4732.3,5236.7
XS Rating Curve= 0 ,0
Exp/Cntr=0.3,0.1

Type RM Length L Ch R = 1 ,5791    ,472,472,472
BEGIN DESCRIPTION:
UNT 016 IN CACR 12.0
END DESCRIPTION:
XS GIS Cut Line= 3
      3692599.65     10760860.17      3691949.61     10761110.19
      3691599.63     10761060.19
#Sta/Elev= 30
  4320.3  382.09  4352.5  380.38  4384.6  376.57  4395.3  372.81  4414.6  369.45
    4420  365.46  4427.5  363.91  4444.6  357.57    4450  357.95  4459.6  353.78
  4491.8  348.75  4504.6  345.22  4534.6  340.55  4594.5  335.81  4638.6   333.3
  4673.9  330.81    4756  330.35  4984.6  331.15  5004.1  328.57  5006.9  328.07
  5010.1  328.57  5014.1  330.05  5038.8   329.8  5077.4  329.54  5097.6  333.35
    5138   336.7  5158.2  340.42  5178.4  342.41  5289.5  351.27  5370.3  363.97
#Mann= 6 ,-1 , 0
  4320.3     .16       0  4594.5     .05       0    4756     .12       0
  5004.1     .07       0  5010.1     .12       0  5038.8     .16       0
Bank Sta=4638.6,5097.6
XS Rating Curve= 0 ,0
Exp/Cntr=0.3,0.1

Type RM Length L Ch R = 1 ,5319    ,473,473,473
BEGIN DESCRIPTION:
UNT 016 IN CACR 11.0
END DESCRIPTION:
XS GIS Cut Line= 3
      3692549.65      10760810.2      3691899.61     10760660.19
      3691499.64     10760860.17
#Sta/Elev= 30
  4311.5   380.6  4373.1  375.68  4383.4  370.81  4393.6  369.11  4403.9  364.56
  4414.2   363.1    4421  360.28  4496.3  346.46  4554.4  339.65  4636.4  334.88
  4666.2  333.28  4711.8  330.74  4793.9  328.63  4906.8  328.55    4914  326.81
  4916.8  326.31    4920  326.81  4927.3  328.08  4976.1  328.94    5001  327.72
    5015  329.31  5149.1  327.16  5161.3  328.73  5179.9  331.31  5216.2  334.55
  5300.1  347.59    5314  348.41  5367.1  358.94  5397.5  363.19  5425.8  367.63
#Mann= 7 ,-1 , 0
  4311.5     .16       0  4636.4     .05       0  4666.2     .12       0
    4914     .07       0    4920     .12       0  5161.3     .05       0
  5397.5     .16       0
Bank Sta=4711.8,5179.9
XS Rating Curve= 0 ,0
Exp/Cntr=0.3,0.1

Type RM Length L Ch R = 1 ,4846    ,467,467,467
BEGIN DESCRIPTION:
UNT 016 IN CACR 10.0
END DESCRIPTION:
XS GIS Cut Line= 3
      3692449.58     10760660.16      3692049.61     10760260.19
      3691399.63     10760460.18
#Sta/Elev= 30
    4424  350.21  4516.8  344.34  4551.2  342.91  4678.5  334.02  4754.6  330.45
  4791.7  328.67  4834.1   326.7  4889.4   326.8  5104.1  326.12  5109.3  327.12
  5122.7  325.65  5125.4  325.15  5128.7  325.65  5154.3  326.11    5331  326.18
  5355.8  326.32  5397.7  328.84    5452  333.41  5479.4  337.68  5484.7  336.78
  5540.6  345.57  5550.1  347.93  5565.1  348.64  5582.7  352.28    5588  352.06
  5606.9  355.92  5615.4  359.39  5627.9  361.51  5648.1   364.3  5669.7  365.71
#Mann= 9 ,-1 , 0
    4424     .16       0  4516.8     .05       0  4754.6     .16       0
  4889.4     .12       0  5122.7     .07       0  5128.7     .12       0
  5154.3     .16       0    5331     .05       0  5540.6     .16       0
Bank Sta=4791.7,5397.7
XS Rating Curve= 0 ,0
Exp/Cntr=0.3,0.1

Type RM Length L Ch R = 1 ,4379    ,721,721,721
BEGIN DESCRIPTION:
UNT 016 IN CACR 9.0
END DESCRIPTION:
XS GIS Cut Line= 2
      3692646.32     10759759.71      3691043.36     10759856.86
#Sta/Elev= 30
  4392.1  374.93  4398.8  371.91  4408.8  370.46  4418.9  365.47  4428.9  363.01
  4451.9  362.09  4483.3  358.88  4529.1  352.42  4559.1  346.78  4589.2  343.12
  4639.3  338.91  4669.3  335.03  4769.5  328.73  4849.7  325.25  4897.9  324.95
  4936.8  324.23  4939.6  323.73  4942.8  324.23  5168.2  326.65  5280.4  328.19
  5360.6  327.47    5395  328.74    5561  329.75    5611  331.93  5645.1  335.22
  5671.2  337.09  5741.3  344.81  5849.5  351.41  5911.6   356.8    5998  359.45
#Mann= 9 ,-1 , 0
  4392.1     .16       0  4451.9     .05       0  4897.9     .16       0
  4936.8     .07       0  4942.8     .16       0  5168.2     .05       0
    5395     .12       0  5645.1     .16       0  5849.5     .05       0
Bank Sta=4769.5,5280.4
XS Rating Curve= 0 ,0
Exp/Cntr=0.3,0.1