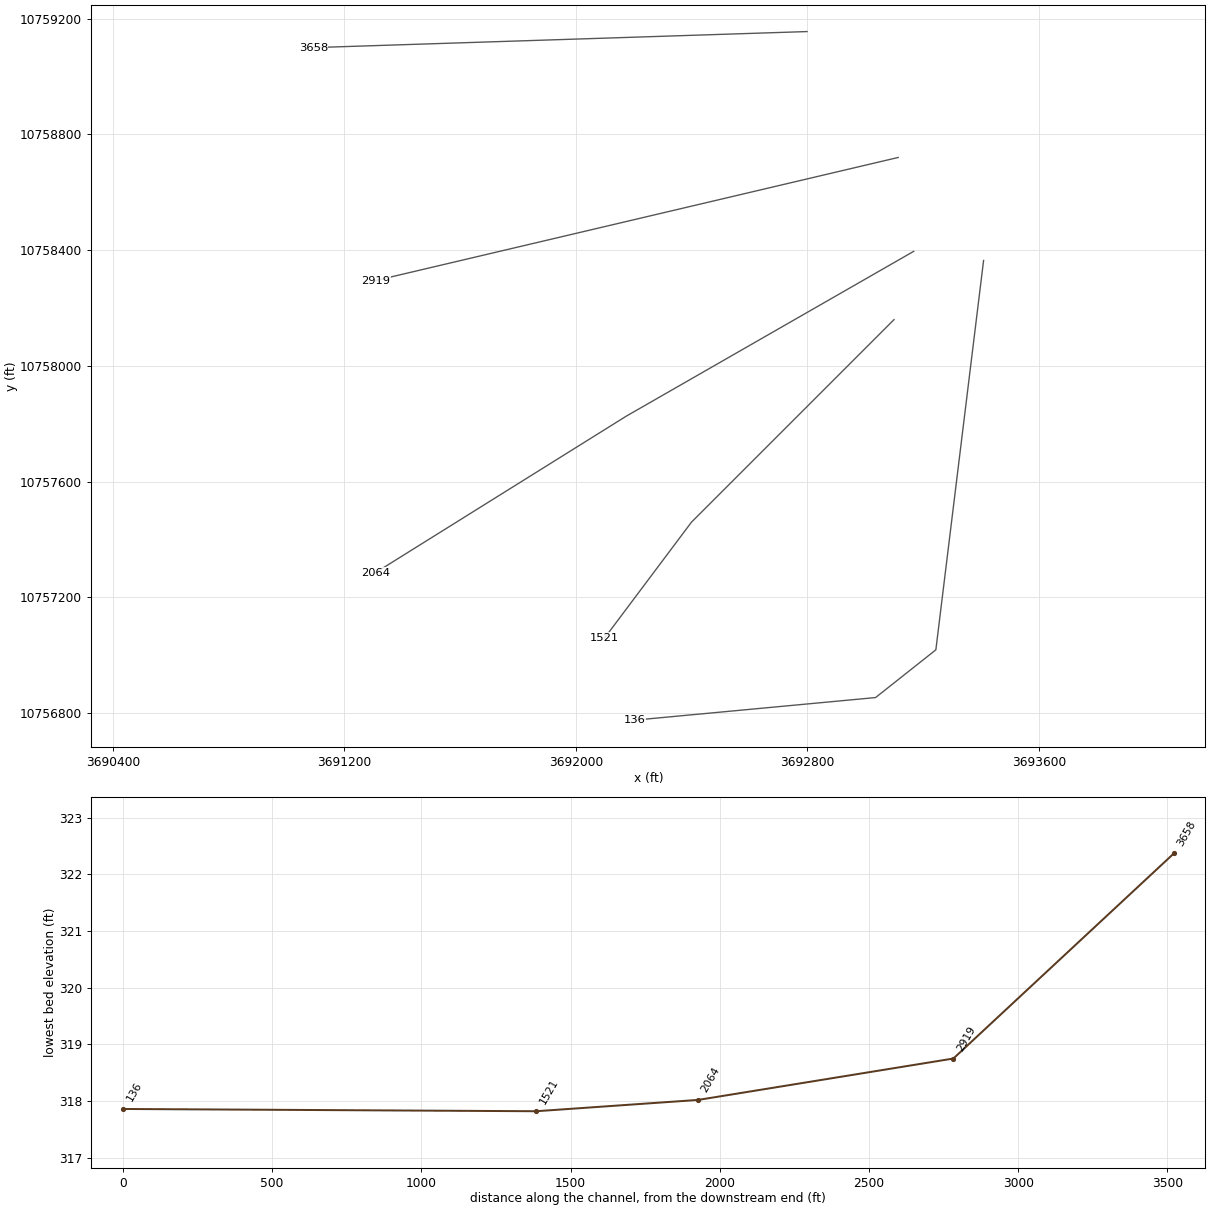
HEC-RAS study UNT 016 IN CACR.prj: UNT 016 IN CACR Base Level Engineering

--- UNT 016 IN CACR.g01 (geometry) --- (continued)

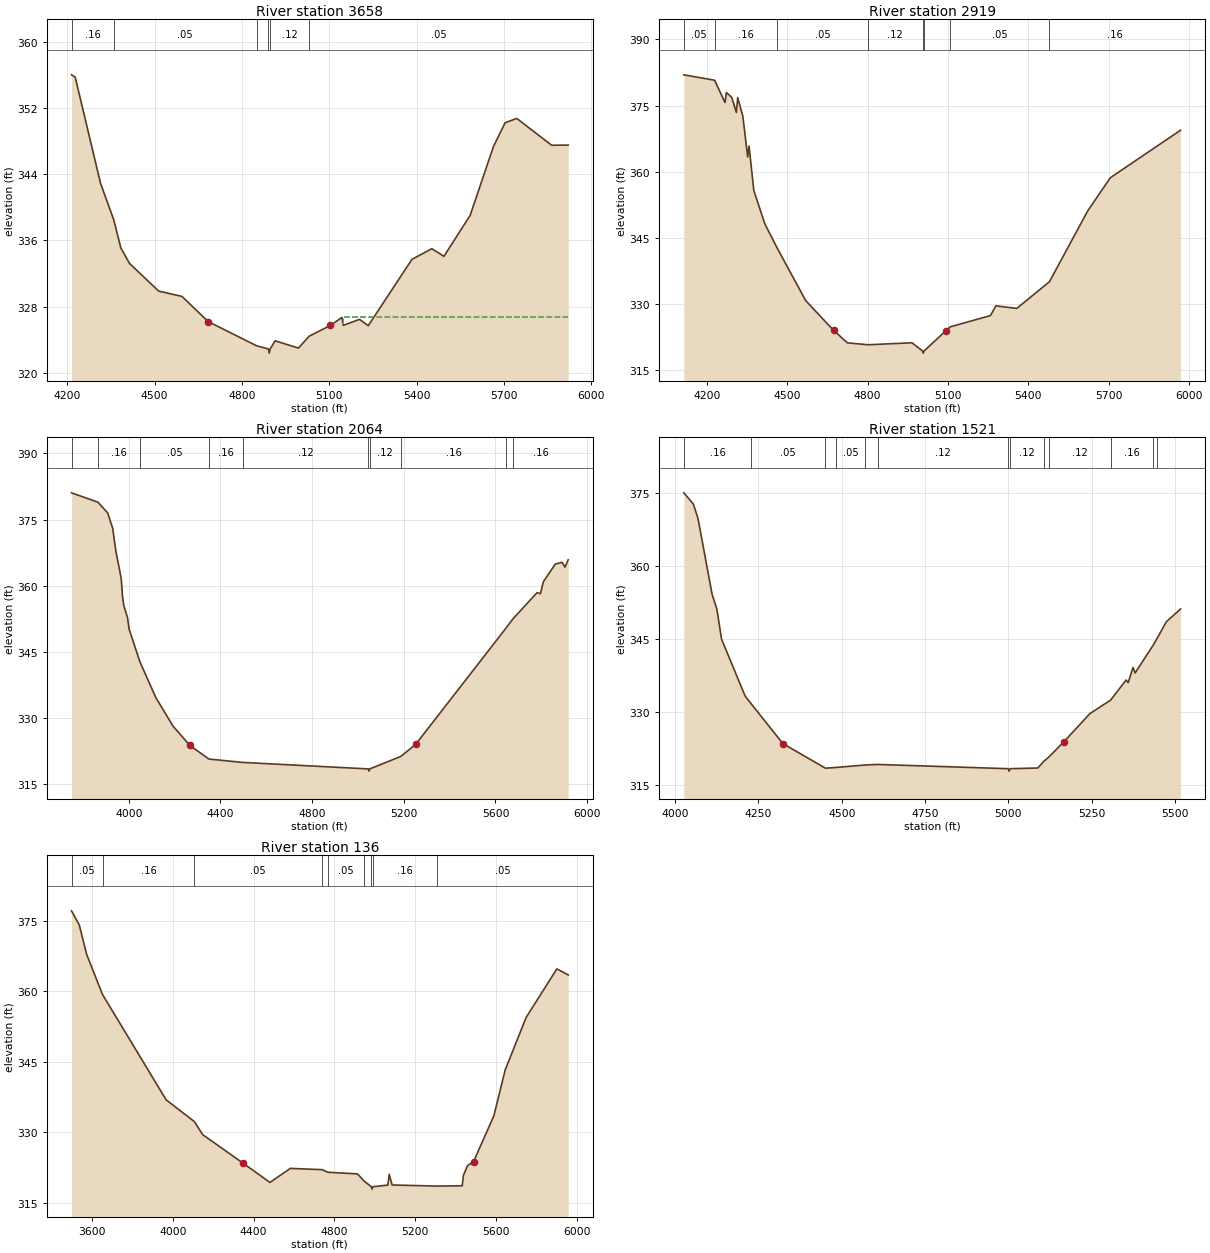
Type RM Length L Ch R = 1 ,3658    ,739,739,739
BEGIN DESCRIPTION:
UNT 016 IN CACR 7.0
END DESCRIPTION:
XS GIS Cut Line= 2
      3692799.11     10759155.54      3691092.71     10759100.05
#Sta/Elev= 30
  4214.2  356.03  4226.9  355.76  4313.8  342.93  4359.4   338.5  4383.8  335.08
  4413.8  333.21  4513.9  329.87  4593.9  329.23  4683.9  326.19  4850.3  323.26
  4891.1  322.87  4893.8  322.37  4897.1  322.87  4914.1  323.86  4994.1  322.98
  5031.2  324.42  5104.2  325.72  5143.6  326.69  5148.6  325.73  5204.2  326.45
  5234.2  325.69  5384.3  333.71  5452.5     335  5494.4  334.08  5584.4  339.03
  5664.5  347.36  5704.5  350.23  5744.5  350.76  5864.6  347.51  5921.5  347.53
#Mann= 6 ,-1 , 0
  4214.2     .16       0  4359.4     .05       0  4850.3     .12       0
  4891.1     .07       0  4897.1     .12       0  5031.2     .05       0
#XS Ineff= 2 , 0
                         5147.77           326.7
Permanent Ineff=
       F       F
Bank Sta=4683.9,5104.2
XS Rating Curve= 0 ,0
Exp/Cntr=0.3,0.1

Type RM Length L Ch R = 1 ,2919    ,855,855,855
BEGIN DESCRIPTION:
UNT 016 IN CACR 6.0
END DESCRIPTION:
XS GIS Cut Line= 2
       3693113.9     10758720.48      3691308.52     10758295.18
#Sta/Elev= 30
  4113.8  381.97  4228.6  380.74  4267.5  375.68  4272.6  377.96  4292.9  376.83
  4309.8  373.43  4314.9  376.78    4334  372.61  4352.2  363.32  4357.3  365.78
  4375.1  355.69  4416.2  348.12  4461.7  342.69  4569.1  330.66    4673  323.92
  4724.4  321.09  4801.9  320.65  4965.6   321.1    5005  319.25  5007.8  318.75
    5011  319.25  5092.7  323.86  5108.6  324.72  5258.6  327.28  5279.1  329.49
  5357.1  328.91  5479.1  334.98  5621.5  351.02  5706.2  358.59  5968.6  369.39
#Mann= 8 ,-1 , 0
  4113.8     .05       0  4228.6     .16       0  4461.7     .05       0
  4801.9     .12       0    5005     .07       0    5011     .12       0
  5108.6     .05       0  5479.1     .16       0
Bank Sta=4673,5092.7
XS Rating Curve= 0 ,0
Exp/Cntr=0.3,0.1

Type RM Length L Ch R = 1 ,2064    ,543,543,543
BEGIN DESCRIPTION:
UNT 016 IN CACR 4.0
END DESCRIPTION:
XS GIS Cut Line= 3
      3693167.67     10758396.16      3692174.63     10757826.72
      3691306.68     10757285.12
#Sta/Elev= 30
  3749.9  381.05  3864.9  378.94    3908  376.49  3929.6  373.02  3943.6  367.81
  3966.7  361.71  3972.7  357.51  3978.5  355.45  3994.3  352.79  4001.3   350.2
  4048.4  342.78    4118  334.68  4192.8  328.22  4266.4  323.85  4349.4  320.76
  4497.5  319.99  5045.3  318.52    5048  318.02  5051.3  318.52  5187.2  321.35
  5252.3  324.11  5646.7  350.45    5675  352.42    5782  358.46  5796.4  358.21
  5809.1   360.9    5861  364.91  5890.7  365.31  5903.5  364.22  5917.7   365.9
#Mann= 10 ,-1 , 0
  3749.9     .05       0  3864.9     .16       0  4048.4     .05       0
  4349.4     .16       0  4497.5     .12       0  5045.3     .07       0
  5051.3     .12       0  5187.2     .16       0  5646.7     .12       0
    5675     .16       0
Bank Sta=4266.4,5252.3
XS Rating Curve= 0 ,0
Exp/Cntr=0.3,0.1

Type RM Length L Ch R = 1 ,1521    ,1385,1385,1385
BEGIN DESCRIPTION:
UNT 016 IN CACR 3.0
END DESCRIPTION:
XS GIS Cut Line= 3
       3693099.6     10758160.18      3692399.61     10757460.19
      3692099.64     10757060.22
#Sta/Elev= 30
  4026.5  374.95  4054.8  372.66  4068.9  369.72  4111.3   354.1  4125.5  351.09
  4139.6  344.91  4210.3  333.23  4227.7  331.72  4323.5  323.48  4451.2  318.42
  4482.7  318.57  4571.3  319.08  4607.4  319.19  4999.3  318.32  5002.1  317.82
  5005.3  318.32  5088.3  318.46  5105.4  319.79  5121.8  320.75  5166.4  323.84
  5244.6  329.64  5306.5  332.39  5352.9  336.51  5359.2  335.99  5373.7   339.1
    5380  337.96  5434.7  343.73  5446.2   345.1  5473.7  348.48  5516.4  351.11
#Mann= 13 ,-1 , 0
  4026.5     .16       0  4227.7     .05       0  4451.2     .16       0
  4482.7     .05       0  4571.3     .16       0  4607.4     .12       0
  4999.3     .07       0  5005.3     .12       0  5105.4     .16       0
  5121.8     .12       0  5306.5     .16       0  5434.7     .05       0
  5446.2     .16       0
Bank Sta=4323.5,5166.4
XS Rating Curve= 0 ,0
Exp/Cntr=0.3,0.1

Type RM Length L Ch R = 1 ,136     ,0,0,0
BEGIN DESCRIPTION:
UNT 016 IN CACR 1.0
END DESCRIPTION:
XS GIS Cut Line= 4
      3693409.09     10758364.59      3693244.16     10757019.11
      3693035.82     10756854.18      3692203.54     10756776.15
#Sta/Elev= 30
  3499.1  377.19  3537.4   374.2  3574.1   367.9  3652.5  359.35    3967  336.91
    4107  332.25  4148.3  329.47  4349.8  323.33  4480.8  319.29  4581.5  322.28
  4738.8  322.01  4768.2  321.45  4913.6  321.11  4947.7  319.54  4982.7  318.36
  4985.5  317.86  4988.7  318.36  5064.3  318.73  5070.7  321.01  5085.1  318.74
  5307.3  318.51  5431.9  318.58    5438  320.83  5458.1  322.86  5488.2  323.74
  5588.6  333.51  5644.5  343.28  5748.3  354.48    5900  364.81  5956.3  363.53
#Mann= 9 ,-1 , 0
  3499.1     .05       0  3652.5     .16       0    4107     .05       0
  4738.8     .16       0  4768.2     .05       0  4947.7     .16       0
  4982.7     .07       0  4988.7     .16       0  5307.3     .05       0
Bank Sta=4349.8,5488.2
XS Rating Curve= 0 ,0
Exp/Cntr=0.3,0.1

Chan Stop Cuts=-1
Use User Specified Reach Order=0
Composite Channel Slope=5