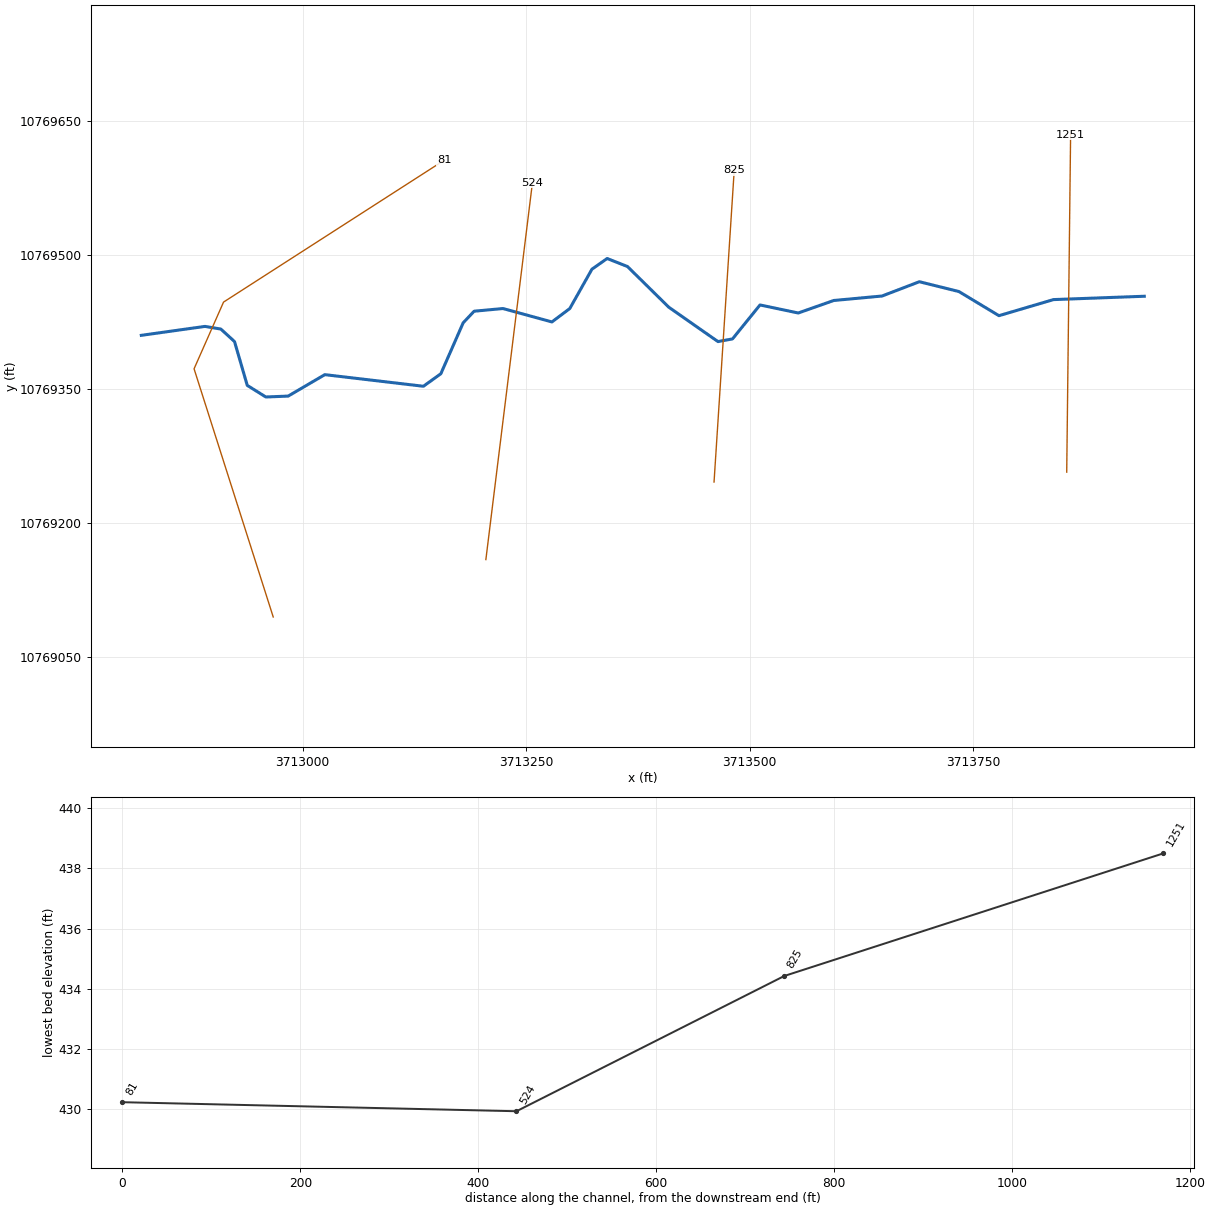
--- UNT 020 IN CACR.prj (project) ---

Proj Title=UNT 020 IN CACR Base Level Engineering
Current Plan=p01
Default Exp/Contr=0.3,0.1
English Units
Geom File=g01
Flow File=f01
Plan File=p01
Y Axis Title=Elevation
X Axis Title(PF)=Main Channel Distance
X Axis Title(XS)=Station
BEGIN DESCRIPTION:
UNT 020 IN CACR
END DESCRIPTION:
DSS Export Rating Curves= 0
DSS Export Rating Curve Sorted= 0
DSS Export Volume Flow Curves= 0
DXF OffsetX= 0
DXF OffsetY= 0
DXF ScaleX= 1
DXF ScaleY= 10

--- UNT 020 IN CACR.p01 (plan) ---

Plan Title=Multiple Run
Short Identifier=Multiple
Geom File=g01
Flow File=f01
Subcritical Flow
K Sum by GR= 0
Std Step Tol= 0.01
Critical Tol= 0.01
Num of Std Step Trials= 20
Max Error Tol= 0.3
Flow Tol Ratio= 0.001
Split Flow NTrial= 30
Split Flow Tol= 0.02
Split Flow Ratio= 0.02
Log Output Level= 0
Friction Slope Method= 1
Unsteady Friction Slope Method= 2
Unsteady Bridges Friction Slope Method= 1
Parabolic Critical Depth
Global Vel Dist=  1 , 1 , 1
Global Log Level= 0
CheckData=True
Encroach Param= -1, 0, 0, 0
BEGIN DESCRIPTION:
Multiple Run
END DESCRIPTION:

--- UNT 020 IN CACR.f01 (steady flow) ---

Flow Title=Multiple
Program Version=4.10
Number of Profiles= 7
Profile Names=10-year,25-year,50-year,1pct_min,100-year,1pct_plu,500-year
River Rch & RM=UNT 020 IN CACR,Reach-1         ,1251
     243     309     360     309     418     565     562
River Rch & RM=UNT 020 IN CACR,Reach-1         ,81
     243     309     360     309     418     565     562
Boundary for River Rch & Prof#=UNT 020 IN CACR,Reach-1         , 1
Up Type= 0
Dn Type= 3
Dn Slope=0.005
Boundary for River Rch & Prof#=UNT 020 IN CACR,Reach-1         , 2
Up Type= 0
Dn Type= 3
Dn Slope=0.005
Boundary for River Rch & Prof#=UNT 020 IN CACR,Reach-1         , 3
Up Type= 0
Dn Type= 3
Dn Slope=0.005
Boundary for River Rch & Prof#=UNT 020 IN CACR,Reach-1         , 4
Up Type= 0
Dn Type= 3
Dn Slope=0.005
Boundary for River Rch & Prof#=UNT 020 IN CACR,Reach-1         , 5
Up Type= 0
Dn Type= 3
Dn Slope=0.005
Boundary for River Rch & Prof#=UNT 020 IN CACR,Reach-1         , 6
Up Type= 0
Dn Type= 3
Dn Slope=0.005
Boundary for River Rch & Prof#=UNT 020 IN CACR,Reach-1         , 7
Up Type= 0
Dn Type= 3
Dn Slope=0.005
DSS Import GetInterval= 0
DSS Import GetPeak= 0
DSS Import FillOption= 0

--- UNT 020 IN CACR.g01 (geometry) ---

Geom Title=Existing Conditions
Program Version=4.10

River Reach=UNT 020 IN CACR ,Reach-1
Reach XY= 30
      3713941.33     10769453.74      3713839.75       10769450.
      3713778.75       10769432.        3713734.       10769459.
      3713689.75       10769470.        3713648.       10769454.
        3713594.       10769449.      3713554.25       10769435.
       3713511.5       10769444.      3713480.75       10769406.
       3713464.5       10769403.      3713409.44     10769441.51
      3713363.25       10769487.       3713340.5       10769496.
       3713323.5       10769484.      3713298.75       10769440.
      3713278.75       10769425.        3713224.       10769440.
      3713191.75       10769437.       3713179.5       10769424.
       3713154.5       10769367.        3713135.       10769353.
      3713024.75       10769366.      3712983.75       10769342.
      3712958.75       10769341.        3712938.       10769354.
      3712923.75       10769403.       3712908.5       10769417.
      3712890.75       10769420.       3712819.5       10769410.

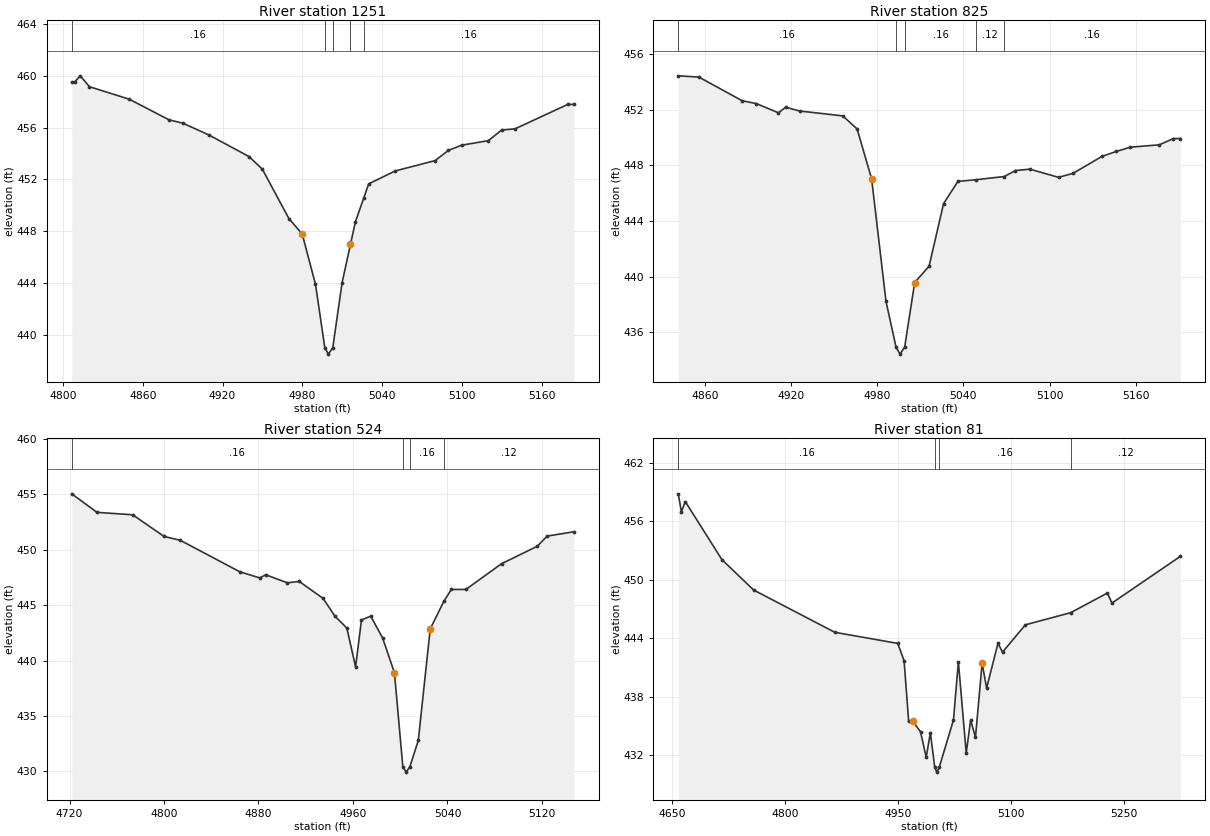
Type RM Length L Ch R = 1 ,1251    ,426,426,426
BEGIN DESCRIPTION:
UNT 020 IN CACR 2.0
END DESCRIPTION:
XS GIS Cut Line= 2
      3713854.56     10769256.93       3713858.9      10769634.5
#Sta/Elev= 30
  4806.6  459.54  4808.8  459.54    4813  460.01  4819.9  459.17  4849.9   458.2
  4879.9   456.6  4889.9  456.36  4909.9  455.43  4939.9  453.77  4949.9   452.8
  4969.9  448.98  4979.9  447.78  4989.9   443.9  4996.9     439  4999.6   438.5
  5002.9     439  5009.9  444.02  5016.2  446.98  5019.9  448.72  5026.1  450.54
  5029.9  451.66  5049.9  452.66  5079.9  453.46  5089.9  454.25  5099.9  454.65
  5119.9     455  5129.9  455.82  5139.9  455.91  5179.6   457.8  5184.2   457.8
#Mann= 5 ,-1 , 0
  4806.6     .16       0  4996.9     .07       0  5002.9     .16       0
  5016.2     .12       0  5026.1     .16       0
Bank Sta=4979.9,5016.2
XS Rating Curve= 0 ,0
Exp/Cntr=0.3,0.1

Type RM Length L Ch R = 1 ,825     ,301,301,301
BEGIN DESCRIPTION:
Mapping XS a74146ea
END DESCRIPTION:
XS GIS Cut Line= 2
      3713460.09     10769245.81      3713482.66     10769594.78
#Sta/Elev= 30
  4841.4  454.44  4855.8  454.35  4885.9  452.65  4895.9  452.44  4911.2  451.78
  4916.2  452.18    4926  451.91    4956  451.56    4966  450.62  4976.1  447.03
  4986.1  438.23  4993.1  434.93  4995.9  434.43  4999.1  434.93  5006.1  439.58
  5016.1  440.75  5026.2  445.25  5036.2  446.85  5048.9  446.97  5068.5   447.2
  5076.3  447.63  5086.3  447.73  5106.3  447.14  5116.4  447.43  5136.4  448.64
  5146.4     449  5156.4  449.31  5176.5  449.48  5186.3  449.93  5191.1  449.93
#Mann= 5 ,-1 , 0
  4841.4     .16       0  4993.1     .07       0  4999.1     .16       0
  5048.9     .12       0  5068.5     .16       0
Bank Sta=4976.1,5006.1
XS Rating Curve= 0 ,0
Exp/Cntr=0.3,0.1

Type RM Length L Ch R = 1 ,524     ,443,443,443
BEGIN DESCRIPTION:
Mapping XS a911787f
END DESCRIPTION:
XS GIS Cut Line= 2
      3713204.88     10769159.01      3713256.97     10769580.91
#Sta/Elev= 30
  4721.9  455.03  4743.2  453.36  4773.5  453.14    4800  451.19  4813.8  450.84
  4864.2     448  4881.1  447.45  4886.1  447.73  4904.5  447.01  4914.5  447.13
  4934.7   445.6  4944.8  443.99  4954.8  442.93  4962.2  439.43  4967.2  443.66
    4975     444  4985.1  442.03  4995.1   438.9  5002.2  430.44    5005  429.94
  5008.2  430.44  5015.3   432.8  5025.4  442.85    5037  445.35  5043.3  446.41
  5055.6  446.41  5085.8  448.73    5116   450.3  5124.4  451.22    5147  451.61
#Mann= 4 ,-1 , 0
  4721.9     .16       0  5002.2     .07       0  5008.2     .16       0
    5037     .12       0
Bank Sta=4995.1,5025.4
XS Rating Curve= 0 ,0
Exp/Cntr=0.3,0.1

Type RM Length L Ch R = 1 ,81      ,0,0,0
BEGIN DESCRIPTION:
UNT 020 IN CACR 1.0
END DESCRIPTION:
XS GIS Cut Line= 4
      3712967.03      10769094.8      3712878.49     10769372.55
      3712911.48      10769447.2      3713158.36     10769606.04
#Sta/Elev= 30
  4658.1   458.8  4662.3  456.96  4667.5     458  4716.2  452.04  4758.2  448.93
    4866  444.59  4949.6  443.45    4958  441.67  4964.1  435.45  4969.6  435.45
  4979.8  434.39  4987.4  431.76  4992.9   434.3  4998.7  430.74  5001.5  430.24
  5004.7  430.74  5023.6   435.6  5030.1  441.56  5040.5  432.21  5046.4  435.58
  5052.8   433.8  5061.6  441.41  5067.6  438.87  5082.7  443.47  5088.7  442.55
  5119.1  445.36  5179.1   446.6    5228  448.62    5234  447.59  5324.8  452.38
#Mann= 4 ,-1 , 0
  4658.1     .16       0  4998.7     .07       0  5004.7     .16       0
  5179.1     .12       0
Bank Sta=4969.6,5061.6
XS Rating Curve= 0 ,0
Exp/Cntr=0.3,0.1

Chan Stop Cuts=-1
Use User Specified Reach Order=0
Composite Channel Slope=5