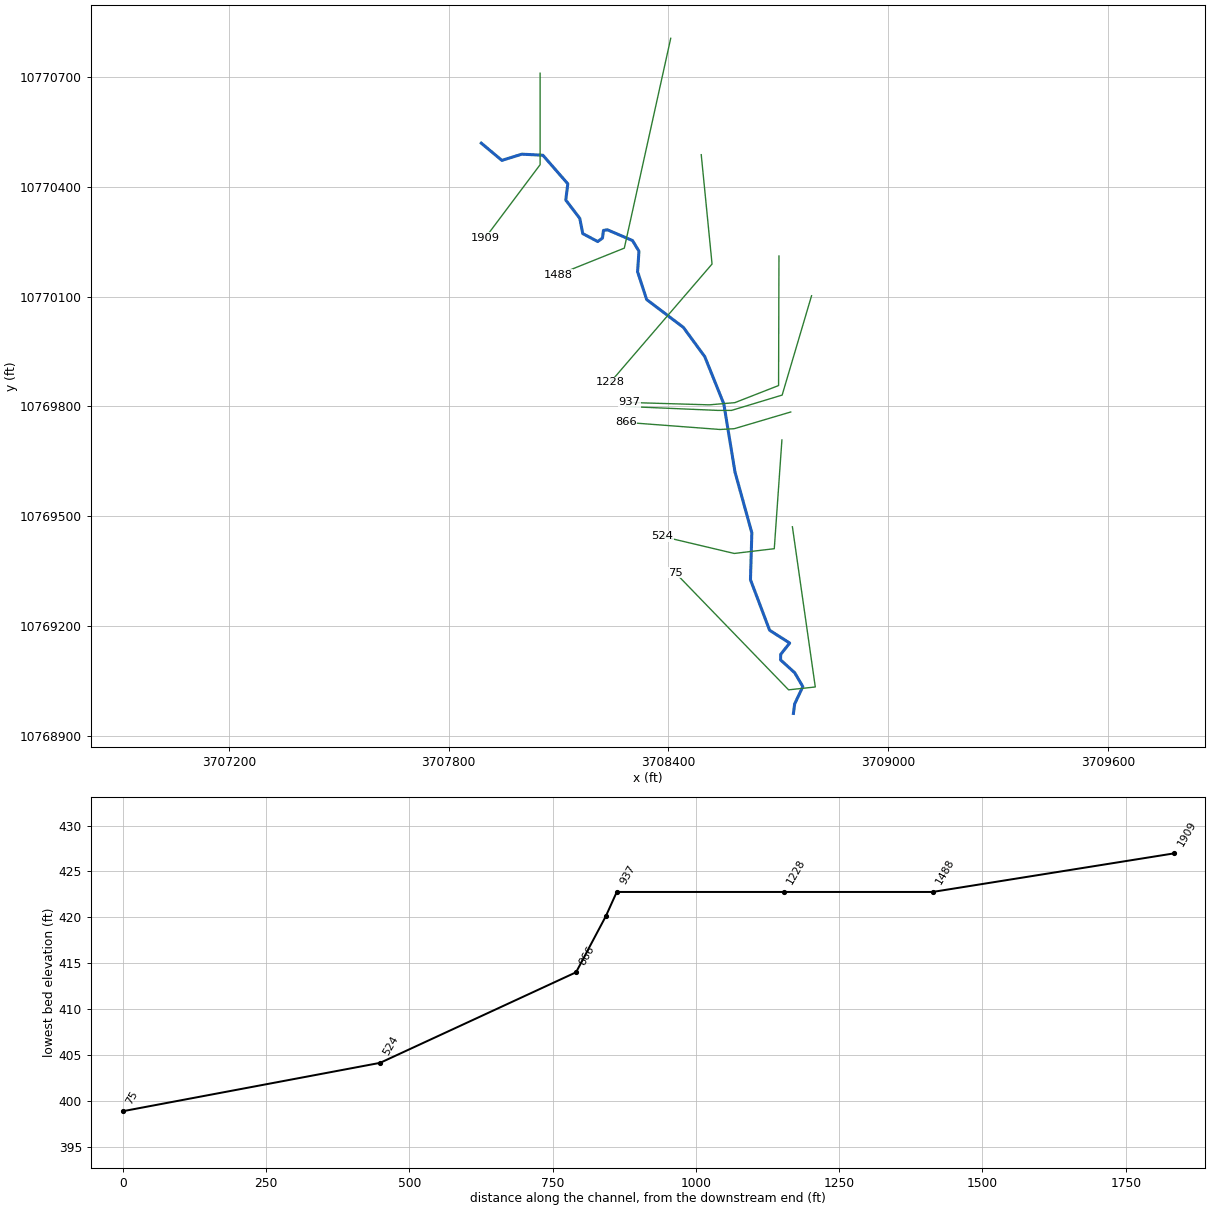
--- UNT 021 IN CACR.prj (project) ---

Proj Title=UNT 021 IN CACR Base Level Engineering
Current Plan=p01
Default Exp/Contr=0.3,0.1
English Units
Geom File=g01
Flow File=f01
Plan File=p01
Y Axis Title=Elevation
X Axis Title(PF)=Main Channel Distance
X Axis Title(XS)=Station
BEGIN DESCRIPTION:
UNT 021 IN CACR
END DESCRIPTION:
DSS Export Rating Curves= 0
DSS Export Rating Curve Sorted= 0
DSS Export Volume Flow Curves= 0
DXF OffsetX= 0
DXF OffsetY= 0
DXF ScaleX= 1
DXF ScaleY= 10

--- UNT 021 IN CACR.p01 (plan) ---

Plan Title=Multiple Run
Short Identifier=Multiple
Geom File=g01
Flow File=f01
Subcritical Flow
K Sum by GR= 0
Std Step Tol= 0.01
Critical Tol= 0.01
Num of Std Step Trials= 20
Max Error Tol= 0.3
Flow Tol Ratio= 0.001
Split Flow NTrial= 30
Split Flow Tol= 0.02
Split Flow Ratio= 0.02
Log Output Level= 0
Friction Slope Method= 1
Unsteady Friction Slope Method= 2
Unsteady Bridges Friction Slope Method= 1
Parabolic Critical Depth
Global Vel Dist=  1 , 1 , 1
Global Log Level= 0
CheckData=True
Encroach Param= -1, 0, 0, 0
BEGIN DESCRIPTION:
Multiple Run
END DESCRIPTION:

--- UNT 021 IN CACR.f01 (steady flow) ---

Flow Title=Multiple
Program Version=4.10
Number of Profiles= 7
Profile Names=10-year,25-year,50-year,1pct_min,100-year,1pct_plu,500-year
River Rch & RM=UNT 021 IN CACR,Reach-1         ,1909
     209     264     307     263     355     481     476
River Rch & RM=UNT 021 IN CACR,Reach-1         ,75
  1081.2  1533.6  1920.6  1756.8    2376    3213  3647.4
Boundary for River Rch & Prof#=UNT 021 IN CACR,Reach-1         , 1
Up Type= 0
Dn Type= 3
Dn Slope=0.01172
Boundary for River Rch & Prof#=UNT 021 IN CACR,Reach-1         , 2
Up Type= 0
Dn Type= 3
Dn Slope=0.01172
Boundary for River Rch & Prof#=UNT 021 IN CACR,Reach-1         , 3
Up Type= 0
Dn Type= 3
Dn Slope=0.01172
Boundary for River Rch & Prof#=UNT 021 IN CACR,Reach-1         , 4
Up Type= 0
Dn Type= 3
Dn Slope=0.01172
Boundary for River Rch & Prof#=UNT 021 IN CACR,Reach-1         , 5
Up Type= 0
Dn Type= 3
Dn Slope=0.01172
Boundary for River Rch & Prof#=UNT 021 IN CACR,Reach-1         , 6
Up Type= 0
Dn Type= 3
Dn Slope=0.01172
Boundary for River Rch & Prof#=UNT 021 IN CACR,Reach-1         , 7
Up Type= 0
Dn Type= 3
Dn Slope=0.01172
DSS Import GetInterval= 0
DSS Import GetPeak= 0
DSS Import FillOption= 0

--- UNT 021 IN CACR.g01 (geometry) ---

Geom Title=Existing Conditions
Program Version=4.10

River Reach=UNT 021 IN CACR ,Reach-1
Reach XY= 30
        3707889.       10770519.      3707945.25       10770472.
      3707999.75       10770489.      3708057.25       10770486.
      3708125.25       10770408.      3708119.67     10770363.65
      3708157.86     10770313.74      3708166.11     10770272.07
      3708206.91     10770250.37      3708219.93     10770259.92
      3708222.53     10770280.75      3708233.38     10770282.49
        3708302.       10770253.       3708319.5       10770224.
      3708315.75       10770168.       3708340.5       10770092.
      3708440.75       10770016.      3708499.25       10769936.
      3708551.25       10769807.      3708581.75       10769621.
      3708627.75       10769455.        3708624.       10769327.
      3708676.25       10769189.        3708731.       10769154.
       3708706.5       10769123.      3708706.25       10769108.
      3708744.75       10769073.        3708767.       10769035.
      3708744.75       10768988.      3708741.25       10768962.

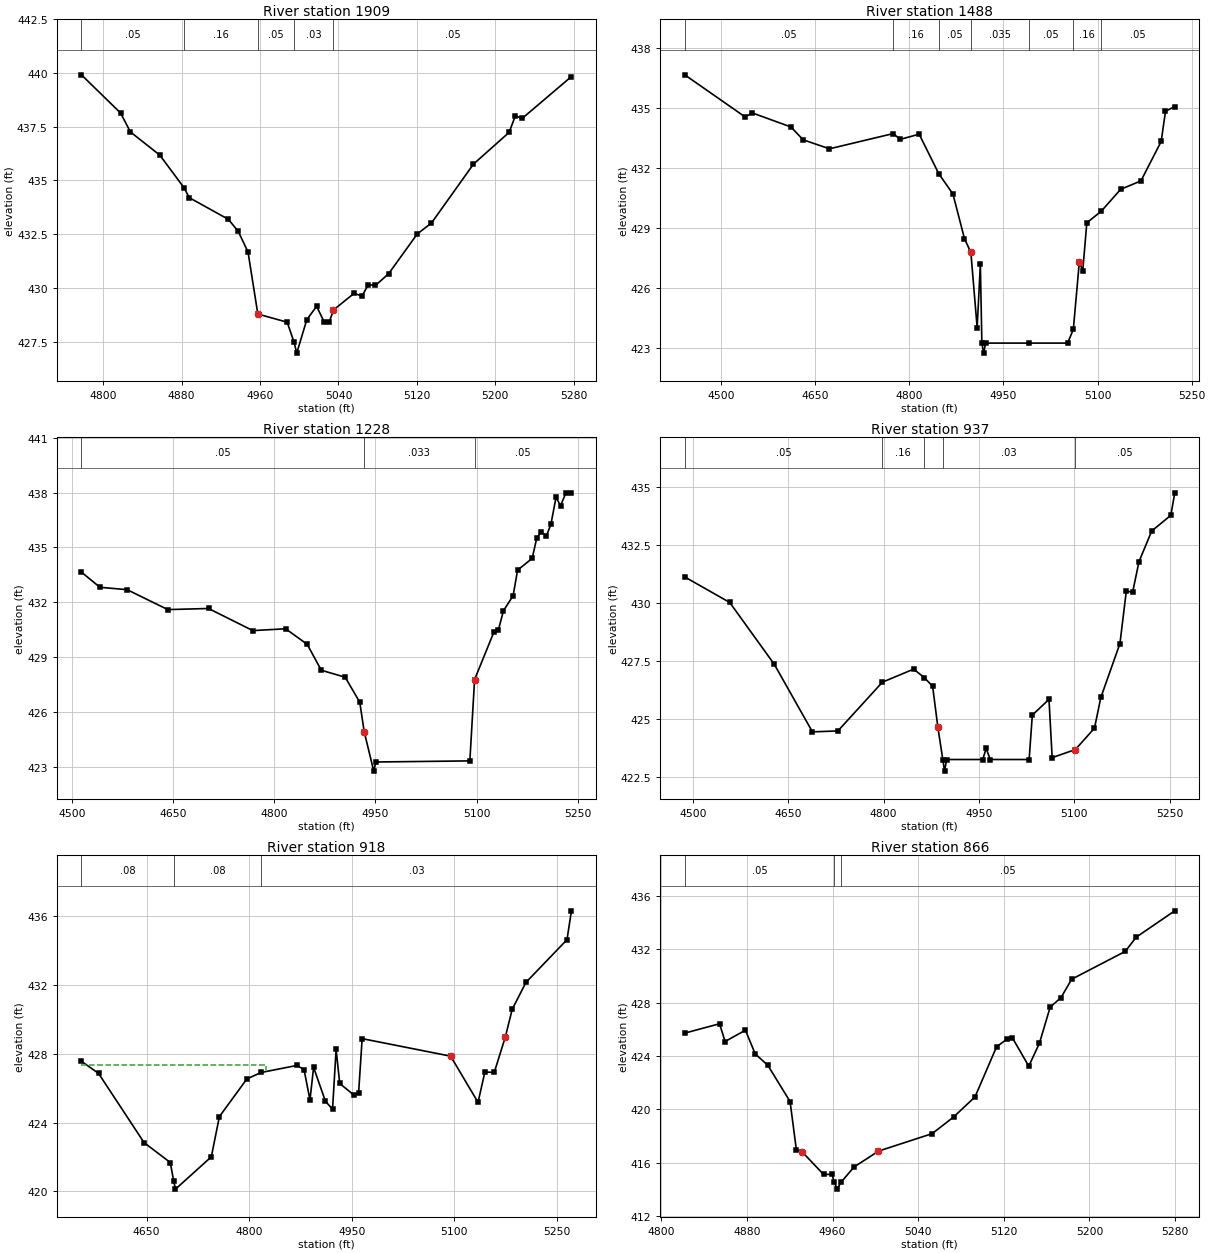
Type RM Length L Ch R = 1 ,1909    ,421,421,421
BEGIN DESCRIPTION:
UNT 021 IN CACR 3.0
END DESCRIPTION:
XS GIS Cut Line= 3
      3708049.61     10770710.14      3708049.61     10770460.19
      3707899.58     10770260.15
#Sta/Elev= 30
  4777.7  439.92  4817.7  438.14  4827.7  437.26  4857.7  436.18  4882.6  434.65
  4887.7   434.2  4927.7  433.19  4937.7  432.63  4947.7  431.67  4957.7  428.78
  4987.7   428.4  4994.7  427.46  4997.4  426.96  5007.7  428.52  5017.7  429.14
  5025.2  428.43  5030.8  428.43  5034.9  428.97  5055.8  429.74  5064.1  429.62
  5070.4  430.15  5077.7  430.11  5091.2  430.66  5120.4  432.51  5134.9  433.02
  5177.7  435.76  5214.1  437.24  5220.4     438  5227.7   437.9  5277.7  439.84
#Mann= 5 ,-1 , 0
  4777.7     .05       0  4882.6     .16       0  4957.7     .05       0
  4994.7     .03       0  5034.9     .05       0
Bank Sta=4957.7,5034.9
XS Rating Curve= 0 ,0
Exp/Cntr=0.3,0.1

Type RM Length L Ch R = 1 ,1488    ,260,260,260
BEGIN DESCRIPTION:
UNT 021 IN CACR 2.0
END DESCRIPTION:
XS GIS Cut Line= 3
      3708406.25     10770805.26      3708279.52     10770232.38
       3708099.6     10770160.18
#Sta/Elev= 30
  4442.4  436.64  4538.6  434.54    4550  434.74  4611.5  434.04    4631   433.4
  4672.9  432.95  4774.5  433.71  4785.6  433.42  4815.8  433.68  4847.2   431.7
  4869.6   430.7    4888  428.47  4898.2  427.78  4908.2  424.03  4913.3  427.19
  4915.7  423.26  4918.5  422.76  4921.7  423.26  4990.4  423.26  5052.2  423.26
  5061.4  423.94    5071  427.32  5076.4  426.86  5082.9  429.26    5106  429.84
  5136.8  430.93  5169.1  431.35  5201.4  433.32  5208.2  434.82    5223  435.06
#Mann= 7 ,-1 , 0
  4442.4     .05       0  4774.5     .16       0  4847.2     .05       0
  4898.2    .035       0  4990.4     .05       0  5061.4     .16       0
    5106     .05       0
Bank Sta=4898.2,5071
XS Rating Curve= 0 ,0
Exp/Cntr=0.3,0.1

Type RM Length L Ch R = 1 ,1228    ,291,291,291
BEGIN DESCRIPTION:
Mapping XS 9e465951
END DESCRIPTION:
XS GIS Cut Line= 3
      3708489.58     10770487.59       3708519.1     10770188.97
      3708241.34     10769866.08
#Sta/Elev= 30
  4514.4  433.65  4541.9  432.82  4582.1  432.69  4642.4   431.6  4702.7  431.66
  4768.4  430.45    4817  430.55  4848.9   429.7  4869.8  428.28  4905.2   427.9
  4926.8  426.53  4933.4  424.91  4947.5  422.76  4950.7  423.26  5089.9  423.32
  5096.9  427.77  5125.4  430.36    5132  430.46  5139.7  431.54    5154  432.36
  5160.6  433.76  5182.2   434.4  5189.1  435.53  5195.7  435.85  5203.4  435.64
    5210  436.27  5217.6  437.75  5224.2  437.28  5231.9  437.96  5240.4  437.99
#Mann= 3 , 0 , 0
  4514.4     .05       0  4933.4    .033       0  5096.9     .05       0
Bank Sta=4933.4,5096.9
XS Rating Curve= 0 ,0
Exp/Cntr=0.3,0.1

Type RM Length L Ch R = 1 ,937     ,19,19,19
BEGIN DESCRIPTION:
Mapping XS 74fc3932
END DESCRIPTION:
XS GIS Cut Line= 5
      3708701.82     10770210.91      3708700.74     10769857.16
      3708581.38      10769810.5      3708511.51     10769804.47
      3708293.44     10769810.95
#Sta/Elev= 30
  4487.5  431.12  4558.2  430.02  4628.2  427.36  4688.2  424.45  4728.2  424.49
  4798.2  426.59  4847.2  427.15  4863.9  426.79  4877.1  426.41  4885.4  424.64
  4893.1  423.26  4895.9  422.76  4899.1  423.26  4955.9  423.26  4961.2  423.74
  4967.7  423.26  5028.8  423.26  5033.8  425.17    5060  425.85    5065  423.34
  5101.5  423.69  5131.5  424.61  5141.5  425.93  5171.5  428.25  5181.5   430.5
  5191.5  430.47  5201.5  431.78  5221.5   433.1  5251.5  433.77  5257.7  434.74
#Mann= 5 ,-1 , 0
  4487.5     .05       0  4798.2     .16       0  4863.9     .05       0
  4893.1     .03       0  5101.5     .05       0
Bank Sta=4885.4,5101.5
XS Rating Curve= 0 ,0
Exp/Cntr=0.3,0.1

Type RM Length L Ch R = 1 ,918     ,52,52,52
BEGIN DESCRIPTION:
Mapping XS 2d66973e
END DESCRIPTION:
XS GIS Cut Line= 5
      3708790.79     10770102.34      3708710.51     10769831.12
      3708572.27     10769789.28      3708535.38     10769789.28
      3708283.09     10769800.07
#Sta/Elev= 30
  4554.6  427.57  4579.6  426.87  4646.2  422.84  4684.6  421.68  4689.4  420.63
  4692.2  420.13  4744.6  422.01  4756.4  424.35  4796.7  426.55  4817.6  426.92
  4869.7  427.33  4880.2  427.09  4888.9  425.32  4894.2  427.22  4911.5  425.24
  4921.9  424.79  4927.1  428.26  4932.4  426.28  4953.3   425.6    4960  425.73
  4965.2  428.89  5094.6  427.87  5134.7  425.18  5144.7  426.95  5158.4  426.92
  5174.7     429  5184.7   430.6  5204.7  432.16  5264.8  434.65  5271.3  436.33
#Mann= 3 ,-1 , 0
  4554.6     .08       0  4689.4     .08       0  4817.6     .03       0
#XS Ineff= 2 , 0
         4825.08  427.37
Permanent Ineff=
       F       F
Bank Sta=5094.6,5174.7
XS Rating Curve= 0 ,0
Exp/Cntr=0.3,0.1

Type RM Length L Ch R = 1 ,866     ,342,342,342
BEGIN DESCRIPTION:
Mapping XS e46493cc
END DESCRIPTION:
XS GIS Cut Line= 4
      3708733.97     10769784.95      3708579.86     10769739.37
       3708540.8      10769737.2      3708283.57     10769756.66
#Sta/Elev= 30
  4821.9  425.71  4854.4  426.41  4859.6  425.08  4878.6  425.93  4887.7  424.15
  4899.4  423.31  4920.3  420.58  4926.2  416.95  4931.4  416.82  4951.6  415.11
  4959.4  415.12  4961.7  414.51  4964.4  414.01  4967.7  414.51  4980.1  415.67
  5002.9  416.86    5053  418.17  5073.1  419.42  5093.1  420.93  5113.2  424.68
  5122.9  425.26  5127.9  425.37  5143.3  423.23  5153.3  424.96  5163.3  427.66
  5173.4  428.37  5183.4  429.75  5233.5  431.84  5243.6   432.9  5279.7  434.88
#Mann= 3 ,-1 , 0
  4821.9     .05       0  4961.7     .03       0  4967.7     .05       0
Bank Sta=4931.4,5002.9
XS Rating Curve= 0 ,0
Exp/Cntr=0.3,0.1

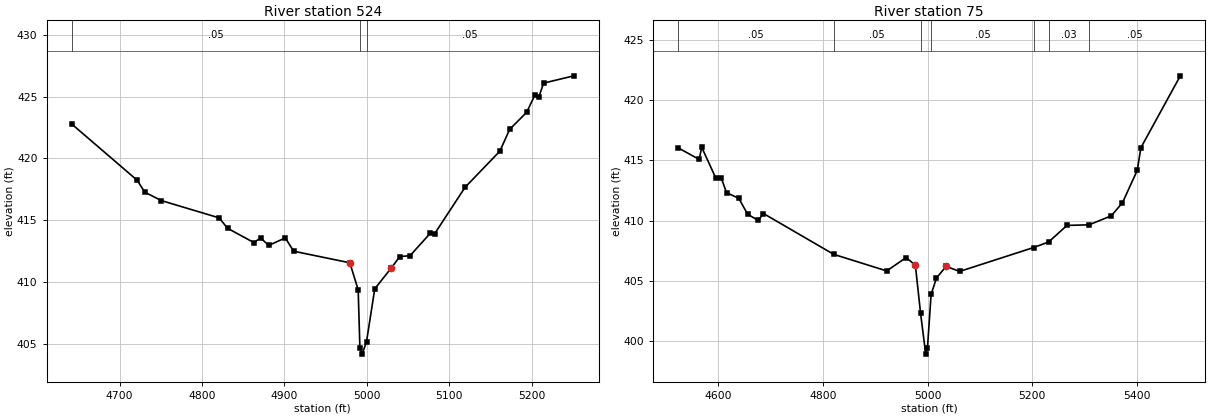
Type RM Length L Ch R = 1 ,524     ,449,449,449
BEGIN DESCRIPTION:
Mapping XS f70aaadb
END DESCRIPTION:
XS GIS Cut Line= 4
      3708709.86     10769708.59      3708689.02     10769411.68
      3708579.65     10769398.66      3708383.85     10769445.03
#Sta/Elev= 30
    4642  422.78  4721.3  418.23  4730.6  417.26  4750.7  416.58  4820.8  415.18
  4830.9  414.34  4862.9  413.18    4871  413.55    4881  412.95    4901  413.56
  4911.1  412.48  4979.3  411.54  4989.4  409.35  4991.5  404.64  4994.2  404.14
  4999.5  405.14  5009.5  409.43  5029.7  411.13  5039.8  412.04  5052.4  412.12
  5076.8  413.93    5082  413.88  5119.1  417.66  5161.3  420.59  5173.1  422.35
  5193.7  423.73  5203.6  425.11  5208.7     425  5214.3   426.1    5251  426.69
#Mann= 3 ,-1 , 0
    4642     .05       0  4991.5     .03       0  4999.5     .05       0
Bank Sta=4979.3,5029.7
XS Rating Curve= 0 ,0
Exp/Cntr=0.3,0.1

Type RM Length L Ch R = 1 ,75      ,0,0,0
BEGIN DESCRIPTION:
UNT 021 IN CACR 1.0
END DESCRIPTION:
XS GIS Cut Line= 4
      3708738.51     10769471.55        3708801.     10769034.08
      3708728.09     10769026.26      3708418.84      10769345.9
#Sta/Elev= 30
  4523.2  416.05  4563.1  415.09  4568.2  416.09  4595.3  413.51  4605.4  413.55
  4615.5  412.32  4638.9  411.85  4655.9  410.52  4676.1  410.01  4686.2  410.58
  4820.5  407.18  4921.8   405.8  4958.9  406.91  4976.6  406.28  4986.6  402.26
  4996.4  398.87  4999.7  399.37  5006.7  403.84  5016.8  405.19  5035.2  406.18
  5061.3  405.76  5202.8  407.75  5231.4  408.21  5266.5  409.59  5308.8  409.64
  5351.2  410.39  5372.6  411.48  5400.9  414.18  5407.8  416.06  5483.2  422.05
#Mann= 7 ,-1 , 0
  4523.2     .05       0  4820.5     .05       0  4986.6     .03       0
  5006.7     .05       0  5202.8     .03       0  5231.4     .03       0
  5308.8     .05       0
Bank Sta=4976.6,5035.2
XS Rating Curve= 0 ,0
Exp/Cntr=0.3,0.1

Chan Stop Cuts=-1
Use User Specified Reach Order=0
Composite Channel Slope=5