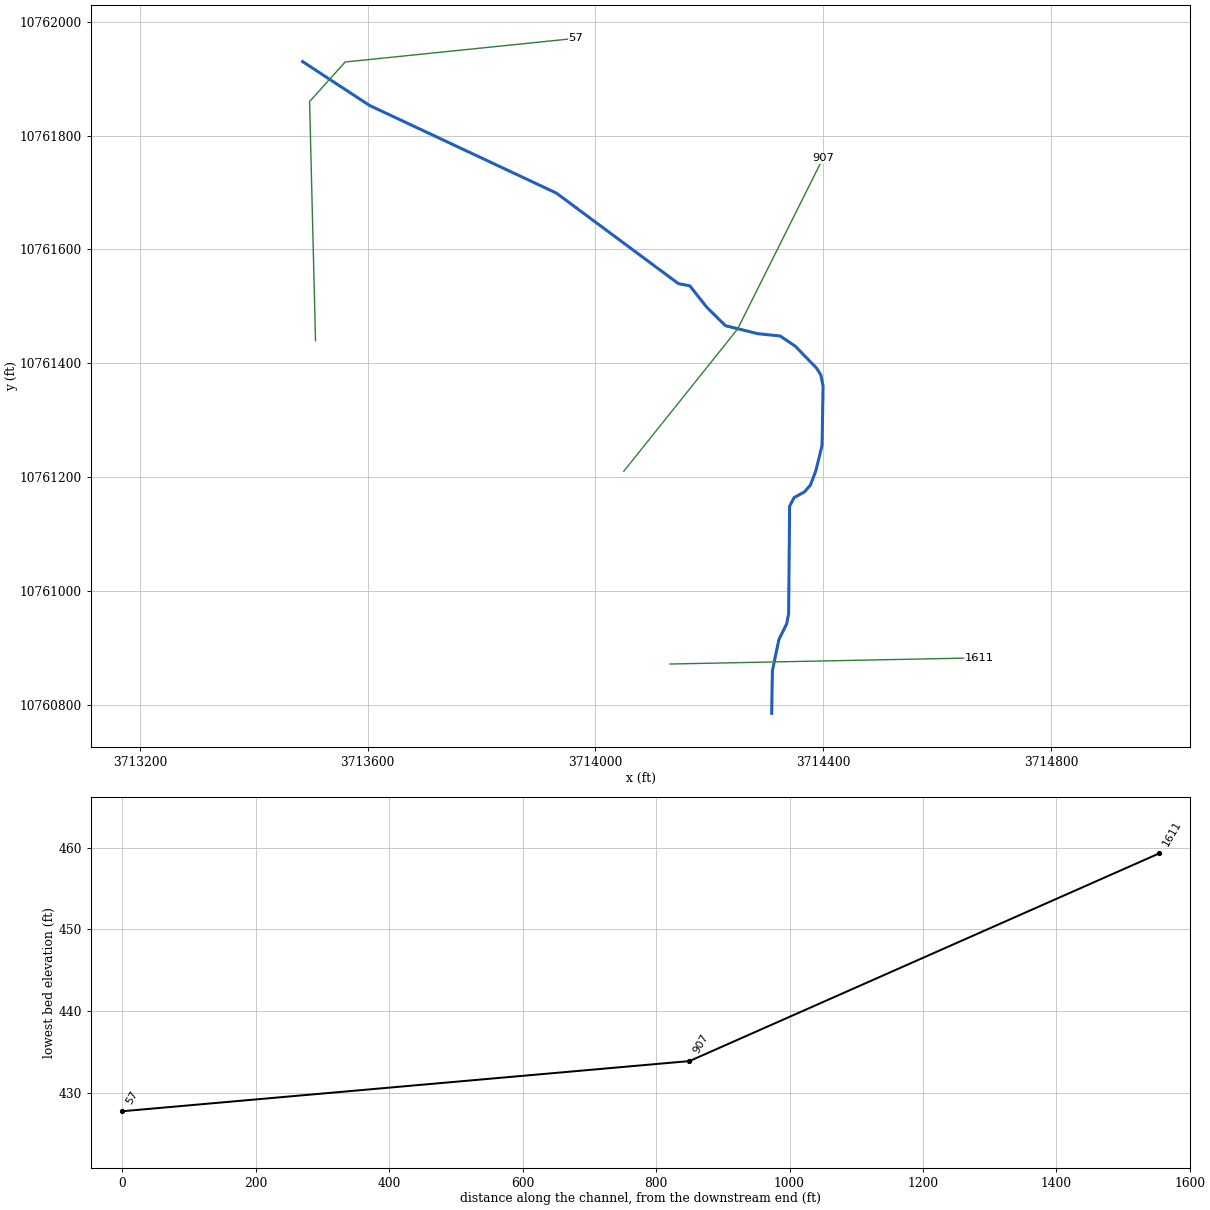
--- UNT 024 IN CACR.prj (project) ---

Proj Title=UNT 024 IN CACR Base Level Engineering
Current Plan=p01
Default Exp/Contr=0.3,0.1
English Units
Geom File=g01
Flow File=f01
Plan File=p01
BEGIN DESCRIPTION:
UNT 024 IN CACR
END DESCRIPTION:

--- UNT 024 IN CACR.p01 (plan) ---

Plan Title=Multiple Run
Short Identifier=Multiple
Geom File=g01
Flow File=f01
Subcritical Flow
K Sum by GR= 0
Std Step Tol= 0.01
Critical Tol= 0.01
Num of Std Step Trials= 20
Max Error Tol= 0.3
Flow Tol Ratio= 0.001
Split Flow NTrial= 30
Split Flow Tol= 0.02
Split Flow Ratio= 0.02
Log Output Level= 0
Friction Slope Method= 1
Unsteady Friction Slope Method= 2
Unsteady Bridges Friction Slope Method= 1
Parabolic Critical Depth
Global Vel Dist=  1 , 1 , 1
Global Log Level= 0
CheckData=True
Encroach Param= -1, 0, 0, 0
BEGIN DESCRIPTION:
Multiple Run
END DESCRIPTION:

--- UNT 024 IN CACR.f01 (steady flow) ---

Flow Title=Multiple
Number of Profiles=7
Profile Names=10-year,25-year,50-year,1pct_min,100-year,1pct_plu,500-year
River Rch & RM= UNT 024 IN CACR,Reach-1,1611
     240     308     361     313     423     572     577
Boundary for River Rch & Prof#=UNT 024 IN CACR,Reach-1,1
Up Type=0
Dn Type=3
Dn Slope=0.005
Boundary for River Rch & Prof#=UNT 024 IN CACR,Reach-1,2
Up Type=0
Dn Type=3
Dn Slope=0.005
Boundary for River Rch & Prof#=UNT 024 IN CACR,Reach-1,3
Up Type=0
Dn Type=3
Dn Slope=0.005
Boundary for River Rch & Prof#=UNT 024 IN CACR,Reach-1,4
Up Type=0
Dn Type=3
Dn Slope=0.005
Boundary for River Rch & Prof#=UNT 024 IN CACR,Reach-1,5
Up Type=0
Dn Type=3
Dn Slope=0.005
Boundary for River Rch & Prof#=UNT 024 IN CACR,Reach-1,6
Up Type=0
Dn Type=3
Dn Slope=0.005
Boundary for River Rch & Prof#=UNT 024 IN CACR,Reach-1,7
Up Type=0
Dn Type=3
Dn Slope=0.005

--- UNT 024 IN CACR.g01 (geometry) ---

Geom Title=Existing Conditions

River Reach=UNT 024 IN CACR,Reach-1
Reach XY= 24
      3714309.50     10760785.00      3714310.75     10760860.00
      3714322.25     10760915.00      3714335.75     10760942.00
      3714339.25     10760960.00      3714341.00     10761149.00
      3714348.75     10761164.00      3714367.00     10761174.00
      3714377.50     10761186.00      3714387.00     10761211.00
      3714398.00     10761256.00      3714399.75     10761360.00
      3714396.00     10761379.00      3714388.75     10761391.00
      3714351.00     10761430.00      3714324.25     10761448.00
      3714285.00     10761452.00      3714228.25     10761466.00
      3714195.00     10761499.00      3714165.75     10761536.00
      3714145.50     10761540.00      3713931.25     10761699.00
      3713603.00     10761853.00      3713485.50     10761930.00

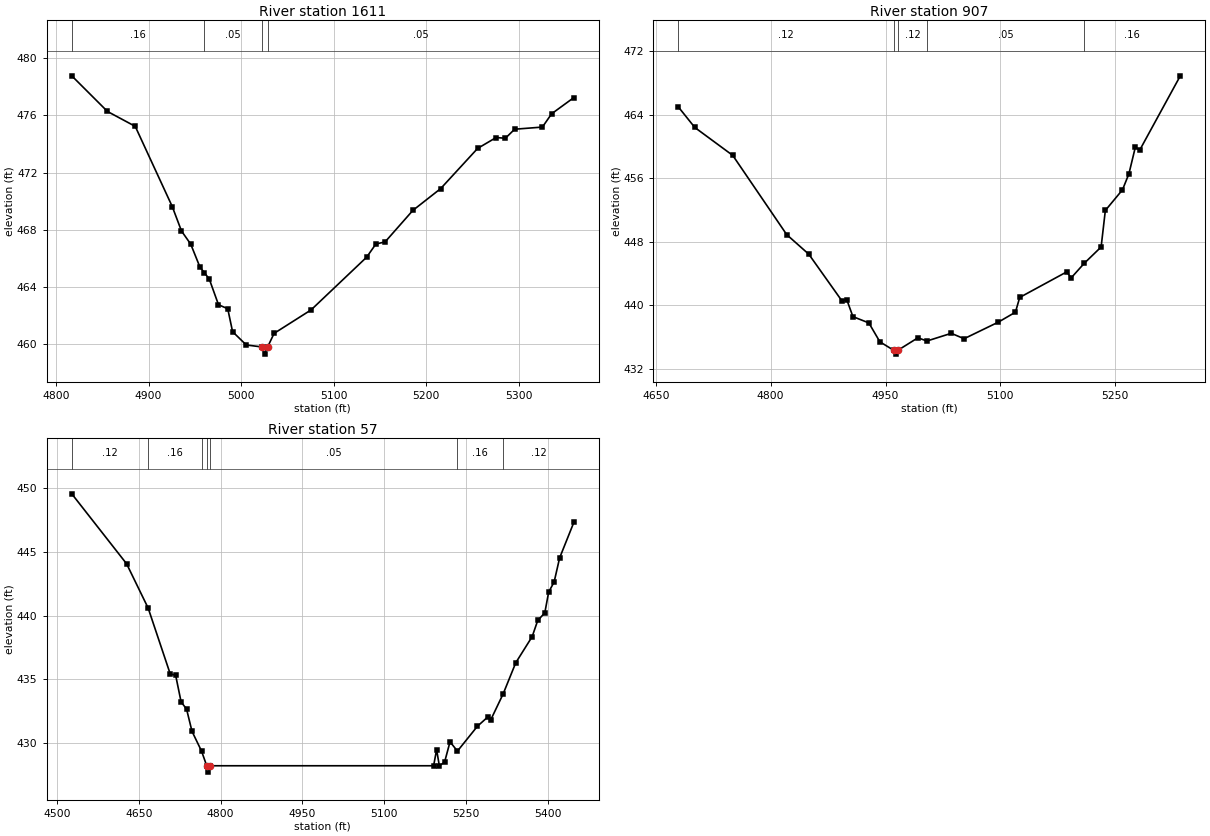
Type RM Length L Ch R = 1,1611,704,704,704
BEGIN DESCRIPTION:
UNT 024 IN CACR 3.0
END DESCRIPTION:
XS GIS Cut Line= 2
      3714131.00     10760871.71      3714673.59     10760882.56
#Sta/Elev= 30
  4817.0  478.76  4855.6  476.27  4885.6  475.23  4925.6  469.63  4935.6  467.92
  4945.6  467.00  4955.6  465.39  4960.4  465.00  4965.6  464.57  4975.6  462.77
  4985.6  462.49  4990.8  460.89  5005.6  459.96  5022.7  459.82  5025.4  459.32
  5028.7  459.82  5035.7  460.77  5075.7  462.41  5135.7  466.09  5145.7  467.01
  5155.7  467.16  5185.7  469.36  5215.7  470.88  5255.7  473.69  5275.7  474.45
  5285.7  474.40  5295.7  475.03  5325.7  475.18  5335.7  476.11  5359.7  477.24
#Mann=4,-1,0
  4817.0    0.16       0  4960.4    0.05       0  5022.7    0.04       0
  5028.7    0.05       0
Bank Sta=5022.7,5028.7
Exp/Cntr=0.3,0.1

Type RM Length L Ch R = 1,907,850,850,850
BEGIN DESCRIPTION:
UNT 024 IN CACR 2.0
END DESCRIPTION:
XS GIS Cut Line= 3
      3714049.61     10761210.19      3714249.61     10761460.19
      3714399.62     10761760.21
#Sta/Elev= 30
  4679.3  465.00  4700.9  462.40  4750.5  458.88  4821.0  448.90  4849.8  446.44
  4893.0  440.57  4899.4  440.71  4907.4  438.58  4928.2  437.79  4942.6  435.41
  4960.4  434.36  4963.2  433.86  4966.4  434.36  4992.3  435.92  5004.0  435.51
  5035.8  436.48  5052.6  435.80  5097.3  437.89  5119.6  439.14  5125.2  441.00
  5186.7  444.22  5192.3  443.45  5209.5  445.30  5231.5  447.35  5237.0  451.95
  5259.4  454.55  5267.8  456.57  5276.2  459.93  5281.8  459.53  5334.9  468.90
#Mann=5,-1,0
  4679.3    0.12       0  4960.4    0.07       0  4966.4    0.12       0
  5004.0    0.05       0  5209.5    0.16       0
Bank Sta=4960.4,4966.4
Exp/Cntr=0.3,0.1

Type RM Length L Ch R = 1,57,0,0,0
BEGIN DESCRIPTION:
UNT 024 IN CACR 1.0
END DESCRIPTION:
XS GIS Cut Line= 4
      3713508.18     10761439.64      3713497.77     10761859.81
      3713560.27     10761929.26      3713965.61     10761970.83
#Sta/Elev= 30
  4527.1  449.55  4627.7  444.06  4667.3  440.58  4707.7  435.42  4717.7  435.31
  4727.7  433.22  4737.7  432.66  4747.7  430.91  4765.2  429.36  4774.7  428.21
  4777.5  427.71  4780.7  428.21  5191.0  428.21  5196.5  429.47  5201.5  428.21
  5211.1  428.49  5221.1  430.09  5234.7  429.36  5271.4  431.31  5290.7  432.05
  5295.7  431.80  5318.7  433.86  5341.7  436.29  5371.9  438.35  5382.0  439.61
  5395.0  440.21  5402.1  441.84  5412.1  442.63  5422.2  444.52  5448.3  447.31
#Mann=7,-1,0
  4527.1    0.12       0  4667.3    0.16       0  4765.2    0.05       0
  4774.7   0.033       0  4780.7    0.05       0  5234.7    0.16       0
  5318.7    0.12       0
Bank Sta=4774.7,4780.7
Exp/Cntr=0.3,0.1

Chan Stop Cuts=-1