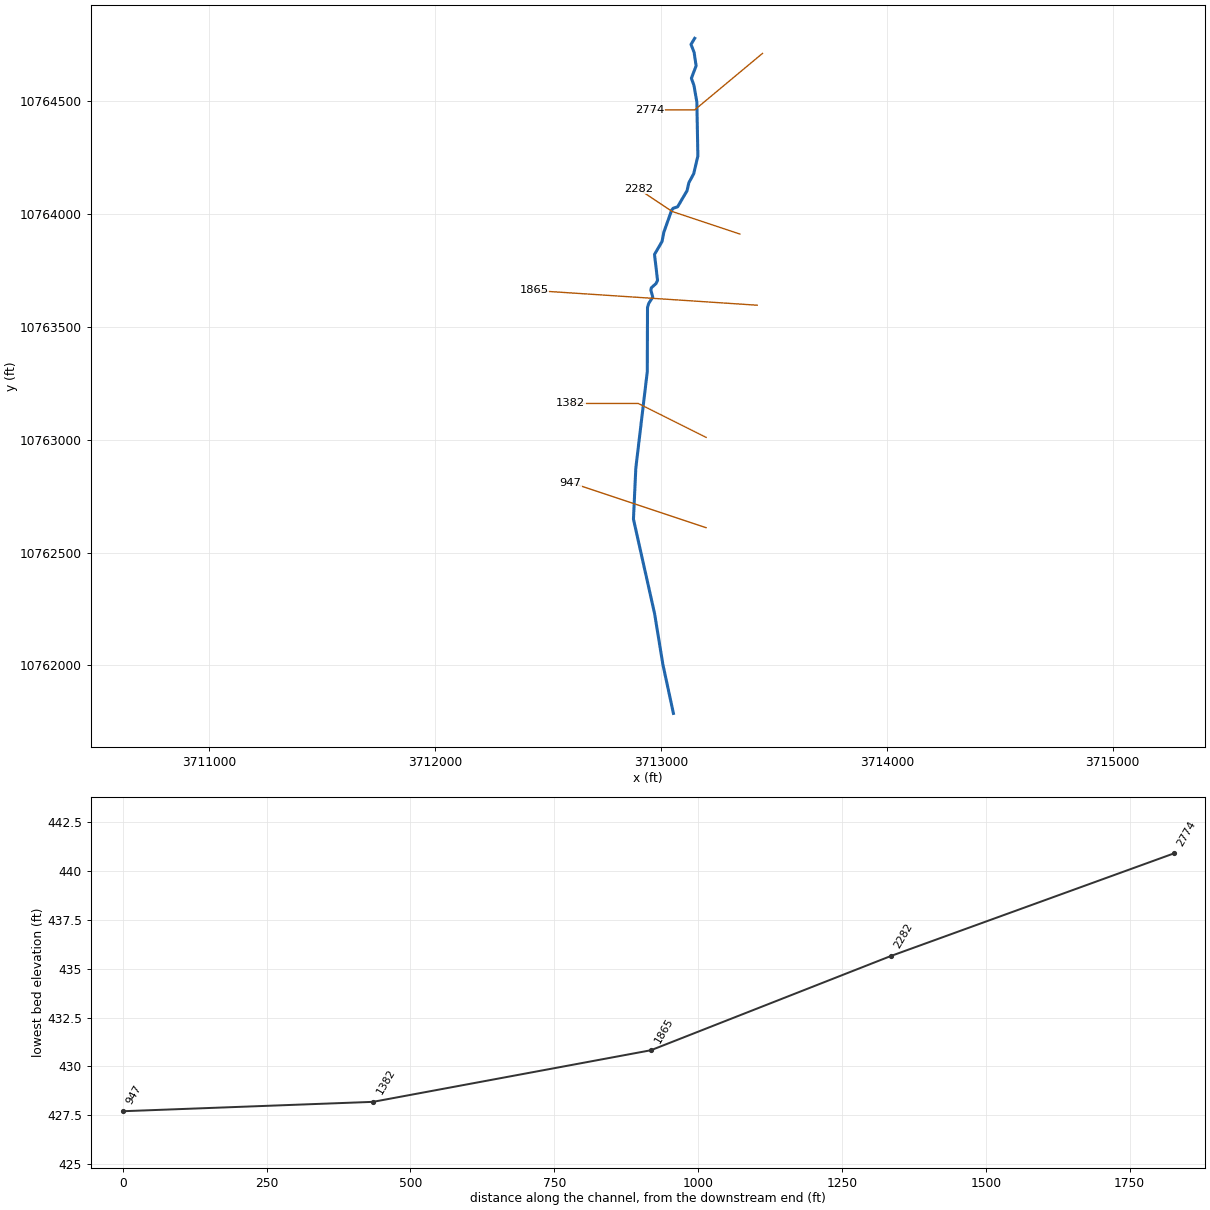
--- UNT 025 IN CACR.prj (project) ---

Proj Title=UNT 025 IN CACR Base Level Engineering
Current Plan=p01
Default Exp/Contr=0.3,0.1
English Units
Geom File=g01
Flow File=f01
Plan File=p01
BEGIN DESCRIPTION:
UNT 025 IN CACR
END DESCRIPTION:

--- UNT 025 IN CACR.p01 (plan) ---

Plan Title=Multiple Run
Short Identifier=Multiple
Geom File=g01
Flow File=f01
Subcritical Flow
K Sum by GR= 0
Std Step Tol= 0.01
Critical Tol= 0.01
Num of Std Step Trials= 20
Max Error Tol= 0.3
Flow Tol Ratio= 0.001
Split Flow NTrial= 30
Split Flow Tol= 0.02
Split Flow Ratio= 0.02
Log Output Level= 0
Friction Slope Method= 1
Unsteady Friction Slope Method= 2
Unsteady Bridges Friction Slope Method= 1
Parabolic Critical Depth
Global Vel Dist=  1 , 1 , 1
Global Log Level= 0
CheckData=True
Encroach Param= -1, 0, 0, 0
BEGIN DESCRIPTION:
Multiple Run
END DESCRIPTION:

--- UNT 025 IN CACR.f01 (steady flow) ---

Flow Title=Multiple
Number of Profiles=7
Profile Names=10-year,25-year,50-year,1pct_min,100-year,1pct_plu,500-year
River Rch & RM= UNT 025 IN CACR,Reach-1,2774
     278     359     422     366     495     670     680
Boundary for River Rch & Prof#=UNT 025 IN CACR,Reach-1,1
Up Type=0
Dn Type=3
Dn Slope=0.005
Boundary for River Rch & Prof#=UNT 025 IN CACR,Reach-1,2
Up Type=0
Dn Type=3
Dn Slope=0.005
Boundary for River Rch & Prof#=UNT 025 IN CACR,Reach-1,3
Up Type=0
Dn Type=3
Dn Slope=0.005
Boundary for River Rch & Prof#=UNT 025 IN CACR,Reach-1,4
Up Type=0
Dn Type=3
Dn Slope=0.005
Boundary for River Rch & Prof#=UNT 025 IN CACR,Reach-1,5
Up Type=0
Dn Type=3
Dn Slope=0.005
Boundary for River Rch & Prof#=UNT 025 IN CACR,Reach-1,6
Up Type=0
Dn Type=3
Dn Slope=0.005
Boundary for River Rch & Prof#=UNT 025 IN CACR,Reach-1,7
Up Type=0
Dn Type=3
Dn Slope=0.005

--- UNT 025 IN CACR.g01 (geometry) ---

Geom Title=Existing Conditions

River Reach=UNT 025 IN CACR,Reach-1
Reach XY= 30
      3713149.35     10764776.81      3713133.00     10764750.00
      3713146.75     10764715.00      3713155.75     10764655.00
      3713134.75     10764600.00      3713146.00     10764569.00
      3713159.00     10764495.00      3713163.50     10764256.00
      3713145.00     10764177.00      3713123.75     10764138.00
      3713115.50     10764102.00      3713073.75     10764031.00
      3713053.50     10764024.00      3713047.50     10764016.00
      3713013.00     10763919.00      3713004.75     10763877.00
      3712971.50     10763820.00      3712985.00     10763705.00
      3712978.00     10763691.00      3712957.25     10763672.00
      3712955.50     10763661.00      3712963.75     10763631.00
      3712945.75     10763603.00      3712940.50     10763585.00
      3712939.50     10763301.00      3712888.75     10762874.00
      3712878.25     10762648.00      3712972.00     10762229.00
      3713008.50     10762005.00      3713055.25     10761788.00

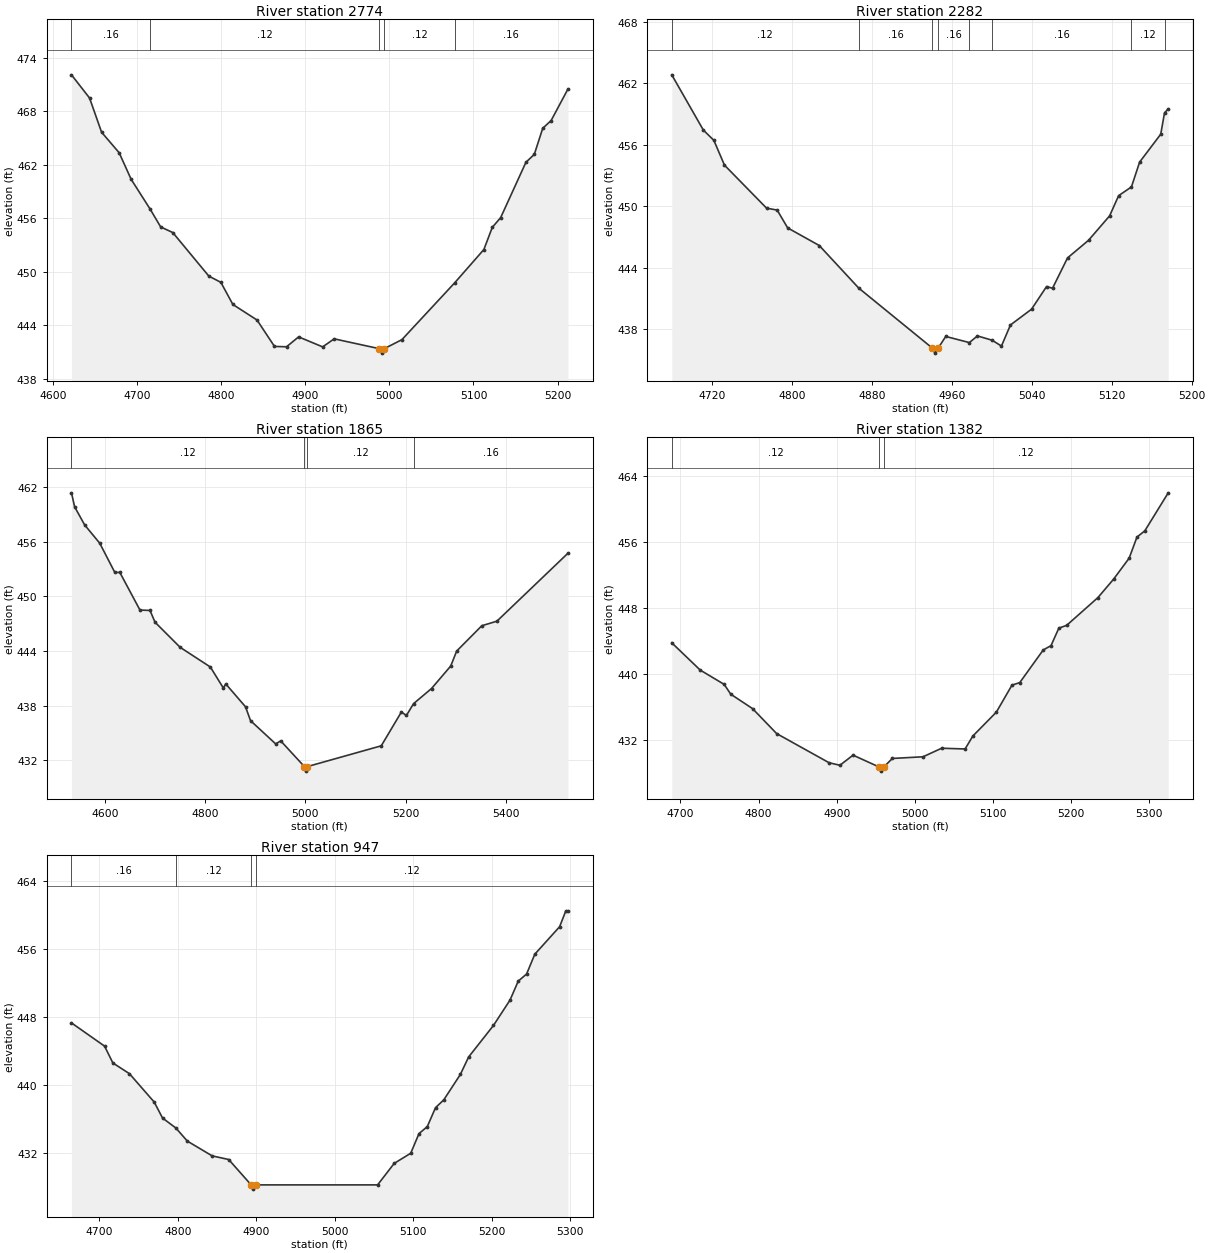
Type RM Length L Ch R = 1,2774,492,492,492
BEGIN DESCRIPTION:
UNT 025 IN CACR 6.0
END DESCRIPTION:
XS GIS Cut Line= 3
      3713449.64     10764710.22      3713149.61     10764460.19
      3712949.57     10764460.19
#Sta/Elev= 30
  4621.8  472.08  4643.3  469.48  4657.6  465.65  4678.5  463.35  4692.8  460.37
  4715.2  457.06  4727.9  455.04  4742.3  454.41  4785.2  449.53  4799.5  448.83
  4813.8  446.35  4842.5  444.61  4863.3  441.65  4877.6  441.61  4892.0  442.72
  4920.6  441.60  4934.3  442.50  4987.9  441.40  4990.6  440.90  4993.9  441.40
  5014.9  442.41  5077.6  448.77  5112.4  452.51  5122.4  454.99  5132.4  456.09
  5162.4  462.28  5172.4  463.17  5182.4  466.09  5192.4  466.96  5212.4  470.49
#Mann=5,-1,0
  4621.8    0.16       0  4715.2    0.12       0  4987.9    0.07       0
  4993.9    0.12       0  5077.6    0.16       0
Bank Sta=4987.9,4993.9
Exp/Cntr=0.3,0.1

Type RM Length L Ch R = 1,2282,417,417,417
BEGIN DESCRIPTION:
UNT 025 IN CACR 5.0
END DESCRIPTION:
XS GIS Cut Line= 3
      3713349.58     10763910.20      3713049.61     10764010.19
      3712899.59     10764110.20
#Sta/Elev= 30
  4680.0  462.83  4711.6  457.43  4722.1  456.43  4732.7  454.01  4774.8  449.81
  4785.4  449.62  4795.9  447.88  4827.5  446.16  4867.0  442.00  4940.5  436.15
  4943.2  435.65  4946.5  436.15  4954.0  437.28  4977.6  436.68  4985.7  437.33
  5000.4  436.91  5009.7  436.34  5018.7  438.40  5039.8  439.94  5054.8  442.15
  5060.8  441.99  5075.8  444.95  5096.8  446.67  5117.9  449.06  5126.9  451.03
  5139.7  451.88  5147.9  454.31  5169.0  457.03  5172.8  459.12  5176.5  459.50
#Mann=8,-1,0
  4680.0    0.12       0  4867.0    0.16       0  4940.5    0.07       0
  4946.5    0.16       0  4977.6    0.12       0  5000.4    0.16       0
  5139.7    0.12       0  5172.8    0.16       0
Bank Sta=4940.5,4946.5
Exp/Cntr=0.3,0.1

Type RM Length L Ch R = 1,1865,483,483,483
BEGIN DESCRIPTION:
UNT 025 IN CACR 4.0
END DESCRIPTION:
XS GIS Cut Line= 2
      3713425.77     10763595.23      3712438.31     10763660.34
#Sta/Elev= 30
  4533.7  461.38  4539.9  459.85  4559.9  457.86  4590.0  455.85  4620.0  452.65
  4630.1  452.64  4670.2  448.51  4690.2  448.47  4700.2  447.18  4750.3  444.42
  4810.5  442.26  4836.3  439.96  4841.3  440.40  4880.6  437.89  4890.6  436.37
  4940.7  433.82  4950.8  434.15  4997.9  431.33  5000.6  430.83  5003.9  431.33
  5151.2  433.61  5191.3  437.32  5201.3  436.94  5215.6  438.24  5251.4  439.90
  5289.7  442.37  5301.5  444.01  5351.6  446.79  5381.7  447.29  5523.3  454.75
#Mann=4,-1,0
  4533.7    0.12       0  4997.9    0.07       0  5003.9    0.12       0
  5215.6    0.16       0
Bank Sta=4997.9,5003.9
Exp/Cntr=0.3,0.1

Type RM Length L Ch R = 1,1382,435,435,435
BEGIN DESCRIPTION:
UNT 025 IN CACR 3.0
END DESCRIPTION:
XS GIS Cut Line= 3
      3713199.63     10763010.18      3712899.61     10763160.19
      3712599.65     10763160.19
#Sta/Elev= 30
  4689.0  443.77  4725.4  440.46  4756.1  438.72  4764.5  437.53  4792.4  435.78
  4823.2  432.75  4890.3  429.21  4904.2  428.90  4921.0  430.13  4954.4  428.69
  4957.1  428.19  4960.4  428.69  4971.3  429.73  5010.5  429.93  5034.4  430.97
  5064.4  430.88  5074.4  432.46  5104.4  435.35  5124.4  438.63  5134.4  438.94
  5164.4  442.90  5174.4  443.43  5184.4  445.55  5194.4  445.89  5234.4  449.26
  5254.4  451.49  5274.4  454.05  5284.4  456.61  5294.4  457.36  5324.4  461.98
#Mann=3,-1,0
  4689.0    0.12       0  4954.4    0.07       0  4960.4    0.12       0
Bank Sta=4954.4,4960.4
Exp/Cntr=0.3,0.1

Type RM Length L Ch R = 1,947,0,0,0
BEGIN DESCRIPTION:
UNT 025 IN CACR 2.0
END DESCRIPTION:
XS GIS Cut Line= 3
      3713199.61     10762610.19      3712899.61     10762710.19
      3712599.57     10762810.20
#Sta/Elev= 30
  4664.6  447.30  4706.8  444.56  4717.3  442.58  4738.4  441.32  4770.0  437.97
  4780.6  436.09  4797.5  434.92  4812.2  433.37  4843.8  431.63  4864.9  431.20
  4893.5  428.21  4896.3  427.71  4899.5  428.21  5054.6  428.21  5075.7  430.74
  5096.8  431.94  5107.3  434.25  5117.9  435.08  5128.4  437.31  5138.9  438.23
  5160.0  441.22  5170.6  443.29  5202.2  447.00  5223.3  449.99  5233.8  452.23
  5244.4  453.06  5254.9  455.40  5286.5  458.64  5294.4  460.51  5297.1  460.51
#Mann=4,-1,0
  4664.6    0.16       0  4797.5    0.12       0  4893.5    0.07       0
  4899.5    0.12       0
Bank Sta=4893.5,4899.5
Exp/Cntr=0.3,0.1

Chan Stop Cuts=-1