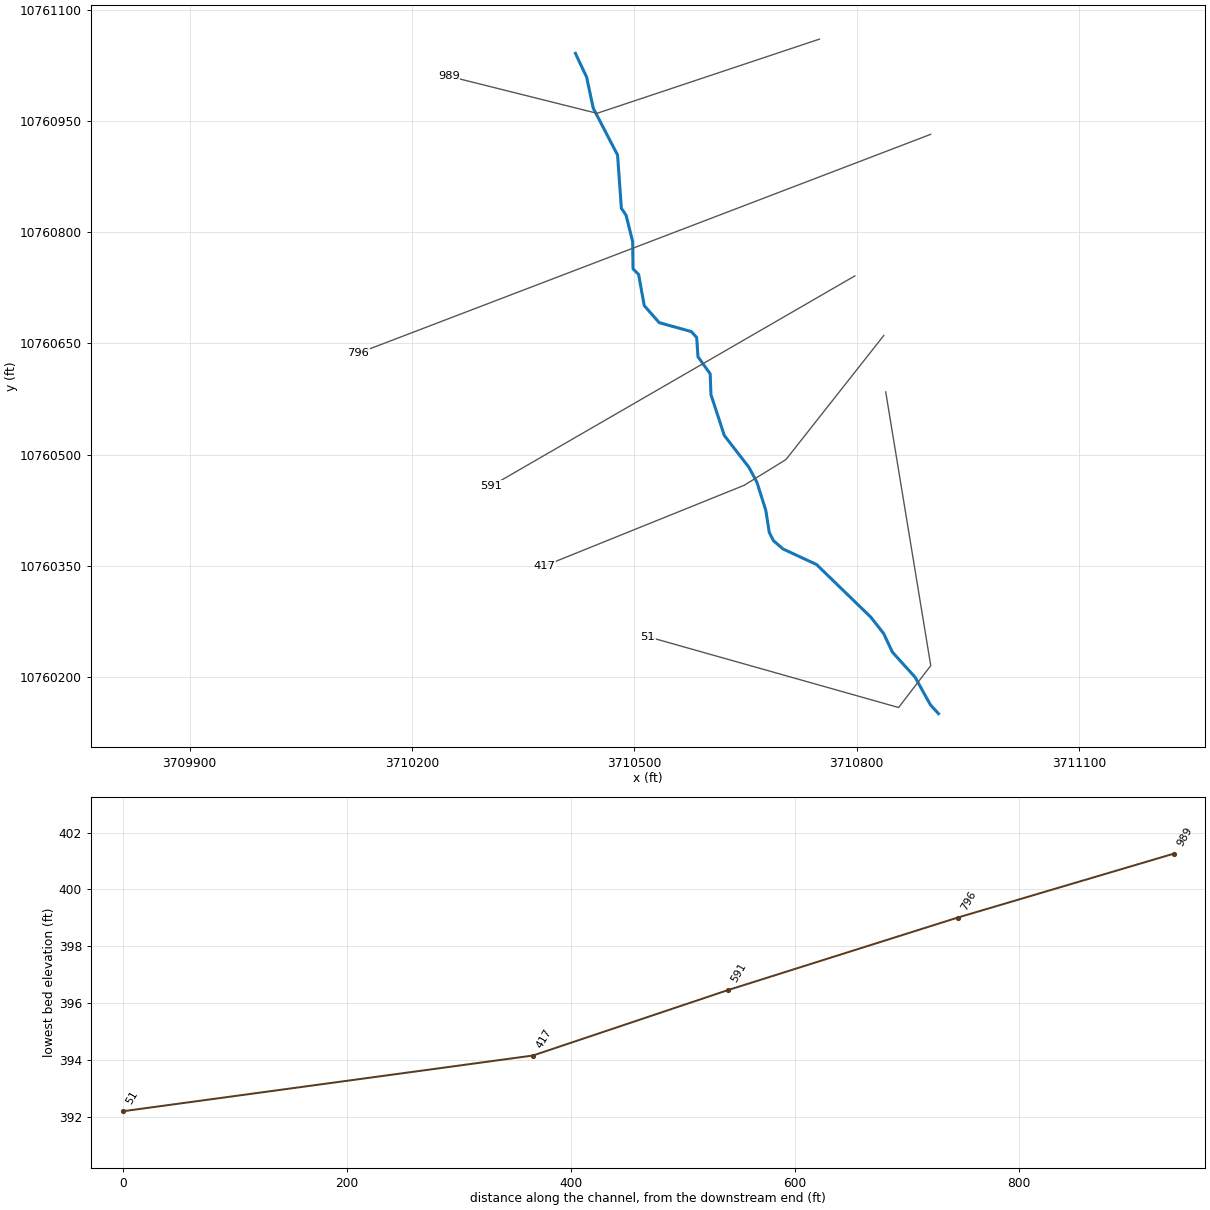
--- UNT 026 IN CACR.prj (project) ---

Proj Title=UNT 026 IN CACR Base Level Engineering
Current Plan=p01
Default Exp/Contr=0.3,0.1
English Units
Geom File=g01
Flow File=f01
Plan File=p01
BEGIN DESCRIPTION:
UNT 026 IN CACR
END DESCRIPTION:

--- UNT 026 IN CACR.p01 (plan) ---

Plan Title=Multiple Run
Short Identifier=Multiple
Geom File=g01
Flow File=f01
Subcritical Flow
K Sum by GR= 0
Std Step Tol= 0.01
Critical Tol= 0.01
Num of Std Step Trials= 20
Max Error Tol= 0.3
Flow Tol Ratio= 0.001
Split Flow NTrial= 30
Split Flow Tol= 0.02
Split Flow Ratio= 0.02
Log Output Level= 0
Friction Slope Method= 1
Unsteady Friction Slope Method= 2
Unsteady Bridges Friction Slope Method= 1
Parabolic Critical Depth
Global Vel Dist=  1 , 1 , 1
Global Log Level= 0
CheckData=True
Encroach Param= -1, 0, 0, 0
BEGIN DESCRIPTION:
Multiple Run
END DESCRIPTION:

--- UNT 026 IN CACR.f01 (steady flow) ---

Flow Title=Multiple
Number of Profiles=7
Profile Names=10-year,25-year,50-year,1pct_min,100-year,1pct_plu,500-year
River Rch & RM= UNT 026 IN CACR,Reach-1,989
     327     429     511     448     606     820     853
River Rch & RM= UNT 026 IN CACR,Reach-1,51
    1040    1446    1789    1621    2192    2964    3298
Boundary for River Rch & Prof#=UNT 026 IN CACR,Reach-1,1
Up Type=0
Dn Type=3
Dn Slope=0.005
Boundary for River Rch & Prof#=UNT 026 IN CACR,Reach-1,2
Up Type=0
Dn Type=3
Dn Slope=0.005
Boundary for River Rch & Prof#=UNT 026 IN CACR,Reach-1,3
Up Type=0
Dn Type=3
Dn Slope=0.005
Boundary for River Rch & Prof#=UNT 026 IN CACR,Reach-1,4
Up Type=0
Dn Type=3
Dn Slope=0.005
Boundary for River Rch & Prof#=UNT 026 IN CACR,Reach-1,5
Up Type=0
Dn Type=3
Dn Slope=0.005
Boundary for River Rch & Prof#=UNT 026 IN CACR,Reach-1,6
Up Type=0
Dn Type=3
Dn Slope=0.005
Boundary for River Rch & Prof#=UNT 026 IN CACR,Reach-1,7
Up Type=0
Dn Type=3
Dn Slope=0.005

--- UNT 026 IN CACR.g01 (geometry) ---

Geom Title=Existing Conditions

River Reach=UNT 026 IN CACR,Reach-1
Reach XY= 30
      3710420.43     10761040.98      3710435.50     10761009.00
      3710444.50     10760967.00      3710477.25     10760904.00
      3710482.42     10760832.13      3710488.76     10760822.76
      3710497.67     10760787.13      3710498.11     10760750.60
      3710505.68     10760743.03      3710513.25     10760701.00
      3710533.50     10760678.00      3710576.75     10760666.00
      3710584.00     10760658.00      3710585.75     10760632.00
      3710602.25     10760609.00      3710603.25     10760581.00
      3710621.25     10760526.00      3710654.50     10760483.00
      3710665.25     10760463.00      3710677.25     10760425.00
      3710682.00     10760395.00      3710687.75     10760384.00
      3710700.50     10760373.00      3710745.75     10760352.00
      3710819.00     10760281.00      3710836.25     10760259.00
      3710848.00     10760234.00      3710878.75     10760200.00
      3710899.25     10760163.00      3710910.25     10760151.00

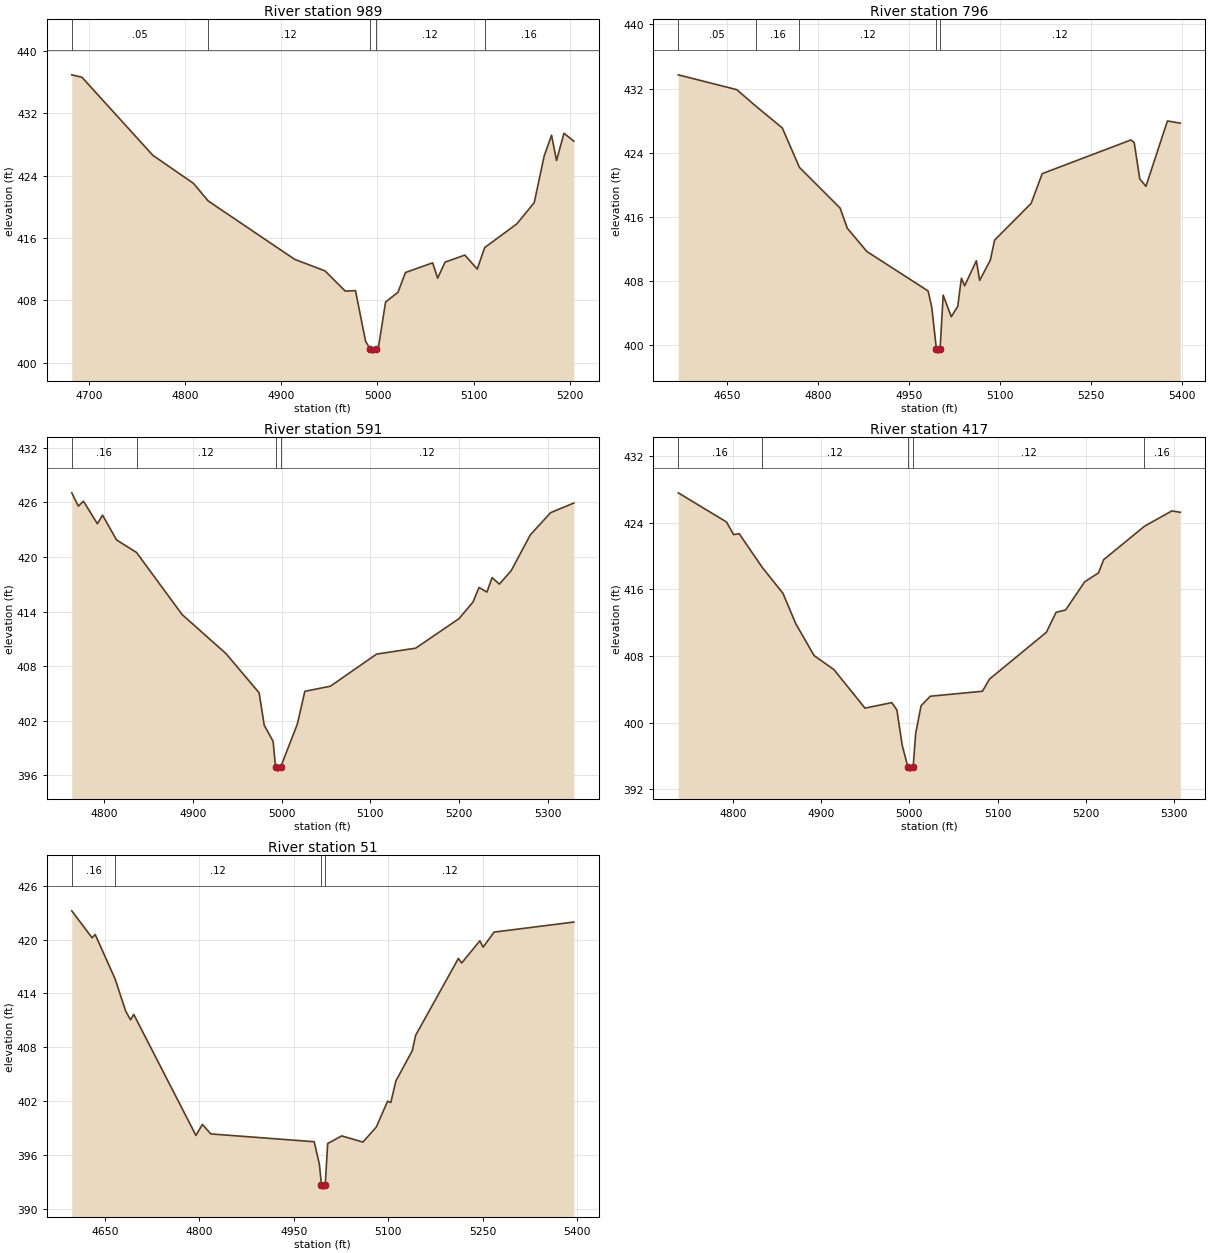
Type RM Length L Ch R = 1,989,193,193,193
BEGIN DESCRIPTION:
UNT 026 IN CACR 2.0
END DESCRIPTION:
XS GIS Cut Line= 3
      3710749.62     10761060.19      3710449.61     10760960.19
      3710249.61     10761010.19
#Sta/Elev= 30
  4681.9  436.89  4692.5  436.58  4766.2  426.59  4808.4  423.01  4823.9  420.74
  4913.8  413.27  4945.4  411.79  4966.5  409.20  4977.1  409.26  4987.6  402.78
  4992.5  401.76  4995.3  401.26  4998.5  401.76  5000.7  401.76  5008.4  407.80
  5021.3  409.05  5029.1  411.58  5057.4  412.82  5062.6  410.86  5070.3  412.91
  5090.9  413.81  5103.8  412.02  5111.5  414.77  5145.0  417.81  5163.1  420.53
  5173.4  426.49  5181.1  429.16  5186.3  425.91  5194.0  429.41  5204.3  428.40
#Mann=5,-1,0
  4681.9    0.05       0  4823.9    0.12       0  4992.5    0.07       0
  4998.5    0.12       0  5111.5    0.16       0
Bank Sta=4992.5,4998.5
Exp/Cntr=0.3,0.1

Type RM Length L Ch R = 1,796,205,205,205
BEGIN DESCRIPTION:
Mapping XS 8caa8df3
END DESCRIPTION:
XS GIS Cut Line= 2
      3710899.74     10760931.87      3710127.19     10760636.74
#Sta/Elev= 30
  4569.7  433.71  4666.2  431.86  4697.0  429.84  4741.1  427.09  4769.3  422.17
  4836.4  417.09  4848.2  414.58  4880.3  411.69  4981.3  406.76  4987.3  404.73
  4995.0  399.51  4997.8  399.01  5001.0  399.51  5006.1  406.24  5019.4  403.55
  5030.1  404.84  5036.1  408.35  5041.5  407.41  5060.8  410.53  5066.2  408.08
  5083.7  410.59  5090.9  413.11  5151.0  417.68  5169.3  421.39  5315.4  425.59
  5320.8  425.25  5329.9  420.74  5340.1  419.81  5375.5  427.96  5396.7  427.68
#Mann=5,-1,0
  4569.7    0.05       0  4697.0    0.16       0  4769.3    0.12       0
  4995.0    0.07       0  5001.0    0.12       0
Bank Sta=4995,5001
Exp/Cntr=0.3,0.1

Type RM Length L Ch R = 1,591,174,174,174
BEGIN DESCRIPTION:
Mapping XS fac80795
END DESCRIPTION:
XS GIS Cut Line= 2
      3710797.32     10760741.01      3710306.91     10760457.83
#Sta/Elev= 30
  4763.4  427.04  4770.8  425.58  4776.6  426.12  4792.3  423.64  4798.1  424.59
  4813.9  421.87  4836.5  420.48  4887.8  413.67  4937.4  409.37  4974.7  405.07
  4980.5  401.50  4990.5  399.73  4993.2  396.96  4996.0  396.46  4999.2  396.96
  5017.8  401.62  5026.3  405.23  5055.1  405.79  5107.2  409.32  5151.3  409.97
  5200.2  413.22  5215.9  415.03  5222.7  416.64  5231.7  416.14  5237.5  417.73
  5245.7  417.01  5259.0  418.48  5280.6  422.42  5303.5  424.86  5329.7  425.92
#Mann=4,-1,0
  4763.4    0.16       0  4836.5    0.12       0  4993.2    0.07       0
  4999.2    0.12       0
Bank Sta=4993.2,4999.2
Exp/Cntr=0.3,0.1

Type RM Length L Ch R = 1,417,366,366,366
BEGIN DESCRIPTION:
Mapping XS f499074f
END DESCRIPTION:
XS GIS Cut Line= 4
      3710836.42     10760660.75      3710704.47     10760493.52
      3710648.05     10760458.79      3710378.97     10760350.29
#Sta/Elev= 30
  4737.9  427.60  4792.6  424.10  4800.7  422.58  4807.0  422.69  4833.2  418.64
  4856.7  415.52  4871.2  411.87  4892.0  408.04  4914.5  406.36  4949.7  401.73
  4980.1  402.39  4985.9  401.50  4991.9  397.28  4998.3  394.66  5001.1  394.16
  5004.3  394.66  5007.2  398.70  5013.3  402.02  5023.8  403.16  5082.9  403.76
  5091.0  405.23  5155.4  410.84  5166.4  413.24  5177.2  413.52  5198.8  416.90
  5214.5  417.98  5220.4  419.57  5266.6  423.58  5297.7  425.43  5307.3  425.26
#Mann=5,-1,0
  4737.9    0.16       0  4833.2    0.12       0  4998.3    0.07       0
  5004.3    0.12       0  5266.6    0.16       0
Bank Sta=4998.3,5004.3
Exp/Cntr=0.3,0.1

Type RM Length L Ch R = 1,51,0,0,0
BEGIN DESCRIPTION:
UNT 026 IN CACR 1.0
END DESCRIPTION:
XS GIS Cut Line= 4
      3710839.01     10760584.70      3710899.78     10760215.74
      3710856.38     10760159.31      3710517.81     10760254.81
#Sta/Elev= 30
  4597.7  423.20  4629.9  420.20  4634.9  420.56  4666.5  415.61  4683.3  412.02
  4691.0  411.06  4696.1  411.66  4794.8  398.18  4805.0  399.41  4818.4  398.35
  4982.5  397.48  4990.7  394.98  4994.0  392.70  4996.8  392.20  5000.0  392.70
  5003.9  397.28  5026.1  398.13  5059.8  397.44  5081.0  399.11  5099.0  401.99
  5104.1  401.85  5112.2  404.26  5138.2  407.62  5143.4  409.32  5211.4  417.90
  5216.6  417.39  5245.4  419.86  5250.6  419.15  5268.0  420.83  5394.6  421.95
#Mann=4,-1,0
  4597.7    0.16       0  4666.5    0.12       0  4994.0    0.07       0
  5000.0    0.12       0
Bank Sta=4994,5000
Exp/Cntr=0.3,0.1

Chan Stop Cuts=-1