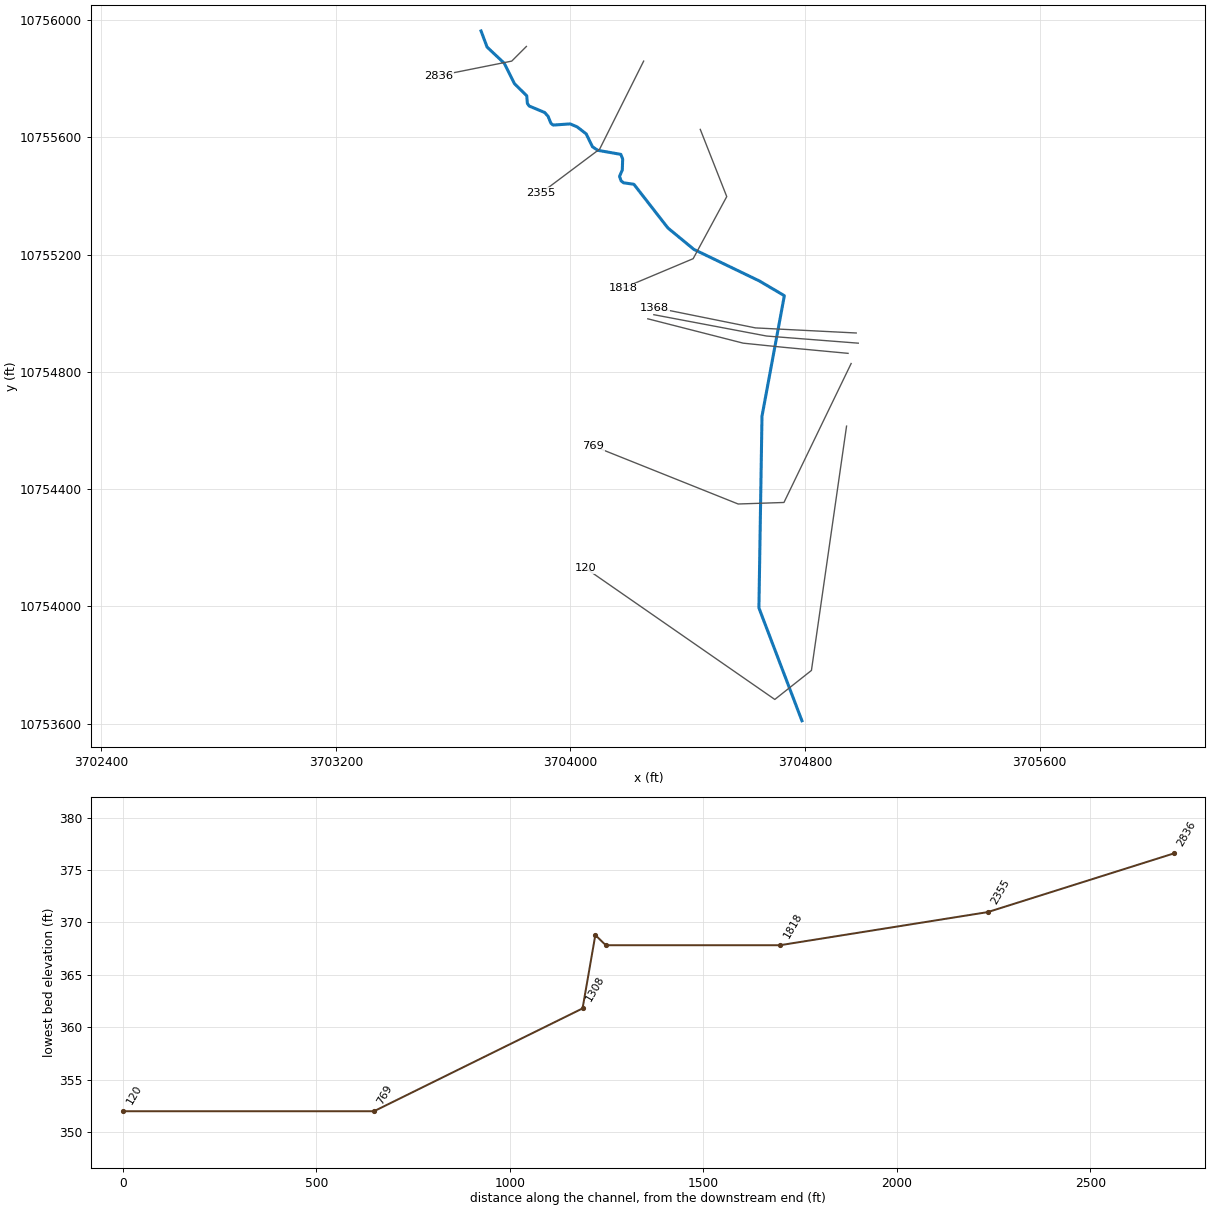
--- UNT 027 IN CACR.prj (project) ---

Proj Title=UNT 027 IN CACR Base Level Engineering
Current Plan=p01
Default Exp/Contr=0.3,0.1
English Units
Geom File=g01
Flow File=f01
Plan File=p01
BEGIN DESCRIPTION:
UNT 027 IN CACR
END DESCRIPTION:

--- UNT 027 IN CACR.p01 (plan) ---

Plan Title=Multiple Run
Short Identifier=Multiple
Geom File=g01
Flow File=f01
Subcritical Flow
K Sum by GR= 0
Std Step Tol= 0.01
Critical Tol= 0.01
Num of Std Step Trials= 20
Max Error Tol= 0.3
Flow Tol Ratio= 0.001
Split Flow NTrial= 30
Split Flow Tol= 0.02
Split Flow Ratio= 0.02
Log Output Level= 0
Friction Slope Method= 1
Unsteady Friction Slope Method= 2
Unsteady Bridges Friction Slope Method= 1
Parabolic Critical Depth
Global Vel Dist=  1 , 1 , 1
Global Log Level= 0
CheckData=True
Encroach Param= -1, 0, 0, 0
BEGIN DESCRIPTION:
Multiple Run
END DESCRIPTION:

--- UNT 027 IN CACR.f01 (steady flow) ---

Flow Title=Multiple
Number of Profiles=7
Profile Names=10-year,25-year,50-year,1pct_min,100-year,1pct_plu,500-year
River Rch & RM= UNT 027 IN CACR,Reach-1,2836
     444     594     716     636     860    1163    1239
Boundary for River Rch & Prof#=UNT 027 IN CACR,Reach-1,1
Up Type=0
Dn Type=3
Dn Slope=0.005
Boundary for River Rch & Prof#=UNT 027 IN CACR,Reach-1,2
Up Type=0
Dn Type=3
Dn Slope=0.005
Boundary for River Rch & Prof#=UNT 027 IN CACR,Reach-1,3
Up Type=0
Dn Type=3
Dn Slope=0.005
Boundary for River Rch & Prof#=UNT 027 IN CACR,Reach-1,4
Up Type=0
Dn Type=3
Dn Slope=0.005
Boundary for River Rch & Prof#=UNT 027 IN CACR,Reach-1,5
Up Type=0
Dn Type=3
Dn Slope=0.005
Boundary for River Rch & Prof#=UNT 027 IN CACR,Reach-1,6
Up Type=0
Dn Type=3
Dn Slope=0.005
Boundary for River Rch & Prof#=UNT 027 IN CACR,Reach-1,7
Up Type=0
Dn Type=3
Dn Slope=0.005

--- UNT 027 IN CACR.g01 (geometry) ---

Geom Title=Existing Conditions

River Reach=UNT 027 IN CACR,Reach-1
Reach XY= 30
      3703694.89     10755963.07      3703715.50     10755908.00
      3703774.00     10755853.00      3703809.00     10755783.00
      3703850.75     10755742.00      3703853.00     10755716.00
      3703859.00     10755707.00      3703911.75     10755685.00
      3703923.50     10755672.00      3703933.25     10755648.00
      3703941.00     10755642.00      3703998.75     10755646.00
      3704022.50     10755636.00      3704053.50     10755612.00
      3704075.00     10755568.00      3704092.75     10755556.00
      3704171.75     10755542.00      3704178.00     10755526.00
      3704176.75     10755489.00      3704167.25     10755467.00
      3704172.50     10755452.00      3704181.25     10755445.00
      3704216.25     10755440.00      3704332.25     10755291.00
      3704420.75     10755218.00      3704644.75     10755110.00
      3704729.50     10755060.00      3704653.25     10754649.00
      3704642.75     10753995.00      3704789.50     10753610.00

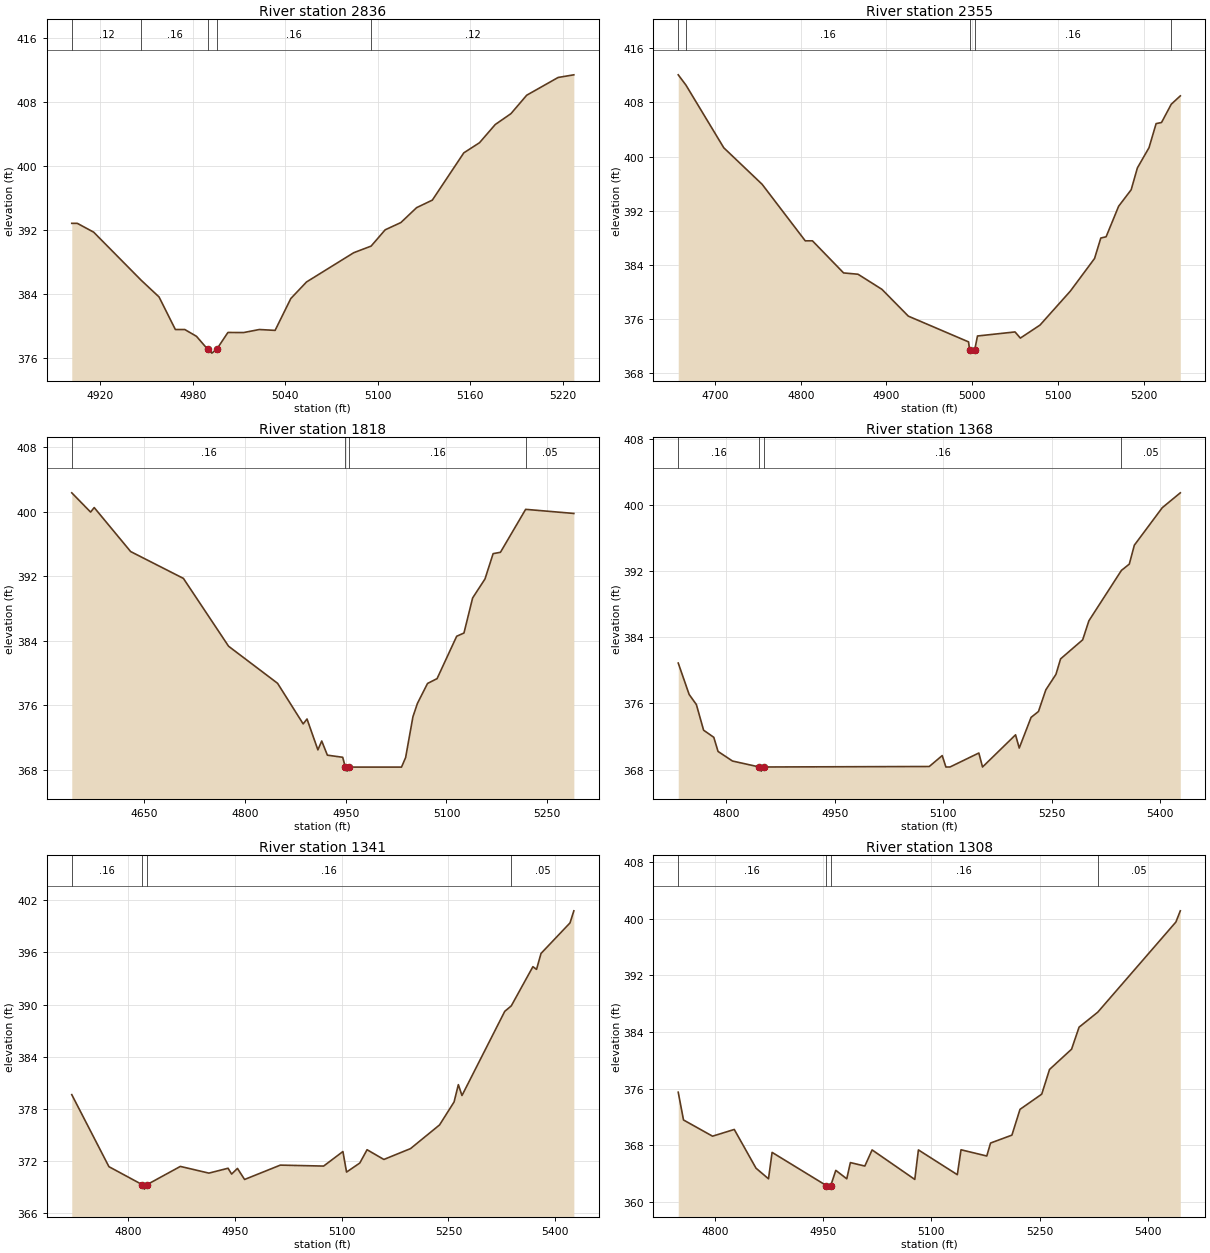
Type RM Length L Ch R = 1,2836,481,481,481
BEGIN DESCRIPTION:
UNT 027 IN CACR 5.0
END DESCRIPTION:
XS GIS Cut Line= 3
      3703849.64     10755910.21      3703799.61     10755860.19
      3703549.61     10755810.19
#Sta/Elev= 30
  4901.6  392.79  4905.2  392.79  4915.8  391.69  4946.7  385.67  4958.2  383.60
  4968.8  379.53  4974.9  379.53  4982.5  378.68  4989.7  377.08  4992.5  376.58
  4995.7  377.08  5002.9  379.16  5013.1  379.15  5023.3  379.53  5033.5  379.42
  5043.7  383.40  5053.9  385.47  5084.5  389.12  5095.8  389.95  5104.9  391.98
  5115.1  392.89  5125.3  394.75  5135.5  395.69  5155.9  401.59  5166.1  402.86
  5176.3  405.13  5186.5  406.49  5196.7  408.79  5217.1  411.01  5227.3  411.34
#Mann=5,-1,0
  4901.6    0.12       0  4946.7    0.16       0  4989.7    0.07       0
  4995.7    0.16       0  5095.8    0.12       0
Bank Sta=4989.7,4995.7
Exp/Cntr=0.3,0.1

Type RM Length L Ch R = 1,2355,537,537,537
BEGIN DESCRIPTION:
UNT 027 IN CACR 4.0
END DESCRIPTION:
XS GIS Cut Line= 3
      3704249.59     10755860.14      3704099.61     10755560.19
      3703899.58     10755410.16
#Sta/Elev= 30
  4657.2  412.07  4666.2  410.55  4710.3  401.30  4755.0  395.91  4805.3  387.56
  4813.7  387.56  4850.0  382.82  4866.8  382.63  4894.7  380.40  4925.5  376.44
  4995.7  372.64  4996.9  371.48  4999.6  370.98  5002.9  371.48  5006.1  373.51
  5049.9  374.11  5056.1  373.20  5079.0  375.12  5114.4  380.14  5142.6  384.95
  5149.9  387.97  5156.1  388.16  5170.7  392.67  5185.3  395.10  5192.6  398.34
  5206.1  401.31  5214.4  404.87  5220.7  405.03  5232.1  407.74  5242.6  408.96
#Mann=5,-1,0
  4657.2    0.05       0  4666.2    0.16       0  4996.9    0.07       0
  5002.9    0.16       0  5232.1    0.05       0
Bank Sta=4996.9,5002.9
Exp/Cntr=0.3,0.1

Type RM Length L Ch R = 1,1818,450,450,450
BEGIN DESCRIPTION:
Mapping XS bfdaf513
END DESCRIPTION:
XS GIS Cut Line= 4
      3704442.74     10755627.23      3704533.03     10755398.03
      3704418.45     10755186.22      3704178.90     10755085.54
#Sta/Elev= 30
  4542.5  402.36  4570.5  399.97  4575.9  400.53  4630.1  395.07  4708.6  391.74
  4775.8  383.32  4848.7  378.72  4886.8  373.68  4892.5  374.29  4908.7  370.46
  4914.4  371.56  4922.8  369.80  4945.6  369.54  4949.5  368.32  4952.2  367.82
  4955.5  368.32  5033.1  368.32  5039.2  369.50  5050.1  374.57  5056.8  376.23
  5071.8  378.70  5086.0  379.30  5115.2  384.56  5126.0  384.96  5138.9  389.31
  5157.3  391.67  5169.4  394.81  5180.3  394.98  5217.8  400.31  5289.5  399.80
#Mann=4,-1,0
  4542.5    0.16       0  4949.5    0.07       0  4955.5    0.16       0
  5217.8    0.05       0
Bank Sta=4949.5,4955.5
Exp/Cntr=0.3,0.1

Type RM Length L Ch R = 1,1368,27,27,27
BEGIN DESCRIPTION:
Mapping XS f799eee1
END DESCRIPTION:
XS GIS Cut Line= 3
      3704974.65     10754932.75      3704630.95     10754950.11
      3704287.23     10755019.55
#Sta/Elev= 30
  4733.4  380.89  4748.5  377.09  4758.5  375.87  4768.5  372.77  4782.6  371.91
  4788.5  370.20  4808.5  369.04  4845.6  368.32  4848.3  367.82  4851.6  368.32
  5080.8  368.38  5098.7  369.70  5103.8  368.32  5109.5  368.32  5149.4  370.01
  5154.5  368.32  5200.2  372.21  5205.3  370.61  5221.7  374.32  5231.9  375.03
  5242.1  377.65  5256.1  379.52  5262.5  381.39  5293.1  383.70  5301.7  386.00
  5346.7  392.09  5357.6  392.85  5364.6  395.14  5403.2  399.67  5428.2  401.47
#Mann=4,-1,0
  4733.4    0.16       0  4845.6    0.07       0  4851.6    0.16       0
  5346.7    0.05       0
Bank Sta=4845.6,4851.6
Exp/Cntr=0.3,0.1

Type RM Length L Ch R = 1,1341,33,33,33
BEGIN DESCRIPTION:
Mapping XS cf49a8dd
END DESCRIPTION:
XS GIS Cut Line= 3
      3704981.62     10754898.03      3704669.14     10754922.34
      3704284.30     10754995.14
#Sta/Elev= 30
  4721.0  379.65  4773.2  371.37  4820.3  369.29  4823.1  368.79  4826.3  369.29
  4873.5  371.40  4913.6  370.63  4940.5  371.19  4945.5  370.52  4953.7  371.17
  4963.7  369.90  5013.9  371.55  5074.7  371.44  5101.8  373.11  5106.9  370.75
  5125.5  371.79  5135.7  373.32  5159.3  372.20  5196.8  373.45  5237.5  376.17
  5257.9  378.81  5263.9  380.80  5269.0  379.55  5329.1  389.23  5338.2  389.85
  5368.6  394.36  5373.7  394.05  5380.0  395.88  5420.7  399.39  5426.1  400.78
#Mann=4,-1,0
  4721.0    0.16       0  4820.3    0.07       0  4826.3    0.16       0
  5338.2    0.05       0
Bank Sta=4820.3,4826.3
Exp/Cntr=0.3,0.1

Type RM Length L Ch R = 1,1308,539,539,539
BEGIN DESCRIPTION:
UNT 027 IN CACR 3.0
END DESCRIPTION:
XS GIS Cut Line= 4
      3704946.88     10754863.31      3704724.70     10754884.14
      3704589.28     10754898.03      3704263.70     10754981.16
#Sta/Elev= 30
  4749.4  375.48  4756.7  371.56  4796.9  369.27  4827.0  370.22  4857.1  364.75
  4874.4  363.25  4879.4  366.98  4954.6  362.29  4957.3  361.79  4960.6  362.29
  4967.6  364.44  4982.8  363.25  4987.8  365.54  5007.8  365.05  5017.9  367.33
  5077.0  363.16  5082.0  367.33  5135.9  363.83  5141.0  367.35  5176.7  366.47
  5181.9  368.30  5211.5  369.42  5222.7  373.06  5252.8  375.21  5263.6  378.70
  5294.1  381.56  5304.5  384.67  5330.4  386.79  5438.6  399.53  5444.7  401.11
#Mann=4,-1,0
  4749.4    0.16       0  4954.6    0.07       0  4960.6    0.16       0
  5330.4    0.05       0
Bank Sta=4954.6,4960.6
Exp/Cntr=0.3,0.1

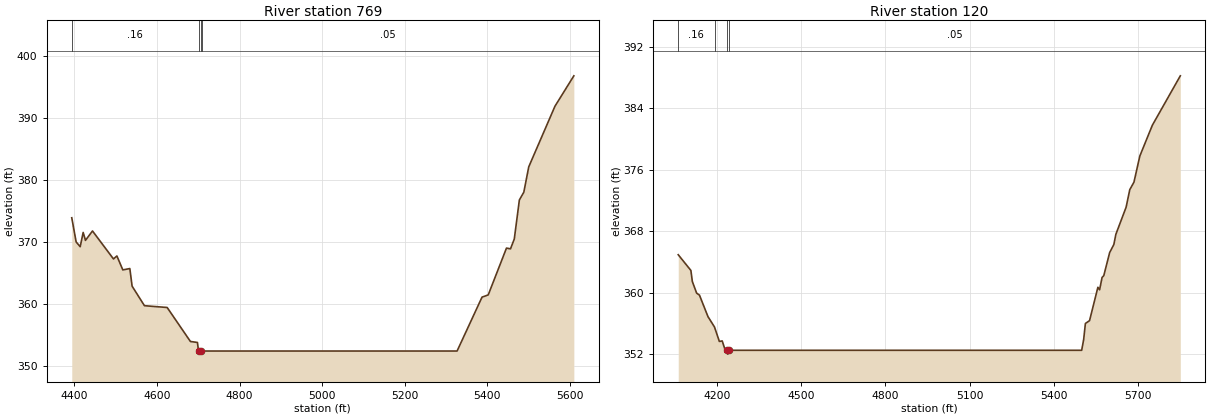
Type RM Length L Ch R = 1,769,649,649,649
BEGIN DESCRIPTION:
UNT 027 IN CACR 2.0
END DESCRIPTION:
XS GIS Cut Line= 4
      3704957.34     10754828.60      3704728.17     10754354.63
      3704571.92     10754349.42      3704077.14     10754547.33
#Sta/Elev= 30
  4393.8  373.97  4404.4  370.07  4414.2  369.30  4421.4  371.60  4427.0  370.33
  4444.0  371.84  4494.8  367.33  4503.1  367.81  4517.4  365.56  4534.4  365.78
  4539.9  362.94  4569.8  359.79  4624.8  359.50  4681.1  354.02  4698.1  353.86
  4700.7  352.48  4703.4  351.98  4706.7  352.48  4709.8  352.48  5326.8  352.48
  5387.2  361.17  5402.2  361.53  5446.4  369.08  5456.1  368.96  5465.3  370.54
  5477.6  376.84  5488.4  378.10  5500.3  382.18  5563.8  391.96  5609.5  396.86
#Mann=4,-1,0
  4393.8    0.16       0  4700.7   0.033       0  4706.7    0.16       0
  4709.8    0.05       0
Bank Sta=4700.7,4706.7
Exp/Cntr=0.3,0.1

Type RM Length L Ch R = 1,120,0,0,0
BEGIN DESCRIPTION:
UNT 027 IN CACR 1.0
END DESCRIPTION:
XS GIS Cut Line= 4
      3704941.71     10754615.05      3704821.92     10753781.71
      3704696.92     10753682.75      3704051.08     10754130.67
#Sta/Elev= 30
  4062.2  364.92  4107.3  362.87  4112.4  361.44  4127.7  359.92  4137.8  359.66
  4168.1  356.86  4191.3  355.51  4208.6  353.63  4218.7  353.70  4228.8  352.57
  4235.9  352.48  4238.6  351.98  4241.9  352.48  5498.4  352.48  5505.5  353.89
  5511.6  355.97  5526.4  356.34  5556.1  360.68  5562.2  360.36  5571.0  361.96
  5577.1  362.20  5598.0  365.20  5612.9  366.25  5620.1  367.58  5656.6  371.11
  5669.6  373.39  5684.5  374.37  5705.4  377.77  5750.0  381.78  5849.5  388.21
#Mann=4,-1,0
  4062.2    0.16       0  4191.3    0.05       0  4235.9   0.033       0
  4241.9    0.05       0
Bank Sta=4235.9,4241.9
Exp/Cntr=0.3,0.1

Chan Stop Cuts=-1