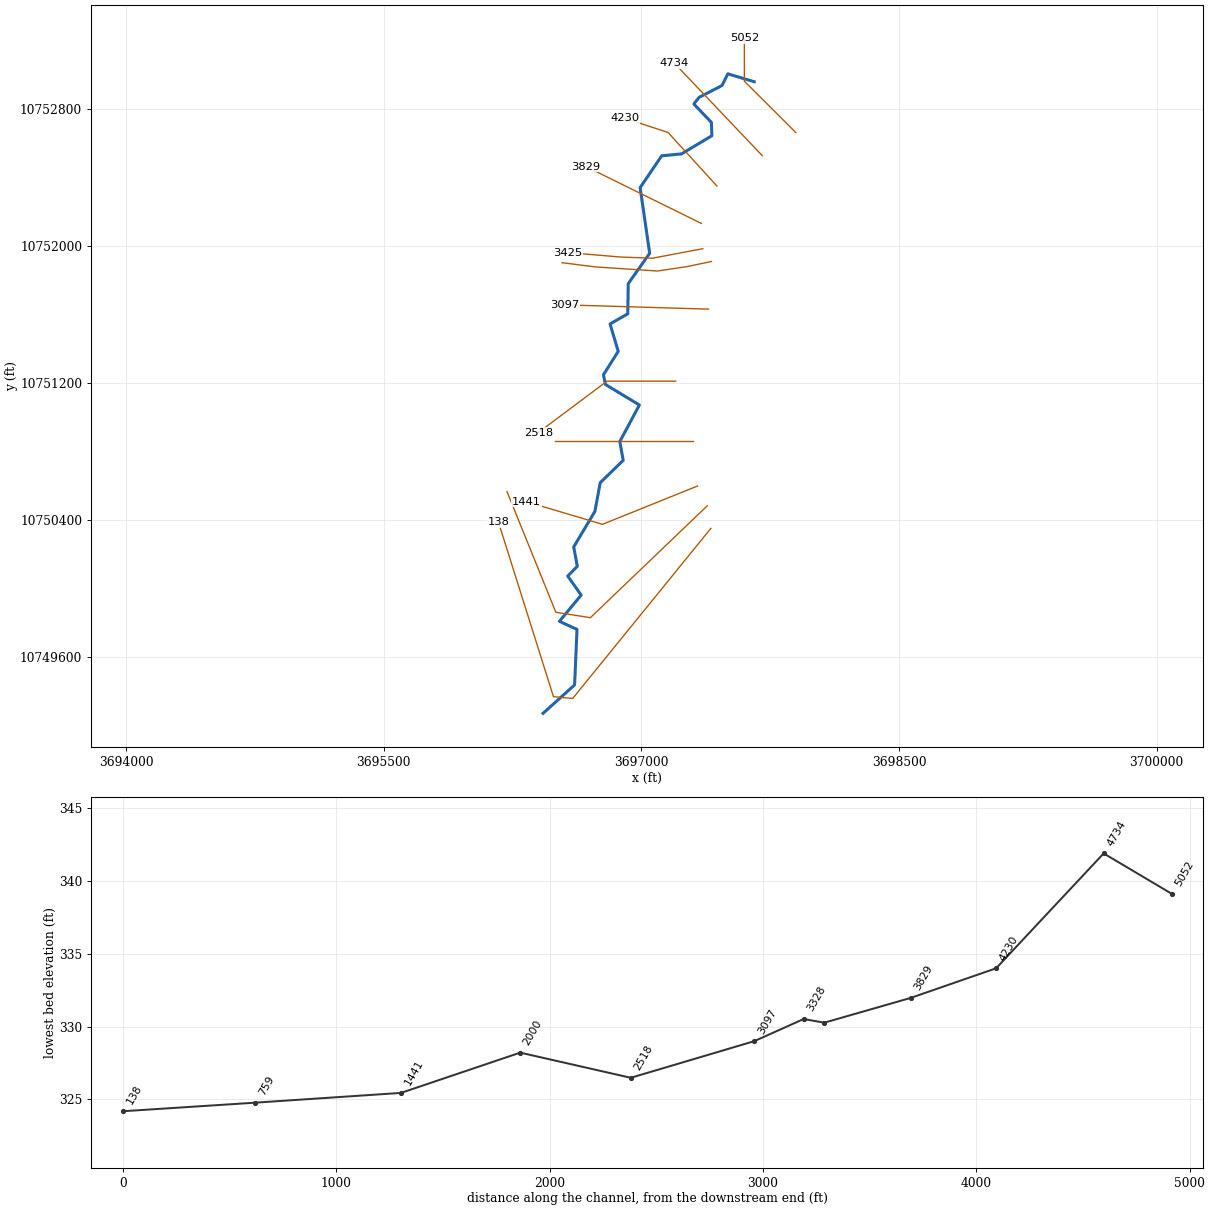
--- UNT 028 IN CACR.prj (project) ---

Proj Title=UNT 028 IN CACR Base Level Engineering
Current Plan=p01
Default Exp/Contr=0.3,0.1
English Units
Geom File=g01
Flow File=f01
Plan File=p01
BEGIN DESCRIPTION:
UNT 028 IN CACR
END DESCRIPTION:

--- UNT 028 IN CACR.p01 (plan) ---

Plan Title=Multiple Run
Short Identifier=Multiple
Geom File=g01
Flow File=f01
Subcritical Flow
K Sum by GR= 0
Std Step Tol= 0.01
Critical Tol= 0.01
Num of Std Step Trials= 20
Max Error Tol= 0.3
Flow Tol Ratio= 0.001
Split Flow NTrial= 30
Split Flow Tol= 0.02
Split Flow Ratio= 0.02
Log Output Level= 0
Friction Slope Method= 1
Unsteady Friction Slope Method= 2
Unsteady Bridges Friction Slope Method= 1
Parabolic Critical Depth
Global Vel Dist=  1 , 1 , 1
Global Log Level= 0
CheckData=True
Encroach Param= -1, 0, 0, 0
BEGIN DESCRIPTION:
Multiple Run
END DESCRIPTION:

--- UNT 028 IN CACR.f01 (steady flow) ---

Flow Title=Multiple
Number of Profiles=7
Profile Names=10-year,25-year,50-year,1pct_min,100-year,1pct_plu,500-year
River Rch & RM= UNT 028 IN CACR,Reach-1,5052
     738    1019    1255    1135    1535    2076    2299
River Rch & RM= UNT 028 IN CACR,Reach-1,4734
     815    1127    1388    1254    1695    2293    2535
Boundary for River Rch & Prof#=UNT 028 IN CACR,Reach-1,1
Up Type=0
Dn Type=3
Dn Slope=0.005
Boundary for River Rch & Prof#=UNT 028 IN CACR,Reach-1,2
Up Type=0
Dn Type=3
Dn Slope=0.005
Boundary for River Rch & Prof#=UNT 028 IN CACR,Reach-1,3
Up Type=0
Dn Type=3
Dn Slope=0.005
Boundary for River Rch & Prof#=UNT 028 IN CACR,Reach-1,4
Up Type=0
Dn Type=3
Dn Slope=0.005
Boundary for River Rch & Prof#=UNT 028 IN CACR,Reach-1,5
Up Type=0
Dn Type=3
Dn Slope=0.005
Boundary for River Rch & Prof#=UNT 028 IN CACR,Reach-1,6
Up Type=0
Dn Type=3
Dn Slope=0.005
Boundary for River Rch & Prof#=UNT 028 IN CACR,Reach-1,7
Up Type=0
Dn Type=3
Dn Slope=0.005

--- UNT 028 IN CACR.g01 (geometry) ---

Geom Title=Existing Conditions
Program Version=4.10

River Reach=UNT 028 IN CACR ,Reach-1
Reach XY= 30
        3697657.       10752957.      3697503.25       10753003.
       3697469.5       10752935.        3697336.       10752866.
      3697305.25       10752827.       3697407.5       10752720.
       3697410.5       10752642.       3697233.5       10752536.
      3697118.25       10752525.       3696992.5       10752339.
      3697048.25       10751956.      3696923.25       10751779.
      3696920.75       10751603.      3696817.25       10751544.
        3696865.       10751384.      3696778.75       10751247.
       3696790.5       10751191.      3696988.25       10751071.
      3696874.25       10750858.        3696894.       10750748.
      3696760.25       10750618.        3696729.       10750450.
      3696605.75       10750243.      3696626.75       10750130.
        3696571.       10750073.      3696649.25       10749962.
       3696522.5       10749809.        3696625.       10749762.
        3696611.       10749438.        3696427.       10749272.

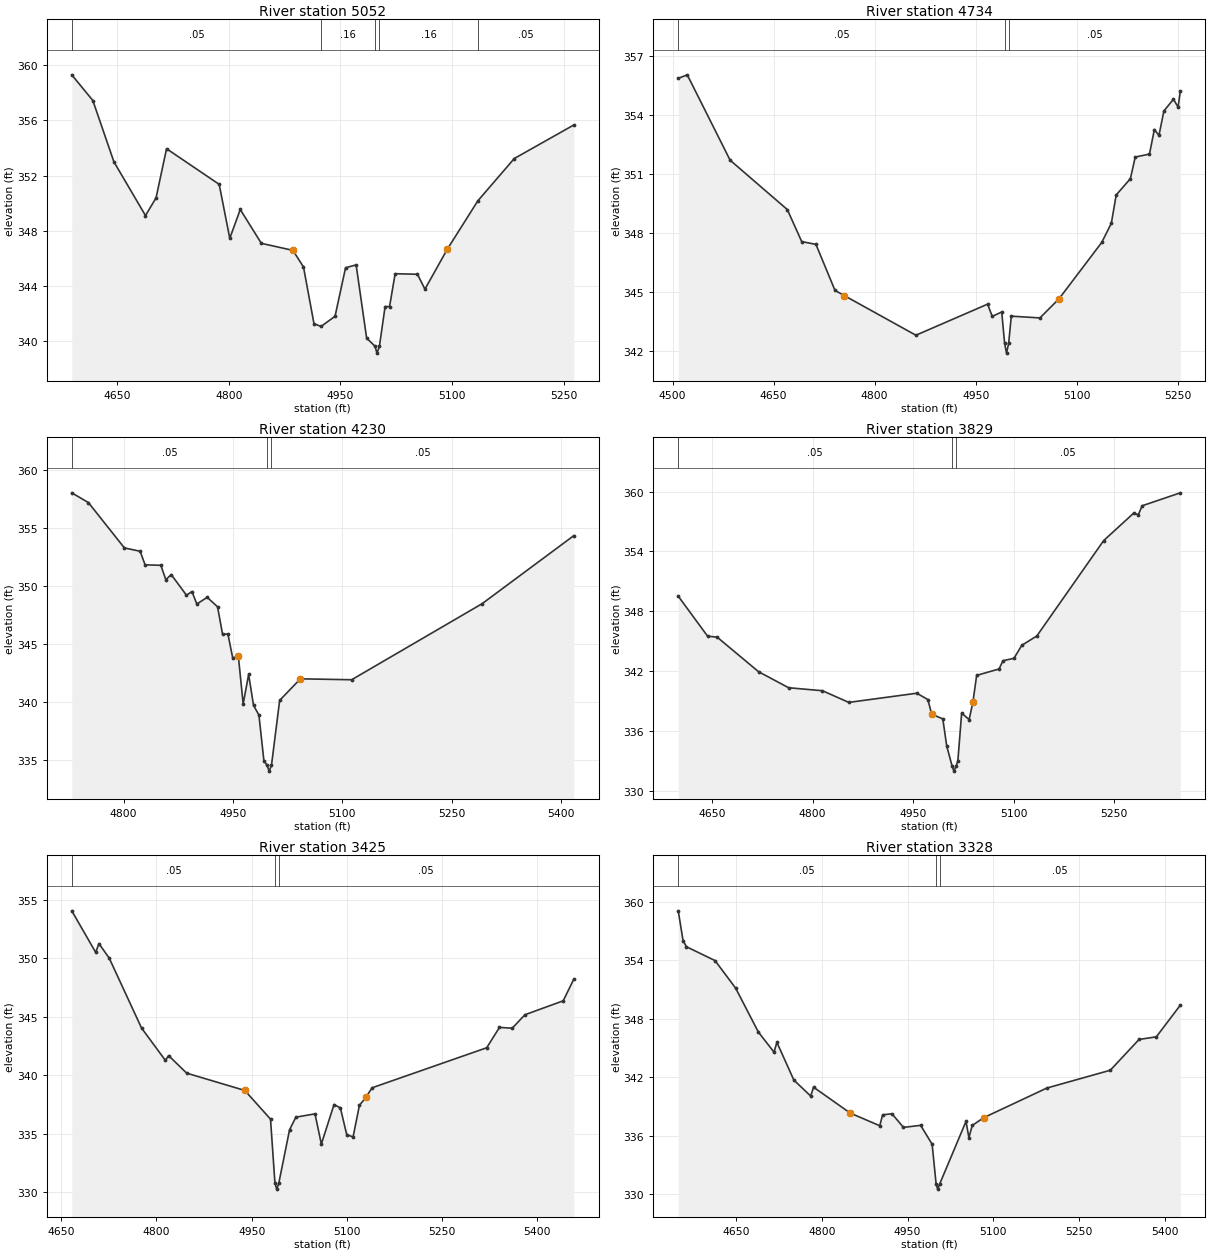
Type RM Length L Ch R = 1 ,5052    ,318,318,318
BEGIN DESCRIPTION:
UNT 028 IN CACR 9.0
END DESCRIPTION:
XS GIS Cut Line= 3
      3697899.63     10752660.17      3697599.61     10752960.19
      3697599.61     10753210.19
#Sta/Elev= 30
  4589.2  359.29  4617.5  357.43  4645.8  352.99  4688.2   349.1  4702.4  350.38
  4716.5  353.94  4787.2  351.36  4801.4  347.45  4815.5  349.54  4843.8  347.09
  4886.2  346.58  4900.4  345.38  4914.5  341.27    4924  341.07  4942.8  341.81
  4956.9  345.32  4971.1  345.53  4985.2  340.23  4996.4  339.64  4999.1  339.14
  5002.4  339.64    5010  342.51    5016  342.51  5023.5  344.89  5053.5  344.85
  5063.5  343.77  5093.5  346.66  5134.6  350.17  5183.5  353.23  5263.5  355.66
#Mann= 5 ,-1 , 0
  4589.2     .05       0    4924     .16       0  4996.4     .07       0
  5002.4     .16       0  5134.6     .05       0
Bank Sta=4886.2,5093.5
XS Rating Curve= 0 ,0
Exp/Cntr=0.3,0.1

Type RM Length L Ch R = 1 ,4734    ,504,504,504
BEGIN DESCRIPTION:
UNT 028 IN CACR 8.0
END DESCRIPTION:
XS GIS Cut Line= 2
      3697703.92      10752525.5      3697190.96     10753066.18
#Sta/Elev= 30
  4508.5  355.88  4521.9  356.06  4585.5  351.72  4670.4  349.21  4691.8  347.58
  4712.9  347.44  4741.2   345.1  4755.3  344.83  4861.3  342.82  4967.7   344.4
  4974.6  343.78  4988.7     344    4993  342.41  4995.8  341.91    4999  342.41
  5002.9  343.79  5045.4   343.7  5073.7  344.67  5137.2  347.54  5151.4  348.51
  5158.6  349.95  5179.7  350.78  5186.9  351.88    5208  352.03  5215.3  353.28
  5222.1  352.98  5229.4  354.22  5243.6  354.82  5250.5  354.42  5253.8  355.22
#Mann= 3 ,-1 , 0
  4508.5     .05       0    4993     .03       0    4999     .05       0
Bank Sta=4755.3,5073.7
XS Rating Curve= 0 ,0
Exp/Cntr=0.3,0.1

Type RM Length L Ch R = 1 ,4230    ,401,401,401
BEGIN DESCRIPTION:
UNT 028 IN CACR 7.0
END DESCRIPTION:
XS GIS Cut Line= 3
      3697440.01     10752348.43      3697155.29     10752660.93
      3696903.22      10752743.8
#Sta/Elev= 30
  4729.1  358.01  4751.9  357.17  4801.2  353.26  4822.8  352.97  4829.6   351.8
  4851.2  351.76    4858  350.52  4865.4  350.96  4886.3  349.18  4893.8   349.5
  4900.5  348.42  4914.7     349  4928.9  348.18  4935.7  345.83  4943.1  345.83
  4949.8  343.73  4957.3  343.98    4964   339.8  4971.5  342.35  4978.2  339.68
  4985.6  338.84  4992.4  334.92  4996.8  334.51  4999.6  334.01  5002.8  334.51
    5014  340.11  5042.4  341.97  5112.7  341.89  5291.5  348.45  5417.2  354.32
#Mann= 3 ,-1 , 0
  4729.1     .05       0  4996.8     .03       0  5002.8     .05       0
Bank Sta=4957.3,5042.4
XS Rating Curve= 0 ,0
Exp/Cntr=0.3,0.1

Type RM Length L Ch R = 1 ,3829    ,404,404,404
BEGIN DESCRIPTION:
UNT 028 IN CACR 6.0
END DESCRIPTION:
XS GIS Cut Line= 2
      3697348.85     10752130.55      3696677.02     10752462.13
#Sta/Elev= 30
  4599.4  349.51  4643.2   345.5  4657.5   345.4  4719.2  341.94  4764.1  340.33
  4814.6  340.03  4853.9  338.86  4955.4  339.78  4971.8  339.15  4977.7  337.67
  4994.2  337.21    5000   334.5  5008.1  332.47  5010.8  331.97  5014.1  332.47
  5016.7  333.02  5022.3  337.78  5033.5  337.14  5039.1  338.88  5044.7  341.57
  5078.1  342.21    5084  343.04  5100.4  343.28    5112  344.58  5134.5  345.52
  5234.2  355.08  5278.8  357.82  5286.1  357.69  5291.6  358.57  5348.6  359.87
#Mann= 3 ,-1 , 0
  4599.4     .05       0  5008.1     .03       0  5014.1     .05       0
Bank Sta=4977.7,5039.1
XS Rating Curve= 0 ,0
Exp/Cntr=0.3,0.1

Type RM Length L Ch R = 1 ,3425    ,97,97,97
BEGIN DESCRIPTION:
Mapping XS 47d6fa7b
END DESCRIPTION:
XS GIS Cut Line= 4
      3697357.59     10751982.98      3697064.15     10751927.42
      3696878.38     10751934.36      3696572.83     10751960.26
#Sta/Elev= 30
  4666.5  354.05  4704.2   350.5  4709.3  351.25  4725.5  350.01  4776.4  344.04
    4814  341.27  4819.1  341.68  4847.6  340.18  4939.2   338.7  4979.7  336.25
  4986.7  330.77  4989.5  330.27  4992.7  330.77  5009.7  335.34  5019.7  336.42
  5049.8   336.7  5059.8  334.12  5079.8   337.5  5089.8  337.21  5099.8  334.92
  5109.8  334.73  5119.8  337.43  5129.8   338.1  5139.8  338.93  5320.4  342.35
  5340.5  344.09  5360.6  344.02  5380.6  345.17  5440.9  346.36  5457.7  348.22
#Mann= 3 ,-1 , 0
  4666.5     .05       0  4986.7     .04       0  4992.7     .05       0
Bank Sta=4939.2,5129.8
XS Rating Curve= 0 ,0
Exp/Cntr=0.3,0.1

Type RM Length L Ch R = 1 ,3328    ,231,231,231
BEGIN DESCRIPTION:
Mapping XS 1a4904f6
END DESCRIPTION:
XS GIS Cut Line= 5
       3697407.9     10751908.32      3697267.27     10751878.81
      3697093.66     10751852.77      3696727.34     10751877.07
      3696538.06     10751901.38
#Sta/Elev= 30
  4549.3   359.1  4557.8  356.02  4563.7  355.41  4613.6  353.99  4649.7  351.15
  4689.2  346.66  4716.6  344.59  4721.7  345.59  4751.3  341.72  4780.7  340.08
  4785.7  340.99  4849.8  338.33  4901.4  337.03  4906.4  338.15  4922.7  338.26
  4942.8  336.86  4972.8  337.07  4992.9  335.13  4999.9  331.02  5002.6  330.52
  5005.9  331.02  5052.1  337.48  5057.1  335.81    5063  337.06  5083.1  337.86
  5193.3   340.9  5304.2  342.73  5354.4  345.89  5384.6  346.16  5426.5  349.41
#Mann= 3 ,-1 , 0
  4549.3     .05       0  4999.9     .04       0  5005.9     .05       0
Bank Sta=4849.8,5083.1
XS Rating Curve= 0 ,0
Exp/Cntr=0.3,0.1

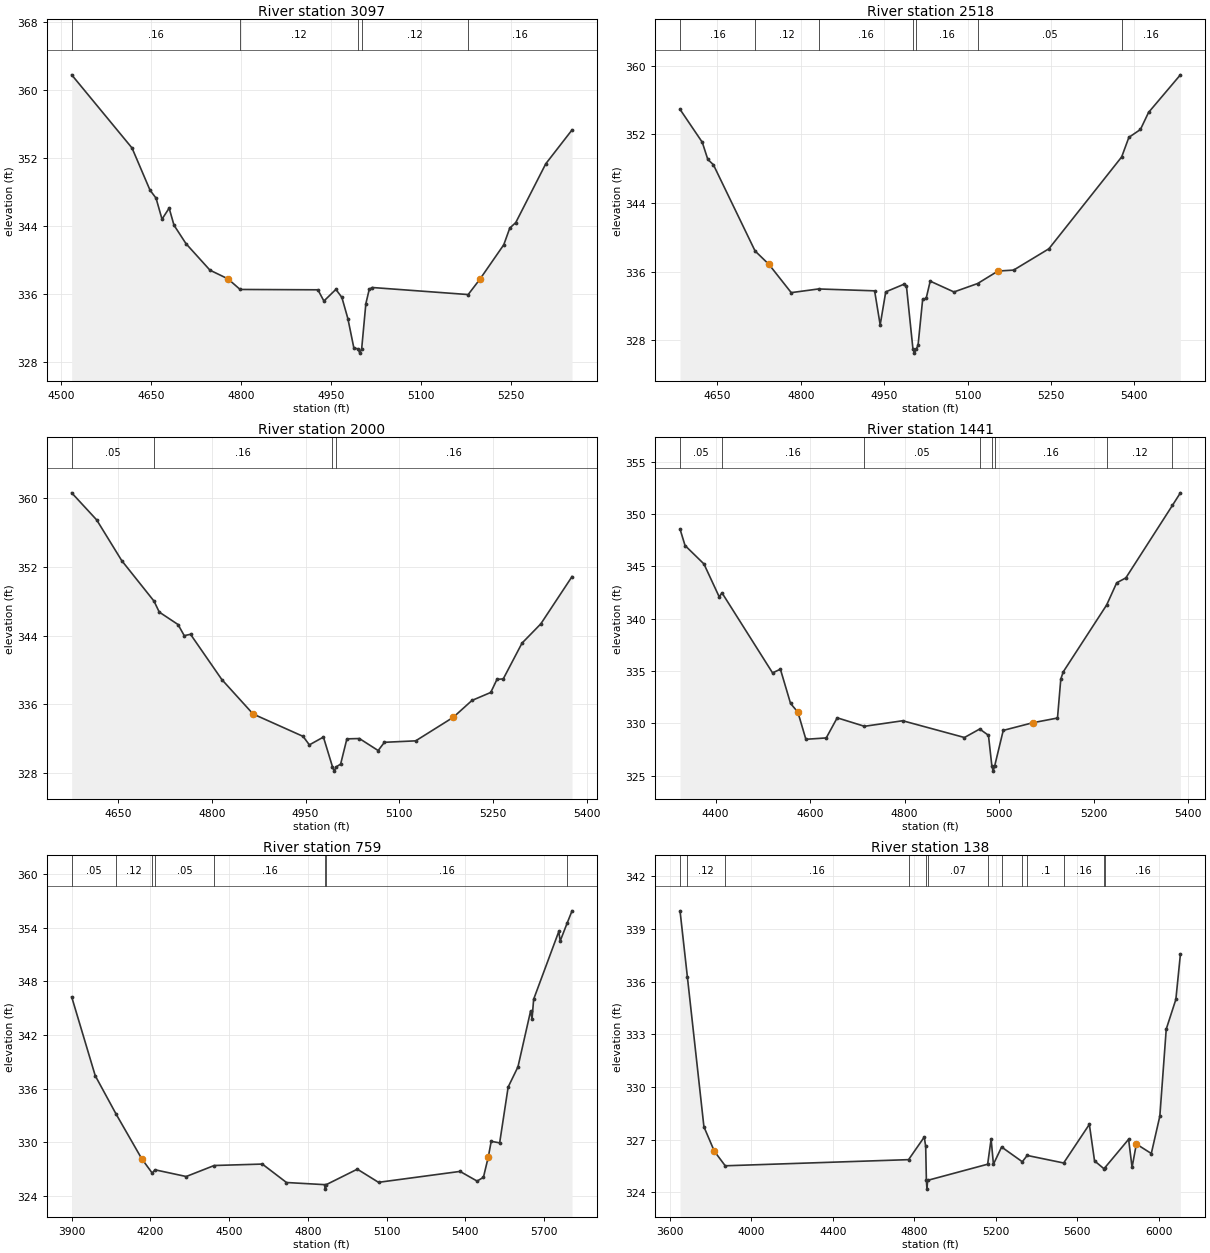
Type RM Length L Ch R = 1 ,3097    ,579,579,579
BEGIN DESCRIPTION:
UNT 028 IN CACR 5.0
END DESCRIPTION:
XS GIS Cut Line= 2
      3697390.23     10751630.46       3696555.8     10751655.19
#Sta/Elev= 30
  4517.5  361.74  4618.2  353.13  4648.2  348.17  4658.2  347.24  4668.2  344.76
  4680.1  346.06  4688.2  344.05  4708.2  341.88  4748.2  338.76  4778.2  337.74
  4798.5  336.49  4928.3  336.45  4938.3  335.13  4958.3   336.5  4968.3  335.55
  4978.3  333.06  4988.3   329.6  4995.3   329.5  4998.1     329  5001.3   329.5
  5008.3  334.82    5014  336.52    5019  336.72    5179  335.89  5198.4  337.68
  5238.4  341.75  5248.4  343.71  5258.4  344.36  5308.5  351.28  5352.3  355.26
#Mann= 5 ,-1 , 0
  4517.5     .16       0  4798.5     .12       0  4995.3     .07       0
  5001.3     .12       0    5179     .16       0
Bank Sta=4778.2,5198.4
XS Rating Curve= 0 ,0
Exp/Cntr=0.3,0.1

Type RM Length L Ch R = 1 ,2518    ,518,518,518
BEGIN DESCRIPTION:
UNT 028 IN CACR 4.0
END DESCRIPTION:
XS GIS Cut Line= 3
      3697199.59     10751210.19      3696799.61     10751210.19
       3696399.6     10750910.18
#Sta/Elev= 30
  4582.8  354.93  4622.8  351.09  4632.8  349.08  4642.8  348.47  4717.8   338.4
  4742.8  336.83  4782.8  333.54  4831.9  333.97  4932.8  333.75  4942.8  329.77
  4952.8  333.63  4985.9  334.53  4990.1  334.26  5001.7  326.98  5004.4  326.48
  5007.7  326.98  5010.9  327.38  5019.2  332.75  5025.5  332.87  5032.8  334.88
  5075.5  333.62    5118   334.6  5154.7  336.06  5182.8  336.17  5246.3  338.66
  5377.2  349.38  5390.1  351.66  5410.9  352.58  5425.5  354.57  5482.8  358.96
#Mann= 7 ,-1 , 0
  4582.8     .16       0  4717.8     .12       0  4831.9     .16       0
  5001.7     .07       0  5007.7     .16       0    5118     .05       0
  5377.2     .16       0
Bank Sta=4742.8,5154.7
XS Rating Curve= 0 ,0
Exp/Cntr=0.3,0.1

Type RM Length L Ch R = 1 ,2000    ,559,559,559
BEGIN DESCRIPTION:
UNT 028 IN CACR 3.0
END DESCRIPTION:
XS GIS Cut Line= 3
      3697299.57     10750860.19      3696899.61     10750860.19
      3696499.57     10750860.19
#Sta/Elev= 30
    4576  360.65    4616  357.49    4656  352.75  4707.7  348.02    4716  346.75
    4746   345.3    4756     344    4766  344.16    4816  338.89    4866  334.87
    4946  332.26    4956  331.27  4978.5  332.18    4993  328.71  4995.7  328.21
    4999  328.71    5006  329.03    5016  331.97    5036  332.01    5066  330.61
    5076  331.57    5126  331.74    5186  334.48    5216  336.45    5246  337.38
    5256  338.91    5266  338.96    5296  343.13    5326  345.37    5376  350.89
#Mann= 4 ,-1 , 0
    4576     .05       0  4707.7     .16       0    4993     .07       0
    4999     .16       0
Bank Sta=4866,5186
XS Rating Curve= 0 ,0
Exp/Cntr=0.3,0.1

Type RM Length L Ch R = 1 ,1441    ,682,682,682
BEGIN DESCRIPTION:
Mapping XS fce68e2d
END DESCRIPTION:
XS GIS Cut Line= 3
      3697326.52     10750598.34      3696773.13     10750374.82
      3696330.42     10750507.19
#Sta/Elev= 30
  4324.9  348.55  4335.5  346.98  4375.5  345.22  4407.8  342.08  4413.7  342.46
  4520.7  334.82  4537.3  335.17  4558.8   331.9  4574.3  331.07  4591.2  328.48
  4634.3  328.61  4657.5  330.53  4715.2  329.72  4796.1  330.25  4926.8  328.65
  4959.1  329.46  4977.6  328.86  4984.8  325.94  4987.6  325.44  4990.8  325.94
  5008.9  329.33  5071.5  330.06  5123.7  330.51  5130.7  334.23  5135.9  334.92
  5227.7   341.3    5249  343.42  5268.4  343.89  5366.9  350.81  5383.8  352.01
#Mann= 8 ,-1 , 0
  4324.9     .05       0  4413.7     .16       0  4715.2     .05       0
  4959.1     .16       0  4984.8     .07       0  4990.8     .16       0
  5227.7     .12       0  5366.9     .16       0
Bank Sta=4574.3,5071.5
XS Rating Curve= 0 ,0
Exp/Cntr=0.3,0.1

Type RM Length L Ch R = 1 ,759     ,621,621,621
BEGIN DESCRIPTION:
UNT 028 IN CACR 2.0
END DESCRIPTION:
XS GIS Cut Line= 4
      3697383.66     10750483.22       3696703.1     10749830.44
      3696501.71     10749861.69      3696217.26     10750565.89
#Sta/Elev= 30
  3900.2  346.25    3990  337.44  4070.1  333.12    4167  328.17    4207  326.56
  4217.6  326.93  4336.5  326.18  4443.2  327.41  4626.5  327.57  4718.6  325.51
    4864  325.27  4866.7  324.77    4870  325.27  4988.4     327  5069.2  325.53
  5379.7  326.75  5444.8  325.67  5468.9  326.09  5487.6  328.39  5498.5  330.11
  5530.7  329.94  5563.1  336.18  5600.4  338.43  5648.7  344.69  5654.1  343.79
  5660.2  345.99    5756  353.56  5761.4   352.5  5787.3  354.46  5806.5  355.87
#Mann= 8 ,-1 , 0
  3900.2     .05       0  4070.1     .12       0    4207     .16       0
  4217.6     .05       0  4443.2     .16       0    4864     .07       0
    4870     .16       0  5787.3     .05       0
Bank Sta=4167,5487.6
XS Rating Curve= 0 ,0
Exp/Cntr=0.3,0.1

Type RM Length L Ch R = 1 ,138     ,0,0,0
BEGIN DESCRIPTION:
UNT 028 IN CACR 1.0
END DESCRIPTION:
XS GIS Cut Line= 4
      3697404.47     10750351.25       3696599.8     10749359.08
      3696487.82      10749369.5      3696167.91     10750386.45
#Sta/Elev= 30
  3650.3  340.04  3686.3  336.28  3767.6  327.73  3818.7  326.34  3872.1  325.51
  4772.1  325.86  4849.1  327.15  4856.1  326.61  4859.5  324.68  4862.3  324.18
  4865.5  324.68  5160.2   325.6  5177.2  327.03  5188.6   325.6  5228.7  326.58
  5330.3  325.74  5354.2   326.1  5533.3  325.67  5659.4  327.87  5684.9  325.79
  5730.3  325.35  5736.3  325.41  5852.1  327.02  5869.1  325.42  5890.1  326.75
  5963.5  326.21  6005.4  328.34  6036.8   333.3    6084  334.99  6106.3  337.56
#Mann= 13 ,-1 , 0
  3650.3     .16       0  3686.3     .12       0  3872.1     .16       0
  4772.1     .07       0  4859.5     .07       0  4865.5     .07       0
  5160.2     .12       0  5228.7      .1       0  5330.3     .16       0
  5354.2      .1       0  5533.3     .16       0  5730.3     .05       0
  5736.3     .16       0
Bank Sta=3818.7,5890.1
XS Rating Curve= 0 ,0
Exp/Cntr=0.3,0.1

Chan Stop Cuts=-1
Use User Specified Reach Order=0
Composite Channel Slope=5