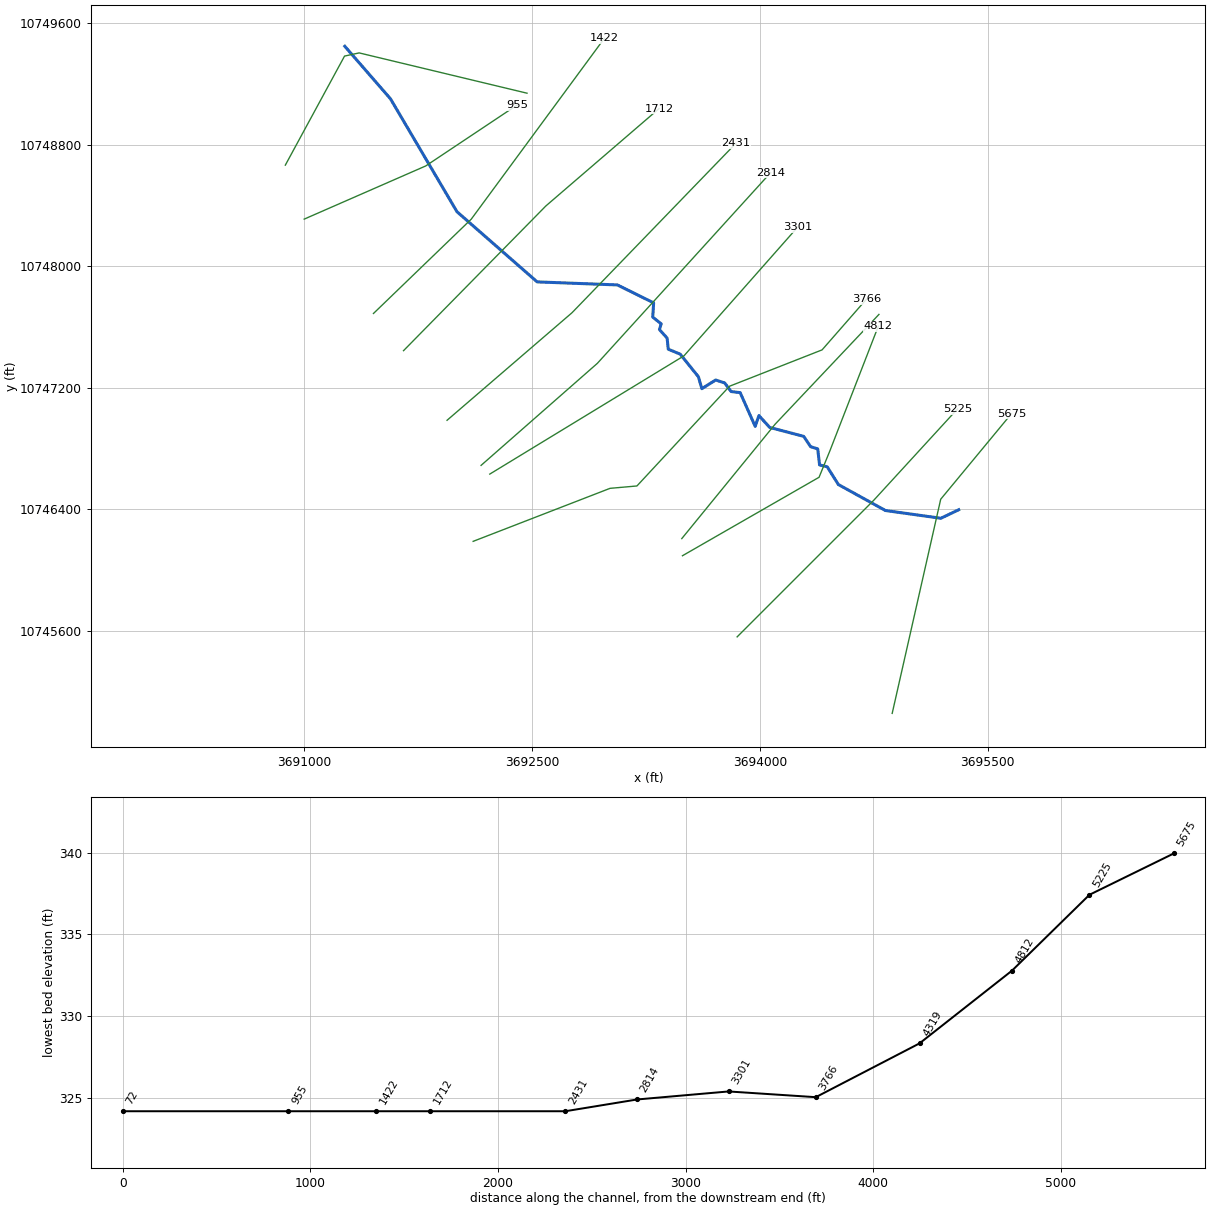
--- UNT 029 IN CACR.prj (project) ---

Proj Title=UNT 029 IN CACR Base Level Engineering
Current Plan=p01
Default Exp/Contr=0.3,0.1
English Units
Geom File=g01
Flow File=f01
Plan File=p01
BEGIN DESCRIPTION:
UNT 029 IN CACR
END DESCRIPTION:

--- UNT 029 IN CACR.p01 (plan) ---

Plan Title=Multiple Run
Short Identifier=Multiple
Geom File=g01
Flow File=f01
Subcritical Flow
K Sum by GR= 0
Std Step Tol= 0.01
Critical Tol= 0.01
Num of Std Step Trials= 20
Max Error Tol= 0.3
Flow Tol Ratio= 0.001
Split Flow NTrial= 30
Split Flow Tol= 0.02
Split Flow Ratio= 0.02
Log Output Level= 0
Friction Slope Method= 1
Unsteady Friction Slope Method= 2
Unsteady Bridges Friction Slope Method= 1
Parabolic Critical Depth
Global Vel Dist=  1 , 1 , 1
Global Log Level= 0
CheckData=True
Encroach Param= -1, 0, 0, 0
BEGIN DESCRIPTION:
Multiple Run
END DESCRIPTION:

--- UNT 029 IN CACR.f01 (steady flow) ---

Flow Title=Multiple
Number of Profiles=7
Profile Names=10-year,25-year,50-year,1pct_min,100-year,1pct_plu,500-year
River Rch & RM= UNT 029 IN CACR,Reach-1,5675
     606     829    1015     913    1235    1670    1831
Boundary for River Rch & Prof#=UNT 029 IN CACR,Reach-1,1
Up Type=0
Dn Type=3
Dn Slope=0.005
Boundary for River Rch & Prof#=UNT 029 IN CACR,Reach-1,2
Up Type=0
Dn Type=3
Dn Slope=0.005
Boundary for River Rch & Prof#=UNT 029 IN CACR,Reach-1,3
Up Type=0
Dn Type=3
Dn Slope=0.005
Boundary for River Rch & Prof#=UNT 029 IN CACR,Reach-1,4
Up Type=0
Dn Type=3
Dn Slope=0.005
Boundary for River Rch & Prof#=UNT 029 IN CACR,Reach-1,5
Up Type=0
Dn Type=3
Dn Slope=0.005
Boundary for River Rch & Prof#=UNT 029 IN CACR,Reach-1,6
Up Type=0
Dn Type=3
Dn Slope=0.005
Boundary for River Rch & Prof#=UNT 029 IN CACR,Reach-1,7
Up Type=0
Dn Type=3
Dn Slope=0.005

--- UNT 029 IN CACR.g01 (geometry) ---

Geom Title=Existing Conditions

River Reach=UNT 029 IN CACR,Reach-1
Reach XY= 30
      3695308.25     10746397.00      3695190.75     10746341.00
      3694826.00     10746392.00      3694516.00     10746563.00
      3694442.50     10746680.00      3694392.25     10746692.00
      3694380.00     10746798.00      3694333.25     10746812.00
      3694288.00     10746880.00      3694064.00     10746939.00
      3693993.00     10747017.00      3693968.50     10746946.00
      3693869.50     10747168.00      3693810.50     10747175.00
      3693767.25     10747232.00      3693708.25     10747251.00
      3693617.50     10747194.00      3693594.25     10747273.00
      3693475.25     10747421.00      3693396.25     10747454.00
      3693388.75     10747527.00      3693338.25     10747583.00
      3693349.50     10747621.00      3693294.00     10747665.00
      3693300.00     10747759.00      3693061.25     10747877.00
      3692533.25     10747897.00      3692005.25     10748359.00
      3691567.75     10749102.00      3691267.00     10749448.00

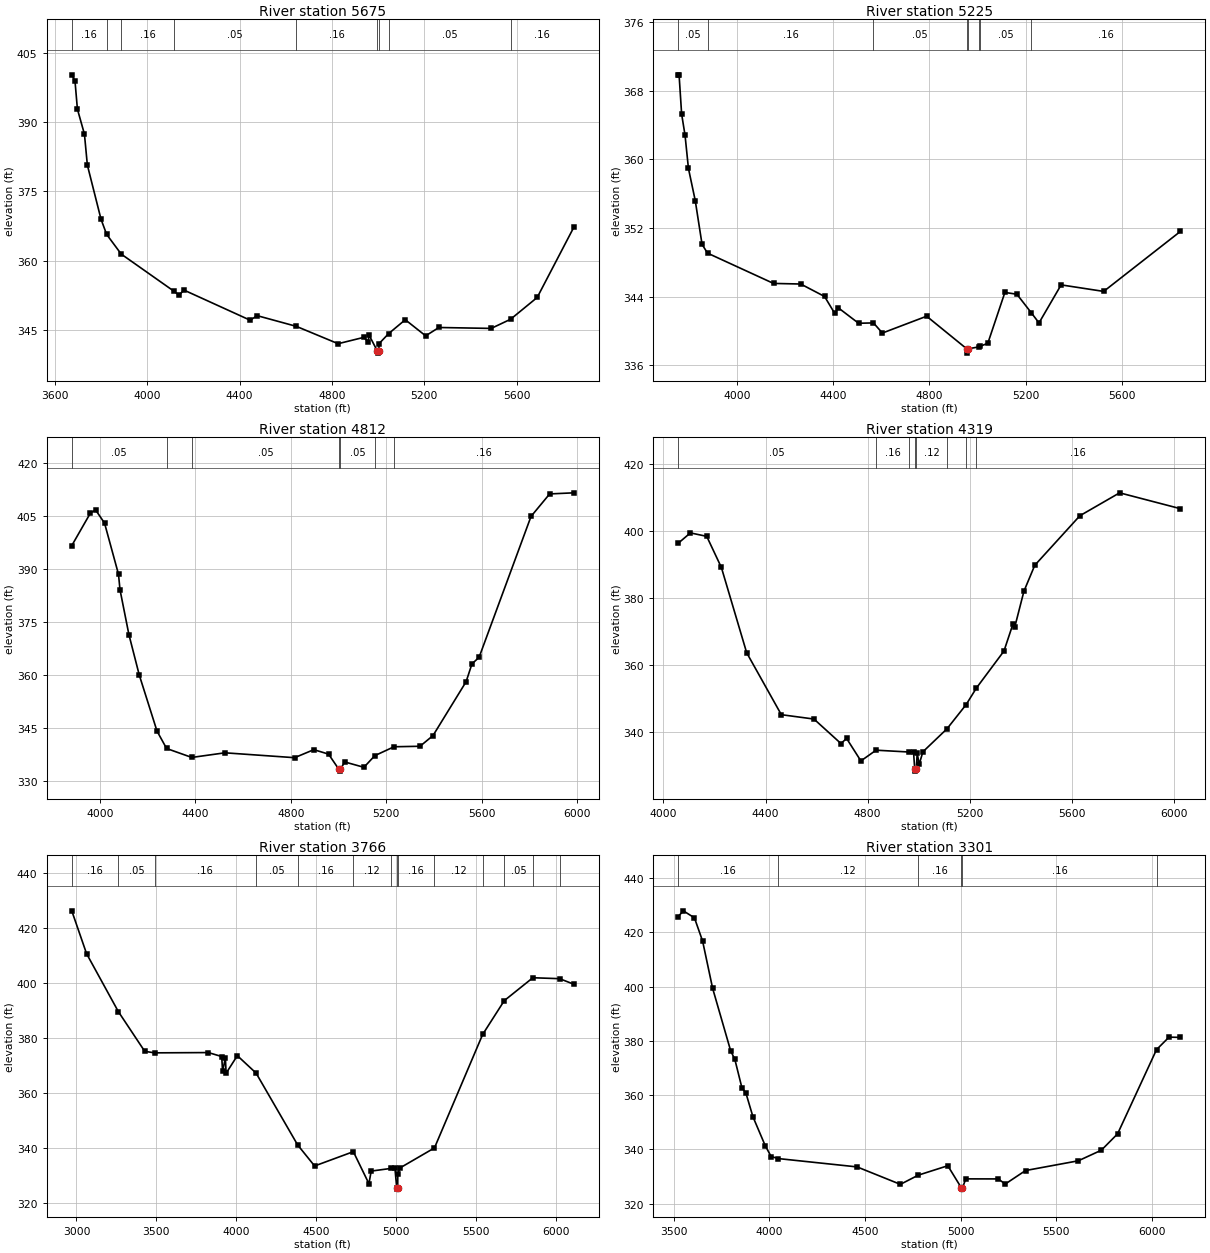
Type RM Length L Ch R = 1,5675,450,450,450
BEGIN DESCRIPTION:
UNT 029 IN CACR 12.0
END DESCRIPTION:
XS GIS Cut Line= 3
      3694870.31     10745056.62      3695189.76     10746466.38
      3695654.85     10747028.65
#Sta/Elev= 30
  3672.7  400.20  3686.6  398.90  3697.1  392.78  3727.6  387.36  3740.2  380.67
  3799.4  368.94  3823.8  365.65  3887.0  361.39  4115.7  353.34  4137.8  352.49
  4158.3  353.61  4445.4  347.08  4476.1  348.06  4645.4  345.75  4826.6  341.99
  4937.5  343.36  4956.0  342.45  4961.2  343.80  4996.1  340.45  4998.8  339.95
  5002.1  340.45  5004.3  342.02  5045.4  344.17  5117.6  347.18  5205.9  343.69
  5263.2  345.50  5489.8  345.30  5573.7  347.28  5689.1  352.00  5847.9  367.21
#Mann=9,-1,0
  3672.7    0.16       0  3823.8    0.05       0  3887.0    0.16       0
  4115.7    0.05       0  4645.4    0.16       0  4996.1    0.07       0
  5002.1    0.16       0  5045.4    0.05       0  5573.7    0.16       0
Bank Sta=4996.1,5002.1
Exp/Cntr=0.3,0.1

Type RM Length L Ch R = 1,5225,413,413,413
BEGIN DESCRIPTION:
UNT 029 IN CACR 11.0
END DESCRIPTION:
XS GIS Cut Line= 3
      3693849.61     10745560.19      3694749.61     10746460.19
      3695299.59     10747060.16
#Sta/Elev= 30
  3756.5  369.84  3760.0  369.84  3770.6  365.27  3784.8  362.80  3798.9  358.94
  3827.2  355.19  3855.5  350.09  3878.2  349.07  4152.5  345.54  4265.6  345.47
  4364.6  344.02  4407.0  342.04  4421.2  342.71  4506.0  340.90  4567.9  340.94
  4605.0  339.76  4788.9  341.72  4955.6  337.92  4958.3  337.42  4961.6  337.92
  5008.2  338.16  5009.8  338.20  5043.2  338.57  5114.1  344.49  5164.0  344.28
  5224.7  342.09  5255.9  340.94  5347.8  345.37  5524.7  344.61  5843.2  351.59
#Mann=8,-1,0
  3756.5    0.05       0  3878.2    0.16       0  4567.9    0.05       0
  4955.6    0.03       0  4961.6    0.05       0  5008.2    0.16       0
  5009.8    0.05       0  5224.7    0.16       0
Bank Sta=4955.6,4961.6
Exp/Cntr=0.3,0.1

Type RM Length L Ch R = 1,4812,493,493,493
BEGIN DESCRIPTION:
UNT 029 IN CACR 10.0
END DESCRIPTION:
XS GIS Cut Line= 4
      3693489.70     10746094.29      3694388.87     10746610.78
      3694460.05     10746784.39      3694778.75     10747604.66
#Sta/Elev= 30
  3882.3  396.55  3960.8  405.80  3982.4  406.62  4019.7  402.91  4078.2  388.44
  4084.4  384.10  4121.8  371.40  4165.0  360.01  4239.7  344.08  4279.8  339.18
  4385.3  336.65  4524.4  337.96  4816.3  336.58  4897.0  338.85  4958.6  337.59
  5002.1  333.28  5004.8  332.78  5008.1  333.28  5026.7  335.37  5106.9  333.86
  5152.7  337.16  5233.1  339.67  5342.1  339.81  5396.5  342.83  5535.3  358.07
  5559.8  363.12  5589.7  364.96  5807.4  404.81  5885.5  411.17  5986.9  411.48
#Mann=7,-1,0
  3882.3    0.05       0  4279.8    0.16       0  4385.3    0.05       0
  5002.1    0.03       0  5008.1    0.05       0  5152.7    0.12       0
  5233.1    0.16       0
Bank Sta=5002.1,5008.1
Exp/Cntr=0.3,0.1

Type RM Length L Ch R = 1,4319,553,553,553
BEGIN DESCRIPTION:
UNT 029 IN CACR 9.0
END DESCRIPTION:
XS GIS Cut Line= 3
      3693485.37     10746207.14      3694099.61     10746960.19
      3694783.13     10747682.85
#Sta/Elev= 30
  4058.2  396.25  4105.9  399.33  4169.8  398.30  4227.2  389.02  4326.3  363.60
  4462.0  345.15  4589.8  343.85  4695.4  336.56  4717.7  338.06  4773.6  331.37
  4833.1  334.57  4963.8  334.02  4979.7  334.09  4984.6  328.83  4987.4  328.33
  4990.6  328.83  4994.1  333.72  5002.0  330.36  5016.4  334.08  5111.0  340.96
  5185.8  348.15  5226.1  353.10  5334.0  364.12  5369.6  372.27  5376.5  371.33
  5412.1  381.93  5454.6  389.67  5631.3  404.44  5787.0  411.27  6024.7  406.55
#Mann=8,-1,0
  4058.2    0.05       0  4833.1    0.16       0  4963.8    0.12       0
  4984.6    0.07       0  4990.6    0.12       0  5111.0    0.16       0
  5185.8    0.12       0  5226.1    0.16       0
Bank Sta=4984.6,4990.6
Exp/Cntr=0.3,0.1

Type RM Length L Ch R = 1,3766,465,465,465
BEGIN DESCRIPTION:
UNT 029 IN CACR 8.0
END DESCRIPTION:
XS GIS Cut Line= 6
      3692111.95     10746189.05      3693012.97     10746538.00
      3693190.05     10746553.62      3693799.61     10747210.19
      3694408.80     10747449.45      3694700.47     10747782.78
#Sta/Elev= 30
  2970.7  426.23  3063.3  410.64  3262.1  389.57  3426.9  375.15  3488.6  374.59
  3825.1  374.69  3908.3  373.25  3913.8  367.82  3931.2  372.77  3935.8  367.18
  4006.0  373.57  4123.2  367.23  4383.3  341.09  4489.2  333.46  4731.4  338.66
  4828.8  327.02  4843.0  331.60  4968.0  332.58  4991.5  332.59  5002.7  325.54
  5005.5  325.04  5008.7  325.54  5009.4  330.58  5022.3  332.72  5238.7  340.03
  5540.0  381.28  5675.2  393.57  5853.9  401.90  6021.0  401.56  6110.2  399.54
#Mann=14,-1,0
  2970.7    0.16       0  3262.1    0.05       0  3488.6    0.16       0
  4123.2    0.05       0  4383.3    0.16       0  4731.4    0.12       0
  4968.0    0.16       0  5002.7    0.07       0  5008.7    0.16       0
  5238.7    0.12       0  5540.0    0.16       0  5675.2    0.05       0
  5853.9    0.16       0  6021.0    0.05       0
Bank Sta=5002.7,5008.7
Exp/Cntr=0.3,0.1

Type RM Length L Ch R = 1,3301,487,487,487
BEGIN DESCRIPTION:
UNT 029 IN CACR 7.0
END DESCRIPTION:
XS GIS Cut Line= 3
      3692221.27     10746631.73      3693499.61     10747410.19
      3694246.67     10748255.99
#Sta/Elev= 30
  3523.6  425.84  3550.2  427.95  3608.3  425.37  3651.0  416.80  3703.2  399.45
  3798.1  376.28  3819.4  373.25  3856.2  362.83  3877.5  360.77  3914.3  352.04
  3978.3  341.43  4009.2  337.41  4046.5  336.65  4458.7  333.58  4685.2  327.15
  4778.7  330.54  4933.1  334.01  5003.7  325.89  5006.5  325.39  5009.7  325.89
  5027.4  329.17  5197.2  329.15  5233.2  327.25  5339.5  332.24  5615.5  335.83
  5736.0  339.74  5820.9  345.77  6024.5  376.81  6089.8  381.40  6148.8  381.31
#Mann=6,-1,0
  3523.6    0.16       0  4046.5    0.12       0  4778.7    0.16       0
  5003.7    0.07       0  5009.7    0.16       0  6024.5    0.05       0
Bank Sta=5003.7,5009.7
Exp/Cntr=0.3,0.1

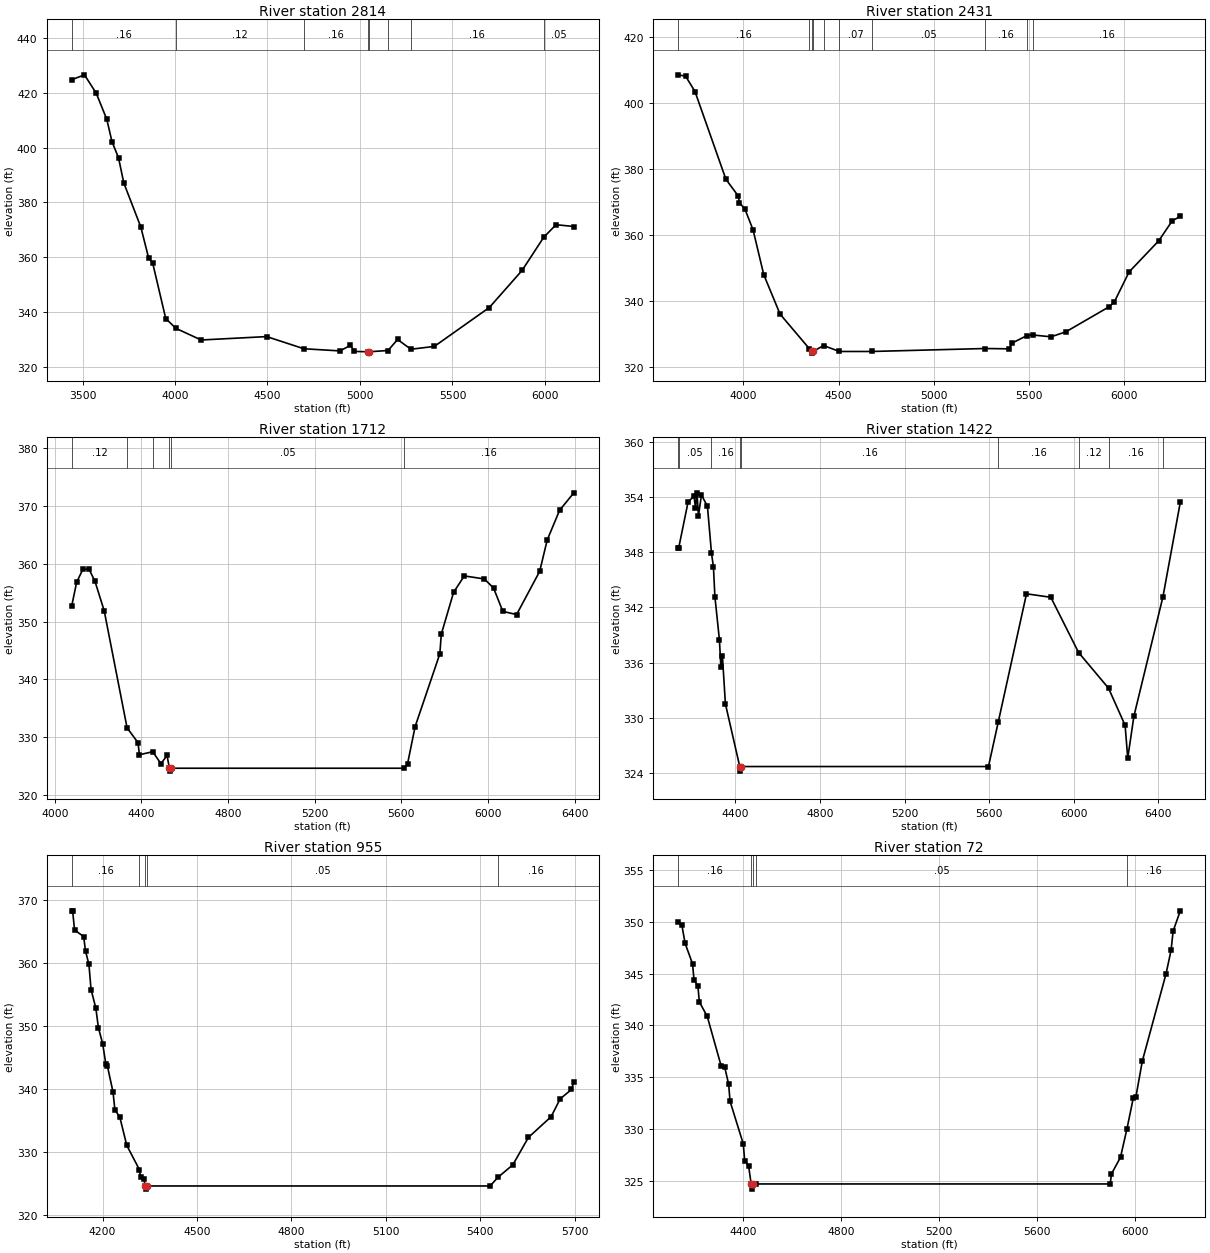
Type RM Length L Ch R = 1,2814,383,383,383
BEGIN DESCRIPTION:
UNT 029 IN CACR 6.0
END DESCRIPTION:
XS GIS Cut Line= 3
      3692164.01     10746689.04      3692929.64     10747360.91
      3694069.81     10748615.63
#Sta/Elev= 30
  3442.0  424.78  3510.6  426.57  3574.2  419.85  3631.2  410.34  3659.6  402.10
  3694.7  396.27  3723.2  387.08  3815.2  370.97  3857.9  359.54  3878.8  357.97
  3950.0  337.52  4005.1  333.95  4141.3  329.70  4495.6  330.94  4696.6  326.50
  4892.0  325.71  4948.3  327.75  4970.0  325.52  5044.7  325.40  5047.4  324.90
  5050.7  325.40  5151.7  325.86  5203.1  329.88  5275.3  326.32  5401.8  327.35
  5699.1  341.56  5876.1  355.10  5993.3  367.24  6059.9  371.82  6156.0  371.16
#Mann=8,-1,0
  3442.0    0.16       0  4005.1    0.12       0  4696.6    0.16       0
  5044.7    0.07       0  5050.7    0.16       0  5151.7    0.05       0
  5275.3    0.16       0  5993.3    0.05       0
Bank Sta=5044.7,5050.7
Exp/Cntr=0.3,0.1

Type RM Length L Ch R = 1,2431,719,719,719
BEGIN DESCRIPTION:
UNT 029 IN CACR 5.0
END DESCRIPTION:
XS GIS Cut Line= 3
      3691940.07     10746985.93      3692762.97     10747694.25
      3693841.13     10748808.87
#Sta/Elev= 30
  3658.1  408.56  3696.7  408.16  3746.1  403.49  3908.5  376.88  3973.2  371.83
  3979.8  369.78  4008.3  367.85  4051.1  361.54  4107.1  347.98  4192.7  336.02
  4346.8  325.51  4359.7  324.68  4362.5  324.18  4365.7  324.68  4421.4  326.48
  4504.1  324.68  4674.2  324.68  5268.8  325.58  5396.3  325.48  5410.4  327.21
  5489.8  329.51  5519.8  329.68  5615.4  329.13  5693.4  330.63  5919.7  338.20
  5948.0  339.69  6025.7  348.80  6181.4  358.24  6252.1  364.29  6294.6  365.65
#Mann=10,-1,0
  3658.1    0.16       0  4346.8    0.07       0  4359.7   0.035       0
  4365.7    0.07       0  4421.4    0.12       0  4504.1    0.07       0
  4674.2    0.05       0  5268.8    0.16       0  5489.8    0.05       0
  5519.8    0.16       0
Bank Sta=4359.7,4365.7
Exp/Cntr=0.3,0.1

Type RM Length L Ch R = 1,1712,290,290,290
BEGIN DESCRIPTION:
UNT 029 IN CACR 4.0
END DESCRIPTION:
XS GIS Cut Line= 3
      3691653.56     10747444.21      3692591.09     10748397.37
      3693335.23     10749037.43
#Sta/Elev= 30
  4078.4  352.74  4101.0  356.79  4129.3  358.98  4157.6  359.08  4185.8  356.91
  4228.3  351.83  4333.8  331.65  4383.9  329.11  4391.0  327.01  4452.4  327.53
  4490.0  325.46  4518.3  326.88  4529.4  324.68  4532.2  324.18  4535.4  324.68
  5612.1  324.68  5628.9  325.44  5664.0  331.87  5778.1  344.43  5784.7  347.80
  5841.7  355.05  5891.1  357.87  5983.3  357.35  6026.1  355.79  6068.9  351.75
  6132.5  351.20  6239.0  358.65  6274.1  364.09  6331.1  369.20  6396.9  372.21
#Mann=6,-1,0
  4078.4    0.12       0  4333.8    0.16       0  4452.4    0.05       0
  4529.4   0.033       0  4535.4    0.05       0  5612.1    0.16       0
Bank Sta=4529.4,4535.4
Exp/Cntr=0.3,0.1

Type RM Length L Ch R = 1,1422,467,467,467
BEGIN DESCRIPTION:
UNT 029 IN CACR 3.0
END DESCRIPTION:
XS GIS Cut Line= 3
      3691455.68     10747689.04      3692099.61     10748310.19
      3692975.58     10749500.27
#Sta/Elev= 30
  4130.8  348.44  4132.7  348.44  4176.9  353.43  4205.2  354.14  4212.2  352.85
  4219.4  354.47  4226.3  351.97  4240.5  354.24  4268.8  353.00  4287.9  347.91
  4297.1  346.41  4304.0  343.18  4325.4  338.47  4332.3  335.50  4339.5  336.72
  4353.7  331.50  4421.4  324.68  4424.2  324.18  4427.4  324.68  5596.7  324.68
  5643.2  329.55  5776.4  343.48  5891.4  343.10  6022.5  337.09  6163.9  333.21
  6242.3  329.17  6254.8  325.59  6284.0  330.17  6421.0  343.14  6503.2  353.45
#Mann=9,-1,0
  4130.8    0.12       0  4132.7    0.05       0  4287.9    0.16       0
  4421.4   0.033       0  4427.4    0.16       0  5643.2    0.16       0
  6022.5    0.12       0  6163.9    0.16       0  6421.0    0.12       0
Bank Sta=4421.4,4427.4
Exp/Cntr=0.3,0.1

Type RM Length L Ch R = 1,955,883,883,883
BEGIN DESCRIPTION:
UNT 029 IN CACR 2.0
END DESCRIPTION:
XS GIS Cut Line= 3
      3690999.64     10748310.20      3691799.61     10748660.19
      3692399.62     10749060.19
#Sta/Elev= 30
  4102.4  368.36  4105.1  368.36  4111.3  365.31  4140.2  364.28  4146.0  361.98
  4156.9  359.85  4163.6  355.87  4178.8  352.93  4187.0  349.79  4200.6  347.27
  4210.4  344.06  4215.8  343.66  4233.4  339.59  4239.2  336.82  4255.2  335.56
  4277.0  331.13  4317.2  327.27  4320.7  326.04  4331.6  325.82  4335.2  324.68
  4338.0  324.18  4341.2  324.68  5430.8  324.68  5456.0  326.07  5502.9  328.03
  5552.5  332.39  5624.6  335.68  5653.1  338.50  5689.2  340.00  5696.7  341.24
#Mann=5,-1,0
  4102.4    0.16       0  4317.2    0.05       0  4335.2   0.033       0
  4341.2    0.05       0  5456.0    0.16       0
Bank Sta=4335.2,4341.2
Exp/Cntr=0.3,0.1

Type RM Length L Ch R = 1,72,0,0,0
BEGIN DESCRIPTION:
UNT 029 IN CACR 1.0
END DESCRIPTION:
XS GIS Cut Line= 4
      3690875.55     10748665.64      3691265.28     10749383.48
      3691361.64     10749404.32      3692466.46     10749139.16
#Sta/Elev= 30
  4133.4  349.96  4148.3  349.69  4161.3  347.94  4192.0  345.94  4197.7  344.43
  4213.9  343.77  4219.6  342.27  4251.9  340.87  4309.3  336.04  4323.2  335.97
  4339.4  334.32  4345.1  332.67  4399.2  328.55  4404.9  326.93  4421.1  326.39
  4431.4  324.68  4434.2  324.18  4437.4  324.68  4451.6  324.68  5898.6  324.68
  5903.7  325.65  5940.6  327.26  5967.1  330.02  5992.9  332.99  6003.1  333.04
  6029.7  336.55  6126.5  344.97  6147.1  347.24  6155.7  349.12  6185.0  351.07
#Mann=5,-1,0
  4133.4    0.16       0  4431.4   0.033       0  4437.4    0.16       0
  4451.6    0.05       0  5967.1    0.16       0
Bank Sta=4431.4,4437.4
Exp/Cntr=0.3,0.1

Chan Stop Cuts=-1