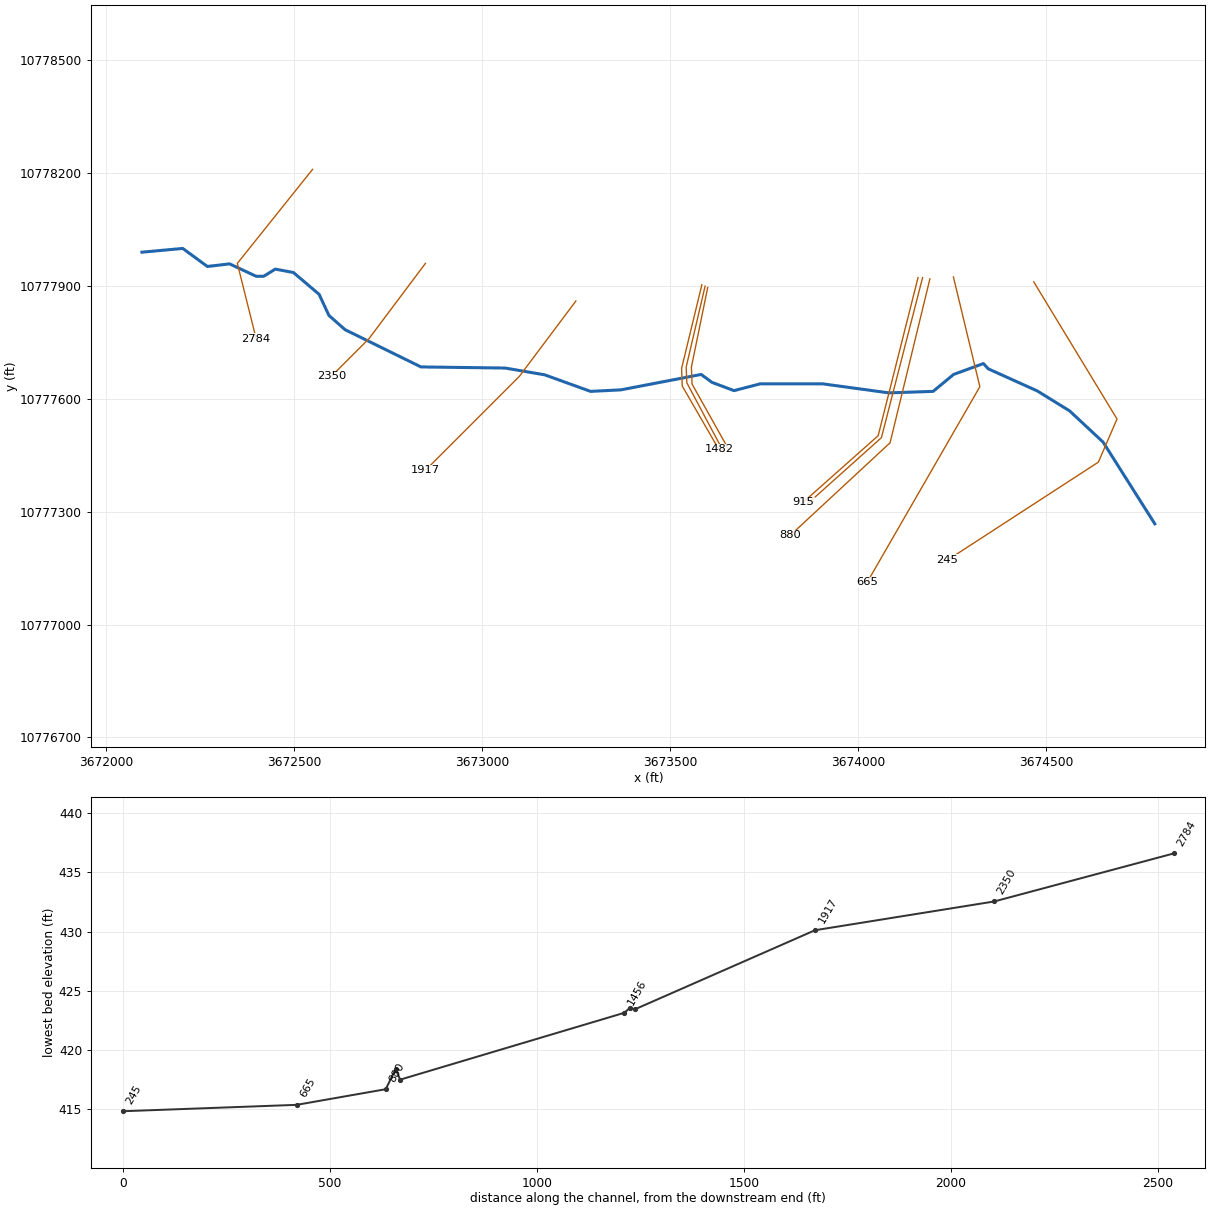
--- UNT 031 IN CACR.prj (project) ---

Proj Title=UNT 031 IN CACR Base Level Engineering
Current Plan=p01
Default Exp/Contr=0.3,0.1
English Units
Geom File=g01
Flow File=f01
Plan File=p01
BEGIN DESCRIPTION:
UNT 031 IN CACR
END DESCRIPTION:

--- UNT 031 IN CACR.p01 (plan) ---

Plan Title=Multiple Run
Short Identifier=Multiple
Geom File=g01
Flow File=f01
Subcritical Flow
K Sum by GR= 0
Std Step Tol= 0.01
Critical Tol= 0.01
Num of Std Step Trials= 20
Max Error Tol= 0.3
Flow Tol Ratio= 0.001
Split Flow NTrial= 30
Split Flow Tol= 0.02
Split Flow Ratio= 0.02
Log Output Level= 0
Friction Slope Method= 1
Unsteady Friction Slope Method= 2
Unsteady Bridges Friction Slope Method= 1
Parabolic Critical Depth
Global Vel Dist=  1 , 1 , 1
Global Log Level= 0
CheckData=True
Encroach Param= -1, 0, 0, 0
BEGIN DESCRIPTION:
Multiple Run
END DESCRIPTION:

--- UNT 031 IN CACR.f01 (steady flow) ---

Flow Title=Multiple
Number of Profiles=7
Profile Names=10-year,25-year,50-year,1pct_min,100-year,1pct_plu,500-year
River Rch & RM= UNT 031 IN CACR,Reach-1,2784
     597     814     993     890    1204    1628    1771
Boundary for River Rch & Prof#=UNT 031 IN CACR,Reach-1,1
Up Type=0
Dn Type=3
Dn Slope=0.005
Boundary for River Rch & Prof#=UNT 031 IN CACR,Reach-1,2
Up Type=0
Dn Type=3
Dn Slope=0.005
Boundary for River Rch & Prof#=UNT 031 IN CACR,Reach-1,3
Up Type=0
Dn Type=3
Dn Slope=0.005
Boundary for River Rch & Prof#=UNT 031 IN CACR,Reach-1,4
Up Type=0
Dn Type=3
Dn Slope=0.005
Boundary for River Rch & Prof#=UNT 031 IN CACR,Reach-1,5
Up Type=0
Dn Type=3
Dn Slope=0.005
Boundary for River Rch & Prof#=UNT 031 IN CACR,Reach-1,6
Up Type=0
Dn Type=3
Dn Slope=0.005
Boundary for River Rch & Prof#=UNT 031 IN CACR,Reach-1,7
Up Type=0
Dn Type=3
Dn Slope=0.005

--- UNT 031 IN CACR.g01 (geometry) ---

Geom Title=Existing Conditions

River Reach=UNT 031 IN CACR,Reach-1
Reach XY= 30
      3672096.00     10777990.00      3672204.50     10778000.00
      3672270.00     10777952.00      3672329.00     10777959.00
      3672399.50     10777926.00      3672419.75     10777926.00
      3672450.50     10777945.00      3672498.75     10777936.00
      3672567.00     10777878.00      3672593.00     10777822.00
      3672636.00     10777784.00      3672837.75     10777685.00
      3673061.75     10777682.00      3673166.75     10777664.00
      3673288.50     10777620.00      3673369.00     10777624.00
      3673582.75     10777665.00      3673611.25     10777644.00
      3673670.00     10777622.00      3673739.50     10777640.00
      3673906.00     10777640.00      3674081.75     10777616.00
      3674199.25     10777620.00      3674253.75     10777665.00
      3674333.00     10777694.00      3674345.75     10777680.00
      3674476.50     10777621.00      3674562.25     10777568.00
      3674651.25     10777485.00      3674788.50     10777268.00

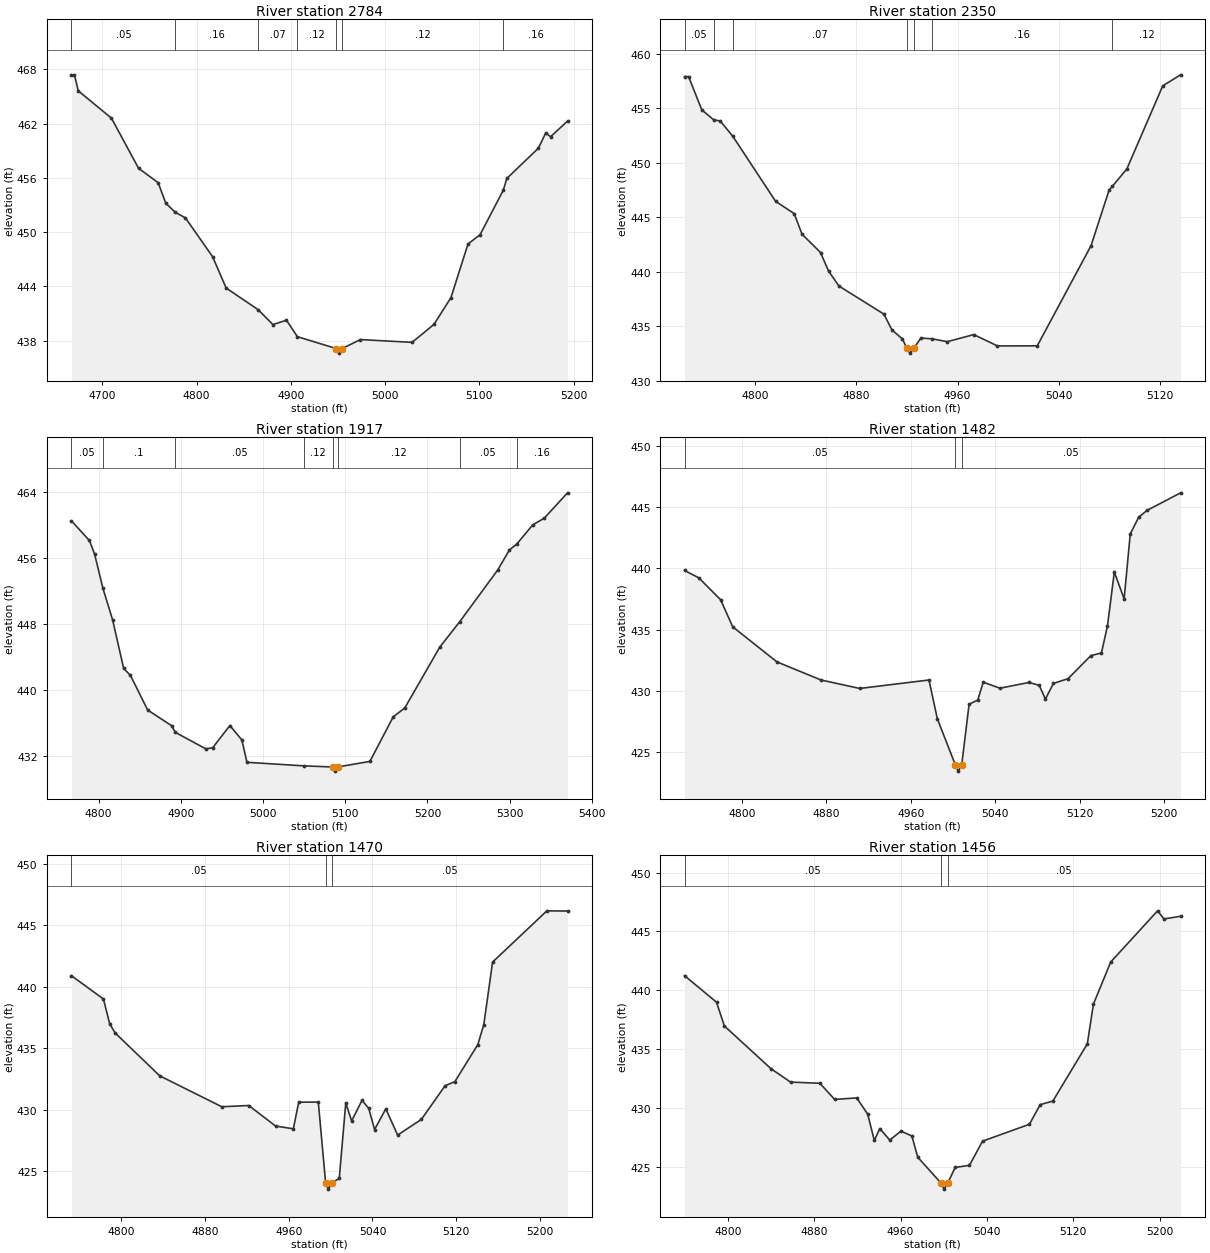
Type RM Length L Ch R = 1,2784,434,434,434
BEGIN DESCRIPTION:
UNT 031 IN CACR 6.0
END DESCRIPTION:
XS GIS Cut Line= 3
      3672549.61     10778210.18      3672349.61     10777960.19
      3672399.61     10777760.19
#Sta/Elev= 30
  4667.2  467.39  4670.4  467.39  4674.4  465.62  4709.6  462.60  4738.4  457.05
  4759.2  455.46  4767.2  453.20  4777.4  452.18  4788.1  451.57  4816.9  447.28
  4831.3  443.81  4865.3  441.41  4880.9  439.77  4895.3  440.25  4906.9  438.43
  4948.3  437.11  4951.1  436.61  4954.3  437.11  4973.7  438.11  5028.6  437.80
  5051.8  439.79  5069.8  442.75  5087.9  448.68  5100.7  449.71  5125.3  454.62
  5129.1  455.93  5162.6  459.28  5170.3  460.95  5175.5  460.55  5193.5  462.27
#Mann=7,-1,0
  4667.2    0.05       0  4777.4    0.16       0  4865.3    0.07       0
  4906.9    0.12       0  4948.3    0.07       0  4954.3    0.12       0
  5125.3    0.16       0
Bank Sta=4948.3,4954.3
Exp/Cntr=0.3,0.1

Type RM Length L Ch R = 1,2350,433,433,433
BEGIN DESCRIPTION:
UNT 031 IN CACR 5.0
END DESCRIPTION:
XS GIS Cut Line= 3
      3672849.63     10777960.21      3672699.61     10777760.19
      3672599.64     10777660.22
#Sta/Elev= 30
  4744.6  457.92  4747.8  457.92  4758.2  454.87  4767.5  453.96  4772.8  453.84
  4782.7  452.44  4816.5  446.47  4831.1  445.35  4837.3  443.46  4851.9  441.78
  4858.2  440.08  4866.5  438.70  4901.9  436.13  4908.2  434.69  4916.5  433.85
  4919.8  433.05  4922.5  432.55  4925.8  433.05  4931.1  433.93  4939.6  433.87
  4951.9  433.60  4972.8  434.25  4991.5  433.21  5022.9  433.22  5065.3  442.40
  5079.5  447.48  5082.2  447.86  5093.6  449.45  5121.9  457.07  5136.0  458.08
#Mann=7,-1,0
  4744.6    0.05       0  4767.5    0.16       0  4782.7    0.07       0
  4919.8    0.07       0  4925.8    0.07       0  4939.6    0.16       0
  5082.2    0.12       0
Bank Sta=4919.8,4925.8
Exp/Cntr=0.3,0.1

Type RM Length L Ch R = 1,1917,435,435,435
BEGIN DESCRIPTION:
UNT 031 IN CACR 4.0
END DESCRIPTION:
XS GIS Cut Line= 3
      3673249.59     10777860.16      3673099.61     10777660.19
      3672849.63     10777410.20
#Sta/Elev= 30
  4767.0  460.47  4788.8  458.09  4795.1  456.45  4805.2  452.31  4817.0  448.48
  4830.5  442.58  4838.8  441.72  4859.7  437.53  4888.8  435.63  4893.5  434.81
  4930.5  432.82  4938.8  432.96  4959.7  435.65  4974.3  433.90  4980.5  431.19
  5049.7  430.76  5084.7  430.62  5087.4  430.12  5090.7  430.62  5130.1  431.30
  5158.4  436.70  5172.5  437.78  5215.0  445.15  5239.4  448.25  5285.7  454.53
  5299.8  456.95  5308.4  457.62  5328.1  459.98  5342.2  460.80  5370.5  463.87
#Mann=8,-1,0
  4767.0    0.05       0  4805.2     0.1       0  4893.5    0.05       0
  5049.7    0.12       0  5084.7   0.035       0  5090.7    0.12       0
  5239.4    0.05       0  5308.4    0.16       0
Bank Sta=5084.7,5090.7
Exp/Cntr=0.3,0.1

Type RM Length L Ch R = 1,1482,12,12,12
BEGIN DESCRIPTION:
Mapping XS 6c7459c3
END DESCRIPTION:
XS GIS Cut Line= 4
      3673584.46     10777903.31      3673530.64     10777681.07
      3673532.38     10777634.20      3673629.59     10777465.81
#Sta/Elev= 30
  4745.6  439.82  4759.1  439.22  4779.7  437.44  4791.3  435.22  4833.1  432.36
  4874.9  430.88  4911.6  430.19  4977.2  430.88  4985.1  427.72  5002.2  423.94
  5004.9  423.44  5008.2  423.94  5015.2  428.90  5023.4  429.24  5028.6  430.70
  5044.4  430.21  5072.0  430.68  5081.7  430.44  5087.5  429.32  5095.1  430.60
  5109.0  430.99  5130.6  432.87  5140.6  433.09  5146.3  435.30  5152.8  439.69
  5162.1  437.50  5167.9  442.81  5175.9  444.17  5183.7  444.72  5215.6  446.16
#Mann=3,-1,0
  4745.6    0.05       0  5002.2    0.03       0  5008.2    0.05       0
Bank Sta=5002.2,5008.2
Exp/Cntr=0.3,0.1

Type RM Length L Ch R = 1,1470,14,14,14
BEGIN DESCRIPTION:
Mapping XS a766fe7d
END DESCRIPTION:
XS GIS Cut Line= 4
      3673593.15     10777899.85      3673542.79     10777684.55
      3673544.53     10777642.88      3673643.49     10777457.11
#Sta/Elev= 30
  4752.8  440.89  4783.3  439.00  4789.3  436.98  4794.5  436.24  4837.0  432.76
  4896.2  430.25  4922.0  430.35  4947.6  428.68  4964.5  428.46  4969.6  430.62
  4988.3  430.63  4995.3  424.06  4998.0  423.56  5001.3  424.06  5008.3  424.44
  5014.5  430.55  5020.1  429.10  5030.0  430.77  5036.4  430.12  5042.0  428.40
  5052.7  430.08  5064.0  427.95  5086.6  429.22  5109.3  431.96  5118.6  432.29
  5140.5  435.30  5146.2  436.92  5154.6  442.00  5206.4  446.16  5226.1  446.14
#Mann=3,-1,0
  4752.8    0.05       0  4995.3    0.03       0  5001.3    0.05       0
Bank Sta=4995.3,5001.3
Exp/Cntr=0.3,0.1

Type RM Length L Ch R = 1,1456,541,541,541
BEGIN DESCRIPTION:
UNT 031 IN CACR 3.0
END DESCRIPTION:
XS GIS Cut Line= 4
      3673600.09     10777896.36      3673556.68     10777684.55
      3673558.42     10777639.41      3673655.12     10777466.73
#Sta/Elev= 30
  4760.0  441.25  4789.6  439.00  4796.9  436.98  4840.0  433.36  4858.2  432.22
  4885.3  432.12  4899.0  430.75  4919.4  430.88  4929.6  429.50  4935.7  427.27
  4940.8  428.28  4950.0  427.30  4960.3  428.06  4970.5  427.65  4975.9  425.85
  4997.6  423.64  5000.3  423.14  5003.6  423.64  5010.6  424.98  5023.8  425.16
  5035.9  427.21  5079.3  428.64  5089.3  430.31  5101.0  430.61  5132.9  435.46
  5138.6  438.84  5154.6  442.41  5198.0  446.75  5203.9  446.06  5219.3  446.29
#Mann=3,-1,0
  4760.0    0.05       0  4997.6    0.03       0  5003.6    0.05       0
Bank Sta=4997.6,5003.6
Exp/Cntr=0.3,0.1

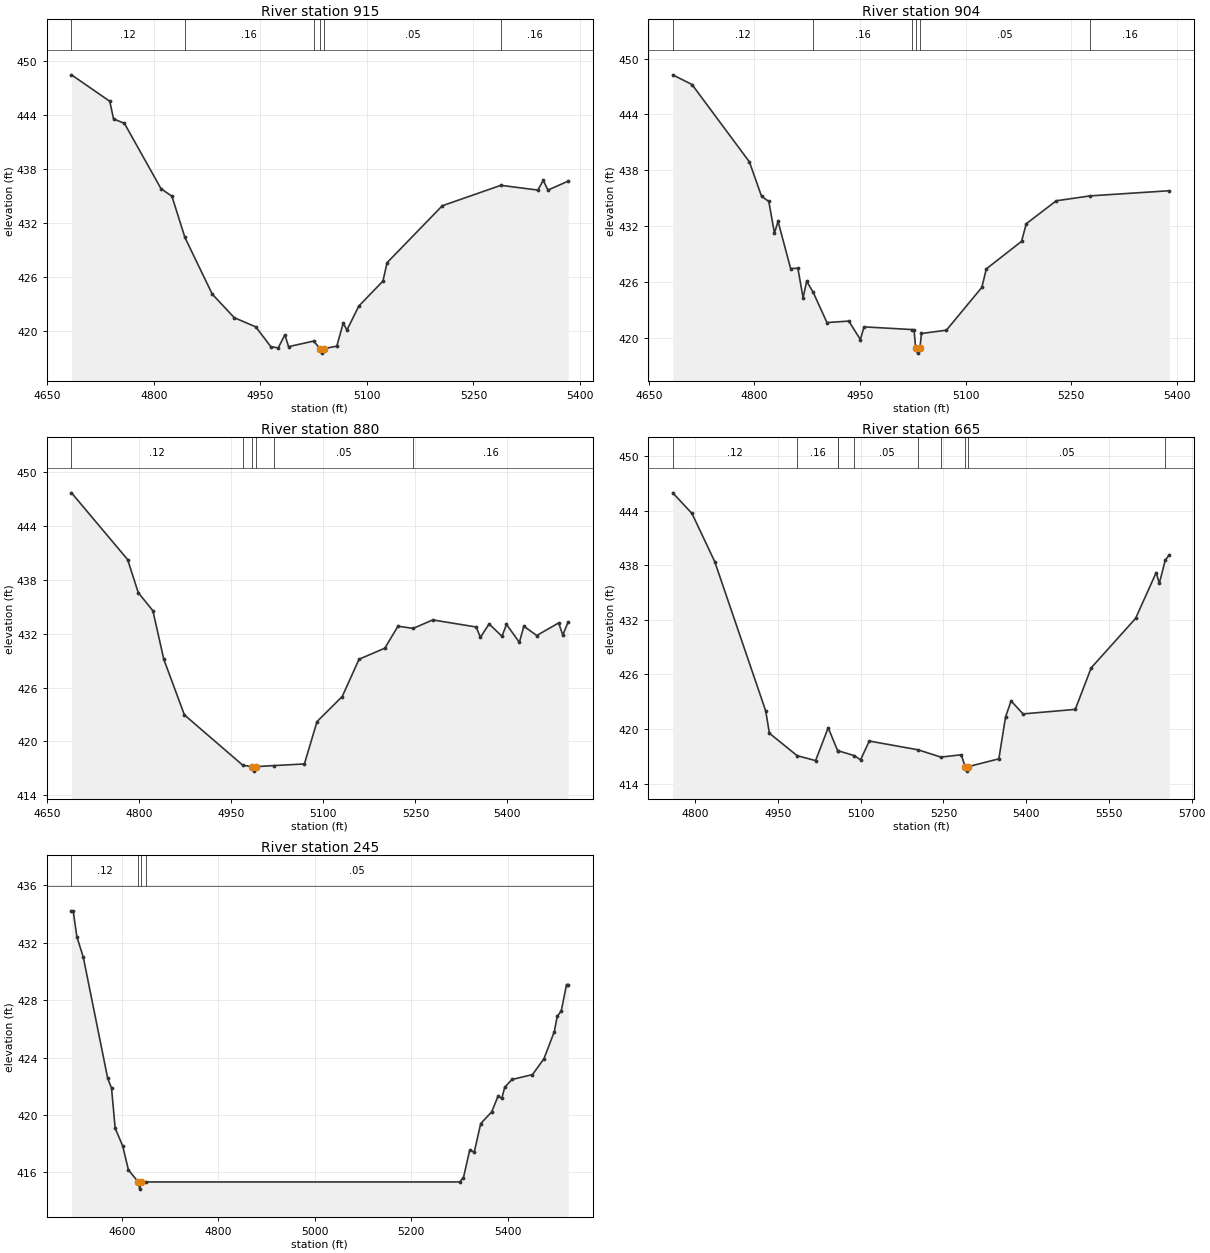
Type RM Length L Ch R = 1,915,11,11,11
BEGIN DESCRIPTION:
Mapping XS 11111b1f
END DESCRIPTION:
XS GIS Cut Line= 3
      3674159.12     10777922.42      3674053.21     10777502.25
      3673854.24     10777325.58
#Sta/Elev= 30
  4684.0  448.43  4737.9  445.49  4743.2  443.53  4758.5  443.04  4810.1  435.77
  4825.4  434.94  4843.7  430.36  4882.2  424.06  4913.2  421.44  4943.5  420.42
  4964.7  418.22  4975.1  418.08  4984.5  419.54  4989.7  418.22  5025.1  418.84
  5033.9  418.00  5036.7  417.50  5039.9  418.00  5057.6  418.28  5066.7  420.84
  5071.9  420.06  5088.5  422.72  5122.6  425.51  5128.4  427.55  5206.2  433.88
  5288.7  436.15  5340.8  435.62  5348.3  436.70  5355.0  435.62  5383.4  436.61
#Mann=6,-1,0
  4684.0    0.12       0  4843.7    0.16       0  5025.1    0.05       0
  5033.9    0.07       0  5039.9    0.05       0  5288.7    0.16       0
Bank Sta=5033.9,5039.9
Exp/Cntr=0.3,0.1

Type RM Length L Ch R = 1,904,24,24,24
BEGIN DESCRIPTION:
Mapping XS d8ef5e6e
END DESCRIPTION:
XS GIS Cut Line= 3
      3674171.27     10777922.41      3674061.89     10777497.05
      3673863.45     10777319.31
#Sta/Elev= 30
  4684.0  448.25  4711.4  447.21  4792.9  438.91  4810.2  435.21  4820.5  434.66
  4828.5  431.26  4833.6  432.53  4851.5  427.46  4861.8  427.49  4869.2  424.32
  4874.3  426.09  4883.5  424.92  4903.1  421.66  4934.1  421.82  4950.6  419.84
  4955.8  421.20  5023.7  420.91  5026.9  420.87  5029.1  418.88  5031.8  418.38
  5035.1  418.88  5037.4  420.49  5072.8  420.84  5123.2  425.44  5129.5  427.42
  5179.6  430.38  5186.3  432.27  5228.9  434.73  5277.3  435.26  5389.6  435.81
#Mann=6,-1,0
  4684.0    0.12       0  4883.5    0.16       0  5023.7    0.05       0
  5029.1    0.07       0  5035.1    0.05       0  5277.3    0.16       0
Bank Sta=5029.1,5035.1
Exp/Cntr=0.3,0.1

Type RM Length L Ch R = 1,880,215,215,215
BEGIN DESCRIPTION:
Mapping XS 53589f48
END DESCRIPTION:
XS GIS Cut Line= 3
      3674190.72     10777919.12      3674084.81     10777483.33
      3673819.95     10777237.70
#Sta/Elev= 30
  4689.3  447.68  4780.8  440.25  4798.1  436.57  4822.0  434.55  4839.8  429.14
  4873.4  422.95  4968.7  417.34  4983.6  417.19  4986.4  416.69  4989.6  417.19
  5020.1  417.31  5069.0  417.49  5089.6  422.21  5130.7  425.00  5158.1  429.15
  5200.1  430.38  5221.6  432.83  5246.3  432.58  5278.3  433.53  5349.1  432.74
  5356.0  431.58  5370.1  433.08  5391.1  431.71  5398.5  433.03  5419.5  431.03
  5426.8  432.83  5447.8  431.79  5483.5  433.19  5490.3  431.84  5499.0  433.31
#Mann=6,-1,0
  4689.3    0.12       0  4968.7    0.16       0  4983.6    0.07       0
  4989.6    0.16       0  5020.1    0.05       0  5246.3    0.16       0
Bank Sta=4983.6,4989.6
Exp/Cntr=0.3,0.1

Type RM Length L Ch R = 1,665,420,420,420
BEGIN DESCRIPTION:
UNT 031 IN CACR 2.0
END DESCRIPTION:
XS GIS Cut Line= 3
      3674253.21     10777924.14      3674323.52     10777632.46
      3674023.87     10777112.34
#Sta/Elev= 30
  4759.3  445.97  4794.2  443.70  4835.4  438.41  4927.9  421.98  4934.5  419.54
  4984.8  417.07  5018.3  416.53  5041.1  420.14  5058.4  417.60  5059.7  417.60
  5088.7  417.07  5099.8  416.61  5115.6  418.68  5204.4  417.71  5245.5  416.91
  5282.3  417.17  5289.3  415.87  5292.0  415.37  5295.3  415.87  5350.5  416.72
  5362.7  421.35  5372.7  423.09  5394.3  421.66  5489.0  422.16  5517.9  426.73
  5598.3  432.16  5635.7  437.20  5641.4  436.02  5652.1  438.56  5659.6  439.16
#Mann=10,-1,0
  4759.3    0.12       0  4984.8    0.16       0  5058.4    0.07       0
  5059.7    0.16       0  5088.7    0.05       0  5204.4    0.07       0
  5245.5    0.05       0  5289.3    0.07       0  5295.3    0.05       0
  5652.1    0.16       0
Bank Sta=5289.3,5295.3
Exp/Cntr=0.3,0.1

Type RM Length L Ch R = 1,245,0,0,0
BEGIN DESCRIPTION:
UNT 031 IN CACR 1.0
END DESCRIPTION:
XS GIS Cut Line= 4
      3674466.73     10777911.14      3674688.11     10777546.52
      3674638.63     10777431.94      3674237.62     10777171.55
#Sta/Elev= 30
  4495.9  434.22  4499.4  434.22  4507.0  432.42  4520.4  430.98  4571.0  422.54
  4578.9  421.87  4586.4  419.08  4601.9  417.85  4614.0  416.16  4634.4  415.33
  4637.1  414.83  4640.4  415.33  4650.5  415.33  5300.4  415.33  5308.4  415.63
  5321.5  417.57  5330.7  417.40  5344.2  419.40  5366.9  420.21  5379.9  421.29
  5388.0  421.17  5394.0  421.93  5409.1  422.47  5451.5  422.81  5475.3  423.92
  5496.8  425.81  5502.7  426.86  5511.1  427.25  5522.1  429.08  5525.4  429.08
#Mann=4,-1,0
  4495.9    0.12       0  4634.4   0.033       0  4640.4    0.12       0
  4650.5    0.05       0
Bank Sta=4634.4,4640.4
Exp/Cntr=0.3,0.1

Chan Stop Cuts=-1