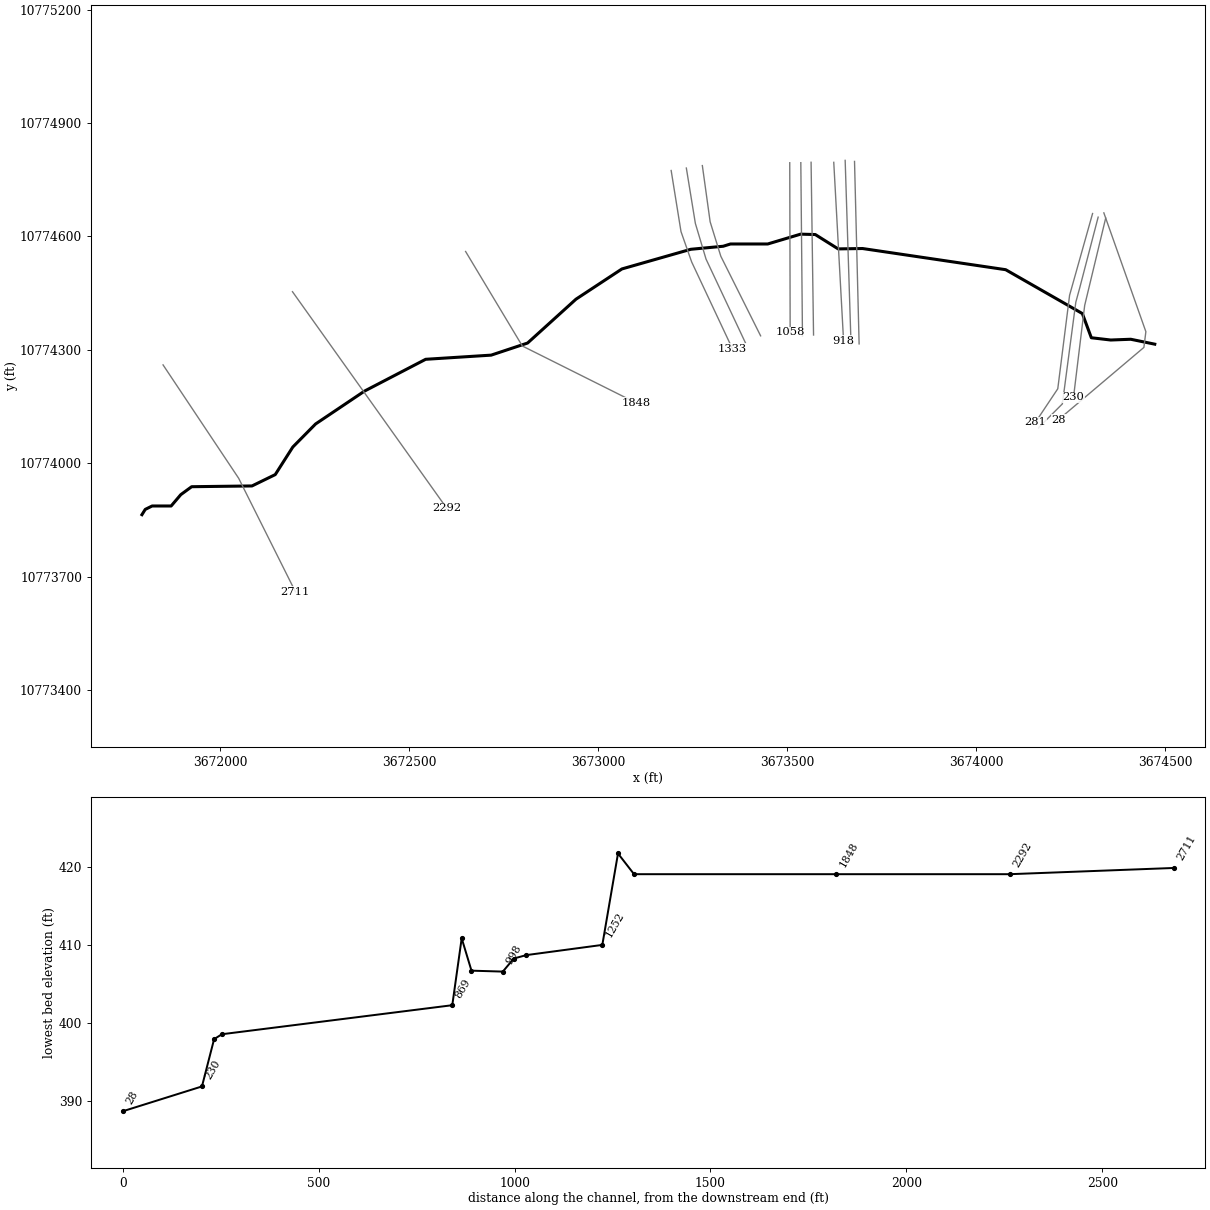
--- UNT 032 IN CACR.prj (project) ---

Proj Title=UNT 032 IN CACR Base Level Engineering
Current Plan=p01
Default Exp/Contr=0.3,0.1
English Units
Geom File=g01
Flow File=f01
Plan File=p01
BEGIN DESCRIPTION:
UNT 032 IN CACR
END DESCRIPTION:

--- UNT 032 IN CACR.p01 (plan) ---

Plan Title=Multiple Run
Short Identifier=Multiple
Geom File=g01
Flow File=f01
Subcritical Flow
K Sum by GR= 0
Std Step Tol= 0.01
Critical Tol= 0.01
Num of Std Step Trials= 20
Max Error Tol= 0.3
Flow Tol Ratio= 0.001
Split Flow NTrial= 30
Split Flow Tol= 0.02
Split Flow Ratio= 0.02
Log Output Level= 0
Friction Slope Method= 1
Unsteady Friction Slope Method= 2
Unsteady Bridges Friction Slope Method= 1
Parabolic Critical Depth
Global Vel Dist=  1 , 1 , 1
Global Log Level= 0
CheckData=True
Encroach Param= -1, 0, 0, 0
BEGIN DESCRIPTION:
Multiple Run
END DESCRIPTION:

--- UNT 032 IN CACR.f01 (steady flow) ---

Flow Title=Multiple
Number of Profiles=7
Profile Names=10-year,25-year,50-year,1pct_min,100-year,1pct_plu,500-year
River Rch & RM= UNT 032 IN CACR,Reach-1,2711
     587     805     988     891    1205    1630    1795
River Rch & RM= UNT 032 IN CACR,Reach-1,28
    1470    2084    2610    2391    3234    4374    4979
Boundary for River Rch & Prof#=UNT 032 IN CACR,Reach-1,1
Up Type=0
Dn Type=3
Dn Slope=0.005
Boundary for River Rch & Prof#=UNT 032 IN CACR,Reach-1,2
Up Type=0
Dn Type=3
Dn Slope=0.005
Boundary for River Rch & Prof#=UNT 032 IN CACR,Reach-1,3
Up Type=0
Dn Type=3
Dn Slope=0.005
Boundary for River Rch & Prof#=UNT 032 IN CACR,Reach-1,4
Up Type=0
Dn Type=3
Dn Slope=0.005
Boundary for River Rch & Prof#=UNT 032 IN CACR,Reach-1,5
Up Type=0
Dn Type=3
Dn Slope=0.005
Boundary for River Rch & Prof#=UNT 032 IN CACR,Reach-1,6
Up Type=0
Dn Type=3
Dn Slope=0.005
Boundary for River Rch & Prof#=UNT 032 IN CACR,Reach-1,7
Up Type=0
Dn Type=3
Dn Slope=0.005

--- UNT 032 IN CACR.g01 (geometry) ---

Geom Title=Existing Conditions

River Reach=UNT 032 IN CACR,Reach-1
Reach XY= 30
      3671793.75     10773864.00      3671802.50     10773878.00
      3671820.75     10773887.00      3671871.00     10773887.00
      3671896.50     10773917.00      3671925.25     10773938.00
      3672084.75     10773940.00      3672146.25     10773970.00
      3672192.75     10774043.00      3672253.00     10774104.00
      3672382.50     10774191.00      3672544.00     10774275.00
      3672717.25     10774286.00      3672813.50     10774318.00
      3672941.50     10774434.00      3673063.00     10774514.00
      3673245.25     10774566.00      3673330.75     10774574.00
      3673350.00     10774580.00      3673448.50     10774580.00
      3673535.50     10774606.00      3673574.25     10774605.00
      3673634.75     10774567.00      3673699.25     10774568.00
      3674077.75     10774512.00      3674280.50     10774396.00
      3674304.25     10774332.00      3674355.50     10774326.00
      3674408.50     10774328.00      3674472.00     10774315.00

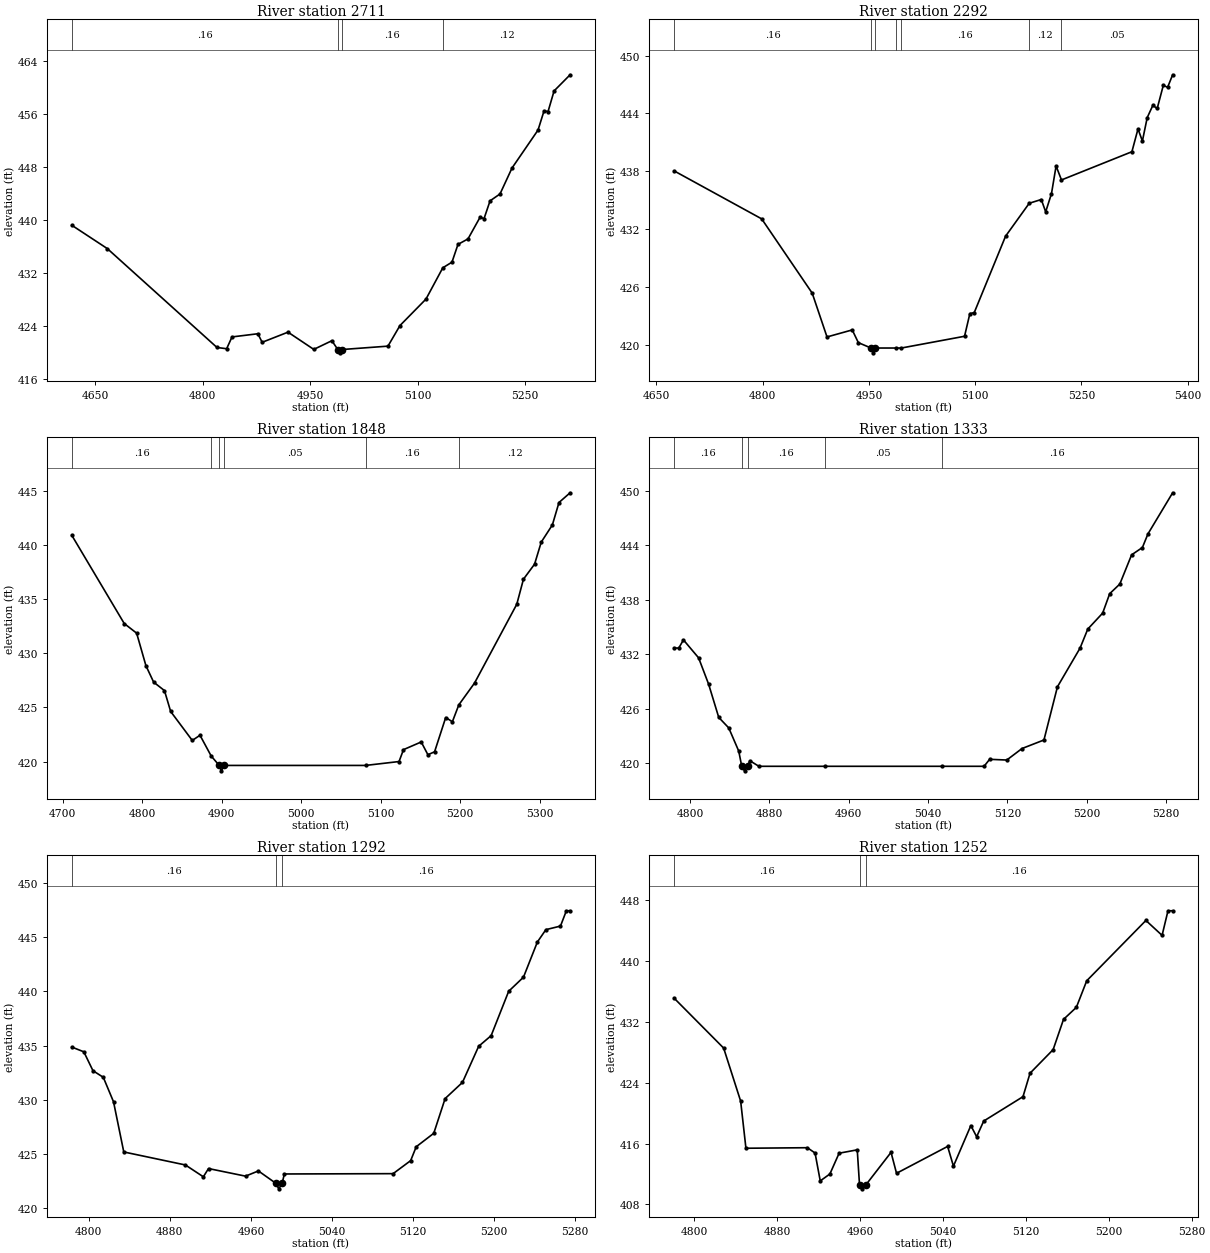
Type RM Length L Ch R = 1,2711,419,419,419
BEGIN DESCRIPTION:
UNT 032 IN CACR 6.0
END DESCRIPTION:
XS GIS Cut Line= 3
      3671849.62     10774260.18      3672049.61     10773960.19
      3672199.63     10773660.15
#Sta/Elev= 30
  4617.1  439.19  4666.7  435.67  4819.9  420.75  4833.4  420.56  4840.9  422.34
  4877.0  422.82  4883.0  421.53  4919.1  423.06  4955.1  420.46  4980.4  421.77
  4988.6  420.44  4991.4  419.94  4994.6  420.44  5058.7  420.95  5075.5  424.06
  5111.8  428.05  5135.3  432.77  5148.1  433.62  5156.5  436.30  5170.5  437.13
  5187.3  440.39  5192.9  440.19  5201.3  442.87  5215.2  443.91  5232.0  447.83
  5268.3  453.55  5276.7  456.45  5282.3  456.34  5290.7  459.45  5313.1  461.89
#Mann=4,-1,0
  4617.1    0.16       0  4988.6    0.07       0  4994.6    0.16       0
  5135.3    0.12       0
Bank Sta=4988.6,4994.6
Exp/Cntr=0.3,0.1

Type RM Length L Ch R = 1,2292,444,444,444
BEGIN DESCRIPTION:
UNT 032 IN CACR 5.0
END DESCRIPTION:
XS GIS Cut Line= 2
      3672191.82     10774453.81      3672599.79     10773880.92
#Sta/Elev= 30
  4675.4  438.02  4798.7  433.05  4870.0  425.34  4890.9  420.79  4926.5  421.52
  4935.1  420.20  4953.0  419.64  4955.8  419.14  4959.0  419.64  4987.7  419.64
  4995.8  419.64  5085.0  420.86  5092.5  423.21  5098.7  423.32  5142.9  431.25
  5176.3  434.67  5193.3  435.06  5199.5  433.78  5207.7  435.67  5214.2  438.54
  5221.8  437.09  5321.2  440.02  5329.8  442.39  5336.0  441.13  5342.8  443.56
  5350.7  444.83  5356.9  444.51  5365.5  446.91  5371.6  446.71  5378.7  448.01
#Mann=7,-1,0
  4675.4    0.16       0  4953.0    0.07       0  4959.0    0.16       0
  4987.7    0.05       0  4995.8    0.16       0  5176.3    0.12       0
  5221.8    0.05       0
Bank Sta=4953,4959
Exp/Cntr=0.3,0.1

Type RM Length L Ch R = 1,1848,515,515,515
BEGIN DESCRIPTION:
UNT 032 IN CACR 4.0
END DESCRIPTION:
XS GIS Cut Line= 3
      3672649.63     10774560.15      3672799.61     10774310.19
      3673099.60     10774160.20
#Sta/Elev= 30
  4711.6  440.92  4777.6  432.76  4793.2  431.87  4804.9  428.86  4814.6  427.34
  4828.2  426.56  4836.0  424.63  4863.2  421.95  4872.9  422.43  4887.0  420.51
  4897.1  419.64  4899.8  419.14  4903.1  419.64  5081.2  419.64  5123.3  420.00
  5128.9  421.10  5151.2  421.81  5159.6  420.63  5168.0  420.90  5182.0  424.07
  5190.4  423.68  5198.5  425.24  5218.3  427.26  5271.4  434.54  5279.8  436.86
  5293.8  438.25  5302.2  440.29  5316.2  441.88  5324.5  443.95  5338.5  444.85
#Mann=6,-1,0
  4711.6    0.16       0  4887.0    0.05       0  4897.1   0.033       0
  4903.1    0.05       0  5081.2    0.16       0  5198.5    0.12       0
Bank Sta=4897.1,4903.1
Exp/Cntr=0.3,0.1

Type RM Length L Ch R = 1,1333,41,41,41
BEGIN DESCRIPTION:
UNT 032 IN CACR 3.0
END DESCRIPTION:
XS GIS Cut Line= 4
      3673193.17     10774774.37      3673219.21     10774612.70
      3673247.42     10774532.40      3673355.26     10774302.72
#Sta/Elev= 30
  4784.1  432.67  4788.6  432.67  4793.3  433.57  4808.6  431.59  4818.7  428.69
  4828.9  425.03  4839.0  423.87  4849.1  421.31  4852.1  419.64  4854.9  419.14
  4858.1  419.64  4860.2  420.26  4869.4  419.64  4936.1  419.64  5053.7  419.64
  5096.5  419.64  5102.1  420.41  5119.4  420.33  5134.8  421.60  5156.9  422.54
  5170.5  428.40  5193.3  432.66  5201.1  434.76  5216.1  436.52  5223.2  438.66
  5233.4  439.72  5245.3  442.94  5256.2  443.75  5261.8  445.25  5286.7  449.78
#Mann=5,-1,0
  4784.1    0.16       0  4852.1   0.033       0  4858.1    0.16       0
  4936.1    0.05       0  5053.7    0.16       0
Bank Sta=4852.1,4858.1
Exp/Cntr=0.3,0.1

Type RM Length L Ch R = 1,1292,40,40,40
BEGIN DESCRIPTION:
Mapping XS 91a0b1b5
END DESCRIPTION:
XS GIS Cut Line= 4
      3673233.32     10774780.86      3673257.19     10774634.40
      3673285.40     10774540.00      3673389.59     10774318.60
#Sta/Elev= 30
  4783.3  434.87  4795.2  434.43  4804.2  432.69  4814.4  432.08  4824.5  429.82
  4834.6  425.20  4895.4  424.00  4913.1  422.91  4918.2  423.67  4954.7  422.97
  4967.4  423.45  4984.8  422.30  4987.5  421.80  4990.8  422.30  4993.0  423.17
  5100.3  423.20  5117.6  424.40  5123.1  425.68  5140.4  426.92  5151.6  430.12
  5168.7  431.61  5184.7  434.94  5197.0  435.92  5214.3  440.01  5228.9  441.31
  5242.6  444.55  5251.0  445.69  5265.4  446.02  5271.2  447.43  5274.9  447.43
#Mann=3,-1,0
  4783.3    0.16       0  4984.8    0.07       0  4990.8    0.16       0
Bank Sta=4984.8,4990.8
Exp/Cntr=0.3,0.1

Type RM Length L Ch R = 1,1252,194,194,194
BEGIN DESCRIPTION:
Mapping XS 649d1b1d
END DESCRIPTION:
XS GIS Cut Line= 4
      3673275.64     10774787.37      3673296.25     10774638.74
      3673324.46     10774547.60      3673429.71     10774337.10
#Sta/Elev= 30
  4780.8  435.06  4828.4  428.53  4844.8  421.57  4849.9  415.38  4909.2  415.45
  4916.6  414.75  4921.6  411.09  4930.9  412.00  4939.8  414.73  4957.3  415.17
  4959.5  410.55  4962.3  410.05  4965.5  410.55  4989.9  414.84  4995.2  412.09
  5044.5  415.62  5050.1  413.03  5066.9  418.36  5072.5  416.89  5079.3  418.95
  5117.2  422.15  5124.0  425.23  5146.3  428.33  5156.3  432.30  5168.7  433.88
  5178.7  437.37  5235.8  445.29  5251.4  443.33  5257.1  446.56  5261.6  446.56
#Mann=3,-1,0
  4780.8    0.16       0  4959.5    0.07       0  4965.5    0.16       0
Bank Sta=4959.5,4965.5
Exp/Cntr=0.3,0.1

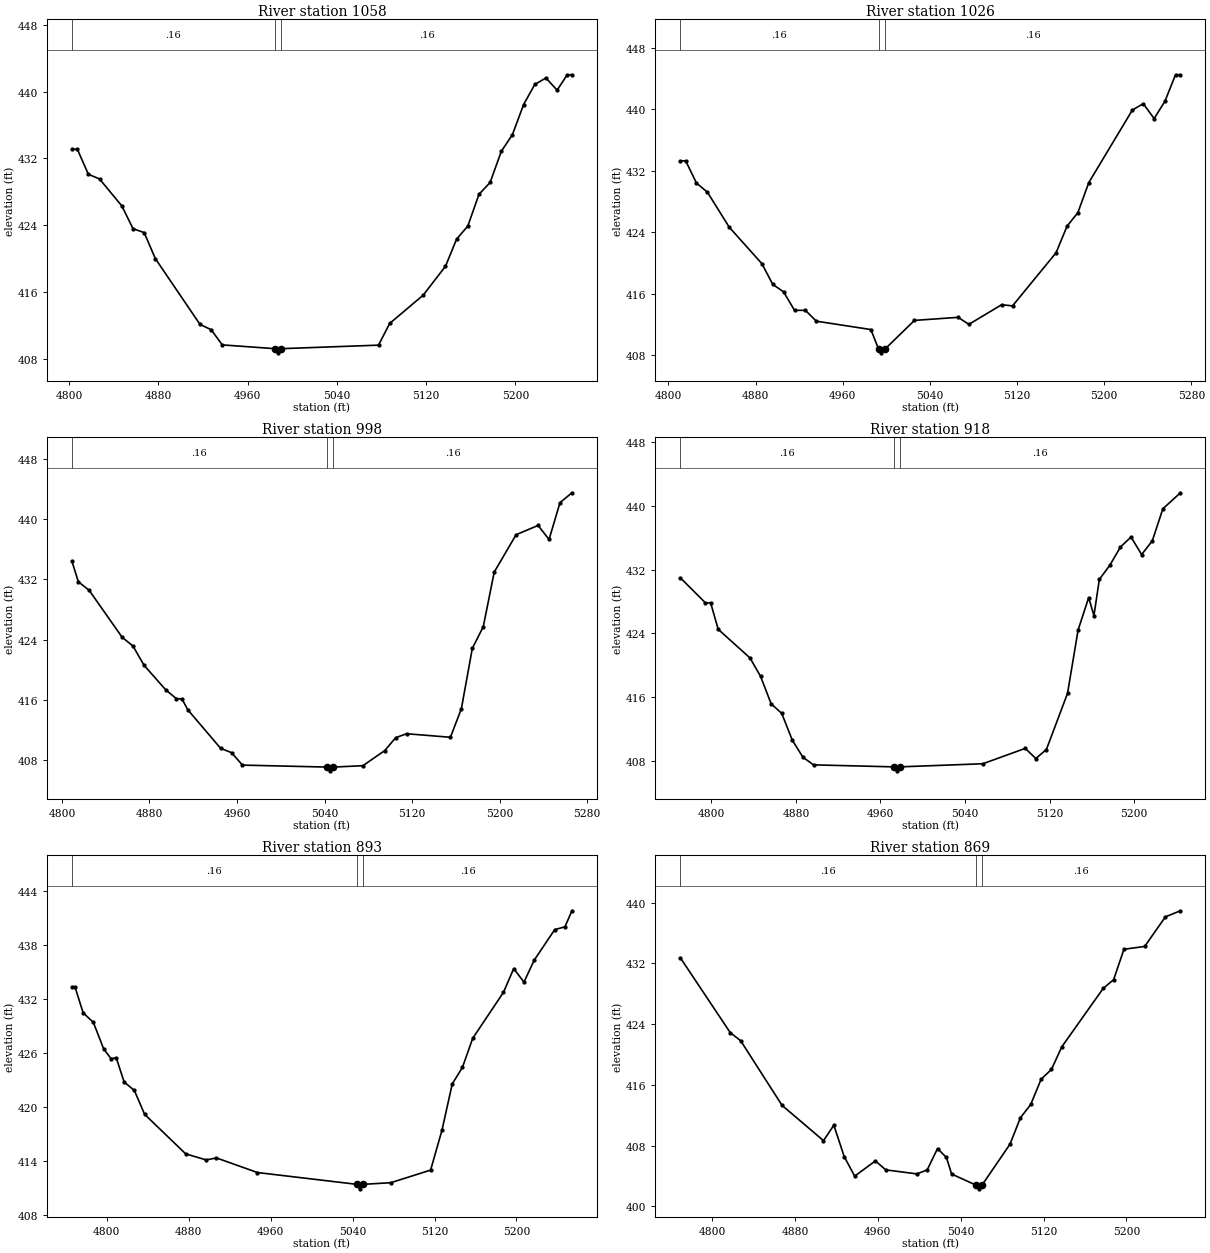
Type RM Length L Ch R = 1,1058,32,32,32
BEGIN DESCRIPTION:
Mapping XS 7495322f
END DESCRIPTION:
XS GIS Cut Line= 2
      3673506.76     10774794.95      3673507.84     10774346.85
#Sta/Elev= 30
  4802.6  433.11  4807.5  433.11  4817.4  430.11  4827.4  429.55  4847.4  426.32
  4857.4  423.60  4867.4  423.13  4877.4  420.02  4917.4  412.15  4927.4  411.51
  4937.4  409.69  4984.4  409.24  4987.1  408.74  4990.4  409.24  5077.4  409.66
  5087.4  412.26  5117.4  415.64  5137.4  419.10  5147.4  422.36  5157.4  423.91
  5167.4  427.71  5177.4  429.13  5187.4  432.85  5197.4  434.86  5207.4  438.45
  5217.4  440.86  5227.4  441.64  5237.4  440.18  5246.5  442.02  5250.7  442.02
#Mann=3,-1,0
  4802.6    0.16       0  4984.4    0.07       0  4990.4    0.16       0
Bank Sta=4984.4,4990.4
Exp/Cntr=0.3,0.1

Type RM Length L Ch R = 1,1026,28,28,28
BEGIN DESCRIPTION:
Mapping XS 9eb20958
END DESCRIPTION:
XS GIS Cut Line= 2
      3673536.05     10774795.03      3673540.39     10774336.05
#Sta/Elev= 30
  4810.9  433.28  4815.8  433.28  4825.7  430.39  4835.7  429.21  4855.7  424.66
  4885.7  419.91  4895.7  417.21  4905.7  416.23  4915.7  413.83  4925.7  413.83
  4935.7  412.42  4985.8  411.33  4992.8  408.80  4995.5  408.30  4998.8  408.80
  5025.8  412.52  5065.8  412.92  5075.8  412.01  5105.8  414.56  5115.8  414.41
  5155.8  421.33  5165.8  424.77  5175.8  426.55  5185.8  430.45  5225.8  439.89
  5235.8  440.72  5245.8  438.78  5255.8  441.07  5265.4  444.48  5269.9  444.48
#Mann=3,-1,0
  4810.9    0.16       0  4992.8    0.07       0  4998.8    0.16       0
Bank Sta=4992.8,4998.8
Exp/Cntr=0.3,0.1

Type RM Length L Ch R = 1,998,80,80,80
BEGIN DESCRIPTION:
Mapping XS 76be280e
END DESCRIPTION:
XS GIS Cut Line= 2
      3673563.18     10774796.10      3673569.69     10774339.24
#Sta/Elev= 30
  4809.1  434.44  4815.0  431.70  4825.0  430.54  4855.0  424.34  4865.0  423.16
  4875.0  420.63  4895.0  417.34  4904.7  416.18  4909.7  416.17  4915.0  414.72
  4945.0  409.61  4955.0  409.03  4965.0  407.38  5042.0  407.12  5044.8  406.62
  5048.0  407.12  5075.0  407.30  5095.0  409.31  5105.0  411.02  5115.0  411.54
  5155.0  411.07  5165.0  414.86  5175.0  422.86  5185.0  425.73  5195.0  432.97
  5215.0  437.93  5235.1  439.16  5245.1  437.30  5255.1  442.18  5266.0  443.49
#Mann=3,-1,0
  4809.1    0.16       0  5042.0    0.07       0  5048.0    0.16       0
Bank Sta=5042,5048
Exp/Cntr=0.3,0.1

Type RM Length L Ch R = 1,918,25,25,25
BEGIN DESCRIPTION:
Mapping XS 46c24c00
END DESCRIPTION:
XS GIS Cut Line= 2
      3673623.15     10774795.97      3673649.10     10774323.58
#Sta/Elev= 30
  4770.7  430.99  4794.4  427.85  4799.4  427.83  4806.5  424.52  4836.6  420.92
  4846.6  418.61  4856.6  415.16  4866.6  413.96  4876.6  410.60  4886.7  408.44
  4896.7  407.49  4972.7  407.24  4975.4  406.74  4978.7  407.24  5056.9  407.63
  5097.0  409.56  5107.0  408.29  5117.0  409.42  5137.0  416.47  5147.0  424.43
  5157.0  428.50  5162.0  426.25  5167.1  430.79  5177.1  432.58  5187.1  434.86
  5197.1  436.11  5207.1  433.91  5217.2  435.63  5227.2  439.66  5243.8  441.67
#Mann=3,-1,0
  4770.7    0.16       0  4972.7    0.07       0  4978.7    0.16       0
Bank Sta=4972.7,4978.7
Exp/Cntr=0.3,0.1

Type RM Length L Ch R = 1,893,24,24,24
BEGIN DESCRIPTION:
Mapping XS a2a18317
END DESCRIPTION:
XS GIS Cut Line= 2
      3673653.31     10774801.18      3673668.88     10774313.43
#Sta/Elev= 30
  4766.1  433.33  4769.1  433.33  4777.1  430.44  4787.1  429.37  4797.1  426.44
  4804.4  425.34  4809.4  425.45  4817.1  422.76  4827.1  421.82  4837.1  419.17
  4877.2  414.78  4897.2  414.11  4907.2  414.33  4947.2  412.71  5044.2  411.40
  5047.0  410.90  5050.2  411.40  5077.3  411.58  5116.2  412.98  5127.3  417.41
  5137.3  422.54  5147.3  424.39  5157.3  427.61  5187.3  432.71  5197.3  435.34
  5207.3  433.84  5217.3  436.28  5237.3  439.67  5247.3  439.98  5254.1  441.76
#Mann=3,-1,0
  4766.1    0.16       0  5044.2    0.07       0  5050.2    0.16       0
Bank Sta=5044.2,5050.2
Exp/Cntr=0.3,0.1

Type RM Length L Ch R = 1,869,588,588,588
BEGIN DESCRIPTION:
UNT 032 IN CACR 2.0
END DESCRIPTION:
XS GIS Cut Line= 2
      3673678.05     10774798.39      3673690.20     10774315.74
#Sta/Elev= 30
  4769.3  432.74  4817.5  422.88  4827.5  421.82  4867.5  413.30  4907.5  408.65
  4917.5  410.68  4927.5  406.55  4937.6  403.97  4957.6  405.98  4967.6  404.80
  4997.6  404.27  5007.6  404.79  5017.6  407.61  5026.2  406.43  5031.2  404.25
  5054.6  402.80  5057.3  402.30  5060.6  402.80  5087.6  408.19  5097.6  411.66
  5107.6  413.42  5117.6  416.74  5127.6  418.04  5137.6  421.02  5177.6  428.72
  5187.6  429.86  5197.6  433.87  5217.6  434.24  5237.6  438.14  5252.1  438.94
#Mann=3,-1,0
  4769.3    0.16       0  5054.6    0.07       0  5060.6    0.16       0
Bank Sta=5054.6,5060.6
Exp/Cntr=0.3,0.1

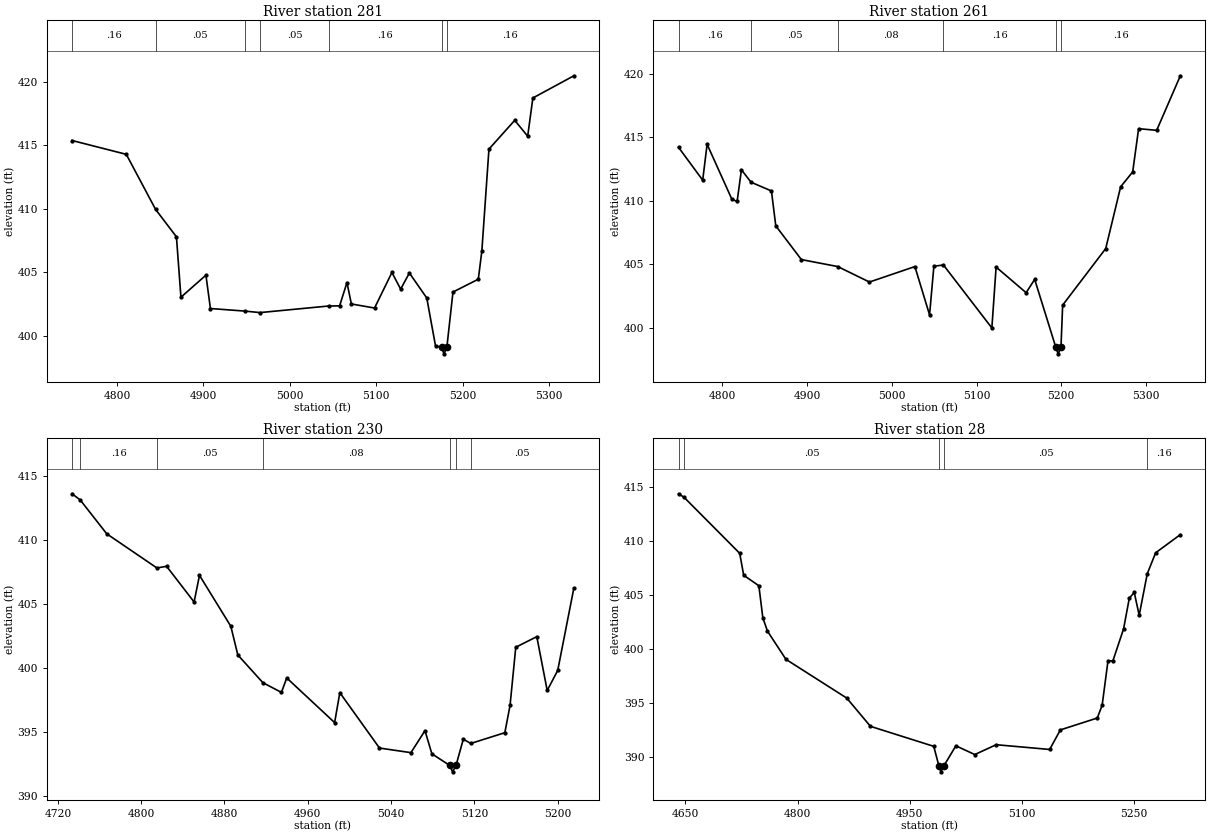
Type RM Length L Ch R = 1,281,20,20,20
BEGIN DESCRIPTION:
Mapping XS aaa03a3e
END DESCRIPTION:
XS GIS Cut Line= 4
      3674307.52     10774660.58      3674246.75     10774444.40
      3674215.50     10774197.01      3674156.49     10774108.49
#Sta/Elev= 30
  4748.1  415.38  4810.8  414.29  4844.7  409.95  4868.8  407.79  4874.0  403.03
  4902.9  404.77  4908.1  402.14  4947.7  401.94  4965.4  401.82  5045.0  402.34
  5057.5  402.35  5066.0  404.19  5071.1  402.50  5097.9  402.18  5118.0  404.98
  5128.1  403.67  5138.2  404.94  5158.3  402.97  5168.4  399.20  5175.5  399.07
  5178.2  398.57  5181.5  399.07  5188.6  403.44  5217.9  404.45  5222.0  406.68
  5230.2  414.70  5260.0  416.97  5275.0  415.72  5281.0  418.73  5328.4  420.48
#Mann=7,-1,0
  4748.1    0.16       0  4844.7    0.05       0  4947.7    0.08       0
  4965.4    0.05       0  5045.0    0.16       0  5175.5   0.033       0
  5181.5    0.16       0
Bank Sta=5175.5,5181.5
Exp/Cntr=0.3,0.1

Type RM Length L Ch R = 1,261,31,31,31
BEGIN DESCRIPTION:
Mapping XS 82228bdb
END DESCRIPTION:
XS GIS Cut Line= 5
      3674322.27     10774651.02      3674273.66     10774464.37
      3674263.24     10774426.17      3674227.65     10774157.08
      3674165.43     10774094.85
#Sta/Elev= 30
  4748.5  414.22  4777.0  411.63  4782.2  414.46  4811.4  410.13  4817.6  409.95
  4822.7  412.45  4834.0  411.47  4858.1  410.78  4863.2  408.03  4893.4  405.37
  4936.3  404.82  4973.7  403.60  5027.3  404.82  5044.6  401.01  5049.7  404.85
  5061.0  404.94  5118.1  399.98  5123.1  404.78  5158.5  402.76  5168.6  403.81
  5193.6  398.44  5196.3  397.94  5199.6  398.44  5201.6  401.78  5252.4  406.24
  5270.0  411.11  5284.2  412.28  5291.2  415.69  5312.5  415.56  5340.4  419.86
#Mann=6,-1,0
  4748.5    0.16       0  4834.0    0.05       0  4936.3    0.08       0
  5061.0    0.16       0  5193.6    0.07       0  5199.6    0.16       0
Bank Sta=5193.6,5199.6
Exp/Cntr=0.3,0.1

Type RM Length L Ch R = 1,230,202,202,202
BEGIN DESCRIPTION:
Mapping XS 895f9a08
END DESCRIPTION:
XS GIS Cut Line= 3
      3674342.20     10774648.43      3674286.65     10774417.53
      3674257.17     10774174.80
#Sta/Elev= 30
  4733.6  413.60  4741.5  413.11  4766.9  410.47  4815.1  407.80  4824.4  407.93
  4850.8  405.14  4856.0  407.22  4886.1  403.24  4892.8  401.00  4916.9  398.83
  4934.7  398.07  4939.8  399.20  4985.8  395.71  4990.8  398.05  5028.9  393.72
  5059.1  393.36  5072.6  395.08  5079.2  393.27  5096.4  392.36  5099.1  391.86
  5102.4  392.36  5109.4  394.41  5116.6  394.08  5149.3  394.92  5154.3  397.05
  5159.8  401.60  5180.0  402.43  5190.0  398.22  5200.1  399.79  5215.6  406.23
#Mann=7,-1,0
  4733.6    0.05       0  4741.5    0.16       0  4815.1    0.05       0
  4916.9    0.08       0  5096.4    0.07       0  5102.4    0.08       0
  5116.6    0.05       0
Bank Sta=5096.4,5102.4
Exp/Cntr=0.3,0.1

Type RM Length L Ch R = 1,28,0,0,0
BEGIN DESCRIPTION:
UNT 032 IN CACR 1.0
END DESCRIPTION:
XS GIS Cut Line= 4
      3674337.35     10774662.28      3674448.45     10774348.09
      3674443.24     10774306.42      3674217.55     10774115.45
#Sta/Elev= 30
  4640.9  414.40  4648.2  414.08  4722.7  408.89  4728.0  406.86  4748.3  405.89
  4753.6  402.93  4759.8  401.69  4784.5  399.08  4865.9  395.49  4897.5  392.88
  4982.1  391.03  4989.2  389.17  4991.9  388.67  4995.2  389.17  5011.7  391.08
  5037.0  390.27  5065.6  391.18  5137.1  390.74  5151.4  392.55  5200.8  393.65
  5207.3  394.84  5215.1  398.95  5221.6  398.93  5235.9  401.89  5243.6  404.74
  5250.2  405.27  5256.8  403.16  5267.6  407.00  5278.8  408.94  5311.8  410.62
#Mann=5,-1,0
  4640.9    0.16       0  4648.2    0.05       0  4989.2    0.03       0
  4995.2    0.05       0  5267.6    0.16       0
Bank Sta=4989.2,4995.2
Exp/Cntr=0.3,0.1

Chan Stop Cuts=-1