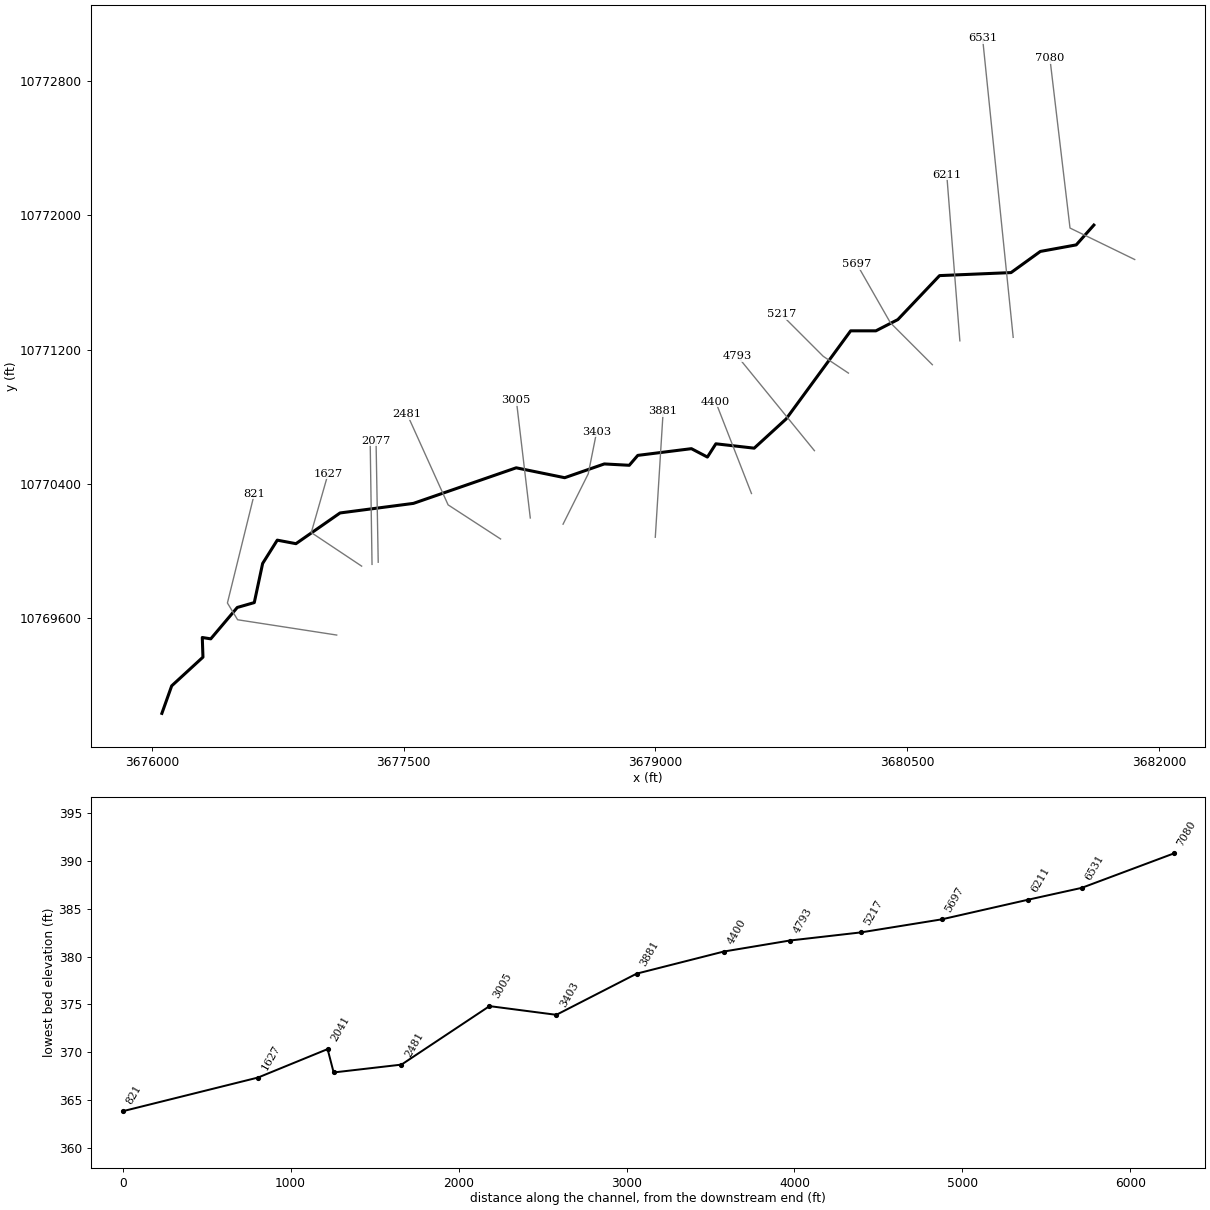
--- UNT 034 IN CACR.prj (project) ---

Proj Title=UNT 034 IN CACR Base Level Engineering
Current Plan=p01
Default Exp/Contr=0.3,0.1
English Units
Geom File=g01
Flow File=f01
Plan File=p01
BEGIN DESCRIPTION:
UNT 034 IN CACR
END DESCRIPTION:

--- UNT 034 IN CACR.p01 (plan) ---

Plan Title=Multiple Run
Short Identifier=Multiple
Geom File=g01
Flow File=f01
Subcritical Flow
K Sum by GR= 0
Std Step Tol= 0.01
Critical Tol= 0.01
Num of Std Step Trials= 20
Max Error Tol= 0.3
Flow Tol Ratio= 0.001
Split Flow NTrial= 30
Split Flow Tol= 0.02
Split Flow Ratio= 0.02
Log Output Level= 0
Friction Slope Method= 1
Unsteady Friction Slope Method= 2
Unsteady Bridges Friction Slope Method= 1
Parabolic Critical Depth
Global Vel Dist=  1 , 1 , 1
Global Log Level= 0
CheckData=True
Encroach Param= -1, 0, 0, 0
BEGIN DESCRIPTION:
Multiple Run
END DESCRIPTION:

--- UNT 034 IN CACR.f01 (steady flow) ---

Flow Title=Multiple
Number of Profiles=7
Profile Names=10-year,25-year,50-year,1pct_min,100-year,1pct_plu,500-year
River Rch & RM= UNT 034 IN CACR,Reach-1,7080
     750    1038    1280    1159    1567    2119    2353
River Rch & RM= UNT 034 IN CACR,Reach-1,6211
    1105    1551    1931    1760    2381    3219    3629
Boundary for River Rch & Prof#=UNT 034 IN CACR,Reach-1,1
Up Type=0
Dn Type=3
Dn Slope=0.005
Boundary for River Rch & Prof#=UNT 034 IN CACR,Reach-1,2
Up Type=0
Dn Type=3
Dn Slope=0.005
Boundary for River Rch & Prof#=UNT 034 IN CACR,Reach-1,3
Up Type=0
Dn Type=3
Dn Slope=0.005
Boundary for River Rch & Prof#=UNT 034 IN CACR,Reach-1,4
Up Type=0
Dn Type=3
Dn Slope=0.005
Boundary for River Rch & Prof#=UNT 034 IN CACR,Reach-1,5
Up Type=0
Dn Type=3
Dn Slope=0.005
Boundary for River Rch & Prof#=UNT 034 IN CACR,Reach-1,6
Up Type=0
Dn Type=3
Dn Slope=0.005
Boundary for River Rch & Prof#=UNT 034 IN CACR,Reach-1,7
Up Type=0
Dn Type=3
Dn Slope=0.005

--- UNT 034 IN CACR.g01 (geometry) ---

Geom Title=Existing Conditions

River Reach=UNT 034 IN CACR,Reach-1
Reach XY= 30
      3681611.84     10771942.05      3681506.75     10771824.00
      3681293.00     10771785.00      3681118.50     10771659.00
      3680692.50     10771641.00      3680444.00     10771379.00
      3680313.25     10771312.00      3680163.00     10771312.00
      3679778.50     10770787.00      3679588.25     10770613.00
      3679360.00     10770639.00      3679309.50     10770560.00
      3679214.25     10770610.00      3678894.75     10770570.00
      3678844.00     10770511.00      3678695.25     10770519.00
      3678459.25     10770437.00      3678170.50     10770496.00
      3677558.00     10770284.00      3677121.00     10770227.00
      3676858.25     10770044.00      3676747.00     10770065.00
      3676659.75     10769926.00      3676610.00     10769693.00
      3676508.75     10769664.00      3676350.75     10769477.00
      3676300.25     10769485.00      3676304.25     10769368.00
      3676118.00     10769197.00      3676059.50     10769033.00

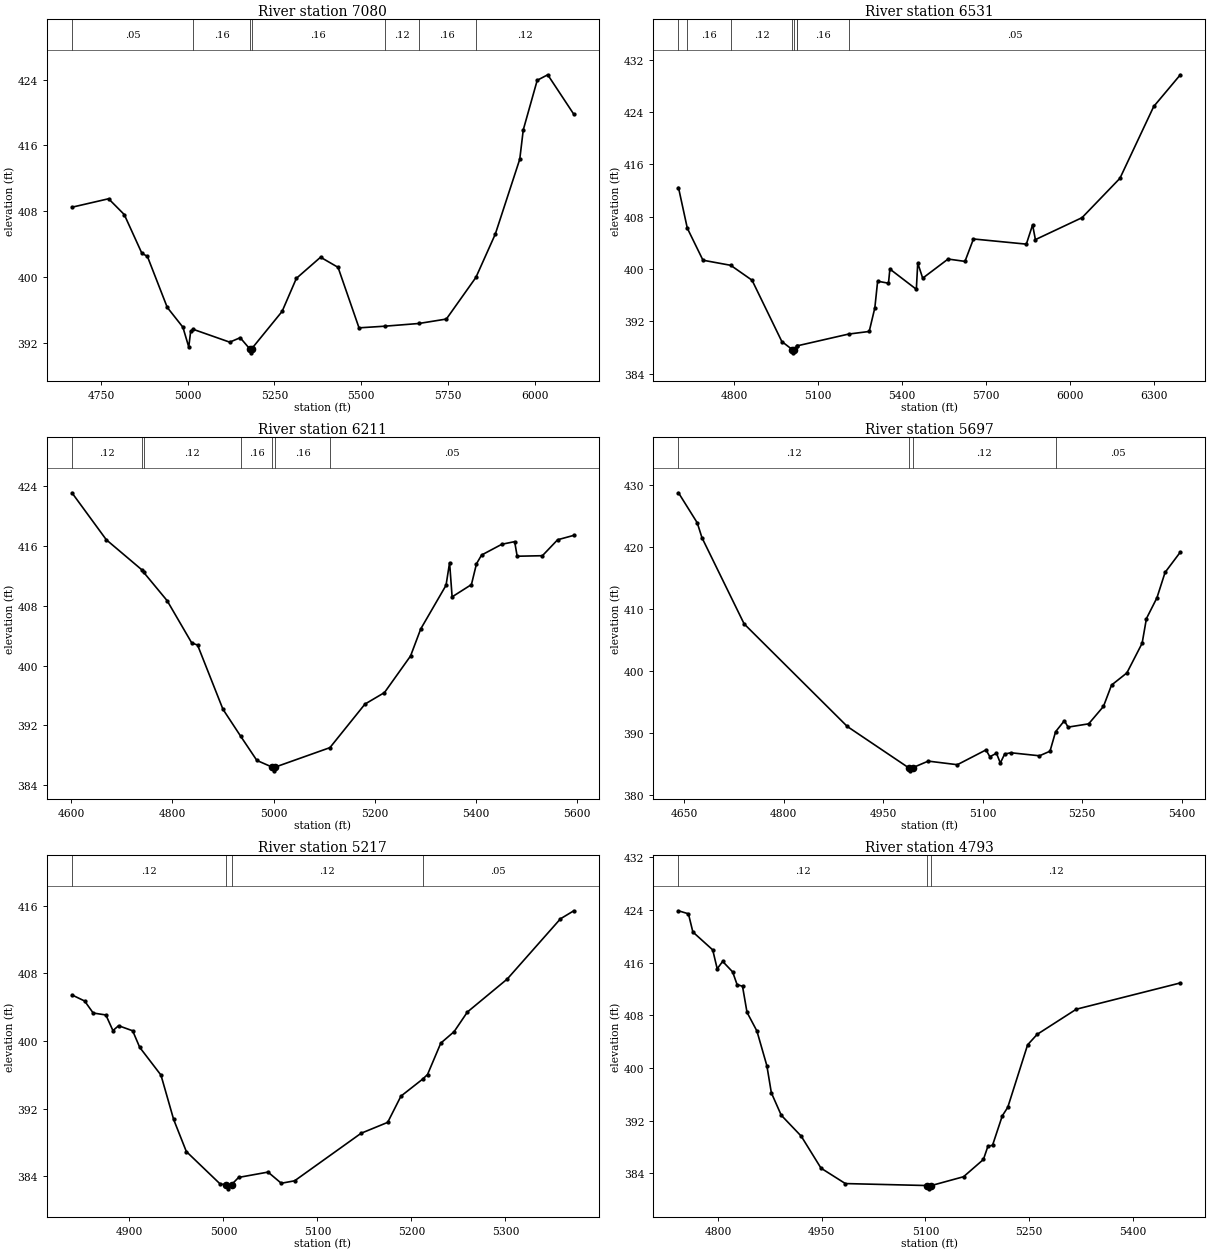
Type RM Length L Ch R = 1,7080,549,549,549
BEGIN DESCRIPTION:
UNT 034 IN CACR 14.0
END DESCRIPTION:
XS GIS Cut Line= 3
      3681855.18     10771736.87      3681469.79     10771924.36
      3681350.00     10772934.81
#Sta/Elev= 30
  4666.5  408.48  4772.1  409.51  4817.2  407.59  4867.8  402.90  4884.0  402.49
  4941.1  396.30  4986.2  393.89  5003.1  391.48  5008.7  393.42  5016.6  393.62
  5121.1  392.07  5151.3  392.61  5178.5  391.27  5181.3  390.77  5184.5  391.27
  5272.1  395.81  5313.2  399.83  5382.9  402.40  5433.3  401.17  5493.7  393.81
  5567.9  394.01  5666.1  394.34  5745.4  394.88  5830.6  399.95  5886.4  405.21
  5956.9  414.32  5967.0  417.89  6007.2  423.92  6037.5  424.59  6112.6  419.79
#Mann=7,-1,0
  4666.5    0.05       0  5016.6    0.16       0  5178.5    0.03       0
  5184.5    0.16       0  5567.9    0.12       0  5666.1    0.16       0
  5830.6    0.12       0
Bank Sta=5178.5,5184.5
Exp/Cntr=0.3,0.1

Type RM Length L Ch R = 1,6531,320,320,320
BEGIN DESCRIPTION:
UNT 034 IN CACR 13.0
END DESCRIPTION:
XS GIS Cut Line= 2
      3681131.25     10771273.27      3680948.96     10773054.57
#Sta/Elev= 30
  4602.1  412.46  4633.6  406.24  4689.5  401.34  4788.5  400.56  4864.6  398.28
  4970.9  388.90  5008.1  387.67  5010.9  387.17  5014.1  387.67  5025.3  388.14
  5026.6  388.25  5209.0  390.04  5282.6  390.44  5302.7  394.05  5312.7  398.13
  5351.4  397.82  5356.4  399.99  5450.8  396.89  5455.8  400.91  5473.5  398.59
  5564.0  401.52  5624.3  401.16  5654.6  404.59  5843.3  403.80  5865.6  406.75
  5875.6  404.49  6042.0  407.85  6177.2  413.87  6297.8  424.86  6392.7  429.71
#Mann=8,-1,0
  4602.1    0.12       0  4633.6    0.16       0  4788.5    0.12       0
  5008.1    0.07       0  5014.1    0.12       0  5025.3    0.05       0
  5026.6    0.16       0  5209.0    0.05       0
Bank Sta=5008.1,5014.1
Exp/Cntr=0.3,0.1

Type RM Length L Ch R = 1,6211,514,514,514
BEGIN DESCRIPTION:
UNT 034 IN CACR 12.0
END DESCRIPTION:
XS GIS Cut Line= 2
      3680813.55     10771252.44      3680735.42     10772242.06
#Sta/Elev= 30
  4601.1  423.09  4669.1  416.81  4739.1  412.81  4743.1  412.45  4789.4  408.67
  4838.1  403.02  4849.6  402.74  4899.8  394.16  4935.2  390.52  4966.9  387.32
  4997.1  386.43  4999.8  385.93  5003.1  386.43  5111.4  389.03  5180.7  394.85
  5219.3  396.39  5270.9  401.28  5291.0  404.89  5341.1  410.73  5348.1  413.75
  5353.1  409.18  5391.3  410.82  5401.3  413.60  5411.4  414.77  5451.5  416.21
  5476.8  416.56  5481.8  414.61  5531.7  414.68  5561.8  416.81  5593.8  417.40
#Mann=7,-1,0
  4601.1    0.12       0  4739.1    0.16       0  4743.1    0.12       0
  4935.2    0.16       0  4997.1    0.07       0  5003.1    0.16       0
  5111.4    0.05       0
Bank Sta=4997.1,5003.1
Exp/Cntr=0.3,0.1

Type RM Length L Ch R = 1,5697,480,480,480
BEGIN DESCRIPTION:
UNT 034 IN CACR 11.0
END DESCRIPTION:
XS GIS Cut Line= 3
      3680649.62     10771110.17      3680399.61     10771360.19
      3680199.60     10771710.20
#Sta/Elev= 30
  4641.1  428.78  4669.4  423.93  4676.5  421.53  4740.1  407.61  4895.7  391.04
  4988.1  384.38  4990.9  383.88  4994.1  384.38  5017.7  385.45  5061.6  384.87
  5104.8  387.26  5110.6  386.16  5120.6  386.72  5126.4  385.14  5132.9  386.59
  5142.2  386.80  5185.4  386.31  5201.3  387.05  5209.7  390.19  5222.9  391.97
  5228.6  390.94  5259.6  391.47  5281.9  394.28  5294.1  397.73  5317.2  399.69
  5340.2  404.48  5346.7  408.47  5362.5  411.81  5374.8  415.92  5397.8  419.20
#Mann=4,-1,0
  4641.1    0.12       0  4988.1    0.07       0  4994.1    0.12       0
  5209.7    0.05       0
Bank Sta=4988.1,4994.1
Exp/Cntr=0.3,0.1

Type RM Length L Ch R = 1,5217,424,424,424
BEGIN DESCRIPTION:
UNT 034 IN CACR 10.0
END DESCRIPTION:
XS GIS Cut Line= 3
      3680149.63     10771060.18      3679999.61     10771160.19
      3679749.58     10771410.22
#Sta/Elev= 30
  4838.8  405.45  4852.3  404.73  4861.4  403.31  4874.9  403.08  4882.4  401.23
  4888.4  401.81  4903.4  401.21  4910.9  399.25  4933.5  395.97  4947.0  390.72
  4960.5  386.93  4996.6  383.08  5002.6  383.02  5005.3  382.52  5008.6  383.02
  5016.1  383.87  5047.4  384.50  5061.5  383.18  5075.7  383.47  5146.4  389.09
  5174.7  390.38  5188.8  393.48  5212.1  395.51  5217.1  396.04  5231.2  399.75
  5245.4  401.11  5259.5  403.43  5301.9  407.33  5358.5  414.45  5372.7  415.40
#Mann=4,-1,0
  4838.8    0.12       0  5002.6    0.07       0  5008.6    0.12       0
  5212.1    0.05       0
Bank Sta=5002.6,5008.6
Exp/Cntr=0.3,0.1

Type RM Length L Ch R = 1,4793,393,393,393
BEGIN DESCRIPTION:
UNT 034 IN CACR 9.0
END DESCRIPTION:
XS GIS Cut Line= 2
      3679947.00     10770598.14      3679488.66     10771160.65
#Sta/Elev= 30
  4743.0  423.90  4757.4  423.44  4763.8  420.68  4792.5  417.96  4799.0  415.09
  4806.9  416.21  4821.3  414.62  4827.7  412.70  4835.6  412.43  4842.1  408.48
  4856.4  405.64  4870.8  400.37  4877.3  396.25  4891.6  392.85  4920.4  389.68
  4949.1  384.81  4984.3  382.47  5102.6  382.17  5105.4  381.67  5108.6  382.17
  5155.2  383.51  5183.9  386.13  5190.4  388.14  5197.1  388.29  5211.2  392.76
  5219.1  394.05  5247.8  403.54  5261.6  405.13  5318.2  408.95  5468.6  412.94
#Mann=3,-1,0
  4743.0    0.12       0  5102.6    0.07       0  5108.6    0.12       0
Bank Sta=5102.6,5108.6
Exp/Cntr=0.3,0.1

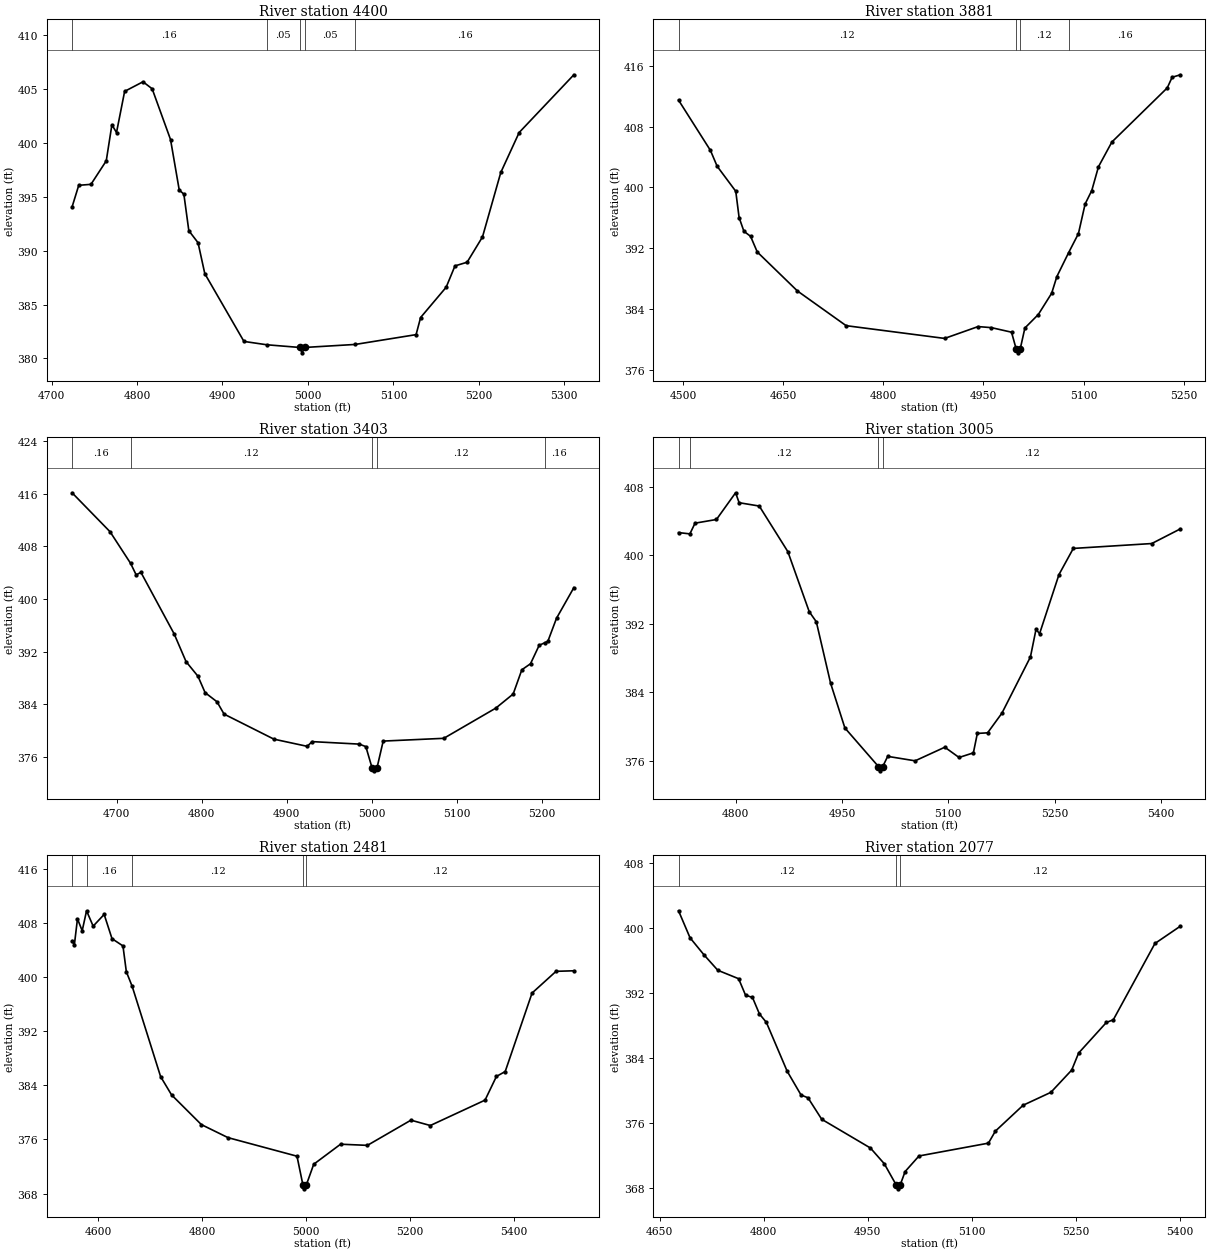
Type RM Length L Ch R = 1,4400,519,519,519
BEGIN DESCRIPTION:
UNT 034 IN CACR 8.0
END DESCRIPTION:
XS GIS Cut Line= 2
      3679572.02     10770342.90      3679358.47     10770889.79
#Sta/Elev= 30
  4724.0  394.06  4731.8  396.07  4746.1  396.16  4764.0  398.34  4770.6  401.69
  4776.0  400.97  4785.5  404.79  4807.0  405.68  4817.7  405.03  4839.2  400.32
  4849.4  395.63  4854.8  395.25  4860.6  391.86  4871.4  390.74  4879.3  387.87
  4925.1  381.58  4951.7  381.27  4990.3  381.02  4993.1  380.52  4996.3  381.02
  5055.3  381.30  5126.5  382.21  5131.8  383.80  5161.7  386.61  5172.0  388.59
  5186.2  388.93  5204.2  391.28  5225.6  397.26  5247.1  400.97  5311.1  406.33
#Mann=5,-1,0
  4724.0    0.16       0  4951.7    0.05       0  4990.3   0.033       0
  4996.3    0.05       0  5055.3    0.16       0
Bank Sta=4990.3,4996.3
Exp/Cntr=0.3,0.1

Type RM Length L Ch R = 1,3881,478,478,478
BEGIN DESCRIPTION:
UNT 034 IN CACR 7.0
END DESCRIPTION:
XS GIS Cut Line= 2
      3678999.09     10770082.47      3679045.97     10770832.51
#Sta/Elev= 30
  4493.5  411.51  4541.3  404.88  4551.3  402.80  4579.2  399.50  4584.2  396.04
  4591.4  394.23  4601.4  393.56  4611.4  391.50  4671.6  386.36  4744.5  381.79
  4892.0  380.11  4942.1  381.67  4962.1  381.53  4992.2  380.93  4999.2  378.71
  5002.0  378.21  5005.2  378.71  5012.2  381.48  5032.3  383.26  5052.3  386.06
  5060.1  388.26  5077.7  391.41  5092.4  393.92  5102.4  397.82  5112.4  399.60
  5122.4  402.73  5142.5  405.99  5225.4  413.12  5232.7  414.52  5245.0  414.85
#Mann=4,-1,0
  4493.5    0.12       0  4999.2    0.07       0  5005.2    0.12       0
  5077.7    0.16       0
Bank Sta=4999.2,5005.2
Exp/Cntr=0.3,0.1

Type RM Length L Ch R = 1,3403,398,398,398
BEGIN DESCRIPTION:
UNT 034 IN CACR 6.0
END DESCRIPTION:
XS GIS Cut Line= 3
      3678449.63     10770160.23      3678599.61     10770460.19
      3678649.61     10770710.17
#Sta/Elev= 30
  4647.5  416.15  4692.2  410.23  4716.3  405.44  4722.9  403.68  4728.5  404.06
  4767.6  394.71  4781.6  390.50  4795.6  388.28  4804.0  385.79  4818.0  384.40
  4826.3  382.53  4885.0  378.72  4924.2  377.63  4929.8  378.35  4985.4  377.97
  4993.1  377.59  5000.3  374.41  5003.0  373.91  5006.3  374.41  5013.5  378.43
  5084.8  378.85  5146.0  383.44  5166.4  385.58  5176.6  389.26  5186.8  390.18
  5197.0  392.98  5203.3  393.35  5207.2  393.58  5217.4  397.09  5237.8  401.74
#Mann=5,-1,0
  4647.5    0.16       0  4716.3    0.12       0  5000.3    0.07       0
  5006.3    0.12       0  5203.3    0.16       0
Bank Sta=5000.3,5006.3
Exp/Cntr=0.3,0.1

Type RM Length L Ch R = 1,3005,524,524,524
BEGIN DESCRIPTION:
UNT 034 IN CACR 5.0
END DESCRIPTION:
XS GIS Cut Line= 2
      3678254.30     10770197.10      3678170.97     10770900.18
#Sta/Elev= 30
  4719.4  402.65  4735.4  402.50  4742.7  403.75  4772.9  404.18  4799.9  407.30
  4804.9  406.14  4833.3  405.75  4873.6  400.43  4903.8  393.41  4913.8  392.23
  4934.0  385.04  4954.1  379.83  5001.5  375.32  5004.2  374.82  5007.5  375.32
  5014.5  376.51  5053.2  375.99  5095.1  377.58  5115.2  376.38  5135.4  376.92
  5141.0  379.19  5155.5  379.26  5175.7  381.56  5215.9  388.12  5223.8  391.35
  5228.8  390.84  5256.2  397.75  5276.4  400.80  5387.1  401.37  5427.4  403.08
#Mann=4,-1,0
  4719.4    0.16       0  4735.4    0.12       0  5001.5    0.07       0
  5007.5    0.12       0
Bank Sta=5001.5,5007.5
Exp/Cntr=0.3,0.1

Type RM Length L Ch R = 1,2481,404,404,404
BEGIN DESCRIPTION:
UNT 034 IN CACR 4.0
END DESCRIPTION:
XS GIS Cut Line= 3
      3678077.23     10770072.08      3677764.72     10770275.21
      3677520.31     10770816.03
#Sta/Elev= 30
  4549.5  405.33  4553.9  404.72  4559.9  408.58  4569.0  406.82  4577.4  409.77
  4590.1  407.50  4611.3  409.23  4626.4  405.65  4647.5  404.58  4654.0  400.77
  4665.3  398.60  4720.0  385.28  4741.1  382.58  4798.4  378.20  4849.8  376.27
  4982.6  373.53  4994.2  369.21  4996.9  368.71  5000.2  369.21  5014.8  372.34
  5066.5  375.30  5118.2  375.13  5202.0  378.85  5239.3  378.06  5344.7  381.81
  5366.6  385.31  5383.5  386.03  5435.2  397.62  5481.4  400.83  5515.7  400.91
#Mann=5,-1,0
  4549.5    0.12       0  4577.4    0.16       0  4665.3    0.12       0
  4994.2    0.07       0  5000.2    0.12       0
Bank Sta=4994.2,5000.2
Exp/Cntr=0.3,0.1

Type RM Length L Ch R = 1,2077,36,36,36
BEGIN DESCRIPTION:
Mapping XS 81f695d6
END DESCRIPTION:
XS GIS Cut Line= 2
      3677348.40     10769933.60      3677335.41     10770656.78
#Sta/Elev= 30
  4677.2  402.15  4693.8  398.82  4713.8  396.73  4733.8  394.82  4763.8  393.78
  4773.8  391.75  4783.8  391.47  4793.8  389.44  4803.8  388.40  4833.8  382.38
  4853.8  379.45  4863.8  379.11  4883.6  376.46  4953.8  372.92  4973.8  370.98
  4990.8  368.39  4993.6  367.89  4996.8  368.39  5003.8  370.02  5023.8  371.94
  5123.9  373.52  5133.9  375.00  5173.9  378.19  5213.9  379.78  5243.9  382.52
  5253.9  384.62  5293.9  388.39  5303.9  388.72  5363.9  398.12  5400.5  400.25
#Mann=3,-1,0
  4677.2    0.12       0  4990.8    0.07       0  4996.8    0.12       0
Bank Sta=4990.8,4996.8
Exp/Cntr=0.3,0.1

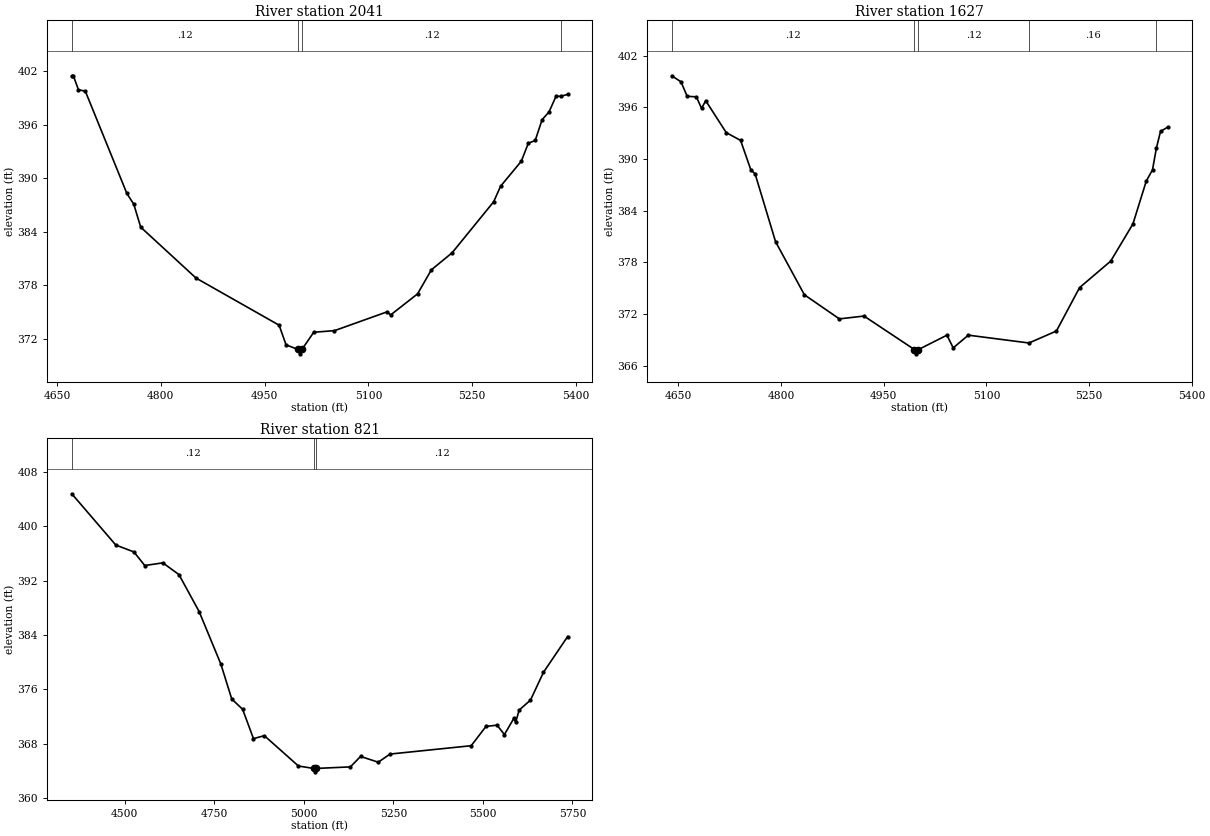
Type RM Length L Ch R = 1,2041,414,414,414
BEGIN DESCRIPTION:
UNT 034 IN CACR 3.0
END DESCRIPTION:
XS GIS Cut Line= 2
      3677311.51     10769920.63      3677300.69     10770637.04
#Sta/Elev= 30
  4671.3  401.50  4673.6  401.50  4680.9  399.94  4690.9  399.77  4750.9  388.31
  4760.9  387.10  4770.9  384.53  4850.9  378.82  4970.9  373.54  4980.9  371.34
  4997.9  370.83  5000.7  370.33  5003.9  370.83  5020.9  372.75  5050.9  372.93
  5127.0  375.04  5132.0  374.69  5170.9  377.05  5190.9  379.75  5220.9  381.66
  5280.9  387.38  5290.9  389.12  5320.9  391.93  5330.9  393.93  5340.9  394.25
  5350.9  396.58  5360.9  397.45  5370.9  399.19  5378.6  399.21  5387.8  399.42
#Mann=4,-1,0
  4671.3    0.12       0  4997.9    0.07       0  5003.9    0.12       0
  5378.6    0.16       0
Bank Sta=4997.9,5003.9
Exp/Cntr=0.3,0.1

Type RM Length L Ch R = 1,1627,806,806,806
BEGIN DESCRIPTION:
UNT 034 IN CACR 2.0
END DESCRIPTION:
XS GIS Cut Line= 3
      3677249.60     10769910.20      3676949.61     10770110.19
      3677049.60     10770460.15
#Sta/Elev= 30
  4640.3  399.66  4653.8  398.96  4662.8  397.28  4676.3  397.21  4683.9  395.87
  4689.9  396.77  4719.9  393.06  4740.9  392.15  4756.0  388.70  4762.0  388.29
  4792.0  380.38  4834.1  374.22  4885.2  371.42  4921.2  371.75  4994.8  367.86
  4997.6  367.36  5000.8  367.86  5042.4  369.53  5051.5  368.05  5073.6  369.53
  5162.2  368.62  5202.3  370.01  5236.1  375.05  5281.6  378.13  5314.1  382.45
  5333.6  387.43  5342.7  388.74  5348.3  391.23  5354.4  393.20  5364.8  393.69
#Mann=5,-1,0
  4640.3    0.12       0  4994.8    0.07       0  5000.8    0.12       0
  5162.2    0.16       0  5348.3    0.12       0
Bank Sta=4994.8,5000.8
Exp/Cntr=0.3,0.1

Type RM Length L Ch R = 1,821,0,0,0
BEGIN DESCRIPTION:
UNT 034 IN CACR 1.0
END DESCRIPTION:
XS GIS Cut Line= 4
      3677101.03     10769499.61      3676510.73     10769590.76
      3676449.96     10769690.59      3676610.55     10770341.61
#Sta/Elev= 30
  4352.0  404.81  4474.9  397.26  4525.5  396.24  4555.8  394.24  4606.4  394.63
  4651.3  392.90  4707.6  387.46  4768.3  379.72  4798.7  374.57  4829.0  373.06
  4859.4  368.73  4889.7  369.17  4984.9  364.70  5027.6  364.34  5030.3  363.84
  5033.6  364.34  5130.0  364.57  5158.5  366.11  5207.8  365.26  5240.8  366.46
  5467.4  367.69  5508.6  370.53  5539.5  370.72  5560.1  369.33  5586.3  371.71
  5591.4  371.13  5601.3  372.94  5632.9  374.41  5669.2  378.51  5736.7  383.78
#Mann=3,-1,0
  4352.0    0.12       0  5027.6    0.07       0  5033.6    0.12       0
Bank Sta=5027.6,5033.6
Exp/Cntr=0.3,0.1

Chan Stop Cuts=-1