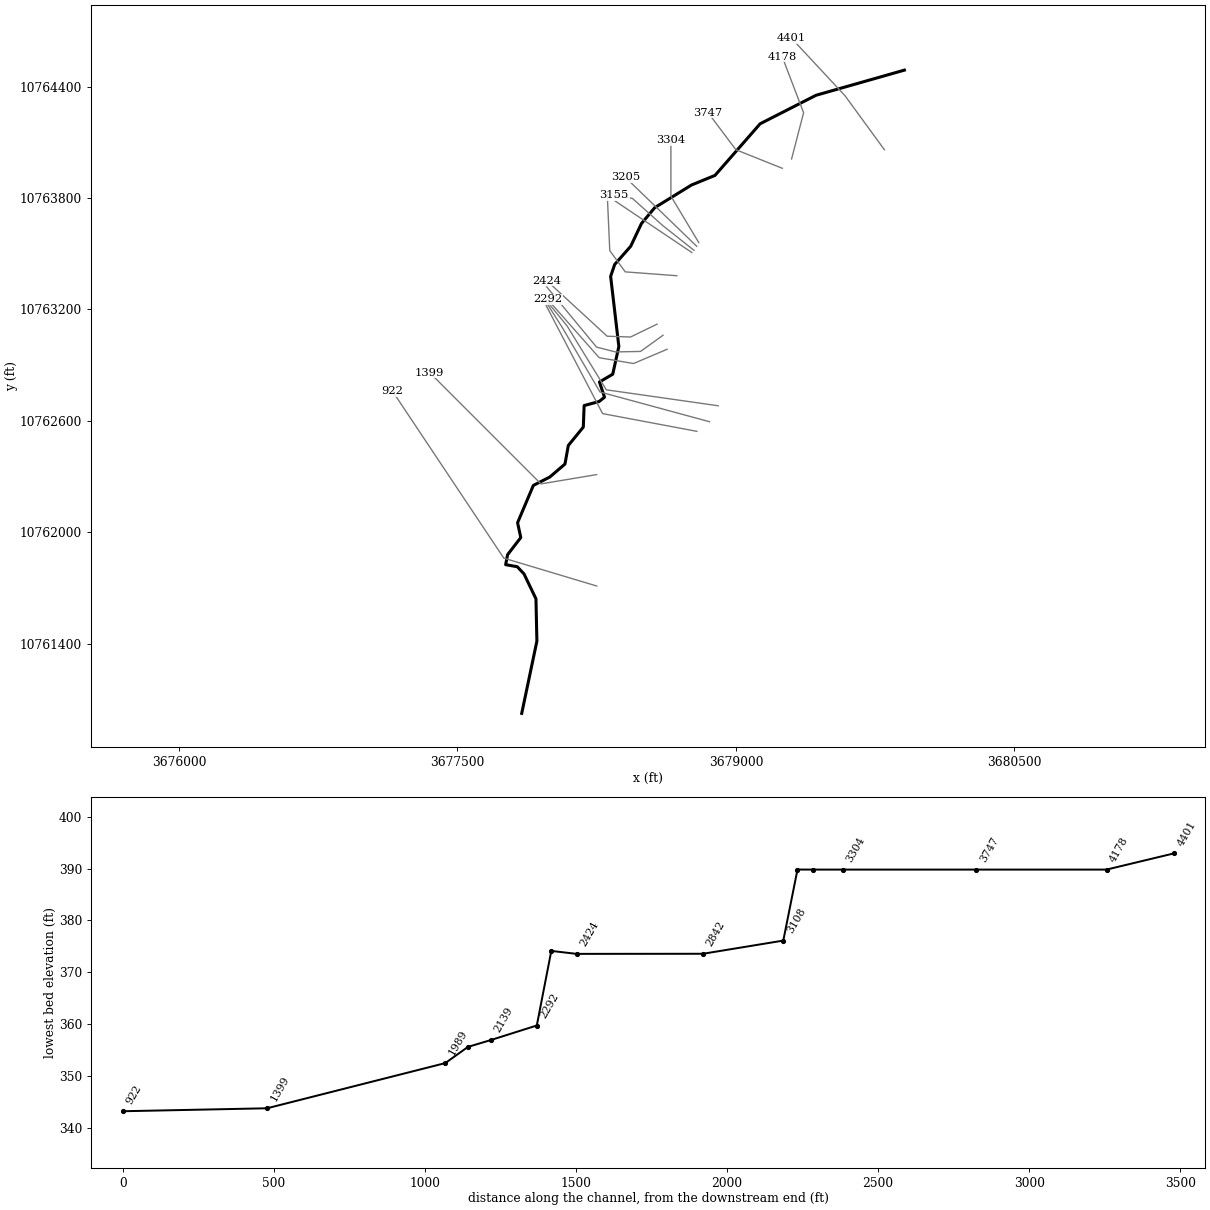
--- UNT 035 IN CACR.prj (project) ---

Proj Title=UNT 035 IN CACR Base Level Engineering
Current Plan=p01
Default Exp/Contr=0.3,0.1
English Units
Geom File=g01
Flow File=f01
Plan File=p01
Y Axis Title=Elevation
X Axis Title(PF)=Main Channel Distance
X Axis Title(XS)=Station
BEGIN DESCRIPTION:
UNT 035 IN CACR
END DESCRIPTION:
DSS Export Rating Curves= 0
DSS Export Rating Curve Sorted= 0
DSS Export Volume Flow Curves= 0
DXF OffsetX= 0
DXF OffsetY= 0
DXF ScaleX= 1
DXF ScaleY= 10

--- UNT 035 IN CACR.p01 (plan) ---

Plan Title=Multiple Run
Short Identifier=Multiple
Geom File=g01
Flow File=f01
Subcritical Flow
K Sum by GR= 0
Std Step Tol= 0.01
Critical Tol= 0.01
Num of Std Step Trials= 20
Max Error Tol= 0.3
Flow Tol Ratio= 0.001
Split Flow NTrial= 30
Split Flow Tol= 0.02
Split Flow Ratio= 0.02
Log Output Level= 0
Friction Slope Method= 1
Unsteady Friction Slope Method= 2
Unsteady Bridges Friction Slope Method= 1
Parabolic Critical Depth
Global Vel Dist=  1 , 1 , 1
Global Log Level= 0
CheckData=True
Encroach Param= -1, 0, 0, 0
BEGIN DESCRIPTION:
Multiple Run
END DESCRIPTION:

--- UNT 035 IN CACR.f01 (steady flow) ---

Flow Title=Multiple
Number of Profiles=7
Profile Names=10-year,25-year,50-year,1pct_min,100-year,1pct_plu,500-year
River Rch & RM= UNT 035 IN CACR,Reach-1,4401
     254     326     382     329     445     602     606
Boundary for River Rch & Prof#=UNT 035 IN CACR,Reach-1,1
Up Type=0
Dn Type=3
Dn Slope=0.005
Boundary for River Rch & Prof#=UNT 035 IN CACR,Reach-1,2
Up Type=0
Dn Type=3
Dn Slope=0.005
Boundary for River Rch & Prof#=UNT 035 IN CACR,Reach-1,3
Up Type=0
Dn Type=3
Dn Slope=0.005
Boundary for River Rch & Prof#=UNT 035 IN CACR,Reach-1,4
Up Type=0
Dn Type=3
Dn Slope=0.005
Boundary for River Rch & Prof#=UNT 035 IN CACR,Reach-1,5
Up Type=0
Dn Type=3
Dn Slope=0.005
Boundary for River Rch & Prof#=UNT 035 IN CACR,Reach-1,6
Up Type=0
Dn Type=3
Dn Slope=0.005
Boundary for River Rch & Prof#=UNT 035 IN CACR,Reach-1,7
Up Type=0
Dn Type=3
Dn Slope=0.005

--- UNT 035 IN CACR.g01 (geometry) ---

Geom Title=Existing Conditions
Program Version=4.10

River Reach=UNT 035 IN CACR ,Reach-1
Reach XY= 30
      3679907.43     10764488.95      3679431.51     10764353.53
      3679130.25       10764200.      3678887.25       10763922.
       3678760.5       10763870.       3678562.5       10763748.
      3678491.25       10763663.        3678433.       10763540.
      3678346.75       10763442.        3678325.       10763378.
      3678369.25       10763000.      3678336.25       10762851.
      3678264.75       10762809.        3678292.       10762727.
      3678263.25       10762704.      3678182.25       10762682.
      3678177.75       10762566.        3678097.       10762467.
        3678079.       10762367.      3677997.25       10762297.
      3677908.75       10762252.      3677823.75       10762051.
        3677841.       10761971.        3677770.       10761879.
       3677759.5       10761825.        3677822.       10761814.
       3677858.5       10761775.      3677922.75       10761641.
      3677927.75       10761413.        3677846.       10761024.

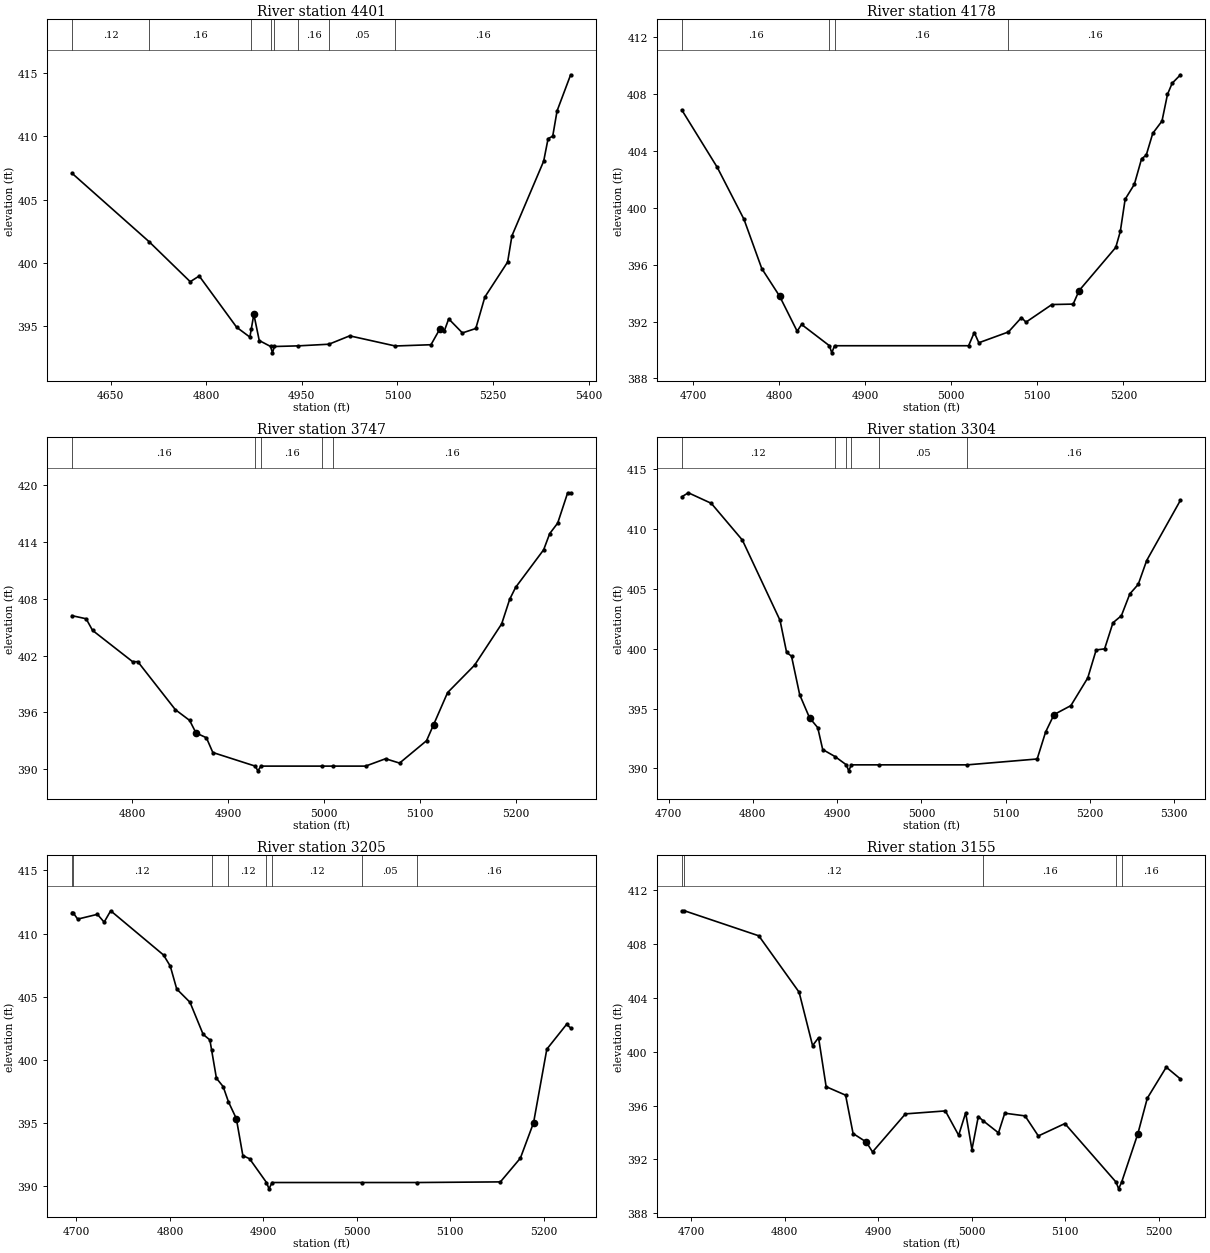
Type RM Length L Ch R = 1 ,4401    ,223,223,223
BEGIN DESCRIPTION:
UNT 035 IN CACR 9.0
END DESCRIPTION:
XS GIS Cut Line= 3
       3679799.6      10764060.2      3679587.57     10764350.95
      3679299.61     10764660.19
#Sta/Elev= 30
  4589.4  407.09  4710.4  401.69    4775  398.53  4789.1  398.98  4847.8  394.94
  4868.6  394.16  4870.8   394.8  4874.8  395.96  4883.3  393.89  4901.2  393.42
  4903.9  392.92  4907.2  393.42  4944.4  393.47  4992.6   393.6  5025.2  394.26
  5096.7  393.46  5152.7  393.56  5166.8  394.82  5173.7  394.66  5180.5   395.6
    5202  394.49    5223  394.84  5237.2  397.32  5272.9  400.08  5279.7  402.15
  5329.5  408.04  5336.4  409.81  5343.7  410.01  5350.5     412  5371.8  414.85
#Mann= 8 ,-1 , 0
  4589.4     .12       0  4710.4     .16       0  4870.8     .05       0
  4901.2    .033       0  4907.2     .05       0  4944.4     .16       0
  4992.6     .05       0  5096.7     .16       0
Bank Sta=4874.8,5166.8
XS Rating Curve= 0 ,0
Exp/Cntr=0.3,0.1

Type RM Length L Ch R = 1 ,4178    ,431,431,431
BEGIN DESCRIPTION:
UNT 035 IN CACR 8.0
END DESCRIPTION:
XS GIS Cut Line= 3
      3679299.61      10764010.2      3679364.45     10764259.37
      3679249.59     10764560.23
#Sta/Elev= 30
  4686.8   406.9  4728.1  402.85  4759.1   399.2  4779.8  395.73  4800.4   393.8
  4820.9  391.32    4826   391.8  4858.4   390.3  4861.1   389.8  4864.4   390.3
  5020.1   390.3  5026.7  391.23    5032  390.51  5066.4  391.27  5081.5  392.28
  5086.8  391.96  5116.9   393.2  5141.6  393.23  5148.5  394.18  5191.1  397.22
  5196.4  398.35    5202  400.61  5212.7  401.66  5221.1  403.46  5226.5  403.71
  5234.1  405.25  5244.8  406.11  5251.2  407.99  5256.6  408.77  5266.3  409.37
#Mann= 4 ,-1 , 0
  4686.8     .16       0  4858.4     .03       0  4864.4     .16       0
  5066.4     .16       0
Bank Sta=4800.4,5148.5
XS Rating Curve= 0 ,0
Exp/Cntr=0.3,0.1

Type RM Length L Ch R = 1 ,3747    ,443,443,443
BEGIN DESCRIPTION:
UNT 035 IN CACR 7.0
END DESCRIPTION:
XS GIS Cut Line= 3
      3679249.58      10763960.2      3678999.61     10764060.19
      3678849.63     10764260.17
#Sta/Elev= 30
  4737.5  406.22  4752.3  405.89    4759  404.66  4800.7  401.35  4806.1  401.35
  4845.2  396.27    4860  395.14  4866.7  393.81  4877.5   393.3  4884.2  391.74
  4928.3   390.3  4931.1   389.8  4934.3   390.3    4998   390.3  5009.3   390.3
  5043.2   390.3    5064  391.08  5078.6  390.62  5106.7  392.99    5114  394.68
  5128.6  398.08  5156.7  400.98  5184.9  405.35  5193.2  407.94  5199.4  409.21
  5228.6  413.19  5234.9   414.9  5243.2  416.01  5253.6  419.22  5256.7  419.22
#Mann= 5 ,-1 , 0
  4737.5     .16       0  4928.3    .033       0  4934.3     .16       0
    4998     .05       0  5009.3     .16       0
Bank Sta=4866.7,5114
XS Rating Curve= 0 ,0
Exp/Cntr=0.3,0.1

Type RM Length L Ch R = 1 ,3304    ,99,99,99
BEGIN DESCRIPTION:
UNT 035 IN CACR 6.0
END DESCRIPTION:
XS GIS Cut Line= 3
      3678799.61     10763560.19      3678649.61     10763810.19
      3678649.61     10764110.24
#Sta/Elev= 30
  4715.7  412.69  4723.5  413.03  4750.7  412.15  4787.6  409.08  4832.3  402.37
  4840.1  399.69  4845.9  399.38  4855.6  396.16  4867.3  394.23    4877  393.41
  4882.9  391.58  4897.6  390.99    4911   390.3  4913.7   389.8    4917   390.3
  4949.3   390.3  5054.4   390.3  5137.3  390.79  5147.3  393.04  5157.3   394.5
  5177.3  395.25  5197.3  397.56  5207.3   399.9  5217.3  399.99  5227.2  402.17
  5237.2  402.76  5247.2  404.58  5257.2  405.38  5267.2  407.37  5307.3  412.41
#Mann= 6 ,-1 , 0
  4715.7     .12       0  4897.6     .16       0    4911    .033       0
    4917     .16       0  4949.3     .05       0  5054.4     .16       0
Bank Sta=4867.3,5157.3
XS Rating Curve= 0 ,0
Exp/Cntr=0.3,0.1

Type RM Length L Ch R = 1 ,3205    ,50,50,50
BEGIN DESCRIPTION:
Mapping XS f7833222
END DESCRIPTION:
XS GIS Cut Line= 2
      3678788.48     10763540.28       3678404.5     10763911.24
#Sta/Elev= 30
  4695.1  411.66  4696.2  411.66  4701.3  411.14  4722.4  411.52  4729.6   410.9
  4736.6   411.8  4793.2   408.3  4800.4  407.42  4807.3  405.61  4821.5  404.56
  4835.6  402.02  4842.8  401.58  4844.7  400.76  4849.8  398.55    4857  397.89
  4862.7  396.68  4871.1  395.36  4878.1  392.43  4885.3  392.18  4903.4   390.3
  4906.1   389.8  4909.4   390.3  5005.6   390.3  5064.5   390.3  5153.8  390.35
  5175.2  392.23  5189.3  395.03  5203.5  400.85  5224.6  402.81    5229  402.53
#Mann= 8 ,-1 , 0
  4695.1     .05       0  4696.2     .12       0  4844.7     .16       0
  4862.7     .12       0  4903.4     .07       0  4909.4     .12       0
  5005.6     .05       0  5064.5     .16       0
Bank Sta=4871.1,5189.3
XS Rating Curve= 0 ,0
Exp/Cntr=0.3,0.1

Type RM Length L Ch R = 1 ,3155    ,47,47,47
BEGIN DESCRIPTION:
Mapping XS 85d17904
END DESCRIPTION:
XS GIS Cut Line= 4
      3678774.16     10763518.14      3678603.58     10763653.56
      3678442.12     10763798.09      3678344.56      10763813.7
#Sta/Elev= 30
    4690  410.47  4692.9  410.47  4772.4  408.61  4815.5  404.42  4829.9  400.45
  4836.3  401.04  4844.4   397.4  4865.2  396.77  4873.2  393.92  4887.3  393.29
    4894  392.55  4929.2  395.38  4971.9   395.6  4986.1  393.79  4993.6  395.46
  5000.3  392.73  5007.1  395.18  5012.4  394.86  5028.7  393.97  5035.4  395.43
  5057.1  395.23  5071.3  393.74  5099.7  394.66  5154.4  390.31  5157.2  389.81
  5160.4  390.31  5177.7   393.9  5187.8  396.54  5208.1  398.85  5223.3  397.97
#Mann= 5 ,-1 , 0
    4690     .05       0  4692.9     .12       0  5012.4     .16       0
  5154.4     .07       0  5160.4     .16       0
Bank Sta=4887.3,5177.7
XS Rating Curve= 0 ,0
Exp/Cntr=0.3,0.1

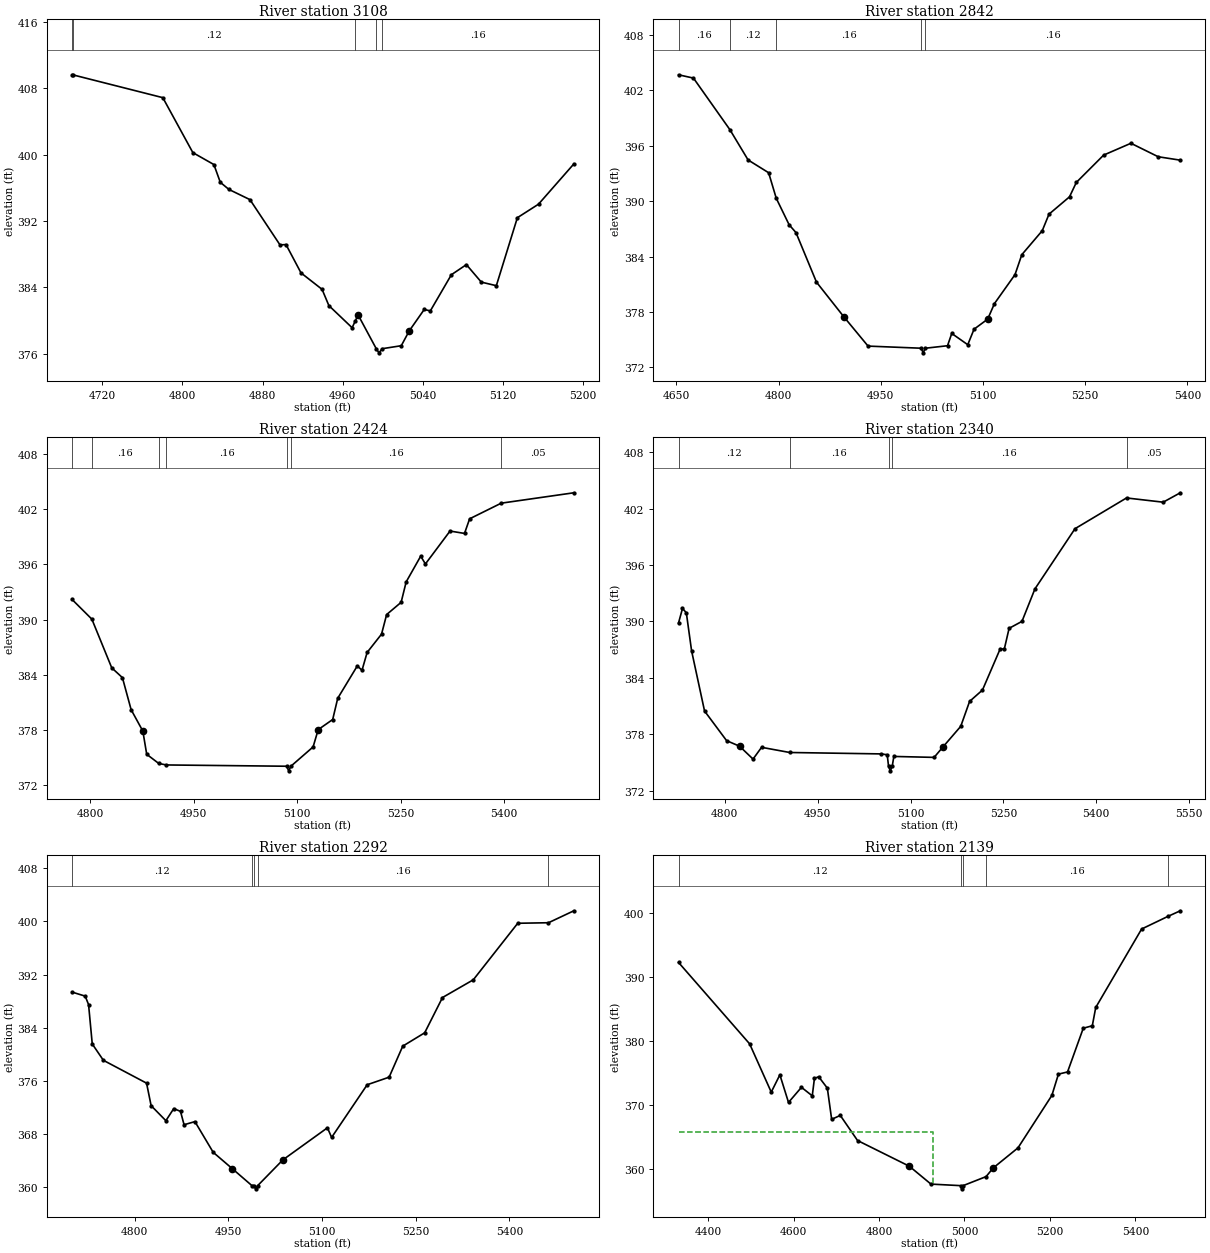
Type RM Length L Ch R = 1 ,3108    ,266,266,266
BEGIN DESCRIPTION:
Mapping XS ebb1b474
END DESCRIPTION:
XS GIS Cut Line= 2
      3678762.47      10763506.4      3678346.62      10763785.8
#Sta/Elev= 30
  4689.8  409.65  4690.3  409.65  4780.4  406.89  4810.4  400.26  4831.4  398.82
  4837.8  396.68  4846.4  395.82  4867.4  394.59  4897.4  389.13  4903.4  389.17
  4918.4  385.75  4939.4  383.77  4946.2  381.81  4969.4  379.14  4972.4  379.91
  4975.4  380.68  4993.5  376.61  4996.2  376.11  4999.5  376.61  5018.5  376.97
  5026.4  378.75  5041.4  381.34  5047.5  381.17  5068.5  385.53  5083.5  386.75
  5098.4  384.64  5113.4  384.21  5134.4  392.41  5155.5  394.04  5190.8   398.9
#Mann= 5 ,-1 , 0
  4689.8     .05       0  4690.3     .12       0  4972.4     .16       0
  4993.5     .07       0  4999.5     .16       0
Bank Sta=4975.4,5026.4
XS Rating Curve= 0 ,0
Exp/Cntr=0.3,0.1

Type RM Length L Ch R = 1 ,2842    ,418,418,418
BEGIN DESCRIPTION:
UNT 035 IN CACR 5.0
END DESCRIPTION:
XS GIS Cut Line= 4
      3678681.44     10763381.43      3678403.66     10763402.26
      3678320.33     10763516.84      3678306.22     10763832.59
#Sta/Elev= 30
  4653.2  403.69  4675.1  403.33  4728.6  397.74  4755.3  394.46  4785.4  393.08
  4796.6  390.31  4815.5  387.44  4825.5   386.6  4855.6  381.23  4895.7  377.48
  4931.3   374.3  5009.4  374.07  5012.1  373.57  5015.4  374.07  5047.9  374.34
  5054.1  375.67  5077.6  374.45  5086.8  376.13  5106.8  377.22  5116.8  378.91
  5146.9  382.04  5156.9   384.2  5186.9   386.8  5196.8  388.59  5226.9  390.47
  5236.9  392.03    5277  394.99    5317  396.27  5357.1  394.81  5389.5  394.44
#Mann= 5 ,-1 , 0
  4653.2     .16       0  4728.6     .12       0  4796.6     .16       0
  5009.4     .07       0  5015.4     .16       0
Bank Sta=4895.7,5106.8
XS Rating Curve= 0 ,0
Exp/Cntr=0.3,0.1

Type RM Length L Ch R = 1 ,2424    ,84,84,84
BEGIN DESCRIPTION:
UNT 035 IN CACR 4.0
END DESCRIPTION:
XS GIS Cut Line= 4
      3678575.32     10763120.75      3678432.09      10763051.3
      3678306.22     10763055.64      3677980.74     10763355.09
#Sta/Elev= 30
  4773.9  392.18  4802.6  390.04  4831.4  384.75  4846.9  383.68  4859.5   380.2
  4876.5  377.87  4882.1  375.35  4899.6  374.35  4910.6  374.19  5085.1  374.05
  5087.9  373.55  5091.1  374.05  5123.3  376.15  5130.7  378.03  5151.7  379.13
    5159  381.44  5187.4  384.96  5194.2  384.48  5201.6  386.42  5222.5  388.41
  5229.9  390.54  5250.9  391.87  5258.2  394.09  5279.3  396.89  5286.1  396.04
  5321.8  399.62  5342.8  399.36  5350.2  400.95    5396  402.65  5501.3  403.78
#Mann= 7 ,-1 , 0
  4773.9     .12       0  4802.6     .16       0  4899.6     .12       0
  4910.6     .16       0  5085.1     .07       0  5091.1     .16       0
    5396     .05       0
Bank Sta=4876.5,5130.7
XS Rating Curve= 0 ,0
Exp/Cntr=0.3,0.1

Type RM Length L Ch R = 1 ,2340    ,48,48,48
BEGIN DESCRIPTION:
Mapping XS b7fe4e58
END DESCRIPTION:
XS GIS Cut Line= 5
      3678607.18     10763060.82      3678486.13     10762973.61
      3678350.71     10762971.01      3678249.15     10762997.05
      3677980.91     10763321.28
#Sta/Elev= 30
  4725.4  389.84  4731.8  391.39    4738  390.92  4746.5  386.87  4767.4  380.48
    4803  377.33  4823.9  376.74  4845.7  375.37  4859.5  376.62    4905  376.07
  5052.5  375.92  5062.4  375.83  5064.5  374.62  5067.3  374.12  5070.5  374.62
  5073.1  375.65  5138.1  375.55  5152.4  376.66  5181.1  378.85  5195.4   381.5
  5216.2  382.71  5244.9   387.1  5251.4  387.05  5259.2  389.27    5280  390.01
  5300.9  393.46  5365.6  399.86  5448.8  403.13    5508  402.68  5535.7  403.68
#Mann= 5 ,-1 , 0
  4725.4     .12       0    4905     .16       0  5064.5     .07       0
  5070.5     .16       0  5448.8     .05       0
Bank Sta=4823.9,5152.4
XS Rating Curve= 0 ,0
Exp/Cntr=0.3,0.1

Type RM Length L Ch R = 1 ,2292    ,153,153,153
BEGIN DESCRIPTION:
Mapping XS dadacedc
END DESCRIPTION:
XS GIS Cut Line= 4
      3678629.33     10762985.32      3678448.37     10762908.51
      3678263.47     10762939.76      3677986.13     10763253.56
#Sta/Elev= 30
  4700.1  389.36  4721.1  388.75  4726.5  387.48  4732.4  381.55  4750.2  379.09
  4819.3  375.65  4826.6  372.26  4850.2     370  4862.8  371.82  4873.6   371.4
  4879.3  369.39  4896.7  369.86  4925.9  365.24  4956.3  362.79  4987.7  360.24
  4991.3  360.24    4994  359.74  4997.3  360.24  5037.4   364.1  5108.7  368.93
  5115.4  367.48  5172.3  375.41  5207.4  376.55  5229.2  381.22  5264.3  383.23
  5292.8  388.54  5342.1  391.21  5413.2  399.72  5462.4   399.8    5503   401.6
#Mann= 5 ,-1 , 0
  4700.1     .12       0  4987.7     .16       0  4991.3     .07       0
  4997.3     .16       0  5462.4     .05       0
Bank Sta=4956.3,5037.4
XS Rating Curve= 0 ,0
Exp/Cntr=0.3,0.1

Type RM Length L Ch R = 1 ,2139    ,75,75,75
BEGIN DESCRIPTION:
Mapping XS c5b263a8
END DESCRIPTION:
XS GIS Cut Line= 4
      3678904.46       10762681.      3678301.56     10762766.95
      3678090.63      10763110.7      3677987.99     10763236.29
#Sta/Elev= 30
  4330.8  392.29  4497.2  379.57  4547.8  372.03    4568  374.73  4588.2  370.42
  4618.5  372.78  4643.8  371.45  4648.9  374.18  4658.9  374.43  4679.1  372.65
  4689.2  367.78  4709.4  368.39  4749.8  364.47  4871.1  360.45  4921.6  357.66
  4990.9  357.42  4993.6  356.92  4996.9  357.42  5050.6  358.83  5067.3  360.18
  5125.3  363.32  5204.6  371.51    5220  374.84  5241.3  375.18  5278.1  382.01
  5299.3   382.4  5307.3  385.25  5414.7  397.51  5476.5  399.49  5505.3  400.36
#Mann= 5 ,-1 , 0
  4330.8     .12       0  4990.9     .07       0  4996.9     .12       0
  5050.6     .16       0  5476.5     .05       0
#XS Ineff= 2 , 0
         4925.45  365.77
Permanent Ineff=
       F       F
Bank Sta=4871.1,5067.3
XS Rating Curve= 0 ,0
Exp/Cntr=0.3,0.1

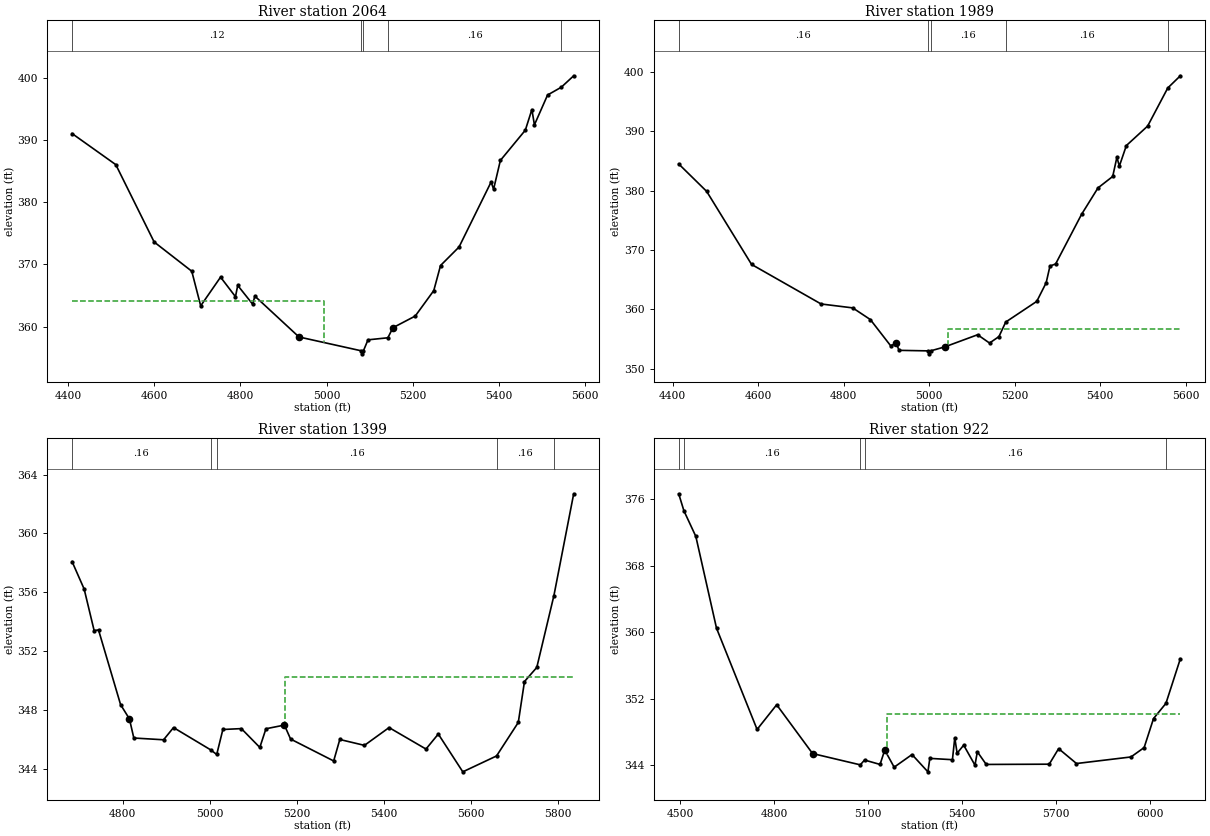
Type RM Length L Ch R = 1 ,2064    ,75,75,75
BEGIN DESCRIPTION:
Mapping XS c6b2a73b
END DESCRIPTION:
XS GIS Cut Line= 4
      3678857.58     10762595.06      3678267.71     10762755.23
      3678065.89     10763100.28      3677983.81     10763229.08
#Sta/Elev= 30
  4409.3     391  4510.8     386  4599.7  373.58    4687  368.88  4707.7  363.32
  4753.8  367.93  4788.4  364.79  4793.6   366.6  4828.2  363.59  4833.4  364.88
  4935.7  358.32  5079.3  356.11    5082  355.61  5085.3  356.11  5095.8  357.86
  5141.9  358.19  5153.7  359.81  5205.4  361.68  5248.4  365.77  5264.1   369.8
    5307  372.77  5381.4  383.21  5387.2  382.07  5402.9  386.68  5460.8  391.54
    5476  394.85  5481.9   392.4  5512.4  397.19  5544.2  398.44    5573  400.28
#Mann= 5 ,-1 , 0
  4409.3     .12       0  5079.3     .07       0  5085.3     .12       0
  5141.9     .16       0  5544.2     .05       0
#XS Ineff= 2 , 0
         4994.55  364.04
Permanent Ineff=
       F       F
Bank Sta=4935.7,5153.7
XS Rating Curve= 0 ,0
Exp/Cntr=0.3,0.1

Type RM Length L Ch R = 1 ,1989    ,590,590,590
BEGIN DESCRIPTION:
UNT 035 IN CACR 3.0
END DESCRIPTION:
XS GIS Cut Line= 3
      3678789.52     10762543.23      3678281.73     10762638.72
      3677977.89     10763220.34
#Sta/Elev= 30
  4414.3  384.52  4479.7  379.89  4584.7  367.57  4747.2   360.9  4821.2  360.24
  4862.4  358.27  4909.8  353.86    4923  354.27  4929.5  353.08  4997.3  352.99
  5000.1  352.49  5003.3  352.99  5036.3  353.66  5113.2  355.71  5141.1  354.31
  5163.1   355.4  5178.9  357.85  5251.5  361.34  5273.5  364.48  5282.4   367.3
  5295.6  367.65  5356.2  376.01  5394.7  380.48  5429.1  382.41  5438.9  385.65
  5444.6  384.15    5461  387.62  5510.8  390.91  5557.8  397.33  5587.2  399.39
#Mann= 5 ,-1 , 0
  4414.3     .16       0  4997.3     .07       0  5003.3     .16       0
  5178.9     .16       0  5557.8     .05       0
#XS Ineff= 2 , 0
                            5045          356.63
Permanent Ineff=
       F       F
Bank Sta=4923,5036.3
XS Rating Curve= 0 ,0
Exp/Cntr=0.3,0.1

Type RM Length L Ch R = 1 ,1399    ,477,477,477
BEGIN DESCRIPTION:
UNT 035 IN CACR 2.0
END DESCRIPTION:
XS GIS Cut Line= 3
      3678249.57     10762310.18      3677949.61     10762260.19
      3677349.63     10762860.17
#Sta/Elev= 30
  4684.1  358.08  4711.9  356.21  4734.8  353.39  4744.9  353.43  4795.6  348.35
  4815.9  347.38    4826  346.08  4894.4  345.96  4917.2  346.79  5002.3  345.28
  5016.5  344.96  5030.6  346.66  5073.1  346.72  5115.5  345.44  5129.6  346.71
    5172  346.96  5186.2  346.01  5285.2  344.52  5299.3  345.98  5355.9  345.58
  5412.5  346.79  5497.3  345.33  5525.6  346.35  5581.9  343.78  5659.4  344.86
  5709.4  347.14  5723.6  349.92  5751.9  350.88  5791.2  355.76  5836.7  362.69
#Mann= 5 ,-1 , 0
  4684.1     .16       0  5002.3     .07       0  5016.5     .16       0
  5659.4     .16       0  5791.2     .05       0
#XS Ineff= 2 , 0
                         5174.32          350.23
Permanent Ineff=
       F       F
Bank Sta=4815.9,5172
XS Rating Curve= 0 ,0
Exp/Cntr=0.3,0.1

Type RM Length L Ch R = 1 ,922     ,0,0,0
BEGIN DESCRIPTION:
UNT 035 IN CACR 1.0
END DESCRIPTION:
XS GIS Cut Line= 3
       3678249.6     10761710.19      3677749.61     10761860.19
      3677149.59     10762760.21
#Sta/Elev= 30
  4494.5  376.66  4511.2  374.61  4549.3  371.53  4615.4  360.49  4745.1  348.31
  4807.7  351.28  4922.5  345.41  5075.1  344.05  5088.6  344.63  5138.2   344.1
  5153.2  345.83  5183.3  343.77  5240.4  345.29  5291.2  343.21  5297.4  344.83
  5369.6  344.67  5377.1  347.31  5384.6  345.45  5405.6  346.42  5441.7  344.01
  5449.2  345.62  5477.7   344.1    5679  344.13  5709.1     346  5766.2  344.21
  5940.4     345  5982.5  346.13  6012.5  349.62  6052.2  351.45  6098.2  356.81
#Mann= 5 ,-1 , 0
  4494.5     .05       0  4511.2     .16       0  5075.1     .07       0
  5088.6     .16       0  6052.2     .05       0
#XS Ineff= 2 , 0
                         5161.93          350.11
Permanent Ineff=
       F       F
Bank Sta=4922.5,5153.2
XS Rating Curve= 0 ,0
Exp/Cntr=0.3,0.1

Chan Stop Cuts=-1
Use User Specified Reach Order=0
Composite Channel Slope=5