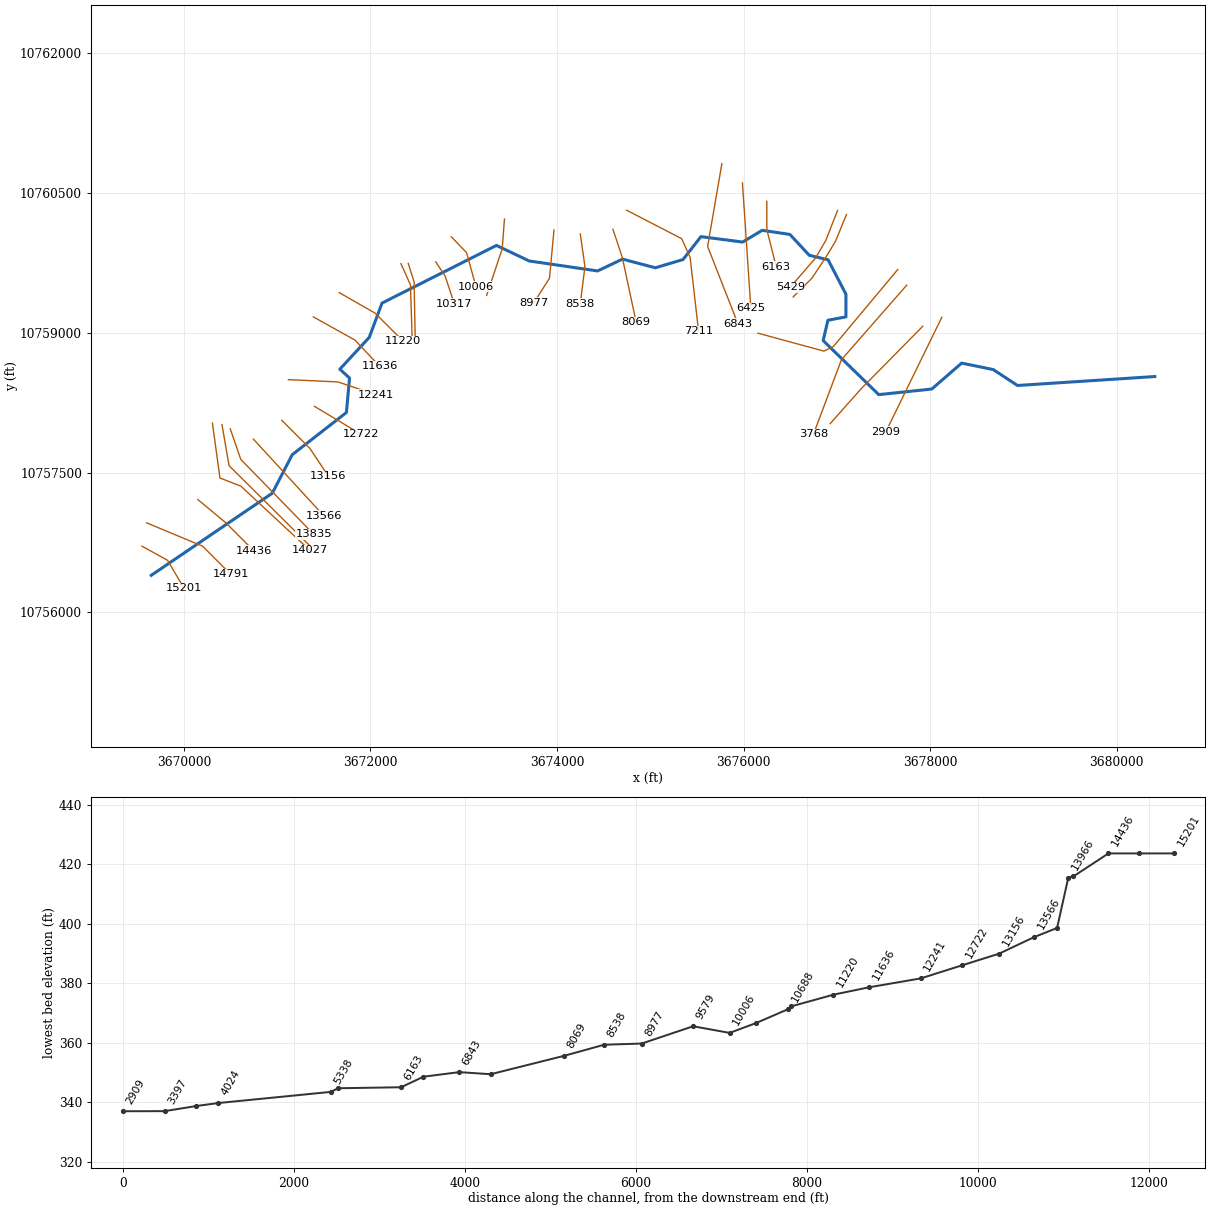
--- UNT 036 IN CACR.prj (project) ---

Proj Title=UNT 036 IN CACR Base Level Engineering
Current Plan=p01
Default Exp/Contr=0.3,0.1
English Units
Geom File=g01
Flow File=f01
Plan File=p01
Y Axis Title=Elevation
X Axis Title(PF)=Main Channel Distance
X Axis Title(XS)=Station
BEGIN DESCRIPTION:
UNT 036 IN CACR
END DESCRIPTION:
DSS Export Rating Curves= 0
DSS Export Rating Curve Sorted= 0
DSS Export Volume Flow Curves= 0
DXF OffsetX= 0
DXF OffsetY= 0
DXF ScaleX= 1
DXF ScaleY= 10

--- UNT 036 IN CACR.p01 (plan) ---

Plan Title=Multiple Run
Short Identifier=Multiple
Geom File=g01
Flow File=f01
Subcritical Flow
K Sum by GR= 0
Std Step Tol= 0.01
Critical Tol= 0.01
Num of Std Step Trials= 20
Max Error Tol= 0.3
Flow Tol Ratio= 0.001
Split Flow NTrial= 30
Split Flow Tol= 0.02
Split Flow Ratio= 0.02
Log Output Level= 0
Friction Slope Method= 1
Unsteady Friction Slope Method= 2
Unsteady Bridges Friction Slope Method= 1
Parabolic Critical Depth
Global Vel Dist=  1 , 1 , 1
Global Log Level= 0
CheckData=True
Encroach Param= -1, 0, 0, 0
BEGIN DESCRIPTION:
Multiple Run
END DESCRIPTION:

--- UNT 036 IN CACR.f01 (steady flow) ---

Flow Title=Multiple
Program Version=4.10
Number of Profiles= 7
Profile Names=10-year,25-year,50-year,1pct_min,100-year,1pct_plu,500-year
River Rch & RM=UNT 036 IN CACR,Reach-1         ,15201
     619     849    1040     936    1266    1713    1880
River Rch & RM=UNT 036 IN CACR,Reach-1         ,10317
     717     989    1217    1100    1488    2012    2226
River Rch & RM=UNT 036 IN CACR,Reach-1         ,8538
     822    1141    1411    1279    1730    2340    2609
River Rch & RM=UNT 036 IN CACR,Reach-1         ,6843
    1177    1663    2079    1904    2575    3483    3962
River Rch & RM=UNT 036 IN CACR,Reach-1         ,3768
    1626    2326    2932    2703    3655    4944    5701
River Rch & RM=UNT 036 IN CACR,Reach-1         ,3397
    1626    2326    2932    2703    3655    4944    5701
Boundary for River Rch & Prof#=UNT 036 IN CACR,Reach-1         , 1
Up Type= 0
Dn Type= 3
Dn Slope=0.0001
Boundary for River Rch & Prof#=UNT 036 IN CACR,Reach-1         , 2
Up Type= 0
Dn Type= 3
Dn Slope=0.0001
Boundary for River Rch & Prof#=UNT 036 IN CACR,Reach-1         , 3
Up Type= 0
Dn Type= 3
Dn Slope=0.0001
Boundary for River Rch & Prof#=UNT 036 IN CACR,Reach-1         , 4
Up Type= 0
Dn Type= 3
Dn Slope=0.0001
Boundary for River Rch & Prof#=UNT 036 IN CACR,Reach-1         , 5
Up Type= 0
Dn Type= 3
Dn Slope=0.0001
Boundary for River Rch & Prof#=UNT 036 IN CACR,Reach-1         , 6
Up Type= 0
Dn Type= 3
Dn Slope=0.0001
Boundary for River Rch & Prof#=UNT 036 IN CACR,Reach-1         , 7
Up Type= 0
Dn Type= 3
Dn Slope=0.0001
DSS Import GetInterval= 0
DSS Import GetPeak= 0
DSS Import FillOption= 0

--- UNT 036 IN CACR.g01 (geometry) ---

Geom Title=Existing Conditions
Program Version=4.10

River Reach=UNT 036 IN CACR ,Reach-1
Reach XY= 30
      3669649.41     10756397.11        3670947.       10757278.
      3671161.75       10757692.        3671742.       10758144.
      3671775.75       10758514.      3671671.75       10758609.
       3671987.5       10758951.      3672123.75       10759318.
      3673351.25       10759937.        3673702.       10759770.
      3674435.25       10759663.      3674702.25       10759790.
       3675054.5       10759697.        3675351.       10759785.
      3675543.25       10760031.      3675990.25       10759973.
      3676200.25       10760099.      3676497.25       10760055.
      3676704.75       10759831.       3676906.5       10759783.
      3677097.75       10759414.        3677098.       10759170.
        3676905.       10759134.      3676853.75       10758916.
        3677450.       10758336.      3678018.75       10758396.
      3678338.75       10758674.      3678677.25       10758605.
       3678937.5       10758434.       3680409.5       10758530.

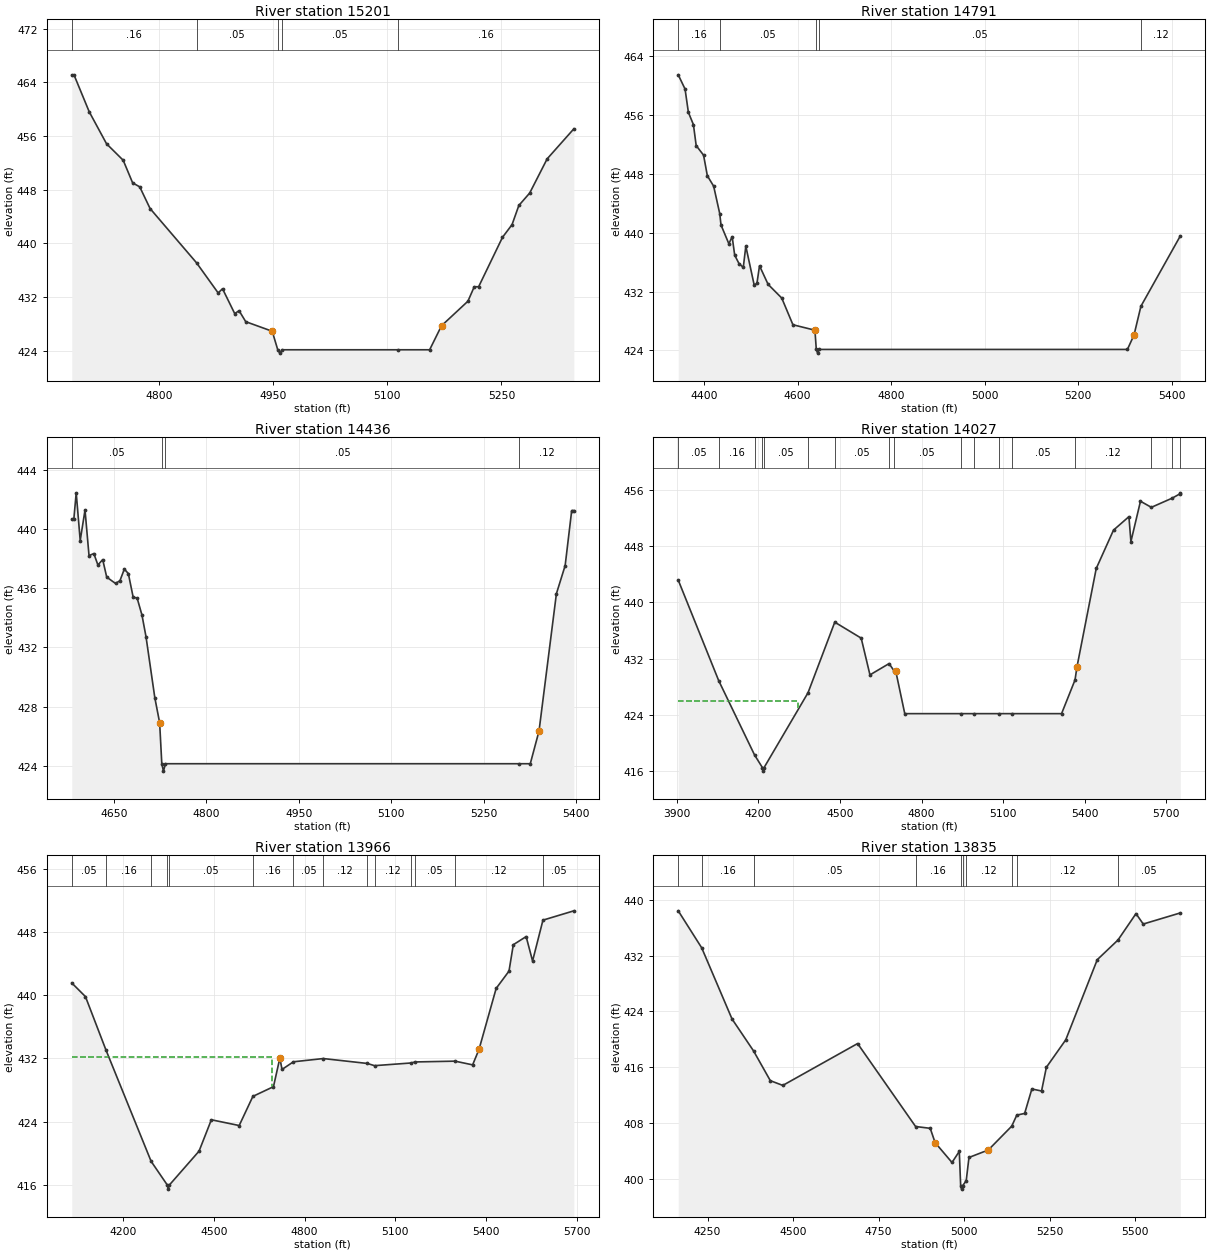
Type RM Length L Ch R = 1 ,15201   ,410,410,410
BEGIN DESCRIPTION:
UNT 036 IN CACR 30.0
END DESCRIPTION:
XS GIS Cut Line= 3
      3669549.61     10756710.19      3669824.96     10756557.81
      3669999.62     10756260.17
#Sta/Elev= 30
  4685.3  465.13  4688.2  465.13  4708.2  459.63    4731  454.85  4752.9  452.39
  4765.3  449.02  4774.6  448.43  4788.2   445.2  4849.3   437.1  4877.7  432.61
  4883.4  433.24  4899.4  429.54  4905.2  429.96  4913.9  428.33  4948.7   426.9
    4956  424.14  4958.7  423.64    4962  424.14  5113.7  424.14  5155.6  424.14
  5171.2  427.72  5205.9  431.38  5214.2  433.53    5220  433.54  5251.3   440.9
  5263.9   442.8  5272.8  445.65  5287.1  447.51    5310   452.6  5345.1  457.08
#Mann= 5 ,-1 , 0
  4685.3     .16       0  4849.3     .05       0    4956    .033       0
    4962     .05       0  5113.7     .16       0
Bank Sta=4948.7,5171.2
XS Rating Curve= 0 ,0
Exp/Cntr=0.3,0.1

Type RM Length L Ch R = 1 ,14791   ,355,355,355
BEGIN DESCRIPTION:
UNT 036 IN CACR 29.0
END DESCRIPTION:
XS GIS Cut Line= 3
      3669599.62     10756960.18      3670199.61     10756710.19
      3670499.64     10756410.15
#Sta/Elev= 30
  4344.5   461.4  4359.1  459.47  4366.2  456.31    4377  454.64  4382.9   451.8
  4398.7   450.5  4406.8   447.7  4420.3  446.29  4433.3  442.57    4436  441.03
  4452.8  438.48  4459.9  439.44  4465.3  436.93  4474.5  435.79  4483.7  435.27
  4489.1  438.15    4507  432.88  4512.9   433.1  4518.4  435.49  4536.8  432.97
    4566  431.11  4589.9  427.49    4637  426.75  4639.9  424.14  4642.7  423.64
  4645.9  424.14  5305.6  424.14  5319.8  426.11  5334.5     430  5418.8  439.54
#Mann= 5 ,-1 , 0
  4344.5     .16       0  4433.3     .05       0  4639.9    .033       0
  4645.9     .05       0  5334.5     .12       0
Bank Sta=4637,5319.8
XS Rating Curve= 0 ,0
Exp/Cntr=0.3,0.1

Type RM Length L Ch R = 1 ,14436   ,409,409,409
BEGIN DESCRIPTION:
UNT 036 IN CACR 28.0
END DESCRIPTION:
XS GIS Cut Line= 3
      3670149.57     10757210.22      3670449.61     10756960.19
      3670749.59     10756660.21
#Sta/Elev= 30
  4581.8  440.63  4585.1  440.63    4589  442.43  4595.5  439.21  4603.3  441.27
  4609.8  438.19  4617.6  438.33  4624.2  437.56    4632  437.92  4638.5  436.74
  4652.8  436.31    4660   436.5  4667.1  437.28  4673.6  436.98  4681.4  435.39
  4687.9  435.32  4695.7  434.18  4702.3  432.71  4716.6  428.59  4724.4  426.91
  4727.9  424.14  4730.6  423.64  4733.9  424.14  5308.3  424.14  5325.9  424.14
  5340.1  426.35  5368.3  435.62  5382.5  437.52  5393.1  441.23  5396.6  441.23
#Mann= 4 ,-1 , 0
  4581.8     .05       0  4727.9    .033       0  4733.9     .05       0
  5308.3     .12       0
Bank Sta=4724.4,5340.1
XS Rating Curve= 0 ,0
Exp/Cntr=0.3,0.1

Type RM Length L Ch R = 1 ,14027   ,61,61,61
BEGIN DESCRIPTION:
UNT 036 IN CACR 27.0
END DESCRIPTION:
XS GIS Cut Line= 4
      3670305.44     10758029.85      3670386.17     10757441.28
      3670610.81     10757353.65      3671350.79     10756664.35
#Sta/Elev= 30
    3905  443.19  4053.8  428.85  4185.5  418.26  4214.6  416.44  4217.3  415.94
  4220.6  416.44  4382.3  427.12  4480.7  437.19  4577.9  434.91  4610.1  429.67
  4680.4  431.28  4698.7  430.25  4704.9  430.22  4738.1  424.14  4943.2  424.14
  4992.9  424.14  5083.5  424.14    5131  424.14  5314.8  424.14  5364.3  428.95
  5371.4   430.8  5442.3  444.85  5505.8  450.32  5562.5  452.24  5569.8  448.68
    5605  454.44    5645  453.57    5721  454.87  5750.4   455.5  5751.5  455.64
#Mann= 17 ,-1 , 0
    3905     .05       0  4053.8     .16       0  4185.5     .05       0
  4214.6    .033       0  4220.6     .05       0  4382.3     .16       0
  4480.7     .05       0  4680.4     .16       0  4698.7     .05       0
  4943.2     .12       0  4992.9     .05       0  5083.5     .12       0
    5131     .05       0  5364.3     .12       0    5645     .05       0
    5721     .16       0  5750.4     .05       0
#XS Ineff= 2 , 0
         4345.64  425.92  6012.2          426.34
Permanent Ineff=
       F       F
Bank Sta=4704.9,5371.4
XS Rating Curve= 0 ,0
Exp/Cntr=0.3,0.1

Type RM Length L Ch R = 1 ,13966   ,131,131,131
BEGIN DESCRIPTION:
Mapping XS 9473e370
END DESCRIPTION:
XS GIS Cut Line= 3
      3670407.74     10758014.37       3670483.7     10757573.83
      3671343.08     10756720.96
#Sta/Elev= 30
  4031.4  441.55  4076.6  439.82  4144.1  433.08  4293.4  418.97  4347.2  415.95
    4350  415.45  4353.2  415.95  4451.7  420.26  4492.3  424.23  4584.2   423.5
  4629.4  427.19  4697.4  428.42  4718.5  432.04  4725.6   430.6  4763.3  431.57
  4861.9  431.98    5007  431.36  5031.1  431.08  5152.1  431.42  5165.1  431.55
  5297.1  431.65    5355  431.18  5376.1  433.14  5432.7  440.86  5475.1  443.05
  5489.3  446.39  5531.7  447.42  5552.9  444.33  5587.2   449.5  5689.2  450.68
#Mann= 14 ,-1 , 0
  4031.4     .05       0  4144.1     .16       0  4293.4     .05       0
  4347.2     .07       0  4353.2     .05       0  4629.4     .16       0
  4763.3     .05       0  4861.9     .12       0    5007     .16       0
  5031.1     .12       0  5152.1     .16       0  5165.1     .05       0
  5297.1     .12       0  5587.2     .05       0
#XS Ineff= 2 , 0
         4692.98  432.21
Permanent Ineff=
       F       F
Bank Sta=4718.5,5376.1
XS Rating Curve= 0 ,0
Exp/Cntr=0.3,0.1

Type RM Length L Ch R = 1 ,13835   ,269,269,269
BEGIN DESCRIPTION:
Mapping XS 1760edef
END DESCRIPTION:
XS GIS Cut Line= 3
      3670496.73     10757968.76      3670609.56      10757641.1
      3671390.79     10756838.18
#Sta/Elev= 30
  4164.5   438.4  4233.1   433.1  4321.6  422.93  4384.6  418.35  4433.5   414.1
    4470  413.42  4688.5  419.41  4857.9  407.54  4900.7  407.28  4914.9  405.24
  4964.3  402.39  4985.6  403.98  4989.6  399.08  4992.3  398.58  4995.6  399.08
  5005.8  399.78  5013.9  403.11  5070.4  404.18  5138.8  407.59  5153.6  409.17
  5176.5  409.41  5197.6  412.91  5225.9  412.62    5240  416.01  5296.6  419.94
  5388.7  431.41  5449.3  434.23  5501.8     438    5523  436.51  5631.3   438.1
#Mann= 10 ,-1 , 0
  4164.5     .05       0  4233.1     .16       0  4384.6     .05       0
  4857.9     .16       0  4989.6     .07       0  4995.6     .16       0
  5005.8     .12       0  5138.8     .16       0  5153.6     .12       0
  5449.3     .05       0
#XS Ineff= 2 , 0
                         5535.33          404.25
Permanent Ineff=
       F       F
Bank Sta=4914.9,5070.4
XS Rating Curve= 0 ,0
Exp/Cntr=0.3,0.1

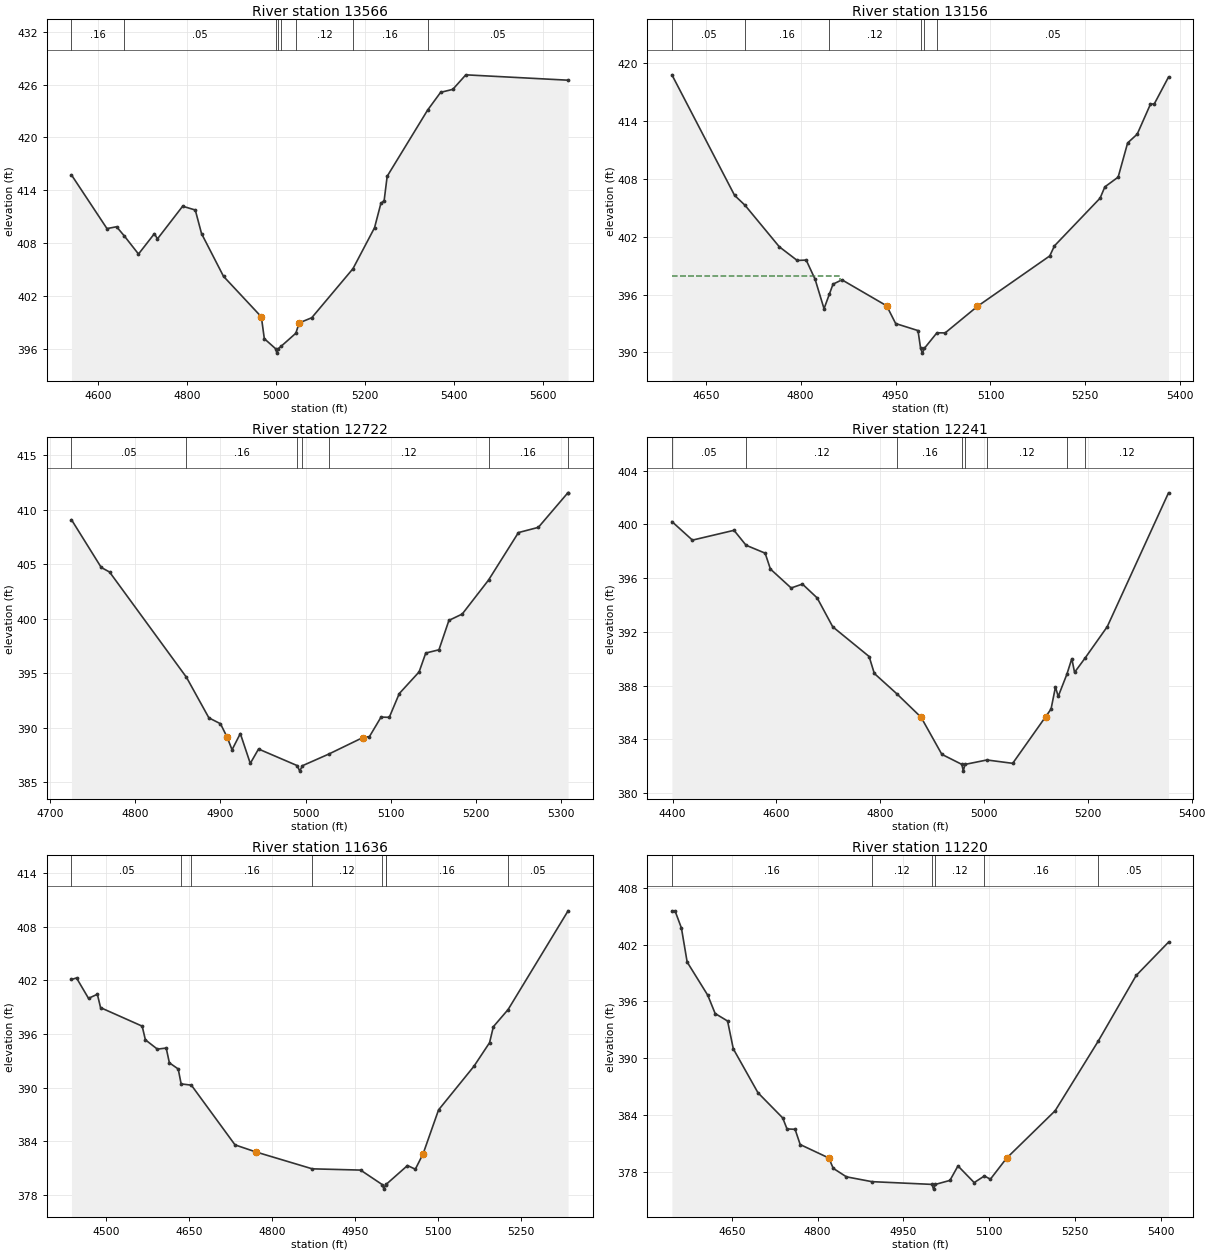
Type RM Length L Ch R = 1 ,13566   ,410,410,410
BEGIN DESCRIPTION:
UNT 036 IN CACR 26.0
END DESCRIPTION:
XS GIS Cut Line= 2
      3670744.75     10757858.47      3671499.94     10757035.58
#Sta/Elev= 30
  4539.7  415.73  4619.5  409.64  4641.1  409.85  4658.9  408.78  4690.4  406.75
  4726.2  409.07    4733  408.47  4789.7  412.18  4818.1  411.75  4832.2  409.07
  4881.6  404.22  4966.7  399.62  4973.4  397.14  4998.8     396  5001.6   395.5
  5004.8     396  5010.8  396.26  5044.3  397.76  5051.7  398.93  5080.1  399.52
  5172.8  405.09  5221.3  409.74  5235.5  412.49  5242.9  412.82  5249.7  415.58
  5340.7   423.1  5369.9  425.11  5397.3  425.45  5426.6   427.1  5656.6  426.49
#Mann= 8 ,-1 , 0
  4539.7     .16       0  4658.9     .05       0  4998.8     .03       0
  5004.8     .05       0  5010.8     .16       0  5044.3     .12       0
  5172.8     .16       0  5340.7     .05       0
Bank Sta=4966.7,5051.7
XS Rating Curve= 0 ,0
Exp/Cntr=0.3,0.1

Type RM Length L Ch R = 1 ,13156   ,434,434,434
BEGIN DESCRIPTION:
UNT 036 IN CACR 25.0
END DESCRIPTION:
XS GIS Cut Line= 3
      3671049.59      10758060.2      3671349.61     10757760.19
      3671549.59     10757460.22
#Sta/Elev= 30
  4596.6  418.82  4695.6  406.31  4712.1  405.28  4766.3  400.97  4794.6  399.55
  4808.8  399.59  4822.9  397.59    4837  394.54  4845.5  396.07  4851.2  397.09
  4865.3  397.54    4936  394.84  4950.2     393  4985.5  392.27  4989.6  390.43
  4992.4  389.93  4995.6  390.43  5015.4  392.04  5028.4  392.03  5079.5  394.79
  5193.7  400.02  5201.2  401.07  5273.3  406.02  5280.8  407.19  5301.8   408.2
  5316.8  411.75  5331.9  412.66  5352.9  415.78  5358.9   415.8  5381.4  418.59
#Mann= 6 ,-1 , 0
  4596.6     .05       0  4712.1     .16       0  4845.5     .12       0
  4989.6     .07       0  4995.6     .12       0  5015.4     .05       0
#XS Ineff= 2 , 0
         4862.48  397.95
Permanent Ineff=
       F       F
Bank Sta=4936,5079.5
XS Rating Curve= 0 ,0
Exp/Cntr=0.3,0.1

Type RM Length L Ch R = 1 ,12722   ,481,481,481
BEGIN DESCRIPTION:
UNT 036 IN CACR 24.0
END DESCRIPTION:
XS GIS Cut Line= 3
      3671399.65     10758210.16      3671649.61     10758060.19
      3671899.57     10757910.21
#Sta/Elev= 30
  4725.2  409.09  4760.1  404.71  4769.9  404.29  4860.2  394.62  4886.5   390.9
  4900.1  390.36  4907.9  389.13  4913.7  387.97  4923.4  389.46  4935.1  386.72
  4944.8  388.04  4990.4  386.51  4993.1  386.01  4996.4  386.51  5027.1  387.57
  5067.2  389.09    5075  389.18  5088.6  390.97  5098.3  390.95    5110  393.13
  5133.3  395.12  5141.1  396.85  5156.6  397.15  5168.3  399.85  5183.9  400.43
  5214.8  403.55  5249.9  407.91  5273.3  408.39  5307.9  411.56  5308.2  411.56
#Mann= 7 ,-1 , 0
  4725.2     .05       0  4860.2     .16       0  4990.4     .07       0
  4996.4     .16       0  5027.1     .12       0  5214.8     .16       0
  5307.9     .05       0
Bank Sta=4907.9,5067.2
XS Rating Curve= 0 ,0
Exp/Cntr=0.3,0.1

Type RM Length L Ch R = 1 ,12241   ,605,605,605
BEGIN DESCRIPTION:
UNT 036 IN CACR 23.0
END DESCRIPTION:
XS GIS Cut Line= 3
      3671120.15     10758496.53      3671651.38     10758472.22
      3672054.14     10758336.81
#Sta/Elev= 30
  4398.7   400.2  4438.2  398.82  4518.3  399.55  4541.5  398.44  4578.3  397.85
  4588.4  396.67  4628.4  395.26  4650.1  395.55  4678.5  394.52  4708.5  392.37
  4778.6  390.16  4788.6   388.9  4832.1  387.38  4878.7  385.64  4918.7  382.88
  4957.3  382.13    4960  381.63  4963.3  382.13  5005.5  382.46  5055.2  382.21
  5118.5  385.67  5129.1  386.25  5137.6  387.89  5142.9  387.19  5159.5  388.83
  5169.1     390  5174.4  388.98  5194.6  390.04  5237.4  392.38  5355.4  402.34
#Mann= 8 ,-1 , 0
  4398.7     .05       0  4541.5     .12       0  4832.1     .16       0
  4957.3     .07       0  4963.3     .16       0  5005.5     .12       0
  5159.5     .16       0  5194.6     .12       0
Bank Sta=4878.7,5118.5
XS Rating Curve= 0 ,0
Exp/Cntr=0.3,0.1

Type RM Length L Ch R = 1 ,11636   ,416,416,416
BEGIN DESCRIPTION:
UNT 036 IN CACR 22.0
END DESCRIPTION:
XS GIS Cut Line= 3
      3671387.52     10759170.13      3671835.41     10758920.14
       3672099.3     10758638.89
#Sta/Elev= 30
  4436.8  402.09  4445.9  402.26  4467.6  399.98  4483.6  400.44  4489.4  398.94
  4564.7  396.87  4570.5  395.34  4592.2   394.3  4608.2  394.42  4613.9  392.77
  4629.9  392.08  4635.2  390.41  4653.7  390.27  4732.7  383.59  4770.4   382.8
  4872.5  380.91  4959.9  380.77  4999.3  379.14  5002.1  378.64  5005.3  379.14
    5006  379.16  5044.8  381.28    5059  380.87  5073.1   382.6    5101   387.5
    5165  392.38  5193.3  395.02  5200.2  396.81  5226.9  398.73  5335.4  409.77
#Mann= 8 ,-1 , 0
  4436.8     .05       0  4635.2     .12       0  4653.7     .16       0
  4872.5     .12       0  4999.3     .07       0  5005.3     .12       0
    5006     .16       0  5226.9     .05       0
Bank Sta=4770.4,5073.1
XS Rating Curve= 0 ,0
Exp/Cntr=0.3,0.1

Type RM Length L Ch R = 1 ,11220   ,492,492,492
BEGIN DESCRIPTION:
UNT 036 IN CACR 21.0
END DESCRIPTION:
XS GIS Cut Line= 3
      3671665.25     10759430.57      3672049.61     10759210.19
       3672349.6      10758910.2
#Sta/Elev= 30
  4545.6  405.56    4551  405.56  4562.2  403.74  4572.2  400.15  4608.3  396.63
  4621.1  394.71  4642.8  393.92  4652.8  390.98  4695.9  386.34  4739.1  383.68
  4746.6  382.52  4760.7  382.48  4769.6  380.87  4819.6  379.45  4827.3  378.36
  4850.3  377.46  4894.8  376.95  4999.8  376.66  5002.5  376.16  5005.8  376.66
  5031.1  377.08  5045.2  378.61  5073.5  376.85  5091.3  377.55  5101.8  377.21
  5130.1  379.43  5214.9  384.44  5290.1  391.79  5356.4  398.73  5412.9  402.25
#Mann= 6 ,-1 , 0
  4545.6     .16       0  4894.8     .12       0  4999.8     .07       0
  5005.8     .12       0  5091.3     .16       0  5290.1     .05       0
Bank Sta=4819.6,5130.1
XS Rating Curve= 0 ,0
Exp/Cntr=0.3,0.1

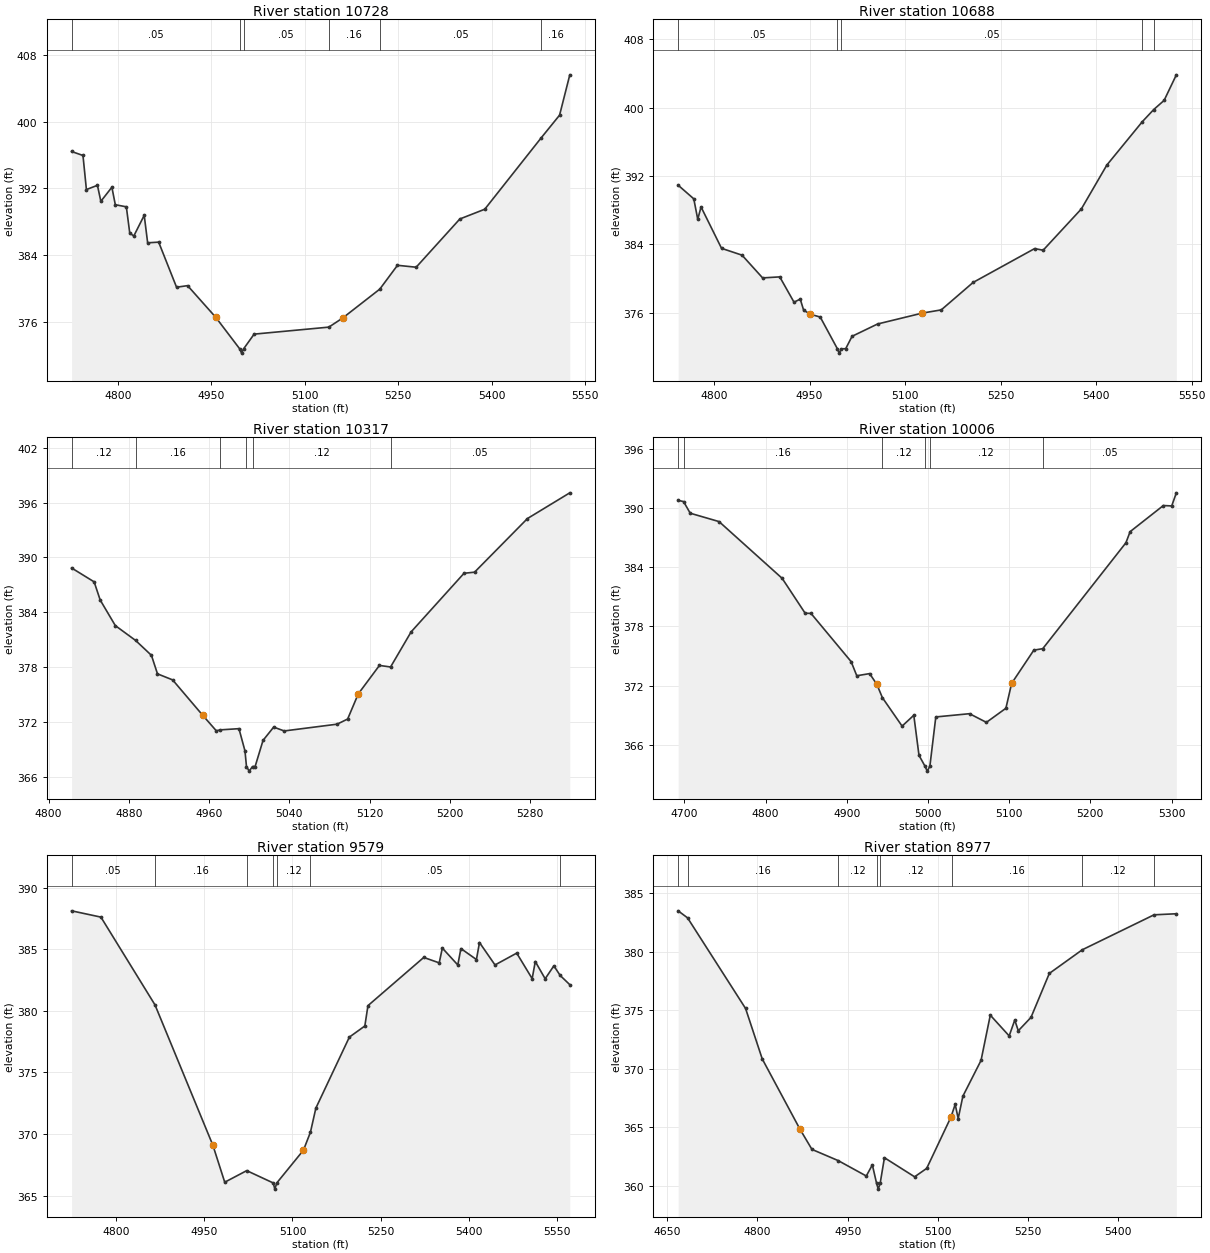
Type RM Length L Ch R = 1 ,10728   ,40,40,40
BEGIN DESCRIPTION:
UNT 036 IN CACR 20.0
END DESCRIPTION:
XS GIS Cut Line= 3
      3672326.88      10759741.4      3672428.86     10759513.57
      3672446.18     10758963.76
#Sta/Elev= 30
  4725.5  396.44  4743.8  395.96  4749.3  391.87    4767  392.38  4772.5  390.46
  4790.2  392.15  4795.7  390.05  4813.4   389.8  4818.9  386.64  4825.4   386.3
  4842.1  388.78  4847.6  385.48  4865.3  385.56    4894  380.15  4911.7  380.34
  4956.9  376.54  4995.5  372.74  4998.3  372.24  5001.5  372.74  5018.5  374.52
  5138.4  375.36  5160.6  376.45  5220.2  379.92  5248.6  382.78  5278.6  382.55
  5348.7  388.34  5388.7  389.51  5479.2  398.07  5508.8   400.8  5525.2  405.64
#Mann= 6 ,-1 , 0
  4725.5     .05       0  4995.5     .04       0  5001.5     .05       0
  5138.4     .16       0  5220.2     .05       0  5479.2     .16       0
Bank Sta=4956.9,5160.6
XS Rating Curve= 0 ,0
Exp/Cntr=0.3,0.1

Type RM Length L Ch R = 1 ,10688   ,371,371,371
BEGIN DESCRIPTION:
Mapping XS 487a488e
END DESCRIPTION:
XS GIS Cut Line= 3
      3672404.98     10759743.64      3672467.93     10759546.12
      3672478.78     10758971.03
#Sta/Elev= 30
  4743.5  390.92  4768.1  389.32  4774.3  386.93  4779.5  388.37  4811.7  383.53
  4843.9  382.73  4876.2  380.07  4903.1  380.19  4925.5  377.23  4935.3  377.59
  4940.6   376.3  4950.8  375.83  4966.7  375.49  4993.7  371.77  4996.5  371.27
  4999.7  371.77  5006.7  371.79  5016.7  373.24  5056.8  374.68  5126.8  375.95
  5156.8  376.33  5206.8  379.54  5303.4   383.5  5316.8  383.31  5376.8  388.14
  5416.8  393.27  5472.7  398.36  5490.5  399.77  5506.8  400.84    5526  403.83
#Mann= 5 ,-1 , 0
  4743.5     .05       0  4993.7     .04       0  4999.7     .05       0
  5472.7     .16       0  5490.5     .05       0
Bank Sta=4950.8,5126.8
XS Rating Curve= 0 ,0
Exp/Cntr=0.3,0.1

Type RM Length L Ch R = 1 ,10317   ,311,311,311
BEGIN DESCRIPTION:
UNT 036 IN CACR 19.0
END DESCRIPTION:
XS GIS Cut Line= 3
      3672699.61     10759760.18      3672799.61     10759610.19
      3672899.61     10759310.19
#Sta/Elev= 30
  4822.9  388.85  4845.4  387.33  4851.4  385.35  4866.5  382.55  4886.7  380.93
  4902.5   379.3  4908.5  377.28  4923.6  376.62  4953.6  372.75  4967.1  371.06
  4971.3  371.16  4989.7  371.29  4995.7  368.86  4997.2  367.15  4999.9  366.65
  5003.2  367.15  5005.8  367.15  5013.7  370.01  5024.3  371.46  5034.8  371.04
  5087.5  371.78    5098  372.34  5108.6  375.09  5129.7   378.2  5140.8  378.03
  5161.3  381.87    5214  388.27  5224.5  388.39  5277.2  394.25  5319.4  397.06
#Mann= 6 ,-1 , 0
  4822.9     .12       0  4886.7     .16       0  4971.3     .12       0
  4997.2     .07       0  5003.2     .12       0  5140.8     .05       0
Bank Sta=4953.6,5108.6
XS Rating Curve= 0 ,0
Exp/Cntr=0.3,0.1

Type RM Length L Ch R = 1 ,10006   ,427,427,427
BEGIN DESCRIPTION:
UNT 036 IN CACR 18.0
END DESCRIPTION:
XS GIS Cut Line= 3
      3672867.21     10760028.97      3673030.44      10759858.8
      3673130.99     10759494.72
#Sta/Elev= 30
  4692.4   390.8  4699.1  390.67  4707.3  389.49  4742.8  388.64  4820.5  382.88
  4848.8  379.34    4856  379.32  4905.4  374.43  4912.4  372.99  4928.2  373.21
  4937.1  372.12  4943.9  370.77  4968.2  367.88  4982.6  368.98    4989  364.91
  4996.4  363.81  4999.1  363.31  5002.4  363.81  5009.7  368.81  5051.2  369.14
    5072  368.26    5096  369.69  5103.1  372.22  5130.4  375.59  5141.4  375.74
  5243.8  386.49    5249  387.62  5289.9  390.27  5300.2  390.23  5305.9  391.56
#Mann= 6 ,-1 , 0
  4692.4     .05       0  4699.1     .16       0  4943.9     .12       0
  4996.4     .07       0  5002.4     .12       0  5141.4     .05       0
Bank Sta=4937.1,5103.1
XS Rating Curve= 0 ,0
Exp/Cntr=0.3,0.1

Type RM Length L Ch R = 1 ,9579    ,602,602,602
BEGIN DESCRIPTION:
UNT 036 IN CACR 17.0
END DESCRIPTION:
XS GIS Cut Line= 3
      3673436.69     10760219.91      3673412.38     10759900.46
      3673245.72     10759400.47
#Sta/Elev= 30
  4724.3  388.11  4774.2   387.6  4866.2  380.48  4964.7  369.09  4984.8   366.1
  5022.2  367.04  5067.3  366.04    5070  365.54  5073.3  366.04  5118.7   368.7
  5130.6  370.16  5139.8  372.11  5196.8  377.87  5223.1  378.77  5228.4  380.42
  5323.3  384.33  5349.6  383.89  5354.9  385.09  5381.2  383.72  5386.5  385.05
  5412.9  384.16  5418.1  385.54  5444.5  383.72  5481.4  384.68  5507.7  382.61
    5513     384  5529.8   382.6  5544.6  383.65  5555.3  382.87  5571.7  382.12
#Mann= 7 ,-1 , 0
  4724.3     .05       0  4866.2     .16       0  5022.2     .12       0
  5067.3     .07       0  5073.3     .12       0  5130.6     .05       0
  5555.3     .16       0
Bank Sta=4964.7,5118.7
XS Rating Curve= 0 ,0
Exp/Cntr=0.3,0.1

Type RM Length L Ch R = 1 ,8977    ,439,439,439
BEGIN DESCRIPTION:
UNT 036 IN CACR 16.0
END DESCRIPTION:
XS GIS Cut Line= 3
      3673967.94     10760101.86      3673919.32     10759584.49
      3673752.67      10759324.1
#Sta/Elev= 30
    4668  383.47  4683.7  382.87  4780.2  375.14  4807.9  370.84  4870.6  364.85
  4890.6  363.12  4934.4  362.16    4981  360.85  4991.1   361.8  4998.1  360.23
  5000.9  359.73  5004.1  360.23  5011.2  362.41  5061.4  360.78  5081.5   361.5
  5121.7  365.86  5122.9  366.04  5128.9  366.96  5133.9  365.75  5141.7  367.66
  5171.9  370.71  5187.3  374.57  5218.7   372.8    5228  374.15  5233.9  373.24
    5255  374.38  5285.5  378.13  5340.4  380.15  5459.7  383.13  5496.8  383.22
#Mann= 8 ,-1 , 0
    4668     .05       0  4683.7     .16       0  4934.4     .12       0
  4998.1     .07       0  5004.1     .12       0  5122.9     .16       0
  5340.4     .12       0  5459.7     .16       0
Bank Sta=4870.6,5121.7
XS Rating Curve= 0 ,0
Exp/Cntr=0.3,0.1

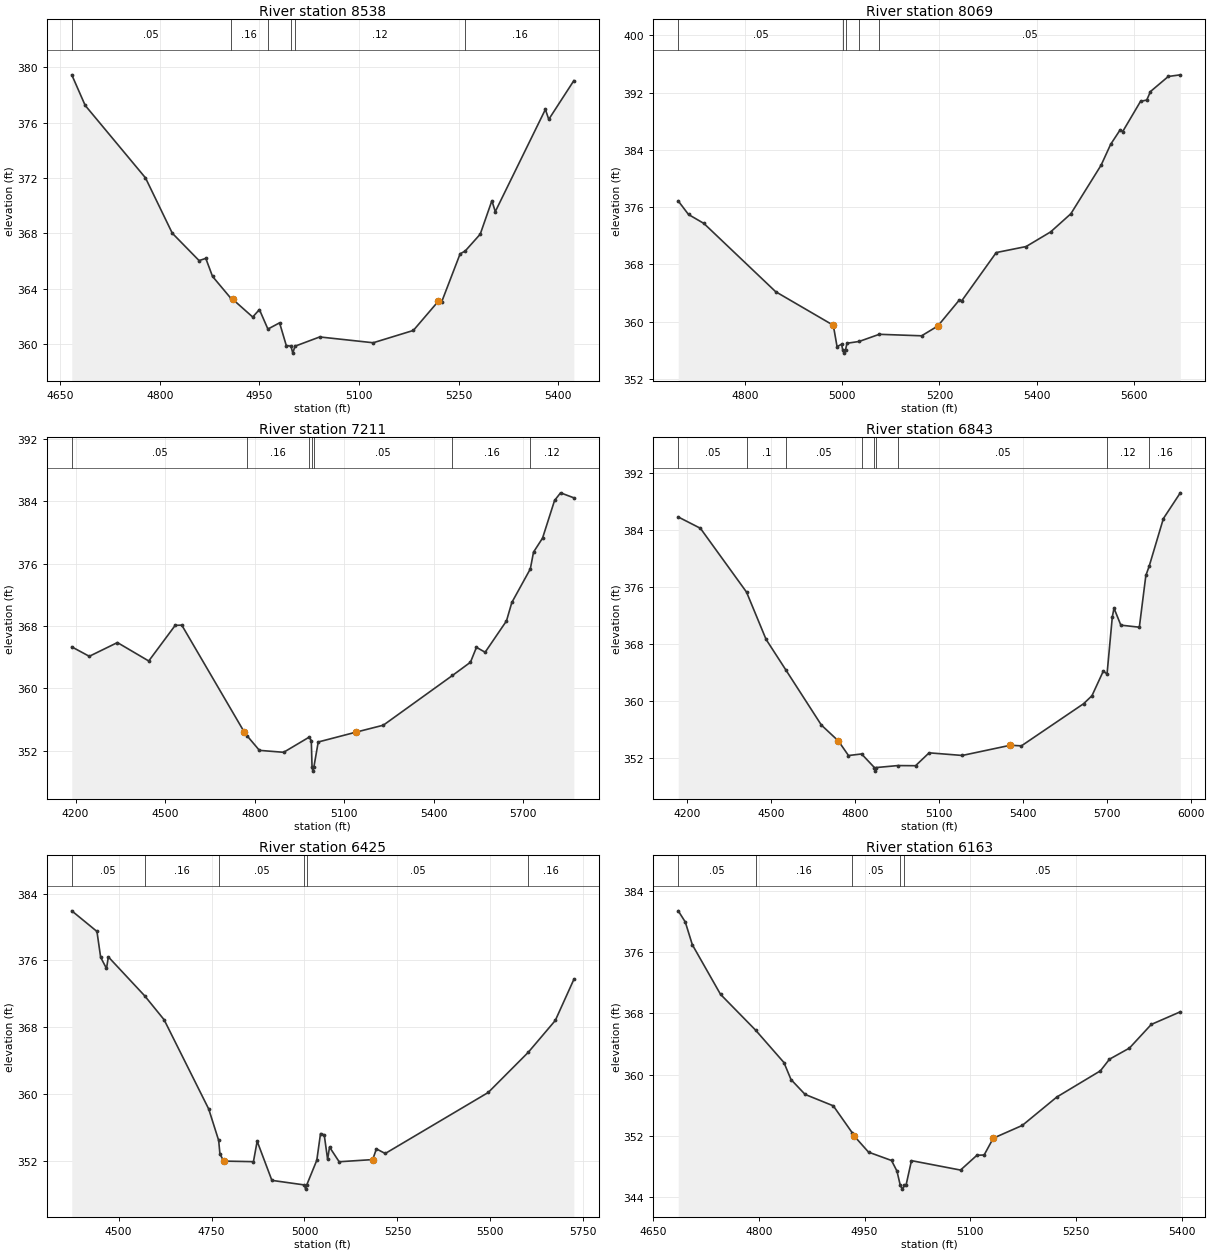
Type RM Length L Ch R = 1 ,8538    ,469,469,469
BEGIN DESCRIPTION:
UNT 036 IN CACR 15.0
END DESCRIPTION:
XS GIS Cut Line= 3
      3674249.61     10760060.19      3674299.61     10759710.19
      3674249.61     10759310.16
#Sta/Elev= 30
  4667.1  379.45  4687.3  377.24  4778.2     372  4818.6     368    4859  366.02
  4869.1  366.18  4879.2  364.88  4906.6  363.31  4909.5  363.23  4939.8  361.94
  4949.9  362.48  4962.7  361.07  4980.3  361.52  4990.4  359.88  4997.5  359.83
  5000.2  359.33  5003.5  359.83  5040.8   360.5  5121.4  360.08  5181.9  360.97
  5219.7  363.09  5224.7  363.05  5252.4  366.51    5260  366.71  5282.7  367.93
  5300.3  370.35  5305.4  369.56  5380.9  376.95    5386  376.23  5423.8  379.03
#Mann= 6 ,-1 , 0
  4667.1     .05       0  4906.6     .16       0  4962.7     .12       0
  4997.5     .07       0  5003.5     .12       0    5260     .16       0
Bank Sta=4909.5,5219.7
XS Rating Curve= 0 ,0
Exp/Cntr=0.3,0.1

Type RM Length L Ch R = 1 ,8069    ,858,858,858
BEGIN DESCRIPTION:
UNT 036 IN CACR 14.0
END DESCRIPTION:
XS GIS Cut Line= 3
      3674599.61      10760110.2      3674699.61     10759810.19
       3674849.6     10759110.21
#Sta/Elev= 30
    4663  376.86  4684.1  374.97  4715.7  373.72  4863.3  364.18  4981.8  359.49
  4989.5   356.5  4998.8  356.85    5001   356.1  5003.7   355.6    5007   356.1
  5009.9  356.98  5034.9  357.23  5076.3  358.23  5163.3  358.02  5196.6  359.39
  5240.9  363.03    5246  362.93  5316.7  369.65  5378.1  370.49  5428.4  372.53
  5470.1  375.07  5532.3  381.86  5551.9  384.77  5571.6  386.81  5576.7  386.56
  5613.3  390.77  5626.1  390.96  5633.8  392.15  5670.4  394.25  5695.1  394.48
#Mann= 5 ,-1 , 0
    4663     .05       0    5001     .03       0    5007     .05       0
  5034.9     .16       0  5076.3     .05       0
Bank Sta=4981.8,5196.6
XS Rating Curve= 0 ,0
Exp/Cntr=0.3,0.1

Type RM Length L Ch R = 1 ,7211    ,368,368,368
BEGIN DESCRIPTION:
UNT 036 IN CACR 13.0
END DESCRIPTION:
XS GIS Cut Line= 4
      3674747.05     10760314.55      3675337.28     10760009.01
      3675427.56     10759807.63      3675517.84     10759015.98
#Sta/Elev= 30
  4187.1  365.33  4245.8  364.12    4340  365.88    4445  363.52  4533.6  368.08
  4555.7  368.11  4764.3  354.47  4775.2  353.91  4815.7  352.08  4896.9  351.83
  4982.4  353.77  4989.6  353.33  4992.1  349.92  4994.9  349.42  4998.1  349.92
  5012.8  353.15  5140.3  354.42  5230.9   355.3  5462.6  361.67  5522.8  363.36
  5542.9  365.27    5572  364.64  5643.5  368.65  5661.4  371.01  5723.4  375.31
  5734.1  377.46  5764.3  379.25  5804.6  384.07  5824.7  385.05  5869.2  384.41
#Mann= 7 ,-1 , 0
  4187.1     .05       0  4775.2     .16       0  4982.4     .05       0
  4992.1     .03       0  4998.1     .05       0  5462.6     .16       0
  5723.4     .12       0
Bank Sta=4764.3,5140.3
XS Rating Curve= 0 ,0
Exp/Cntr=0.3,0.1

Type RM Length L Ch R = 1 ,6843    ,418,418,418
BEGIN DESCRIPTION:
UNT 036 IN CACR 12.0
END DESCRIPTION:
XS GIS Cut Line= 3
      3675767.84     10760814.55      3675615.06     10759925.68
      3675940.88     10759093.81
#Sta/Elev= 30
    4168  385.81  4247.3  384.22  4412.2  375.26  4482.1  368.62  4553.6  364.28
  4679.8  356.59  4740.6  354.36  4776.8  352.31  4823.6  352.53  4869.5  350.62
  4872.3  350.12  4875.5  350.62  4953.1   350.9  5016.6  350.88  5065.1  352.69
  5183.5  352.32    5355  353.75  5395.2  353.67  5617.6  359.59  5647.4  360.71
    5688  364.17  5701.3  363.75  5720.2  371.79  5726.2     373  5750.6  370.62
  5816.8  370.33  5840.1   377.6  5851.7  378.86  5902.8  385.59  5963.3   389.2
#Mann= 9 ,-1 , 0
    4168     .05       0  4412.2      .1       0  4553.6     .05       0
  4823.6     .16       0  4869.5     .03       0  4875.5     .16       0
  4953.1     .05       0  5701.3     .12       0  5851.7     .16       0
Bank Sta=4740.6,5355
XS Rating Curve= 0 ,0
Exp/Cntr=0.3,0.1

Type RM Length L Ch R = 1 ,6425    ,262,262,262
BEGIN DESCRIPTION:
UNT 036 IN CACR 11.0
END DESCRIPTION:
XS GIS Cut Line= 2
      3675988.32     10760607.69      3676078.61     10759260.41
#Sta/Elev= 30
  4374.1  381.94  4441.8  379.47  4451.8  376.37  4467.5  375.03  4472.5  376.42
  4570.3  371.75  4622.4  368.89  4742.4  358.19  4769.2  354.42  4772.5  352.83
  4782.5  351.95  4862.7  351.88  4872.7  354.33  4912.3  349.64    5000  349.09
  5002.8  348.59    5006  349.09  5033.1  352.05  5043.1  355.25  5053.1  355.09
  5062.2  352.15  5067.3  353.63  5093.2  351.87  5183.4  352.13  5193.4  353.41
  5217.2  352.86  5494.1  360.17  5601.9  364.99  5674.5   368.8  5724.4  373.72
#Mann= 6 ,-1 , 0
  4374.1     .05       0  4570.3     .16       0  4769.2     .05       0
    5000     .03       0    5006     .05       0  5601.9     .16       0
Bank Sta=4782.5,5183.4
XS Rating Curve= 0 ,0
Exp/Cntr=0.3,0.1

Type RM Length L Ch R = 1 ,6163    ,734,734,734
BEGIN DESCRIPTION:
UNT 036 IN CACR 10.0
END DESCRIPTION:
XS GIS Cut Line= 3
      3676249.61     10760410.16      3676249.61     10760110.19
      3676349.61     10759710.17
#Sta/Elev= 30
  4685.6  381.39  4695.6  379.93  4705.6  376.96  4745.6  370.48  4795.3  365.81
  4835.6  361.57  4845.6  359.35  4865.6  357.41  4905.6  355.92  4932.3  352.42
  4935.6  351.94  4955.6  349.87  4988.2  348.78  4995.9   347.4  5000.6  345.54
  5003.4  345.04  5006.6  345.54  5008.8  345.56  5016.5  348.76  5086.1  347.53
  5109.3  349.46  5119.6   349.5  5132.5  351.69  5173.7  353.36  5222.7  357.07
  5284.5  360.49  5297.4  362.01  5325.7  363.46  5356.7  366.55  5397.9   368.2
#Mann= 5 ,-1 , 0
  4685.6     .05       0  4795.3     .16       0  4932.3     .05       0
  5000.6     .03       0  5006.6     .05       0
Bank Sta=4935.6,5132.5
XS Rating Curve= 0 ,0
Exp/Cntr=0.3,0.1

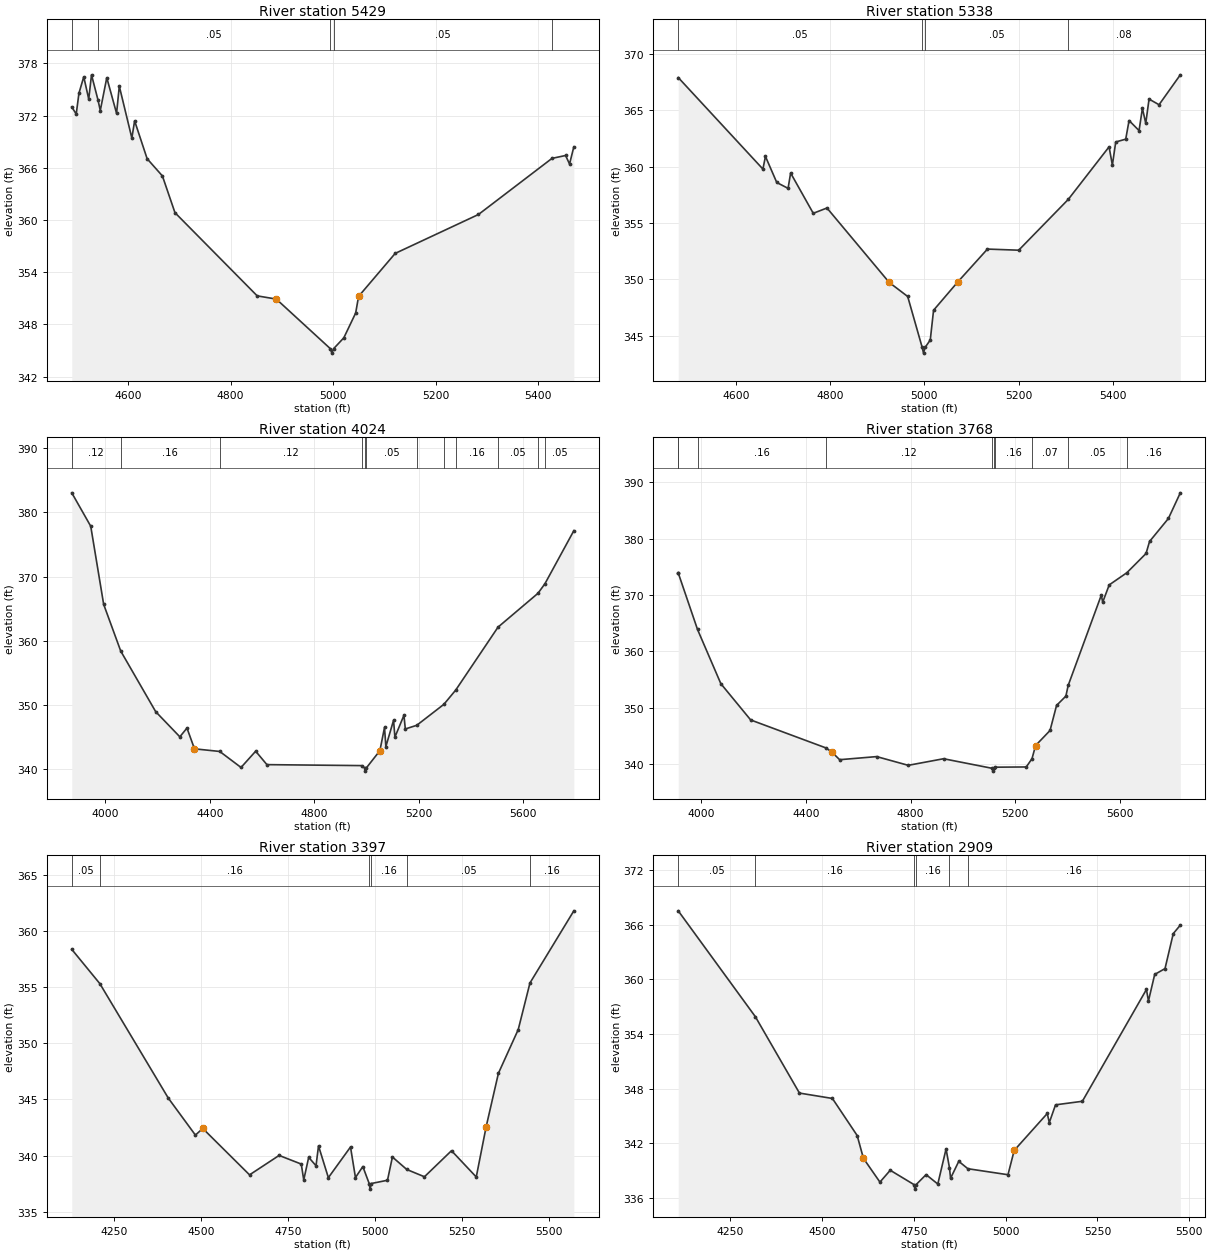
Type RM Length L Ch R = 1 ,5429    ,91,91,91
BEGIN DESCRIPTION:
UNT 036 IN CACR 9.0
END DESCRIPTION:
XS GIS Cut Line= 4
      3677008.29     10760311.96      3676882.42     10759990.79
      3676773.92     10759804.15      3676500.45     10759487.28
#Sta/Elev= 30
  4490.2     373  4498.9  372.18  4504.2  374.58  4513.6  376.46  4523.3   373.9
  4528.7  376.69  4541.4  373.79  4545.8  372.58  4558.5  376.36  4577.6  372.26
  4582.9  375.39  4607.4  369.42  4612.8   371.4  4637.2  367.05    4667  365.07
  4691.5  360.85  4851.9  351.29  4889.2  350.92  4994.8  345.21  4997.5  344.71
  5000.8  345.21  5020.9  346.47    5044  349.32  5049.7  351.23  5121.1  356.17
  5283.5  360.64    5427  367.09  5453.5  367.42  5461.2  366.44  5469.6  368.42
#Mann= 5 ,-1 , 0
  4490.2     .08       0  4541.4     .05       0  4994.8     .04       0
  5000.8     .05       0    5427     .08       0
Bank Sta=4889.2,5049.7
XS Rating Curve= 0 ,0
Exp/Cntr=0.3,0.1

Type RM Length L Ch R = 1 ,5338    ,1314,1314,1314
BEGIN DESCRIPTION:
UNT 036 IN CACR 8.0
END DESCRIPTION:
XS GIS Cut Line= 5
      3677103.78     10760268.56      3676986.59     10759982.11
      3676895.44      10759830.2      3676734.85     10759587.14
      3676531.89     10759384.18
#Sta/Elev= 30
  4477.8  367.89  4657.4  359.78  4662.8   360.9  4686.8  358.59  4710.8  358.07
  4716.2  359.43  4764.2  355.86  4793.3  356.33  4925.4  349.73  4964.5  348.49
  4995.3  343.97  4998.1  343.47  5001.3  343.97  5012.4  344.63  5019.4  347.27
  5070.6  349.77  5133.7  352.69    5200  352.59  5305.1  357.09  5391.7  361.75
  5398.7  360.13  5405.8  362.18    5427  362.43  5434.1  364.08  5455.3  363.19
  5462.4  365.16  5469.5  363.84  5476.5  365.98  5497.7  365.48  5542.8  368.13
#Mann= 4 ,-1 , 0
  4477.8     .05       0  4995.3     .04       0  5001.3     .05       0
  5305.1     .08       0
Bank Sta=4925.4,5070.6
XS Rating Curve= 0 ,0
Exp/Cntr=0.3,0.1

Type RM Length L Ch R = 1 ,4024    ,256,256,256
BEGIN DESCRIPTION:
UNT 036 IN CACR 7.0
END DESCRIPTION:
XS GIS Cut Line= 4
      3677653.66     10759677.93      3676966.15     10758855.01
      3676861.99     10758802.92      3676154.97     10758995.27
#Sta/Elev= 30
  3871.7  383.03  3944.3  377.83  3993.8  365.67  4059.1  358.41  4192.9  348.98
  4285.3  345.07  4312.6  346.43  4341.3   343.2  4438.1  342.79  4519.5   340.3
  4575.5  342.83  4618.5  340.74    4981  340.59  4993.1  340.23  4995.8  339.73
  4999.1  340.23  5050.9  342.91  5068.6  346.52  5073.8  343.55  5103.2  347.64
  5108.4  345.02    5143  348.42  5148.2  346.29    5192  346.86  5295.7  350.12
  5341.1  352.34    5503  362.13    5656   367.4  5682.6  368.89  5793.2  377.14
#Mann= 12 ,-1 , 0
  3871.7     .12       0  4059.1     .16       0  4438.1     .12       0
    4981     .05       0  4993.1     .03       0  4999.1     .05       0
    5192     .12       0  5295.7     .07       0  5341.1     .16       0
    5503     .05       0    5656     .08       0  5682.6     .05       0
Bank Sta=4341.3,5050.9
XS Rating Curve= 0 ,0
Exp/Cntr=0.3,0.1

Type RM Length L Ch R = 1 ,3768    ,371,371,371
BEGIN DESCRIPTION:
UNT 036 IN CACR 6.0
END DESCRIPTION:
XS GIS Cut Line= 3
      3677749.59     10759510.16      3677049.61     10758710.19
       3676749.6     10757910.17
#Sta/Elev= 30
  3912.9  373.83  3913.6  373.83  3986.5  363.89  4075.6  354.26  4189.5  347.82
  4477.6  342.84  4500.8  342.06  4529.3  340.76  4670.7  341.31  4791.3  339.76
  4926.1  340.93  5111.7  339.23  5114.5  338.73  5117.7  339.23    5124  339.43
    5242  339.47  5263.9  340.94  5277.6  343.27  5332.8  345.95  5357.7   350.4
  5393.3  352.05    5402  353.94  5528.6  369.98  5533.9  368.73  5558.8   371.8
  5626.1  373.96  5699.5  377.38  5712.8  379.51  5784.9   383.6  5830.3  388.15
#Mann= 10 ,-1 , 0
  3912.9     .16       0  3913.6     .12       0  3986.5     .16       0
  4477.6     .12       0  5111.7     .07       0  5117.7     .12       0
    5124     .16       0  5263.9     .07       0    5402     .05       0
  5626.1     .16       0
Bank Sta=4500.8,5277.6
XS Rating Curve= 0 ,0
Exp/Cntr=0.3,0.1

Type RM Length L Ch R = 1 ,3397    ,488,488,488
BEGIN DESCRIPTION:
UNT 036 IN CACR 5.0
END DESCRIPTION:
XS GIS Cut Line= 3
      3677922.07     10759069.72      3677255.39     10758392.62
       3676929.3     10758024.91
#Sta/Elev= 30
  4128.8  358.35  4209.4   355.3    4406  345.11  4483.8  341.82    4505  342.41
  4639.3  338.28  4724.2  340.01  4787.8  339.24  4794.9  337.83  4809.1  339.84
  4830.2  339.09  4837.3  340.86  4865.6  338.03  4929.2  340.76  4943.4  338.04
  4964.6  339.02  4982.8  337.51  4985.5  337.01  4988.8  337.51  5035.4   337.8
  5049.5  339.87  5090.7  338.76  5141.5  338.11  5219.2  340.43  5290.3  338.09
  5318.8  342.58  5353.9  347.32  5410.8  351.21  5444.5  355.36  5570.5  361.78
#Mann= 6 ,-1 , 0
  4128.8     .05       0  4209.4     .16       0  4982.8     .07       0
  4988.8     .16       0  5090.7     .05       0  5444.5     .16       0
Bank Sta=4505,5318.8
XS Rating Curve= 0 ,0
Exp/Cntr=0.3,0.1

Type RM Length L Ch R = 1 ,2909    ,994,994,994
BEGIN DESCRIPTION:
UNT 036 IN CACR 4.0
END DESCRIPTION:
XS GIS Cut Line= 2
      3678126.93     10759166.96      3677526.24     10757937.79
#Sta/Elev= 30
  4107.6  367.52  4317.8   355.9  4437.9  347.52  4527.7  346.93  4595.2  342.86
  4612.2  340.36  4657.2  337.75  4685.3  339.05  4749.9  337.48  4752.6  336.98
  4755.9  337.48    4783  338.57  4814.9  337.54  4837.4  341.39  4846.6  339.34
  4849.7  338.17    4872  340.03  4896.8  339.22  5006.1  338.56  5023.1  341.23
  5113.2  345.28  5118.7  344.28  5135.7  346.23  5208.8  346.62  5383.4  358.89
  5388.9  357.63  5405.9  360.54    5434  361.18  5456.5  365.02  5475.7  365.95
#Mann= 6 ,-1 , 0
  4107.6     .05       0  4317.8     .16       0  4749.9     .07       0
  4755.9     .16       0  4846.6     .05       0  4896.8     .16       0
Bank Sta=4612.2,5023.1
XS Rating Curve= 0 ,0
Exp/Cntr=0.3,0.1