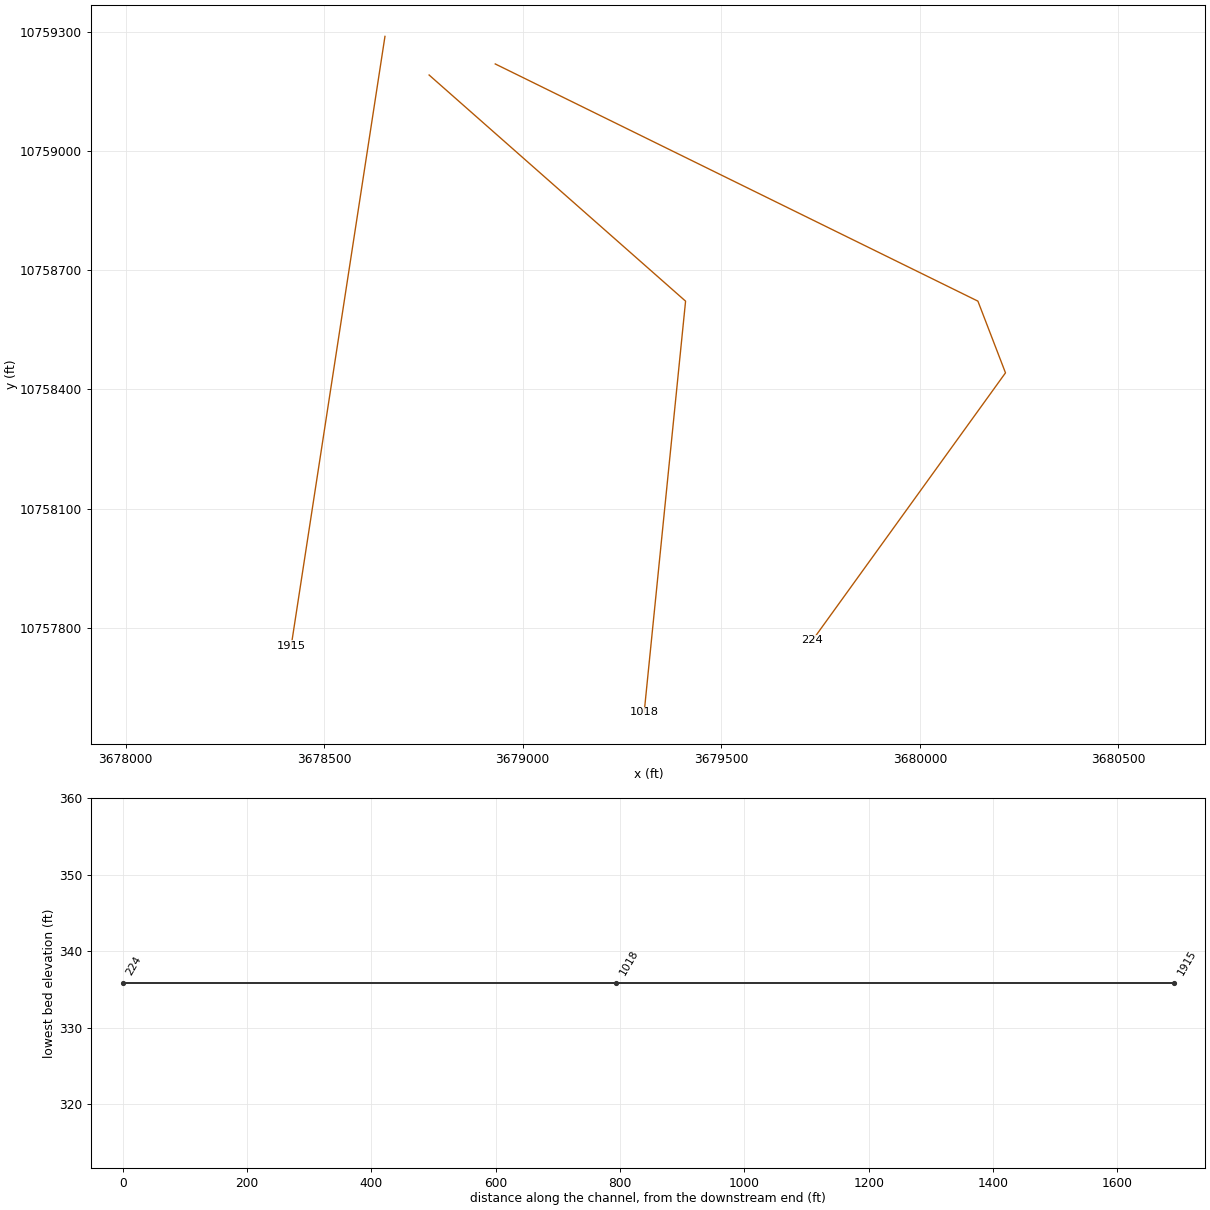
HEC-RAS study UNT 036 IN CACR.prj: UNT 036 IN CACR Base Level Engineering

--- UNT 036 IN CACR.g01 (geometry) --- (continued)

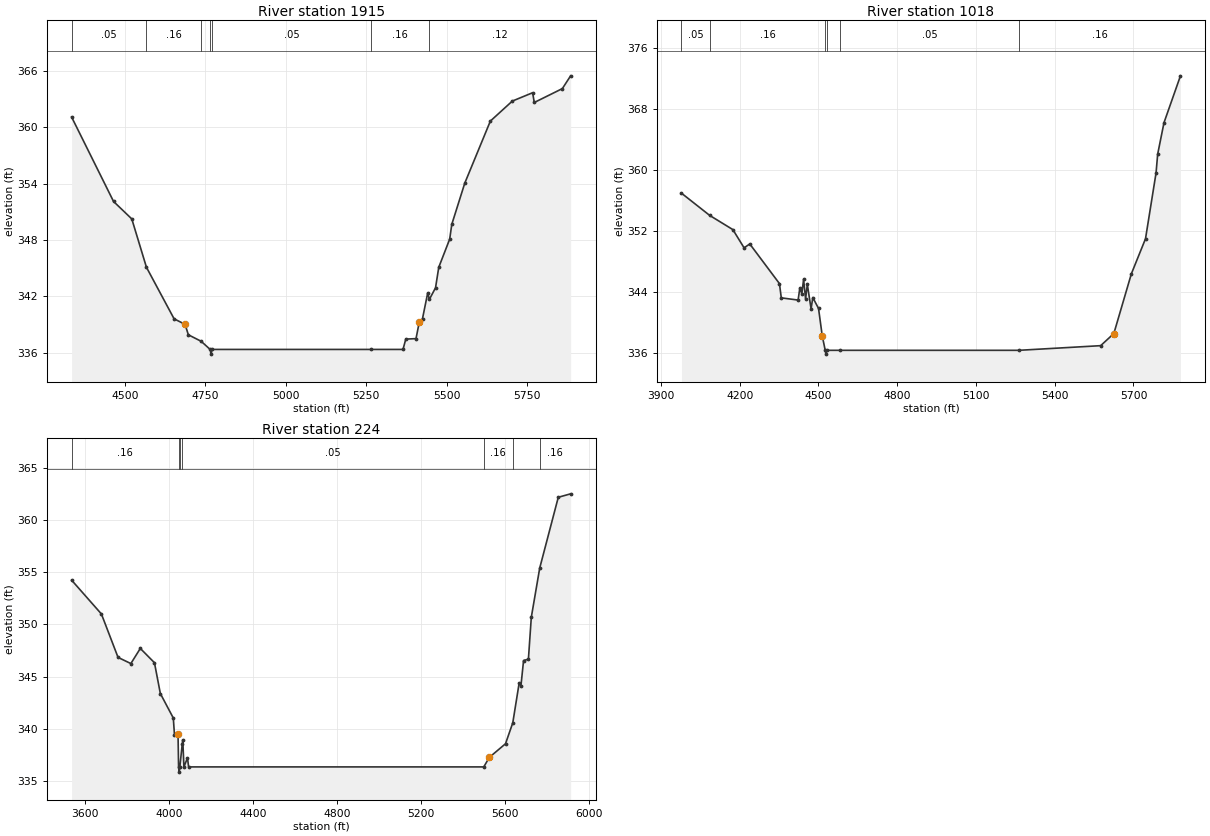
Type RM Length L Ch R = 1 ,1915    ,897,897,897
BEGIN DESCRIPTION:
UNT 036 IN CACR 3.0
END DESCRIPTION:
XS GIS Cut Line= 2
      3678653.25      10759289.1       3678417.2     10757754.75
#Sta/Elev= 30
  4333.7  361.09  4464.1   352.1  4520.9  350.24  4566.5  345.09  4652.5   339.6
  4686.7  339.01  4696.8   337.9  4736.6  337.21  4764.7  336.34  4767.4  335.84
  4770.7  336.34  5264.8  336.34  5364.6  336.34  5373.3  337.44  5405.1  337.49
  5415.2  339.24  5425.3  339.62  5441.6  342.38  5446.6  341.67  5465.8   342.9
  5475.9  345.09  5509.9  348.09  5516.4  349.66  5556.8  354.05  5636.4  360.66
  5704.7  362.79  5767.9  363.68    5773  362.64  5860.4  364.12  5886.1  365.48
#Mann= 7 ,-1 , 0
  4333.7     .05       0  4566.5     .16       0  4736.6     .05       0
  4764.7    .033       0  4770.7     .05       0  5264.8     .16       0
  5446.6     .12       0
Bank Sta=4686.7,5415.2
XS Rating Curve= 0 ,0
Exp/Cntr=0.3,0.1

Type RM Length L Ch R = 1 ,1018    ,794,794,794
BEGIN DESCRIPTION:
UNT 036 IN CACR 2.0
END DESCRIPTION:
XS GIS Cut Line= 3
      3678764.39     10759191.87       3679410.2     10758622.44
      3679306.03     10757587.67
#Sta/Elev= 30
    3978  356.95  4085.7  354.03  4173.9  352.17  4216.6  349.78  4238.3  350.29
  4351.3  345.09  4358.3  343.22  4422.4  342.93  4429.1  344.54  4436.6  343.74
  4443.3  345.66  4450.9  343.08  4457.5  344.99  4471.8  341.78  4478.4  343.26
  4500.2  341.83  4514.4  338.22  4525.7  336.34  4528.4  335.84  4531.7  336.34
  4583.8  336.34  5263.4  336.34    5575  336.95  5625.2  338.54    5692  346.38
  5745.8  350.97    5786   359.6  5792.2  362.07  5816.2  366.19    5879  372.34
#Mann= 6 ,-1 , 0
    3978     .05       0  4085.7     .16       0  4525.7    .033       0
  4531.7     .16       0  4583.8     .05       0  5263.4     .16       0
Bank Sta=4514.4,5625.2
XS Rating Curve= 0 ,0
Exp/Cntr=0.3,0.1

Type RM Length L Ch R = 1 ,224     ,0,0,0
BEGIN DESCRIPTION:
UNT 036 IN CACR 1.0
END DESCRIPTION:
XS GIS Cut Line= 4
      3678930.99     10759219.68      3680146.31     10758622.44
      3680215.76     10758441.89      3679729.64     10757768.27
#Sta/Elev= 30
  3536.2  354.23  3678.2  350.99  3757.5  346.83  3818.6  346.24  3863.6  347.69
    3931  346.32  3959.1  343.37  4020.9  341.02  4026.5  339.39  4043.4  339.47
    4046  336.34  4048.7  335.84    4052  336.34  4063.3  338.49  4065.9  338.94
  4071.5  336.34  4088.4   337.2  4093.9  336.34  5500.6  336.34  5526.9  337.25
  5604.2  338.56  5638.9  340.57  5669.2  344.37  5677.8  344.12  5690.2  346.53
  5713.3  346.66  5727.1  350.67  5767.2  355.39  5855.7  362.17  5914.5   362.5
#Mann= 7 ,-1 , 0
  3536.2     .16       0    4046    .033       0    4052     .16       0
  4063.3     .05       0  5500.6     .16       0  5638.9     .12       0
  5767.2     .16       0
Bank Sta=4043.4,5526.9
XS Rating Curve= 0 ,0
Exp/Cntr=0.3,0.1

Chan Stop Cuts=-1
Use User Specified Reach Order=0
Composite Channel Slope=5