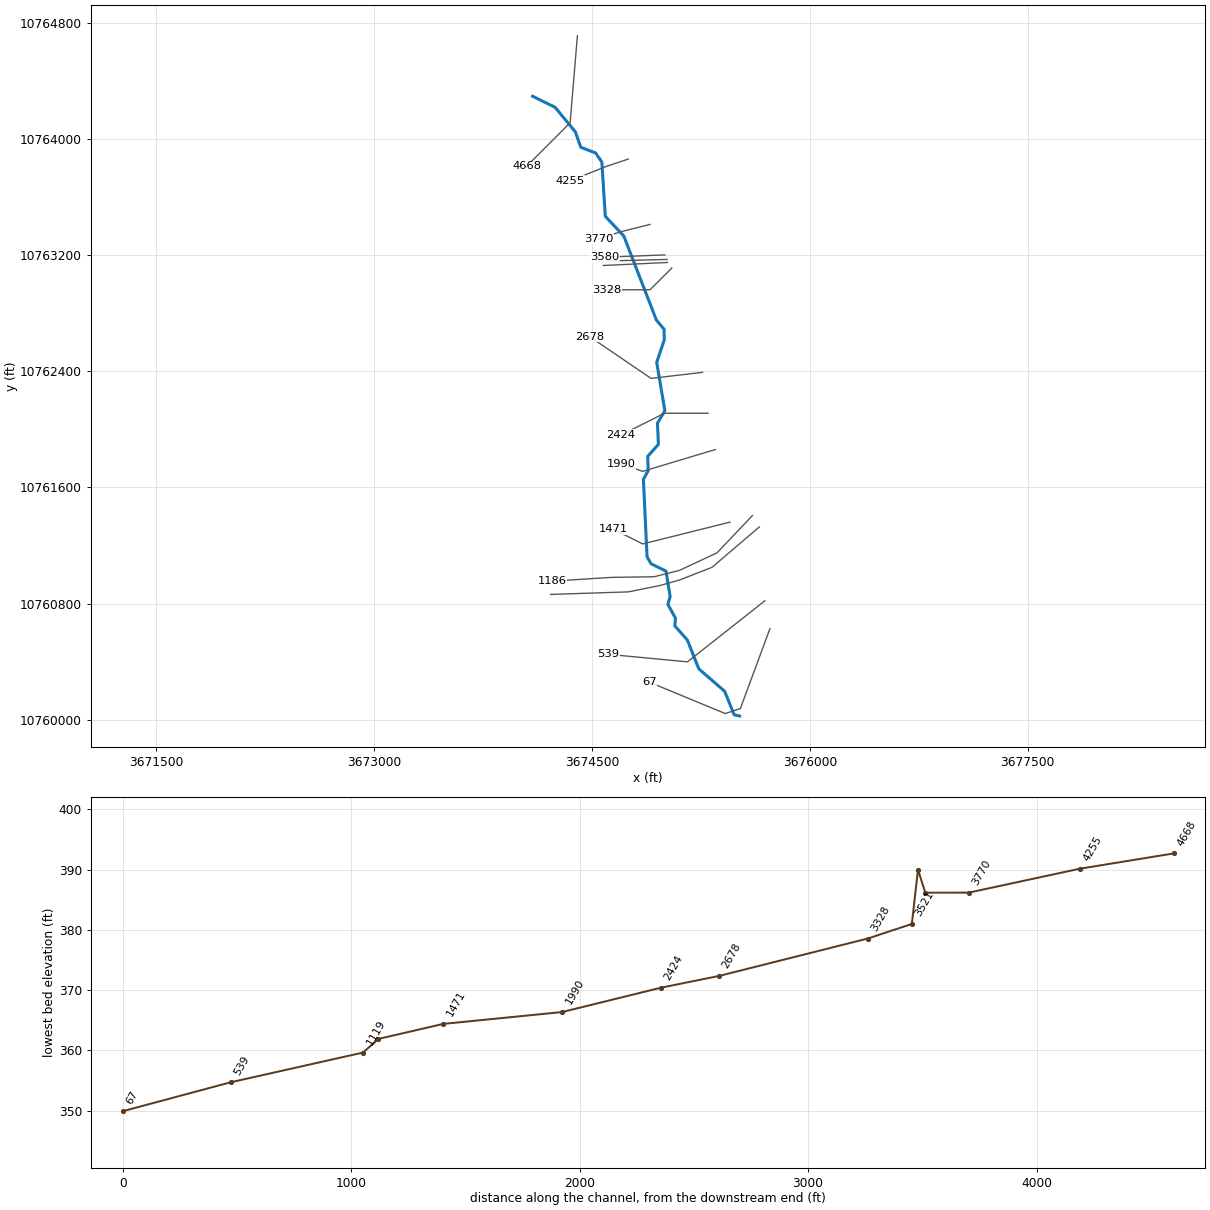
--- UNT 038 IN CACR.prj (project) ---

Proj Title=UNT 038 IN CACR Base Level Engineering
Current Plan=p01
Default Exp/Contr=0.3,0.1
English Units
Geom File=g01
Flow File=f01
Plan File=p01
BEGIN DESCRIPTION:
UNT 038 IN CACR
END DESCRIPTION:

--- UNT 038 IN CACR.p01 (plan) ---

Plan Title=Multiple Run
Short Identifier=Multiple
Geom File=g01
Flow File=f01
Subcritical Flow
K Sum by GR= 0
Std Step Tol= 0.01
Critical Tol= 0.01
Num of Std Step Trials= 20
Max Error Tol= 0.3
Flow Tol Ratio= 0.001
Split Flow NTrial= 30
Split Flow Tol= 0.02
Split Flow Ratio= 0.02
Log Output Level= 0
Friction Slope Method= 1
Unsteady Friction Slope Method= 2
Unsteady Bridges Friction Slope Method= 1
Parabolic Critical Depth
Global Vel Dist=  1 , 1 , 1
Global Log Level= 0
CheckData=True
Encroach Param= -1, 0, 0, 0
BEGIN DESCRIPTION:
Multiple Run
END DESCRIPTION:

--- UNT 038 IN CACR.f01 (steady flow) ---

Flow Title=Multiple
Number of Profiles=7
Profile Names=10-year,25-year,50-year,1pct_min,100-year,1pct_plu,500-year
River Rch & RM= UNT 038 IN CACR,Reach-1,4668
     332     436     519     455     616     832     866
River Rch & RM= UNT 038 IN CACR,Reach-1,2424
     559     759     924     827    1118    1512    1640
Boundary for River Rch & Prof#=UNT 038 IN CACR,Reach-1,1
Up Type=0
Dn Type=3
Dn Slope=0.005
Boundary for River Rch & Prof#=UNT 038 IN CACR,Reach-1,2
Up Type=0
Dn Type=3
Dn Slope=0.005
Boundary for River Rch & Prof#=UNT 038 IN CACR,Reach-1,3
Up Type=0
Dn Type=3
Dn Slope=0.005
Boundary for River Rch & Prof#=UNT 038 IN CACR,Reach-1,4
Up Type=0
Dn Type=3
Dn Slope=0.005
Boundary for River Rch & Prof#=UNT 038 IN CACR,Reach-1,5
Up Type=0
Dn Type=3
Dn Slope=0.005
Boundary for River Rch & Prof#=UNT 038 IN CACR,Reach-1,6
Up Type=0
Dn Type=3
Dn Slope=0.005
Boundary for River Rch & Prof#=UNT 038 IN CACR,Reach-1,7
Up Type=0
Dn Type=3
Dn Slope=0.005

--- UNT 038 IN CACR.g01 (geometry) ---

Geom Title=Existing Conditions

River Reach=UNT 038 IN CACR,Reach-1
Reach XY= 30
      3674091.00     10764293.00      3674245.75     10764217.00
      3674385.50     10764048.00      3674422.50     10763942.00
      3674525.25     10763902.00      3674568.00     10763840.00
      3674591.75     10763466.00      3674718.75     10763331.00
      3674943.50     10762752.00      3674996.00     10762689.00
      3674998.00     10762616.00      3674945.50     10762460.00
      3675002.00     10762128.00      3674950.75     10762041.00
      3674957.50     10761896.00      3674883.75     10761813.00
      3674887.25     10761715.00      3674854.00     10761655.00
      3674879.25     10761122.00      3674906.25     10761074.00
      3675009.75     10761023.00      3675038.25     10760848.00
      3675022.75     10760794.00      3675074.75     10760699.00
      3675070.50     10760646.00      3675156.50     10760549.00
      3675235.75     10760350.00      3675413.25     10760196.00
      3675479.00     10760034.00      3675516.75     10760025.00

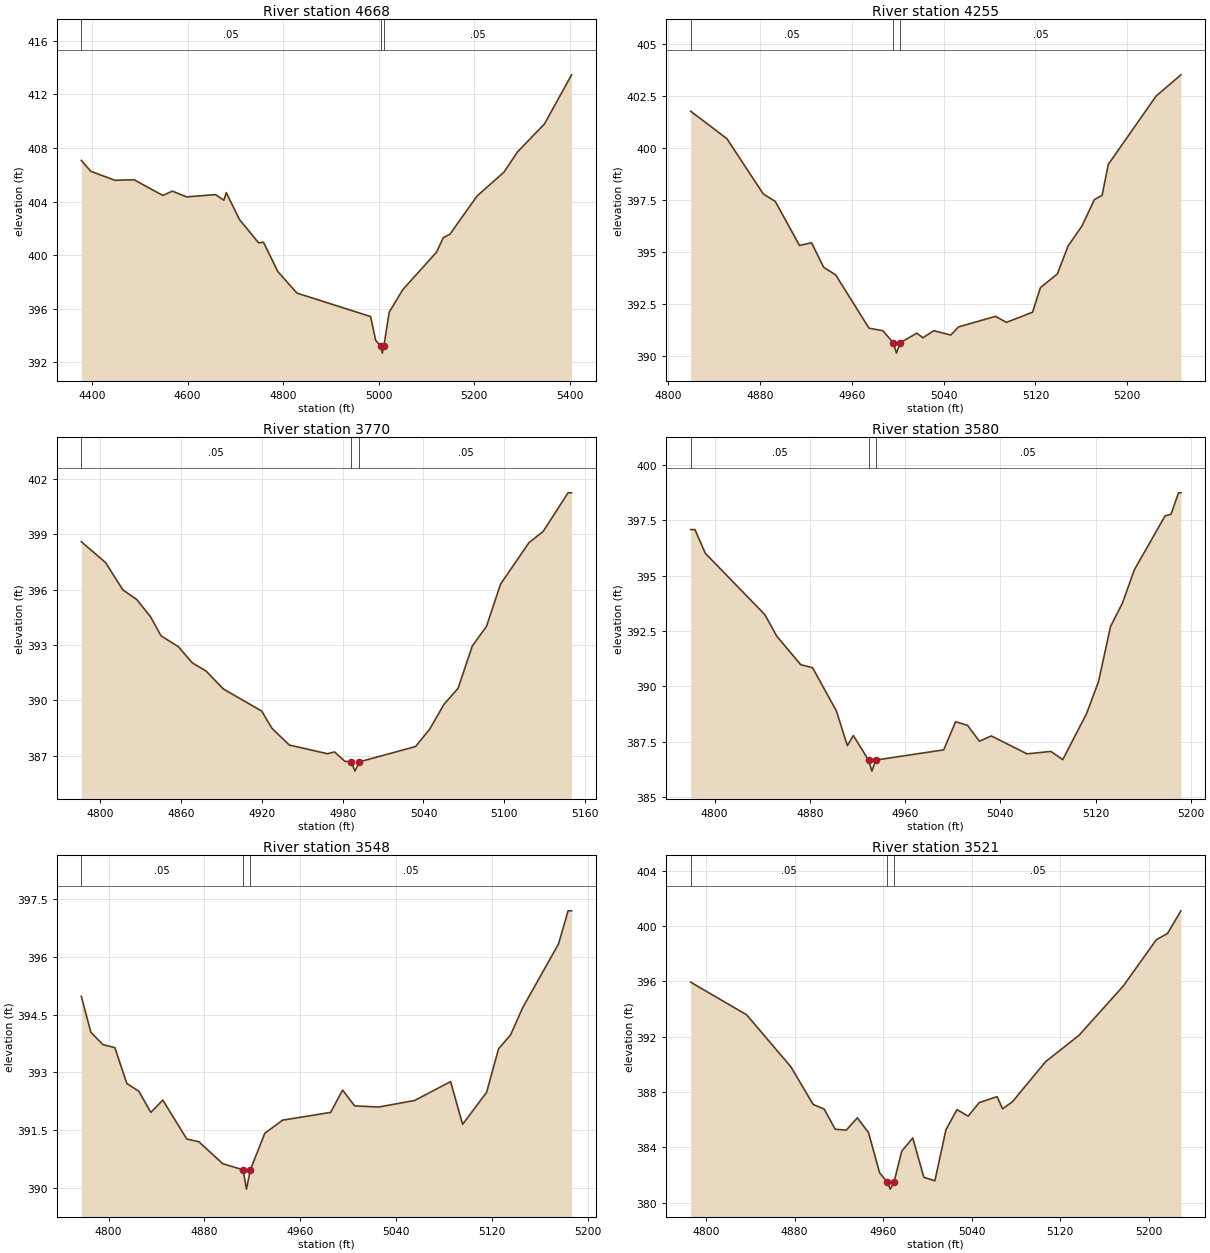
Type RM Length L Ch R = 1,4668,413,413,413
BEGIN DESCRIPTION:
UNT 038 IN CACR 10.0
END DESCRIPTION:
XS GIS Cut Line= 3
      3674399.61     10764710.16      3674349.61     10764110.19
      3674049.62     10763810.20
#Sta/Elev= 30
  4377.6  407.07  4397.6  406.26  4447.8  405.59  4488.0  405.63  4548.2  404.46
  4568.2  404.78  4598.3  404.35  4658.5  404.52  4676.1  404.10  4681.1  404.67
  4708.7  402.66  4748.9  400.92  4758.9  400.97  4789.0  398.78  4829.1  397.17
  4983.2  395.42  4993.8  393.65  5004.9  393.19  5007.7  392.69  5010.9  393.19
  5022.1  395.74  5050.4  397.42  5121.1  400.22  5135.2  401.30  5149.4  401.57
  5205.9  404.41  5262.5  406.20  5290.8  407.71  5347.3  409.80  5403.9  413.46
#Mann=3,-1,0
  4377.6    0.05       0  5004.9    0.03       0  5010.9    0.05       0
Bank Sta=5004.9,5010.9
Exp/Cntr=0.3,0.1

Type RM Length L Ch R = 1,4255,485,485,485
BEGIN DESCRIPTION:
UNT 038 IN CACR 9.0
END DESCRIPTION:
XS GIS Cut Line= 3
      3674749.62     10763860.19      3674599.61     10763810.19
      3674349.59     10763710.18
#Sta/Elev= 30
  4819.4  401.78  4851.0  400.46  4882.7  397.80  4893.2  397.44  4914.3  395.32
  4924.8  395.45  4935.4  394.27  4945.9  393.90  4974.9  391.34  4986.9  391.22
  4996.1  390.64  4998.8  390.14  5002.1  390.64  5016.6  391.10  5021.9  390.88
  5031.4  391.22  5046.2  391.01  5052.9  391.40  5085.2  391.91  5094.7  391.62
  5117.5  392.11  5124.3  393.29  5139.1  393.95  5148.5  395.30  5160.6  396.26
  5171.4  397.53  5178.1  397.73  5183.5  399.22  5225.2  402.51  5246.8  403.53
#Mann=3,-1,0
  4819.4    0.05       0  4996.1    0.03       0  5002.1    0.05       0
Bank Sta=4996.1,5002.1
Exp/Cntr=0.3,0.1

Type RM Length L Ch R = 1,3770,190,190,190
BEGIN DESCRIPTION:
UNT 038 IN CACR 8.0
END DESCRIPTION:
XS GIS Cut Line= 3
      3674899.57     10763410.18      3674699.61     10763360.19
      3674549.64     10763310.20
#Sta/Elev= 30
  4785.8  398.59  4803.8  397.46  4816.7  395.98  4827.0  395.46  4837.3  394.52
  4845.0  393.50  4857.9  392.91  4868.2  392.04  4878.5  391.59  4891.4  390.62
  4919.8  389.43  4927.5  388.49  4940.4  387.59  4968.7  387.12  4973.9  387.22
  4981.6  386.71  4986.3  386.68  4989.1  386.18  4992.3  386.68  5034.1  387.51
  5044.6  388.45  5055.2  389.79  5065.7  390.66  5076.2  392.94  5086.8  394.01
  5097.3  396.30  5118.4  398.54  5128.9  399.14  5147.4  401.23  5150.0  401.23
#Mann=3,-1,0
  4785.8    0.05       0  4986.3    0.03       0  4992.3    0.05       0
Bank Sta=4986.3,4992.3
Exp/Cntr=0.3,0.1

Type RM Length L Ch R = 1,3580,32,32,32
BEGIN DESCRIPTION:
Mapping XS c51a863b
END DESCRIPTION:
XS GIS Cut Line= 2
      3675001.91     10763200.34      3674590.50     10763184.72
#Sta/Elev= 30
  4779.9  397.08  4783.5  397.08  4792.2  396.01  4842.2  393.24  4852.2  392.27
  4872.3  390.98  4882.3  390.84  4902.3  388.89  4911.5  387.32  4916.5  387.78
  4929.3  386.67  4932.1  386.17  4935.3  386.67  4992.4  387.13  5002.4  388.40
  5012.4  388.24  5022.4  387.52  5032.4  387.76  5062.4  386.95  5082.4  387.06
  5092.4  386.69  5112.4  388.77  5122.4  390.21  5132.5  392.70  5142.5  393.76
  5152.5  395.26  5178.3  397.70  5183.3  397.77  5189.6  398.74  5191.6  398.74
#Mann=3,-1,0
  4779.9    0.05       0  4929.3    0.03       0  4935.3    0.05       0
Bank Sta=4929.3,4935.3
Exp/Cntr=0.3,0.1

Type RM Length L Ch R = 1,3548,27,27,27
BEGIN DESCRIPTION:
Mapping XS 28e284dc
END DESCRIPTION:
XS GIS Cut Line= 2
      3675017.58     10763169.09      3674608.72     10763158.67
#Sta/Elev= 30
  4777.3  394.97  4785.3  394.04  4795.3  393.72  4805.3  393.64  4815.3  392.71
  4825.3  392.51  4835.3  391.96  4845.3  392.28  4865.3  391.27  4875.3  391.20
  4895.3  390.63  4912.3  390.47  4915.1  389.97  4918.3  390.47  4930.4  391.42
  4945.3  391.76  4985.3  391.96  4995.3  392.54  5005.3  392.13  5025.4  392.10
  5055.4  392.27  5085.4  392.76  5095.4  391.65  5115.4  392.48  5125.4  393.61
  5135.4  393.97  5145.4  394.67  5175.4  396.33  5183.4  397.19  5186.3  397.19
#Mann=3,-1,0
  4777.3    0.05       0  4912.3    0.03       0  4918.3    0.05       0
Bank Sta=4912.3,4918.3
Exp/Cntr=0.3,0.1

Type RM Length L Ch R = 1,3521,193,193,193
BEGIN DESCRIPTION:
Mapping XS aab17dd4
END DESCRIPTION:
XS GIS Cut Line= 2
      3675020.19     10763148.26      3674577.48     10763127.43
#Sta/Elev= 30
  4786.0  395.95  4836.6  393.59  4876.7  389.82  4896.7  387.11  4906.7  386.77
  4916.7  385.31  4926.7  385.25  4936.7  386.14  4946.8  385.07  4956.8  382.17
  4963.8  381.48  4966.5  380.98  4969.8  381.48  4976.8  383.72  4986.8  384.68
  4996.8  381.84  5006.8  381.58  5016.8  385.28  5026.8  386.73  5036.9  386.26
  5046.9  387.24  5063.0  387.67  5068.0  386.79  5076.9  387.30  5106.9  390.20
  5137.0  392.10  5177.0  395.66  5207.0  399.02  5217.1  399.47  5229.2  401.11
#Mann=3,-1,0
  4786.0    0.05       0  4963.8    0.03       0  4969.8    0.05       0
Bank Sta=4963.8,4969.8
Exp/Cntr=0.3,0.1

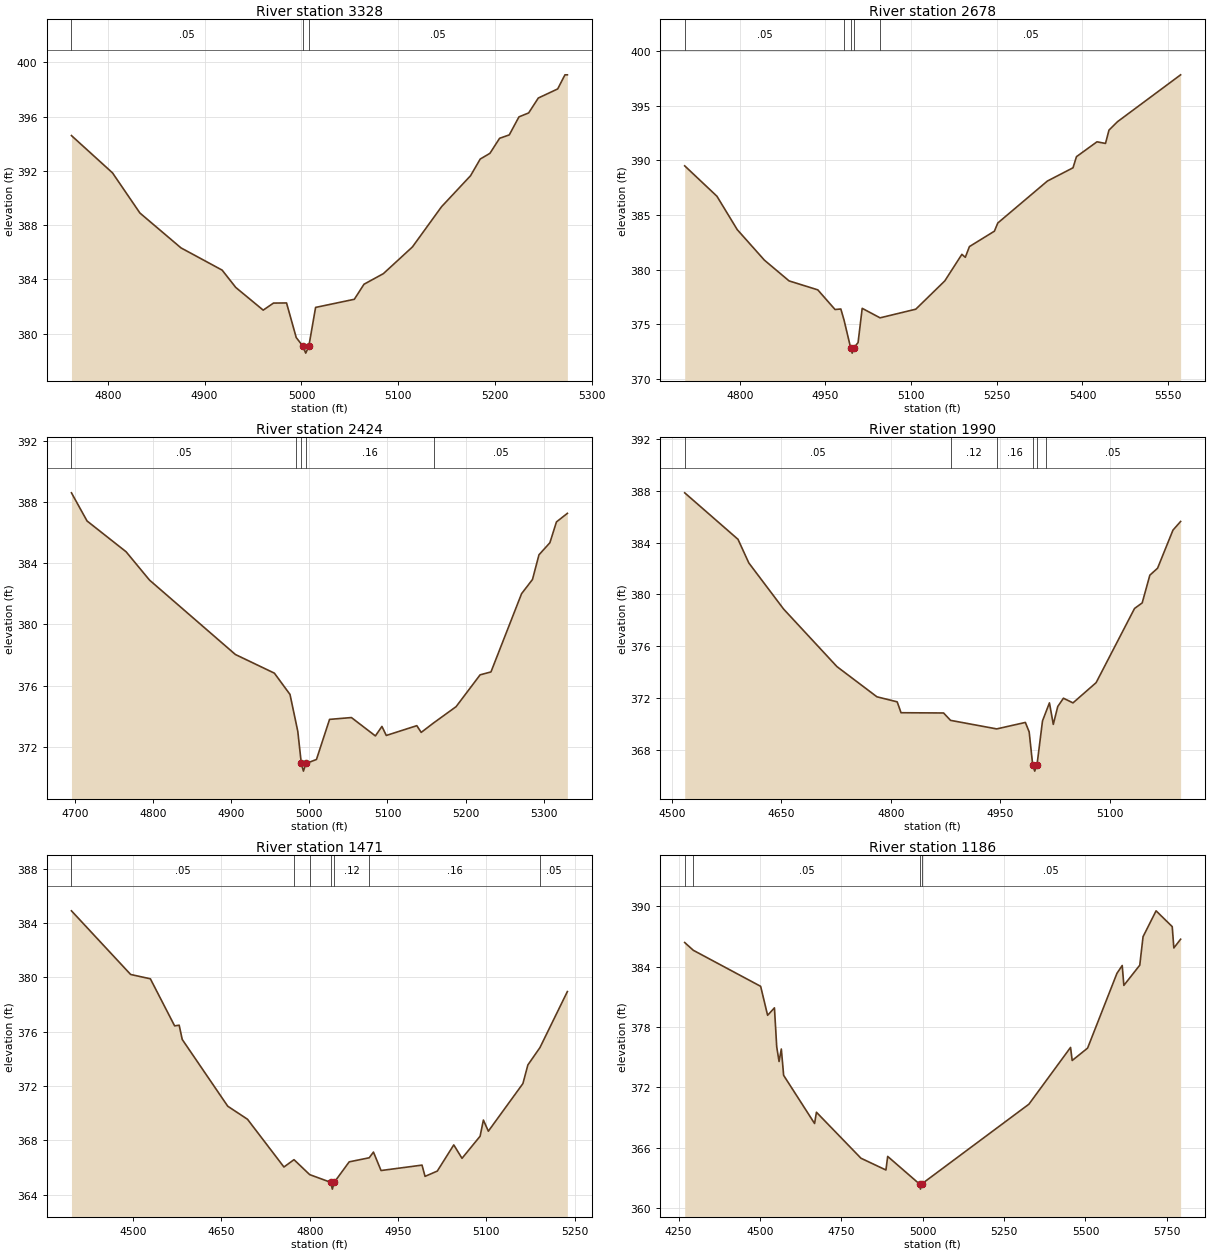
Type RM Length L Ch R = 1,3328,650,650,650
BEGIN DESCRIPTION:
UNT 038 IN CACR 7.0
END DESCRIPTION:
XS GIS Cut Line= 3
      3675049.61     10763110.19      3674899.61     10762960.19
      3674599.64     10762960.19
#Sta/Elev= 30
  4762.5  394.60  4804.9  391.85  4833.2  388.89  4875.6  386.32  4918.1  384.68
  4932.2  383.40  4960.5  381.73  4971.1  382.25  4984.6  382.26  4994.6  379.71
  5001.6  379.06  5004.4  378.56  5007.6  379.06  5014.6  381.93  5054.6  382.53
  5064.6  383.64  5084.6  384.42  5114.6  386.39  5144.6  389.35  5174.6  391.64
  5184.6  392.87  5194.6  393.29  5204.6  394.40  5214.6  394.65  5224.6  395.98
  5234.6  396.27  5244.6  397.37  5264.6  398.04  5272.1  399.08  5274.6  399.08
#Mann=3,-1,0
  4762.5    0.05       0  5001.6    0.03       0  5007.6    0.05       0
Bank Sta=5001.6,5007.6
Exp/Cntr=0.3,0.1

Type RM Length L Ch R = 1,2678,254,254,254
BEGIN DESCRIPTION:
UNT 038 IN CACR 6.0
END DESCRIPTION:
XS GIS Cut Line= 3
      3675261.01     10762391.74      3674906.89     10762350.08
      3674483.96     10762637.82
#Sta/Elev= 30
  4703.7  389.50  4760.1  386.72  4795.7  383.66  4843.2  380.87  4886.4  378.97
  4936.7  378.15  4966.9  376.35  4977.0  376.40  4982.6  375.39  4994.1  372.86
  4996.9  372.36  5000.1  372.86  5007.2  373.33  5014.4  376.46  5045.7  375.59
  5108.2  376.38  5159.0  378.97  5188.9  381.40  5194.9  381.13  5202.1  382.11
  5245.8  383.52  5251.8  384.27  5338.6  388.11  5383.4  389.32  5389.5  390.34
  5425.4  391.70  5440.3  391.55  5446.4  392.77  5461.3  393.54  5571.8  397.83
#Mann=5,-1,0
  4703.7    0.05       0  4982.6    0.16       0  4994.1    0.07       0
  5000.1    0.16       0  5045.7    0.05       0
Bank Sta=4994.1,5000.1
Exp/Cntr=0.3,0.1

Type RM Length L Ch R = 1,2424,434,434,434
BEGIN DESCRIPTION:
UNT 038 IN CACR 5.0
END DESCRIPTION:
XS GIS Cut Line= 3
      3675299.57     10762110.19      3674999.61     10762110.19
      3674699.59     10761960.18
#Sta/Elev= 30
  4695.1  388.59  4715.1  386.75  4765.1  384.74  4795.1  382.89  4905.1  378.03
  4955.1  376.81  4975.1  375.42  4982.2  373.71  4985.1  373.01  4989.6  370.91
  4992.3  370.41  4995.6  370.91  5009.0  371.17  5025.8  373.79  5053.8  373.91
  5084.5  372.71  5092.9  373.33  5098.5  372.74  5137.6  373.38  5143.2  372.94
  5159.4  373.57  5187.9  374.62  5218.7  376.70  5232.6  376.89  5271.8  382.00
  5285.8  382.93  5294.1  384.54  5308.1  385.33  5316.5  386.69  5330.5  387.25
#Mann=5,-1,0
  4695.1    0.05       0  4982.2    0.16       0  4989.6    0.07       0
  4995.6    0.16       0  5159.4    0.05       0
Bank Sta=4989.6,4995.6
Exp/Cntr=0.3,0.1

Type RM Length L Ch R = 1,1990,519,519,519
BEGIN DESCRIPTION:
UNT 038 IN CACR 4.0
END DESCRIPTION:
XS GIS Cut Line= 3
      3675349.59     10761860.18      3674849.61     10761710.19
      3674699.62     10761760.18
#Sta/Elev= 30
  4517.3  387.85  4590.4  384.26  4605.2  382.44  4653.0  378.87  4726.1  374.43
  4780.9  372.10  4808.7  371.71  4814.0  370.87  4872.3  370.85  4881.9  370.28
  4945.2  369.62  4984.5  370.12  4989.7  369.39  4994.5  366.86  4997.3  366.36
  5000.5  366.86  5008.0  370.24  5012.5  370.90  5017.5  371.63  5022.8  369.97
  5028.9  371.35  5036.7  371.99  5049.8  371.63  5081.5  373.19  5134.2  378.92
  5144.7  379.35  5155.2  381.49  5165.8  382.03  5186.9  384.97  5197.4  385.64
#Mann=6,-1,0
  4517.3    0.05       0  4881.9    0.12       0  4945.2    0.16       0
  4994.5    0.07       0  5000.5    0.16       0  5012.5    0.05       0
Bank Sta=4994.5,5000.5
Exp/Cntr=0.3,0.1

Type RM Length L Ch R = 1,1471,285,285,285
BEGIN DESCRIPTION:
UNT 038 IN CACR 3.0
END DESCRIPTION:
XS GIS Cut Line= 3
      3675449.60     10761360.19      3674849.61     10761210.19
      3674649.57     10761310.21
#Sta/Elev= 30
  4395.4  384.91  4495.9  380.22  4529.4  379.90  4570.6  376.43  4578.3  376.48
  4583.5  375.43  4660.8  370.51  4694.3  369.55  4756.2  366.03  4773.3  366.57
  4799.9  365.47  4835.6  364.90  4838.4  364.40  4841.6  364.90  4867.0  366.41
  4901.0  366.71  4908.2  367.13  4921.1  365.77  4990.7  366.17  4995.8  365.34
  5016.6  365.73  5044.6  367.66  5058.6  366.67  5089.3  368.30  5094.9  369.49
  5103.3  368.67  5162.0  372.18  5170.4  373.55  5190.9  374.83  5237.5  378.96
#Mann=7,-1,0
  4395.4    0.05       0  4773.3    0.16       0  4799.9    0.12       0
  4835.6    0.07       0  4841.6    0.12       0  4901.0    0.16       0
  5190.9    0.05       0
Bank Sta=4835.6,4841.6
Exp/Cntr=0.3,0.1

Type RM Length L Ch R = 1,1186,67,67,67
BEGIN DESCRIPTION:
Mapping XS 6ae0d666
END DESCRIPTION:
XS GIS Cut Line= 6
      3675604.39     10761405.22      3675361.32     10761149.13
      3675100.90     10761027.60      3674927.29     10760984.20
      3674632.15     10760979.86      3674224.41     10760953.83
#Sta/Elev= 30
  4268.9  386.40  4295.3  385.63  4502.2  382.05  4523.6  379.17  4544.6  379.91
  4551.6  376.03  4558.8  374.58  4565.7  375.82  4572.9  373.20  4667.9  368.42
  4673.6  369.54  4810.4  364.97  4887.1  363.80  4892.5  365.15  4990.5  362.40
  4993.2  361.90  4996.5  362.40  5326.4  370.34  5454.3  375.98  5459.3  374.68
  5506.6  375.91  5596.8  383.34  5613.0  384.12  5618.0  382.14  5666.9  384.15
  5677.0  386.98  5717.0  389.55  5766.6  387.98  5771.6  385.86  5792.4  386.73
#Mann=4,-1,0
  4268.9    0.08       0  4295.3    0.05       0  4990.5    0.04       0
  4996.5    0.05       0
Bank Sta=4990.5,4996.5
Exp/Cntr=0.3,0.1

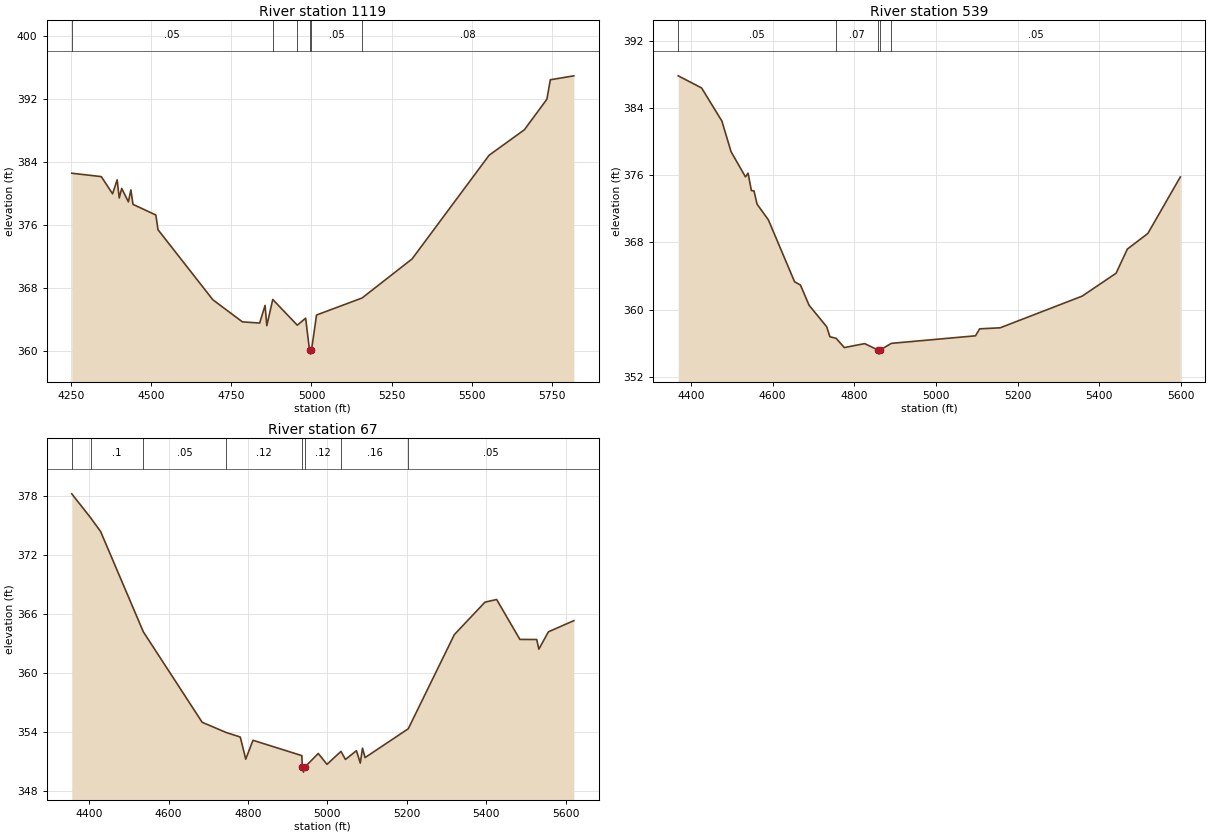
Type RM Length L Ch R = 1,1119,580,580,580
BEGIN DESCRIPTION:
Mapping XS 68f4bf30
END DESCRIPTION:
XS GIS Cut Line= 6
      3675652.13     10761327.08      3675326.60     10761049.30
      3675105.25     10760962.49      3674966.36     10760923.43
      3674749.34     10760880.03      3674215.52     10760862.67
#Sta/Elev= 30
  4252.7  382.58  4344.8  382.15  4379.9  379.97  4394.2  381.74  4400.7  379.44
  4408.4  380.65  4429.3  378.95  4437.0  380.47  4443.6  378.63  4514.9  377.28
  4521.5  375.42  4692.7  366.53  4784.8  363.73  4838.5  363.58  4855.4  365.82
  4860.8  363.25  4879.4  366.57  4955.9  363.31  4981.9  364.20  4994.0  360.14
  4996.7  359.64  5000.0  360.14  5015.9  364.60  5157.9  366.76  5313.7  371.71
  5553.9  384.86  5663.9  388.09  5734.0  391.96  5744.8  394.43  5818.1  394.93
#Mann=6,-1,0
  4252.7    0.05       0  4879.4    0.08       0  4955.9    0.05       0
  4994.0    0.04       0  5000.0    0.05       0  5157.9    0.08       0
Bank Sta=4994,5000
Exp/Cntr=0.3,0.1

Type RM Length L Ch R = 1,539,472,472,472
BEGIN DESCRIPTION:
UNT 038 IN CACR 2.0
END DESCRIPTION:
XS GIS Cut Line= 3
      3675691.17     10760819.26      3675157.33     10760398.26
      3674610.48     10760450.34
#Sta/Elev= 30
  4369.2  387.80  4426.4  386.36  4476.1  382.42  4498.5  378.78  4533.8  375.78
  4540.2  376.22  4548.3  374.15  4554.6  374.12  4562.2  372.54  4589.9  370.67
  4654.0  363.31  4668.5  362.91  4689.6  360.51  4732.6  357.96  4740.5  356.77
  4755.8  356.58  4775.9  355.48  4825.6  355.95  4857.9  355.20  4860.6  354.70
  4863.9  355.20  4890.8  355.98  5097.0  356.88  5107.1  357.71  5157.3  357.83
  5358.2  361.60  5441.1  364.32  5468.7  367.19  5518.9  369.05  5598.4  375.77
#Mann=5,-1,0
  4369.2    0.05       0  4755.8    0.07       0  4857.9    0.03       0
  4863.9    0.07       0  4890.8    0.05       0
Bank Sta=4857.9,4863.9
Exp/Cntr=0.3,0.1

Type RM Length L Ch R = 1,67,0,0,0
BEGIN DESCRIPTION:
UNT 038 IN CACR 1.0
END DESCRIPTION:
XS GIS Cut Line= 4
      3675725.90     10760628.27      3675521.91     10760077.08
      3675417.75     10760042.36      3674893.56     10760258.96
#Sta/Elev= 30
  4356.2  378.21  4403.4  375.79  4428.8  374.38  4536.5  364.17  4684.7  354.97
  4745.3  353.93  4780.7  353.47  4794.4  351.22  4812.7  353.14  4935.7  351.58
  4937.0  350.40  4939.8  349.90  4943.0  350.40  4977.1  351.80  4999.1  350.69
  5034.3  352.01  5045.6  351.19  5073.3  352.08  5083.0  350.82  5088.5  352.34
  5095.0  351.38  5203.8  354.31  5319.9  363.89  5397.0  367.19  5426.4  367.46
  5485.0  363.40  5527.4  363.39  5532.8  362.41  5556.8  364.17  5620.9  365.31
#Mann=8,-1,0
  4356.2    0.05       0  4403.4     0.1       0  4536.5    0.05       0
  4745.3    0.12       0  4937.0    0.07       0  4943.0    0.12       0
  5034.3    0.16       0  5203.8    0.05       0
Bank Sta=4937,4943
Exp/Cntr=0.3,0.1

Chan Stop Cuts=-1