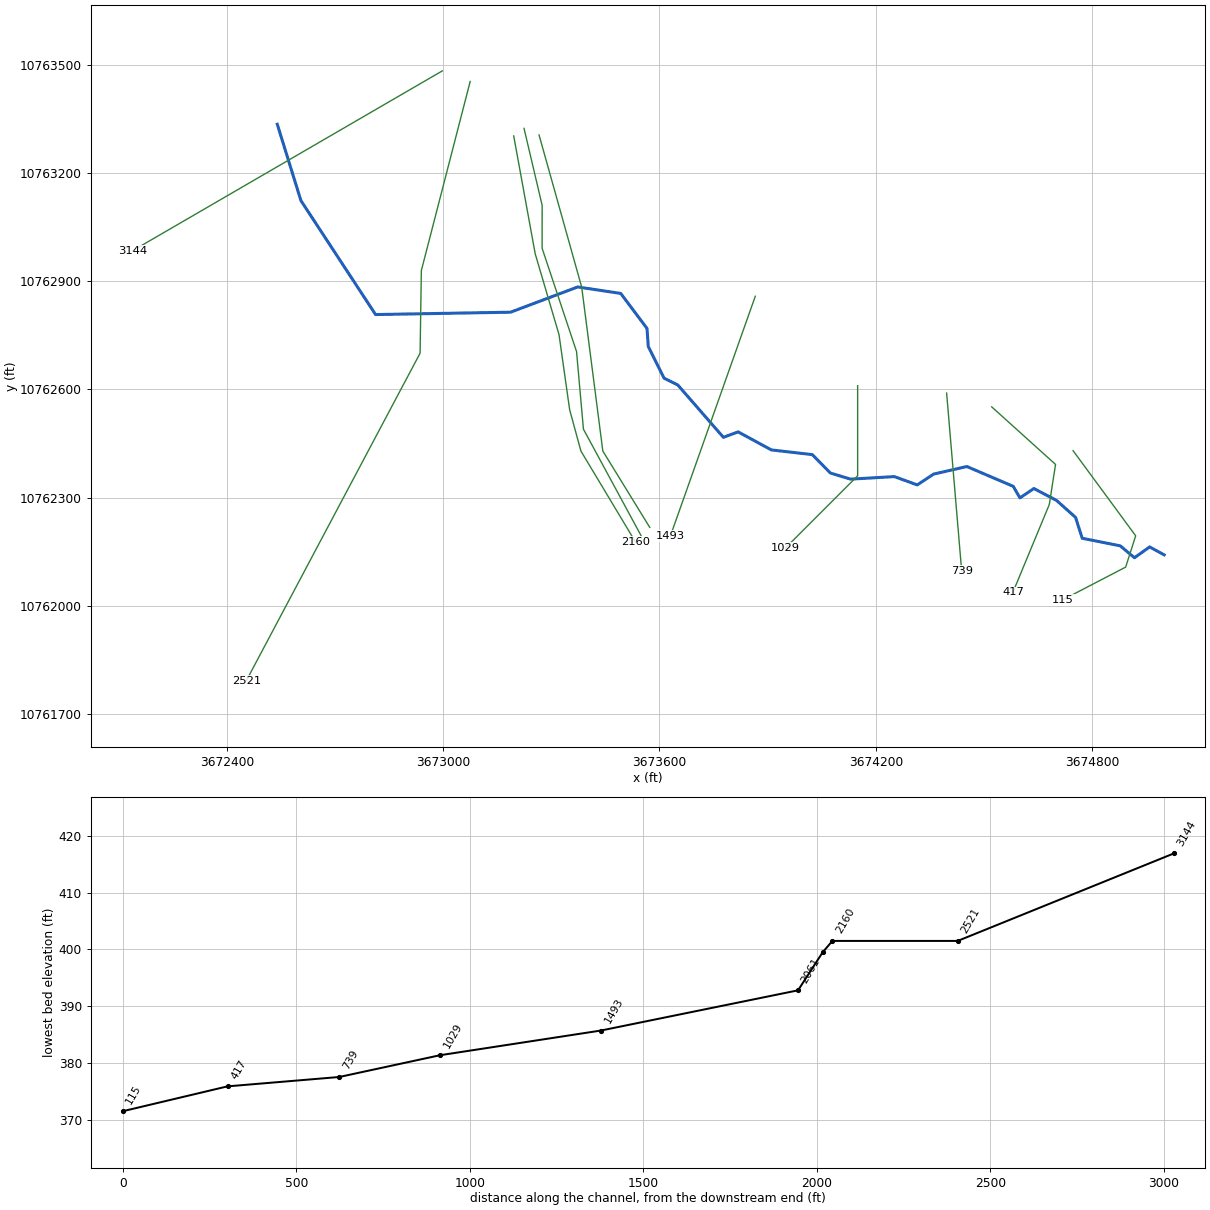
--- UNT 039 IN CACR.prj (project) ---

Proj Title=UNT 039 IN CACR Base Level Engineering
Current Plan=p01
Default Exp/Contr=0.3,0.1
English Units
Geom File=g01
Flow File=f01
Plan File=p01
BEGIN DESCRIPTION:
UNT 039 IN CACR
END DESCRIPTION:

--- UNT 039 IN CACR.p01 (plan) ---

Plan Title=Multiple Run
Short Identifier=Multiple
Geom File=g01
Flow File=f01
Subcritical Flow
K Sum by GR= 0
Std Step Tol= 0.01
Critical Tol= 0.01
Num of Std Step Trials= 20
Max Error Tol= 0.3
Flow Tol Ratio= 0.001
Split Flow NTrial= 30
Split Flow Tol= 0.02
Split Flow Ratio= 0.02
Log Output Level= 0
Friction Slope Method= 1
Unsteady Friction Slope Method= 2
Unsteady Bridges Friction Slope Method= 1
Parabolic Critical Depth
Global Vel Dist=  1 , 1 , 1
Global Log Level= 0
CheckData=True
Encroach Param= -1, 0, 0, 0
BEGIN DESCRIPTION:
Multiple Run
END DESCRIPTION:

--- UNT 039 IN CACR.f01 (steady flow) ---

Flow Title=Multiple
Number of Profiles=7
Profile Names=10-year,25-year,50-year,1pct_min,100-year,1pct_plu,500-year
River Rch & RM= UNT 039 IN CACR,Reach-1,3144
     245     317     374     325     440     595     608
Boundary for River Rch & Prof#=UNT 039 IN CACR,Reach-1,1
Up Type=0
Dn Type=3
Dn Slope=0.005
Boundary for River Rch & Prof#=UNT 039 IN CACR,Reach-1,2
Up Type=0
Dn Type=3
Dn Slope=0.005
Boundary for River Rch & Prof#=UNT 039 IN CACR,Reach-1,3
Up Type=0
Dn Type=3
Dn Slope=0.005
Boundary for River Rch & Prof#=UNT 039 IN CACR,Reach-1,4
Up Type=0
Dn Type=3
Dn Slope=0.005
Boundary for River Rch & Prof#=UNT 039 IN CACR,Reach-1,5
Up Type=0
Dn Type=3
Dn Slope=0.005
Boundary for River Rch & Prof#=UNT 039 IN CACR,Reach-1,6
Up Type=0
Dn Type=3
Dn Slope=0.005
Boundary for River Rch & Prof#=UNT 039 IN CACR,Reach-1,7
Up Type=0
Dn Type=3
Dn Slope=0.005

--- UNT 039 IN CACR.g01 (geometry) ---

Geom Title=Existing Conditions

River Reach=UNT 039 IN CACR,Reach-1
Reach XY= 30
      3672540.10     10763335.22      3672605.71     10763123.40
      3672812.67     10762807.44      3673187.25     10762814.00
      3673373.25     10762884.00      3673492.75     10762866.00
      3673565.50     10762769.00      3673569.00     10762719.00
      3673612.75     10762631.00      3673651.00     10762612.00
      3673777.25     10762467.00      3673818.25     10762482.00
      3673910.50     10762432.00      3674024.00     10762419.00
      3674074.00     10762368.00      3674130.00     10762351.00
      3674251.50     10762358.00      3674315.00     10762335.00
      3674360.50     10762365.00      3674452.50     10762386.00
      3674581.25     10762331.00      3674599.75     10762299.00
      3674638.50     10762325.00      3674701.25     10762292.00
      3674754.00     10762245.00      3674772.50     10762187.00
      3674878.00     10762166.00      3674917.50     10762133.00
      3674959.50     10762163.00      3674999.75     10762141.00

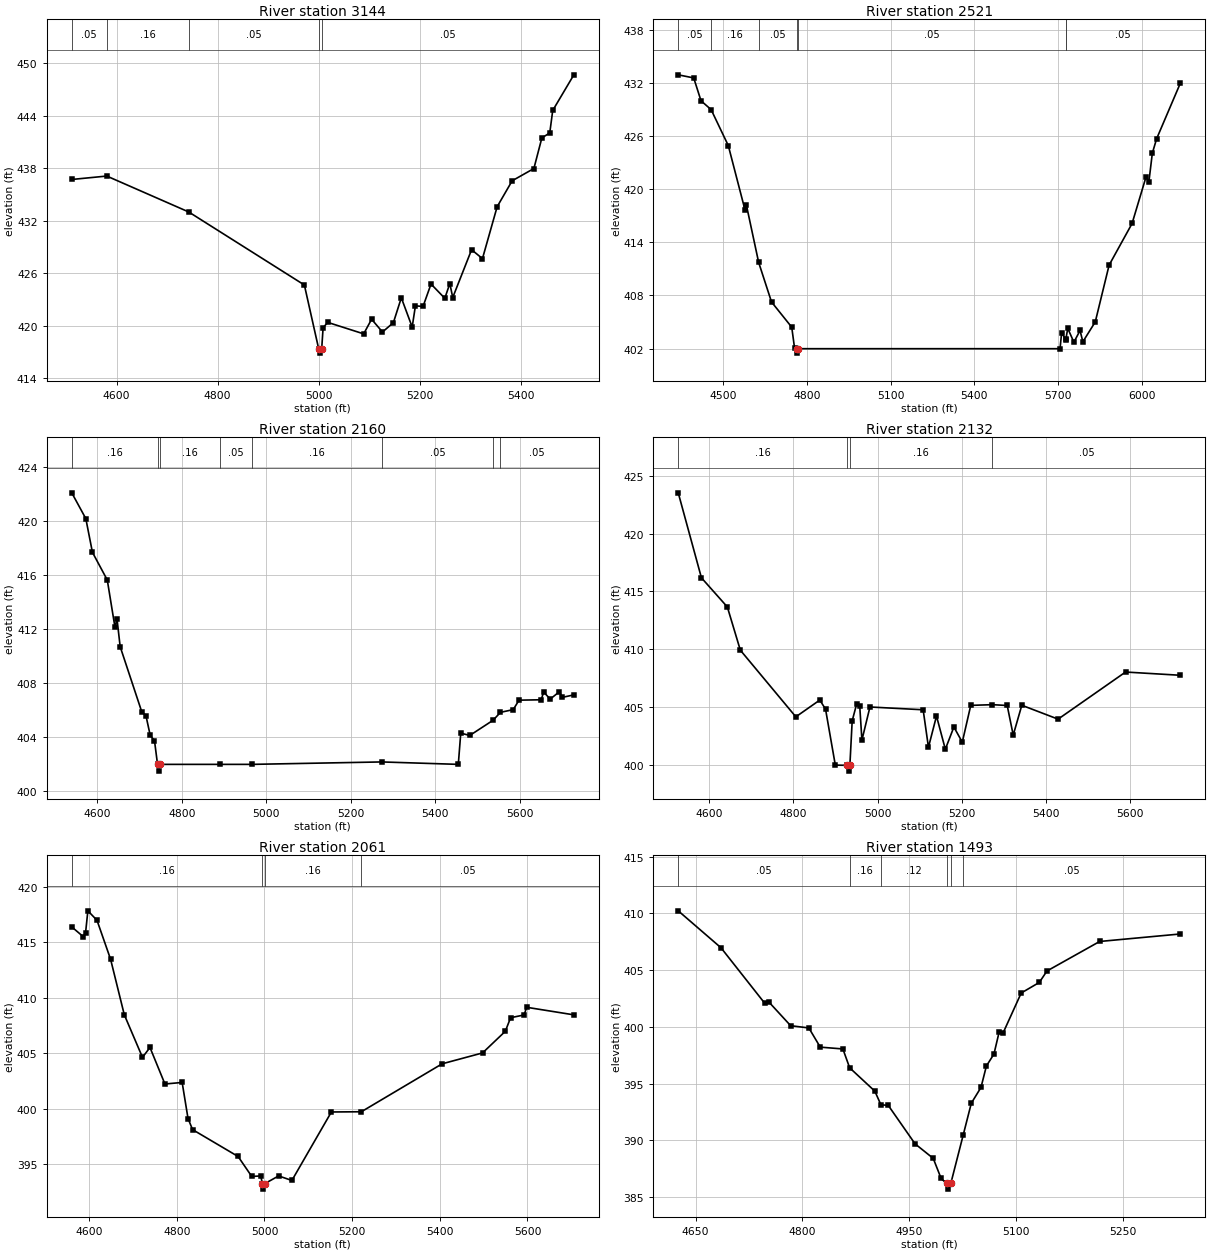
Type RM Length L Ch R = 1,3144,623,623,623
BEGIN DESCRIPTION:
UNT 039 IN CACR 6.0
END DESCRIPTION:
XS GIS Cut Line= 2
      3672997.80     10763483.26      3672138.37     10762984.24
#Sta/Elev= 30
  4511.2  436.72  4580.5  437.11  4742.7  433.01  4971.6  424.67  4999.9  417.39
  5002.6  416.89  5005.9  417.39  5008.7  419.80  5017.9  420.40  5089.0  419.09
  5104.7  420.76  5126.2  419.30  5147.8  420.37  5163.5  423.21  5185.0  419.87
  5191.4  422.29  5206.5  422.22  5222.3  424.78  5249.6  423.15  5259.5  424.84
  5265.3  423.24  5302.6  428.70  5324.1  427.68  5353.2  433.61  5382.9  436.57
  5425.9  437.97  5441.7  441.47  5457.3  442.03  5463.2  444.60  5505.0  448.67
#Mann=5,-1,0
  4511.2    0.05       0  4580.5    0.16       0  4742.7    0.05       0
  4999.9    0.03       0  5005.9    0.05       0
Bank Sta=4999.9,5005.9
Exp/Cntr=0.3,0.1

Type RM Length L Ch R = 1,2521,361,361,361
BEGIN DESCRIPTION:
Mapping XS a23d77d0
END DESCRIPTION:
XS GIS Cut Line= 4
      3673075.10     10763453.91      3672939.67     10762929.56
      3672936.19     10762700.39      3672454.06     10761791.62
#Sta/Elev= 30
  4338.5  432.91  4394.0  432.56  4420.1  429.98  4456.4  428.98  4517.9  424.92
  4577.6  417.67  4582.7  418.21  4626.7  411.73  4672.8  407.26  4745.3  404.41
  4755.5  402.03  4762.8  401.98  4765.6  401.48  4768.8  401.98  5706.9  401.98
  5712.6  403.77  5727.1  403.04  5727.5  402.99  5734.6  404.28  5756.6  402.71
  5778.6  404.04  5788.7  402.76  5833.2  405.01  5882.8  411.42  5965.1  416.12
  6015.1  421.38  6025.5  420.86  6037.7  424.06  6053.1  425.69  6138.0  431.96
#Mann=7,-1,0
  4338.5    0.05       0  4456.4    0.16       0  4626.7    0.05       0
  4762.8   0.033       0  4768.8    0.05       0  5727.1    0.12       0
  5727.5    0.05       0
Bank Sta=4762.8,4768.8
Exp/Cntr=0.3,0.1

Type RM Length L Ch R = 1,2160,28,28,28
BEGIN DESCRIPTION:
UNT 039 IN CACR 5.0
END DESCRIPTION:
XS GIS Cut Line= 6
      3673195.78     10763302.95      3673255.49     10762975.71
      3673321.47     10762751.75      3673350.98     10762543.42
      3673382.23     10762428.84      3673533.29     10762177.08
#Sta/Elev= 30
  4539.7  422.07  4573.0  420.16  4588.6  417.67  4623.8  415.62  4641.8  412.16
  4646.9  412.71  4654.3  410.69  4705.3  405.88  4715.3  405.59  4725.5  404.12
  4735.6  403.73  4742.8  401.98  4745.6  401.48  4748.8  401.98  4890.8  401.98
  4966.7  401.98  5273.9  402.16  5455.0  401.98  5460.8  404.29  5482.2  404.12
  5537.2  405.24  5554.9  405.83  5585.0  406.03  5598.8  406.73  5651.3  406.76
  5657.1  407.33  5672.7  406.81  5694.1  407.35  5701.6  406.94  5728.6  407.12
#Mann=8,-1,0
  4539.7    0.16       0  4742.8    0.07       0  4748.8    0.16       0
  4890.8    0.05       0  4966.7    0.16       0  5273.9    0.05       0
  5537.2    0.16       0  5554.9    0.05       0
Bank Sta=4742.8,4748.8
Exp/Cntr=0.3,0.1

Type RM Length L Ch R = 1,2132,71,71,71
BEGIN DESCRIPTION:
Mapping XS 80665d90
END DESCRIPTION:
XS GIS Cut Line= 6
      3673224.43     10763323.80      3673274.68     10763110.23
      3673274.59     10762991.34      3673370.08     10762704.88
      3673389.17     10762489.60      3673548.71     10762194.80
#Sta/Elev= 30
  4526.4  423.52  4581.5  416.18  4643.1  413.66  4673.9  409.93  4805.8  404.17
  4862.8  405.62  4876.4  404.83  4899.6  400.00  4928.2  399.98  4931.0  399.48
  4934.2  399.98  4939.7  403.83  4950.2  405.26  4957.6  405.12  4962.8  402.16
  4981.9  405.02  5108.3  404.78  5120.9  401.54  5140.0  404.24  5161.0  401.37
  5181.3  403.29  5201.3  401.98  5221.4  405.16  5272.8  405.22  5308.0  405.15
  5322.3  402.59  5342.7  405.17  5428.9  403.97  5589.2  408.04  5719.3  407.76
#Mann=4,-1,0
  4526.4    0.16       0  4928.2    0.07       0  4934.2    0.16       0
  5272.8    0.05       0
Bank Sta=4928.2,4934.2
Exp/Cntr=0.3,0.1

Type RM Length L Ch R = 1,2061,568,568,568
BEGIN DESCRIPTION:
UNT 039 IN CACR 4.0
END DESCRIPTION:
XS GIS Cut Line= 4
      3673266.10     10763305.54      3673384.40     10762883.26
      3673442.99     10762428.84      3673573.18     10762217.07
#Sta/Elev= 30
  4560.5  416.40  4586.8  415.52  4592.0  415.88  4597.2  417.85  4618.0  417.00
  4649.1  413.48  4680.3  408.49  4721.8  404.65  4738.9  405.54  4773.0  402.25
  4812.3  402.39  4825.7  399.14  4836.1  398.14  4939.9  395.72  4971.1  393.92
  4991.8  393.97  4995.0  393.28  4997.8  392.78  5001.0  393.28  5032.4  393.97
  5062.6  393.56  5152.7  399.73  5221.1  399.75  5405.4  404.07  5497.6  405.05
  5549.5  407.00  5561.5  408.22  5592.3  408.47  5598.2  409.16  5705.8  408.48
#Mann=4,-1,0
  4560.5    0.16       0  4995.0    0.07       0  5001.0    0.16       0
  5221.1    0.05       0
Bank Sta=4995,5001
Exp/Cntr=0.3,0.1

Type RM Length L Ch R = 1,1493,464,464,464
BEGIN DESCRIPTION:
UNT 039 IN CACR 3.0
END DESCRIPTION:
XS GIS Cut Line= 2
      3673865.84     10762858.26      3673630.38     10762193.43
#Sta/Elev= 30
  4625.7  410.22  4685.7  406.97  4747.4  402.06  4752.7  402.21  4783.6  400.10
  4809.2  399.90  4825.2  398.21  4857.0  398.05  4866.5  396.39  4901.9  394.33
  4910.4  393.13  4920.7  393.08  4958.4  389.69  4983.9  388.41  4995.0  386.64
  5002.6  386.20  5005.3  385.70  5008.6  386.20  5026.1  390.49  5037.4  393.27
  5051.0  394.66  5058.6  396.55  5069.2  397.60  5076.6  399.57  5081.9  399.44
  5107.5  402.98  5132.9  403.91  5143.7  404.92  5217.7  407.52  5331.0  408.18
#Mann=6,-1,0
  4625.7    0.05       0  4866.5    0.16       0  4910.4    0.12       0
  5002.6    0.07       0  5008.6    0.12       0  5026.1    0.05       0
Bank Sta=5002.6,5008.6
Exp/Cntr=0.3,0.1

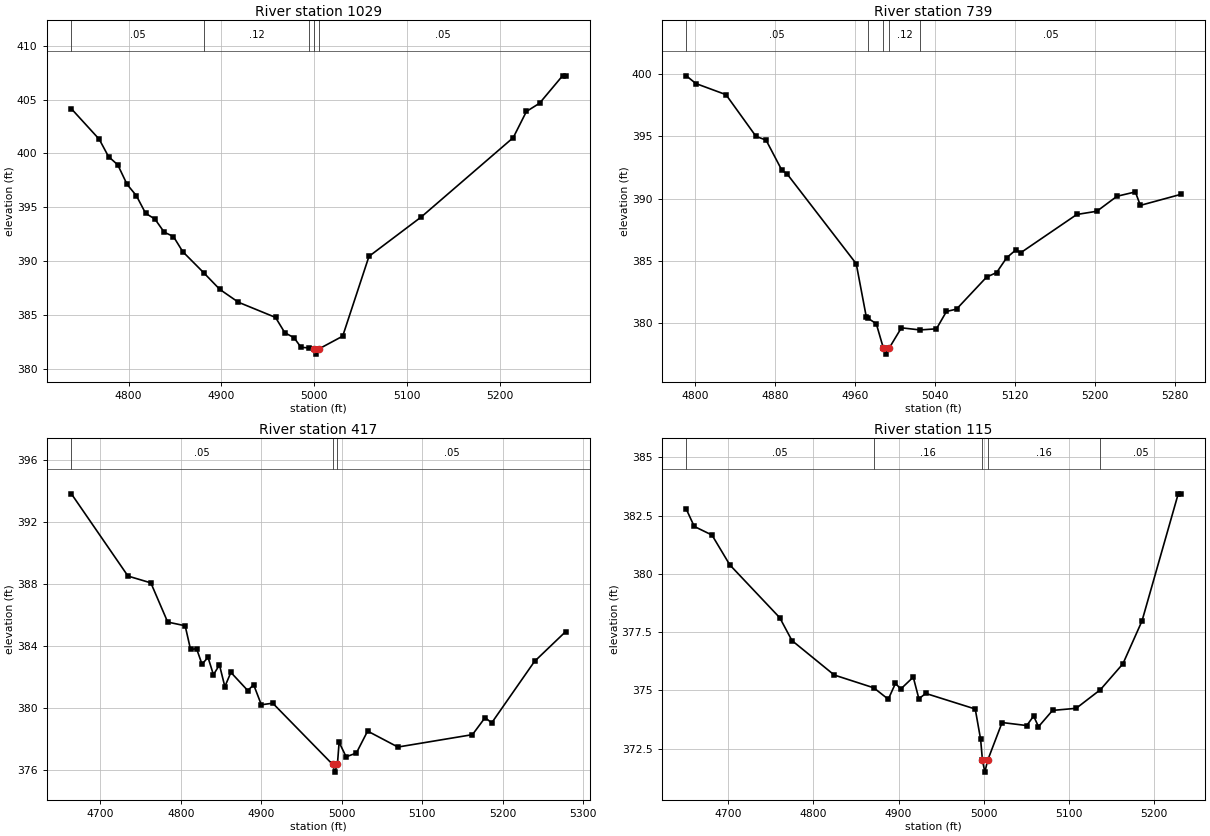
Type RM Length L Ch R = 1,1029,290,290,290
BEGIN DESCRIPTION:
UNT 039 IN CACR 2.0
END DESCRIPTION:
XS GIS Cut Line= 3
      3674149.61     10762610.14      3674149.61     10762360.19
      3673949.61     10762160.19
#Sta/Elev= 30
  4738.4  404.14  4768.4  401.31  4778.4  399.70  4788.4  398.93  4798.4  397.12
  4808.4  396.07  4818.4  394.43  4828.4  393.90  4838.4  392.68  4848.4  392.27
  4858.4  390.87  4881.0  388.91  4898.4  387.36  4918.4  386.17  4958.4  384.76
  4968.4  383.34  4978.4  382.87  4985.9  381.98  4994.6  381.93  4999.5  381.85
  5002.2  381.35  5005.5  381.85  5030.8  383.02  5059.1  390.43  5115.6  394.10
  5214.6  401.46  5228.8  403.89  5242.9  404.65  5267.7  407.20  5271.2  407.20
#Mann=5,-1,0
  4738.4    0.05       0  4881.0    0.12       0  4994.6    0.05       0
  4999.5    0.03       0  5005.5    0.05       0
Bank Sta=4999.5,5005.5
Exp/Cntr=0.3,0.1

Type RM Length L Ch R = 1,739,322,322,322
BEGIN DESCRIPTION:
Mapping XS a14ac477
END DESCRIPTION:
XS GIS Cut Line= 2
      3674396.47     10762589.71      3674438.15     10762096.57
#Sta/Elev= 30
  4790.9  399.84  4800.5  399.22  4830.6  398.33  4860.7  394.98  4870.7  394.69
  4886.6  392.26  4891.6  391.99  4961.0  384.77  4971.1  380.49  4972.8  380.40
  4981.1  379.95  4988.1  378.02  4990.9  377.52  4994.1  378.02  5006.2  379.63
  5024.9  379.46  5041.3  379.55  5051.3  380.94  5061.4  381.13  5091.5  383.70
  5101.5  384.06  5111.6  385.25  5120.8  385.88  5125.8  385.66  5181.8  388.72
  5201.9  388.98  5222.0  390.18  5240.4  390.53  5245.4  389.45  5285.8  390.33
#Mann=5,-1,0
  4790.9    0.05       0  4972.8    0.12       0  4988.1    0.07       0
  4994.1    0.12       0  5024.9    0.05       0
Bank Sta=4988.1,4994.1
Exp/Cntr=0.3,0.1

Type RM Length L Ch R = 1,417,302,302,302
BEGIN DESCRIPTION:
Mapping XS f823c504
END DESCRIPTION:
XS GIS Cut Line= 4
      3674521.50     10762551.45      3674698.56     10762391.75
      3674681.20     10762280.64      3674580.50     10762037.57
#Sta/Elev= 30
  4664.1  393.84  4734.4  388.53  4762.8  388.09  4783.7  385.56  4805.4  385.32
  4812.1  383.79  4819.6  383.84  4826.3  382.84  4833.8  383.28  4840.5  382.16
  4848.0  382.79  4854.7  381.39  4862.2  382.31  4883.1  381.14  4890.5  381.51
  4900.0  380.22  4914.2  380.32  4988.5  376.37  4991.3  375.87  4994.5  376.37
  4996.6  377.80  5005.3  376.86  5018.0  377.10  5032.0  378.52  5069.6  377.49
  5162.2  378.29  5177.9  379.39  5186.1  379.05  5239.3  383.02  5278.1  384.95
#Mann=3,-1,0
  4664.1    0.05       0  4988.5    0.03       0  4994.5    0.05       0
Bank Sta=4988.5,4994.5
Exp/Cntr=0.3,0.1

Type RM Length L Ch R = 1,115,0,0,0
BEGIN DESCRIPTION:
UNT 039 IN CACR 1.0
END DESCRIPTION:
XS GIS Cut Line= 4
      3674747.15     10762429.97      3674920.78     10762193.83
      3674893.01     10762107.03      3674719.42     10762016.76
#Sta/Elev= 30
  4651.1  382.78  4660.4  382.04  4681.2  381.67  4702.1  380.39  4760.7  378.12
  4775.0  377.14  4824.6  375.66  4871.0  375.11  4888.0  374.62  4896.4  375.30
  4902.7  375.06  4917.3  375.57  4923.9  374.64  4931.9  374.87  4990.0  374.20
  4996.3  372.90  4998.5  371.99  5001.3  371.49  5004.5  371.99  5021.5  373.62
  5050.4  373.49  5058.5  373.90  5064.2  373.44  5080.7  374.14  5108.4  374.23
  5136.8  375.03  5163.2  376.14  5185.6  377.98  5228.1  383.44  5231.0  383.44
#Mann=5,-1,0
  4651.1    0.05       0  4871.0    0.16       0  4998.5    0.07       0
  5004.5    0.16       0  5136.8    0.05       0
Bank Sta=4998.5,5004.5
Exp/Cntr=0.3,0.1

Chan Stop Cuts=-1