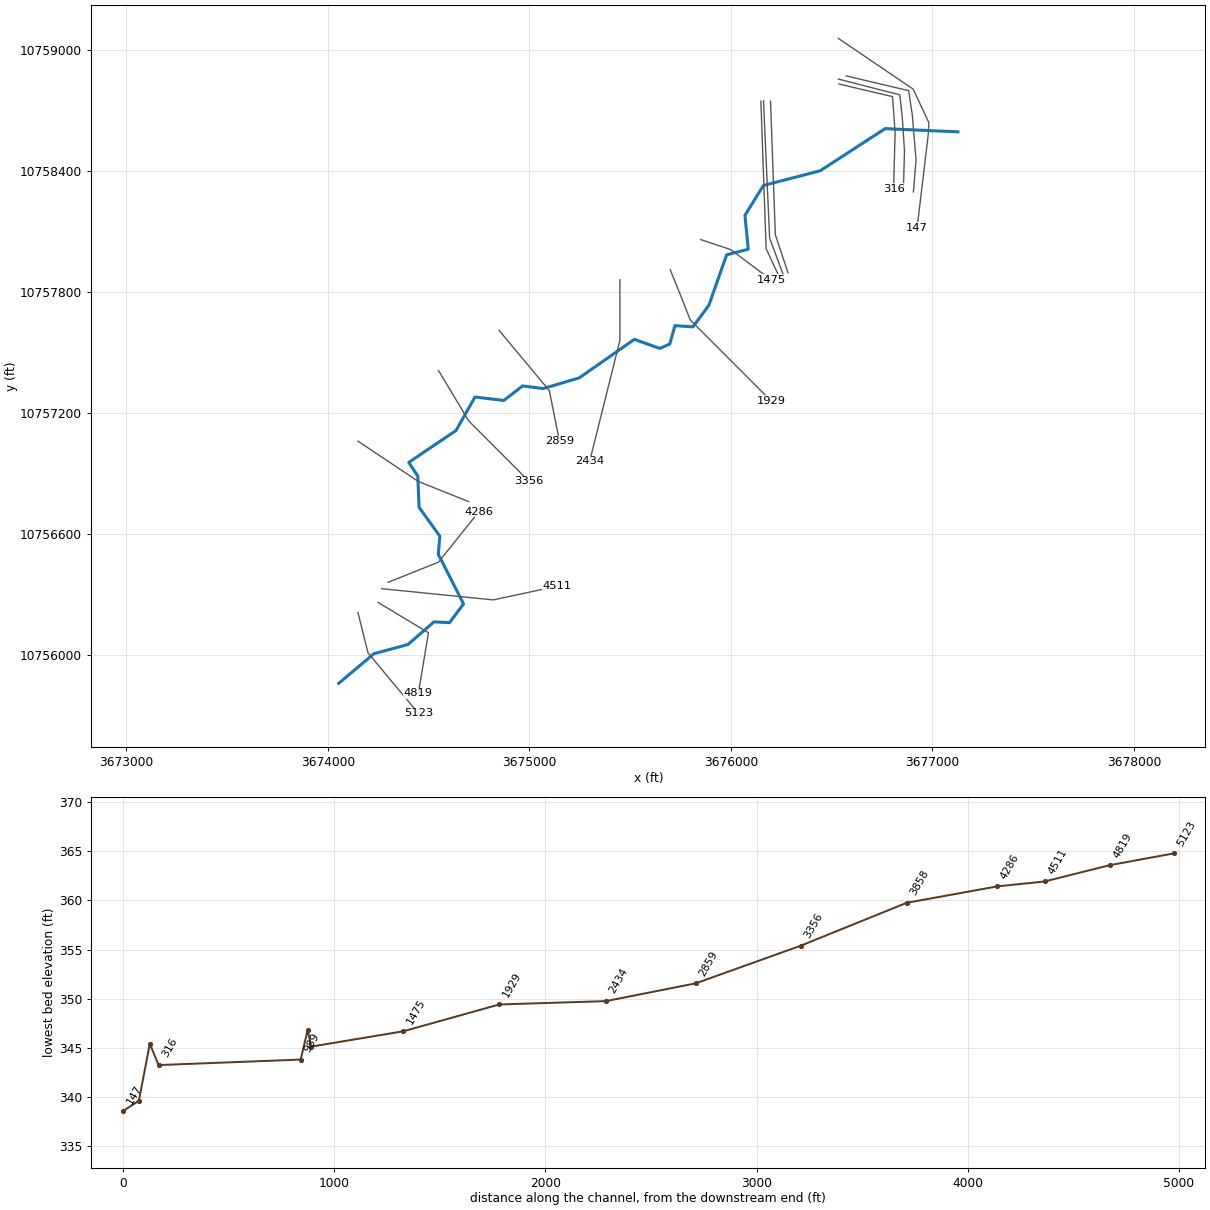
--- UNT 040 IN CACR.prj (project) ---

Proj Title=UNT 040 IN CACR Base Level Engineering
Current Plan=p01
Default Exp/Contr=0.3,0.1
English Units
Geom File=g01
Flow File=f01
Plan File=p01
BEGIN DESCRIPTION:
UNT 040 IN CACR
END DESCRIPTION:

--- UNT 040 IN CACR.p01 (plan) ---

Plan Title=Multiple Run
Short Identifier=Multiple
Geom File=g01
Flow File=f01
Subcritical Flow
K Sum by GR= 0
Std Step Tol= 0.01
Critical Tol= 0.01
Num of Std Step Trials= 20
Max Error Tol= 0.3
Flow Tol Ratio= 0.001
Split Flow NTrial= 30
Split Flow Tol= 0.02
Split Flow Ratio= 0.02
Log Output Level= 0
Friction Slope Method= 1
Unsteady Friction Slope Method= 2
Unsteady Bridges Friction Slope Method= 1
Parabolic Critical Depth
Global Vel Dist=  1 , 1 , 1
Global Log Level= 0
CheckData=True
Encroach Param= -1, 0, 0, 0
BEGIN DESCRIPTION:
Multiple Run
END DESCRIPTION:

--- UNT 040 IN CACR.f01 (steady flow) ---

Flow Title=Multiple
Number of Profiles=7
Profile Names=10-year,25-year,50-year,1pct_min,100-year,1pct_plu,500-year
River Rch & RM= UNT 040 IN CACR,Reach-1,5123
     550     738     890     788    1066    1442    1532
River Rch & RM= UNT 040 IN CACR,Reach-1,1929
     621     839    1017     904    1223    1653    1771
Boundary for River Rch & Prof#=UNT 040 IN CACR,Reach-1,1
Up Type=0
Dn Type=3
Dn Slope=0.005
Boundary for River Rch & Prof#=UNT 040 IN CACR,Reach-1,2
Up Type=0
Dn Type=3
Dn Slope=0.005
Boundary for River Rch & Prof#=UNT 040 IN CACR,Reach-1,3
Up Type=0
Dn Type=3
Dn Slope=0.005
Boundary for River Rch & Prof#=UNT 040 IN CACR,Reach-1,4
Up Type=0
Dn Type=3
Dn Slope=0.005
Boundary for River Rch & Prof#=UNT 040 IN CACR,Reach-1,5
Up Type=0
Dn Type=3
Dn Slope=0.005
Boundary for River Rch & Prof#=UNT 040 IN CACR,Reach-1,6
Up Type=0
Dn Type=3
Dn Slope=0.005
Boundary for River Rch & Prof#=UNT 040 IN CACR,Reach-1,7
Up Type=0
Dn Type=3
Dn Slope=0.005

--- UNT 040 IN CACR.g01 (geometry) ---

Geom Title=Existing Conditions

River Reach=UNT 040 IN CACR,Reach-1
Reach XY= 30
      3674054.45     10755859.20      3674229.00     10756006.00
      3674398.25     10756052.00      3674527.00     10756164.00
      3674604.00     10756160.00      3674673.75     10756253.00
      3674548.50     10756499.00      3674556.00     10756589.00
      3674453.00     10756732.00      3674446.84     10756886.75
      3674401.78     10756954.72      3674636.50     10757113.00
      3674730.25     10757279.00      3674873.75     10757262.00
      3674966.75     10757334.00      3675069.00     10757321.00
      3675248.00     10757374.00      3675521.50     10757565.00
      3675647.75     10757520.00      3675697.25     10757542.00
      3675722.75     10757633.00      3675812.00     10757627.00
      3675891.25     10757734.00      3675979.25     10757984.00
      3676086.50     10758012.00      3676070.25     10758180.00
      3676161.75     10758328.00      3676443.75     10758401.00
      3676766.00     10758610.00      3677127.25     10758594.00

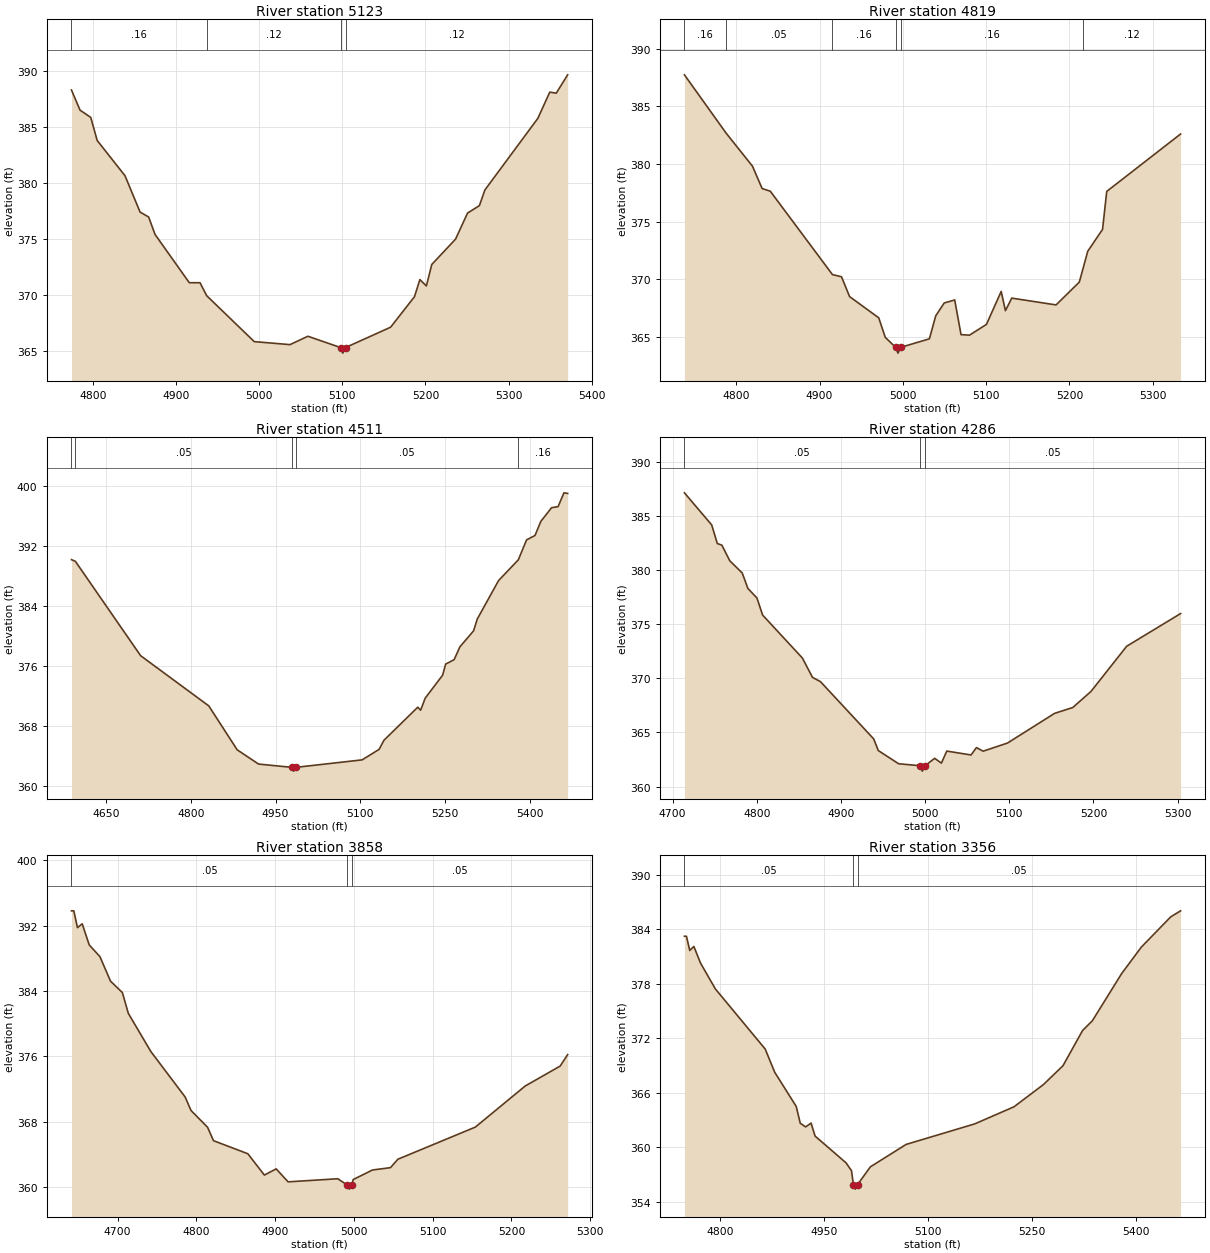
Type RM Length L Ch R = 1,5123,304,304,304
BEGIN DESCRIPTION:
UNT 040 IN CACR 11.0
END DESCRIPTION:
XS GIS Cut Line= 3
      3674149.61     10756210.19      3674199.61     10756010.19
      3674449.63     10755710.17
#Sta/Elev= 30
  4774.4  388.33  4784.7  386.53  4797.6  385.88  4805.3  383.82  4838.8  380.66
  4856.9  377.41  4867.2  376.97  4874.9  375.41  4916.1  371.09  4929.0  371.09
  4937.0  369.93  4994.2  365.82  5037.2  365.55  5058.7  366.30  5098.0  365.29
  5100.7  364.79  5104.0  365.29  5158.2  367.11  5186.9  369.84  5193.4  371.37
  5201.2  370.80  5207.7  372.72  5236.3  374.99  5250.7  377.32  5265.0  377.99
  5271.5  379.38  5335.3  385.80  5349.6  388.14  5357.4  388.05  5371.1  389.69
#Mann=4,-1,0
  4774.4    0.16       0  4937.0    0.12       0  5098.0    0.07       0
  5104.0    0.12       0
Bank Sta=5098,5104
Exp/Cntr=0.3,0.1

Type RM Length L Ch R = 1,4819,308,308,308
BEGIN DESCRIPTION:
UNT 040 IN CACR 10.0
END DESCRIPTION:
XS GIS Cut Line= 3
      3674249.57     10756260.21      3674499.61     10756110.19
      3674449.61     10755810.22
#Sta/Elev= 30
  4737.8  387.72  4787.8  382.67  4819.5  379.80  4831.1  377.86  4840.9  377.63
  4915.5  370.40  4926.4  370.21  4936.1  368.49  4971.1  366.65  4978.9  364.96
  4991.4  364.09  4994.2  363.59  4997.4  364.09  5031.9  364.83  5039.5  366.82
  5049.7  367.94  5062.3  368.20  5069.9  365.19  5080.1  365.15  5100.4  366.08
  5118.1  368.94  5123.2  367.27  5130.8  368.36  5184.0  367.77  5211.9  369.75
  5216.0  370.83  5222.0  372.42  5239.8  374.32  5244.8  377.61  5333.5  382.59
#Mann=6,-1,0
  4737.8    0.16       0  4787.8    0.05       0  4915.5    0.16       0
  4991.4    0.07       0  4997.4    0.16       0  5216.0    0.12       0
Bank Sta=4991.4,4997.4
Exp/Cntr=0.3,0.1

Type RM Length L Ch R = 1,4511,225,225,225
BEGIN DESCRIPTION:
Mapping XS a86cf059
END DESCRIPTION:
XS GIS Cut Line= 3
      3674267.81     10756328.51      3674821.60     10756272.96
      3675136.09     10756340.35
#Sta/Elev= 30
  4588.7  390.12  4595.6  389.90  4711.1  377.32  4831.7  370.63  4882.0  364.77
  4919.9  362.87  4979.5  362.43  4982.2  361.93  4985.5  362.43  5103.1  363.43
  5133.2  364.83  5141.8  366.05  5201.6  370.45  5206.7  370.05  5214.8  371.66
  5245.5  374.71  5251.0  376.20  5266.0  376.79  5276.2  378.50  5300.4  380.63
  5306.9  382.20  5344.7  387.34  5379.6  390.10  5394.2  392.76  5409.1  393.34
  5419.4  395.22  5438.5  397.05  5450.0  397.19  5460.3  399.03  5466.9  398.95
#Mann=5,-1,0
  4588.7    0.16       0  4595.6    0.05       0  4979.5    0.03       0
  4985.5    0.05       0  5379.6    0.16       0
Bank Sta=4979.5,4985.5
Exp/Cntr=0.3,0.1

Type RM Length L Ch R = 1,4286,428,428,428
BEGIN DESCRIPTION:
UNT 040 IN CACR 9.0
END DESCRIPTION:
XS GIS Cut Line= 3
      3674299.57     10756360.17      3674549.61     10756460.19
      3674749.64     10756710.22
#Sta/Elev= 30
  4714.0  387.11  4746.4  384.15  4753.1  382.43  4758.5  382.28  4767.9  380.84
  4782.7  379.71  4789.4  378.29  4800.2  377.40  4806.9  375.83  4854.1  371.87
  4866.2  370.08  4875.6  369.69  4938.9  364.40  4944.3  363.33  4968.5  362.11
  4993.9  361.93  4996.7  361.43  4999.9  361.93  5011.3  362.61  5019.3  362.17
  5025.7  363.28  5054.5  362.92  5060.9  363.60  5068.9  363.27  5097.8  364.02
  5153.8  366.76  5175.4  367.30  5197.0  368.78  5239.4  372.95  5303.5  375.97
#Mann=3,-1,0
  4714.0    0.05       0  4993.9    0.03       0  4999.9    0.05       0
Bank Sta=4993.9,4999.9
Exp/Cntr=0.3,0.1

Type RM Length L Ch R = 1,3858,502,502,502
BEGIN DESCRIPTION:
UNT 040 IN CACR 8.0
END DESCRIPTION:
XS GIS Cut Line= 3
      3674149.57     10757060.21      3674449.61     10756860.19
      3674699.65     10756760.17
#Sta/Elev= 30
  4641.4  393.82  4644.4  393.82  4649.0  391.76  4655.0  392.23  4664.0  389.64
  4677.5  388.22  4691.0  385.21  4706.0  383.82  4713.6  381.27  4742.1  376.61
  4785.7  371.04  4793.2  369.38  4814.2  367.33  4821.7  365.69  4865.3  364.09
  4886.3  361.48  4901.3  362.24  4916.4  360.65  4979.5  361.03  4991.5  360.26
  4994.2  359.76  4997.5  360.26  4999.0  360.93  5023.5  362.10  5046.4  362.39
  5055.8  363.42  5154.1  367.35  5217.4  372.38  5261.8  374.82  5271.3  376.22
#Mann=3,-1,0
  4641.4    0.05       0  4991.5    0.03       0  4997.5    0.05       0
Bank Sta=4991.5,4997.5
Exp/Cntr=0.3,0.1

Type RM Length L Ch R = 1,3356,497,497,497
BEGIN DESCRIPTION:
UNT 040 IN CACR 7.0
END DESCRIPTION:
XS GIS Cut Line= 3
      3674549.63     10757410.16      3674699.61     10757160.19
      3674999.62     10756860.17
#Sta/Elev= 30
  4748.1  383.22  4751.0  383.22  4755.8  381.66  4761.7  382.10  4771.4  380.26
  4792.8  377.42  4864.7  370.80  4878.3  368.26  4909.4  364.49  4915.2  362.64
  4923.0  362.24  4930.8  362.66  4936.6  361.23  4981.3  358.28  4989.1  357.42
  4991.9  355.89  4994.7  355.39  4997.9  355.89  5016.3  357.84  5067.9  360.31
  5166.9  362.57  5223.5  364.45  5265.9  366.89  5294.2  368.97  5322.5  372.85
  5336.6  373.92  5379.0  379.13  5407.3  382.03  5449.7  385.36  5463.9  386.02
#Mann=3,-1,0
  4748.1    0.05       0  4991.9    0.03       0  4997.9    0.05       0
Bank Sta=4991.9,4997.9
Exp/Cntr=0.3,0.1

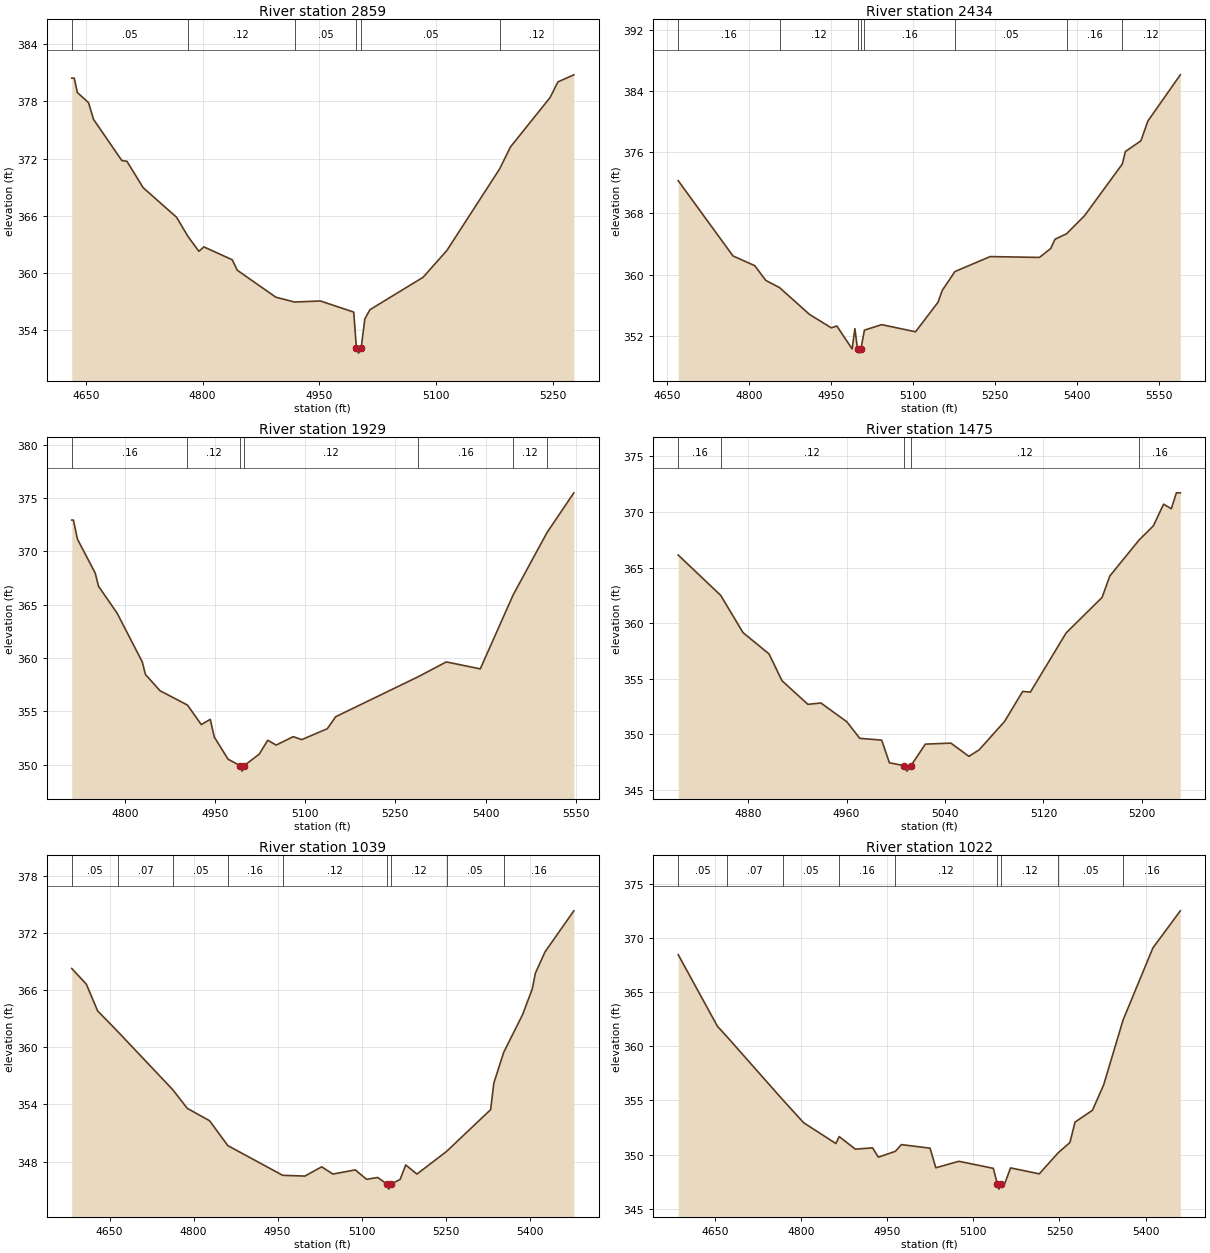
Type RM Length L Ch R = 1,2859,425,425,425
BEGIN DESCRIPTION:
UNT 040 IN CACR 6.0
END DESCRIPTION:
XS GIS Cut Line= 3
      3674849.61     10757610.18      3675099.61     10757310.19
      3675149.62     10757060.14
#Sta/Elev= 30
  4631.7  380.45  4634.9  380.45  4638.9  378.94  4653.2  377.88  4659.7  376.12
  4696.1  371.79  4702.6  371.72  4723.5  368.94  4766.4  365.84  4781.2  363.81
  4795.1  362.26  4801.6  362.72  4838.0  361.37  4844.5  360.27  4894.0  357.44
  4918.1  356.93  4951.3  357.04  4994.2  355.87  4997.7  352.06  5000.5  351.56
  5003.7  352.06  5008.5  355.16  5015.0  356.12  5083.4  359.53  5114.0  362.35
  5181.9  370.93  5195.6  373.21  5246.6  378.41  5256.8  380.06  5277.2  380.80
#Mann=6,-1,0
  4631.7    0.05       0  4781.2    0.12       0  4918.1    0.05       0
  4997.7    0.03       0  5003.7    0.05       0  5181.9    0.12       0
Bank Sta=4997.7,5003.7
Exp/Cntr=0.3,0.1

Type RM Length L Ch R = 1,2434,505,505,505
BEGIN DESCRIPTION:
UNT 040 IN CACR 5.0
END DESCRIPTION:
XS GIS Cut Line= 3
      3675449.61     10757860.24      3675449.61     10757560.19
      3675299.61     10756960.20
#Sta/Elev= 30
  4670.8  372.27  4770.9  362.45  4810.9  361.17  4830.9  359.25  4856.3  358.30
  4910.9  354.81  4950.9  353.05  4960.9  353.30  4988.9  350.30  4994.0  352.95
  4998.8  350.25  5001.5  349.75  5004.8  350.25  5011.4  352.75  5043.0  353.47
  5104.9  352.54  5146.1  356.40  5153.8  357.95  5177.1  360.41  5241.4  362.36
  5331.6  362.25  5352.2  363.41  5360.0  364.62  5381.2  365.34  5414.1  367.70
  5483.2  374.45  5488.8  376.08  5517.2  377.48  5530.0  380.07  5589.3  386.10
#Mann=8,-1,0
  4670.8    0.16       0  4856.3    0.12       0  4998.8    0.07       0
  5004.8    0.12       0  5011.4    0.16       0  5177.1    0.05       0
  5381.2    0.16       0  5483.2    0.12       0
Bank Sta=4998.8,5004.8
Exp/Cntr=0.3,0.1

Type RM Length L Ch R = 1,1929,454,454,454
BEGIN DESCRIPTION:
UNT 040 IN CACR 4.0
END DESCRIPTION:
XS GIS Cut Line= 3
      3675699.59     10757910.23      3675799.61     10757660.19
      3676199.62     10757260.18
#Sta/Elev= 30
  4711.9  372.93  4714.6  372.93  4721.4  371.14  4751.0  367.95  4756.4  366.73
  4787.3  364.21  4829.1  359.65  4834.5  358.46  4858.7  356.94  4904.3  355.60
  4927.3  353.77  4942.2  354.26  4948.9  352.61  4971.8  350.53  4992.3  349.91
  4995.1  349.41  4998.3  349.91  5023.6  351.00  5037.8  352.30  5051.9  351.85
  5080.2  352.64  5094.3  352.36  5136.8  353.38  5150.9  354.51  5288.0  358.25
  5334.8  359.64  5391.3  358.99  5445.9  365.91  5502.1  371.74  5546.9  375.48
#Mann=7,-1,0
  4711.9    0.16       0  4904.3    0.12       0  4992.3    0.07       0
  4998.3    0.12       0  5288.0    0.16       0  5445.9    0.12       0
  5502.1    0.05       0
Bank Sta=4992.3,4998.3
Exp/Cntr=0.3,0.1

Type RM Length L Ch R = 1,1475,436,436,436
BEGIN DESCRIPTION:
UNT 040 IN CACR 3.0
END DESCRIPTION:
XS GIS Cut Line= 3
      3675849.57     10758060.20      3675999.61     10758010.19
      3676199.65     10757860.16
#Sta/Elev= 30
  4823.1  366.12  4857.6  362.50  4875.8  359.14  4896.9  357.23  4907.5  354.81
  4928.5  352.69  4939.1  352.81  4960.2  351.12  4970.7  349.63  4988.5  349.47
  4994.8  347.43  5006.4  347.18  5009.1  346.68  5012.4  347.18  5024.0  349.11
  5044.8  349.20  5059.4  348.01  5067.7  348.59  5088.5  351.16  5103.1  353.85
  5109.4  353.79  5138.5  359.12  5167.7  362.31  5174.0  364.24  5197.9  367.49
  5209.4  368.75  5217.7  370.70  5224.0  370.29  5228.1  371.72  5231.3  371.72
#Mann=5,-1,0
  4823.1    0.16       0  4857.6    0.12       0  5006.4    0.07       0
  5012.4    0.12       0  5197.9    0.16       0
Bank Sta=5006.4,5012.4
Exp/Cntr=0.3,0.1

Type RM Length L Ch R = 1,1039,17,17,17
BEGIN DESCRIPTION:
UNT 040 IN CACR 2.0
END DESCRIPTION:
XS GIS Cut Line= 3
      3676149.31     10758746.21      3676175.36     10758014.84
      3676244.67     10757865.37
#Sta/Elev= 30
  4582.4  368.27  4608.4  366.63  4628.5  363.83  4665.1  361.62  4763.1  355.53
  4788.6  353.60  4828.6  352.29  4861.0  349.69  4959.0  346.57  4998.7  346.49
  5028.7  347.46  5048.7  346.70  5088.7  347.14  5108.8  346.15  5128.8  346.34
  5145.8  345.62  5148.5  345.12  5151.8  345.62  5168.8  346.14  5178.8  347.66
  5198.8  346.70  5251.6  349.07  5330.4  353.46  5336.1  356.25  5353.8  359.48
  5387.4  363.42  5404.8  366.13  5410.3  367.77  5427.7  370.03  5479.0  374.32
#Mann=9,-1,0
  4582.4    0.05       0  4665.1    0.07       0  4763.1    0.05       0
  4861.0    0.16       0  4959.0    0.12       0  5145.8    0.07       0
  5151.8    0.12       0  5251.6    0.05       0  5353.8    0.16       0
Bank Sta=5145.8,5151.8
Exp/Cntr=0.3,0.1

Type RM Length L Ch R = 1,1022,33,33,33
BEGIN DESCRIPTION:
Mapping XS 56322cdf
END DESCRIPTION:
XS GIS Cut Line= 3
      3676162.33     10758748.37      3676192.72     10758066.92
      3676259.99     10757886.80
#Sta/Elev= 30
  4586.1  368.45  4654.4  361.84  4670.5  360.91  4768.4  355.04  4804.5  352.94
  4860.6  351.02  4866.4  351.66  4894.6  350.50  4924.6  350.62  4934.6  349.76
  4964.3  350.30  4974.7  350.92  5024.7  350.59  5034.7  348.78  5074.8  349.38
  5134.8  348.73  5141.8  347.31  5144.6  346.81  5147.8  347.31  5154.8  347.33
  5164.9  348.77  5214.9  348.22  5247.5  350.15  5268.2  351.11  5277.2  353.00
  5307.5  354.09  5327.1  356.45  5360.8  362.42  5412.7  369.07  5460.5  372.50
#Mann=9,-1,0
  4586.1    0.05       0  4670.5    0.07       0  4768.4    0.05       0
  4866.4    0.16       0  4964.3    0.12       0  5141.8    0.07       0
  5147.8    0.12       0  5247.5    0.05       0  5360.8    0.16       0
Bank Sta=5141.8,5147.8
Exp/Cntr=0.3,0.1

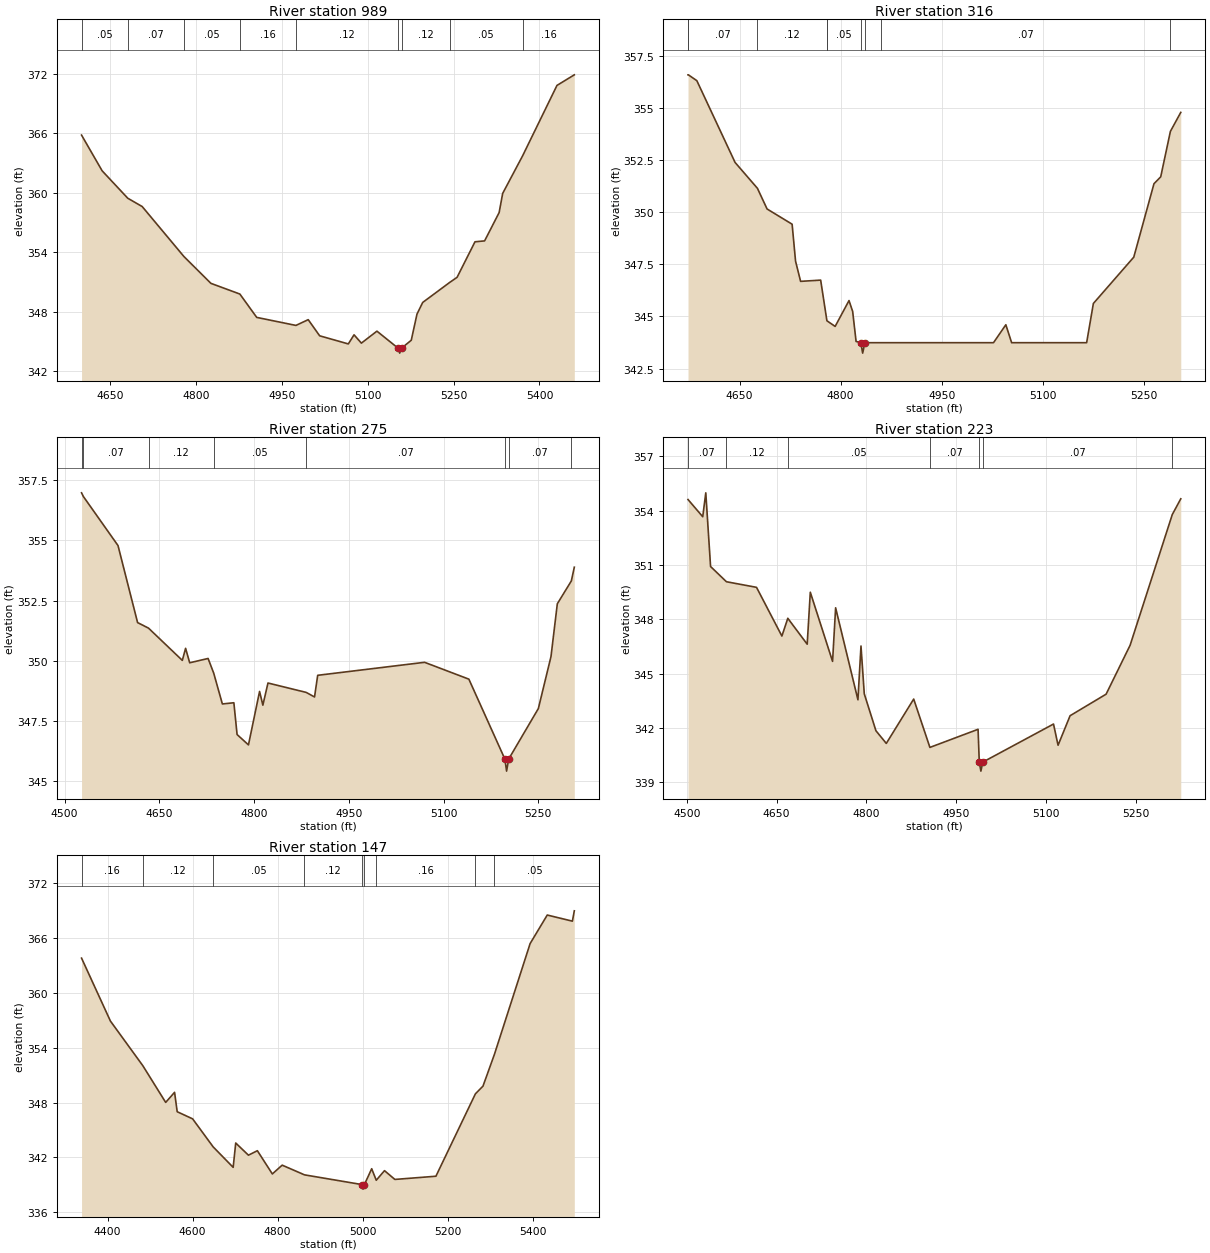
Type RM Length L Ch R = 1,989,673,673,673
BEGIN DESCRIPTION:
Mapping XS f4cafe8d
END DESCRIPTION:
XS GIS Cut Line= 3
      3676197.06     10758746.14      3676220.93     10758084.28
      3676283.86     10757895.49
#Sta/Elev= 30
  4599.6  365.83  4635.6  362.22  4680.4  359.45  4705.6  358.61  4778.4  353.57
  4825.7  350.85  4876.3  349.77  4905.8  347.41  4974.3  346.60  4995.8  347.18
  5015.8  345.55  5065.9  344.73  5075.9  345.65  5088.7  344.81  5115.9  346.02
  5152.9  344.30  5155.7  343.80  5158.9  344.30  5175.9  345.10  5185.9  347.74
  5195.9  348.92  5243.0  350.94  5256.0  351.46  5287.3  355.05  5304.1  355.14
  5329.5  358.00  5335.7  359.94  5370.4  363.72  5430.6  370.85  5460.9  371.92
#Mann=9,-1,0
  4599.6    0.05       0  4680.4    0.07       0  4778.4    0.05       0
  4876.3    0.16       0  4974.3    0.12       0  5152.9    0.07       0
  5158.9    0.12       0  5243.0    0.05       0  5370.4    0.16       0
Bank Sta=5152.9,5158.9
Exp/Cntr=0.3,0.1

Type RM Length L Ch R = 1,316,41,41,41
BEGIN DESCRIPTION:
Mapping XS f184e707
END DESCRIPTION:
XS GIS Cut Line= 4
      3676536.87     10758831.25      3676802.53     10758768.74
      3676815.55     10758591.66      3676807.73     10758310.44
#Sta/Elev= 30
  4573.3  356.58  4573.8  356.58  4586.4  356.30  4643.2  352.38  4676.4  351.14
  4690.7  350.15  4727.9  349.42  4733.0  347.65  4740.5  346.68  4770.3  346.74
  4779.1  344.89  4779.6  344.79  4791.8  344.52  4812.4  345.76  4817.8  345.24
  4822.9  343.80  4829.9  343.74  4832.7  343.24  4835.9  343.74  4860.5  343.74
  5027.0  343.74  5045.3  344.60  5053.9  343.74  5165.3  343.74  5175.3  345.62
  5235.3  347.84  5265.3  351.36  5275.3  351.69  5289.7  353.87  5305.1  354.78
#Mann=9,-1,0
  4573.3    0.05       0  4573.8    0.07       0  4676.4    0.12       0
  4779.1    0.07       0  4779.6    0.05       0  4829.9    0.07       0
  4835.9    0.05       0  4860.5    0.07       0  5289.7    0.05       0
Bank Sta=4829.9,4835.9
Exp/Cntr=0.3,0.1

Type RM Length L Ch R = 1,275,52,52,52
BEGIN DESCRIPTION:
Mapping XS 4f1b1f46
END DESCRIPTION:
XS GIS Cut Line= 5
      3676533.73     10758855.74      3676838.46     10758777.60
      3676851.48     10758660.41      3676861.90     10758498.95
      3676856.74     10758313.32
#Sta/Elev= 30
  4526.9  356.98  4529.7  356.83  4584.6  354.79  4615.6  351.59  4632.9  351.36
  4686.4  350.02  4691.6  350.52  4698.1  349.92  4727.2  350.10  4736.1  349.49
  4749.8  348.21  4768.0  348.26  4773.1  346.94  4791.1  346.51  4808.7  348.73
  4813.9  348.16  4822.0  349.08  4882.5  348.69  4895.7  348.50  4900.7  349.40
  5069.9  349.94  5140.0  349.24  5197.0  345.92  5199.7  345.42  5203.0  345.92
  5250.0  348.02  5270.0  350.18  5280.0  352.37  5302.2  353.32  5306.9  353.89
#Mann=8,-1,0
  4526.9    0.05       0  4529.7    0.07       0  4632.9    0.12       0
  4736.1    0.05       0  4882.5    0.07       0  5197.0    0.07       0
  5203.0    0.07       0  5302.2    0.05       0
Bank Sta=5197,5203
Exp/Cntr=0.3,0.1

Type RM Length L Ch R = 1,223,76,76,76
BEGIN DESCRIPTION:
Mapping XS aa74df81
END DESCRIPTION:
XS GIS Cut Line= 5
      3676572.88     10758871.34      3676882.73     10758798.43
      3676900.96     10758676.04      3676919.19     10758454.68
      3676906.17     10758295.78
#Sta/Elev= 30
  4501.9  354.61  4526.5  353.66  4531.6  354.98  4539.6  350.91  4566.1  350.07
  4616.4  349.76  4658.8  347.07  4668.7  348.05  4701.1  346.62  4706.3  349.49
  4743.5  345.67  4748.6  348.63  4785.9  343.55  4791.0  346.52  4796.5  343.88
  4816.0  341.84  4833.3  341.14  4879.1  343.59  4906.2  340.92  4986.7  341.92
  4988.7  340.11  4991.4  339.61  4994.7  340.11  5112.8  342.21  5120.4  341.04
  5140.5  342.67  5200.7  343.86  5240.8  346.56  5311.3  353.78  5325.5  354.65
#Mann=7,-1,0
  4501.9    0.07       0  4566.1    0.12       0  4668.7    0.05       0
  4906.2    0.07       0  4988.7    0.07       0  4994.7    0.07       0
  5311.3    0.05       0
Bank Sta=4988.7,4994.7
Exp/Cntr=0.3,0.1

Type RM Length L Ch R = 1,147,0,0,0
BEGIN DESCRIPTION:
UNT 040 IN CACR 1.0
END DESCRIPTION:
XS GIS Cut Line= 5
      3676533.41     10759057.82      3676904.96     10758806.07
      3676983.08     10758639.40      3676979.61     10758578.64
      3676924.51     10758117.05
#Sta/Elev= 30
  4338.9  363.79  4406.8  356.91  4483.0  352.03  4536.7  348.02  4557.6  349.12
  4563.8  347.00  4600.1  346.22  4648.3  343.16  4695.4  340.92  4701.4  343.58
  4731.3  342.25  4752.3  342.74  4787.5  340.20  4810.6  341.16  4863.1  340.10
  4998.0  339.04  5000.8  338.54  5004.0  339.04  5021.1  340.77  5031.8  339.51
  5051.2  340.56  5075.6  339.60  5172.1  339.95  5265.0  348.96  5282.8  349.80
  5309.6  353.26  5393.6  365.38  5433.9  368.50  5493.0  367.83  5497.5  368.96
#Mann=9,-1,0
  4338.9    0.16       0  4483.0    0.12       0  4648.3    0.05       0
  4863.1    0.12       0  4998.0    0.07       0  5004.0    0.12       0
  5031.8    0.16       0  5265.0    0.07       0  5309.6    0.05       0
Bank Sta=4998,5004
Exp/Cntr=0.3,0.1

Chan Stop Cuts=-1