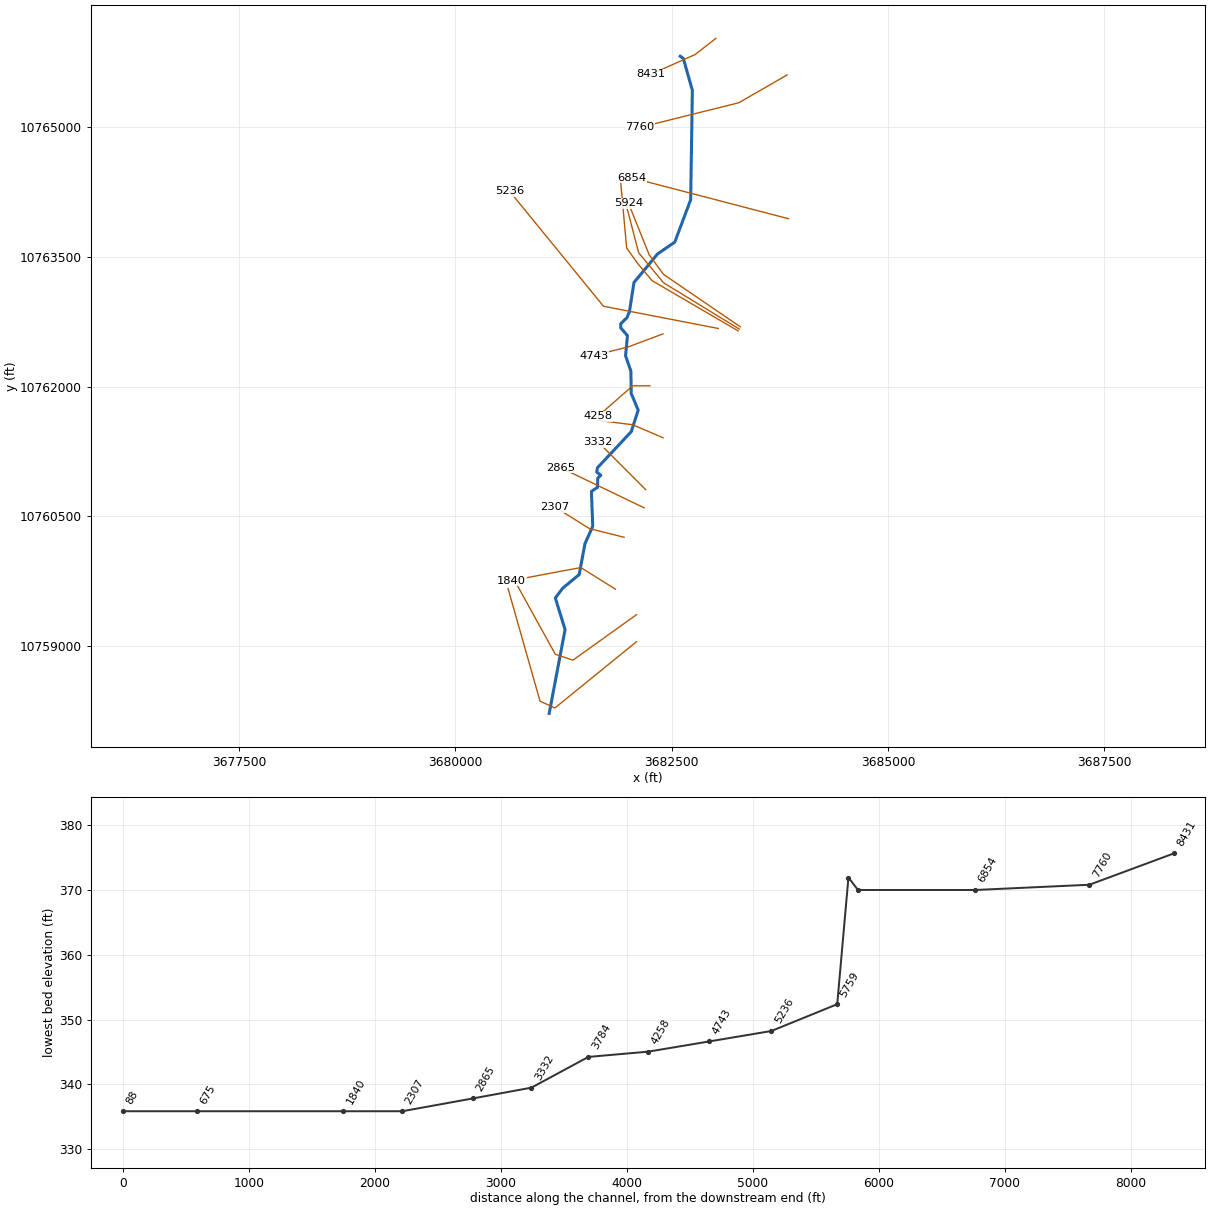
--- UNT 041 IN CACR.prj (project) ---

Proj Title=UNT 041 IN CACR Base Level Engineering
Current Plan=p01
Default Exp/Contr=0.3,0.1
English Units
Geom File=g01
Flow File=f01
Plan File=p01
Y Axis Title=Elevation
X Axis Title(PF)=Main Channel Distance
X Axis Title(XS)=Station
BEGIN DESCRIPTION:
UNT 041 IN CACR
END DESCRIPTION:
DSS Export Rating Curves= 0
DSS Export Rating Curve Sorted= 0
DSS Export Volume Flow Curves= 0
DXF OffsetX= 0
DXF OffsetY= 0
DXF ScaleX= 1
DXF ScaleY= 10

--- UNT 041 IN CACR.p01 (plan) ---

Plan Title=Multiple Run
Short Identifier=Multiple
Geom File=g01
Flow File=f01
Subcritical Flow
K Sum by GR= 0
Std Step Tol= 0.01
Critical Tol= 0.01
Num of Std Step Trials= 20
Max Error Tol= 0.3
Flow Tol Ratio= 0.001
Split Flow NTrial= 30
Split Flow Tol= 0.02
Split Flow Ratio= 0.02
Log Output Level= 0
Friction Slope Method= 1
Unsteady Friction Slope Method= 2
Unsteady Bridges Friction Slope Method= 1
Parabolic Critical Depth
Global Vel Dist=  1 , 1 , 1
Global Log Level= 0
CheckData=True
Encroach Param= -1, 0, 0, 0
BEGIN DESCRIPTION:
Multiple Run
END DESCRIPTION:

--- UNT 041 IN CACR.f01 (steady flow) ---

Flow Title=Multiple
Number of Profiles=7
Profile Names=10-year,25-year,50-year,1pct_min,100-year,1pct_plu,500-year
River Rch & RM= UNT 041 IN CACR,Reach-1,8431
     789    1099    1362    1239    1675    2265    2539
River Rch & RM= UNT 041 IN CACR,Reach-1,5236
    1014    1422    1769    1613    2182    2951    3326
Boundary for River Rch & Prof#=UNT 041 IN CACR,Reach-1,1
Up Type=0
Dn Type=3
Dn Slope=0.005
Boundary for River Rch & Prof#=UNT 041 IN CACR,Reach-1,2
Up Type=0
Dn Type=3
Dn Slope=0.005
Boundary for River Rch & Prof#=UNT 041 IN CACR,Reach-1,3
Up Type=0
Dn Type=3
Dn Slope=0.005
Boundary for River Rch & Prof#=UNT 041 IN CACR,Reach-1,4
Up Type=0
Dn Type=3
Dn Slope=0.005
Boundary for River Rch & Prof#=UNT 041 IN CACR,Reach-1,5
Up Type=0
Dn Type=3
Dn Slope=0.005
Boundary for River Rch & Prof#=UNT 041 IN CACR,Reach-1,6
Up Type=0
Dn Type=3
Dn Slope=0.005
Boundary for River Rch & Prof#=UNT 041 IN CACR,Reach-1,7
Up Type=0
Dn Type=3
Dn Slope=0.005

--- UNT 041 IN CACR.g01 (geometry) ---

Geom Title=Existing Conditions
Program Version=4.10

River Reach=UNT 041 IN CACR ,Reach-1
Reach XY= 30
      3682599.28     10765817.77      3682634.75       10765793.
        3682739.       10765425.       3682719.5       10764160.
       3682535.5       10763670.      3682337.75       10763535.
      3682064.25       10763204.      3682011.75       10762867.
      3681983.75       10762798.        3681912.       10762729.
       3681910.5       10762681.        3681989.       10762590.
        3681967.       10762357.       3682028.5       10762180.
       3682032.5       10761921.        3682113.       10761730.
       3682033.5       10761481.        3681642.       10761063.
        3681634.       10761013.       3681681.5       10760977.
      3681646.25       10760944.       3681642.5       10760837.
       3681572.5       10760790.      3681587.75       10760386.
      3681498.25       10760187.        3681431.       10759829.
        3681240.       10759671.      3681155.25       10759558.
      3681268.25       10759194.       3681084.5       10758225.

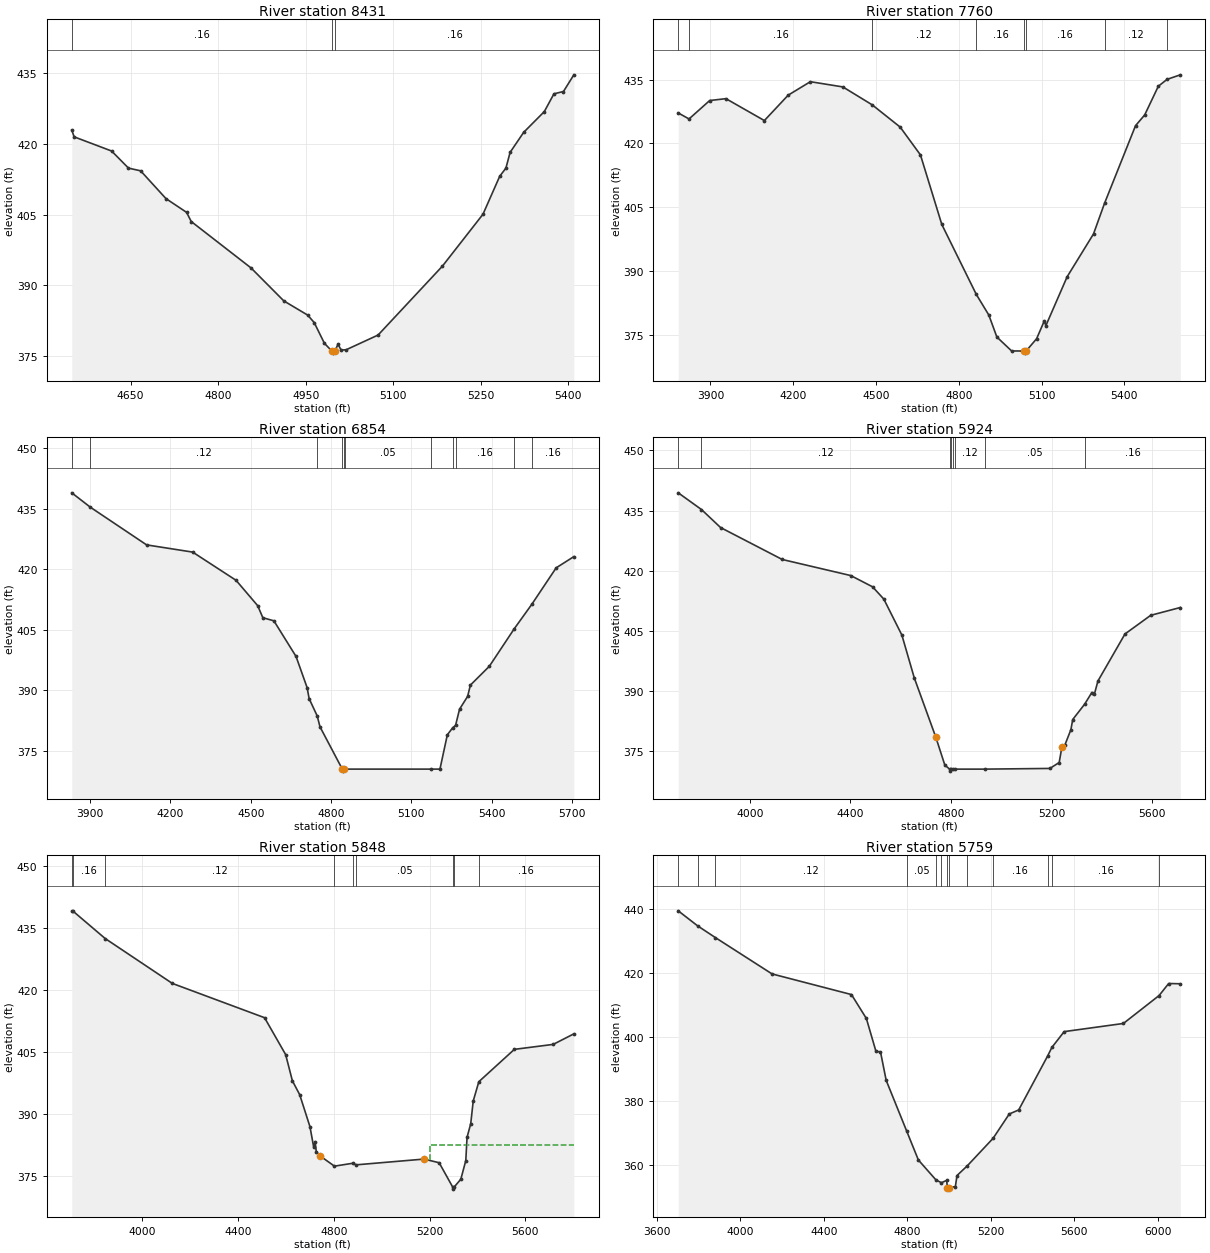
Type RM Length L Ch R = 1 ,8431    ,671,671,671
BEGIN DESCRIPTION:
UNT 041 IN CACR 10.0
END DESCRIPTION:
XS GIS Cut Line= 3
       3683010.9     10766025.26      3682772.19     10765838.64
      3682263.37     10765611.29
#Sta/Elev= 30
  4549.2  422.87  4553.3  421.44  4617.5  418.44  4646.4  414.82  4667.2  414.25
  4710.6  408.37  4745.9  405.46  4753.9  403.52  4856.4  393.69  4912.5  386.72
  4953.4  383.71  4964.6  382.13  4982.1  377.74  4994.4  376.16  4997.2  375.66
  5000.4  376.16  5005.3  377.53  5010.8  376.32  5019.3  376.37  5074.1  379.49
  5184.2  394.06  5253.8  405.06  5282.5   413.1  5293.1  414.82  5300.3  418.16
  5323.5  422.39  5358.9  426.79  5375.4  430.55  5391.7  431.04  5409.5  434.57
#Mann= 3 ,-1 , 0
  4549.2     .16       0  4994.4     .07       0  5000.4     .16       0
Bank Sta=4994.4,5000.4
XS Rating Curve= 0 ,0
Exp/Cntr=0.3,0.1

Type RM Length L Ch R = 1 ,7760    ,906,906,906
BEGIN DESCRIPTION:
Mapping XS b3684318
END DESCRIPTION:
XS GIS Cut Line= 3
      3683833.35     10765602.07      3683275.66     10765280.91
      3682134.37     10764996.67
#Sta/Elev= 30
  3783.3  427.16  3822.4  425.75  3897.3  430.07  3956.2  430.51  4095.5  425.37
  4181.8  431.33  4262.2  434.49  4380.1  433.26  4486.5  429.05  4587.7  423.84
  4661.2  417.31  4738.6     401  4863.7  384.58    4909  379.75  4938.1   374.6
  4991.6  371.33  5038.1  371.32  5040.9  370.82  5044.1  371.32  5082.3  374.21
  5110.3  378.42  5115.5  377.23  5192.9  388.74  5288.4  398.78  5328.4  405.97
  5440.7  424.17  5473.9  426.69  5523.3  433.42  5554.8  435.03    5603   436.1
#Mann= 8 ,-1 , 0
  3783.3     .12       0  3822.4     .16       0  4486.5     .12       0
  4863.7     .16       0  5038.1     .07       0  5044.1     .16       0
  5328.4     .12       0  5554.8     .16       0
Bank Sta=5038.1,5044.1
XS Rating Curve= 0 ,0
Exp/Cntr=0.3,0.1

Type RM Length L Ch R = 1 ,6854    ,930,930,930
BEGIN DESCRIPTION:
Mapping XS 02065cdb
END DESCRIPTION:
XS GIS Cut Line= 2
        3683850.     10763940.86      3682035.76     10764413.95
#Sta/Elev= 30
  3831.7  438.98    3901  435.42  4111.1  426.08  4283.2  424.29  4445.2   417.3
  4526.1     411  4545.2  408.03  4586.5  407.26  4669.2  398.43  4710.5  390.71
  4718.2  387.96  4748.2  383.69  4758.7  380.98  4841.9  370.51  4844.6  370.01
  4847.9  370.51  4851.6  370.51  5173.9  370.51  5206.6  370.51  5234.2  379.02
  5253.8  380.72    5265  381.37  5279.8  385.36  5309.9  388.53  5320.3  391.33
    5391  395.99    5484  405.29  5549.6  411.35  5640.6  420.39  5706.6  423.17
#Mann= 11 ,-1 , 0
  3831.7     .16       0    3901     .12       0  4748.2     .16       0
  4841.9    .033       0  4847.9     .16       0  4851.6     .05       0
  5173.9     .16       0  5253.8     .12       0    5265     .16       0
    5484     .12       0  5549.6     .16       0
Bank Sta=4841.9,4847.9
XS Rating Curve= 0 ,0
Exp/Cntr=0.3,0.1

Type RM Length L Ch R = 1 ,5924    ,76,76,76
BEGIN DESCRIPTION:
Mapping XS 8ee2c543
END DESCRIPTION:
XS GIS Cut Line= 4
      3683294.46     10762690.85      3682404.71     10763298.49
      3682239.78     10763524.18      3682001.78     10764117.01
#Sta/Elev= 30
  3715.3  439.44  3807.7  435.27  3883.6  430.78  4128.8  422.81  4401.1   418.8
  4487.8  415.99  4532.5  412.93  4604.3  403.95  4653.6  393.27  4739.1  378.49
    4775  371.53    4794  370.51  4796.7  370.01    4800  370.51  4805.7  370.51
  4814.8  370.51  4932.9  370.51  5192.7  370.68  5229.6  372.16  5240.4  376.03
  5251.9  376.48  5276.1  380.34  5283.5  382.89  5330.8  386.71  5359.4  389.62
  5369.7  389.24  5383.6  392.49  5491.2  404.23  5593.4  408.88  5711.1  410.83
#Mann= 8 ,-1 , 0
  3715.3     .16       0  3807.7     .12       0    4794    .033       0
    4800     .12       0  4805.7     .05       0  4814.8     .12       0
  4932.9     .05       0  5330.8     .16       0
Bank Sta=4739.1,5240.4
XS Rating Curve= 0 ,0
Exp/Cntr=0.3,0.1

Type RM Length L Ch R = 1 ,5848    ,89,89,89
BEGIN DESCRIPTION:
Mapping XS d3a7af0a
END DESCRIPTION:
XS GIS Cut Line= 4
      3683281.43     10762665.69      3682406.45      10763200.4
      3682118.25     10763547.62      3681962.42     10764146.71
#Sta/Elev= 30
  3706.4  439.27    3710  439.27  3845.8  432.57    4126  421.71  4511.1  413.41
  4599.2  404.48  4627.2  398.15  4657.8  394.78  4700.7  387.02  4716.2   382.1
  4722.1  383.43    4727  380.98  4744.2  379.91  4802.8  377.49  4878.5  378.18
  4893.9  377.81  5176.5   379.2  5239.9  378.32  5296.4  372.43  5299.1  371.93
  5302.4  372.43  5330.4  374.33  5351.1  378.84  5356.3  384.45  5371.7  387.77
  5382.1  393.25  5405.5  397.92  5553.8  405.75  5715.9  406.95  5802.1   409.5
#Mann= 9 ,-1 , 0
  3706.4     .12       0    3710     .16       0  3845.8     .12       0
  4802.8     .05       0  4878.5     .12       0  4893.9     .05       0
  5296.4     .03       0  5302.4     .05       0  5405.5     .16       0
#XS Ineff= 2 , 0
                         5200.28          382.62
Permanent Ineff=
       F       F
Bank Sta=4744.2,5176.5
XS Rating Curve= 0 ,0
Exp/Cntr=0.3,0.1

Type RM Length L Ch R = 1 ,5759    ,523,523,523
BEGIN DESCRIPTION:
Mapping XS 2424d7c6
END DESCRIPTION:
XS GIS Cut Line= 5
      3683267.56     10762644.84       3682274.5      10763224.7
      3682107.84     10763422.62      3681979.36     10763603.18
      3681909.91     10764374.05
#Sta/Elev= 30
  3702.8  439.44  3795.2  434.76  3880.4  431.08    4152   419.7  4532.4  413.24
  4603.7  405.76  4649.8  395.43  4671.3  395.34  4698.6   386.4  4797.4  370.43
  4852.7  361.49  4937.3  355.23    4963  354.38  4988.2  355.09  4991.8  352.87
  4994.5  352.37  4997.8  352.87  5029.9  353.15  5037.7  356.62  5087.1  359.67
  5210.6  368.27    5288  375.88  5333.1  377.14  5471.2  393.96    5492  396.71
    5551  401.65  5834.5   404.2  6005.5  412.94  6051.4   416.7  6107.1  416.62
#Mann= 13 ,-1 , 0
  3702.8     .12       0  3795.2     .16       0  3880.4     .12       0
  4797.4     .05       0  4937.3     .12       0    4963     .16       0
  4991.8     .07       0  4997.8     .16       0  5087.1     .05       0
  5210.6     .16       0  5471.2     .05       0    5492     .16       0
  6005.5     .12       0
Bank Sta=4991.8,4997.8
XS Rating Curve= 0 ,0
Exp/Cntr=0.3,0.1

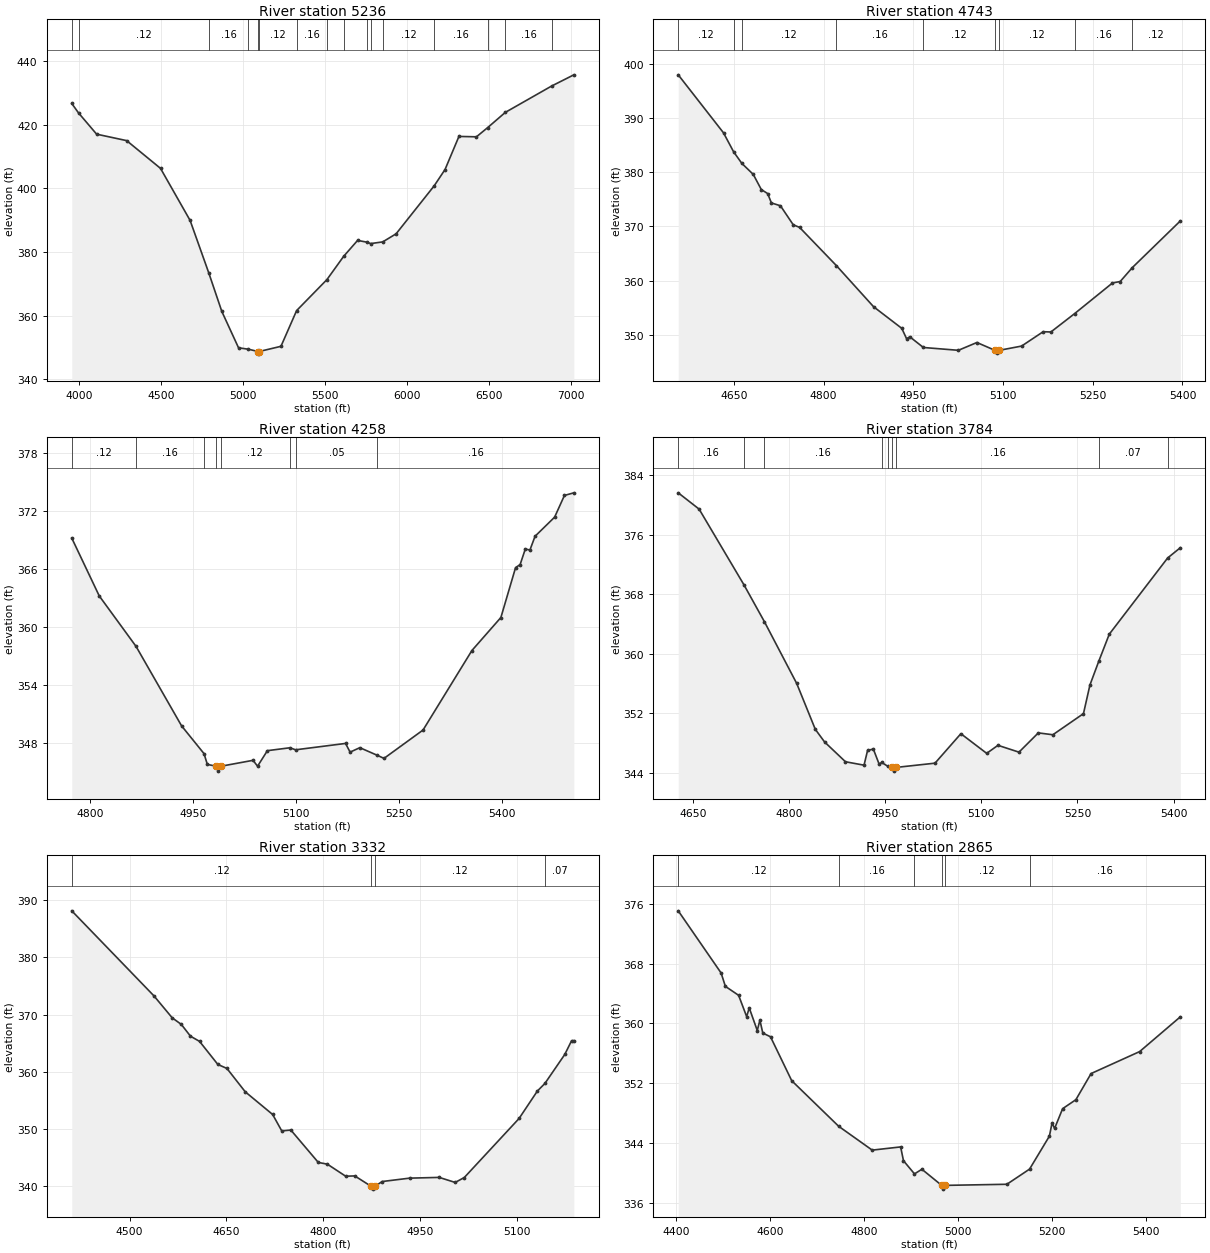
Type RM Length L Ch R = 1 ,5236    ,493,493,493
BEGIN DESCRIPTION:
Mapping XS 6e8a92bf
END DESCRIPTION:
XS GIS Cut Line= 3
      3683038.42     10762672.62        3681712.     10762929.56
      3680628.95     10764255.61
#Sta/Elev= 30
  3954.5  426.65    3996  423.67  4106.1  417.01  4289.4  414.98    4496  406.26
  4676.5  389.91  4789.9   373.5    4870  361.32    4972   349.9  5032.2  349.46
  5091.1  348.73  5093.9  348.23  5097.1  348.73  5230.8  350.37  5326.3  361.59
  5511.3  371.33  5613.7  378.66  5698.4  383.64  5756.6  383.07    5778  382.64
  5851.7  383.17  5933.2  385.71  6165.1  400.75  6231.9  405.91  6316.6   416.3
  6423.5  416.18  6492.6   419.1  6599.5  423.85  6881.4  432.11  7017.7  435.65
#Mann= 16 ,-1 , 0
  3954.5     .16       0    3996     .12       0  4789.9     .16       0
  5032.2     .12       0  5091.1     .07       0  5097.1     .12       0
  5326.3     .16       0  5511.3     .12       0  5613.7     .16       0
  5756.6     .12       0    5778     .16       0  5851.7     .12       0
  6165.1     .16       0  6492.6     .12       0  6599.5     .16       0
  6881.4     .12       0
Bank Sta=5091.1,5097.1
XS Rating Curve= 0 ,0
Exp/Cntr=0.3,0.1

Type RM Length L Ch R = 1 ,4743    ,485,485,485
BEGIN DESCRIPTION:
UNT 041 IN CACR 9.0
END DESCRIPTION:
XS GIS Cut Line= 3
      3682399.62     10762610.19      3681999.61     10762460.19
      3681599.64      10762360.2
#Sta/Elev= 30
  4556.9  397.95  4632.6  387.25  4649.5  383.75  4663.3  381.61  4682.4  379.58
  4695.8  376.79  4706.4  376.05  4712.7  374.32  4727.8   373.8  4749.2  370.29
  4759.8  369.81  4821.2  362.78  4883.5  355.18  4930.7  351.19  4938.7  349.28
  4944.1  349.63  4966.8  347.66  5025.3  347.14  5056.3  348.58  5086.8  347.12
  5089.5  346.62  5092.8  347.12    5131  347.92  5167.1  350.57    5180  350.52
  5219.7  353.91    5283  359.56  5295.9  359.83  5316.3  362.41  5396.4     371
#Mann= 9 ,-1 , 0
  4556.9     .12       0  4649.5     .16       0  4663.3     .12       0
  4821.2     .16       0  4966.8     .12       0  5086.8     .07       0
  5092.8     .12       0  5219.7     .16       0  5316.3     .12       0
Bank Sta=5086.8,5092.8
XS Rating Curve= 0 ,0
Exp/Cntr=0.3,0.1

Type RM Length L Ch R = 1 ,4258    ,474,474,474
BEGIN DESCRIPTION:
UNT 041 IN CACR 8.0
END DESCRIPTION:
XS GIS Cut Line= 3
      3682249.62     10762010.19      3682049.61     10762010.19
      3681649.62      10761660.2
#Sta/Elev= 30
    4773  369.19    4813   363.2  4866.7  357.96    4933  349.73  4965.7  346.85
  4970.5  345.74  4983.8  345.54  4986.5  345.04  4989.8  345.54  5037.1  346.16
  5043.7  345.55    5058  347.16  5090.8  347.46  5099.1  347.25  5171.9  347.91
  5178.5  347.01  5192.7  347.47  5218.1  346.68  5227.9  346.36  5284.8   349.3
    5356  357.54  5398.2  360.96  5419.6  366.13  5426.2  366.44  5433.8  368.06
  5440.5  367.95    5448  369.38  5476.5  371.36  5490.8  373.61  5504.5  373.88
#Mann= 8 ,-1 , 0
    4773     .12       0  4866.7     .16       0  4965.7     .12       0
  4983.8     .07       0  4989.8     .12       0  5090.8     .16       0
  5099.1     .05       0  5218.1     .16       0
Bank Sta=4983.8,4989.8
XS Rating Curve= 0 ,0
Exp/Cntr=0.3,0.1

Type RM Length L Ch R = 1 ,3784    ,452,452,452
BEGIN DESCRIPTION:
UNT 041 IN CACR 7.0
END DESCRIPTION:
XS GIS Cut Line= 3
      3682399.61     10761410.19      3682049.61     10761560.19
      3681649.61     10761610.19
#Sta/Elev= 30
  4626.7  381.64  4659.3  379.45  4729.4  369.26  4761.1  364.34  4811.7  356.01
  4840.7  349.85  4855.2  348.15  4887.8  345.49  4916.8  345.03  4922.3  347.01
  4931.3   347.2  4940.4  345.16  4944.3   345.4  4953.7  344.89    4961  344.73
  4963.7  344.23    4967  344.73  5027.6   345.3    5068  349.26  5108.3  346.62
  5125.9   347.7  5158.7  346.78  5188.9  349.37  5211.6  349.12  5259.4  351.96
  5269.5  355.81  5283.2  358.98  5299.7  362.64  5390.8  372.88  5410.6  374.26
#Mann= 9 ,-1 , 0
  4626.7     .16       0  4729.4     .12       0  4761.1     .16       0
  4944.3     .12       0  4953.7     .16       0    4961     .07       0
    4967     .16       0  5283.2     .07       0  5390.8     .05       0
Bank Sta=4961,4967
XS Rating Curve= 0 ,0
Exp/Cntr=0.3,0.1

Type RM Length L Ch R = 1 ,3332    ,467,467,467
BEGIN DESCRIPTION:
UNT 041 IN CACR 6.0
END DESCRIPTION:
XS GIS Cut Line= 3
      3682199.63     10760810.17      3681799.61     10761210.19
      3681649.64     10761360.16
#Sta/Elev= 30
  4410.4  388.14  4537.7  373.27    4566  369.43  4580.1  368.28  4594.3  366.22
  4608.4  365.31  4636.7  361.28  4650.8  360.58  4679.1   356.5  4721.6  352.53
  4735.7  349.66  4749.8  349.81  4792.3  344.15  4806.4  343.84  4834.7  341.74
  4848.8  341.79  4874.1  339.98  4876.9  339.48  4880.1  339.98  4891.3  340.81
  4933.7   341.4  4979.6  341.53  5004.4  340.65  5018.5  341.51  5103.4  351.84
  5131.7  356.63  5143.3  357.95  5174.1  363.02  5184.7  365.43  5188.2  365.43
#Mann= 4 ,-1 , 0
  4410.4     .12       0  4874.1     .07       0  4880.1     .12       0
  5143.3     .07       0
Bank Sta=4874.1,4880.1
XS Rating Curve= 0 ,0
Exp/Cntr=0.3,0.1

Type RM Length L Ch R = 1 ,2865    ,558,558,558
BEGIN DESCRIPTION:
UNT 041 IN CACR 5.0
END DESCRIPTION:
XS GIS Cut Line= 2
      3682181.87      10760600.1      3681218.37     10761063.63
#Sta/Elev= 30
  4403.8  375.06  4495.1  366.74  4504.2  364.95  4532.4  363.75  4549.5   360.9
    4555  362.07  4572.1  359.04  4577.7  360.42  4583.9   358.7  4600.3   358.2
  4645.5  352.32  4745.5  346.22  4816.9  343.03  4877.4  343.46  4883.5  341.61
  4906.9  339.85  4922.7  340.47  4964.9  338.31  4967.7  337.81  4970.9  338.31
  5103.7  338.46    5152  340.49  5194.2   344.9  5199.8  346.65  5205.3  345.94
  5222.4  348.58  5250.6  349.78    5283  353.28  5386.4  356.22    5473  360.87
#Mann= 6 ,-1 , 0
  4403.8     .12       0  4745.5     .16       0  4906.9     .12       0
  4964.9     .07       0  4970.9     .12       0    5152     .16       0
Bank Sta=4964.9,4970.9
XS Rating Curve= 0 ,0
Exp/Cntr=0.3,0.1

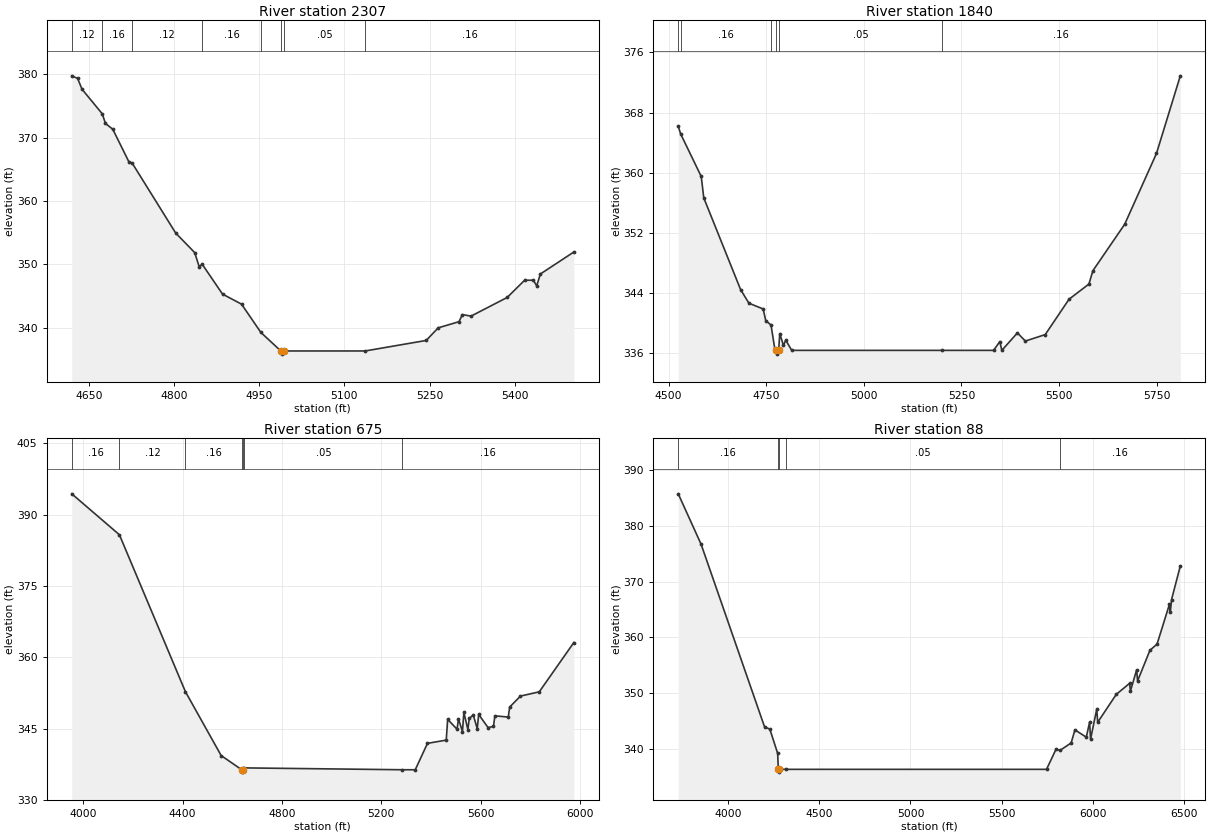
Type RM Length L Ch R = 1 ,2307    ,467,467,467
BEGIN DESCRIPTION:
UNT 041 IN CACR 4.0
END DESCRIPTION:
XS GIS Cut Line= 3
      3681949.62     10760260.19      3681549.61     10760360.19
      3681149.62     10760610.18
#Sta/Elev= 30
  4620.1  379.77  4630.4  379.36  4638.1  377.66  4673.8  373.77  4679.4  372.25
  4692.3  371.34  4720.6  366.21  4726.7  365.96  4803.1  354.95  4836.6  351.86
  4844.3  349.67    4850     350  4885.5  345.32    4919  343.73    4953  339.27
  4988.2  336.34  4990.9  335.84  4994.2  336.34  5136.7  336.34  5244.1     338
  5265.3  339.99  5301.9  340.96  5307.8  342.08  5323.1  341.84  5386.8  344.79
  5417.4   347.5  5432.8  347.51  5438.7  346.62  5445.2  348.49  5504.1  351.96
#Mann= 8 ,-1 , 0
  4620.1     .12       0  4673.8     .16       0  4726.7     .12       0
    4850     .16       0    4953     .05       0  4988.2    .033       0
  4994.2     .05       0  5136.7     .16       0
Bank Sta=4988.2,4994.2
XS Rating Curve= 0 ,0
Exp/Cntr=0.3,0.1

Type RM Length L Ch R = 1 ,1840    ,1165,1165,1165
BEGIN DESCRIPTION:
UNT 041 IN CACR 3.0
END DESCRIPTION:
XS GIS Cut Line= 3
      3681849.58     10759660.21      3681449.61     10759910.19
      3680649.61     10759760.19
#Sta/Elev= 30
  4524.8  366.16  4531.4  365.11  4583.7  359.49  4590.2  356.64  4684.5  344.43
  4705.8  342.62  4742.3  341.85  4748.8  340.31  4762.4  339.71  4772.4  336.43
  4775.9  336.34  4778.6  335.84  4781.9  336.34  4784.8  338.58  4794.2  336.99
  4800.1   337.7  4815.4  336.34  5200.8  336.34  5332.2  336.34  5348.3  337.51
  5353.4  336.34  5393.3  338.67  5413.6  337.58  5464.5  338.44  5525.5  343.15
  5576.4  345.17  5586.6  346.95    5668  353.13  5749.4  362.56  5810.4  372.89
#Mann= 6 ,-1 , 0
  4524.8     .12       0  4531.4     .16       0  4762.4     .05       0
  4775.9    .033       0  4781.9     .05       0  5200.8     .16       0
Bank Sta=4775.9,4781.9
XS Rating Curve= 0 ,0
Exp/Cntr=0.3,0.1

Type RM Length L Ch R = 1 ,675     ,587,587,587
BEGIN DESCRIPTION:
UNT 041 IN CACR 2.0
END DESCRIPTION:
XS GIS Cut Line= 4
      3682093.35     10759365.71      3681358.99     10758839.67
      3681155.86     10758907.38      3680718.34     10759699.09
#Sta/Elev= 30
  3953.7  394.35  4145.6  385.74  4411.3  352.76  4555.3  339.33  4638.2  336.34
    4641  335.84  4644.2  336.34  4648.5  336.73  5285.5  336.34    5337  336.34
  5386.2  341.89  5461.8  342.57  5467.5  346.94  5505.4  344.86  5511.1  347.04
  5527.1  344.38  5532.8   348.4  5548.9   344.8  5554.6  347.13  5570.6  347.85
  5586.7  344.98  5592.4  347.97  5630.2  345.21    5652  345.46  5657.7  347.67
  5711.6  347.42  5717.3  349.52  5760.8  351.83  5836.4  352.72  5975.7  363.09
#Mann= 7 ,-1 , 0
  3953.7     .16       0  4145.6     .12       0  4411.3     .16       0
  4638.2    .033       0  4644.2     .16       0  4648.5     .05       0
  5285.5     .16       0
Bank Sta=4638.2,4644.2
XS Rating Curve= 0 ,0
Exp/Cntr=0.3,0.1

Type RM Length L Ch R = 1 ,88      ,0,0,0
BEGIN DESCRIPTION:
UNT 041 IN CACR 1.0
END DESCRIPTION:
XS GIS Cut Line= 4
      3682093.39     10759053.24      3681150.65     10758287.59
      3680978.78     10758365.71      3680609.36     10759666.49
#Sta/Elev= 30
  3725.4  385.77  3850.9  376.72  4199.3  343.94  4228.1  343.56  4271.2  339.19
  4274.6  336.34  4277.4  335.84  4280.6  336.34  4317.3  336.34  5746.7  336.34
  5798.1   339.9  5822.7  339.78  5881.8  341.08  5902.6  343.42    5965  342.11
  5983.2  344.82  5988.4  341.77  6022.3  347.14  6027.5  344.78  6129.2  349.78
  6202.2  351.76  6207.4   350.4  6241.3   354.2  6246.4   352.2  6314.2   357.7
  6353.3  358.81  6421.1  365.93  6426.3  364.61  6432.8   366.8  6480.9  372.82
#Mann= 5 ,-1 , 0
  3725.4     .16       0  4274.6    .033       0  4280.6     .16       0
  4317.3     .05       0  5822.7     .16       0
Bank Sta=4274.6,4280.6
XS Rating Curve= 0 ,0
Exp/Cntr=0.3,0.1

Chan Stop Cuts=-1
Use User Specified Reach Order=0
Composite Channel Slope=5