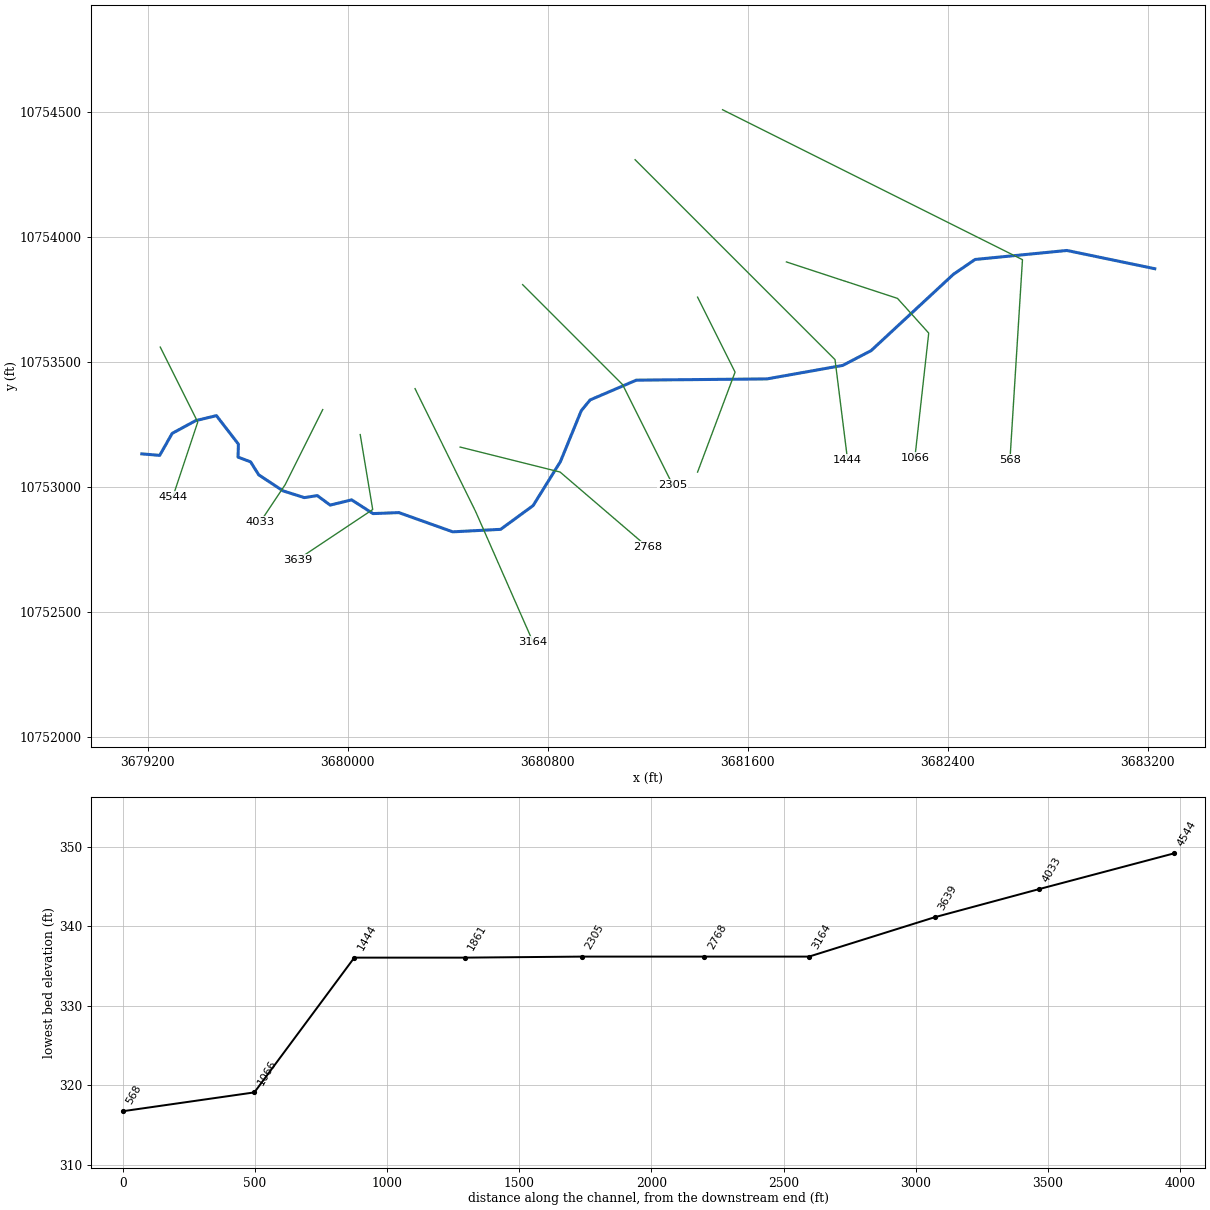
--- UNT 042 IN CACR.prj (project) ---

Proj Title=UNT 042 IN CACR Base Level Engineering
Current Plan=p01
Default Exp/Contr=0.3,0.1
English Units
Geom File=g01
Flow File=f01
Plan File=p01
BEGIN DESCRIPTION:
UNT 042 IN CACR
END DESCRIPTION:

--- UNT 042 IN CACR.p01 (plan) ---

Plan Title=Multiple Run
Short Identifier=Multiple
Geom File=g01
Flow File=f01
Subcritical Flow
K Sum by GR= 0
Std Step Tol= 0.01
Critical Tol= 0.01
Num of Std Step Trials= 20
Max Error Tol= 0.3
Flow Tol Ratio= 0.001
Split Flow NTrial= 30
Split Flow Tol= 0.02
Split Flow Ratio= 0.02
Log Output Level= 0
Friction Slope Method= 1
Unsteady Friction Slope Method= 2
Unsteady Bridges Friction Slope Method= 1
Parabolic Critical Depth
Global Vel Dist=  1 , 1 , 1
Global Log Level= 0
CheckData=True
Encroach Param= -1, 0, 0, 0
BEGIN DESCRIPTION:
Multiple Run
END DESCRIPTION:

--- UNT 042 IN CACR.f01 (steady flow) ---

Flow Title=Multiple
Number of Profiles=7
Profile Names=10-year,25-year,50-year,1pct_min,100-year,1pct_plu,500-year
River Rch & RM= UNT 042 IN CACR,Reach-1,4544
     721     995    1225    1107    1497    2024    2238
River Rch & RM= UNT 042 IN CACR,Reach-1,3164
    1015    1425    1774    1619    2189    2961    3343
Boundary for River Rch & Prof#=UNT 042 IN CACR,Reach-1,1
Up Type=0
Dn Type=3
Dn Slope=0.005
Boundary for River Rch & Prof#=UNT 042 IN CACR,Reach-1,2
Up Type=0
Dn Type=3
Dn Slope=0.005
Boundary for River Rch & Prof#=UNT 042 IN CACR,Reach-1,3
Up Type=0
Dn Type=3
Dn Slope=0.005
Boundary for River Rch & Prof#=UNT 042 IN CACR,Reach-1,4
Up Type=0
Dn Type=3
Dn Slope=0.005
Boundary for River Rch & Prof#=UNT 042 IN CACR,Reach-1,5
Up Type=0
Dn Type=3
Dn Slope=0.005
Boundary for River Rch & Prof#=UNT 042 IN CACR,Reach-1,6
Up Type=0
Dn Type=3
Dn Slope=0.005
Boundary for River Rch & Prof#=UNT 042 IN CACR,Reach-1,7
Up Type=0
Dn Type=3
Dn Slope=0.005

--- UNT 042 IN CACR.g01 (geometry) ---

Geom Title=Existing Conditions

River Reach=UNT 042 IN CACR,Reach-1
Reach XY= 30
      3679175.75     10753133.00      3679247.25     10753127.00
      3679297.25     10753215.00      3679391.25     10753266.00
      3679474.25     10753286.00      3679562.25     10753172.00
      3679560.75     10753120.00      3679611.00     10753101.00
      3679643.75     10753049.00      3679740.75     10752985.00
      3679825.75     10752958.00      3679878.00     10752966.00
      3679929.50     10752928.00      3680015.25     10752949.00
      3680100.75     10752894.00      3680204.25     10752898.00
      3680420.00     10752821.00      3680611.50     10752831.00
      3680741.50     10752926.00      3680850.75     10753102.00
      3680934.25     10753306.00      3680969.75     10753349.00
      3681154.50     10753428.00      3681677.25     10753433.00
      3681980.25     10753487.00      3682093.75     10753546.00
      3682423.75     10753852.00      3682510.00     10753911.00
      3682877.50     10753947.00      3683229.00     10753874.00

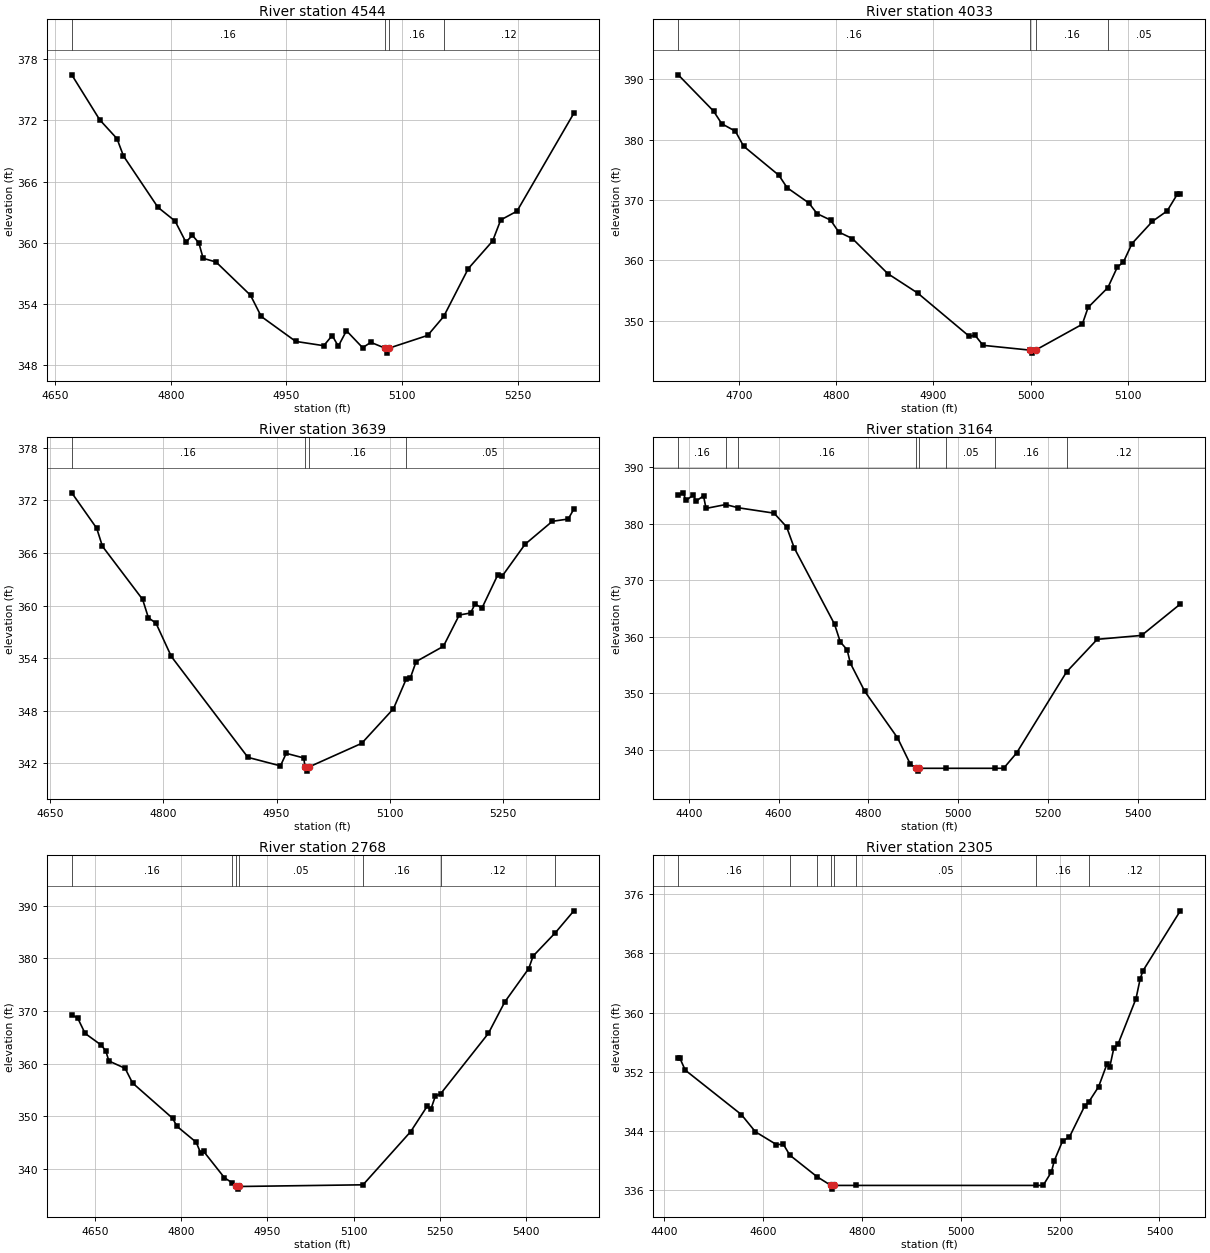
Type RM Length L Ch R = 1,4544,511,511,511
BEGIN DESCRIPTION:
UNT 042 IN CACR 10.0
END DESCRIPTION:
XS GIS Cut Line= 3
      3679249.62     10753560.17      3679399.61     10753260.19
      3679299.61     10752960.20
#Sta/Elev= 30
  4671.5  376.48  4707.8  372.06  4730.2  370.21  4738.6  368.51  4783.3  363.47
  4805.6  362.12  4819.6  360.05  4828.0  360.72  4836.4  359.98  4842.0  358.46
  4858.7  358.10  4903.5  354.83  4917.4  352.75  4962.2  350.30  4998.5  349.88
  5009.5  350.88  5017.4  349.83  5028.0  351.35  5049.0  349.68  5059.6  350.21
  5077.7  349.65  5080.4  349.15  5083.7  349.65  5133.4  350.89  5154.2  352.75
  5186.1  357.45  5217.7  360.16  5228.2  362.23  5249.3  363.09  5323.1  372.71
#Mann=4,-1,0
  4671.5    0.16       0  5077.7    0.07       0  5083.7    0.16       0
  5154.2    0.12       0
Bank Sta=5077.7,5083.7
Exp/Cntr=0.3,0.1

Type RM Length L Ch R = 1,4033,394,394,394
BEGIN DESCRIPTION:
UNT 042 IN CACR 9.0
END DESCRIPTION:
XS GIS Cut Line= 3
      3679899.61     10753310.19      3679749.61     10753010.19
      3679649.61     10752860.18
#Sta/Elev= 30
  4637.9  390.74  4674.2  384.73  4682.6  382.64  4696.6  381.40  4705.0  378.93
  4741.3  374.10  4749.7  372.05  4772.1  369.51  4780.5  367.75  4794.4  366.68
  4802.8  364.70  4816.8  363.62  4853.1  357.82  4883.9  354.59  4937.0  347.41
  4942.6  347.64  4951.0  345.94  4998.9  345.15  5001.6  344.65  5004.9  345.15
  5052.9  349.43  5058.9  352.22  5079.2  355.50  5089.0  358.93  5095.0  359.68
  5104.0  362.80  5125.0  366.48  5140.1  368.20  5150.6  370.99  5153.6  370.99
#Mann=4,-1,0
  4637.9    0.16       0  4998.9    0.07       0  5004.9    0.16       0
  5079.2    0.05       0
Bank Sta=4998.9,5004.9
Exp/Cntr=0.3,0.1

Type RM Length L Ch R = 1,3639,475,475,475
BEGIN DESCRIPTION:
UNT 042 IN CACR 8.0
END DESCRIPTION:
XS GIS Cut Line= 3
      3680049.60     10753210.23      3680099.61     10752910.19
      3679799.64     10752710.21
#Sta/Elev= 30
  4678.9  372.87  4711.9  368.83  4719.5  366.77  4772.7  360.71  4780.3  358.63
  4790.5  357.98  4810.7  354.20  4912.1  342.69  4955.2  341.72  4962.8  343.15
  4986.1  342.62  4987.6  341.62  4990.3  341.12  4993.6  341.62  5062.7  344.29
  5104.8  348.24  5121.5  351.59  5127.3  351.79  5134.8  353.62  5170.9  355.36
  5191.9  358.93  5206.9  359.16  5212.9  360.20  5221.9  359.71  5243.0  363.53
  5249.0  363.40  5279.0  367.00  5315.1  369.62  5336.1  369.88  5343.6  371.01
#Mann=4,-1,0
  4678.9    0.16       0  4987.6    0.07       0  4993.6    0.16       0
  5121.5    0.05       0
Bank Sta=4987.6,4993.6
Exp/Cntr=0.3,0.1

Type RM Length L Ch R = 1,3164,396,396,396
BEGIN DESCRIPTION:
UNT 042 IN CACR 7.0
END DESCRIPTION:
XS GIS Cut Line= 3
      3680268.96     10753394.11      3680511.99     10752901.09
      3680741.16     10752380.25
#Sta/Elev= 30
  4376.3  385.03  4387.7  385.47  4393.2  384.12  4410.1  385.07  4415.7  383.97
  4432.6  384.94  4438.2  382.71  4481.9  383.39  4510.4  382.82  4589.8  381.87
  4617.8  379.43  4634.7  375.72  4724.5  362.21  4737.4  359.05  4752.6  357.67
  4759.7  355.31  4791.9  350.30  4864.8  342.08  4893.5  337.40  4906.8  336.67
  4909.5  336.17  4912.8  336.67  4972.2  336.67  5082.5  336.67  5101.3  336.67
  5130.1  339.37  5241.7  353.76  5309.9  359.52  5408.7  360.21  5495.0  365.77
#Mann=8,-1,0
  4376.3    0.16       0  4481.9    0.12       0  4510.4    0.16       0
  4906.8   0.033       0  4912.8    0.16       0  4972.2    0.05       0
  5082.5    0.16       0  5241.7    0.12       0
Bank Sta=4906.8,4912.8
Exp/Cntr=0.3,0.1

Type RM Length L Ch R = 1,2768,463,463,463
BEGIN DESCRIPTION:
UNT 042 IN CACR 6.0
END DESCRIPTION:
XS GIS Cut Line= 3
      3680449.58     10753160.20      3680849.61     10753060.19
      3681199.60     10752760.20
#Sta/Elev= 30
  4609.8  369.26  4620.1  368.64  4633.0  365.73  4661.4  363.48  4669.1  362.36
  4674.3  360.50  4702.6  359.10  4715.5  356.32  4785.1  349.63  4792.8  348.09
  4826.3  345.06  4834.0  343.01  4839.2  343.33  4875.3  338.34  4888.1  337.41
  4895.4  336.67  4898.2  336.17  4901.4  336.67  5116.4  336.99  5199.4  347.10
  5227.9  351.89  5234.5  351.37  5242.2  353.82  5251.2  354.24  5334.4  365.73
  5362.9  371.69  5404.6  378.04  5412.3  380.42  5451.0  384.85  5483.1  389.00
#Mann=7,-1,0
  4609.8    0.16       0  4888.1    0.05       0  4895.4   0.033       0
  4901.4    0.05       0  5116.4    0.16       0  5251.2    0.12       0
  5451.0    0.16       0
Bank Sta=4895.4,4901.4
Exp/Cntr=0.3,0.1

Type RM Length L Ch R = 1,2305,444,444,444
BEGIN DESCRIPTION:
UNT 042 IN CACR 5.0
END DESCRIPTION:
XS GIS Cut Line= 3
      3680699.61     10753810.19      3681099.61     10753410.19
      3681299.61     10753010.19
#Sta/Elev= 30
  4429.1  353.82  4432.6  353.82  4443.2  352.24  4556.4  346.24  4584.7  343.92
  4627.1  342.19  4641.2  342.22  4654.2  340.76  4708.8  337.86  4737.2  336.67
  4740.0  336.17  4743.2  336.67  4787.6  336.67  5150.4  336.67  5165.3  336.67
  5182.1  338.51  5187.6  339.98  5204.4  342.66  5218.4  343.22  5249.1  347.40
  5257.9  348.00  5277.1  349.99  5293.9  353.04  5299.5  352.60  5307.8  355.20
  5316.2  355.72  5352.6  361.89  5360.9  364.53  5366.5  365.64  5442.0  373.75
#Mann=8,-1,0
  4429.1    0.16       0  4654.2    0.05       0  4708.8    0.16       0
  4737.2   0.033       0  4743.2    0.16       0  4787.6    0.05       0
  5150.4    0.16       0  5257.9    0.12       0
Bank Sta=4737.2,4743.2
Exp/Cntr=0.3,0.1

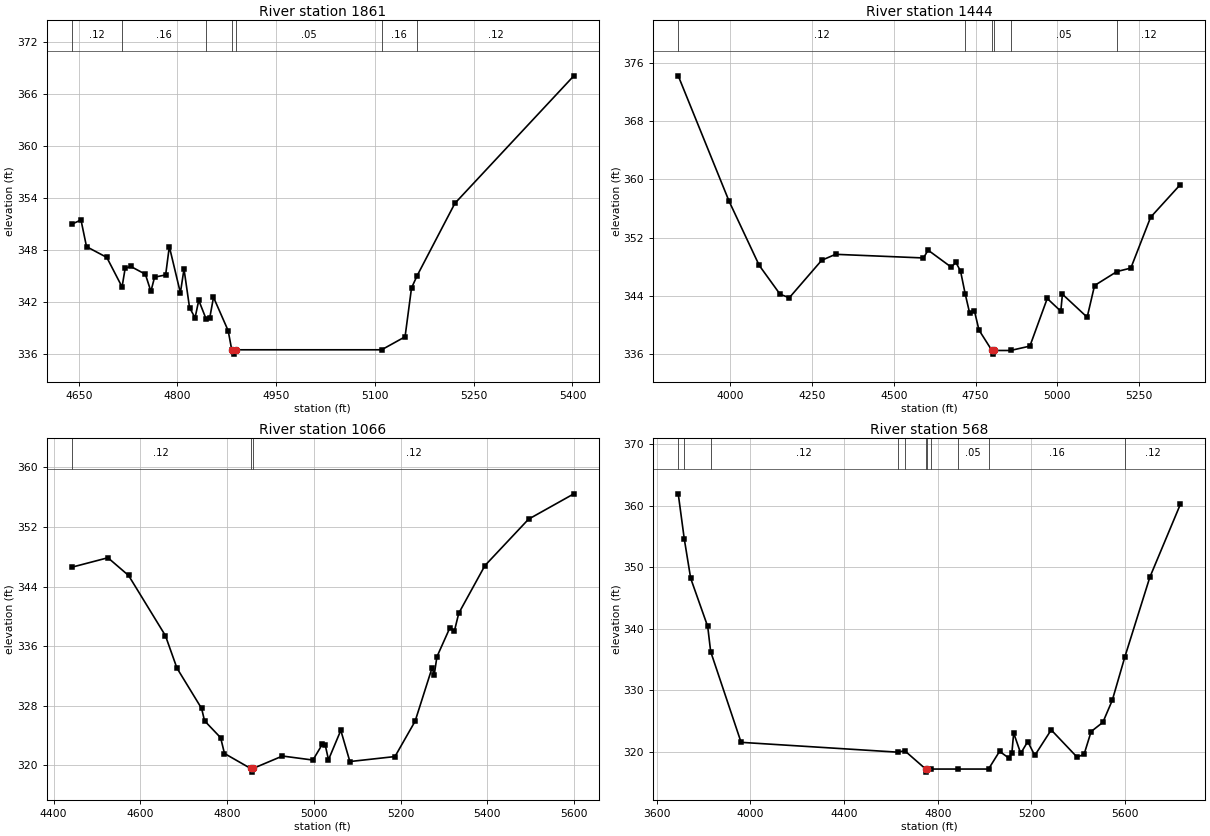
Type RM Length L Ch R = 1,1861,417,417,417
BEGIN DESCRIPTION:
UNT 042 IN CACR 4.0
END DESCRIPTION:
XS GIS Cut Line= 3
      3681399.59     10753760.23      3681549.61     10753460.19
      3681399.59     10753060.15
#Sta/Elev= 30
  4639.4  351.03  4653.4  351.52  4661.8  348.44  4692.6  347.20  4715.8  343.79
  4720.5  345.94  4728.9  346.16  4751.2  345.26  4759.6  343.28  4765.2  344.92
  4782.0  345.18  4787.6  348.45  4804.4  343.11  4809.9  345.86  4818.3  341.41
  4826.7  340.23  4832.3  342.25  4843.7  340.05  4849.1  340.26  4854.7  342.60
  4877.0  338.74  4882.4  336.54  4885.2  336.04  4888.4  336.54  5110.1  336.54
  5145.7  338.04  5155.5  343.67  5163.9  345.07  5221.4  353.44  5402.1  368.15
#Mann=7,-1,0
  4639.4    0.12       0  4715.8    0.16       0  4843.7    0.05       0
  4882.4   0.033       0  4888.4    0.05       0  5110.1    0.16       0
  5163.9    0.12       0
Bank Sta=4882.4,4888.4
Exp/Cntr=0.3,0.1

Type RM Length L Ch R = 1,1444,378,378,378
BEGIN DESCRIPTION:
UNT 042 IN CACR 3.0
END DESCRIPTION:
XS GIS Cut Line= 3
      3681149.62     10754310.18      3681949.61     10753510.19
      3681999.61     10753110.16
#Sta/Elev= 30
  3841.3  374.21  3996.9  356.99  4088.8  348.21  4152.4  344.26  4180.7  343.77
  4279.7  348.91  4322.1  349.73  4590.8  349.23  4605.0  350.30  4675.7  347.97
  4689.8  348.61  4704.0  347.46  4718.1  344.35  4732.2  341.62  4746.4  341.99
  4760.5  339.34  4800.0  336.54  4802.7  336.04  4806.0  336.54  4856.8  336.54
  4916.1  337.14  4969.1  343.67  5010.5  341.93  5015.5  344.26  5091.1  341.10
  5113.7  345.45  5182.2  347.37  5224.6  347.84  5285.1  354.82  5375.8  359.29
#Mann=6,-1,0
  3841.3    0.12       0  4718.1    0.16       0  4800.0    0.03       0
  4806.0    0.16       0  4856.8    0.05       0  5182.2    0.12       0
Bank Sta=4800,4806
Exp/Cntr=0.3,0.1

Type RM Length L Ch R = 1,1066,498,498,498
BEGIN DESCRIPTION:
UNT 042 IN CACR 2.0
END DESCRIPTION:
XS GIS Cut Line= 4
      3681755.10     10753901.07      3682199.49     10753755.26
      3682324.49     10753616.37      3682268.94     10753116.41
#Sta/Elev= 30
  4441.9  346.59  4525.3  347.86  4572.9  345.48  4657.8  337.41  4684.4  333.05
  4741.3  327.63  4748.0  325.98  4785.1  323.71  4794.0  321.59  4854.1  319.59
  4856.9  319.09  4860.1  319.59  4927.7  321.25  4997.9  320.71  5019.6  322.83
  5026.3  322.72  5033.8  320.75  5062.2  324.70  5083.1  320.51  5187.1  321.18
  5233.5  325.92  5272.6  333.08  5277.6  332.14  5283.8  334.57  5314.0  338.50
  5324.0  338.00  5334.1  340.41  5394.5  346.81  5495.1  353.04  5599.5  356.44
#Mann=3,-1,0
  4441.9    0.12       0  4854.1    0.07       0  4860.1    0.12       0
Bank Sta=4854.1,4860.1
Exp/Cntr=0.3,0.1

Type RM Length L Ch R = 1,568,0,0,0
BEGIN DESCRIPTION:
UNT 042 IN CACR 1.0
END DESCRIPTION:
XS GIS Cut Line= 3
      3681499.59     10754510.20      3682699.61     10753910.19
      3682649.61     10753110.21
#Sta/Elev= 30
  3692.3  361.93  3718.0  354.62  3745.4  348.21  3818.1  340.38  3830.7  336.31
  3960.6  321.56  4630.2  319.96  4659.0  320.20  4748.7  317.22  4751.4  316.72
  4754.7  317.22  4771.8  317.22  4884.7  317.22  5016.8  317.22  5064.0  320.10
  5104.1  318.98  5116.6  319.83  5124.1  323.08  5154.2  319.77  5184.3  321.68
  5214.3  319.43  5284.4  323.58  5394.7  319.16  5424.7  319.61  5454.8  323.31
  5504.9  324.81  5545.0  328.38  5599.1  335.48  5705.3  348.37  5835.5  360.21
#Mann=11,-1,0
  3692.3    0.12       0  3718.0    0.16       0  3830.7    0.12       0
  4630.2    0.16       0  4659.0    0.05       0  4748.7   0.033       0
  4754.7    0.05       0  4771.8    0.16       0  4884.7    0.05       0
  5016.8    0.16       0  5599.1    0.12       0
Bank Sta=4748.7,4754.7
Exp/Cntr=0.3,0.1

Chan Stop Cuts=-1