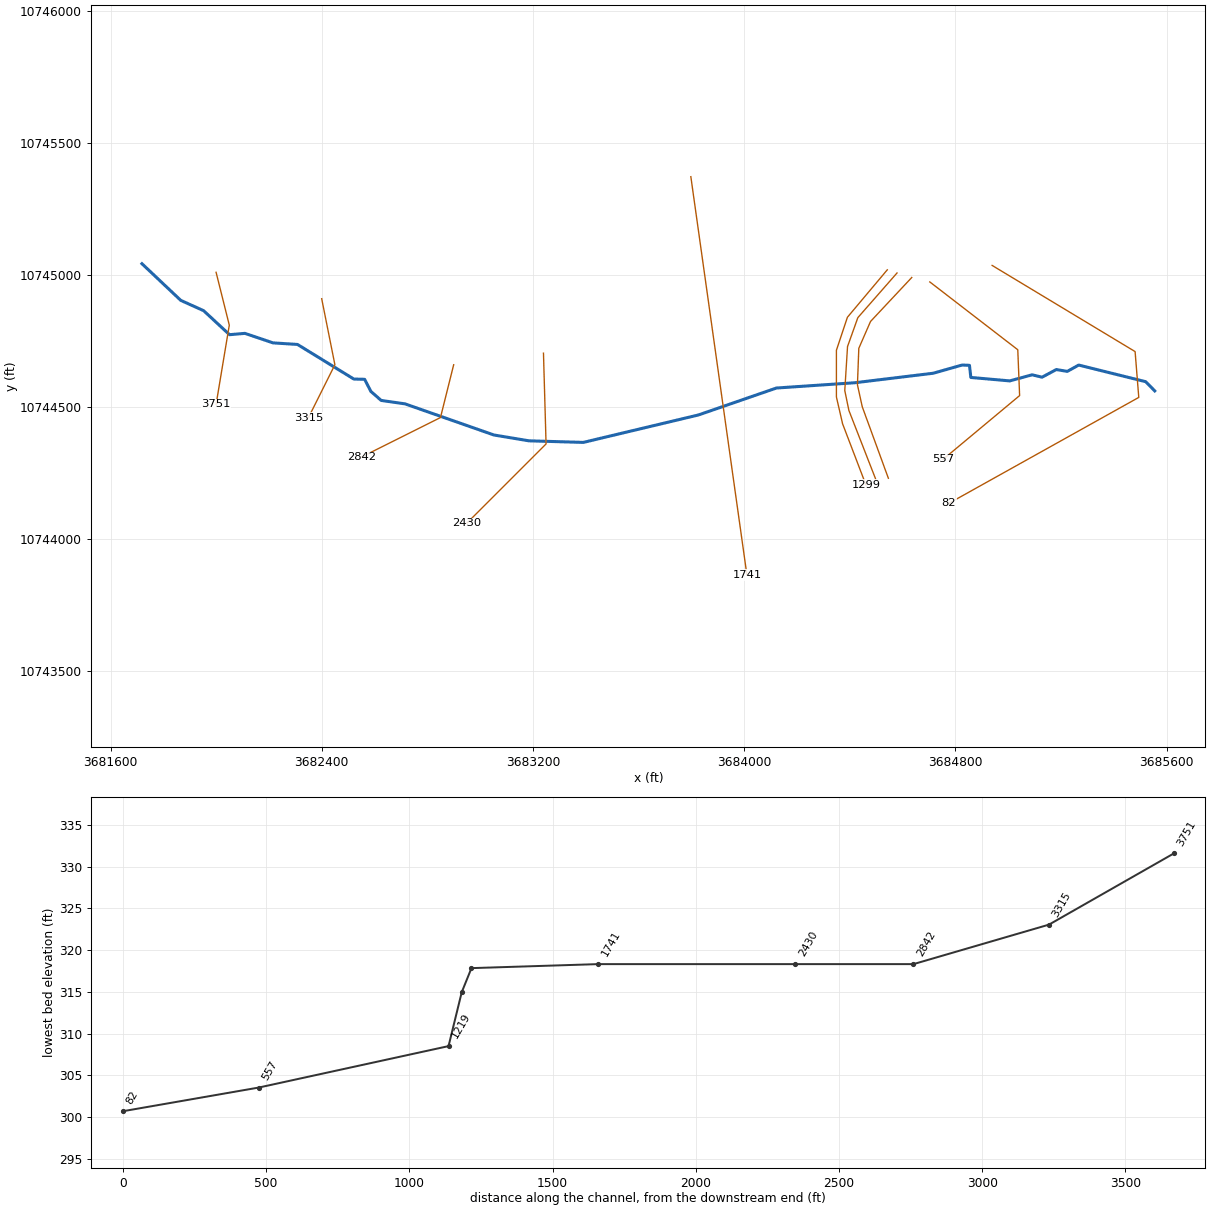
--- UNT 043 IN CACR.prj (project) ---

Proj Title=UNT 043 IN CACR Base Level Engineering
Current Plan=p01
Default Exp/Contr=0.3,0.1
English Units
Geom File=g01
Flow File=f01
Plan File=p01
BEGIN DESCRIPTION:
UNT 043 IN CACR
END DESCRIPTION:

--- UNT 043 IN CACR.p01 (plan) ---

Plan Title=Multiple Run
Short Identifier=Multiple
Geom File=g01
Flow File=f01
Subcritical Flow
K Sum by GR= 0
Std Step Tol= 0.01
Critical Tol= 0.01
Num of Std Step Trials= 20
Max Error Tol= 0.3
Flow Tol Ratio= 0.001
Split Flow NTrial= 30
Split Flow Tol= 0.02
Split Flow Ratio= 0.02
Log Output Level= 0
Friction Slope Method= 1
Unsteady Friction Slope Method= 2
Unsteady Bridges Friction Slope Method= 1
Parabolic Critical Depth
Global Vel Dist=  1 , 1 , 1
Global Log Level= 0
CheckData=True
Encroach Param= -1, 0, 0, 0
BEGIN DESCRIPTION:
Multiple Run
END DESCRIPTION:

--- UNT 043 IN CACR.f01 (steady flow) ---

Flow Title=Multiple
Number of Profiles=7
Profile Names=10-year,25-year,50-year,1pct_min,100-year,1pct_plu,500-year
River Rch & RM= UNT 043 IN CACR,Reach-1,3751
     704     970    1193    1077    1456    1969    2174
River Rch & RM= UNT 043 IN CACR,Reach-1,1741
     835    1161    1436    1302    1761    2382    2657
Boundary for River Rch & Prof#=UNT 043 IN CACR,Reach-1,1
Up Type=0
Dn Type=3
Dn Slope=0.005
Boundary for River Rch & Prof#=UNT 043 IN CACR,Reach-1,2
Up Type=0
Dn Type=3
Dn Slope=0.005
Boundary for River Rch & Prof#=UNT 043 IN CACR,Reach-1,3
Up Type=0
Dn Type=3
Dn Slope=0.005
Boundary for River Rch & Prof#=UNT 043 IN CACR,Reach-1,4
Up Type=0
Dn Type=3
Dn Slope=0.005
Boundary for River Rch & Prof#=UNT 043 IN CACR,Reach-1,5
Up Type=0
Dn Type=3
Dn Slope=0.005
Boundary for River Rch & Prof#=UNT 043 IN CACR,Reach-1,6
Up Type=0
Dn Type=3
Dn Slope=0.005
Boundary for River Rch & Prof#=UNT 043 IN CACR,Reach-1,7
Up Type=0
Dn Type=3
Dn Slope=0.005

--- UNT 043 IN CACR.g01 (geometry) ---

Geom Title=Existing Conditions

River Reach=UNT 043 IN CACR,Reach-1
Reach XY= 30
      3681718.65     10745042.93      3681865.75     10744904.00
      3681952.25     10744865.00      3682050.50     10744774.00
      3682108.75     10744779.00      3682215.25     10744743.00
      3682308.00     10744737.00      3682521.25     10744606.00
      3682562.25     10744605.00      3682586.00     10744559.00
      3682625.00     10744525.00      3682715.25     10744512.00
      3683052.25     10744394.00      3683184.75     10744372.00
      3683390.75     10744366.00      3683827.00     10744470.00
      3684122.25     10744572.00      3684419.25     10744592.00
      3684716.25     10744628.00      3684825.50     10744659.00
      3684853.50     10744658.00      3684858.75     10744612.00
      3685006.00     10744599.00      3685090.75     10744622.00
      3685128.50     10744613.00      3685182.50     10744642.00
      3685224.25     10744635.00      3685267.25     10744659.00
      3685521.00     10744596.00      3685555.50     10744561.00

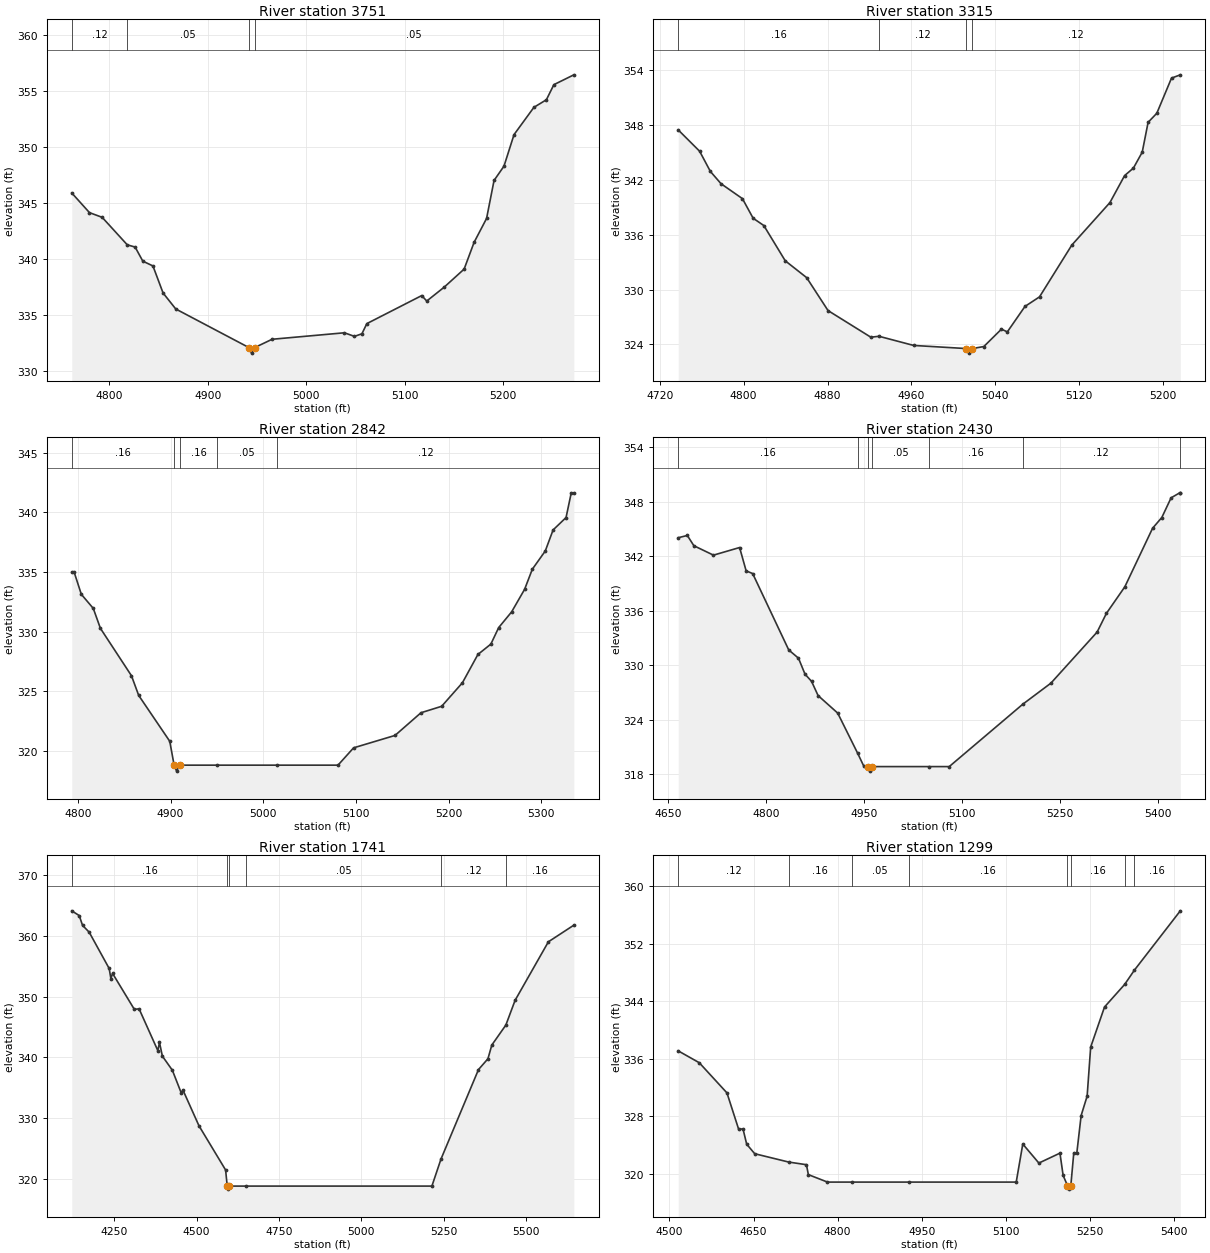
Type RM Length L Ch R = 1,3751,436,436,436
BEGIN DESCRIPTION:
UNT 043 IN CACR 8.0
END DESCRIPTION:
XS GIS Cut Line= 3
      3681999.61     10745010.19      3682049.61     10744810.19
      3681999.61     10744510.19
#Sta/Elev= 30
  4761.8  345.91  4779.8  344.15  4792.7  343.73  4818.2  341.27  4826.2  341.07
  4834.0  339.81  4844.3  339.38  4854.6  336.96  4867.5  335.53  4941.8  332.08
  4944.5  331.58  4947.8  332.08  4965.4  332.82  5038.9  333.40  5049.1  333.08
  5056.7  333.31  5061.7  334.22  5117.5  336.73  5122.6  336.24  5140.3  337.48
  5160.6  339.10  5170.7  341.49  5183.4  343.63  5191.0  347.03  5201.1  348.31
  5211.3  351.13  5231.5  353.57  5244.2  354.25  5251.8  355.60  5272.1  356.48
#Mann=4,-1,0
  4761.8    0.12       0  4818.2    0.05       0  4941.8    0.03       0
  4947.8    0.05       0
Bank Sta=4941.8,4947.8
Exp/Cntr=0.3,0.1

Type RM Length L Ch R = 1,3315,473,473,473
BEGIN DESCRIPTION:
UNT 043 IN CACR 7.0
END DESCRIPTION:
XS GIS Cut Line= 3
      3682399.60     10744910.23      3682449.61     10744660.19
      3682349.61     10744460.19
#Sta/Elev= 30
  4737.7  347.44  4758.1  345.11  4768.3  342.91  4778.5  341.56  4798.9  339.93
  4809.1  337.79  4819.3  336.99  4839.7  333.14  4860.1  331.30  4880.5  327.70
  4921.3  324.79  4929.1  324.89  4962.1  323.89  5012.1  323.55  5014.8  323.05
  5018.1  323.55  5029.0  323.77  5045.8  325.67  5051.4  325.37  5068.2  328.15
  5082.1  329.20  5112.9  334.86  5149.2  339.50  5163.2  342.45  5171.6  343.27
  5180.0  345.01  5185.6  348.27  5193.9  349.26  5207.9  353.10  5216.3  353.46
#Mann=4,-1,0
  4737.7    0.16       0  4929.1    0.12       0  5012.1    0.07       0
  5018.1    0.12       0
Bank Sta=5012.1,5018.1
Exp/Cntr=0.3,0.1

Type RM Length L Ch R = 1,2842,412,412,412
BEGIN DESCRIPTION:
Mapping XS 4b754875
END DESCRIPTION:
XS GIS Cut Line= 3
      3682899.61     10744660.19      3682849.61     10744460.19
      3682549.58     10744310.17
#Sta/Elev= 30
  4793.4  334.98  4796.0  334.98  4803.7  333.13  4816.6  331.95  4824.3  330.28
  4857.8  326.31  4865.6  324.66  4899.1  320.82  4903.8  318.82  4906.5  318.32
  4909.8  318.82  4950.4  318.82  5014.7  318.82  5080.6  318.82  5097.4  320.27
  5142.1  321.31  5170.1  323.21  5192.4  323.75  5214.8  325.72  5231.5  328.09
  5245.5  328.96  5253.9  330.34  5267.9  331.66  5281.9  333.55  5290.2  335.23
  5304.2  336.76  5312.6  338.52  5326.6  339.56  5332.2  341.63  5335.0  341.63
#Mann=5,-1,0
  4793.4    0.16       0  4903.8   0.033       0  4909.8    0.16       0
  4950.4    0.05       0  5014.7    0.12       0
Bank Sta=4903.8,4909.8
Exp/Cntr=0.3,0.1

Type RM Length L Ch R = 1,2430,689,689,689
BEGIN DESCRIPTION:
Mapping XS 1322bf4f
END DESCRIPTION:
XS GIS Cut Line= 3
      3683239.76     10744704.08      3683249.61     10744360.19
      3682949.61     10744060.19
#Sta/Elev= 30
  4665.9  344.05  4679.8  344.30  4689.8  343.17  4719.8  342.13  4759.8  342.97
  4769.8  340.40  4779.8  340.10  4835.0  331.68  4849.9  330.77  4859.9  329.01
  4869.9  328.22  4879.9  326.65  4909.9  324.72  4940.4  320.30  4949.9  318.86
  4956.9  318.82  4959.7  318.32  4962.9  318.82  5049.0  318.82  5080.6  318.82
  5193.2  325.70  5236.2  328.02  5306.9  333.65  5321.1  335.71  5349.3  338.64
  5391.8  345.10  5405.9  346.28  5420.1  348.45  5433.3  349.00  5434.2  349.00
#Mann=7,-1,0
  4665.9    0.16       0  4940.4    0.05       0  4956.9   0.033       0
  4962.9    0.05       0  5049.0    0.16       0  5193.2    0.12       0
  5433.3    0.16       0
Bank Sta=4956.9,4962.9
Exp/Cntr=0.3,0.1

Type RM Length L Ch R = 1,1741,442,442,442
BEGIN DESCRIPTION:
Mapping XS 89f3f171
END DESCRIPTION:
XS GIS Cut Line= 2
      3683798.02     10745372.53      3684010.48     10743863.62
#Sta/Elev= 30
  4121.2  364.13  4143.8  363.35  4153.9  361.74  4174.1  360.61  4234.7  354.64
  4239.9  352.98  4245.0  353.83  4311.1  347.91  4325.5  348.00  4382.4  341.12
  4387.4  342.46  4396.2  340.21  4426.5  337.89  4453.6  334.13  4458.6  334.63
  4507.3  328.74  4588.1  321.47  4593.0  318.82  4595.7  318.32  4599.0  318.82
  4651.0  318.82  5214.2  318.82  5241.8  323.27  5355.6  338.00  5384.3  339.78
  5396.0  342.03  5438.7  345.33  5466.7  349.40  5567.7  359.03  5645.0  361.77
#Mann=6,-1,0
  4121.2    0.16       0  4593.0   0.033       0  4599.0    0.16       0
  4651.0    0.05       0  5241.8    0.12       0  5438.7    0.16       0
Bank Sta=4593,4599
Exp/Cntr=0.3,0.1

Type RM Length L Ch R = 1,1299,34,34,34
BEGIN DESCRIPTION:
Mapping XS ea8b9e13
END DESCRIPTION:
XS GIS Cut Line= 6
      3684542.22     10745019.73      3684391.15     10744840.01
      3684349.49     10744715.01      3684349.49     10744537.92
      3684372.92     10744436.36      3684461.33     10744204.93
#Sta/Elev= 30
  4515.7  337.09  4553.2  335.44  4602.6  331.24  4623.5  326.17  4631.2  326.23
  4637.8  324.10  4652.1  322.77  4712.7  321.61  4744.4  321.24  4747.8  319.86
  4781.9  318.82  4825.3  318.82  4926.9  318.82  5118.6  318.82  5130.3  324.12
  5159.0  321.47  5196.6  322.85  5202.3  319.74  5210.0  318.34  5212.7  317.84
  5216.0  318.34  5221.3  322.90  5226.7  322.88  5234.4  328.09  5245.1  330.79
  5251.4  337.62  5276.1  343.20  5312.0  346.34  5329.4  348.33  5411.3  356.59
#Mann=8,-1,0
  4515.7    0.12       0  4712.7    0.16       0  4825.3    0.05       0
  4926.9    0.16       0  5210.0    0.07       0  5216.0    0.16       0
  5312.0    0.12       0  5329.4    0.16       0
Bank Sta=5210,5216
Exp/Cntr=0.3,0.1

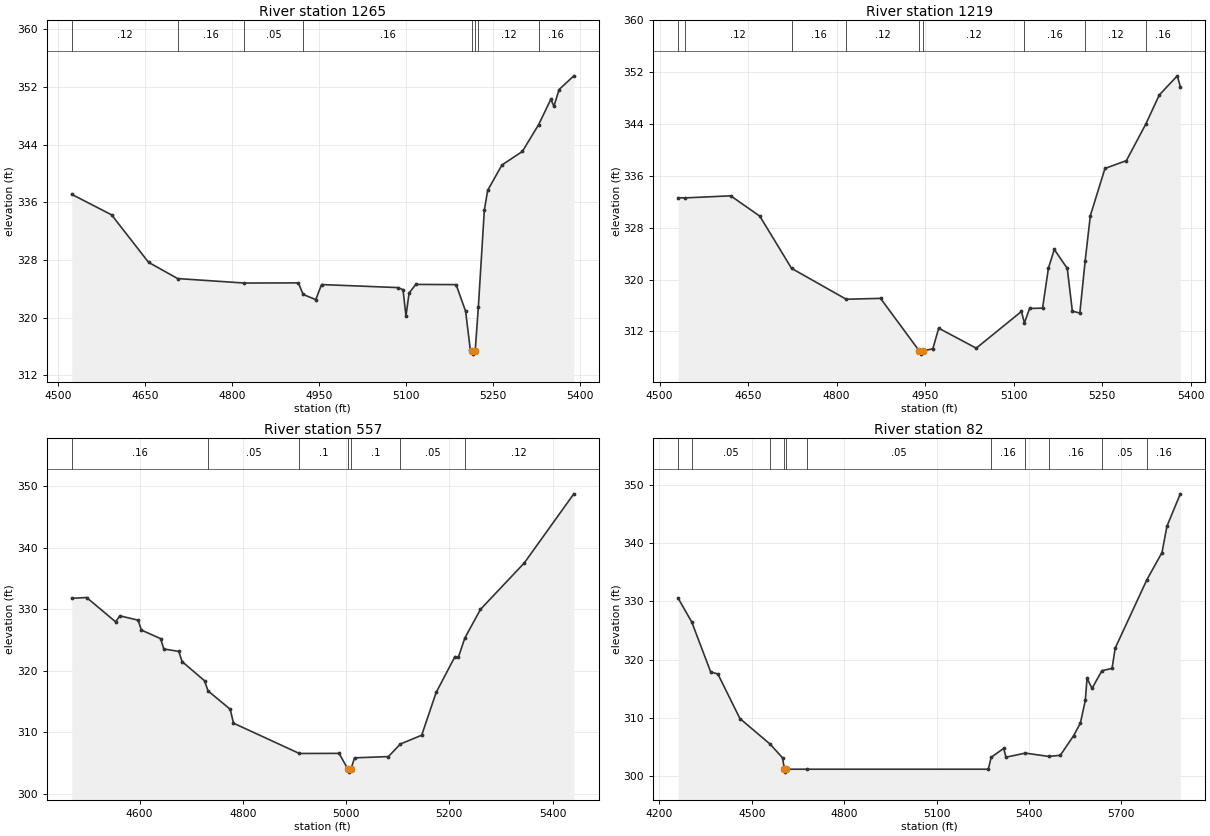
Type RM Length L Ch R = 1,1265,46,46,46
BEGIN DESCRIPTION:
Mapping XS b40588ad
END DESCRIPTION:
XS GIS Cut Line= 6
      3684579.06     10745007.73      3684430.65     10744838.49
      3684391.59     10744729.11      3684381.17     10744562.45
      3684396.79     10744486.93      3684498.37     10744226.48
#Sta/Elev= 30
  4524.1  337.11  4592.7  334.27  4656.3  327.69  4706.5  325.43  4821.3  324.81
  4914.4  324.83  4922.7  323.23  4944.4  322.51  4954.4  324.60  5085.7  324.18
  5094.7  323.89  5099.8  320.24  5105.2  323.42  5116.7  324.62  5186.2  324.59
  5202.6  320.88  5210.7  315.51  5213.1  315.45  5215.8  314.95  5219.1  315.45
  5224.5  321.48  5234.8  334.92  5240.6  337.67  5265.1  341.18  5300.3  343.06
  5328.2  346.76  5349.3  350.28  5354.7  349.33  5363.6  351.65  5389.0  353.55
#Mann=8,-1,0
  4524.1    0.12       0  4706.5    0.16       0  4821.3    0.05       0
  4922.7    0.16       0  5213.1    0.07       0  5219.1    0.16       0
  5224.5    0.12       0  5328.2    0.16       0
Bank Sta=5213.1,5219.1
Exp/Cntr=0.3,0.1

Type RM Length L Ch R = 1,1219,662,662,662
BEGIN DESCRIPTION:
UNT 043 IN CACR 3.0
END DESCRIPTION:
XS GIS Cut Line= 6
      3684634.87     10744990.62      3684478.61     10744823.95
      3684434.34     10744722.39      3684429.13     10744584.36
      3684447.36     10744501.03      3684546.31     10744230.23
#Sta/Elev= 30
  4531.5  332.62  4542.8  332.60  4620.4  332.92  4669.7  329.79  4723.6  321.73
  4816.1  316.97  4874.4  317.10  4940.0  309.00  4942.8  308.50  4946.0  309.00
  4963.0  309.32  4973.0  312.50  5036.6  309.42  5113.2  315.08  5118.3  313.31
  5127.0  315.54  5149.0  315.60  5159.0  321.77  5168.9  324.65  5190.9  321.72
  5199.5  315.14  5212.2  314.83  5221.2  322.87  5230.0  329.86  5254.8  337.14
  5291.1  338.35  5324.1  344.01  5346.8  348.47  5377.4  351.43  5382.5  349.78
#Mann=9,-1,0
  4531.5    0.16       0  4542.8    0.12       0  4723.6    0.16       0
  4816.1    0.12       0  4940.0    0.07       0  4946.0    0.12       0
  5118.3    0.16       0  5221.2    0.12       0  5324.1    0.16       0
Bank Sta=4940,4946
Exp/Cntr=0.3,0.1

Type RM Length L Ch R = 1,557,475,475,475
BEGIN DESCRIPTION:
UNT 043 IN CACR 2.0
END DESCRIPTION:
XS GIS Cut Line= 4
      3684703.25     10744973.88      3685036.55     10744716.96
      3685043.50     10744543.35      3684753.25     10744301.48
#Sta/Elev= 30
  4468.8  331.80  4497.6  331.93  4553.7  327.98  4561.9  328.95  4597.2  328.25
  4603.6  326.64  4640.8  325.25  4647.1  323.56  4676.1  323.17  4682.4  321.52
  4725.9  318.40  4732.7  316.75  4775.7  313.76  4782.0  311.50  4909.6  306.57
  4986.5  306.59  5003.5  304.04  5006.3  303.54  5009.5  304.04  5016.5  305.86
  5082.1  306.07  5105.2  308.11  5146.5  309.54  5174.5  316.49  5210.9  322.32
  5217.4  322.18  5230.1  325.35  5260.4  330.01  5345.0  337.53  5441.2  348.79
#Mann=7,-1,0
  4468.8    0.16       0  4732.7    0.05       0  4909.6     0.1       0
  5003.5    0.07       0  5009.5     0.1       0  5105.2    0.05       0
  5230.1    0.12       0
Bank Sta=5003.5,5009.5
Exp/Cntr=0.3,0.1

Type RM Length L Ch R = 1,82,0,0,0
BEGIN DESCRIPTION:
UNT 043 IN CACR 1.0
END DESCRIPTION:
XS GIS Cut Line= 4
      3684939.36     10745036.39      3685481.00     10744710.02
      3685494.88     10744536.40      3684775.00     10744134.93
#Sta/Elev= 30
  4261.1  330.49  4305.3  326.40  4366.5  317.87  4389.8  317.53  4461.4  309.89
  4559.7  305.49  4600.0  303.14  4606.0  301.20  4608.7  300.70  4612.0  301.20
  4678.1  301.20  5268.3  301.20  5277.6  303.25  5318.2  304.77  5325.6  303.26
  5388.6  303.96  5464.9  303.39  5502.2  303.59  5545.6  306.97  5567.3  309.11
  5583.3  312.98  5589.0  316.83  5605.0  315.05  5637.3  318.09  5670.2  318.48
  5680.4  321.96  5783.7  333.72  5832.4  338.34  5848.4  342.84  5891.9  348.41
#Mann=11,-1,0
  4261.1    0.16       0  4305.3    0.05       0  4559.7    0.07       0
  4606.0   0.033       0  4612.0    0.07       0  4678.1    0.05       0
  5277.6    0.16       0  5388.6    0.12       0  5464.9    0.16       0
  5637.3    0.05       0  5783.7    0.16       0
Bank Sta=4606,4612
Exp/Cntr=0.3,0.1

Chan Stop Cuts=-1