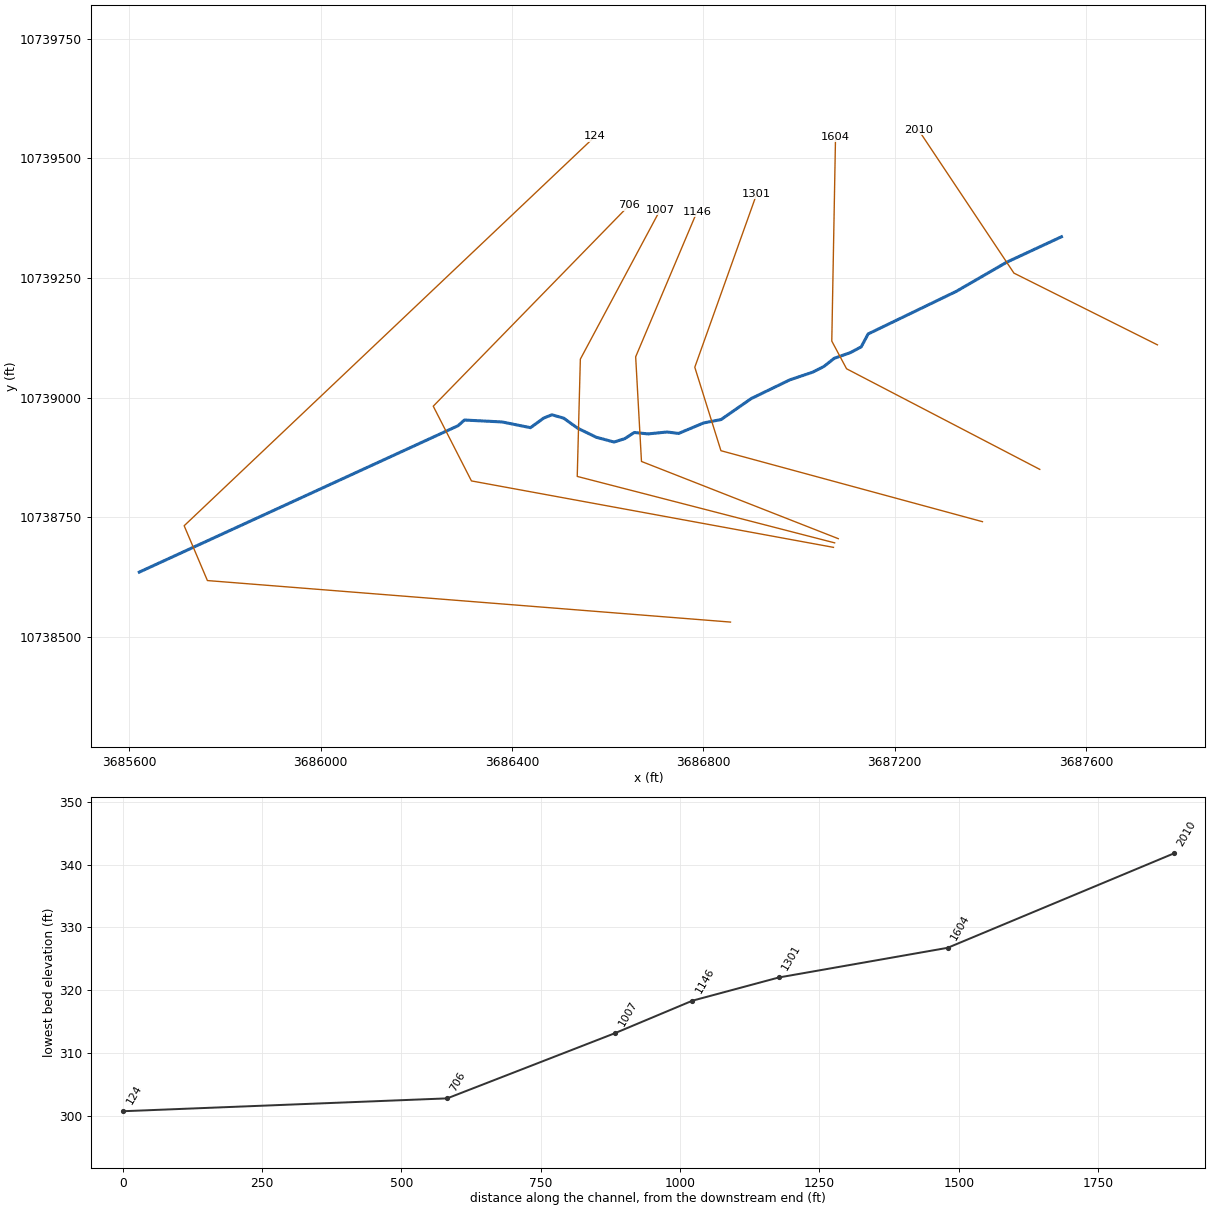
--- UNT 044 IN CACR.prj (project) ---

Proj Title=UNT 044 IN CACR Base Level Engineering
Current Plan=p01
Default Exp/Contr=0.3,0.1
English Units
Geom File=g01
Flow File=f01
Plan File=p01
Y Axis Title=Elevation
X Axis Title(PF)=Main Channel Distance
X Axis Title(XS)=Station
BEGIN DESCRIPTION:
UNT 044 IN CACR
END DESCRIPTION:
DSS Export Rating Curves= 0
DSS Export Rating Curve Sorted= 0
DSS Export Volume Flow Curves= 0
DXF OffsetX= 0
DXF OffsetY= 0
DXF ScaleX= 1
DXF ScaleY= 10

--- UNT 044 IN CACR.p01 (plan) ---

Plan Title=Multiple Run
Short Identifier=Multiple
Geom File=g01
Flow File=f01
Subcritical Flow
K Sum by GR= 0
Std Step Tol= 0.01
Critical Tol= 0.01
Num of Std Step Trials= 20
Max Error Tol= 0.3
Flow Tol Ratio= 0.001
Split Flow NTrial= 30
Split Flow Tol= 0.02
Split Flow Ratio= 0.02
Log Output Level= 0
Friction Slope Method= 1
Unsteady Friction Slope Method= 2
Unsteady Bridges Friction Slope Method= 1
Parabolic Critical Depth
Global Vel Dist=  1 , 1 , 1
Global Log Level= 0
CheckData=True
Encroach Param= -1, 0, 0, 0
BEGIN DESCRIPTION:
Multiple Run
END DESCRIPTION:

--- UNT 044 IN CACR.f01 (steady flow) ---

Flow Title=Multiple
Program Version=4.10
Number of Profiles= 7
Profile Names=10-year,25-year,50-year,1pct_min,100-year,1pct_plu,500-year
River Rch & RM=UNT 044 IN CACR,Reach-1         ,2010
     679     935    1149    1037    1402    1896    2092
Boundary for River Rch & Prof#=UNT 044 IN CACR,Reach-1         , 1
Up Type= 0
Dn Type= 3
Dn Slope=0.00358
Boundary for River Rch & Prof#=UNT 044 IN CACR,Reach-1         , 2
Up Type= 0
Dn Type= 3
Dn Slope=0.00358
Boundary for River Rch & Prof#=UNT 044 IN CACR,Reach-1         , 3
Up Type= 0
Dn Type= 3
Dn Slope=0.00358
Boundary for River Rch & Prof#=UNT 044 IN CACR,Reach-1         , 4
Up Type= 0
Dn Type= 3
Dn Slope=0.00358
Boundary for River Rch & Prof#=UNT 044 IN CACR,Reach-1         , 5
Up Type= 0
Dn Type= 3
Dn Slope=0.00358
Boundary for River Rch & Prof#=UNT 044 IN CACR,Reach-1         , 6
Up Type= 0
Dn Type= 3
Dn Slope=0.00358
Boundary for River Rch & Prof#=UNT 044 IN CACR,Reach-1         , 7
Up Type= 0
Dn Type= 3
Dn Slope=0.00358
DSS Import GetInterval= 0
DSS Import GetPeak= 0
DSS Import FillOption= 0

--- UNT 044 IN CACR.g01 (geometry) ---

Geom Title=Existing Conditions
Program Version=4.10

River Reach=UNT 044 IN CACR ,Reach-1
Reach XY= 29
      3687548.97     10739336.21       3687434.5       10739283.
        3687329.       10739222.      3687144.75       10739133.
      3687130.25       10739106.      3687107.75       10739094.
      3687073.75       10739082.      3687052.25       10739065.
       3687028.5       10739053.        3686981.       10739037.
       3686900.5       10738998.      3686837.25       10738954.
        3686801.       10738947.       3686748.5       10738925.
       3686724.5       10738928.       3686684.5       10738924.
      3686655.75       10738927.      3686635.75       10738914.
       3686613.5       10738907.      3686576.25       10738917.
      3686537.25       10738936.        3686508.       10738957.
       3686483.5       10738964.      3686466.25       10738957.
      3686438.75       10738937.      3686379.25       10738949.
      3686300.75       10738953.        3686287.       10738941.
      3685620.75       10738635.

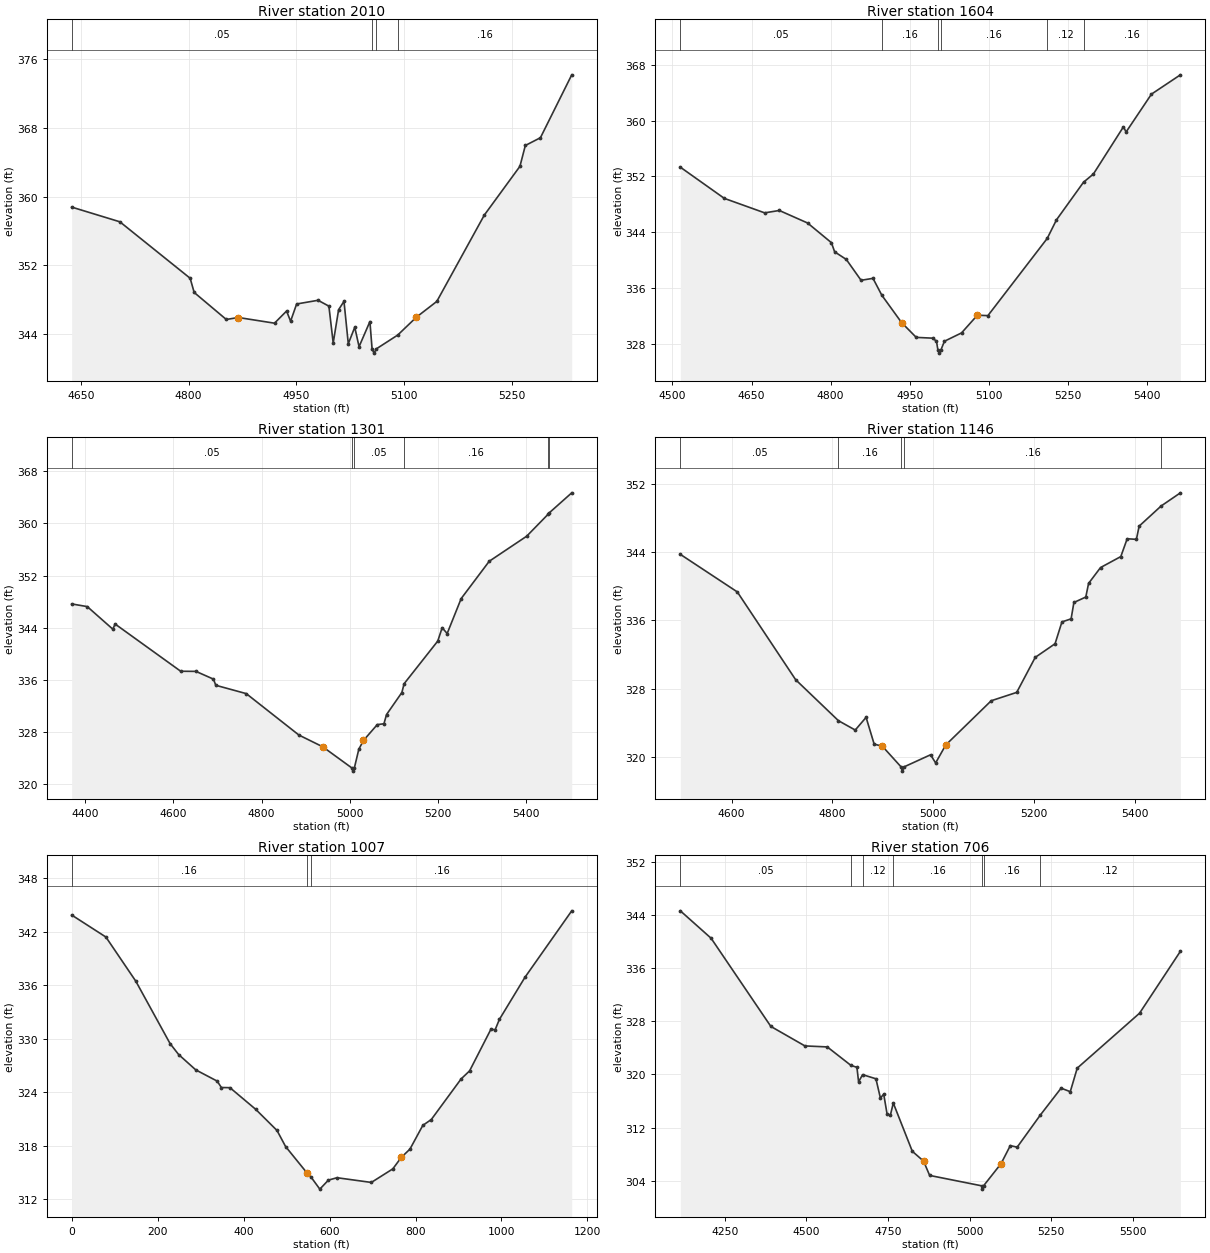
Type RM Length L Ch R = 1 ,2010    ,406,406,406
BEGIN DESCRIPTION:
UNT 044 IN CACR 3.0
END DESCRIPTION:
XS GIS Cut Line= 3
      3687749.63     10739110.18      3687449.61     10739260.19
       3687249.6      10739560.2
#Sta/Elev= 30
  4637.2  358.77  4704.3  357.06  4802.1   350.5  4807.7  348.85  4852.4  345.71
  4869.2  345.94  4919.5  345.28  4936.3  346.69  4941.9  345.51  4950.3  347.51
  4980.1  347.94  4995.2  347.26  5001.2  342.98  5008.7  346.84  5016.2  347.82
  5022.2  342.89  5031.2  344.81  5037.2  342.55  5052.3  345.47  5055.3   342.3
    5058   341.8  5061.3   342.3    5091   343.9  5116.9  345.97  5145.4  347.81
  5211.5  357.84  5261.1  363.51  5268.6  365.93  5289.6  366.83  5333.2  374.14
#Mann= 4 ,-1 , 0
  4637.2     .05       0  5055.3     .03       0  5061.3     .05       0
    5091     .16       0
Bank Sta=4869.2,5116.9
XS Rating Curve= 0 ,0
Exp/Cntr=0.3,0.1

Type RM Length L Ch R = 1 ,1604    ,303,303,303
BEGIN DESCRIPTION:
UNT 044 IN CACR 2.0
END DESCRIPTION:
XS GIS Cut Line= 4
      3687503.62     10738849.84      3687099.61     10739060.19
      3687068.74     10739118.06      3687076.55     10739545.11
#Sta/Elev= 30
    4515  353.33  4598.4  348.87  4674.9   346.8  4702.7  347.14  4756.3  345.35
  4801.4  342.54  4807.6  341.23  4829.7  340.14  4857.7  337.16  4880.3  337.44
    4897  335.03  4934.5  331.12  4962.3     329  4993.2  328.89  5000.6  328.47
  5003.3  327.25    5006  326.75  5009.3  327.25  5015.8  328.45  5048.2  329.64
  5078.2  332.17  5098.2  332.11  5210.7  343.15  5228.2   345.8  5279.5  351.18
  5298.3  352.36  5355.2   359.1  5360.2  358.36  5408.3  363.77  5463.2  366.53
#Mann= 6 ,-1 , 0
    4515     .05       0    4897     .16       0  5003.3     .07       0
  5009.3     .16       0  5210.7     .12       0  5279.5     .16       0
Bank Sta=4934.5,5078.2
XS Rating Curve= 0 ,0
Exp/Cntr=0.3,0.1

Type RM Length L Ch R = 1 ,1301    ,155,155,155
BEGIN DESCRIPTION:
Mapping XS a5b8b416
END DESCRIPTION:
XS GIS Cut Line= 4
       3687383.8     10738740.47      3686836.96     10738888.89
      3686782.28     10739063.37      3686911.98     10739426.54
#Sta/Elev= 30
  4369.1  347.65  4404.5  347.24  4462.5  343.78  4467.7  344.57  4616.6  337.33
  4651.2  337.31    4691  336.12  4696.2  335.18  4765.4   333.9  4884.9  327.55
    4939  325.75  5004.8  322.52  5007.6  322.02  5010.8  322.52  5020.9  325.38
  5031.4  326.72  5062.8  329.15  5077.9  329.28  5083.8  330.69  5118.6  334.07
  5123.7  335.42  5200.1  341.96  5210.1  344.01  5221.4  343.11  5253.2  348.47
  5316.9  354.19  5401.9  358.03  5450.6   361.4  5452.1  361.55  5504.2  364.68
#Mann= 6 ,-1 , 0
  4369.1     .05       0  5004.8     .03       0  5010.8     .05       0
  5123.7     .16       0  5450.6     .12       0  5452.1     .16       0
Bank Sta=4939,5031.4
XS Rating Curve= 0 ,0
Exp/Cntr=0.3,0.1

Type RM Length L Ch R = 1 ,1146    ,139,139,139
BEGIN DESCRIPTION:
Mapping XS 898f904d
END DESCRIPTION:
XS GIS Cut Line= 4
       3687082.3     10738704.93      3686670.81      10738866.4
      3686658.66     10739085.15      3686787.13     10739388.98
#Sta/Elev= 30
  4498.5  343.76  4611.4  339.35    4727  329.05  4811.8  324.24  4845.1  323.14
  4866.6  324.63  4882.6  321.49  4898.9  321.24  4935.9  318.82  4938.6  318.32
  4941.9  318.82  4994.4  320.24  5004.4  319.28  5024.5  321.39  5114.6  326.58
  5165.1  327.56  5201.8  331.67  5241.1  333.27  5254.7  335.83  5272.9  336.19
  5278.4  338.11    5302  338.75  5307.5  340.35  5331.2  342.21  5371.4   343.5
    5384  345.59  5402.3  345.52  5407.7  347.07  5451.4  349.44  5489.5  350.98
#Mann= 5 ,-1 , 0
  4498.5     .05       0  4811.8     .16       0  4935.9     .07       0
  4941.9     .16       0  5451.4     .12       0
Bank Sta=4898.9,5024.5
XS Rating Curve= 0 ,0
Exp/Cntr=0.3,0.1

Type RM Length L Ch R = 1 ,1007    ,301,301,301
XS GIS Cut Line= 4
     3687074.684    10738696.205     3686536.489    10738835.094
     3686542.999     10739080.32       3686710.1     10739392.82
#Sta/Elev= 30
       0  343.89   79.63  341.42   149.3  336.46  228.93  329.47  248.84  328.24
  288.65  326.52  338.42  325.26  348.37  324.54  368.28  324.52     428   322.1
  477.76  319.72  497.67  317.92  547.44  314.96  557.39  314.46  577.36  313.14
  597.34  314.15  617.31  314.42   697.2  313.89  747.13  315.41   767.1  316.71
  787.07  317.63  816.94  320.29  836.75  320.95  906.05   325.5  925.86  326.41
  975.36  331.07  985.26  331.02  995.16  332.18 1054.57   336.9 1163.48  344.36
#Mann= 3 ,-1 , 0
       0     .16       0  547.44     .07       0  557.39     .16       0
Bank Sta=547.44,767.1
XS Rating Curve= 0 ,0
Exp/Cntr=0.3,0.1

Type RM Length L Ch R = 1 ,706     ,582,582,582
BEGIN DESCRIPTION:
Mapping XS ad04e03f
END DESCRIPTION:
XS GIS Cut Line= 4
      3687072.25     10738686.79      3686315.29     10738825.69
      3686235.43     10738981.94      3686644.86     10739401.77
#Sta/Elev= 30
  4113.7  344.59  4207.9  340.47  4390.9  327.21  4495.2  324.28  4563.7  324.13
  4636.5  321.34  4654.5  321.07  4659.6  318.88  4671.9  319.96  4712.7  319.34
  4726.4  316.45  4736.6  317.02  4746.7  314.09  4756.9  313.86  4765.9  315.69
  4824.1  308.44  4858.6  306.96  4877.2  304.81  5036.3  303.25    5039  302.75
  5042.3  303.25  5095.9  306.58  5124.2  309.29  5145.3  309.06  5216.1  313.88
  5279.8  317.93  5307.9   317.4  5329.2  320.94  5520.1   329.2  5645.2  338.51
#Mann= 7 ,-1 , 0
  4113.7     .05       0  4636.5     .16       0  4671.9     .12       0
  4765.9     .16       0  5036.3     .07       0  5042.3     .16       0
  5216.1     .12       0
Bank Sta=4858.6,5095.9
XS Rating Curve= 0 ,0
Exp/Cntr=0.3,0.1

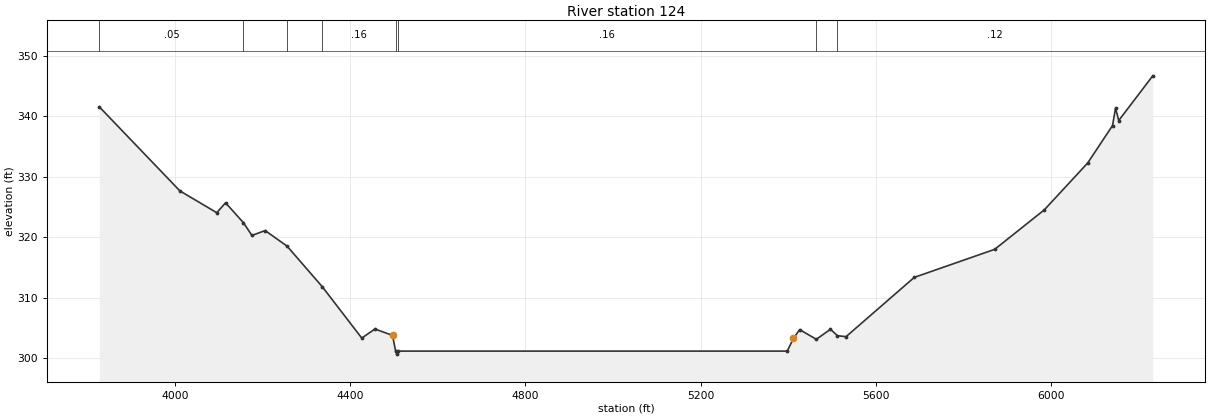
Type RM Length L Ch R = 1 ,124     ,0,0,0
BEGIN DESCRIPTION:
UNT 044 IN CACR 1.0
END DESCRIPTION:
XS GIS Cut Line= 4
      3686856.94     10738530.55      3685763.21     10738617.35
       3685714.6     10738731.94      3686573.72     10739546.02
#Sta/Elev= 30
  3827.3  341.56  4011.3  327.67  4095.5  324.07  4115.5  325.71  4156.3  322.42
  4175.7  320.31  4205.8  321.12  4255.9  318.55  4336.2  311.85  4426.5  303.35
  4456.6  304.85  4496.7   303.8  4503.8   301.2  4506.5   300.7  4509.8   301.2
    5398   301.2  5412.1   303.3  5426.3  304.75  5464.4  303.15  5496.7  304.81
  5512.6  303.74  5532.3  303.59    5688  313.38  5871.7  318.02  5984.9  324.54
    6084  332.29  6140.7  338.47  6147.6  341.38  6154.8   339.3  6232.5  346.69
#Mann= 8 ,-1 , 0
  3827.3     .05       0  4156.3     .16       0  4255.9     .12       0
  4336.2     .16       0  4503.8    .033       0  4509.8     .16       0
  5464.4     .16       0  5512.6     .12       0
Bank Sta=4496.7,5412.1
XS Rating Curve= 0 ,0
Exp/Cntr=0.3,0.1

Chan Stop Cuts=-1
Use User Specified Reach Order=0
Composite Channel Slope=5