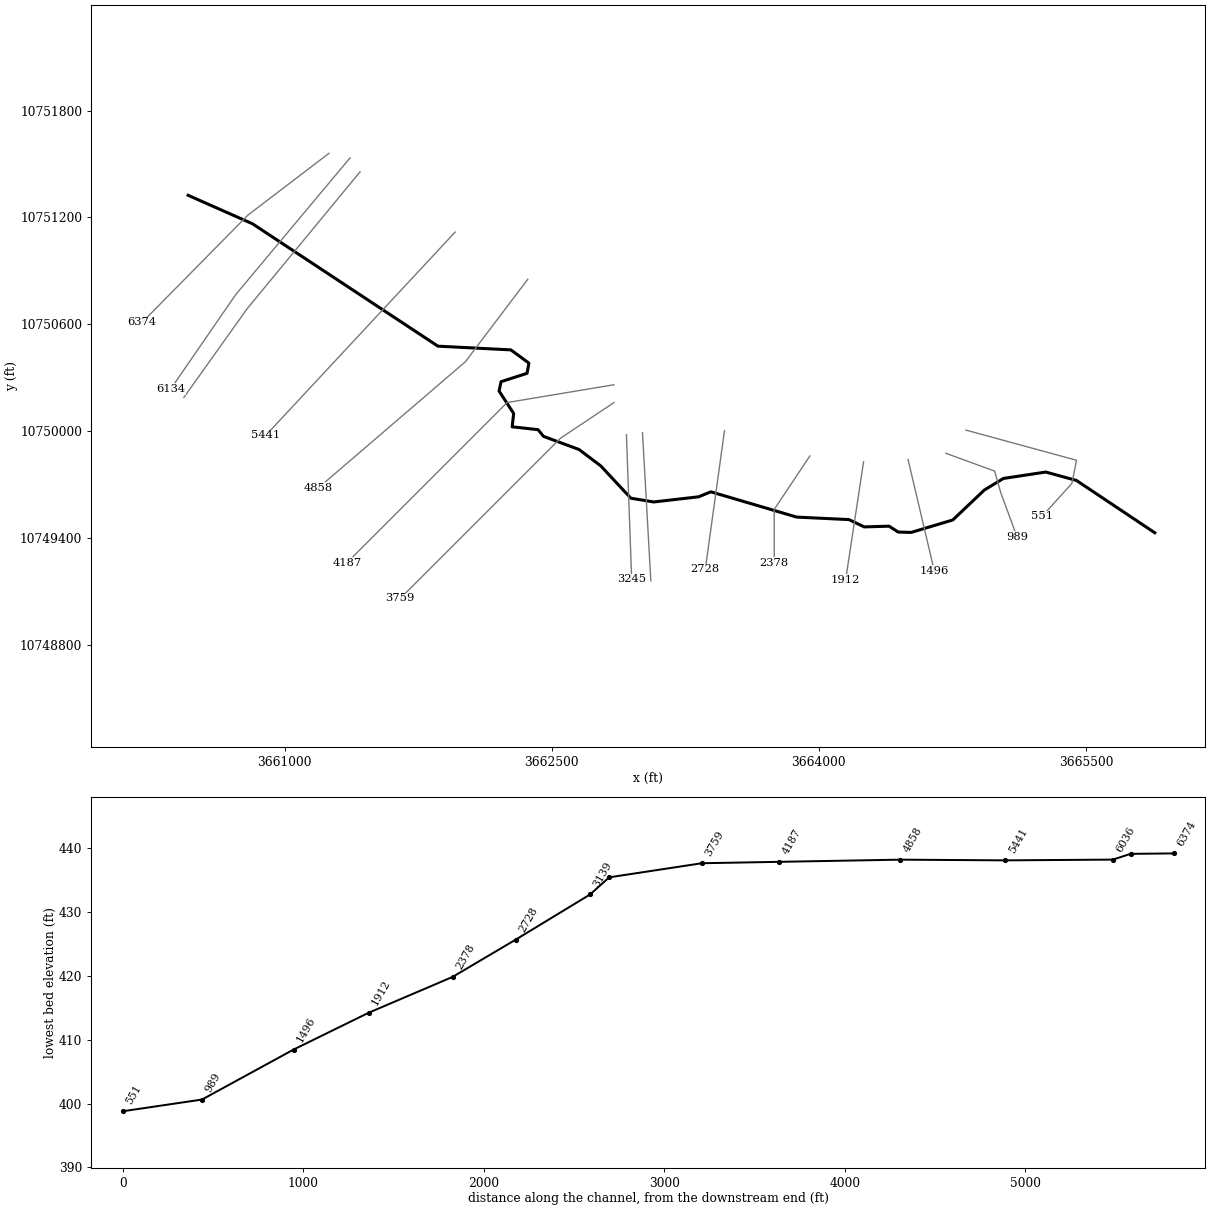
--- UNT 046 IN CACR.prj (project) ---

Proj Title=UNT 046 IN CACR Base Level Engineering
Current Plan=p01
Default Exp/Contr=0.3,0.1
English Units
Geom File=g01
Flow File=f01
Plan File=p01
BEGIN DESCRIPTION:
UNT 046 IN CACR
END DESCRIPTION:

--- UNT 046 IN CACR.p01 (plan) ---

Plan Title=Multiple Run
Short Identifier=Multiple
Geom File=g01
Flow File=f01
Subcritical Flow
K Sum by GR= 0
Std Step Tol= 0.01
Critical Tol= 0.01
Num of Std Step Trials= 20
Max Error Tol= 0.3
Flow Tol Ratio= 0.001
Split Flow NTrial= 30
Split Flow Tol= 0.02
Split Flow Ratio= 0.02
Log Output Level= 0
Friction Slope Method= 1
Unsteady Friction Slope Method= 2
Unsteady Bridges Friction Slope Method= 1
Parabolic Critical Depth
Global Vel Dist=  1 , 1 , 1
Global Log Level= 0
CheckData=True
Encroach Param= -1, 0, 0, 0
BEGIN DESCRIPTION:
Multiple Run
END DESCRIPTION:

--- UNT 046 IN CACR.f01 (steady flow) ---

Flow Title=Multiple
Number of Profiles=7
Profile Names=10-year,25-year,50-year,1pct_min,100-year,1pct_plu,500-year
River Rch & RM= UNT 046 IN CACR,Reach-1,6374
     267     344     404     350     474     641     650
Boundary for River Rch & Prof#=UNT 046 IN CACR,Reach-1,1
Up Type=0
Dn Type=3
Dn Slope=0.005
Boundary for River Rch & Prof#=UNT 046 IN CACR,Reach-1,2
Up Type=0
Dn Type=3
Dn Slope=0.005
Boundary for River Rch & Prof#=UNT 046 IN CACR,Reach-1,3
Up Type=0
Dn Type=3
Dn Slope=0.005
Boundary for River Rch & Prof#=UNT 046 IN CACR,Reach-1,4
Up Type=0
Dn Type=3
Dn Slope=0.005
Boundary for River Rch & Prof#=UNT 046 IN CACR,Reach-1,5
Up Type=0
Dn Type=3
Dn Slope=0.005
Boundary for River Rch & Prof#=UNT 046 IN CACR,Reach-1,6
Up Type=0
Dn Type=3
Dn Slope=0.005
Boundary for River Rch & Prof#=UNT 046 IN CACR,Reach-1,7
Up Type=0
Dn Type=3
Dn Slope=0.005

--- UNT 046 IN CACR.g01 (geometry) ---

Geom Title=Existing Conditions

River Reach=UNT 046 IN CACR,Reach-1
Reach XY= 30
      3660458.39     10751324.11      3660819.50     10751164.39
      3661861.17     10750476.89      3662270.89     10750456.05
      3662372.05     10750381.69      3662361.63     10750324.40
      3662215.80     10750277.52      3662204.50     10750225.00
      3662286.50     10750099.00      3662278.00     10750024.00
      3662423.50     10750008.00      3662453.91     10749970.56
      3662653.64     10749896.55      3662775.40     10749804.65
      3662944.75     10749623.00      3663073.00     10749602.00
      3663325.00     10749631.00      3663393.75     10749659.00
      3663876.00     10749517.00      3664169.50     10749503.00
      3664254.75     10749462.00      3664394.75     10749466.00
      3664446.00     10749433.00      3664519.00     10749431.00
      3664752.75     10749501.00      3664929.50     10749669.00
      3665036.75     10749734.00      3665274.50     10749770.00
      3665446.50     10749723.00      3665886.75     10749429.00

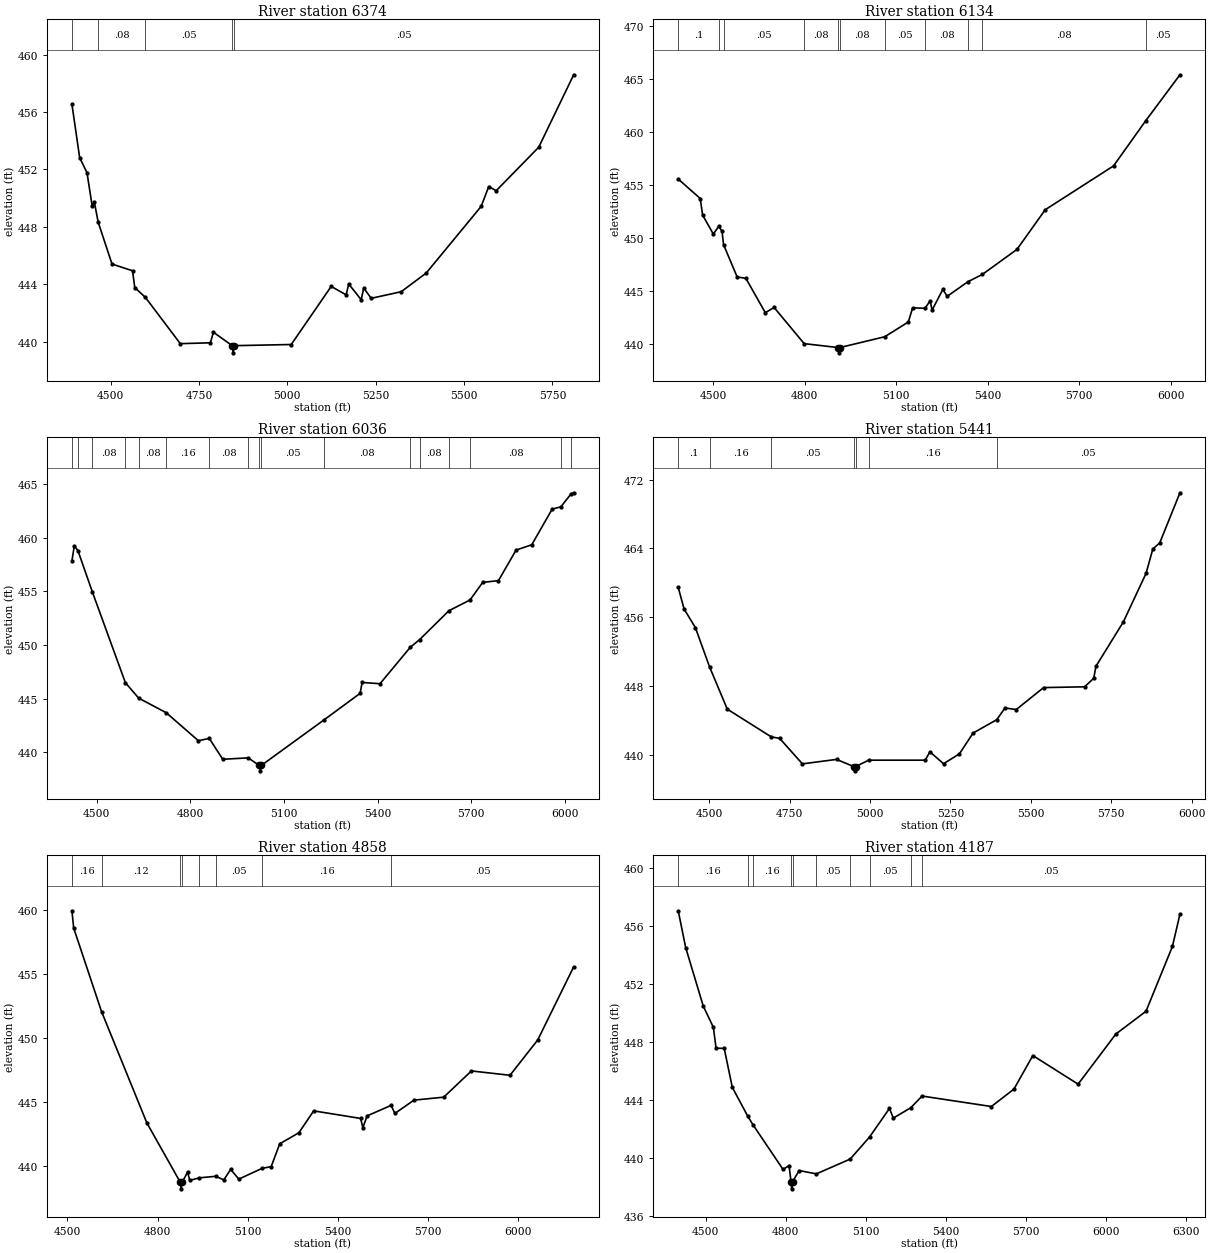
Type RM Length L Ch R = 1,6374,240,240,240
BEGIN DESCRIPTION:
UNT 046 IN CACR 14.0
END DESCRIPTION:
XS GIS Cut Line= 3
      3661249.59     10751560.17      3660794.71     10751213.42
      3660199.64     10750610.22
#Sta/Elev= 30
  4390.8  456.54  4412.6  452.83  4433.4  451.77  4447.9  449.47  4454.2  449.72
  4465.0  448.33  4504.1  445.41  4562.2  444.94  4568.5  443.77  4598.4  443.09
  4697.4  439.86  4782.6  439.92  4790.9  440.66  4844.1  439.72  4846.8  439.22
  4850.1  439.72  5011.1  439.80  5124.2  443.85  5166.6  443.26  5173.7  444.02
  5209.1  442.92  5216.2  443.74  5237.3  443.02  5322.2  443.48  5392.9  444.78
  5548.5  449.43  5569.8  450.81  5590.9  450.52  5711.2  453.55  5810.1  458.60
#Mann=5,-1,0
  4390.8    0.05       0  4465.0    0.08       0  4598.4    0.05       0
  4844.1    0.03       0  4850.1    0.05       0
Bank Sta=4844.1,4850.1
Exp/Cntr=0.3,0.1

Type RM Length L Ch R = 1,6134,98,98,98
BEGIN DESCRIPTION:
UNT 046 IN CACR 13.0
END DESCRIPTION:
XS GIS Cut Line= 3
      3661367.67     10751534.29      3660725.28     10750766.04
      3660360.71     10750236.54
#Sta/Elev= 30
  4385.4  455.57  4457.5  453.73  4465.3  452.17  4500.4  450.37  4518.1  451.10
  4529.0  450.64  4534.0  449.37  4578.5  446.32  4607.1  446.19  4670.9  442.94
  4699.5  443.44  4798.1  440.02  4909.2  439.65  4911.9  439.15  4915.2  439.65
  5062.2  440.67  5139.4  442.06  5153.7  443.40  5194.3  443.36  5210.9  444.06
  5217.4  443.19  5252.6  445.14  5266.9  444.49  5334.9  445.87  5382.2  446.56
  5495.5  448.92  5588.2  452.67  5812.0  456.81  5917.3  461.07  6029.7  465.42
#Mann=11,-1,0
  4385.4     0.1       0  4518.1    0.08       0  4534.0    0.05       0
  4798.1    0.08       0  4909.2    0.07       0  4915.2    0.08       0
  5062.2    0.05       0  5194.3    0.08       0  5334.9    0.05       0
  5382.2    0.08       0  5917.3    0.05       0
Bank Sta=4909.2,4915.2
Exp/Cntr=0.3,0.1

Type RM Length L Ch R = 1,6036,595,595,595
BEGIN DESCRIPTION:
UNT 046 IN CACR 12.0
END DESCRIPTION:
XS GIS Cut Line= 3
      3661424.07     10751456.14      3660790.39     10750687.91
      3660434.53     10750188.85
#Sta/Elev= 30
  4420.2  457.85  4427.9  459.27  4439.9  458.76  4485.5  454.96  4591.5  446.48
  4634.0  445.04  4722.8  443.67  4825.6  441.06  4860.5  441.28  4903.8  439.33
  4985.4  439.46  5021.2  438.75  5024.0  438.25  5027.2  438.75  5228.3  443.00
  5344.2  445.48  5350.7  446.50  5408.0  446.38  5505.1  449.78  5535.1  450.50
  5628.9  453.19  5696.8  454.20  5737.4  455.84  5787.8  456.00  5844.3  458.85
  5894.7  459.35  5959.9  462.67  5987.9  462.89  6020.2  464.08  6029.0  464.20
#Mann=17,-1,0
  4420.2     0.1       0  4439.9    0.05       0  4485.5    0.08       0
  4591.5    0.05       0  4634.0    0.08       0  4722.8    0.16       0
  4860.5    0.08       0  4985.4    0.05       0  5021.2    0.03       0
  5027.2    0.05       0  5228.3    0.08       0  5505.1    0.05       0
  5535.1    0.08       0  5628.9    0.16       0  5696.8    0.08       0
  5987.9    0.05       0  6020.2    0.08       0
Bank Sta=5021.2,5027.2
Exp/Cntr=0.3,0.1

Type RM Length L Ch R = 1,5441,583,583,583
BEGIN DESCRIPTION:
UNT 046 IN CACR 11.0
END DESCRIPTION:
XS GIS Cut Line= 2
      3661957.92     10751117.60      3660894.59     10749976.15
#Sta/Elev= 30
  4403.7  459.46  4422.0  456.94  4457.1  454.78  4501.2  450.21  4556.3  445.30
  4693.4  442.07  4719.0  441.91  4789.8  438.94  4895.9  439.46  4949.5  438.63
  4952.3  438.13  4955.5  438.63  4995.9  439.37  5171.9  439.37  5186.1  440.34
  5228.6  438.96  5277.9  440.10  5320.4  442.52  5394.2  444.08  5419.6  445.44
  5454.8  445.26  5539.8  447.81  5667.3  447.90  5695.6  448.89  5702.5  450.29
  5787.5  455.43  5858.3  461.09  5879.3  463.92  5900.8  464.63  5963.7  470.46
#Mann=7,-1,0
  4403.7     0.1       0  4501.2    0.16       0  4693.4    0.05       0
  4949.5    0.07       0  4955.5    0.05       0  4995.9    0.16       0
  5394.2    0.05       0
Bank Sta=4949.5,4955.5
Exp/Cntr=0.3,0.1

Type RM Length L Ch R = 1,4858,671,671,671
BEGIN DESCRIPTION:
UNT 046 IN CACR 10.0
END DESCRIPTION:
XS GIS Cut Line= 3
      3662365.88     10750852.80      3662014.34     10750388.43
      3661189.66     10749680.94
#Sta/Elev= 30
  4515.0  459.96  4520.8  458.61  4613.4  452.09  4764.2  443.39  4875.7  438.74
  4878.4  438.24  4881.7  438.74  4899.5  439.55  4907.1  438.90  4938.8  439.10
  4993.4  439.22  5020.2  438.94  5043.0  439.76  5070.1  439.00  5148.4  439.85
  5177.7  439.97  5206.2  441.76  5269.9  442.62  5319.2  444.33  5475.1  443.74
  5482.8  443.03  5497.0  443.94  5576.8  444.76  5589.2  444.13  5652.9  445.17
  5751.7  445.40  5843.8  447.45  5972.2  447.11  6064.4  449.87  6184.0  455.58
#Mann=8,-1,0
  4515.0    0.16       0  4613.4    0.12       0  4875.7    0.03       0
  4881.7    0.12       0  4938.8    0.16       0  4993.4    0.05       0
  5148.4    0.16       0  5576.8    0.05       0
Bank Sta=4875.7,4881.7
Exp/Cntr=0.3,0.1

Type RM Length L Ch R = 1,4187,428,428,428
BEGIN DESCRIPTION:
UNT 046 IN CACR 8.0
END DESCRIPTION:
XS GIS Cut Line= 3
      3662849.63     10750260.19      3662249.61     10750160.19
      3661349.60     10749260.18
#Sta/Elev= 30
  4397.6  457.05  4425.5  454.52  4491.4  450.49  4529.4  449.02  4539.5  447.59
  4570.0  447.57  4600.4  444.89  4657.8  442.92  4677.2  442.33  4790.5  439.24
  4813.3  439.50  4820.4  438.40  4823.2  437.90  4826.4  438.40  4851.3  439.16
  4915.5  438.93  5042.3  439.95  5115.0  441.47  5189.7  443.44  5203.9  442.77
  5269.8  443.49  5311.8  444.29  5571.6  443.57  5656.4  444.77  5727.1  447.08
  5896.8  445.11  6038.3  448.56  6151.4  450.13  6250.4  454.59  6278.7  456.82
#Mann=10,-1,0
  4397.6    0.16       0  4657.8    0.12       0  4677.2    0.16       0
  4820.4    0.03       0  4826.4    0.16       0  4915.5    0.05       0
  5042.3     0.1       0  5115.0    0.05       0  5269.8    0.07       0
  5311.8    0.05       0
Bank Sta=4820.4,4826.4
Exp/Cntr=0.3,0.1

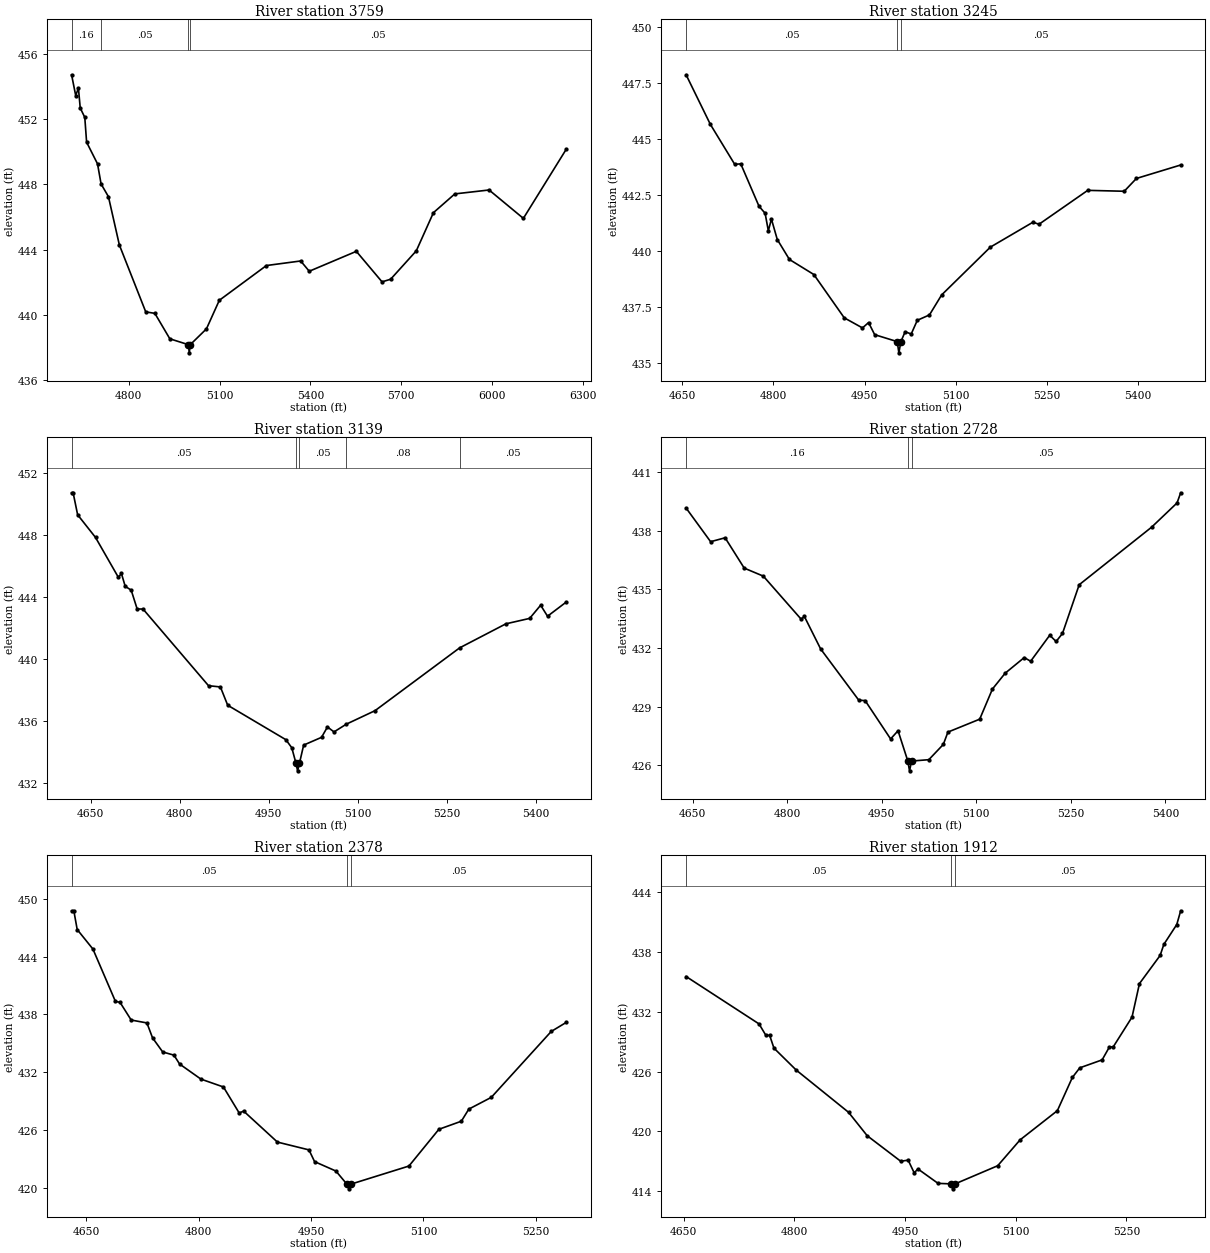
Type RM Length L Ch R = 1,3759,514,514,514
BEGIN DESCRIPTION:
UNT 046 IN CACR 7.0
END DESCRIPTION:
XS GIS Cut Line= 3
      3662849.64     10750160.21      3662549.61     10749960.19
      3661649.60     10749060.18
#Sta/Elev= 30
  4611.1  454.72  4624.7  453.45  4633.7  453.90  4639.7  452.68  4654.7  452.11
  4660.7  450.59  4696.8  449.26  4708.5  448.03  4732.8  447.25  4768.9  444.29
  4856.0  440.19  4886.1  440.10  4935.6  438.54  4997.0  438.18  4999.7  437.68
  5003.0  438.18  5056.5  439.15  5099.0  440.90  5254.5  443.03  5367.7  443.31
  5396.0  442.68  5551.5  443.90  5636.4  442.03  5664.7  442.19  5749.5  443.93
  5806.1  446.27  5876.8  447.42  5989.9  447.66  6103.1  445.92  6244.5  450.15
#Mann=4,-1,0
  4611.1    0.16       0  4708.5    0.05       0  4997.0   0.035       0
  5003.0    0.05       0
Bank Sta=4997,5003
Exp/Cntr=0.3,0.1

Type RM Length L Ch R = 1,3245,106,106,106
BEGIN DESCRIPTION:
UNT 046 IN CACR 6.0
END DESCRIPTION:
XS GIS Cut Line= 2
      3662919.69     10749980.02      3662949.20     10749167.46
#Sta/Elev= 30
  4656.7  447.86  4696.6  445.65  4736.6  443.87  4746.6  443.89  4776.6  442.00
  4786.6  441.69  4791.9  440.91  4797.0  441.43  4806.6  440.52  4826.6  439.63
  4866.7  438.96  4916.7  437.03  4946.7  436.58  4956.7  436.82  4966.7  436.28
  5003.8  435.97  5006.5  435.47  5009.8  435.97  5016.8  436.41  5026.8  436.31
  5036.8  436.92  5056.8  437.16  5076.8  438.05  5156.9  440.18  5226.9  441.29
  5236.9  441.20  5317.0  442.71  5377.0  442.67  5397.0  443.24  5469.8  443.84
#Mann=3,-1,0
  4656.7    0.05       0  5003.8   0.035       0  5009.8    0.05       0
Bank Sta=5003.8,5009.8
Exp/Cntr=0.3,0.1

Type RM Length L Ch R = 1,3139,411,411,411
BEGIN DESCRIPTION:
UNT 046 IN CACR 5.0
END DESCRIPTION:
XS GIS Cut Line= 2
      3663009.97     10749990.39      3663056.84     10749158.81
#Sta/Elev= 30
  4617.8  450.71  4620.4  450.71  4628.0  449.29  4658.1  447.83  4696.7  445.25
  4701.7  445.51  4708.1  444.68  4718.2  444.43  4728.2  443.22  4738.2  443.21
  4848.4  438.27  4868.4  438.19  4880.7  437.01  4978.6  434.79  4988.6  434.27
  4995.6  433.28  4998.4  432.78  5001.6  433.28  5008.6  434.44  5038.7  434.94
  5048.7  435.61  5059.7  435.29  5080.5  435.79  5128.8  436.66  5271.3  440.71
  5349.2  442.26  5389.2  442.61  5407.7  443.46  5419.3  442.75  5450.7  443.66
#Mann=5,-1,0
  4617.8    0.05       0  4995.6    0.04       0  5001.6    0.05       0
  5080.5    0.08       0  5271.3    0.05       0
Bank Sta=4995.6,5001.6
Exp/Cntr=0.3,0.1

Type RM Length L Ch R = 1,2728,350,350,350
BEGIN DESCRIPTION:
Mapping XS 083013cf
END DESCRIPTION:
XS GIS Cut Line= 2
      3663470.25     10750001.53      3663362.70     10749224.43
#Sta/Elev= 30
  4639.8  439.15  4678.7  437.43  4701.7  437.63  4732.0  436.08  4762.3  435.67
  4822.3  433.47  4827.4  433.61  4853.2  431.95  4913.7  429.33  4923.8  429.31
  4964.2  427.35  4976.0  427.77  4991.5  426.22  4994.2  425.72  4997.5  426.22
  5024.8  426.29  5047.8  427.07  5055.1  427.70  5105.5  428.36  5125.7  429.90
  5145.9  430.71  5176.2  431.51  5186.3  431.32  5216.6  432.65  5226.7  432.33
  5236.8  432.74  5263.3  435.23  5378.1  438.17  5418.5  439.41  5424.3  439.93
#Mann=3,-1,0
  4639.8    0.16       0  4991.5    0.03       0  4997.5    0.05       0
Bank Sta=4991.5,4997.5
Exp/Cntr=0.3,0.1

Type RM Length L Ch R = 1,2378,466,466,466
BEGIN DESCRIPTION:
UNT 046 IN CACR 4.0
END DESCRIPTION:
XS GIS Cut Line= 3
      3663949.60     10749860.17      3663749.61     10749560.19
      3663749.61     10749260.23
#Sta/Elev= 30
  4630.1  448.78  4633.1  448.78  4637.6  446.83  4658.6  444.80  4688.7  439.35
  4694.7  439.27  4709.7  437.42  4730.7  437.12  4738.2  435.57  4751.8  434.10
  4766.8  433.77  4774.3  432.85  4802.8  431.28  4832.9  430.46  4853.9  427.76
  4859.9  427.95  4905.0  424.73  4947.1  423.92  4954.6  422.70  4983.1  421.72
  4997.6  420.37  5000.4  419.87  5003.6  420.37  5080.6  422.24  5120.6  426.06
  5150.6  426.90  5160.6  428.16  5190.6  429.38  5270.6  436.23  5290.6  437.17
#Mann=3,-1,0
  4630.1    0.05       0  4997.6    0.03       0  5003.6    0.05       0
Bank Sta=4997.6,5003.6
Exp/Cntr=0.3,0.1

Type RM Length L Ch R = 1,1912,416,416,416
BEGIN DESCRIPTION:
UNT 046 IN CACR 3.0
END DESCRIPTION:
XS GIS Cut Line= 2
      3664251.50     10749827.92      3664150.83     10749164.92
#Sta/Elev= 30
  4653.1  435.56  4752.0  430.80  4761.3  429.65  4766.4  429.65  4772.2  428.37
  4802.5  426.16  4873.3  421.93  4898.7  419.57  4944.1  417.01  4954.2  417.12
  4962.4  415.84  4967.4  416.24  4994.7  414.79  5011.9  414.74  5014.7  414.24
  5017.9  414.74  5075.6  416.56  5106.0  419.16  5156.5  422.09  5176.8  425.42
  5186.9  426.39  5217.2  427.19  5227.1  428.49  5232.2  428.49  5257.7  431.48
  5267.8  434.85  5295.8  437.67  5300.9  438.79  5318.4  440.78  5323.7  442.16
#Mann=3,-1,0
  4653.1    0.05       0  5011.9    0.03       0  5017.9    0.05       0
Bank Sta=5011.9,5017.9
Exp/Cntr=0.3,0.1

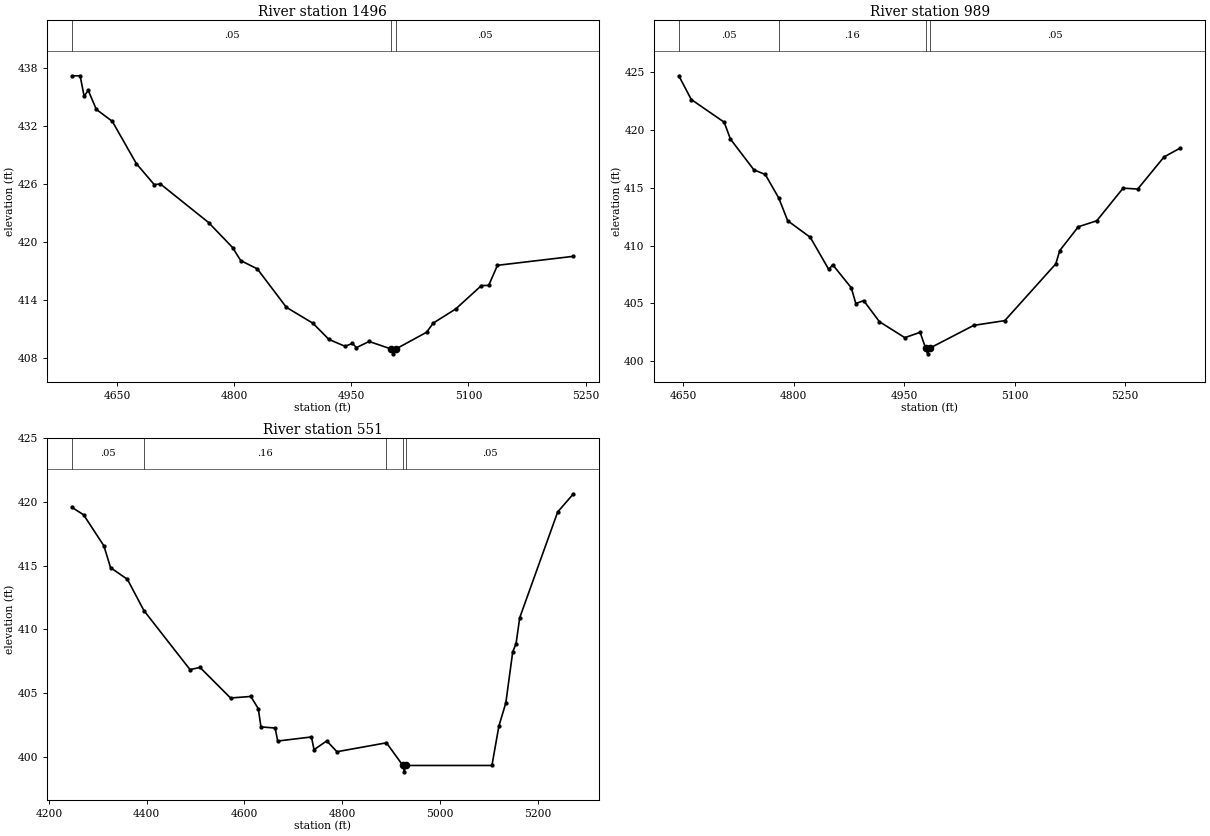
Type RM Length L Ch R = 1,1496,507,507,507
BEGIN DESCRIPTION:
Mapping XS ab69936b
END DESCRIPTION:
XS GIS Cut Line= 2
      3664501.06     10749840.52      3664648.63     10749215.51
#Sta/Elev= 30
  4592.2  437.21  4602.7  437.21  4607.8  435.10  4613.1  435.70  4623.4  433.74
  4643.9  432.50  4674.7  428.13  4697.5  425.97  4705.6  426.02  4767.2  422.04
  4798.0  419.45  4808.3  418.11  4829.6  417.25  4866.8  413.28  4900.8  411.63
  4921.3  409.96  4941.9  409.25  4951.4  409.55  4956.5  409.11  4972.7  409.75
  5001.0  408.97  5003.7  408.47  5007.0  408.97  5046.3  410.70  5054.9  411.65
  5083.5  413.10  5116.6  415.53  5125.8  415.54  5137.1  417.62  5234.4  418.55
#Mann=3,-1,0
  4592.2    0.05       0  5001.0    0.03       0  5007.0    0.05       0
Bank Sta=5001,5007
Exp/Cntr=0.3,0.1

Type RM Length L Ch R = 1,989,438,438,438
BEGIN DESCRIPTION:
UNT 046 IN CACR 2.0
END DESCRIPTION:
XS GIS Cut Line= 4
      3664713.77     10749875.22      3664987.17     10749775.41
      3665021.90     10749653.88      3665113.05     10749406.48
#Sta/Elev= 30
  4643.9  424.67  4660.8  422.62  4705.5  420.66  4714.0  419.20  4745.9  416.54
  4761.3  416.14  4779.6  414.11  4791.8  412.14  4822.4  410.71  4847.6  407.93
  4852.9  408.34  4878.1  406.35  4884.3  404.99  4895.0  405.24  4916.3  403.42
  4950.8  402.04  4971.6  402.50  4979.0  401.14  4981.7  400.64  4985.0  401.14
  5044.4  403.10  5086.6  403.51  5155.9  408.42  5161.2  409.56  5186.4  411.62
  5211.5  412.14  5247.3  414.96  5267.1  414.88  5302.8  417.65  5325.0  418.43
#Mann=4,-1,0
  4643.9    0.05       0  4779.6    0.16       0  4979.0    0.03       0
  4985.0    0.05       0
Bank Sta=4979,4985
Exp/Cntr=0.3,0.1

Type RM Length L Ch R = 1,551,0,0,0
BEGIN DESCRIPTION:
UNT 046 IN CACR 1.0
END DESCRIPTION:
XS GIS Cut Line= 4
      3664826.55     10750005.46      3665447.24     10749836.17
      3665421.20     10749705.97      3665253.29     10749520.83
#Sta/Elev= 30
  4247.0  419.58  4270.9  419.00  4312.4  416.56  4326.0  414.85  4360.5  413.93
  4394.4  411.47  4488.6  406.84  4509.1  407.01  4571.5  404.61  4613.0  404.73
  4628.3  403.77  4633.7  402.34  4662.8  402.25  4668.0  401.23  4737.1  401.55
  4742.3  400.55  4768.4  401.24  4789.2  400.39  4890.5  401.09  4924.1  399.31
  4926.8  398.81  4930.1  399.31  5106.3  399.31  5120.5  402.40  5134.7  404.22
  5148.9  408.25  5155.6  408.86  5163.1  410.91  5240.8  419.22  5273.1  420.65
#Mann=5,-1,0
  4247.0    0.05       0  4394.4    0.16       0  4890.5    0.05       0
  4924.1   0.033       0  4930.1    0.05       0
Bank Sta=4924.1,4930.1
Exp/Cntr=0.3,0.1

Chan Stop Cuts=-1