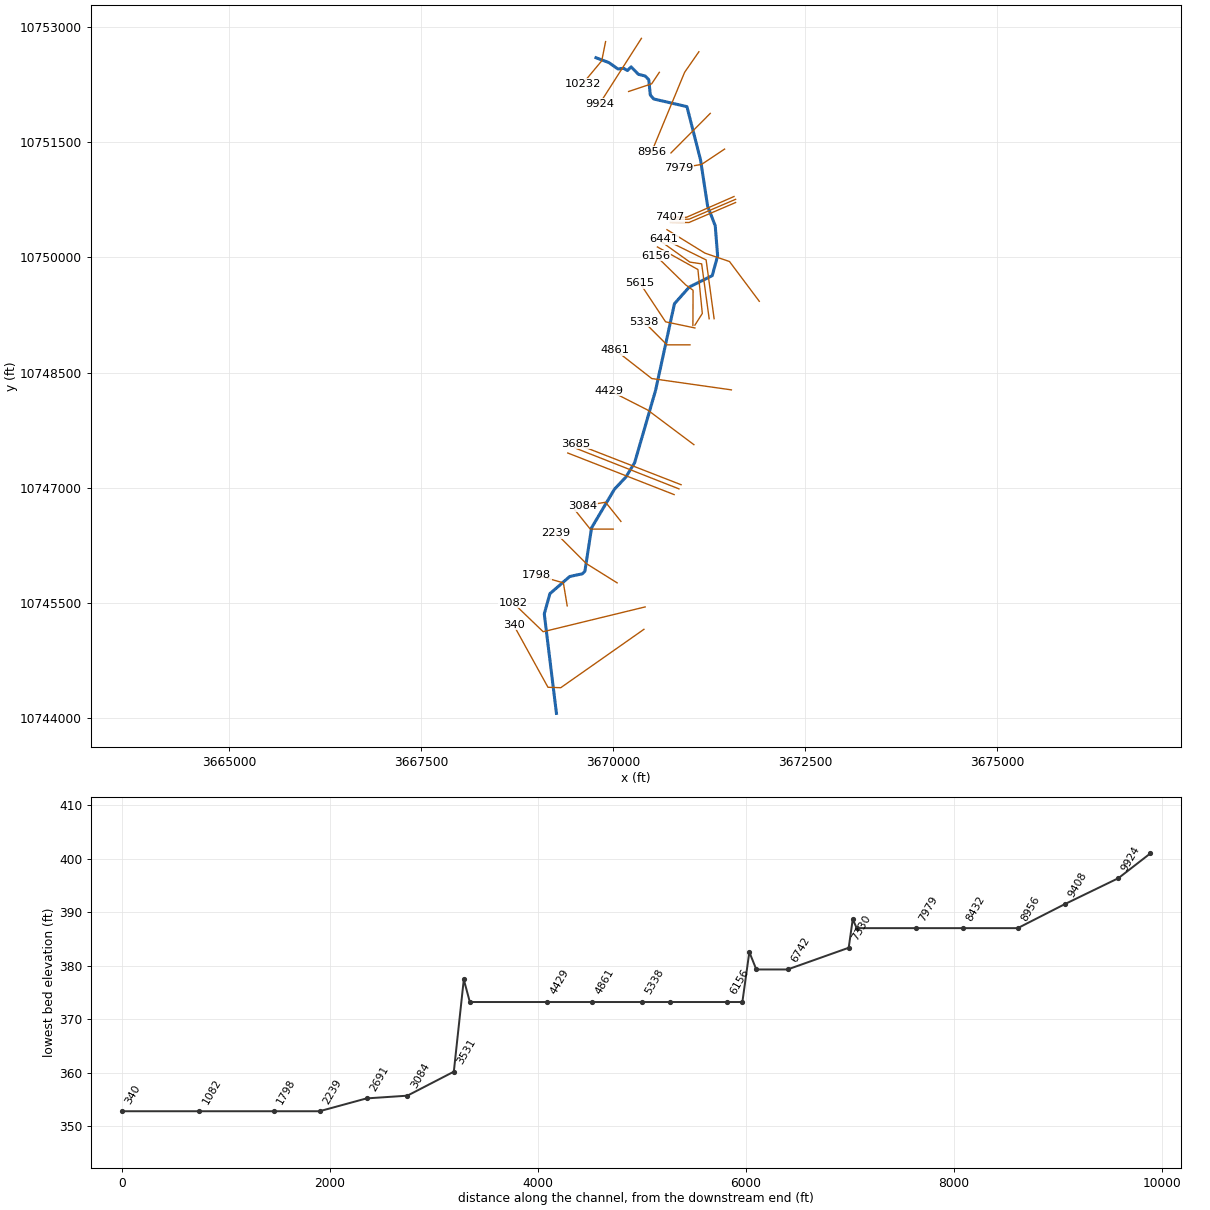
--- UNT 047 IN CACR.prj (project) ---

Proj Title=UNT 047 IN CACR Base Level Engineering
Current Plan=p01
Default Exp/Contr=0.3,0.1
English Units
Geom File=g01
Flow File=f01
Plan File=p01
BEGIN DESCRIPTION:
UNT 047 IN CACR
END DESCRIPTION:

--- UNT 047 IN CACR.p01 (plan) ---

Plan Title=Multiple Run
Short Identifier=Multiple
Geom File=g01
Flow File=f01
Subcritical Flow
K Sum by GR= 0
Std Step Tol= 0.01
Critical Tol= 0.01
Num of Std Step Trials= 20
Max Error Tol= 0.3
Flow Tol Ratio= 0.001
Split Flow NTrial= 30
Split Flow Tol= 0.02
Split Flow Ratio= 0.02
Log Output Level= 0
Friction Slope Method= 1
Unsteady Friction Slope Method= 2
Unsteady Bridges Friction Slope Method= 1
Parabolic Critical Depth
Global Vel Dist=  1 , 1 , 1
Global Log Level= 0
CheckData=True
Encroach Param= -1, 0, 0, 0
BEGIN DESCRIPTION:
Multiple Run
END DESCRIPTION:

--- UNT 047 IN CACR.f01 (steady flow) ---

Flow Title=Multiple
Number of Profiles=7
Profile Names=10-year,25-year,50-year,1pct_min,100-year,1pct_plu,500-year
River Rch & RM= UNT 047 IN CACR,Reach-1,10232
     707     970    1188    1068    1444    1953    2139
Boundary for River Rch & Prof#=UNT 047 IN CACR,Reach-1,1
Up Type=0
Dn Type=3
Dn Slope=0.005
Boundary for River Rch & Prof#=UNT 047 IN CACR,Reach-1,2
Up Type=0
Dn Type=3
Dn Slope=0.005
Boundary for River Rch & Prof#=UNT 047 IN CACR,Reach-1,3
Up Type=0
Dn Type=3
Dn Slope=0.005
Boundary for River Rch & Prof#=UNT 047 IN CACR,Reach-1,4
Up Type=0
Dn Type=3
Dn Slope=0.005
Boundary for River Rch & Prof#=UNT 047 IN CACR,Reach-1,5
Up Type=0
Dn Type=3
Dn Slope=0.005
Boundary for River Rch & Prof#=UNT 047 IN CACR,Reach-1,6
Up Type=0
Dn Type=3
Dn Slope=0.005
Boundary for River Rch & Prof#=UNT 047 IN CACR,Reach-1,7
Up Type=0
Dn Type=3
Dn Slope=0.005

--- UNT 047 IN CACR.g01 (geometry) ---

Geom Title=Existing Conditions

River Reach=UNT 047 IN CACR,Reach-1
Reach XY= 30
      3669774.50     10752600.00      3669942.00     10752537.00
      3670061.00     10752453.00      3670133.00     10752463.00
      3670183.50     10752433.00      3670232.25     10752481.00
      3670327.50     10752384.00      3670416.25     10752362.00
      3670462.00     10752314.00      3670481.75     10752116.00
      3670525.50     10752063.00      3670959.25     10751963.00
      3671136.25     10751270.00      3671228.75     10750666.00
      3671327.75     10750412.00      3671359.00     10750019.00
      3671288.75     10749762.00      3670989.25     10749613.00
      3670796.50     10749396.00      3670550.50     10748267.00
      3670278.25     10747326.00      3670165.00     10747139.00
      3670015.25     10746980.00      3669717.00     10746477.00
      3669630.00     10745911.00      3669597.50     10745878.00
      3669432.75     10745843.00      3669174.00     10745619.00
      3669101.00     10745355.00      3669259.50     10744060.00

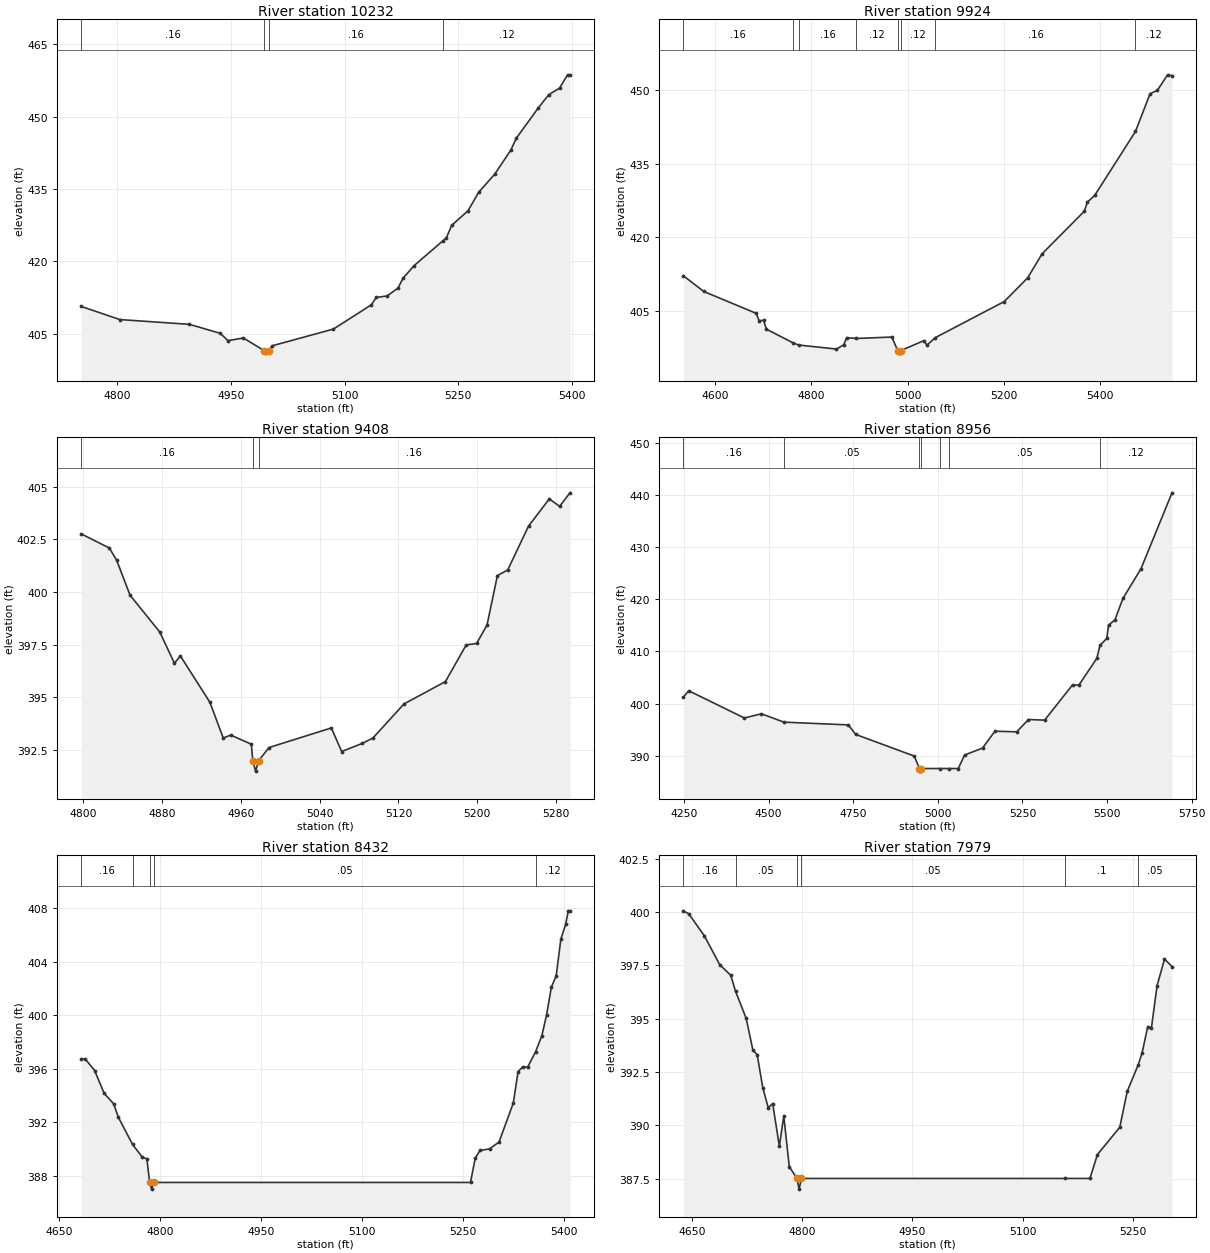
Type RM Length L Ch R = 1,10232,308,308,308
BEGIN DESCRIPTION:
UNT 047 IN CACR 22.0
END DESCRIPTION:
XS GIS Cut Line= 3
      3669899.62     10752810.24      3669849.61     10752560.19
      3669599.62     10752260.20
#Sta/Elev= 30
  4752.2  410.67  4803.2  407.95  4895.0  406.96  4935.8  405.10  4946.0  403.58
  4966.4  404.13  4994.0  401.49  4996.8  400.99  5000.0  401.49  5004.6  402.52
  5085.3  405.98  5135.4  411.01  5141.9  412.55  5156.2  412.84  5170.6  414.48
  5177.1  416.49  5191.4  419.07  5229.9  424.28  5234.3  424.84  5241.5  427.48
  5263.0  430.50  5277.3  434.38  5298.1  438.05  5319.6  443.08  5326.8  445.54
  5355.4  451.74  5369.7  454.59  5384.0  455.94  5394.5  458.70  5397.7  458.70
#Mann=4,-1,0
  4752.2    0.16       0  4994.0    0.07       0  5000.0    0.16       0
  5229.9    0.12       0
Bank Sta=4994,5000
Exp/Cntr=0.3,0.1

Type RM Length L Ch R = 1,9924,516,516,516
BEGIN DESCRIPTION:
UNT 047 IN CACR 21.0
END DESCRIPTION:
XS GIS Cut Line= 2
      3670366.39     10752852.70      3669819.50     10751997.64
#Sta/Elev= 30
  4534.0  412.15  4576.5  408.93  4685.6  404.46  4691.5  402.96  4700.8  403.05
  4706.7  401.23  4762.8  398.41  4773.7  398.00  4852.2  397.18  4867.4  398.05
  4873.3  399.51  4893.0  399.34  4967.2  399.63  4979.4  396.85  4982.2  396.35
  4985.4  396.85  5034.0  398.91  5039.9  397.95  5057.5  399.51  5200.6  406.87
  5249.2  411.70  5279.3  416.62  5367.2  425.32  5373.2  427.15  5388.4  428.51
  5473.2  441.57  5503.4  449.25  5518.6  449.95  5539.8  453.12  5549.0  452.96
#Mann=8,-1,0
  4534.0    0.16       0  4762.8    0.12       0  4773.7    0.16       0
  4893.0    0.12       0  4979.4    0.07       0  4985.4    0.12       0
  5057.5    0.16       0  5473.2    0.12       0
Bank Sta=4979.4,4985.4
Exp/Cntr=0.3,0.1

Type RM Length L Ch R = 1,9408,452,452,452
BEGIN DESCRIPTION:
UNT 047 IN CACR 20.0
END DESCRIPTION:
XS GIS Cut Line= 3
      3670599.63     10752410.21      3670499.61     10752260.19
      3670199.64     10752160.20
#Sta/Elev= 30
  4797.8  402.75  4826.4  402.08  4833.9  401.49  4847.4  399.84  4877.5  398.10
  4892.5  396.61  4898.5  396.96  4928.5  394.76  4942.1  393.06  4949.6  393.20
  4970.6  392.77  4972.1  391.99  4974.9  391.49  4978.1  391.99  4988.6  392.61
  5051.9  393.54  5062.4  392.42  5083.5  392.81  5094.1  393.06  5125.7  394.68
  5167.8  395.74  5188.9  397.48  5199.5  397.55  5210.0  398.42  5220.6  400.77
  5231.1  401.04  5252.2  403.12  5273.3  404.41  5283.8  404.06  5294.3  404.70
#Mann=3,-1,0
  4797.8    0.16       0  4972.1    0.07       0  4978.1    0.16       0
Bank Sta=4972.1,4978.1
Exp/Cntr=0.3,0.1

Type RM Length L Ch R = 1,8956,524,524,524
BEGIN DESCRIPTION:
UNT 047 IN CACR 19.0
END DESCRIPTION:
XS GIS Cut Line= 3
      3671114.55     10752677.38      3670929.06     10752410.27
      3670500.91     10751376.96
#Sta/Elev= 30
  4248.2  401.19  4264.3  402.45  4428.5  397.22  4479.1  398.02  4545.6  396.42
  4735.9  395.89  4757.5  394.06  4930.7  389.90  4945.8  387.51  4948.6  387.01
  4951.8  387.51  5006.4  387.51  5034.1  387.51  5060.6  387.51  5079.1  390.10
  5132.3  391.44  5168.8  394.68  5233.2  394.56  5268.0  396.92  5315.7  396.81
  5398.2  403.59  5416.7  403.52  5469.9  408.68  5479.3  411.16  5499.2  412.50
  5504.6  415.08  5523.1  416.03  5546.9  420.18  5600.1  425.86  5691.9  440.47
#Mann=7,-1,0
  4248.2    0.16       0  4545.6    0.05       0  4945.8   0.033       0
  4951.8    0.05       0  5006.4     0.1       0  5034.1    0.05       0
  5479.3    0.12       0
Bank Sta=4945.8,4951.8
Exp/Cntr=0.3,0.1

Type RM Length L Ch R = 1,8432,453,453,453
BEGIN DESCRIPTION:
Mapping XS 81f71e9a
END DESCRIPTION:
XS GIS Cut Line= 2
      3671262.98     10751874.92      3670751.03     10751359.72
#Sta/Elev= 30
  4682.6  396.74  4688.6  396.74  4702.5  395.88  4716.6  394.18  4730.8  393.39
  4737.8  392.38  4758.9  390.35  4773.2  389.41  4780.2  389.27  4784.3  387.51
  4787.1  387.01  4790.3  387.51  5261.1  387.51  5268.1  389.32  5275.2  389.90
  5289.4  390.02  5303.5  390.53  5324.7  393.45  5331.8  395.79  5338.8  396.16
  5345.9  396.12  5357.7  397.27  5367.1  398.47  5374.2  400.05  5381.3  402.12
  5388.4  402.95  5395.4  405.71  5402.5  406.81  5406.4  407.82  5408.9  407.82
#Mann=5,-1,0
  4682.6    0.16       0  4758.9    0.05       0  4784.3   0.033       0
  4790.3    0.05       0  5357.7    0.12       0
Bank Sta=4784.3,4790.3
Exp/Cntr=0.3,0.1

Type RM Length L Ch R = 1,7979,572,572,572
BEGIN DESCRIPTION:
Mapping XS 220e33f5
END DESCRIPTION:
XS GIS Cut Line= 3
      3671449.57     10751410.17      3671149.61     10751210.19
      3670849.56     10751160.18
#Sta/Elev= 30
  4638.3  400.05  4645.8  399.91  4666.8  398.89  4687.8  397.53  4702.9  397.03
  4709.4  396.28  4723.9  395.01  4732.9  393.54  4738.9  393.30  4746.4  391.77
  4753.9  390.82  4759.9  391.02  4769.0  389.02  4775.0  390.44  4782.5  388.06
  4793.0  387.51  4795.8  387.01  4799.0  387.51  5157.2  387.51  5191.4  387.51
  5201.6  388.63  5232.0  389.91  5242.1  391.59  5256.9  392.82  5262.4  393.40
  5270.0  394.62  5275.1  394.58  5282.7  396.54  5292.8  397.79  5303.0  397.44
#Mann=6,-1,0
  4638.3    0.16       0  4709.4    0.05       0  4793.0   0.033       0
  4799.0    0.05       0  5157.2     0.1       0  5256.9    0.05       0
Bank Sta=4793,4799
Exp/Cntr=0.3,0.1

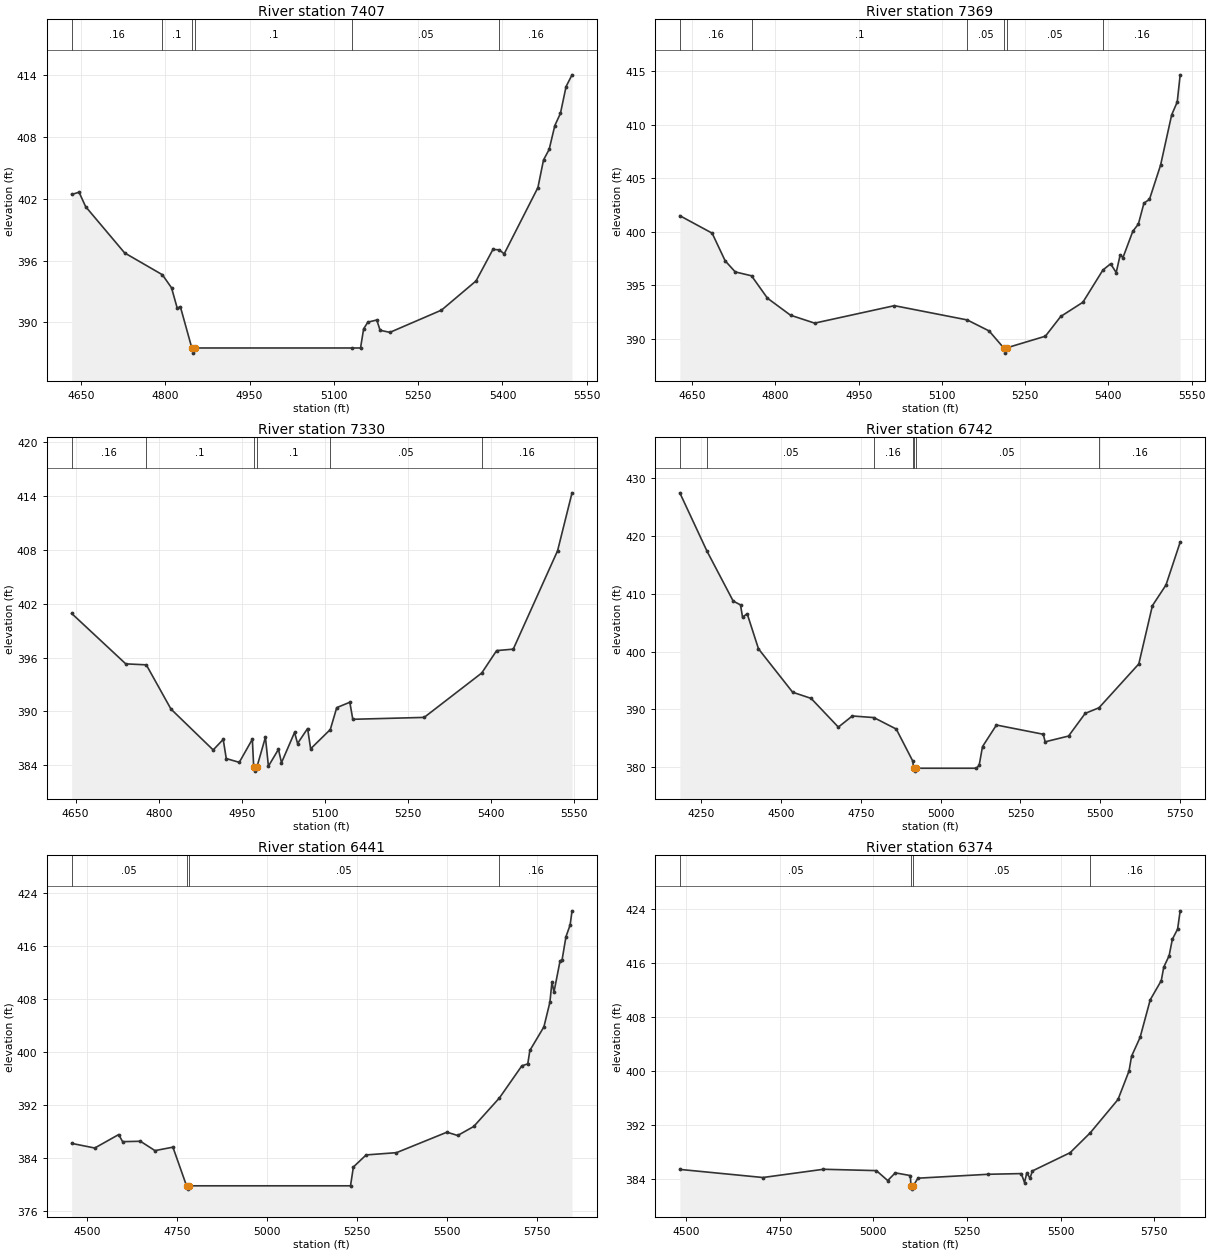
Type RM Length L Ch R = 1,7407,38,38,38
BEGIN DESCRIPTION:
Mapping XS 0c35beb5
END DESCRIPTION:
XS GIS Cut Line= 3
      3671572.34     10750792.30      3670952.51     10750521.45
      3670738.96     10750524.92
#Sta/Elev= 30
  4633.7  402.43  4646.8  402.65  4658.5  401.25  4727.9  396.75  4795.0  394.63
  4811.3  393.36  4821.5  391.37  4827.0  391.53  4847.4  387.51  4850.1  387.01
  4853.4  387.51  5132.5  387.51  5147.5  387.51  5153.0  389.37  5160.5  390.02
  5176.4  390.23  5182.3  389.23  5199.8  389.03  5291.5  391.19  5353.0  394.03
  5383.0  397.09  5394.1  397.05  5403.0  396.66  5463.0  403.10  5473.0  405.79
  5483.0  406.81  5493.1  409.13  5503.1  410.32  5513.1  412.92  5523.7  414.06
#Mann=6,-1,0
  4633.7    0.16       0  4795.0     0.1       0  4847.4    0.07       0
  4853.4     0.1       0  5132.5    0.05       0  5394.1    0.16       0
Bank Sta=4847.4,4853.4
Exp/Cntr=0.3,0.1

Type RM Length L Ch R = 1,7369,39,39,39
BEGIN DESCRIPTION:
Mapping XS 313524a0
END DESCRIPTION:
XS GIS Cut Line= 3
      3671593.12     10750755.82      3670987.24     10750497.15
      3670744.35     10750493.68
#Sta/Elev= 30
  4627.7  401.51  4685.9  399.88  4709.4  397.30  4727.6  396.26  4756.9  395.90
  4785.6  393.81  4827.2  392.22  4870.7  391.48  5014.4  393.11  5145.6  391.78
  5185.1  390.75  5211.2  389.18  5213.9  388.68  5217.2  389.18  5286.5  390.26
  5314.1  392.10  5354.1  393.43  5390.2  396.44  5404.1  397.02  5414.1  396.20
  5421.3  397.85  5426.3  397.60  5444.1  400.06  5454.1  400.73  5464.1  402.68
  5474.1  403.04  5494.1  406.23  5514.1  410.93  5524.1  412.12  5529.4  414.66
#Mann=6,-1,0
  4627.7    0.16       0  4756.9     0.1       0  5145.6    0.05       0
  5211.2    0.07       0  5217.2    0.05       0  5390.2    0.16       0
Bank Sta=5211.2,5217.2
Exp/Cntr=0.3,0.1

Type RM Length L Ch R = 1,7330,588,588,588
BEGIN DESCRIPTION:
Mapping XS 1cbc7db4
END DESCRIPTION:
XS GIS Cut Line= 3
      3671593.14     10750714.16      3670985.50     10750453.74
      3670743.50     10750455.47
#Sta/Elev= 30
  4642.8  400.92  4740.4  395.30  4777.5  395.19  4822.0  390.26  4898.2  385.70
  4916.3  386.88  4921.8  384.74  4945.3  384.32  4968.9  386.90  4971.3  383.84
  4974.1  383.34  4977.3  383.84  4992.5  387.12  4997.9  383.89  5016.0  385.77
  5021.5  384.28  5045.1  387.66  5050.5  386.42  5068.6  388.09  5074.1  385.83
  5109.6  387.98  5121.2  390.42  5144.8  391.02  5150.2  389.12  5279.0  389.33
  5382.9  394.28  5409.8  396.78  5439.8  396.94  5519.8  407.91  5545.9  414.37
#Mann=6,-1,0
  4642.8    0.16       0  4777.5     0.1       0  4971.3    0.07       0
  4977.3     0.1       0  5109.6    0.05       0  5382.9    0.16       0
Bank Sta=4971.3,4977.3
Exp/Cntr=0.3,0.1

Type RM Length L Ch R = 1,6742,301,301,301
BEGIN DESCRIPTION:
Mapping XS fb2a6bbc
END DESCRIPTION:
XS GIS Cut Line= 4
      3671901.70     10749427.36      3671513.66     10749945.62
      3671193.34     10750055.00      3670699.57     10750360.21
#Sta/Elev= 30
  4183.7  427.51  4268.6  417.42  4350.8  408.75  4373.7  408.09  4380.0  405.97
  4394.6  406.55  4430.0  400.47  4537.0  392.95  4594.6  391.89  4680.0  386.91
  4723.8  388.84  4791.2  388.56  4861.3  386.57  4912.8  381.04  4915.7  379.78
  4918.4  379.28  4921.7  379.78  5111.9  379.78  5120.7  380.26  5131.3  383.53
  5174.9  387.27  5321.5  385.67  5327.4  384.36  5400.7  385.36  5452.8  389.29
  5496.0  390.26  5620.6  397.86  5663.2  407.96  5705.7  411.54  5750.1  418.96
#Mann=7,-1,0
  4183.7    0.12       0  4268.6    0.05       0  4791.2    0.16       0
  4912.8    0.05       0  4915.7   0.033       0  4921.7    0.05       0
  5496.0    0.16       0
Bank Sta=4915.7,4921.7
Exp/Cntr=0.3,0.1

Type RM Length L Ch R = 1,6441,67,67,67
BEGIN DESCRIPTION:
Mapping XS a4e9d8bc
END DESCRIPTION:
XS GIS Cut Line= 3
      3671313.14     10749200.80      3671208.97     10749966.46
      3670654.49     10750239.79
#Sta/Elev= 30
  4456.1  386.18  4520.2  385.48  4586.7  387.51  4597.7  386.44  4647.2  386.50
  4687.6  385.09  4737.5  385.61  4775.4  379.78  4778.2  379.28  4781.4  379.78
  5231.2  379.78  5239.2  382.62  5274.7  384.44  5359.0  384.78  5499.3  387.87
  5529.1  387.37  5573.7  388.73  5645.2  393.04  5707.5  397.88  5723.9  398.17
  5729.8  400.20  5768.8  403.76  5785.5  407.47  5791.2  410.55  5796.8  409.01
  5813.7  413.70  5819.3  413.85  5830.1  417.35  5841.7  419.13  5847.0  421.26
#Mann=4,-1,0
  4456.1    0.05       0  4775.4   0.033       0  4781.4    0.05       0
  5645.2    0.16       0
Bank Sta=4775.4,4781.4
Exp/Cntr=0.3,0.1

Type RM Length L Ch R = 1,6374,67,67,67
BEGIN DESCRIPTION:
Mapping XS 0e9f6064
END DESCRIPTION:
XS GIS Cut Line= 4
      3671248.68     10749200.48      3671150.81     10749915.11
      3670997.81     10749937.90      3670623.98     10750204.77
#Sta/Elev= 30
  4483.8  385.46  4705.6  384.26  4867.1  385.48  5008.4  385.28  5038.6  383.81
  5058.8  384.95  5098.8  384.55  5100.8  383.04  5103.6  382.54  5106.8  383.04
  5119.4  384.16  5307.4  384.74  5395.1  384.84  5403.7  383.51  5409.8  384.95
  5418.4  384.15  5424.6  385.23  5525.3  387.93  5579.2  390.88  5653.2  395.81
  5682.7  400.04  5689.3  402.21  5712.2  405.01  5739.2  410.57  5768.7  413.41
  5775.3  415.41  5789.6  417.09  5798.2  419.53  5812.2  421.03  5819.1  423.74
#Mann=4,-1,0
  4483.8    0.05       0  5100.8   0.033       0  5106.8    0.05       0
  5579.2    0.16       0
Bank Sta=5100.8,5106.8
Exp/Cntr=0.3,0.1

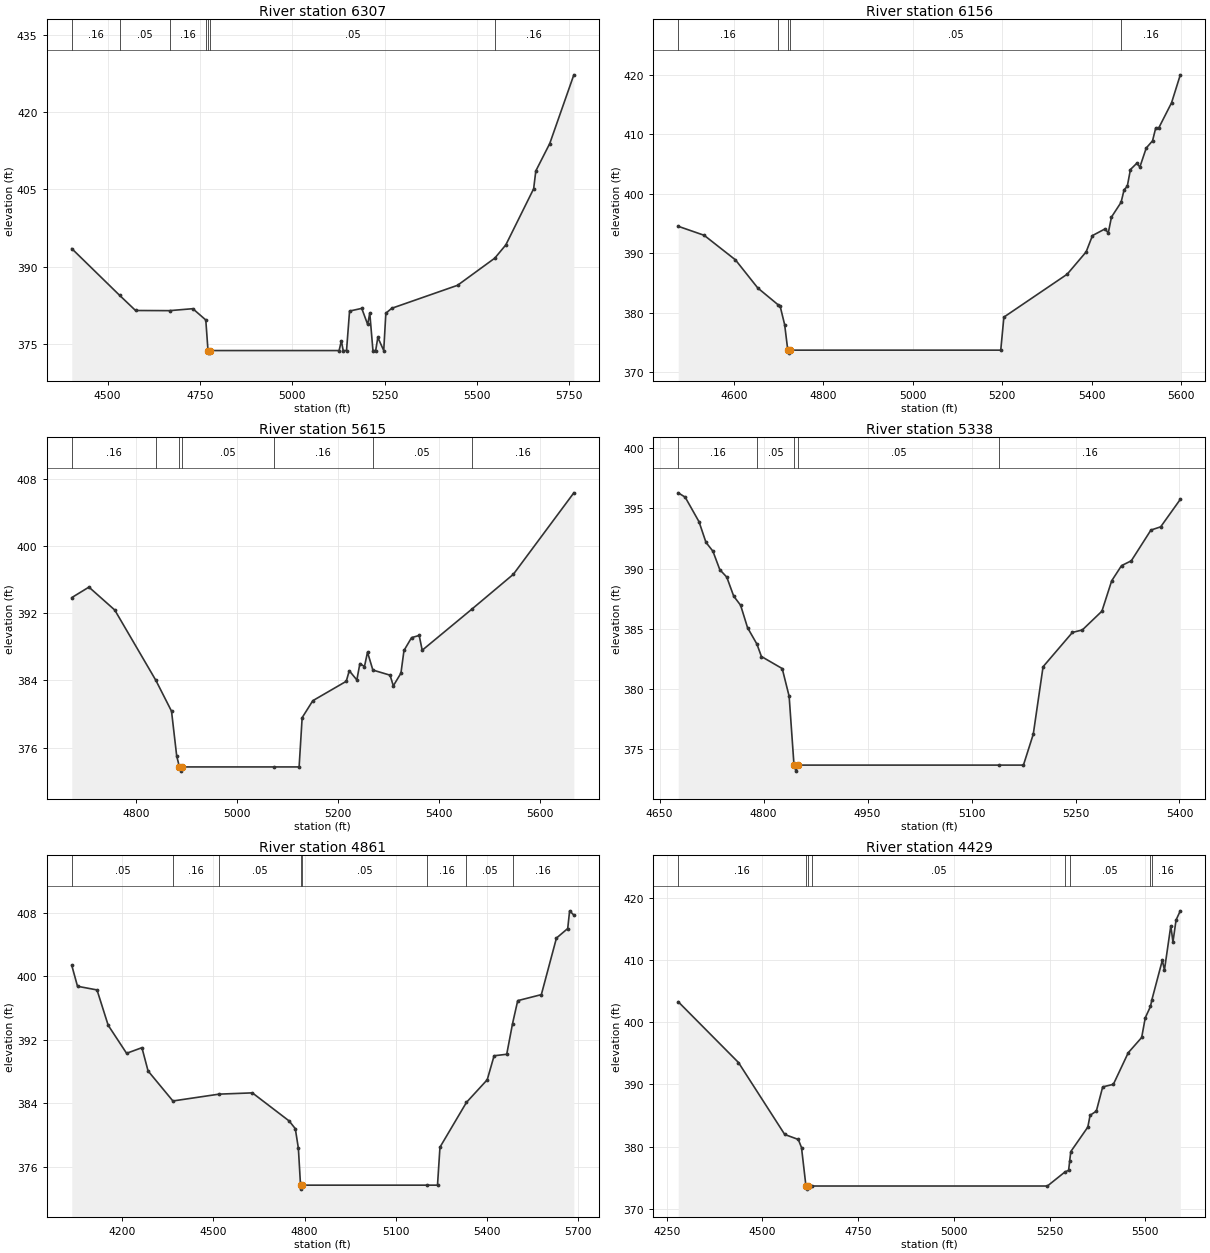
Type RM Length L Ch R = 1,6307,151,151,151
BEGIN DESCRIPTION:
Mapping XS f7c41431
END DESCRIPTION:
XS GIS Cut Line= 4
      3671063.15     10749117.52      3671159.49     10749268.54
      3671102.20     10749841.46      3670574.55     10750135.17
#Sta/Elev= 30
  4403.2  393.49  4532.5  384.43  4575.8  381.47  4667.7  381.44  4730.8  381.82
  4765.9  379.63  4771.9  373.69  4774.7  373.19  4777.9  373.69  5126.7  373.69
  5132.8  375.57  5137.8  373.69  5146.8  373.69  5155.0  381.36  5188.0  381.88
  5204.0  378.76  5209.7  380.97  5218.3  373.69  5225.7  373.69  5231.5  376.24
  5247.5  373.69  5253.2  380.94  5269.2  381.90  5447.2  386.36  5548.1  391.64
  5577.9  394.21  5653.2  405.11  5659.1  408.58  5696.8  413.90  5762.0  427.24
#Mann=7,-1,0
  4403.2    0.16       0  4532.5    0.05       0  4667.7    0.16       0
  4765.9    0.05       0  4771.9   0.033       0  4777.9    0.05       0
  5548.1    0.16       0
Bank Sta=4771.9,4777.9
Exp/Cntr=0.3,0.1

Type RM Length L Ch R = 1,6156,541,541,541
BEGIN DESCRIPTION:
UNT 047 IN CACR 13.0
END DESCRIPTION:
XS GIS Cut Line= 4
      3671037.09     10749112.33      3671039.11     10749571.42
      3670943.63     10749640.86      3670553.78     10750022.05
#Sta/Elev= 30
  4475.7  394.50  4533.6  392.99  4603.6  388.86  4653.6  384.13  4699.0  381.31
  4703.6  381.05  4713.6  377.97  4720.6  373.69  4723.3  373.19  4726.6  373.69
  5196.7  373.69  5203.7  379.24  5345.2  386.45  5387.6  390.20  5401.7  392.94
  5430.0  394.07  5437.0  393.36  5444.2  396.05  5465.7  398.53  5472.5  400.65
  5479.5  401.20  5486.6  404.04  5500.8  405.09  5507.7  404.46  5521.9  407.65
  5536.0  408.86  5543.2  411.04  5550.2  411.07  5578.5  415.25  5598.1  419.95
#Mann=5,-1,0
  4475.7    0.16       0  4699.0    0.05       0  4720.6   0.033       0
  4726.6    0.05       0  5465.7    0.16       0
Bank Sta=4720.6,4726.6
Exp/Cntr=0.3,0.1

Type RM Length L Ch R = 1,5615,277,277,277
BEGIN DESCRIPTION:
Mapping XS 5e9f4b61
END DESCRIPTION:
XS GIS Cut Line= 3
      3671062.88     10749080.29      3670680.94     10749160.15
      3670347.62     10749663.61
#Sta/Elev= 30
  4672.5  393.86  4706.5  395.11  4757.6  392.38  4839.1  383.99  4870.0  380.33
  4880.2  375.01  4885.6  373.69  4888.3  373.19  4891.6  373.69  5072.4  373.69
  5122.6  373.69  5128.6  379.56  5149.7  381.58  5215.9  383.89  5221.9  385.15
  5236.9  384.05  5242.9  386.00  5252.0  385.65  5258.0  387.36  5268.6  385.23
  5302.6  384.62  5309.1  383.35  5324.2  384.86  5330.2  387.56  5345.2  389.09
  5360.3  389.35  5366.3  387.59  5464.3  392.47  5546.8  396.64  5666.5  406.34
#Mann=7,-1,0
  4672.5    0.16       0  4839.1    0.05       0  4885.6   0.033       0
  4891.6    0.05       0  5072.4    0.16       0  5268.6    0.05       0
  5464.3    0.16       0
Bank Sta=4885.6,4891.6
Exp/Cntr=0.3,0.1

Type RM Length L Ch R = 1,5338,477,477,477
BEGIN DESCRIPTION:
Mapping XS 1ab843b3
END DESCRIPTION:
XS GIS Cut Line= 3
      3670999.65     10748860.19      3670699.61     10748860.19
      3670399.61     10749160.19
#Sta/Elev= 30
  4676.9  396.28  4686.9  395.92  4706.9  393.88  4716.9  392.17  4726.9  391.44
  4736.9  389.90  4746.9  389.29  4756.9  387.71  4766.9  386.95  4776.9  385.09
  4790.4  383.73  4796.9  382.70  4826.9  381.70  4836.9  379.40  4843.9  373.69
  4846.7  373.19  4849.9  373.69  5140.3  373.69  5174.9  373.69  5189.1  376.26
  5203.2  381.85  5245.6  384.70  5259.8  384.90  5288.1  386.46  5302.2  388.98
  5316.4  390.24  5330.5  390.64  5358.8  393.19  5372.9  393.46  5401.2  395.74
#Mann=5,-1,0
  4676.9    0.16       0  4790.4    0.05       0  4843.9   0.033       0
  4849.9    0.05       0  5140.3    0.16       0
Bank Sta=4843.9,4849.9
Exp/Cntr=0.3,0.1

Type RM Length L Ch R = 1,4861,432,432,432
BEGIN DESCRIPTION:
UNT 047 IN CACR 10.0
END DESCRIPTION:
XS GIS Cut Line= 3
      3671538.28     10748273.67      3670500.92     10748421.24
      3670024.06     10748794.06
#Sta/Elev= 30
  4033.7  401.36  4052.6  398.73  4116.8  398.27  4153.6  393.82  4214.2  390.29
  4264.7  391.00  4284.9  388.07  4366.7  384.29  4518.8  385.15  4628.3  385.31
  4749.5  381.77  4769.7  380.80  4779.8  378.34  4786.9  373.69  4789.7  373.19
  4792.9  373.69  5203.6  373.69  5237.9  373.69  5246.0  378.47  5333.2  384.11
  5401.6  386.96  5424.2  389.98  5465.8  390.17  5485.0  394.04  5502.0  396.92
  5579.8  397.68  5629.5  404.80  5666.6  406.00  5672.9  408.23  5686.8  407.69
#Mann=8,-1,0
  4033.7    0.05       0  4366.7    0.16       0  4518.8    0.05       0
  4786.9   0.033       0  4792.9    0.05       0  5203.6    0.16       0
  5333.2    0.05       0  5485.0    0.16       0
Bank Sta=4786.9,4792.9
Exp/Cntr=0.3,0.1

Type RM Length L Ch R = 1,4429,744,744,744
BEGIN DESCRIPTION:
UNT 047 IN CACR 9.0
END DESCRIPTION:
XS GIS Cut Line= 3
      3671049.61     10747560.19      3670449.61     10748010.19
      3669949.70     10748265.00
#Sta/Elev= 30
  4280.0  403.29  4437.3  393.53  4558.1  381.97  4593.5  381.17  4601.9  379.87
  4613.5  373.69  4616.2  373.19  4619.5  373.69  4630.3  373.69  5244.0  373.69
  5290.1  375.96  5299.4  376.21  5302.3  377.74  5305.1  379.22  5349.6  383.16
  5355.5  385.05  5371.8  385.72  5388.4  389.61  5416.3  390.03  5455.1  395.10
  5490.2  397.55  5499.6  400.72  5513.2  402.54  5516.7  403.57  5544.1  409.94
  5549.7  408.41  5566.3  415.50  5571.9  412.89  5580.0  416.43  5591.1  417.90
#Mann=8,-1,0
  4280.0    0.16       0  4613.5   0.033       0  4619.5    0.16       0
  4630.3    0.05       0  5290.1    0.16       0  5302.3    0.05       0
  5513.2    0.12       0  5516.7    0.16       0
Bank Sta=4613.5,4619.5
Exp/Cntr=0.3,0.1

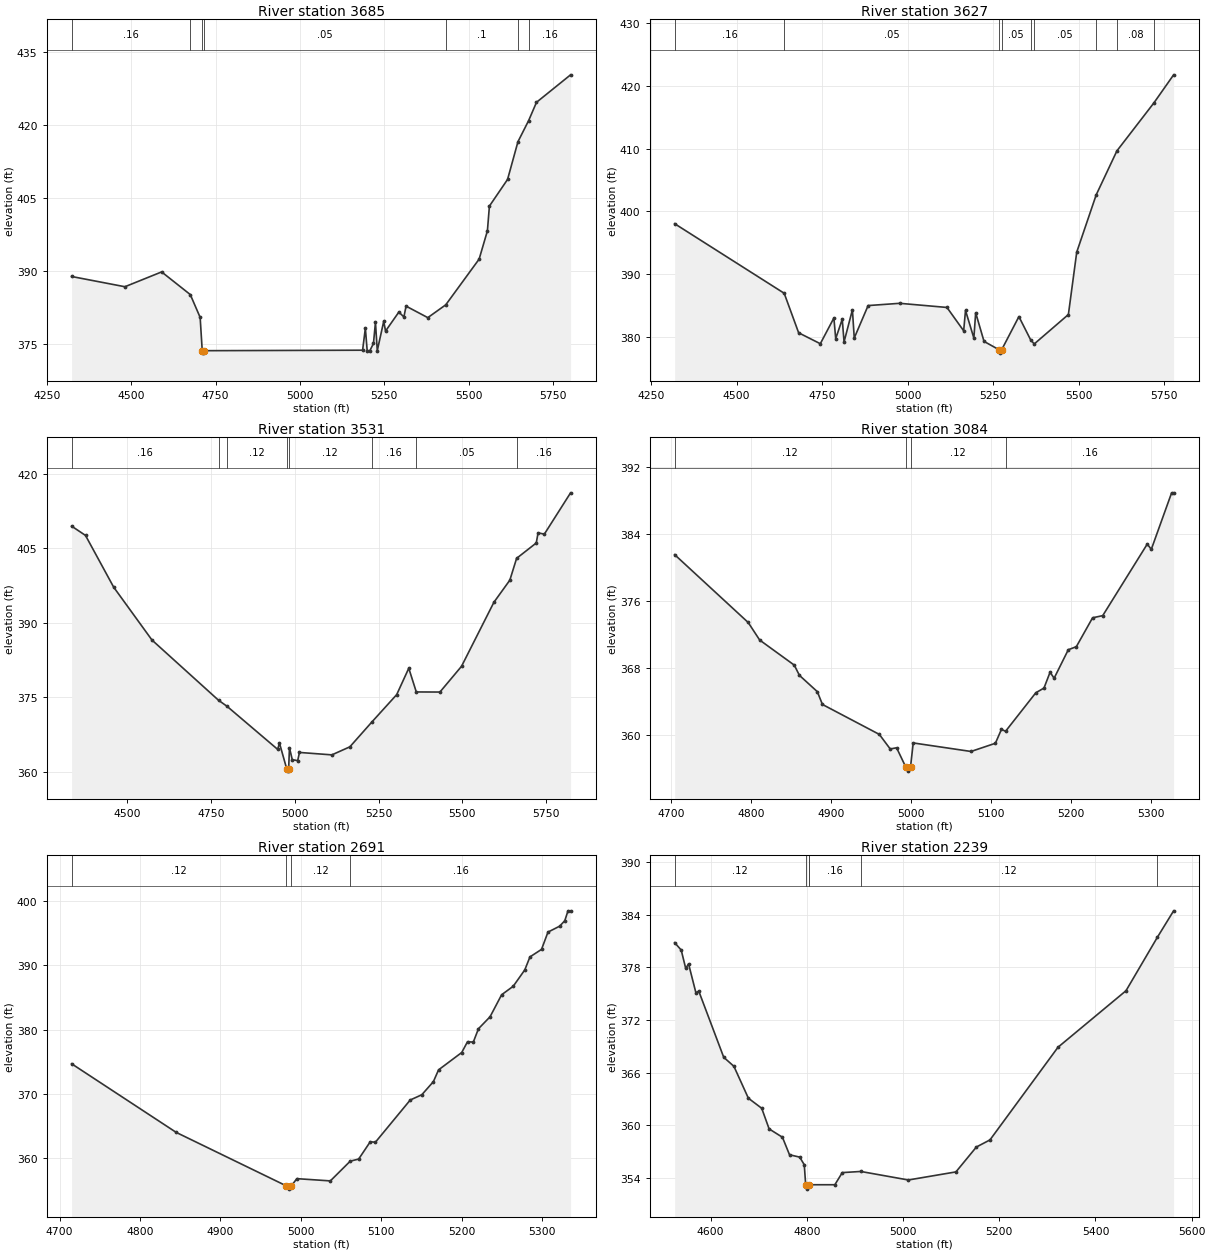
Type RM Length L Ch R = 1,3685,58,58,58
BEGIN DESCRIPTION:
UNT 047 IN CACR 8.0
END DESCRIPTION:
XS GIS Cut Line= 2
      3670882.99     10747038.36      3669505.46     10747574.79
#Sta/Elev= 30
  4323.6  388.91  4481.5  386.81  4590.3  389.85  4675.2  385.20  4704.4  380.52
  4710.6  373.69  4713.3  373.19  4716.6  373.69  5185.7  373.79  5193.9  378.30
  5199.3  373.69  5207.2  373.69  5217.9  375.17  5223.8  379.51  5229.2  373.69
  5248.3  379.72  5253.7  377.71  5293.1  381.61  5308.1  380.61  5314.5  382.83
  5378.9  380.47  5432.1  383.10  5531.0  392.48  5555.5  398.28  5561.4  403.35
  5615.2  408.82  5646.0  416.56  5677.7  420.90  5700.9  424.64  5801.9  430.28
#Mann=7,-1,0
  4323.6    0.16       0  4675.2    0.05       0  4710.6   0.033       0
  4716.6    0.05       0  5432.1     0.1       0  5646.0    0.08       0
  5677.7    0.16       0
Bank Sta=4710.6,4716.6
Exp/Cntr=0.3,0.1

Type RM Length L Ch R = 1,3627,96,96,96
BEGIN DESCRIPTION:
Mapping XS f5f30972
END DESCRIPTION:
XS GIS Cut Line= 2
      3670855.68     10746984.10      3669498.93     10747517.94
#Sta/Elev= 30
  4319.2  398.04  4639.3  386.95  4681.5  380.65  4744.8  378.91  4784.5  383.01
  4789.8  379.72  4808.9  382.81  4814.2  379.20  4838.6  384.31  4844.0  379.82
  4884.5  384.99  4976.8  385.35  5114.9  384.69  5163.7  380.97  5169.1  384.21
  5193.5  379.81  5198.8  383.85  5223.2  379.28  5268.4  377.91  5271.1  377.41
  5274.4  377.91  5325.1  383.23  5359.2  379.55  5369.9  378.87  5469.7  383.56
  5494.1  393.51  5551.0  402.64  5611.5  409.65  5719.5  417.29  5777.2  421.77
#Mann=9,-1,0
  4319.2    0.16       0  4639.3    0.05       0  5268.4    0.03       0
  5274.4    0.05       0  5359.2    0.16       0  5369.9    0.05       0
  5551.0     0.1       0  5611.5    0.08       0  5719.5    0.16       0
Bank Sta=5268.4,5274.4
Exp/Cntr=0.3,0.1

Type RM Length L Ch R = 1,3531,447,447,447
BEGIN DESCRIPTION:
UNT 047 IN CACR 7.0
END DESCRIPTION:
XS GIS Cut Line= 2
      3670792.28     10746909.76      3669406.81     10747451.45
#Sta/Elev= 30
  4334.9  409.45  4376.3  407.58  4460.4  397.16  4574.4  386.54  4772.9  374.42
  4798.3  373.20  4949.2  364.54  4954.6  365.80  4976.0  360.66  4978.8  360.16
  4982.0  360.66  4984.4  364.87  4992.7  362.47  5008.9  362.27  5014.2  363.92
  5110.8  363.43  5164.5  365.05  5229.9  370.03  5304.1  375.55  5340.1  380.86
  5362.5  376.09  5433.0  376.07  5497.4  381.25  5594.0  394.14  5641.4  398.58
  5661.6  402.97  5720.2  406.06  5725.6  408.10  5744.3  407.84  5822.5  416.15
#Mann=8,-1,0
  4334.9    0.16       0  4772.9    0.05       0  4798.3    0.12       0
  4976.0    0.07       0  4982.0    0.12       0  5229.9    0.16       0
  5362.5    0.05       0  5661.6    0.16       0
Bank Sta=4976,4982
Exp/Cntr=0.3,0.1

Type RM Length L Ch R = 1,3084,393,393,393
BEGIN DESCRIPTION:
Mapping XS e9781c03
END DESCRIPTION:
XS GIS Cut Line= 3
      3670099.61     10746560.19      3669899.61     10746810.19
      3669599.60     10746760.19
#Sta/Elev= 30
  4704.6  381.55  4796.6  373.44  4811.0  371.34  4854.3  368.34  4860.7  367.12
  4883.1  365.17  4889.5  363.64  4960.7  360.06  4974.3  358.32  4982.3  358.46
  4993.7  356.17  4996.5  355.67  4999.7  356.17  5003.1  359.04  5075.4  358.02
  5105.9  359.00  5113.5  360.67  5118.6  360.43  5156.5  365.04  5166.7  365.60
  5174.3  367.49  5179.4  366.78  5197.1  370.18  5207.2  370.55  5227.5  374.00
  5240.2  374.26  5295.9  382.81  5301.0  382.19  5326.4  388.94  5328.9  388.94
#Mann=4,-1,0
  4704.6    0.12       0  4993.7    0.07       0  4999.7    0.12       0
  5118.6    0.16       0
Bank Sta=4993.7,4999.7
Exp/Cntr=0.3,0.1

Type RM Length L Ch R = 1,2691,452,452,452
BEGIN DESCRIPTION:
Mapping XS f6c18e06
END DESCRIPTION:
XS GIS Cut Line= 3
      3669999.61     10746460.19      3669699.61     10746460.19
      3669499.58     10746710.22
#Sta/Elev= 30
  4715.0  374.67  4845.0  363.99  4982.0  355.66  4984.8  355.16  4988.0  355.66
  4995.0  356.79  5036.6  356.44  5061.3  359.51  5071.8  359.84  5086.2  362.53
  5092.6  362.46  5135.9  369.03  5150.3  369.85  5164.7  371.89  5171.1  373.72
  5199.9  376.42  5207.1  378.10  5214.3  378.04  5220.7  380.12  5235.1  381.98
  5249.5  385.41  5263.9  386.73  5278.3  389.28  5284.7  391.30  5299.1  392.47
  5307.1  395.16  5321.6  396.08  5328.0  396.93  5332.0  398.47  5335.2  398.47
#Mann=4,-1,0
  4715.0    0.12       0  4982.0    0.07       0  4988.0    0.12       0
  5061.3    0.16       0
Bank Sta=4982,4988
Exp/Cntr=0.3,0.1

Type RM Length L Ch R = 1,2239,441,441,441
BEGIN DESCRIPTION:
UNT 047 IN CACR 4.0
END DESCRIPTION:
XS GIS Cut Line= 3
      3670049.62     10745760.18      3669649.61     10746010.19
      3669249.60     10746410.19
#Sta/Elev= 30
  4525.1  380.80  4538.7  379.96  4548.1  377.87  4554.0  378.39  4569.3  375.09
  4575.2  375.29  4627.1  367.76  4648.3  366.73  4678.4  363.10  4706.1  361.96
  4721.5  359.61  4749.2  358.66  4763.9  356.67  4785.1  356.40  4794.6  355.53
  4797.5  353.26  4800.2  352.76  4803.5  353.26  4805.1  353.26  4858.2  353.26
  4873.6  354.64  4912.0  354.77  5011.0  353.80  5109.9  354.72  5152.4  357.55
  5180.7  358.36  5322.1  368.90  5463.5  375.33  5528.5  381.39  5562.5  384.42
#Mann=6,-1,0
  4525.1    0.12       0  4797.5    0.07       0  4803.5    0.12       0
  4805.1    0.16       0  4912.0    0.12       0  5528.5    0.16       0
Bank Sta=4797.5,4803.5
Exp/Cntr=0.3,0.1

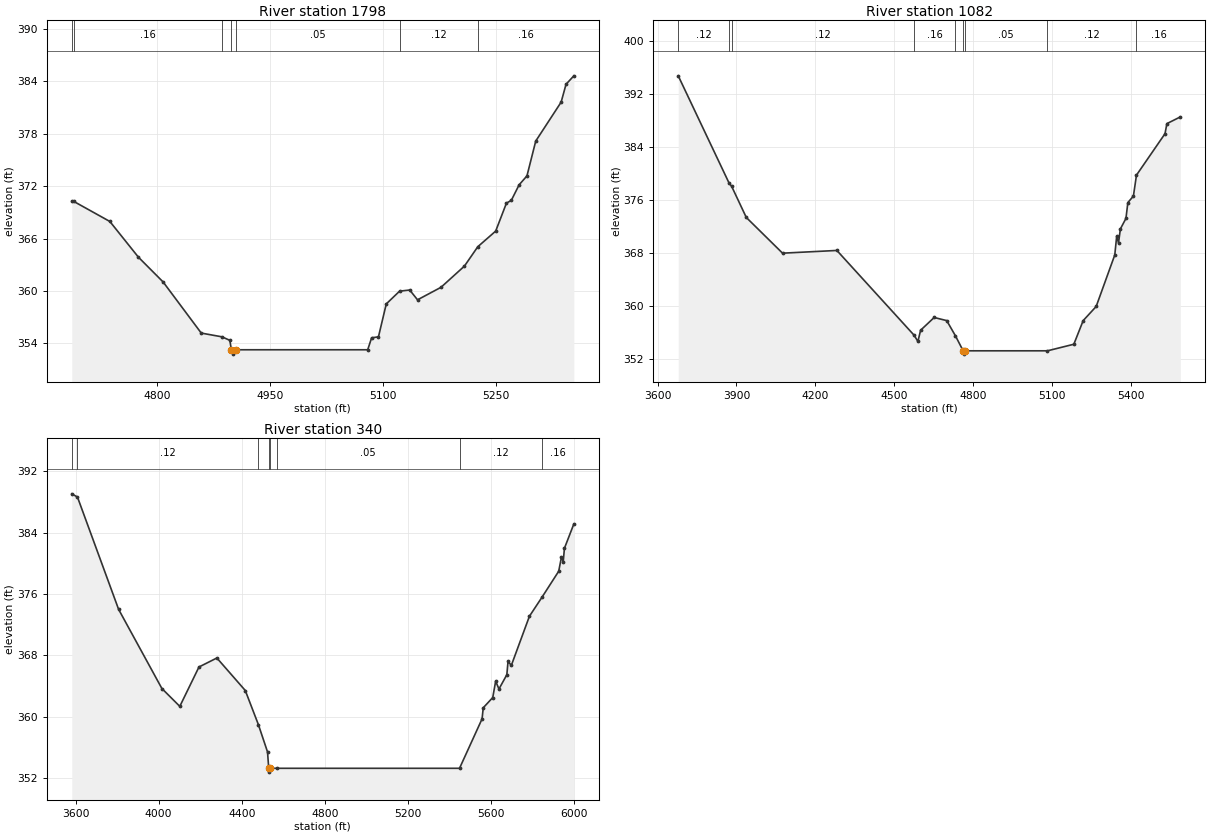
Type RM Length L Ch R = 1,1798,716,716,716
BEGIN DESCRIPTION:
Mapping XS 2ef0426a
END DESCRIPTION:
XS GIS Cut Line= 3
      3669399.60     10745460.21      3669349.61     10745760.19
      3668999.63     10745860.18
#Sta/Elev= 30
  4686.1  370.26  4688.5  370.26  4736.8  367.95  4774.8  363.86  4807.7  361.02
  4858.4  355.17  4886.0  354.74  4896.4  354.34  4898.5  353.26  4901.3  352.76
  4904.5  353.26  5079.9  353.26  5085.1  354.63  5094.2  354.74  5104.6  358.51
  5122.3  359.97  5135.8  360.10  5146.2  358.98  5177.4  360.41  5208.6  362.84
  5226.4  365.06  5250.2  366.85  5264.5  370.05  5271.0  370.37  5281.4  372.15
  5291.8  373.17  5303.5  377.16  5337.3  381.62  5343.8  383.66  5354.2  384.63
#Mann=7,-1,0
  4686.1    0.12       0  4688.5    0.16       0  4886.0    0.05       0
  4898.5   0.033       0  4904.5    0.05       0  5122.3    0.12       0
  5226.4    0.16       0
Bank Sta=4898.5,4904.5
Exp/Cntr=0.3,0.1

Type RM Length L Ch R = 1,1082,742,742,742
BEGIN DESCRIPTION:
UNT 047 IN CACR 2.0
END DESCRIPTION:
XS GIS Cut Line= 3
      3670414.85     10745446.60      3669086.68     10745123.67
      3668696.02     10745498.71
#Sta/Elev= 30
  3678.7  394.69  3871.8  378.54  3881.5  378.06  3937.4  373.35  4075.2  367.97
  4281.7  368.38  4575.4  355.60  4589.7  354.67  4600.0  356.36  4651.5  358.28
  4699.2  357.81  4732.3  355.52  4761.7  353.26  4764.4  352.76  4767.7  353.26
  5082.1  353.26  5182.4  354.25  5217.9  357.81  5267.3  359.94  5338.0  367.70
  5345.3  370.53  5352.2  369.53  5359.4  371.63  5380.5  373.21  5387.7  375.59
  5408.8  376.57  5420.5  379.73  5528.9  385.97  5536.2  387.49  5587.1  388.50
#Mann=9,-1,0
  3678.7    0.12       0  3871.8    0.16       0  3881.5    0.12       0
  4575.4    0.16       0  4732.3    0.05       0  4761.7   0.033       0
  4767.7    0.05       0  5082.1    0.12       0  5420.5    0.16       0
Bank Sta=4761.7,4767.7
Exp/Cntr=0.3,0.1

Type RM Length L Ch R = 1,340,0,0,0
BEGIN DESCRIPTION:
UNT 047 IN CACR 1.0
END DESCRIPTION:
XS GIS Cut Line= 4
      3670399.22     10745154.95      3669315.85     10744394.51
      3669149.18     10744399.72      3668701.24     10745212.26
#Sta/Elev= 30
  3581.4  389.07  3608.8  388.65  3807.1  373.99  4015.4  363.67  4101.7  361.34
  4194.1  366.48  4280.3  367.65  4417.1  363.41  4480.2  358.96  4524.3  355.39
  4530.0  353.26  4532.8  352.76  4536.0  353.26  4568.4  353.26  5449.0  353.26
  5557.6  359.71  5563.3  361.16  5609.0  362.49  5623.0  364.62  5639.0  363.61
  5676.9  365.47  5682.6  367.20  5698.6  366.69  5785.7  373.10  5846.2  375.58
  5926.7  378.97  5940.1  380.84  5948.5  380.22  5954.2  381.96  5999.6  385.14
#Mann=8,-1,0
  3581.4    0.16       0  3608.8    0.12       0  4480.2    0.16       0
  4530.0   0.033       0  4536.0    0.16       0  4568.4    0.05       0
  5449.0    0.12       0  5846.2    0.16       0
Bank Sta=4530,4536
Exp/Cntr=0.3,0.1

Chan Stop Cuts=-1