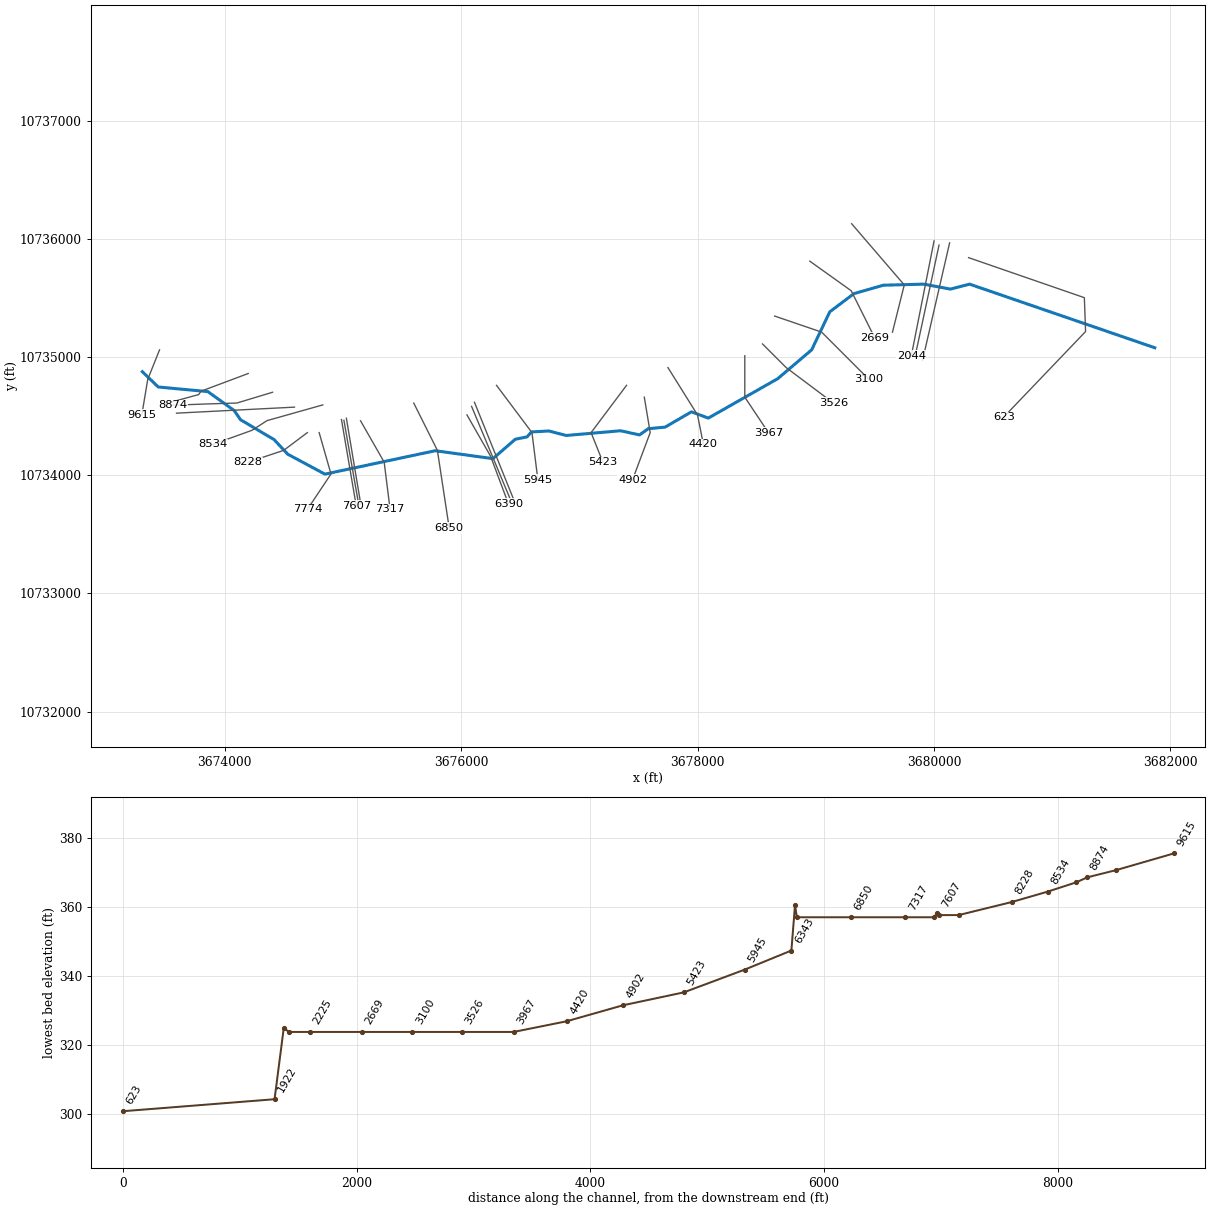
--- UNT 048 IN CACR.prj (project) ---

Proj Title=UNT 048 IN CACR Base Level Engineering
Current Plan=p01
Default Exp/Contr=0.3,0.1
English Units
Geom File=g01
Flow File=f01
Plan File=p01
BEGIN DESCRIPTION:
UNT 048 IN CACR
END DESCRIPTION:

--- UNT 048 IN CACR.p01 (plan) ---

Plan Title=Multiple Run
Short Identifier=Multiple
Geom File=g01
Flow File=f01
Subcritical Flow
K Sum by GR= 0
Std Step Tol= 0.01
Critical Tol= 0.01
Num of Std Step Trials= 20
Max Error Tol= 0.3
Flow Tol Ratio= 0.001
Split Flow NTrial= 30
Split Flow Tol= 0.02
Split Flow Ratio= 0.02
Log Output Level= 0
Friction Slope Method= 1
Unsteady Friction Slope Method= 2
Unsteady Bridges Friction Slope Method= 1
Parabolic Critical Depth
Global Vel Dist=  1 , 1 , 1
Global Log Level= 0
CheckData=True
Encroach Param= -1, 0, 0, 0
BEGIN DESCRIPTION:
Multiple Run
END DESCRIPTION:

--- UNT 048 IN CACR.f01 (steady flow) ---

Flow Title=Multiple
Number of Profiles=7
Profile Names=10-year,25-year,50-year,1pct_min,100-year,1pct_plu,500-year
River Rch & RM= UNT 048 IN CACR,Reach-1,9615
     772    1072    1325    1202    1626    2199    2452
River Rch & RM= UNT 048 IN CACR,Reach-1,7774
    1220    1740    2189    2019    2730    3692    4258
River Rch & RM= UNT 048 IN CACR,Reach-1,4902
    1298    1846    2318    2131    2882    3898    4470
Boundary for River Rch & Prof#=UNT 048 IN CACR,Reach-1,1
Up Type=0
Dn Type=3
Dn Slope=0.005
Boundary for River Rch & Prof#=UNT 048 IN CACR,Reach-1,2
Up Type=0
Dn Type=3
Dn Slope=0.005
Boundary for River Rch & Prof#=UNT 048 IN CACR,Reach-1,3
Up Type=0
Dn Type=3
Dn Slope=0.005
Boundary for River Rch & Prof#=UNT 048 IN CACR,Reach-1,4
Up Type=0
Dn Type=3
Dn Slope=0.005
Boundary for River Rch & Prof#=UNT 048 IN CACR,Reach-1,5
Up Type=0
Dn Type=3
Dn Slope=0.005
Boundary for River Rch & Prof#=UNT 048 IN CACR,Reach-1,6
Up Type=0
Dn Type=3
Dn Slope=0.005
Boundary for River Rch & Prof#=UNT 048 IN CACR,Reach-1,7
Up Type=0
Dn Type=3
Dn Slope=0.005

--- UNT 048 IN CACR.g01 (geometry) ---

Geom Title=Existing Conditions

River Reach=UNT 048 IN CACR,Reach-1
Reach XY= 30
      3673304.15     10734875.63      3673438.75     10734746.00
      3673858.25     10734707.00      3674081.00     10734547.00
      3674134.75     10734469.00      3674418.50     10734301.00
      3674533.50     10734178.00      3674848.50     10734009.00
      3675781.25     10734207.00      3676269.50     10734140.00
      3676458.50     10734304.00      3676558.00     10734324.00
      3676595.25     10734366.00      3676743.50     10734374.00
      3676889.25     10734336.00      3677348.75     10734376.00
      3677509.25     10734341.00      3677583.25     10734393.00
      3677726.25     10734407.00      3677948.50     10734536.00
      3678091.00     10734483.00      3678679.25     10734817.00
      3678965.75     10735061.00      3679118.50     10735382.00
      3679323.25     10735536.00      3679571.75     10735607.00
      3679913.75     10735616.00      3680139.25     10735574.00
      3680300.75     10735616.00      3681867.25     10735078.00

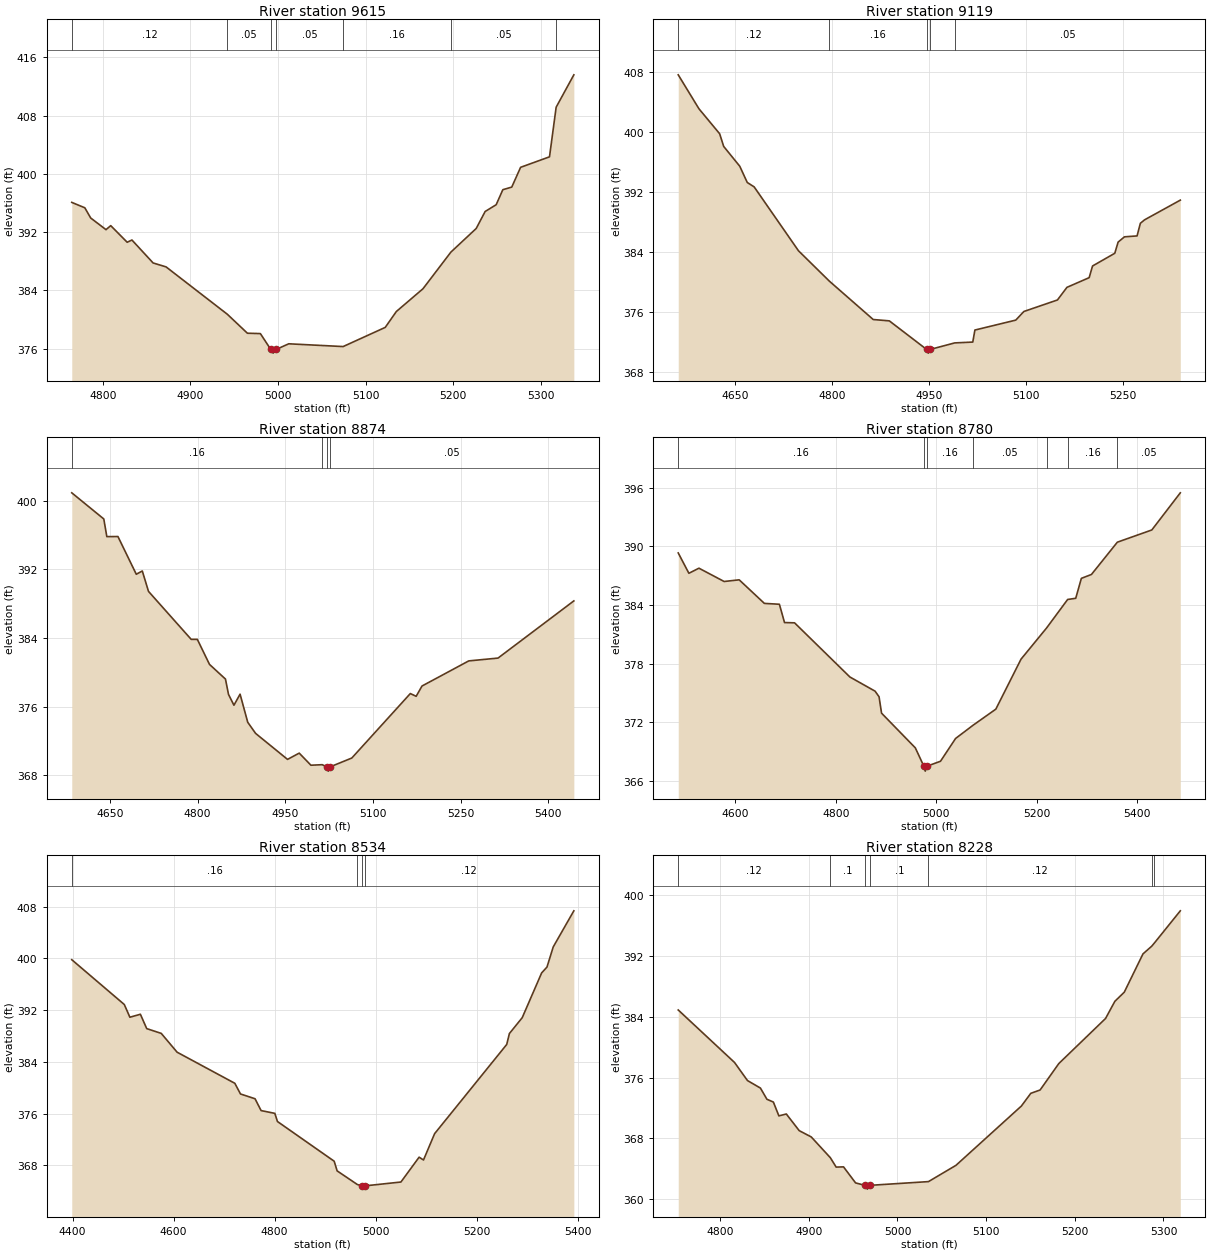
Type RM Length L Ch R = 1,9615,496,496,496
BEGIN DESCRIPTION:
UNT 048 IN CACR 19.0
END DESCRIPTION:
XS GIS Cut Line= 3
      3673449.62     10735060.23      3673349.61     10734810.19
      3673299.62     10734510.23
#Sta/Elev= 30
  4764.5  396.08  4779.4  395.34  4786.1  393.94  4803.6  392.34  4809.0  392.89
  4827.8  390.61  4833.2  390.92  4857.4  387.77  4872.2  387.23  4942.1  380.74
  4965.1  378.13  4979.9  378.08  4991.8  375.90  4994.5  375.40  4997.8  375.90
  5012.3  376.68  5074.4  376.30  5122.5  378.93  5135.2  381.11  5165.6  384.23
  5197.5  389.26  5226.4  392.50  5236.6  394.83  5249.2  395.76  5256.8  397.82
  5267.0  398.18  5277.1  400.89  5310.1  402.33  5317.7  409.14  5337.9  413.58
#Mann=7,-1,0
  4764.5    0.12       0  4942.1    0.05       0  4991.8    0.03       0
  4997.8    0.05       0  5074.4    0.16       0  5197.5    0.05       0
  5317.7    0.16       0
Bank Sta=4991.8,4997.8
Exp/Cntr=0.3,0.1

Type RM Length L Ch R = 1,9119,245,245,245
BEGIN DESCRIPTION:
UNT 048 IN CACR 18.0
END DESCRIPTION:
XS GIS Cut Line= 4
      3674199.61     10734860.19      3673799.61     10734710.19
      3673780.97     10734682.23      3673476.27     10734598.49
#Sta/Elev= 30
  4562.3  407.56  4594.3  403.05  4626.4  399.72  4632.6  398.04  4657.5  395.40
  4669.1  393.24  4679.8  392.65  4748.3  384.16  4796.2  380.11  4864.0  375.01
  4888.9  374.83  4946.5  371.04  4949.2  370.54  4952.5  371.04  4990.1  371.90
  5018.0  372.01  5021.3  373.61  5084.5  374.93  5097.1  376.08  5149.0  377.61
  5163.7  379.29  5198.1  380.58  5203.3  382.13  5237.7  383.82  5242.9  385.31
  5252.7  386.01  5272.2  386.13  5277.3  387.81  5283.8  388.27  5339.1  390.89
#Mann=5,-1,0
  4562.3    0.12       0  4796.2    0.16       0  4946.5    0.03       0
  4952.5    0.16       0  4990.1    0.05       0
Bank Sta=4946.5,4952.5
Exp/Cntr=0.3,0.1

Type RM Length L Ch R = 1,8874,94,94,94
BEGIN DESCRIPTION:
Mapping XS 925edc50
END DESCRIPTION:
XS GIS Cut Line= 4
      3674405.28     10734701.57      3674103.63     10734610.42
      3673855.15     10734602.83      3673559.96     10734591.97
#Sta/Elev= 30
  4584.7  400.94  4639.5  397.89  4644.7  395.83  4663.7  395.84  4695.1  391.44
  4705.4  391.82  4716.0  389.44  4789.1  383.84  4799.6  383.84  4820.4  380.92
  4847.7  379.21  4852.9  377.42  4862.2  376.16  4872.7  377.45  4885.8  374.17
  4899.3  372.87  4953.9  369.84  4973.9  370.57  4993.9  369.16  5013.3  369.22
  5020.9  368.97  5023.6  368.47  5026.9  368.97  5063.9  370.00  5164.0  377.52
  5174.0  377.20  5184.0  378.40  5264.0  381.33  5314.1  381.66  5443.8  388.33
#Mann=4,-1,0
  4584.7    0.16       0  5013.3    0.05       0  5020.9    0.07       0
  5026.9    0.05       0
Bank Sta=5020.9,5026.9
Exp/Cntr=0.3,0.1

Type RM Length L Ch R = 1,8780,246,246,246
BEGIN DESCRIPTION:
Mapping XS 94c90d01
END DESCRIPTION:
XS GIS Cut Line= 2
      3674590.80     10734575.70      3673593.00     10734524.78
#Sta/Elev= 30
  4486.3  389.34  4507.5  387.26  4527.5  387.78  4577.6  386.42  4607.6  386.59
  4657.7  384.18  4687.6  384.09  4697.8  382.22  4717.8  382.19  4827.9  376.65
  4878.0  375.20  4885.9  374.63  4890.9  372.95  4958.1  369.40  4975.1  367.52
  4977.9  367.02  4981.1  367.52  5008.2  368.03  5038.2  370.36  5072.9  371.71
  5118.3  373.36  5168.4  378.47  5219.4  381.67  5261.2  384.58  5277.3  384.70
  5288.5  386.74  5308.6  387.14  5360.1  390.44  5428.7  391.69  5485.4  395.49
#Mann=7,-1,0
  4486.3    0.16       0  4975.1    0.07       0  4981.1    0.16       0
  5072.9    0.05       0  5219.4    0.12       0  5261.2    0.16       0
  5360.1    0.05       0
Bank Sta=4975.1,4981.1
Exp/Cntr=0.3,0.1

Type RM Length L Ch R = 1,8534,306,306,306
BEGIN DESCRIPTION:
UNT 048 IN CACR 17.0
END DESCRIPTION:
XS GIS Cut Line= 4
      3674830.43     10734594.59      3674359.05     10734461.77
      3674231.45     10734379.74      3673899.56     10734260.17
#Sta/Elev= 30
  4398.3  399.80  4502.3  392.87  4513.4  390.90  4534.2  391.36  4546.7  389.14
  4575.5  388.40  4606.9  385.49  4721.2  380.68  4732.4  379.03  4761.2  378.29
  4773.2  376.46  4800.4  376.03  4805.6  374.77  4917.9  368.63  4923.8  367.13
  4963.7  365.03  4972.4  364.81  4975.1  364.31  4978.4  364.81  5050.1  365.41
  5086.1  369.25  5094.8  368.82  5116.8  372.89  5259.6  386.69  5264.9  388.38
  5290.3  390.83  5328.7  397.75  5339.3  398.66  5351.7  401.78  5392.5  407.36
#Mann=4,-1,0
  4398.3    0.16       0  4963.7    0.12       0  4972.4    0.07       0
  4978.4    0.12       0
Bank Sta=4972.4,4978.4
Exp/Cntr=0.3,0.1

Type RM Length L Ch R = 1,8228,454,454,454
BEGIN DESCRIPTION:
UNT 048 IN CACR 16.0
END DESCRIPTION:
XS GIS Cut Line= 3
      3674699.60     10734360.18      3674499.61     10734210.19
      3674199.63     10734110.19
#Sta/Elev= 30
  4752.8  384.89  4816.3  377.98  4830.9  375.60  4845.5  374.61  4852.8  373.14
  4860.1  372.77  4866.3  370.95  4874.7  371.20  4889.2  369.01  4902.8  368.18
  4924.3  365.45  4930.9  364.21  4939.2  364.24  4952.8  362.13  4963.3  361.81
  4966.1  361.31  4969.3  361.81  5035.0  362.30  5066.0  364.44  5139.8  372.25
  5150.4  373.92  5160.9  374.36  5182.0  377.84  5234.7  383.77  5245.2  386.03
  5255.8  387.23  5276.9  392.27  5286.8  393.29  5289.8  393.71  5319.0  397.94
#Mann=7,-1,0
  4752.8    0.12       0  4924.3     0.1       0  4963.3    0.07       0
  4969.3     0.1       0  5035.0    0.12       0  5286.8    0.16       0
  5289.8    0.12       0
Bank Sta=4963.3,4969.3
Exp/Cntr=0.3,0.1

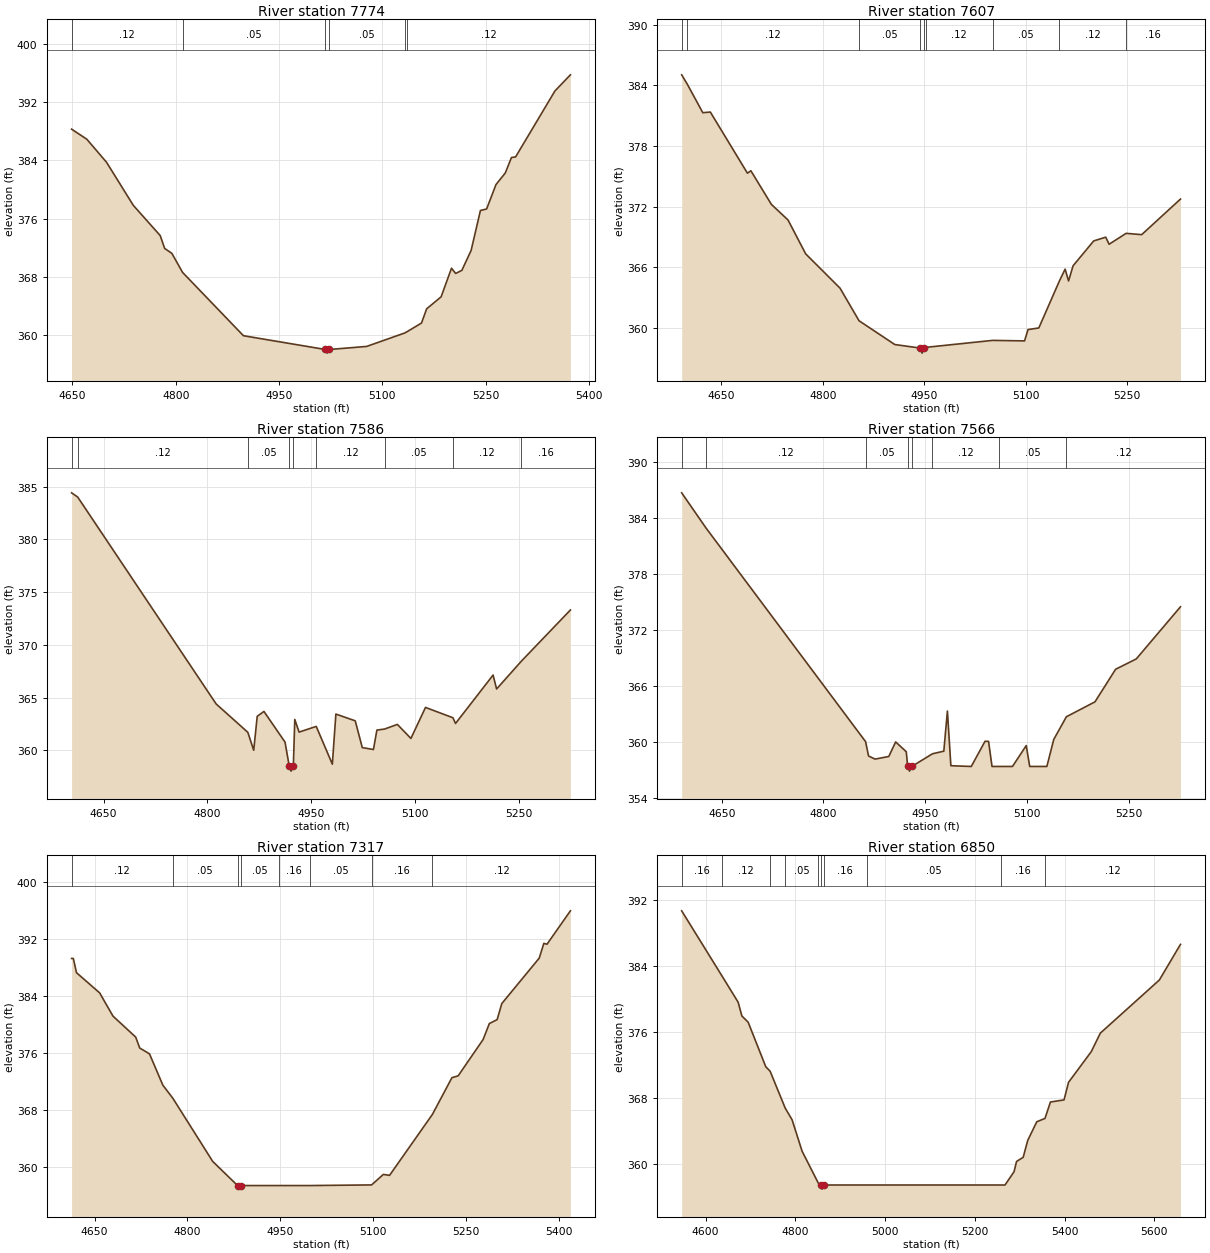
Type RM Length L Ch R = 1,7774,167,167,167
BEGIN DESCRIPTION:
UNT 048 IN CACR 15.0
END DESCRIPTION:
XS GIS Cut Line= 3
      3674799.62     10734360.16      3674899.61     10734010.19
      3674699.62     10733710.21
#Sta/Elev= 30
  4648.8  388.28  4670.9  386.90  4699.5  383.74  4738.5  377.81  4777.5  373.67
  4784.0  371.90  4794.4  371.23  4810.1  368.60  4898.4  359.92  5017.3  358.03
  5020.0  357.53  5023.3  358.03  5077.4  358.45  5132.5  360.29  5136.2  360.48
  5157.0  361.66  5164.5  363.61  5185.5  365.26  5200.6  369.19  5206.6  368.47
  5215.6  368.89  5229.1  371.63  5242.6  377.11  5251.6  377.32  5265.2  380.67
  5278.7  382.26  5287.7  384.39  5293.7  384.47  5350.8  393.52  5373.3  395.74
#Mann=6,-1,0
  4648.8    0.12       0  4810.1    0.05       0  5017.3    0.03       0
  5023.3    0.05       0  5132.5    0.16       0  5136.2    0.12       0
Bank Sta=5017.3,5023.3
Exp/Cntr=0.3,0.1

Type RM Length L Ch R = 1,7607,21,21,21
BEGIN DESCRIPTION:
Mapping XS 4066f52d
END DESCRIPTION:
XS GIS Cut Line= 2
      3674988.16     10734471.09      3675112.87     10733743.60
#Sta/Elev= 30
  4591.1  385.05  4599.2  384.15  4622.4  381.30  4633.5  381.37  4688.4  375.32
  4693.5  375.56  4723.9  372.23  4748.5  370.69  4774.6  367.34  4825.4  363.95
  4853.6  360.72  4906.5  358.37  4944.1  358.02  4946.9  357.52  4950.1  358.02
  4952.4  358.09  5051.2  358.78  5098.5  358.73  5103.6  359.85  5119.6  360.01
  5150.0  364.65  5158.5  365.83  5163.6  364.66  5170.3  366.16  5200.8  368.62
  5218.6  368.99  5223.6  368.29  5248.8  369.37  5271.8  369.24  5329.2  372.76
#Mann=9,-1,0
  4591.1    0.16       0  4599.2    0.12       0  4853.6    0.05       0
  4944.1    0.07       0  4950.1    0.05       0  4952.4    0.12       0
  5051.2    0.05       0  5150.0    0.12       0  5248.8    0.16       0
Bank Sta=4944.1,4950.1
Exp/Cntr=0.3,0.1

Type RM Length L Ch R = 1,7586,20,20,20
BEGIN DESCRIPTION:
Mapping XS a567b406
END DESCRIPTION:
XS GIS Cut Line= 2
      3675008.99     10734464.13      3675133.73     10733753.80
#Sta/Elev= 30
  4603.7  384.41  4612.5  384.01  4812.7  364.39  4858.5  361.70  4867.0  360.00
  4872.1  363.22  4881.8  363.68  4912.3  360.77  4918.3  358.52  4921.1  358.02
  4924.3  358.52  4926.4  362.92  4932.6  361.72  4957.4  362.26  4980.7  358.68
  4985.8  363.43  5013.8  362.79  5024.0  360.25  5040.1  360.07  5045.1  361.91
  5056.2  362.01  5074.7  362.45  5094.3  361.12  5115.4  364.06  5155.1  363.08
  5158.8  362.54  5213.1  367.13  5218.2  365.81  5253.9  368.44  5324.9  373.30
#Mann=9,-1,0
  4603.7    0.16       0  4612.5    0.12       0  4858.5    0.05       0
  4918.3    0.07       0  4924.3    0.05       0  4957.4    0.12       0
  5056.2    0.05       0  5155.1    0.12       0  5253.9    0.16       0
Bank Sta=4918.3,4924.3
Exp/Cntr=0.3,0.1

Type RM Length L Ch R = 1,7566,249,249,249
BEGIN DESCRIPTION:
Mapping XS a373093c
END DESCRIPTION:
XS GIS Cut Line= 2
      3675029.82     10734481.53      3675151.35     10733755.84
#Sta/Elev= 30
  4590.8  386.74  4626.5  382.99  4862.1  360.06  4866.5  358.52  4876.1  358.19
  4896.3  358.47  4906.5  360.03  4922.1  358.98  4924.2  357.40  4926.9  356.90
  4930.2  357.40  4960.8  358.76  4977.5  359.04  4982.8  363.34  4987.9  357.48
  5018.0  357.40  5038.3  360.10  5043.5  360.09  5048.6  357.40  5059.6  357.40
  5078.8  357.40  5099.1  359.64  5104.2  357.40  5129.5  357.40  5139.7  360.30
  5158.3  362.73  5200.5  364.33  5230.9  367.82  5261.4  368.93  5326.6  374.52
#Mann=8,-1,0
  4590.8    0.16       0  4626.5    0.12       0  4862.1    0.05       0
  4924.2    0.07       0  4930.2    0.05       0  4960.8    0.12       0
  5059.6    0.05       0  5158.3    0.12       0
Bank Sta=4924.2,4930.2
Exp/Cntr=0.3,0.1

Type RM Length L Ch R = 1,7317,467,467,467
BEGIN DESCRIPTION:
UNT 048 IN CACR 14.0
END DESCRIPTION:
XS GIS Cut Line= 3
      3675149.63     10734460.15      3675349.61     10734110.19
      3675399.61     10733710.17
#Sta/Elev= 30
  4612.9  389.23  4615.7  389.23  4620.8  387.24  4658.2  384.41  4679.8  381.15
  4716.5  378.21  4723.0  376.68  4738.8  375.86  4760.4  371.47  4776.5  369.64
  4841.0  360.78  4881.2  357.40  4884.0  356.90  4887.2  357.40  4948.0  357.40
  4997.4  357.40  5097.8  357.49  5116.7  358.96  5126.8  358.83  5196.1  367.38
  5227.6  372.52  5237.7  372.78  5278.0  377.87  5288.1  380.11  5300.7  380.66
  5308.2  382.91  5368.7  389.28  5376.2  391.35  5381.3  391.23  5419.1  395.91
#Mann=8,-1,0
  4612.9    0.12       0  4776.5    0.05       0  4881.2   0.033       0
  4887.2    0.05       0  4948.0    0.16       0  4997.4    0.05       0
  5097.8    0.16       0  5196.1    0.12       0
Bank Sta=4881.2,4887.2
Exp/Cntr=0.3,0.1

Type RM Length L Ch R = 1,6850,460,460,460
BEGIN DESCRIPTION:
UNT 048 IN CACR 13.0
END DESCRIPTION:
XS GIS Cut Line= 3
      3675599.61     10734610.18      3675799.61     10734210.19
      3675899.48     10733553.75
#Sta/Elev= 30
  4546.9  390.74  4636.5  382.84  4672.7  379.63  4681.1  377.95  4695.0  377.20
  4734.2  371.79  4744.0  371.23  4777.5  366.76  4792.9  365.33  4815.2  361.51
  4851.6  357.60  4856.9  357.40  4859.7  356.90  4862.9  357.40  4959.1  357.40
  5257.7  357.40  5267.2  357.40  5287.4  359.02  5292.9  360.26  5307.7  360.77
  5317.8  362.82  5338.0  365.09  5356.3  365.50  5368.4  367.49  5398.7  367.75
  5408.8  369.89  5459.4  373.62  5479.6  375.87  5611.1  382.33  5658.1  386.66
#Mann=10,-1,0
  4546.9    0.16       0  4636.5    0.12       0  4744.0    0.16       0
  4777.5    0.05       0  4851.6    0.16       0  4856.9   0.033       0
  4862.9    0.16       0  4959.1    0.05       0  5257.7    0.16       0
  5356.3    0.12       0
Bank Sta=4856.9,4862.9
Exp/Cntr=0.3,0.1

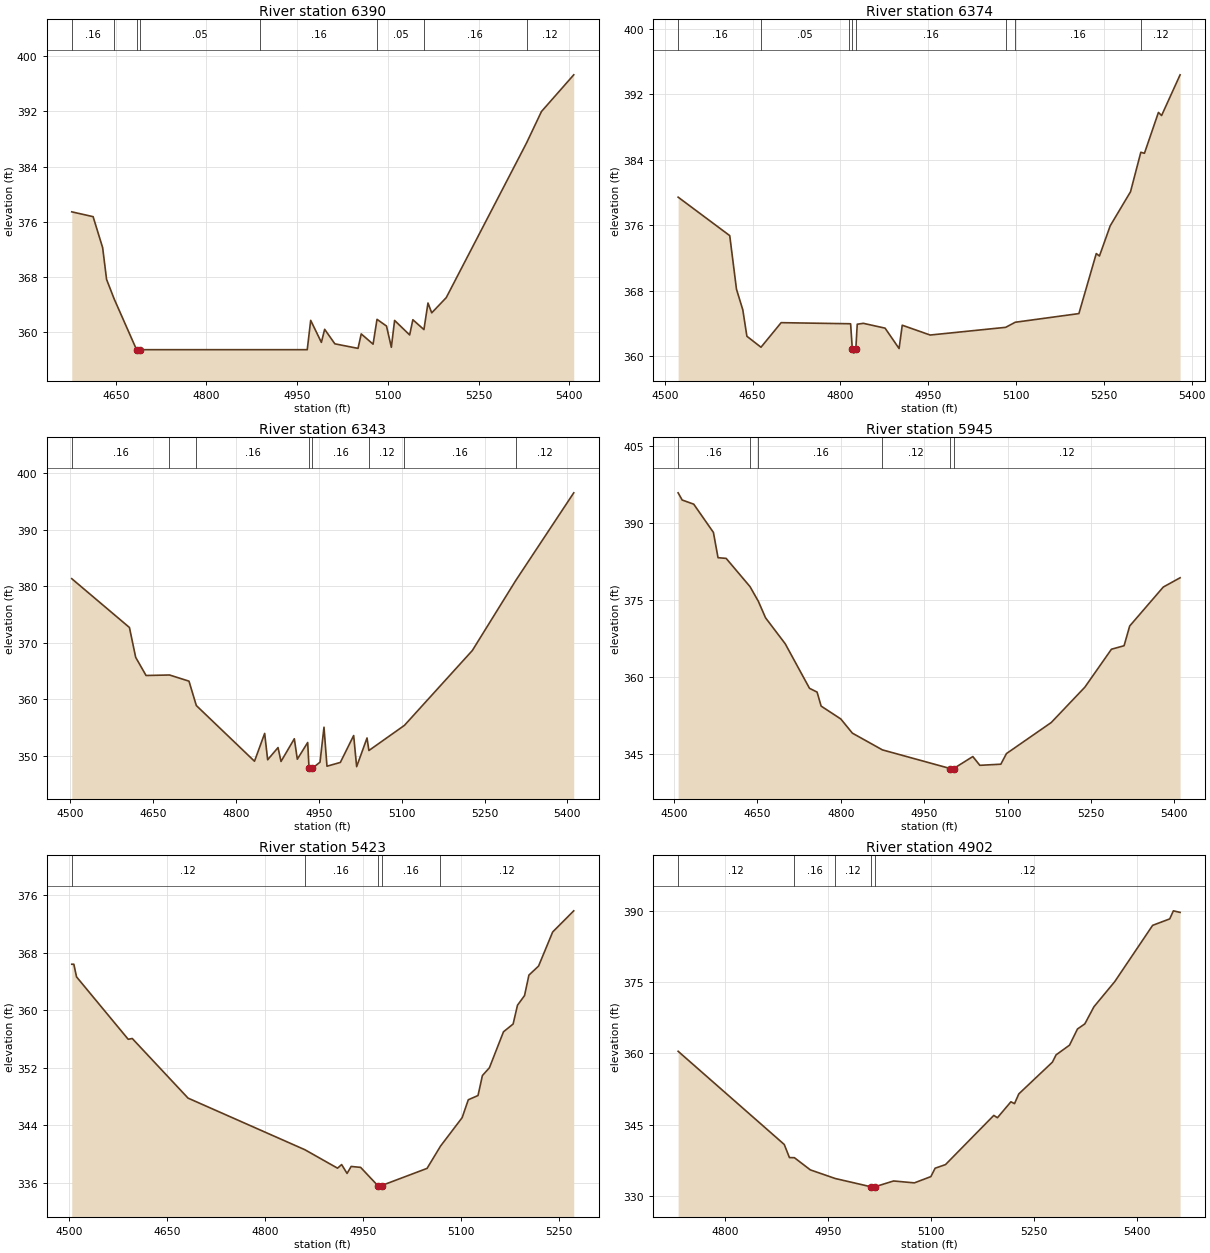
Type RM Length L Ch R = 1,6390,16,16,16
BEGIN DESCRIPTION:
UNT 048 IN CACR 12.0
END DESCRIPTION:
XS GIS Cut Line= 3
      3676049.59     10734510.21      3676249.61     10734160.19
      3676399.59     10733760.23
#Sta/Elev= 30
  4577.2  377.42  4612.5  376.72  4628.3  372.21  4634.8  367.60  4647.4  364.76
  4684.4  357.40  4687.1  356.90  4690.4  357.40  4888.4  357.40  4966.7  357.40
  4972.4  361.66  4990.1  358.46  4995.5  360.36  5012.4  358.25  5050.7  357.59
  5056.0  359.69  5075.6  358.20  5082.1  361.81  5097.8  360.83  5105.8  357.75
  5111.2  361.65  5136.1  359.54  5141.4  361.75  5159.7  360.32  5166.4  364.18
  5172.6  362.75  5196.6  364.96  5329.4  387.42  5354.1  391.99  5407.5  397.32
#Mann=8,-1,0
  4577.2    0.16       0  4647.4    0.05       0  4684.4    0.07       0
  4690.4    0.05       0  4888.4    0.16       0  5082.1    0.05       0
  5159.7    0.16       0  5329.4    0.12       0
Bank Sta=4684.4,4690.4
Exp/Cntr=0.3,0.1

Type RM Length L Ch R = 1,6374,31,31,31
BEGIN DESCRIPTION:
Mapping XS da29c8b8
END DESCRIPTION:
XS GIS Cut Line= 2
      3676088.85     10734582.22      3676418.69     10733790.59
#Sta/Elev= 30
  4522.7  379.42  4610.9  374.72  4622.4  368.18  4633.2  365.66  4640.2  362.43
  4664.3  361.09  4698.7  364.09  4814.8  363.96  4817.4  363.95  4820.3  360.87
  4823.0  360.37  4826.3  360.87  4828.7  363.90  4839.1  364.01  4876.3  363.42
  4900.2  360.93  4905.6  363.78  4953.3  362.58  5082.3  363.52  5098.6  364.14
  5207.4  365.20  5237.1  372.53  5242.5  372.23  5260.9  375.92  5295.6  380.08
  5313.2  384.90  5319.4  384.78  5343.3  389.77  5348.7  389.39  5380.3  394.36
#Mann=8,-1,0
  4522.7    0.16       0  4664.3    0.05       0  4814.8    0.16       0
  4820.3    0.07       0  4826.3    0.16       0  5082.3    0.05       0
  5098.6    0.16       0  5313.2    0.12       0
Bank Sta=4820.3,4826.3
Exp/Cntr=0.3,0.1

Type RM Length L Ch R = 1,6343,398,398,398
BEGIN DESCRIPTION:
Mapping XS 05c7ca2e
END DESCRIPTION:
XS GIS Cut Line= 2
      3676113.14     10734616.98      3676453.01     10733774.23
#Sta/Elev= 30
  4502.8  381.33  4607.2  372.69  4618.5  367.41  4637.3  364.19  4679.7  364.28
  4715.0  363.19  4728.3  358.87  4833.6  349.01  4852.0  353.94  4857.4  349.27
  4876.2  351.43  4881.6  348.97  4905.7  352.99  4911.1  349.37  4929.9  352.33
  4932.3  347.76  4935.0  347.26  4938.3  347.76  4952.2  348.85  4959.4  355.04
  4964.8  348.13  4989.0  348.80  5013.1  353.56  5018.5  348.05  5037.3  353.13
  5040.7  350.91  5105.0  355.36  5227.9  368.61  5306.4  380.99  5411.5  396.53
#Mann=8,-1,0
  4502.8    0.16       0  4679.7    0.05       0  4728.3    0.16       0
  4932.3    0.07       0  4938.3    0.16       0  5040.7    0.12       0
  5105.0    0.16       0  5306.4    0.12       0
Bank Sta=4932.3,4938.3
Exp/Cntr=0.3,0.1

Type RM Length L Ch R = 1,5945,522,522,522
BEGIN DESCRIPTION:
UNT 048 IN CACR 11.0
END DESCRIPTION:
XS GIS Cut Line= 3
      3676299.63     10734760.16      3676599.61     10734360.19
      3676649.61     10733960.17
#Sta/Elev= 30
  4507.3  395.97  4514.6  394.57  4535.4  393.76  4570.8  388.26  4579.1  383.33
  4593.7  383.20  4636.7  377.69  4651.7  374.82  4664.6  371.62  4700.0  366.56
  4743.7  357.88  4757.3  357.15  4764.6  354.42  4800.0  351.91  4820.8  349.15
  4874.8  345.89  4997.0  342.25  4999.7  341.75  5003.0  342.25  5037.5  344.59
  5050.1  342.88  5087.9  343.10  5098.0  345.17  5178.6  351.22  5239.1  358.11
  5286.9  365.50  5309.6  366.18  5319.7  370.02  5380.1  377.61  5410.4  379.42
#Mann=6,-1,0
  4507.3    0.16       0  4636.7    0.05       0  4651.7    0.16       0
  4874.8    0.12       0  4997.0    0.07       0  5003.0    0.12       0
Bank Sta=4997,5003
Exp/Cntr=0.3,0.1

Type RM Length L Ch R = 1,5423,521,521,521
BEGIN DESCRIPTION:
Mapping XS 556ad8c8
END DESCRIPTION:
XS GIS Cut Line= 3
      3677399.63     10734760.22      3677099.61     10734360.19
      3677199.61     10734110.19
#Sta/Elev= 30
  4503.5  366.37  4506.7  366.37  4510.8  364.62  4590.0  355.95  4596.2  356.06
  4681.7  347.78  4860.8  340.61  4910.8  338.05  4917.1  338.55  4925.4  337.32
  4931.7  338.29  4946.2  338.16  4972.4  335.64  4975.2  335.14  4978.4  335.64
  5048.0  338.02  5068.6  341.11  5101.8  345.07  5111.2  347.55  5126.1  348.14
  5132.8  350.91  5143.6  352.00  5165.1  356.99  5179.9  358.07  5186.6  360.68
  5197.4  362.02  5204.1  364.86  5218.9  366.12  5240.5  370.85  5272.8  373.79
#Mann=5,-1,0
  4503.5    0.12       0  4860.8    0.16       0  4972.4    0.07       0
  4978.4    0.16       0  5068.6    0.12       0
Bank Sta=4972.4,4978.4
Exp/Cntr=0.3,0.1

Type RM Length L Ch R = 1,4902,482,482,482
BEGIN DESCRIPTION:
UNT 048 IN CACR 9.0
END DESCRIPTION:
XS GIS Cut Line= 3
      3677549.61     10734660.16      3677599.61     10734360.19
      3677449.61     10733960.20
#Sta/Elev= 30
  4732.1  360.46  4886.7  340.81  4894.3  338.04  4901.5  338.02  4924.7  335.45
  4961.0  333.63  5012.9  331.89  5015.7  331.39  5018.9  331.89  5046.0  333.11
  5076.3  332.71  5100.3  334.03  5106.5  335.80  5121.6  336.56  5192.0  346.94
  5197.3  346.45  5216.9  349.81  5222.2  349.42  5228.4  351.47  5277.4  358.17
  5282.7  359.70  5302.3  361.75  5313.9  365.16  5324.6  366.24  5337.9  369.85
  5368.2  375.15  5423.4  387.02  5448.3  388.38  5453.6  390.08  5463.4  389.75
#Mann=5,-1,0
  4732.1    0.12       0  4901.5    0.16       0  4961.0    0.12       0
  5012.9    0.07       0  5018.9    0.12       0
Bank Sta=5012.9,5018.9
Exp/Cntr=0.3,0.1

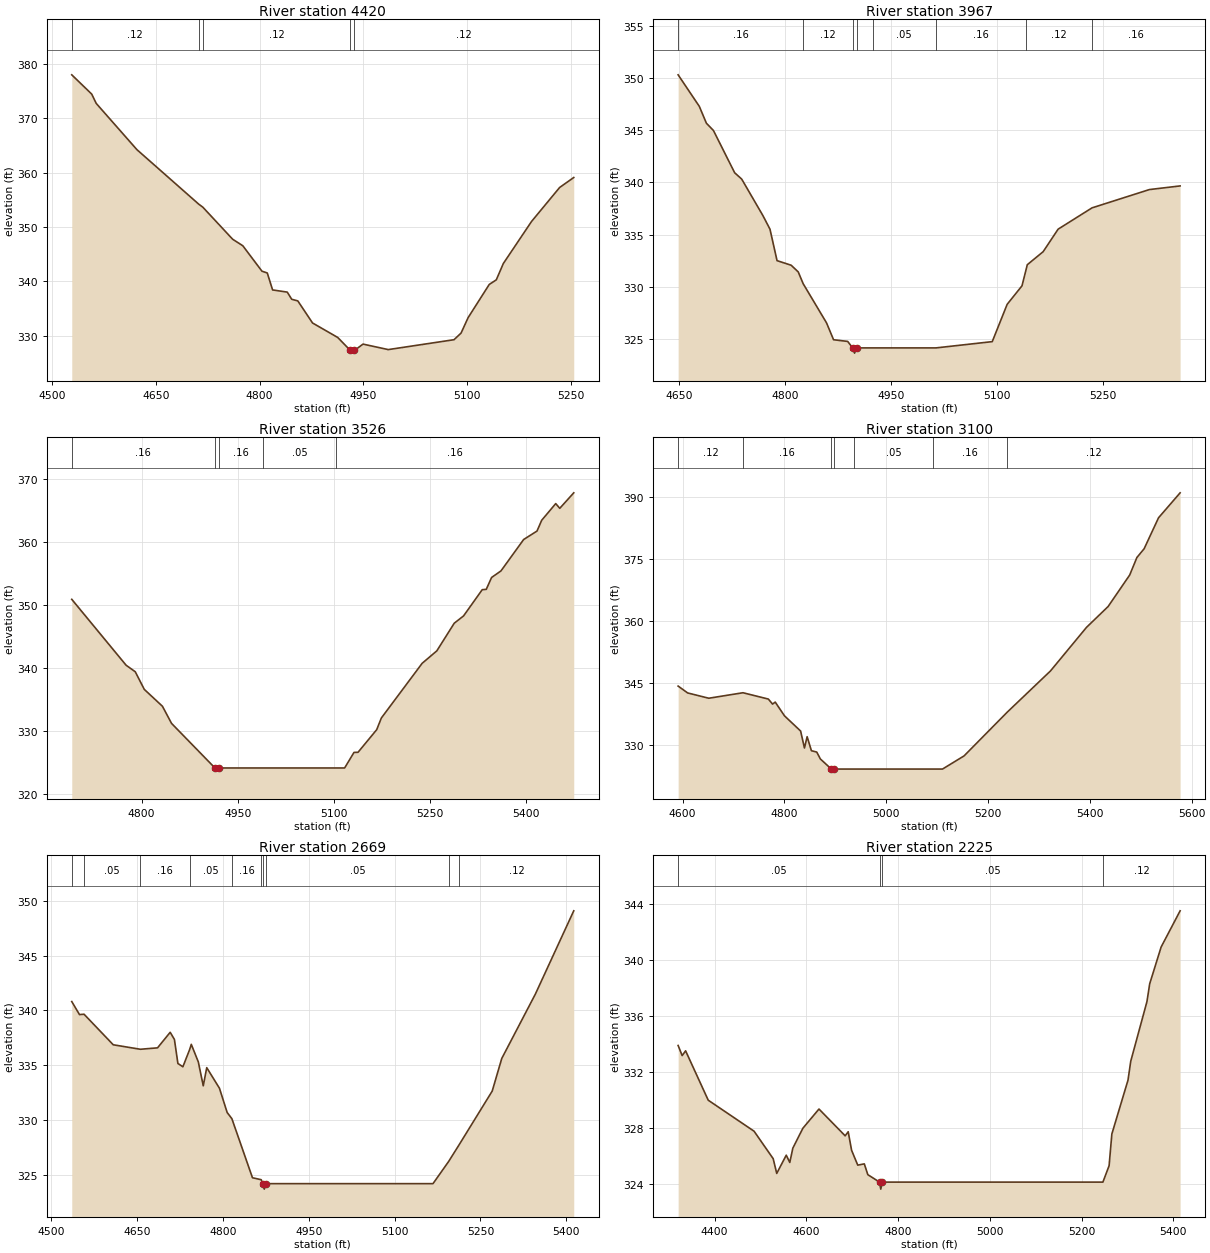
Type RM Length L Ch R = 1,4420,453,453,453
BEGIN DESCRIPTION:
UNT 048 IN CACR 8.0
END DESCRIPTION:
XS GIS Cut Line= 3
      3677749.61     10734910.18      3677999.61     10734510.19
      3678049.60     10734260.23
#Sta/Elev= 30
  4528.0  377.98  4556.9  374.43  4563.4  372.72  4622.3  364.21  4711.5  354.21
  4717.8  353.61  4760.9  347.72  4775.6  346.52  4803.3  341.84  4811.0  341.51
  4818.7  338.39  4839.9  337.99  4846.4  336.67  4855.2  336.37  4876.5  332.31
  4913.0  329.64  4931.2  327.26  4934.0  326.76  4937.2  327.26  4949.6  328.42
  4986.1  327.41  5081.3  329.23  5091.5  330.45  5101.7  333.29  5132.3  339.40
  5142.5  340.25  5152.7  343.26  5193.5  350.99  5234.2  357.25  5254.6  359.08
#Mann=5,-1,0
  4528.0    0.12       0  4711.5    0.16       0  4717.8    0.12       0
  4931.2    0.07       0  4937.2    0.12       0
Bank Sta=4931.2,4937.2
Exp/Cntr=0.3,0.1

Type RM Length L Ch R = 1,3967,441,441,441
BEGIN DESCRIPTION:
UNT 048 IN CACR 7.0
END DESCRIPTION:
XS GIS Cut Line= 3
      3678399.61     10735010.18      3678399.61     10734660.19
      3678599.59     10734360.22
#Sta/Elev= 30
  4648.3  350.30  4678.3  347.28  4688.3  345.67  4698.3  344.97  4728.3  340.93
  4738.3  340.32  4768.3  336.83  4778.3  335.53  4788.3  332.52  4808.3  332.08
  4818.3  331.44  4825.3  330.31  4858.3  326.57  4868.3  324.95  4888.3  324.79
  4895.3  324.17  4898.0  323.67  4901.3  324.17  4923.4  324.17  5013.3  324.17
  5092.9  324.77  5114.0  328.34  5135.0  330.11  5140.2  331.51  5142.5  332.13
  5165.0  333.38  5186.1  335.53  5234.1  337.57  5315.3  339.32  5358.8  339.67
#Mann=8,-1,0
  4648.3    0.16       0  4825.3    0.12       0  4895.3   0.033       0
  4901.3    0.12       0  4923.4    0.05       0  5013.3    0.16       0
  5140.2    0.12       0  5234.1    0.16       0
Bank Sta=4895.3,4901.3
Exp/Cntr=0.3,0.1

Type RM Length L Ch R = 1,3526,426,426,426
BEGIN DESCRIPTION:
UNT 048 IN CACR 6.0
END DESCRIPTION:
XS GIS Cut Line= 3
      3678549.61     10735110.18      3678749.61     10734910.19
      3679149.58     10734610.21
#Sta/Elev= 30
  4691.2  350.95  4776.0  340.48  4790.2  339.45  4804.3  336.65  4832.6  333.97
  4846.8  331.25  4914.5  324.17  4917.2  323.67  4920.5  324.17  4989.0  324.17
  5104.0  324.17  5116.7  324.17  5131.3  326.64  5137.6  326.66  5166.7  330.25
  5174.0  332.11  5237.6  340.79  5260.5  342.77  5287.6  347.15  5302.2  348.32
  5331.3  352.48  5337.6  352.54  5345.9  354.42  5360.5  355.46  5395.9  360.45
  5416.7  361.79  5424.0  363.50  5445.9  366.15  5452.2  365.40  5474.0  367.86
#Mann=5,-1,0
  4691.2    0.16       0  4914.5   0.033       0  4920.5    0.16       0
  4989.0    0.05       0  5104.0    0.16       0
Bank Sta=4914.5,4920.5
Exp/Cntr=0.3,0.1

Type RM Length L Ch R = 1,3100,431,431,431
BEGIN DESCRIPTION:
UNT 048 IN CACR 5.0
END DESCRIPTION:
XS GIS Cut Line= 3
      3678651.90     10735346.12      3679049.61     10735210.19
      3679449.62     10734810.17
#Sta/Elev= 30
  4591.4  344.25  4610.1  342.59  4651.6  341.31  4718.8  342.64  4768.6  341.11
  4776.9  339.89  4782.1  340.38  4800.3  337.05  4832.0  333.37  4839.5  329.27
  4844.8  332.00  4853.2  328.61  4863.7  328.28  4870.8  326.61  4892.4  324.17
  4895.2  323.67  4898.4  324.17  4937.7  324.17  5092.1  324.17  5110.7  324.17
  5153.1  327.36  5237.9  337.95  5322.8  347.92  5393.5  358.46  5436.0  363.51
  5478.4  371.14  5492.5  375.37  5506.7  377.48  5535.0  384.98  5577.4  391.02
#Mann=7,-1,0
  4591.4    0.12       0  4718.8    0.16       0  4892.4   0.033       0
  4898.4    0.16       0  4937.7    0.05       0  5092.1    0.16       0
  5237.9    0.12       0
Bank Sta=4892.4,4898.4
Exp/Cntr=0.3,0.1

Type RM Length L Ch R = 1,2669,444,444,444
BEGIN DESCRIPTION:
UNT 048 IN CACR 4.0
END DESCRIPTION:
XS GIS Cut Line= 3
      3678949.62     10735810.18      3679299.61     10735560.19
      3679499.60     10735160.20
#Sta/Elev= 30
  4535.8  340.81  4549.3  339.62  4557.3  339.65  4608.3  336.86  4655.7  336.45
  4685.7  336.58  4707.8  338.00  4715.2  337.35  4721.3  335.15  4730.0  334.85
  4741.8  336.42  4744.7  336.90  4757.0  335.29  4765.6  333.11  4771.7  334.77
  4793.9  332.89  4807.4  330.67  4815.6  330.11  4851.6  324.71  4866.9  324.53
  4869.5  324.17  4872.3  323.67  4875.5  324.17  5167.1  324.17  5194.5  326.20
  5213.1  327.75  5270.6  332.63  5287.3  335.61  5346.0  341.49  5413.1  349.10
#Mann=10,-1,0
  4535.8    0.16       0  4557.3    0.05       0  4655.7    0.16       0
  4741.8    0.05       0  4815.6    0.16       0  4866.9    0.05       0
  4869.5   0.033       0  4875.5    0.05       0  5194.5    0.16       0
  5213.1    0.12       0
Bank Sta=4869.5,4875.5
Exp/Cntr=0.3,0.1

Type RM Length L Ch R = 1,2225,181,181,181
BEGIN DESCRIPTION:
Mapping XS d5ab27e4
END DESCRIPTION:
XS GIS Cut Line= 3
      3679303.44     10736126.84      3679748.55     10735609.31
      3679648.73     10735210.02
#Sta/Elev= 30
  4320.4  333.91  4329.2  333.19  4336.7  333.53  4386.0  330.01  4485.9  327.80
  4527.6  325.84  4535.3  324.79  4556.1  326.09  4563.8  325.57  4570.4  326.59
  4592.3  328.01  4627.4  329.38  4684.5  327.47  4691.1  327.76  4698.5  326.44
  4711.9  325.38  4726.2  325.47  4733.9  324.70  4759.4  324.17  4762.1  323.67
  4765.4  324.17  5246.3  324.17  5259.8  325.34  5265.8  327.60  5301.0  331.44
  5307.0  332.79  5342.3  337.04  5348.3  338.31  5373.2  340.93  5414.6  343.51
#Mann=4,-1,0
  4320.4    0.05       0  4759.4   0.033       0  4765.4    0.05       0
  5246.3    0.12       0
Bank Sta=4759.4,4765.4
Exp/Cntr=0.3,0.1

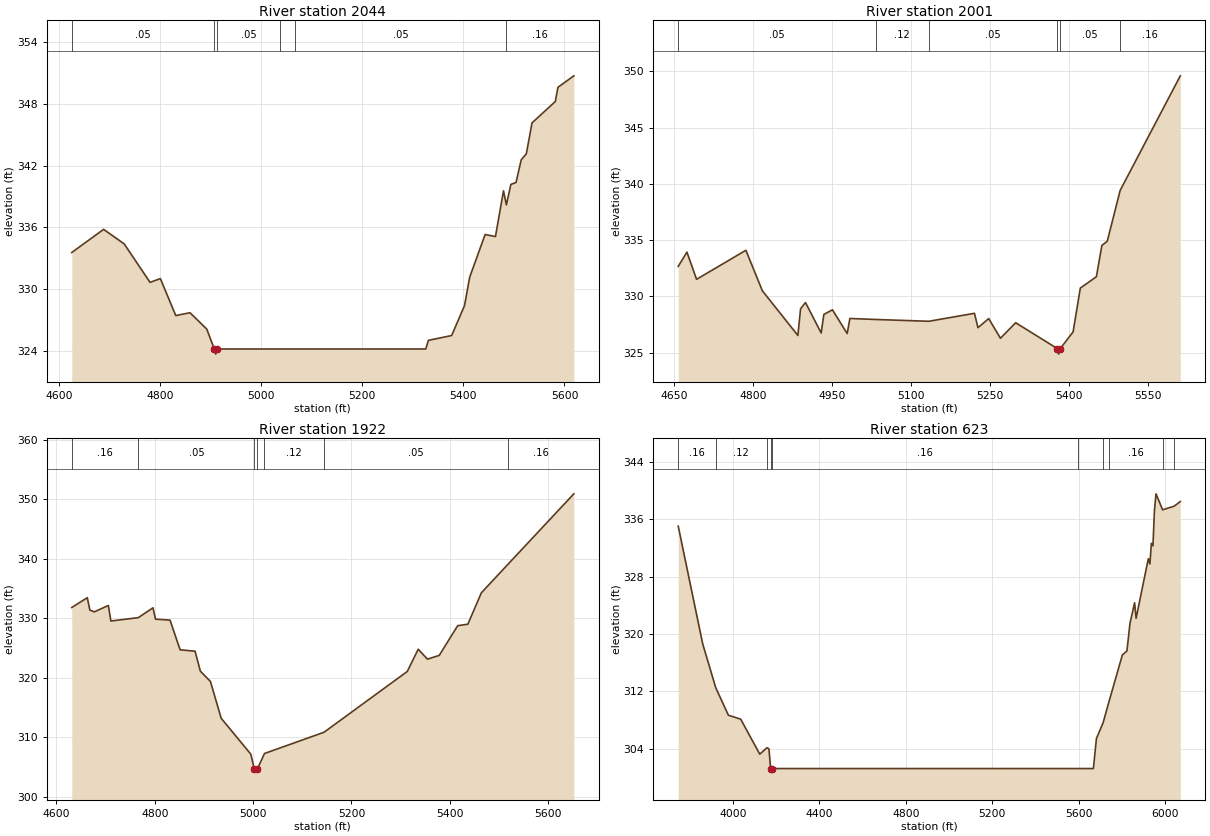
Type RM Length L Ch R = 1,2044,43,43,43
BEGIN DESCRIPTION:
Mapping XS 4e69e29f
END DESCRIPTION:
XS GIS Cut Line= 2
      3680000.44     10735982.02      3679807.74     10735008.10
#Sta/Elev= 30
  4625.8  333.56  4688.8  335.81  4729.6  334.39  4780.6  330.65  4801.0  331.02
  4831.5  327.42  4859.5  327.70  4892.7  326.11  4907.7  324.17  4910.5  323.67
  4913.7  324.17  5037.3  324.17  5067.9  324.17  5325.8  324.17  5331.0  325.01
  5377.0  325.48  5402.4  328.39  5412.6  331.15  5443.2  335.31  5463.6  335.11
  5479.5  339.56  5485.2  338.19  5494.1  340.19  5504.3  340.37  5514.5  342.57
  5524.7  343.17  5535.9  346.17  5582.0  348.25  5587.1  349.63  5618.6  350.75
#Mann=6,-1,0
  4625.8    0.05       0  4907.7    0.03       0  4913.7    0.05       0
  5037.3    0.12       0  5067.9    0.05       0  5485.2    0.16       0
Bank Sta=4907.7,4913.7
Exp/Cntr=0.3,0.1

Type RM Length L Ch R = 1,2001,79,79,79
BEGIN DESCRIPTION:
Mapping XS f9d52683
END DESCRIPTION:
XS GIS Cut Line= 2
      3680042.54     10735946.33      3679842.15     10735014.64
#Sta/Elev= 30
  4657.7  332.67  4674.2  333.94  4692.5  331.52  4786.1  334.10  4817.4  330.50
  4884.8  326.53  4889.9  328.90  4899.2  329.46  4929.0  326.75  4934.1  328.40
  4950.4  328.81  4978.4  326.70  4983.5  328.04  5032.4  327.95  5133.5  327.79
  5220.0  328.50  5226.6  327.22  5247.0  328.03  5269.3  326.28  5298.2  327.66
  5377.0  325.37  5379.7  324.87  5383.0  325.37  5407.2  326.85  5420.9  330.74
  5451.4  331.75  5461.8  334.53  5472.1  334.91  5496.5  339.42  5610.7  349.61
#Mann=6,-1,0
  4657.7    0.05       0  5032.4    0.12       0  5133.5    0.05       0
  5377.0    0.03       0  5383.0    0.05       0  5496.5    0.16       0
Bank Sta=5377,5383
Exp/Cntr=0.3,0.1

Type RM Length L Ch R = 1,1922,1299,1299,1299
BEGIN DESCRIPTION:
UNT 048 IN CACR 2.0
END DESCRIPTION:
XS GIS Cut Line= 2
      3680131.96     10735964.90      3679902.80     10734970.16
#Sta/Elev= 30
  4631.4  331.84  4663.0  333.49  4668.1  331.42  4677.3  331.11  4705.8  332.18
  4710.9  329.57  4766.8  330.14  4796.5  331.79  4801.7  329.88  4831.2  329.72
  4851.7  324.73  4882.1  324.50  4892.8  321.15  4913.3  319.42  4935.2  313.23
  4995.4  307.20  5002.7  304.68  5005.4  304.18  5008.7  304.68  5023.2  307.31
  5144.3  310.88  5313.5  321.09  5335.8  324.83  5354.6  323.16  5378.6  323.80
  5416.1  328.79  5436.7  329.03  5464.1  334.30  5518.6  339.13  5652.2  350.94
#Mann=7,-1,0
  4631.4    0.16       0  4766.8    0.05       0  5002.7    0.03       0
  5008.7    0.05       0  5023.2    0.12       0  5144.3    0.05       0
  5518.6    0.16       0
Bank Sta=5002.7,5008.7
Exp/Cntr=0.3,0.1

Type RM Length L Ch R = 1,623,0,0,0
BEGIN DESCRIPTION:
UNT 048 IN CACR 1.0
END DESCRIPTION:
XS GIS Cut Line= 4
      3680292.53     10735840.13      3681271.72     10735501.58
      3681282.13     10735215.12      3680589.42     10734491.16
#Sta/Elev= 30
  3746.1  335.06  3859.4  318.62  3919.6  312.51  3978.3  308.65  4035.3  308.10
  4123.5  303.21  4157.1  304.11  4166.2  303.95  4173.8  301.20  4176.6  300.70
  4179.8  301.20  5598.1  301.20  5668.3  301.20  5682.4  305.39  5713.5  307.61
  5739.0  310.38  5802.6  317.08  5823.7  317.63  5837.8  321.50  5859.2  324.36
  5866.1  322.19  5922.7  330.51  5930.0  329.78  5936.9  332.67  5944.1  332.32
  5951.0  337.22  5958.3  339.58  5988.7  337.35  6042.1  337.85  6070.8  338.50
#Mann=10,-1,0
  3746.1    0.16       0  3919.6    0.12       0  4157.1    0.16       0
  4173.8   0.033       0  4179.8    0.16       0  5598.1    0.16       0
  5713.5    0.12       0  5739.0    0.16       0  5988.7    0.12       0
  6042.1    0.05       0
Bank Sta=4173.8,4179.8
Exp/Cntr=0.3,0.1

Chan Stop Cuts=-1