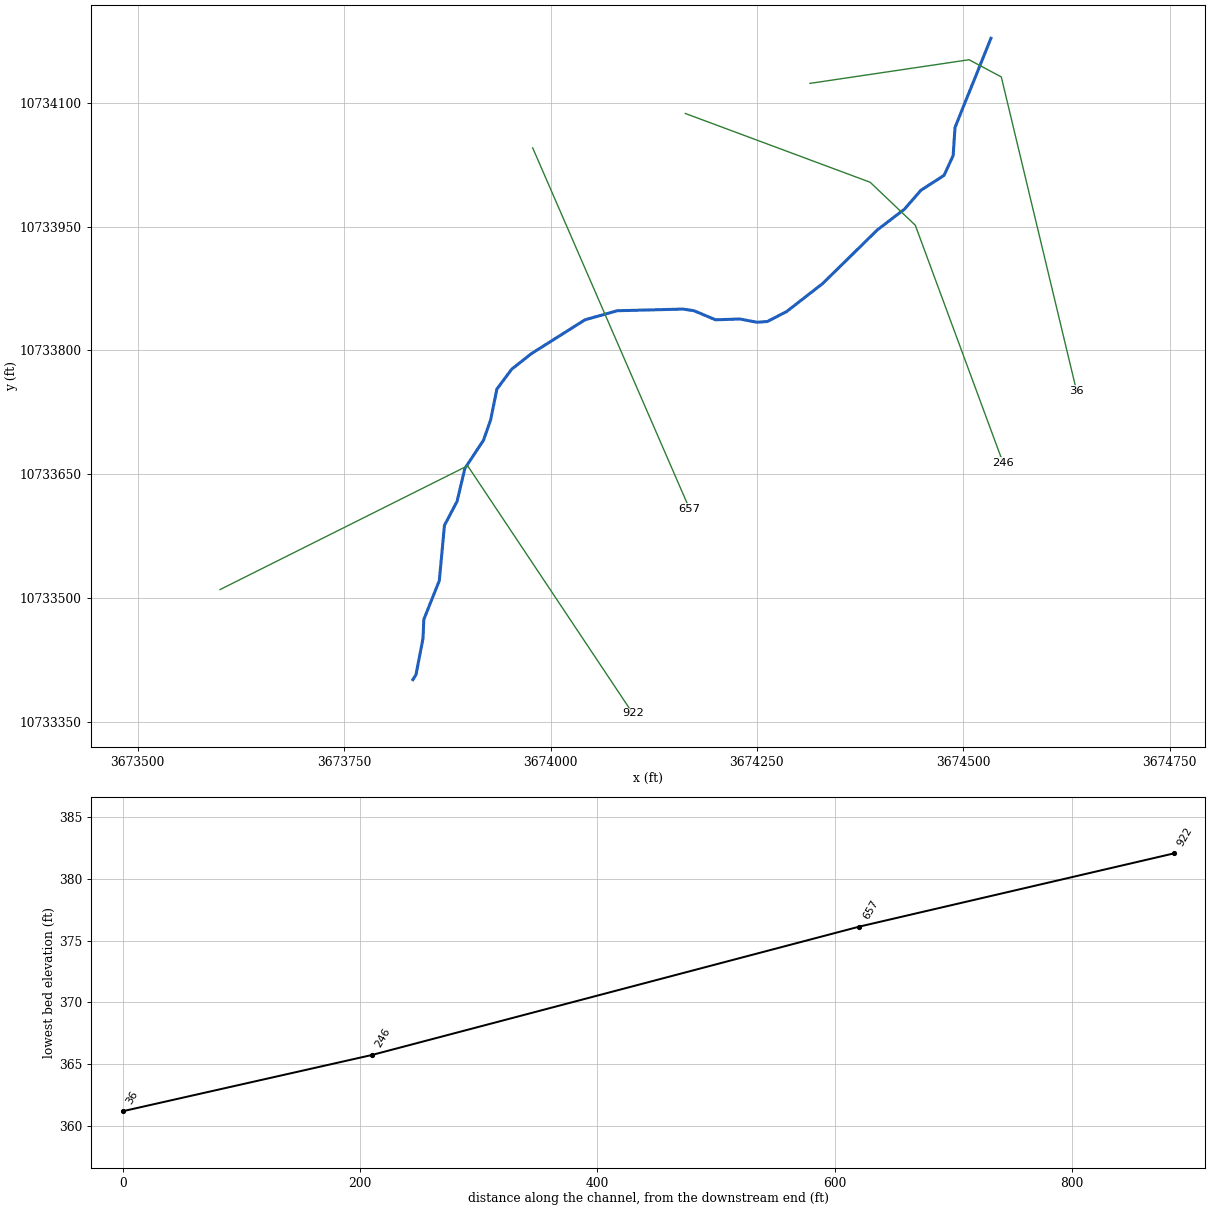
--- UNT 049 IN CACR.prj (project) ---

Proj Title=UNT 049 IN CACR Base Level Engineering
Current Plan=p01
Default Exp/Contr=0.3,0.1
English Units
Geom File=g01
Flow File=f01
Plan File=p01
BEGIN DESCRIPTION:
UNT 049 IN CACR
END DESCRIPTION:

--- UNT 049 IN CACR.p01 (plan) ---

Plan Title=Multiple Run
Short Identifier=Multiple
Geom File=g01
Flow File=f01
Subcritical Flow
K Sum by GR= 0
Std Step Tol= 0.01
Critical Tol= 0.01
Num of Std Step Trials= 20
Max Error Tol= 0.3
Flow Tol Ratio= 0.001
Split Flow NTrial= 30
Split Flow Tol= 0.02
Split Flow Ratio= 0.02
Log Output Level= 0
Friction Slope Method= 1
Unsteady Friction Slope Method= 2
Unsteady Bridges Friction Slope Method= 1
Parabolic Critical Depth
Global Vel Dist=  1 , 1 , 1
Global Log Level= 0
CheckData=True
Encroach Param= -1, 0, 0, 0
BEGIN DESCRIPTION:
Multiple Run
END DESCRIPTION:

--- UNT 049 IN CACR.f01 (steady flow) ---

Flow Title=Multiple
Number of Profiles=7
Profile Names=10-year,25-year,50-year,1pct_min,100-year,1pct_plu,500-year
River Rch & RM= UNT 049 IN CACR,Reach-1,922
     384     512     617     548     741    1002    1068
Boundary for River Rch & Prof#=UNT 049 IN CACR,Reach-1,1
Up Type=0
Dn Type=3
Dn Slope=0.005
Boundary for River Rch & Prof#=UNT 049 IN CACR,Reach-1,2
Up Type=0
Dn Type=3
Dn Slope=0.005
Boundary for River Rch & Prof#=UNT 049 IN CACR,Reach-1,3
Up Type=0
Dn Type=3
Dn Slope=0.005
Boundary for River Rch & Prof#=UNT 049 IN CACR,Reach-1,4
Up Type=0
Dn Type=3
Dn Slope=0.005
Boundary for River Rch & Prof#=UNT 049 IN CACR,Reach-1,5
Up Type=0
Dn Type=3
Dn Slope=0.005
Boundary for River Rch & Prof#=UNT 049 IN CACR,Reach-1,6
Up Type=0
Dn Type=3
Dn Slope=0.005
Boundary for River Rch & Prof#=UNT 049 IN CACR,Reach-1,7
Up Type=0
Dn Type=3
Dn Slope=0.005

--- UNT 049 IN CACR.g01 (geometry) ---

Geom Title=Existing Conditions

River Reach=UNT 049 IN CACR,Reach-1
Reach XY= 30
      3673833.26     10733401.15      3673837.00     10733407.00
      3673845.50     10733451.00      3673846.50     10733474.00
      3673865.25     10733521.00      3673871.50     10733588.00
      3673886.75     10733617.00      3673896.25     10733657.00
      3673918.75     10733691.00      3673927.50     10733716.00
      3673935.00     10733753.00      3673952.75     10733777.00
      3673976.75     10733796.00      3674041.75     10733837.00
      3674080.75     10733848.00      3674160.50     10733850.00
      3674173.75     10733848.00      3674200.00     10733837.00
      3674229.25     10733838.00      3674250.25     10733834.00
      3674262.75     10733835.00      3674286.00     10733847.00
      3674329.75     10733881.00      3674396.00     10733946.00
      3674428.75     10733971.00      3674448.75     10733994.00
      3674476.75     10734012.00      3674487.75     10734036.00
      3674490.00     10734070.00      3674533.50     10734178.00

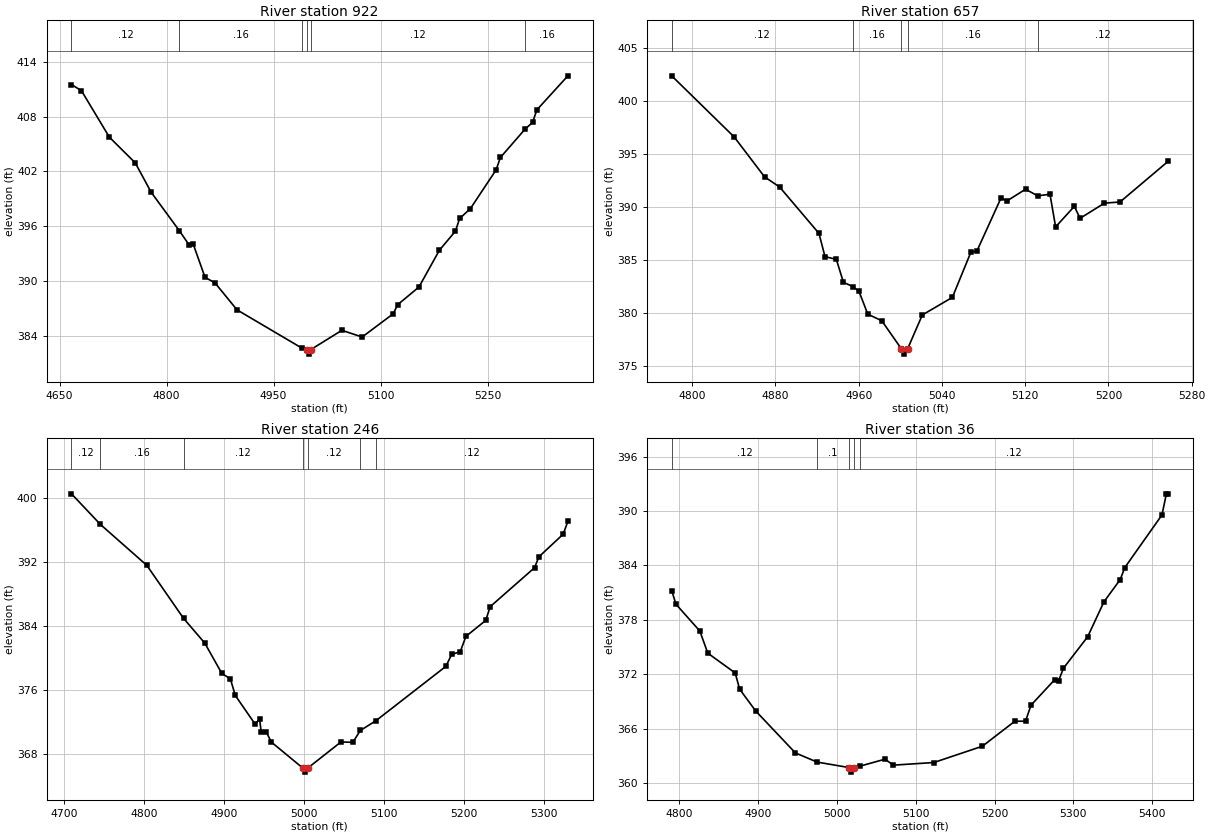
Type RM Length L Ch R = 1,922,265,265,265
BEGIN DESCRIPTION:
UNT 049 IN CACR 2.0
END DESCRIPTION:
XS GIS Cut Line= 3
      3673599.63     10733510.20      3673899.61     10733660.19
      3674099.59     10733360.22
#Sta/Elev= 30
  4666.7  411.50  4680.7  410.82  4719.8  405.75  4756.1  402.94  4778.5  399.72
  4818.0  395.52  4831.6  393.98  4837.2  394.10  4853.9  390.44  4867.9  389.83
  4898.7  386.89  4990.3  382.68  4996.3  382.55  4999.0  382.05  5002.3  382.55
  5045.7  384.65  5074.2  383.92  5117.8  386.46  5123.8  387.44  5153.8  389.38
  5182.4  393.39  5204.9  395.48  5210.9  396.87  5225.9  397.94  5262.0  402.18
  5268.0  403.53  5302.6  406.63  5313.1  407.36  5319.1  408.73  5362.6  412.45
#Mann=6,-1,0
  4666.7    0.12       0  4818.0    0.16       0  4990.3    0.12       0
  4996.3    0.07       0  5002.3    0.12       0  5302.6    0.16       0
Bank Sta=4996.3,5002.3
Exp/Cntr=0.3,0.1

Type RM Length L Ch R = 1,657,411,411,411
BEGIN DESCRIPTION:
Mapping XS 8b1a2264
END DESCRIPTION:
XS GIS Cut Line= 2
      3673978.37     10734045.32      3674168.46     10733607.83
#Sta/Elev= 30
  4780.3  402.36  4840.4  396.59  4869.5  392.84  4884.0  391.88  4921.8  387.51
  4927.6  385.32  4938.5  385.06  4945.3  382.90  4954.5  382.49  4960.3  382.04
  4968.7  379.90  4982.2  379.27  5001.0  376.63  5003.7  376.13  5007.0  376.63
  5021.1  379.82  5050.0  381.48  5068.0  385.79  5073.4  385.81  5096.9  390.88
  5102.3  390.56  5120.3  391.67  5132.0  391.05  5143.8  391.20  5149.2  388.12
  5167.2  390.06  5172.7  388.93  5196.1  390.36  5211.1  390.47  5257.3  394.30
#Mann=5,-1,0
  4780.3    0.12       0  4954.5    0.16       0  5001.0    0.07       0
  5007.0    0.16       0  5132.0    0.12       0
Bank Sta=5001,5007
Exp/Cntr=0.3,0.1

Type RM Length L Ch R = 1,246,210,210,210
BEGIN DESCRIPTION:
Mapping XS 83716757
END DESCRIPTION:
XS GIS Cut Line= 4
      3674163.31     10734086.96      3674387.23     10734003.64
      3674441.91     10733951.55      3674548.20     10733663.80
#Sta/Elev= 30
  4709.3  400.55  4745.5  396.72  4803.6  391.60  4849.5  384.98  4876.1  381.88
  4897.4  378.09  4908.1  377.41  4914.3  375.33  4939.3  371.71  4944.6  372.42
  4946.8  370.71  4953.3  370.71  4959.4  369.50  4998.9  366.24  5001.7  365.74
  5004.9  366.24  5046.5  369.51  5061.4  369.47  5070.8  370.95  5090.3  372.17
  5177.8  378.97  5185.1  380.47  5195.8  380.80  5202.9  382.72  5227.7  384.72
  5233.3  386.44  5288.8  391.31  5294.2  392.67  5324.6  395.50  5330.5  397.11
#Mann=7,-1,0
  4709.3    0.12       0  4745.5    0.16       0  4849.5    0.12       0
  4998.9    0.07       0  5004.9    0.12       0  5070.8    0.16       0
  5090.3    0.12       0
Bank Sta=4998.9,5004.9
Exp/Cntr=0.3,0.1

Type RM Length L Ch R = 1,36,0,0,0
BEGIN DESCRIPTION:
UNT 049 IN CACR 1.0
END DESCRIPTION:
XS GIS Cut Line= 4
      3674314.30     10734123.43      3674507.02     10734152.07
      3674546.08     10734131.24      3674637.23     10733751.02
#Sta/Elev= 30
  4790.2  381.23  4795.6  379.72  4825.9  376.76  4836.0  374.32  4870.8  372.13
  4876.4  370.35  4896.7  367.95  4947.2  363.31  4974.7  362.30  5015.6  361.69
  5018.4  361.19  5021.6  361.69  5029.6  361.86  5061.0  362.62  5071.5  361.96
  5122.9  362.25  5184.6  364.05  5225.8  366.81  5239.3  366.81  5246.3  368.58
  5276.2  371.38  5281.4  371.30  5287.5  372.66  5318.2  376.13  5338.9  379.99
  5359.5  382.44  5365.4  383.77  5412.5  389.57  5418.1  391.90  5420.3  391.90
#Mann=5,-1,0
  4790.2    0.12       0  4974.7     0.1       0  5015.6    0.07       0
  5021.6     0.1       0  5029.6    0.12       0
Bank Sta=5015.6,5021.6
Exp/Cntr=0.3,0.1

Chan Stop Cuts=-1