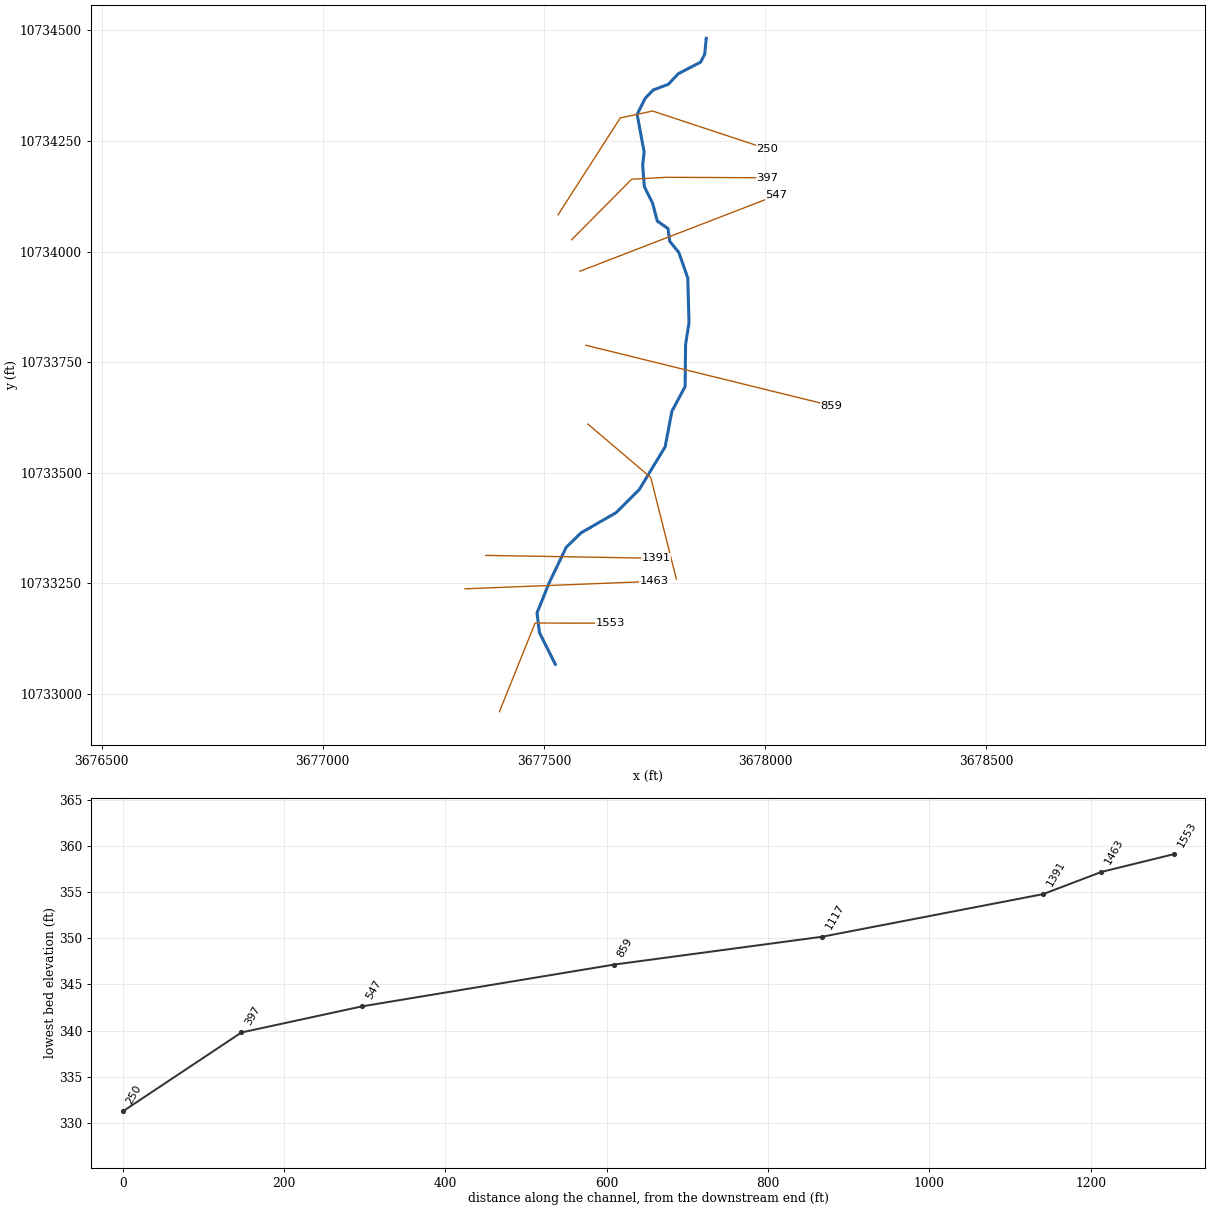
--- UNT 050 IN CACR.prj (project) ---

Proj Title=UNT 050 IN CACR Base Level Engineering
Current Plan=p01
Default Exp/Contr=0.3,0.1
English Units
Geom File=g01
Flow File=f01
Plan File=p01
Y Axis Title=Elevation
X Axis Title(PF)=Main Channel Distance
X Axis Title(XS)=Station
BEGIN DESCRIPTION:
UNT 050 IN CACR
END DESCRIPTION:
DSS Export Rating Curves= 0
DSS Export Rating Curve Sorted= 0
DSS Export Volume Flow Curves= 0
DXF OffsetX= 0
DXF OffsetY= 0
DXF ScaleX= 1
DXF ScaleY= 10

--- UNT 050 IN CACR.p01 (plan) ---

Plan Title=Multiple Run
Short Identifier=Multiple
Geom File=g01
Flow File=f01
Subcritical Flow
K Sum by GR= 0
Std Step Tol= 0.01
Critical Tol= 0.01
Num of Std Step Trials= 20
Max Error Tol= 0.3
Flow Tol Ratio= 0.001
Split Flow NTrial= 30
Split Flow Tol= 0.02
Split Flow Ratio= 0.02
Log Output Level= 0
Friction Slope Method= 1
Unsteady Friction Slope Method= 2
Unsteady Bridges Friction Slope Method= 1
Parabolic Critical Depth
Global Vel Dist=  1 , 1 , 1
Global Log Level= 0
CheckData=True
Encroach Param= -1, 0, 0, 0
BEGIN DESCRIPTION:
Multiple Run
END DESCRIPTION:

--- UNT 050 IN CACR.f01 (steady flow) ---

Flow Title=Multiple
Program Version=4.10
Number of Profiles= 7
Profile Names=10-year,25-year,50-year,1pct_min,100-year,1pct_plu,500-year
River Rch & RM=UNT 050 IN CACR,Reach-1         ,1553
     139     171     195     165     223     301     290
Boundary for River Rch & Prof#=UNT 050 IN CACR,Reach-1         , 1
Up Type= 0
Dn Type= 3
Dn Slope=0.05815
Boundary for River Rch & Prof#=UNT 050 IN CACR,Reach-1         , 2
Up Type= 0
Dn Type= 3
Dn Slope=0.05815
Boundary for River Rch & Prof#=UNT 050 IN CACR,Reach-1         , 3
Up Type= 0
Dn Type= 3
Dn Slope=0.05815
Boundary for River Rch & Prof#=UNT 050 IN CACR,Reach-1         , 4
Up Type= 0
Dn Type= 3
Dn Slope=0.05815
Boundary for River Rch & Prof#=UNT 050 IN CACR,Reach-1         , 5
Up Type= 0
Dn Type= 3
Dn Slope=0.05815
Boundary for River Rch & Prof#=UNT 050 IN CACR,Reach-1         , 6
Up Type= 0
Dn Type= 3
Dn Slope=0.05815
Boundary for River Rch & Prof#=UNT 050 IN CACR,Reach-1         , 7
Up Type= 0
Dn Type= 3
Dn Slope=0.05815
DSS Import GetInterval= 0
DSS Import GetPeak= 0
DSS Import FillOption= 0

--- UNT 050 IN CACR.g01 (geometry) ---

Geom Title=Existing Conditions
Program Version=4.10

River Reach=UNT 050 IN CACR ,Reach-1
Reach XY= 30
      3677525.87     10733067.23      3677490.06     10733138.85
      3677484.64     10733183.34      3677511.77     10733250.61
      3677550.83     10733331.99      3677584.47     10733364.54
      3677663.68     10733410.12      3677715.76      10733462.2
      3677774.35     10733558.77      3677789.54     10733639.07
       3677819.5       10733695.       3677820.5       10733790.
      3677828.25       10733839.       3677825.5       10733940.
      3677805.25       10733998.      3677784.75       10734023.
      3677780.75       10734052.       3677756.5       10734069.
        3677746.       10734109.      3677727.25       10734147.
       3677723.5       10734195.      3677726.75       10734225.
        3677711.       10734310.        3677729.       10734346.
        3677747.       10734365.       3677781.5       10734378.
      3677804.25       10734402.       3677854.5       10734428.
      3677863.75       10734446.      3677867.25       10734482.

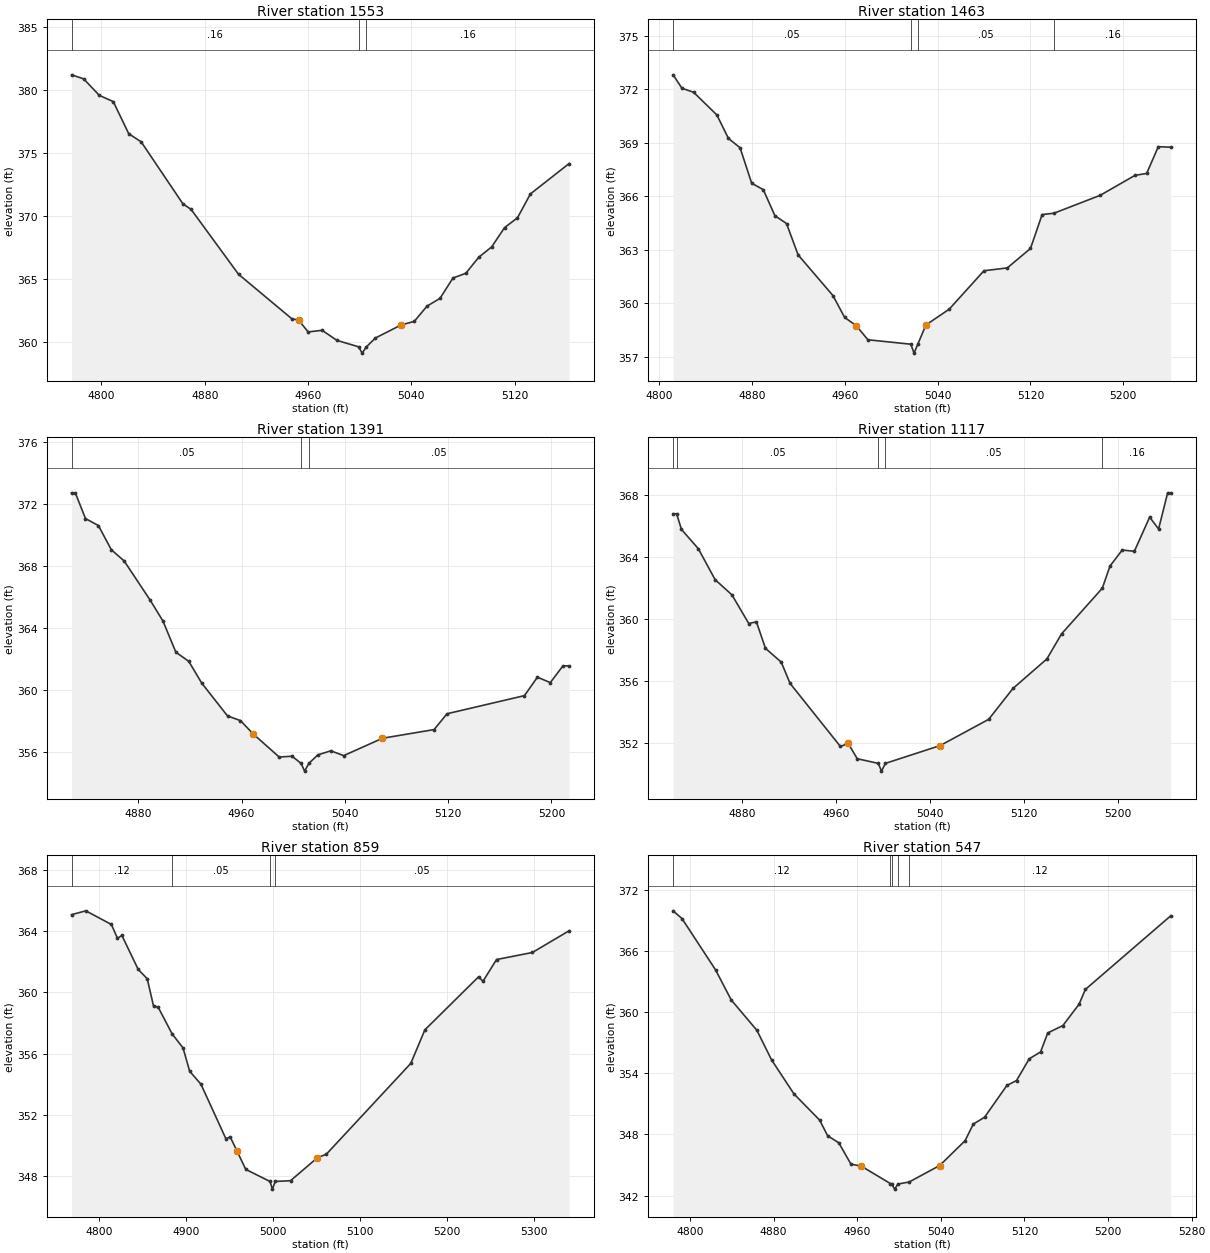
Type RM Length L Ch R = 1 ,1553    ,90,90,90
BEGIN DESCRIPTION:
UNT 050 IN CACR 3.0
END DESCRIPTION:
XS GIS Cut Line= 3
      3677399.62     10732960.21       3677480.3     10733160.55
      3677649.62     10733160.19
#Sta/Elev= 30
  4776.9  381.18  4786.3  380.86  4798.4  379.55  4809.2  379.06  4821.2  376.51
  4830.8  375.87  4863.1  370.96  4869.5  370.51  4906.2  365.37  4947.4  361.85
  4952.8  361.73  4960.1   360.8  4970.9  360.93  4982.4  360.13  4999.2  359.62
  5001.9  359.12  5005.2  359.62  5012.2  360.32  5032.2  361.36  5042.2  361.63
  5052.2  362.85  5062.2  363.46  5072.2  365.07  5082.2  365.45  5092.2  366.72
  5102.2  367.54  5112.2  369.07  5122.2  369.85  5132.2  371.74  5162.2  374.15
#Mann= 3 ,-1 , 0
  4776.9     .16       0  4999.2     .07       0  5005.2     .16       0
Bank Sta=4952.8,5032.2
XS Rating Curve= 0 ,0
Exp/Cntr=0.3,0.1

Type RM Length L Ch R = 1 ,1463    ,72,72,72
BEGIN DESCRIPTION:
Mapping XS 7e87c8a8
END DESCRIPTION:
XS GIS Cut Line= 2
      3677321.97     10733237.88      3677750.34     10733254.81
#Sta/Elev= 30
  4812.2   372.8  4819.8  372.05  4829.9  371.82  4849.9  370.55  4859.9  369.23
  4869.9  368.71  4879.9  366.72  4889.9  366.36  4899.9   364.9  4909.9  364.46
  4919.9   362.7  4949.9  360.42    4960  359.19    4970  358.73    4980  357.94
    5017  357.69  5019.8  357.19    5023  357.69    5030  358.77    5050  359.65
    5080  361.81  5100.1  361.97  5120.1  363.06  5130.1  364.96  5140.4  365.04
  5180.1  366.04  5210.1  367.16  5220.2  367.27  5230.2  368.77  5240.9  368.74
#Mann= 4 ,-1 , 0
  4812.2     .05       0    5017     .03       0    5023     .05       0
  5140.4     .16       0
Bank Sta=4970,5030
XS Rating Curve= 0 ,0
Exp/Cntr=0.3,0.1

Type RM Length L Ch R = 1 ,1391    ,274,274,274
BEGIN DESCRIPTION:
Mapping XS 3a9472d7
END DESCRIPTION:
XS GIS Cut Line= 2
      3677368.84      10733313.4      3677754.18     10733306.89
#Sta/Elev= 30
  4828.3  372.74  4831.2  372.74  4839.1  371.08  4849.1  370.63  4859.1  369.07
  4869.1  368.34  4889.1  365.83  4899.1  364.47  4909.1  362.46  4919.1  361.87
  4929.1  360.47  4949.1  358.35  4959.1  358.05  4969.1  357.18  4989.1   355.7
  4999.1  355.75  5006.1  355.29  5008.8  354.79  5012.1  355.29  5019.1  355.84
  5029.1   356.1  5039.1  355.79  5069.1  356.91  5109.1  357.47  5119.1  358.49
  5179.1  359.66  5189.1  360.85  5199.1   360.5  5208.9  361.58  5213.7  361.58
#Mann= 3 ,-1 , 0
  4828.3     .05       0  5006.1     .03       0  5012.1     .05       0
Bank Sta=4969.1,5069.1
XS Rating Curve= 0 ,0
Exp/Cntr=0.3,0.1

Type RM Length L Ch R = 1 ,1117    ,258,258,258
BEGIN DESCRIPTION:
UNT 050 IN CACR 2.0
END DESCRIPTION:
XS GIS Cut Line= 3
      3677599.62     10733610.18       3677741.8     10733489.33
      3677799.61      10733260.2
#Sta/Elev= 30
  4821.7  366.77  4824.7  366.77  4828.8  365.76  4843.1  364.52  4857.4  362.52
  4871.7  361.54    4886  359.69  4892.5   359.8  4900.2  358.09  4913.6   357.2
  4921.1  355.83  4963.9  351.76  4970.5  351.96  4978.2  350.97  4996.1  350.67
  4998.8  350.17  5002.1  350.67  5048.7  351.82  5089.9  353.51  5110.5   355.5
  5139.4  357.41  5151.8  359.02  5186.5  361.97    5193   363.4  5203.4  364.43
  5213.7  364.35  5226.7  366.55  5234.3  365.79    5242  368.12  5244.6  368.12
#Mann= 5 ,-1 , 0
  4821.7     .16       0  4824.7     .05       0  4996.1     .03       0
  5002.1     .05       0  5186.5     .16       0
Bank Sta=4970.5,5048.7
XS Rating Curve= 0 ,0
Exp/Cntr=0.3,0.1

Type RM Length L Ch R = 1 ,859     ,312,312,312
BEGIN DESCRIPTION:
Mapping XS 351613c4
END DESCRIPTION:
XS GIS Cut Line= 2
      3677595.11     10733788.24      3678150.73      10733651.5
#Sta/Elev= 30
  4768.5  365.07  4784.9  365.32  4814.3  364.43  4821.3  363.53  4826.4  363.71
  4845.2  361.49  4855.5  360.89  4862.8   359.1    4868  359.04  4884.1  357.29
  4896.7  356.37  4904.3  354.85  4917.3     354  4945.9  350.45    4951  350.55
  4958.5  349.67  4968.8  348.44  4996.7  347.65  4999.5  347.15  5002.7  347.65
  5020.3   347.7  5051.2   349.2  5061.5  349.43  5158.6  355.36  5174.8  357.55
  5236.5  361.01  5241.6  360.72  5257.2  362.14  5298.4   362.6  5340.7  364.02
#Mann= 4 ,-1 , 0
  4768.5     .12       0  4884.1     .05       0  4996.7     .03       0
  5002.7     .05       0
Bank Sta=4958.5,5051.2
XS Rating Curve= 0 ,0
Exp/Cntr=0.3,0.1

Type RM Length L Ch R = 1 ,547     ,150,150,150
BEGIN DESCRIPTION:
Mapping XS cb08c52e
END DESCRIPTION:
XS GIS Cut Line= 2
      3677581.72     10733955.54      3678025.79     10734126.94
#Sta/Elev= 30
  4783.9  369.98  4792.4  369.22  4824.5  364.18  4839.5  361.22  4864.1  358.23
  4878.1  355.33  4899.5  351.99  4924.1  349.41  4931.7  347.88  4942.4  347.18
    4954  345.09  4963.9  344.89  4991.7  343.18    4993  343.13  4995.8  342.63
    4999  343.13  5009.7  343.33  5038.9  344.95  5063.2  347.39  5071.1  349.03
  5081.8  349.69  5103.2  352.82  5112.4   353.3  5124.6  355.44  5135.4  356.11
  5142.3  357.98  5156.8  358.71  5172.3  360.81  5178.2  362.25  5259.9  369.49
#Mann= 5 ,-1 , 0
  4783.9     .12       0  4991.7     .05       0    4993     .03       0
    4999     .05       0  5009.7     .12       0
Bank Sta=4963.9,5038.9
XS Rating Curve= 0 ,0
Exp/Cntr=0.3,0.1

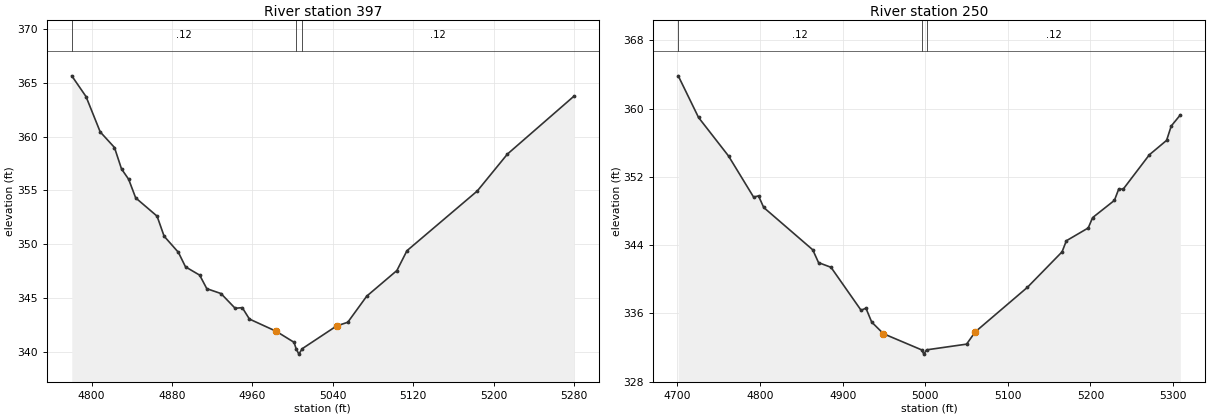
Type RM Length L Ch R = 1 ,397     ,147,147,147
BEGIN DESCRIPTION:
Mapping XS 73764e8e
END DESCRIPTION:
XS GIS Cut Line= 4
      3677563.03     10734026.74      3677698.66     10734163.45
      3677776.78     10734167.79      3678005.67     10734166.71
#Sta/Elev= 30
  4780.2  365.65  4794.4  363.72  4808.5  360.44  4822.7  358.99  4829.7     357
  4836.8  356.04  4843.8  354.31  4865.1  352.61  4872.1  350.75  4886.3  349.25
  4893.4   347.9  4907.5  347.13  4914.6  345.87  4928.7  345.42  4942.8  344.05
  4949.9  344.11    4957  343.05  4983.7  341.91  5001.4  340.89  5003.5  340.29
  5006.2  339.79  5009.5  340.29  5043.8  342.41  5054.9  342.75  5073.8  345.18
  5103.8  347.56  5113.8   349.4  5183.8  354.95  5213.8  358.38  5279.9  363.75
#Mann= 3 ,-1 , 0
  4780.2     .12       0  5003.5     .07       0  5009.5     .12       0
Bank Sta=4983.7,5043.8
XS Rating Curve= 0 ,0
Exp/Cntr=0.3,0.1

Type RM Length L Ch R = 1 ,250     ,0,0,0
BEGIN DESCRIPTION:
UNT 050 IN CACR 1.0
END DESCRIPTION:
XS GIS Cut Line= 4
      3677532.23     10734083.13      3677672.87      10734301.9
      3677745.79     10734317.53      3678005.37     10734231.86
#Sta/Elev= 30
  4700.9  363.84  4725.5  358.96  4761.8  354.45  4792.2  349.63  4798.1  349.78
  4804.4  348.42  4863.8  343.46  4870.8  341.96  4885.9  341.41  4922.3  336.38
  4928.2  336.62  4935.2  334.99  4949.4  333.63  4995.6  331.74  4998.3  331.24
  5001.6  331.74  5050.1  332.41  5060.6  333.85  5123.8  339.07  5165.7  343.22
  5170.9  344.52  5197.4  346.02  5202.7  347.23  5229.1  349.25  5234.4   350.6
  5239.7  350.56  5271.4  354.59  5292.3  356.28  5297.9  357.96  5308.9  359.26
#Mann= 3 ,-1 , 0
  4700.9     .12       0  4995.6     .07       0  5001.6     .12       0
Bank Sta=4949.4,5060.6
XS Rating Curve= 0 ,0
Exp/Cntr=0.3,0.1

Chan Stop Cuts=-1
Use User Specified Reach Order=0
Composite Channel Slope=5