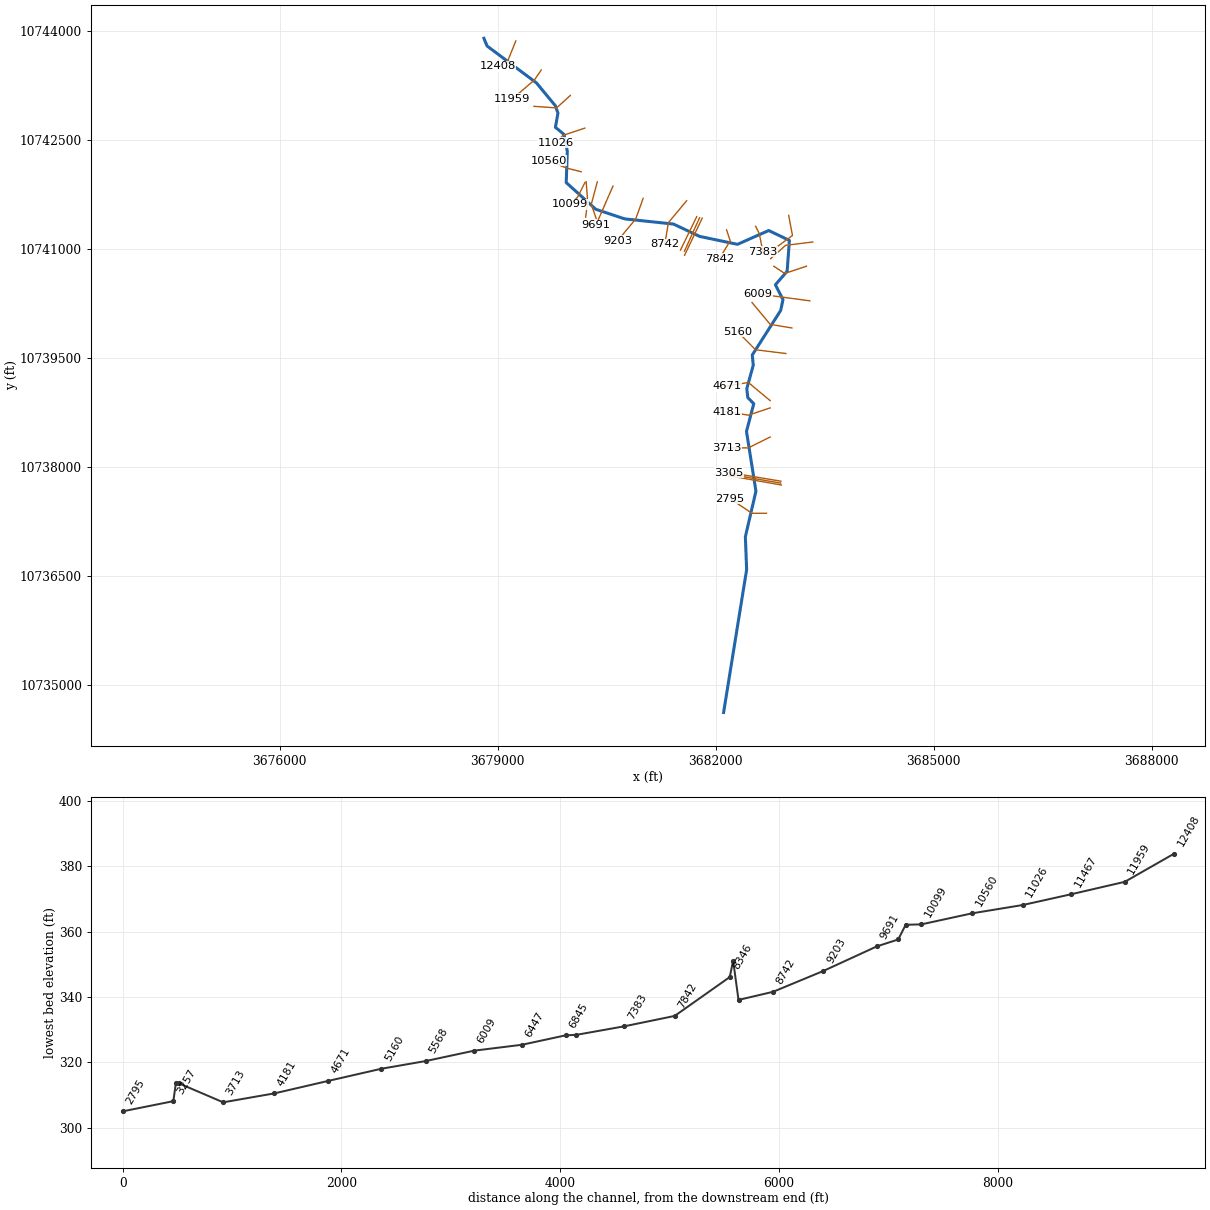
--- UNT 051 IN CACR.prj (project) ---

Proj Title=UNT 051 IN CACR Base Level Engineering
Current Plan=p01
Default Exp/Contr=0.3,0.1
English Units
Geom File=g01
Flow File=f01
Plan File=p01
BEGIN DESCRIPTION:
UNT 051 IN CACR
END DESCRIPTION:

--- UNT 051 IN CACR.p01 (plan) ---

Plan Title=Multiple Run
Short Identifier=Multiple
Geom File=g01
Flow File=f01
Subcritical Flow
K Sum by GR= 0
Std Step Tol= 0.01
Critical Tol= 0.01
Num of Std Step Trials= 20
Max Error Tol= 0.3
Flow Tol Ratio= 0.001
Split Flow NTrial= 30
Split Flow Tol= 0.02
Split Flow Ratio= 0.02
Log Output Level= 0
Friction Slope Method= 1
Unsteady Friction Slope Method= 2
Unsteady Bridges Friction Slope Method= 1
Parabolic Critical Depth
Global Vel Dist=  1 , 1 , 1
Global Log Level= 0
CheckData=True
Encroach Param= -1, 0, 0, 0
BEGIN DESCRIPTION:
Multiple Run
END DESCRIPTION:

--- UNT 051 IN CACR.f01 (steady flow) ---

Flow Title=Multiple
Number of Profiles=7
Profile Names=10-year,25-year,50-year,1pct_min,100-year,1pct_plu,500-year
River Rch & RM= UNT 051 IN CACR,Reach-1,12408
     246     314     368     317     429     580     582
River Rch & RM= UNT 051 IN CACR,Reach-1,6447
     520     699     844     749    1013    1370    1460
River Rch & RM= UNT 051 IN CACR,Reach-1,2795
     550     739     893     791    1070    1447    1541
Boundary for River Rch & Prof#=UNT 051 IN CACR,Reach-1,1
Up Type=0
Dn Type=3
Dn Slope=0.005
Boundary for River Rch & Prof#=UNT 051 IN CACR,Reach-1,2
Up Type=0
Dn Type=3
Dn Slope=0.005
Boundary for River Rch & Prof#=UNT 051 IN CACR,Reach-1,3
Up Type=0
Dn Type=3
Dn Slope=0.005
Boundary for River Rch & Prof#=UNT 051 IN CACR,Reach-1,4
Up Type=0
Dn Type=3
Dn Slope=0.005
Boundary for River Rch & Prof#=UNT 051 IN CACR,Reach-1,5
Up Type=0
Dn Type=3
Dn Slope=0.005
Boundary for River Rch & Prof#=UNT 051 IN CACR,Reach-1,6
Up Type=0
Dn Type=3
Dn Slope=0.005
Boundary for River Rch & Prof#=UNT 051 IN CACR,Reach-1,7
Up Type=0
Dn Type=3
Dn Slope=0.005

--- UNT 051 IN CACR.g01 (geometry) ---

Geom Title=Existing Conditions

River Reach=UNT 051 IN CACR,Reach-1
Reach XY= 30
      3678810.32     10743896.42      3678854.59     10743789.65
      3679532.00     10743284.00      3679792.50     10742970.00
      3679829.25     10742866.00      3679794.25     10742671.00
      3679913.75     10742573.00      3679958.25     10742340.00
      3679943.00     10741911.00      3680350.75     10741543.00
      3680750.00     10741411.00      3681419.00     10741340.00
      3681780.00     10741170.00      3682299.50     10741061.00
      3682729.75     10741251.00      3683014.50     10741115.00
      3682983.25     10740690.00      3682821.75     10740505.00
      3682926.25     10740300.00      3682894.50     10740151.00
      3682503.50     10739538.00      3682517.50     10739399.00
      3682428.25     10739076.00      3682442.25     10738951.00
      3682524.00     10738868.00      3682424.00     10738487.00
      3682554.00     10737664.00      3682408.50     10737037.00
      3682426.00     10736585.00      3682109.00     10734619.00

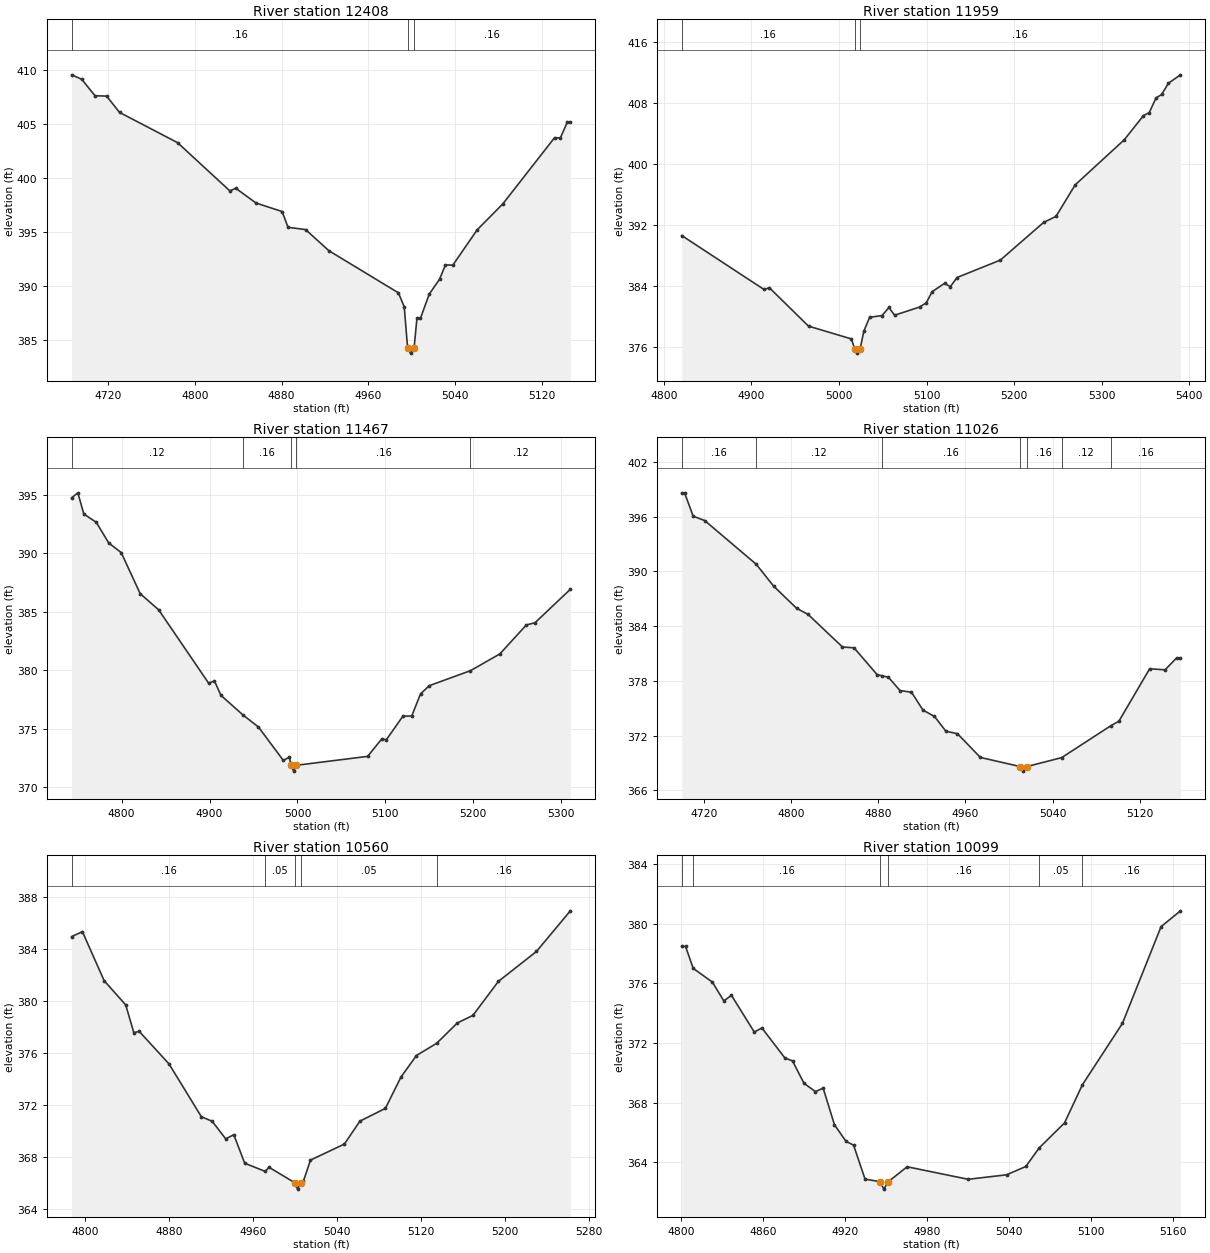
Type RM Length L Ch R = 1,12408,449,449,449
BEGIN DESCRIPTION:
UNT 051 IN CACR 22.0
END DESCRIPTION:
XS GIS Cut Line= 3
      3679249.60     10743860.16      3679129.87     10743564.70
      3678999.62     10743510.19
#Sta/Elev= 30
  4686.3  409.56  4695.6  409.15  4707.9  407.62  4718.6  407.59  4730.5  406.08
  4784.1  403.27  4832.3  398.80  4837.7  399.05  4856.4  397.68  4880.5  396.89
  4885.9  395.43  4902.1  395.22  4923.6  393.26  4987.7  389.36  4993.1  388.06
  4996.2  384.27  4998.9  383.77  5002.2  384.27  5004.8  386.98  5008.0  386.98
  5016.2  389.25  5025.7  390.62  5031.1  391.95  5037.9  391.92  5060.3  395.19
  5084.1  397.61  5131.7  403.73  5137.1  403.71  5143.6  405.20  5146.3  405.20
#Mann=3,-1,0
  4686.3    0.16       0  4996.2    0.07       0  5002.2    0.16       0
Bank Sta=4996.2,5002.2
Exp/Cntr=0.3,0.1

Type RM Length L Ch R = 1,11959,492,492,492
BEGIN DESCRIPTION:
UNT 051 IN CACR 21.0
END DESCRIPTION:
XS GIS Cut Line= 3
      3679599.62     10743460.21      3679504.07     10743321.49
      3679199.58     10743060.16
#Sta/Elev= 30
  4820.4  390.61  4914.4  383.54  4920.5  383.77  4965.2  378.74  5014.2  377.06
  5018.1  375.70  5020.8  375.20  5024.1  375.70  5028.4  378.08  5035.0  379.89
  5049.3  380.13  5057.0  381.18  5063.6  380.17  5092.1  381.24  5099.8  381.80
  5106.4  383.25  5120.6  384.34  5127.2  383.91  5134.9  385.11  5184.3  387.39
  5233.7  392.32  5247.9  393.12  5269.9  397.26  5325.9  403.16  5347.8  406.32
  5354.4  406.71  5362.1  408.63  5368.7  409.10  5376.3  410.57  5390.1  411.67
#Mann=3,-1,0
  4820.4    0.16       0  5018.1    0.07       0  5024.1    0.16       0
Bank Sta=5018.1,5024.1
Exp/Cntr=0.3,0.1

Type RM Length L Ch R = 1,11467,441,441,441
BEGIN DESCRIPTION:
UNT 051 IN CACR 20.0
END DESCRIPTION:
XS GIS Cut Line= 3
      3679999.61     10743110.19      3679810.71     10742938.25
      3679499.63     10742960.19
#Sta/Elev= 30
  4743.1  394.73  4750.2  395.16  4757.0  393.35  4771.2  392.64  4785.3  390.88
  4799.5  390.06  4821.1  386.55  4842.1  385.17  4898.9  378.91  4905.6  379.09
  4913.0  377.86  4938.0  376.19  4955.6  375.16  4984.0  372.30  4990.7  372.58
  4992.9  371.89  4995.7  371.39  4998.9  371.89  5079.8  372.65  5096.0  374.15
  5101.1  374.07  5119.9  376.08  5130.0  376.10  5140.0  377.99  5150.0  378.69
  5196.8  379.97  5230.2  381.40  5260.3  383.87  5270.3  384.07  5310.4  386.92
#Mann=5,-1,0
  4743.1    0.12       0  4938.0    0.16       0  4992.9    0.07       0
  4998.9    0.16       0  5196.8    0.12       0
Bank Sta=4992.9,4998.9
Exp/Cntr=0.3,0.1

Type RM Length L Ch R = 1,11026,466,466,466
BEGIN DESCRIPTION:
UNT 051 IN CACR 19.0
END DESCRIPTION:
XS GIS Cut Line= 3
      3680199.58     10742660.18      3679899.61     10742560.19
      3679799.62     10742460.20
#Sta/Elev= 30
  4699.8  398.60  4702.4  398.60  4710.3  396.04  4720.9  395.56  4768.1  390.78
  4784.1  388.38  4805.2  385.95  4815.7  385.28  4847.3  381.71  4857.9  381.62
  4879.0  378.69  4883.8  378.55  4889.5  378.39  4900.1  376.93  4910.6  376.76
  4921.1  374.80  4931.7  374.10  4942.2  372.48  4952.8  372.21  4973.8  369.61
  5010.4  368.61  5013.1  368.11  5016.4  368.61  5048.4  369.59  5093.2  373.06
  5100.9  373.58  5129.1  379.32  5143.3  379.21  5153.9  380.52  5157.4  380.52
#Mann=7,-1,0
  4699.8    0.16       0  4768.1    0.12       0  4883.8    0.16       0
  5010.4    0.07       0  5016.4    0.16       0  5048.4    0.12       0
  5093.2    0.16       0
Bank Sta=5010.4,5016.4
Exp/Cntr=0.3,0.1

Type RM Length L Ch R = 1,10560,461,461,461
BEGIN DESCRIPTION:
UNT 051 IN CACR 18.0
END DESCRIPTION:
XS GIS Cut Line= 3
      3680149.64     10742060.18      3679949.61     10742110.19
      3679699.65     10742210.17
#Sta/Elev= 30
  4786.9  384.94  4797.2  385.32  4817.9  381.56  4838.5  379.69  4846.2  377.57
  4851.4  377.66  4879.7  375.17  4910.6  371.11  4920.9  370.76  4933.8  369.41
  4941.5  369.73  4951.9  367.54  4971.5  366.91  4975.0  367.23  4999.5  366.05
  5002.3  365.55  5005.5  366.05  5007.9  366.17  5014.6  367.78  5046.9  369.01
  5061.7  370.77  5086.0  371.75  5100.8  374.15  5115.6  375.81  5134.9  376.75
  5154.6  378.31  5169.4  378.89  5193.7  381.50  5230.0  383.80  5262.3  386.92
#Mann=5,-1,0
  4786.9    0.16       0  4971.5    0.05       0  4999.5    0.03       0
  5005.5    0.05       0  5134.9    0.16       0
Bank Sta=4999.5,5005.5
Exp/Cntr=0.3,0.1

Type RM Length L Ch R = 1,10099,144,144,144
BEGIN DESCRIPTION:
UNT 051 IN CACR 17.0
END DESCRIPTION:
XS GIS Cut Line= 3
      3680199.63     10741910.23      3680099.61     10741710.19
      3679999.59     10741610.17
#Sta/Elev= 30
  4800.7  378.47  4803.5  378.47  4809.1  377.00  4823.1  376.08  4831.5  374.82
  4837.1  375.19  4853.8  372.73  4859.4  373.00  4876.2  370.99  4881.8  370.79
  4890.2  369.29  4898.6  368.73  4904.2  368.97  4912.5  366.51  4920.9  365.40
  4926.5  365.14  4934.9  362.86  4945.9  362.69  4948.6  362.19  4951.9  362.69
  4965.7  363.69  5010.4  362.85  5038.5  363.15  5052.6  363.71  5062.3  364.95
  5080.9  366.63  5094.0  369.19  5123.3  373.31  5151.6  379.80  5165.8  380.86
#Mann=6,-1,0
  4800.7    0.05       0  4809.1    0.16       0  4945.9    0.07       0
  4951.9    0.16       0  5062.3    0.05       0  5094.0    0.16       0
Bank Sta=4945.9,4951.9
Exp/Cntr=0.3,0.1

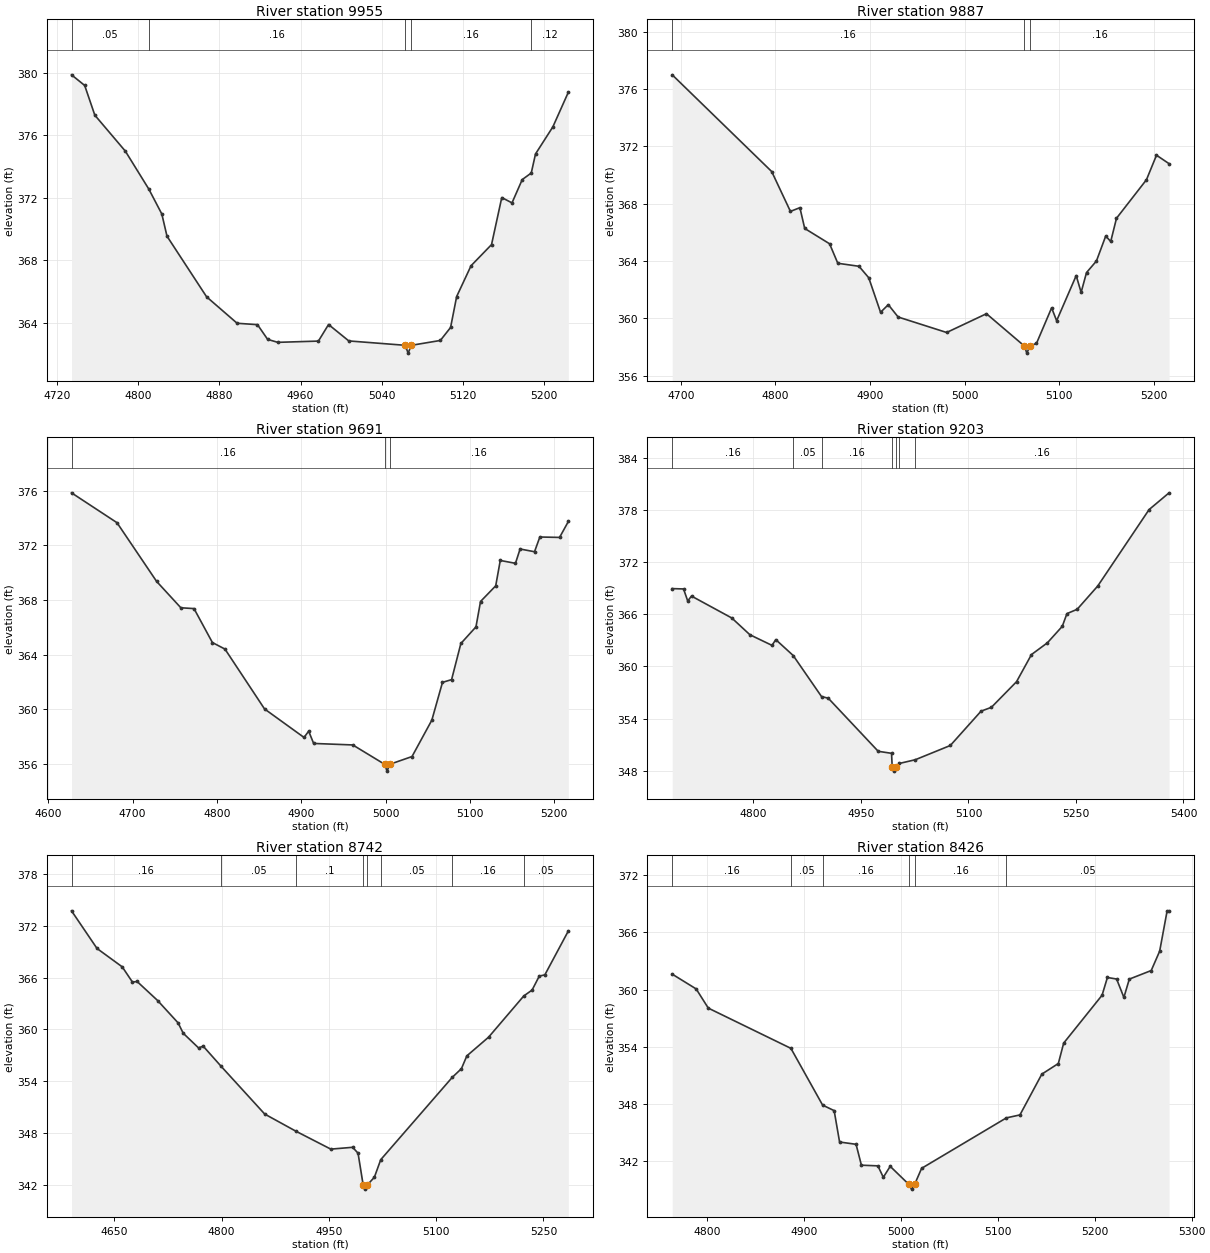
Type RM Length L Ch R = 1,9955,68,68,68
BEGIN DESCRIPTION:
Mapping XS fddc8457
END DESCRIPTION:
XS GIS Cut Line= 4
      3680217.60     10741923.11      3680234.96     10741700.70
      3680230.62     10741587.86      3680210.03     10741435.05
#Sta/Elev= 30
  4734.0  379.86  4747.0  379.18  4757.0  377.28  4787.1  374.98  4810.2  372.56
  4823.1  370.96  4828.2  369.54  4867.3  365.66  4897.4  363.97  4917.5  363.88
  4927.5  362.94  4937.5  362.75  4977.6  362.83  4987.6  363.89  5007.6  362.84
  5063.3  362.56  5066.1  362.06  5069.3  362.56  5097.9  362.87  5108.0  363.70
  5114.0  365.68  5128.2  367.65  5148.4  369.00  5158.5  372.01  5168.6  371.67
  5178.7  373.16  5187.6  373.58  5191.8  374.80  5208.9  376.53  5224.2  378.75
#Mann=5,-1,0
  4734.0    0.05       0  4810.2    0.16       0  5063.3    0.07       0
  5069.3    0.16       0  5187.6    0.12       0
Bank Sta=5063.3,5069.3
Exp/Cntr=0.3,0.1

Type RM Length L Ch R = 1,9887,196,196,196
BEGIN DESCRIPTION:
UNT 051 IN CACR 16.0
END DESCRIPTION:
XS GIS Cut Line= 3
      3680370.60     10741921.01      3680288.13     10741611.73
      3680354.99     10741417.61
#Sta/Elev= 30
  4690.8  376.99  4796.0  370.24  4815.8  367.46  4825.8  367.72  4830.9  366.27
  4857.2  365.20  4865.9  363.84  4888.3  363.63  4898.6  362.83  4911.1  360.42
  4919.3  360.95  4929.7  360.09  4981.0  359.01  5023.1  360.32  5063.1  358.07
  5065.8  357.57  5069.1  358.07  5076.0  358.25  5092.0  360.73  5097.3  359.83
  5118.0  362.98  5123.2  361.81  5128.9  363.19  5139.4  364.00  5149.2  365.74
  5154.5  365.36  5160.6  366.98  5192.3  369.67  5202.9  371.38  5216.2  370.79
#Mann=3,-1,0
  4690.8    0.16       0  5063.1    0.07       0  5069.1    0.16       0
Bank Sta=5063.1,5069.1
Exp/Cntr=0.3,0.1

Type RM Length L Ch R = 1,9691,488,488,488
BEGIN DESCRIPTION:
Mapping XS 01a6fa8a
END DESCRIPTION:
XS GIS Cut Line= 2
      3680586.74     10741863.26      3680351.43     10741323.42
#Sta/Elev= 30
  4627.7  375.86  4681.6  373.67  4728.5  369.37  4757.3  367.43  4772.9  367.37
  4794.7  364.88  4809.6  364.40  4856.5  360.01  4903.3  357.92  4908.8  358.38
  4914.7  357.48  4961.1  357.37  4998.9  355.95  5001.7  355.45  5004.9  355.95
  5031.3  356.52  5054.8  359.19  5067.4  361.96  5078.2  362.16  5089.2  364.81
  5107.1  366.03  5112.5  367.89  5130.5  369.04  5135.9  370.90  5153.9  370.69
  5159.4  371.74  5176.5  371.54  5182.8  372.62  5206.2  372.59  5216.6  373.76
#Mann=3,-1,0
  4627.7    0.16       0  4998.9    0.07       0  5004.9    0.16       0
Bank Sta=4998.9,5004.9
Exp/Cntr=0.3,0.1

Type RM Length L Ch R = 1,9203,461,461,461
BEGIN DESCRIPTION:
UNT 051 IN CACR 15.0
END DESCRIPTION:
XS GIS Cut Line= 3
      3681002.12     10741695.03      3680899.61     10741410.19
      3680649.63     10741110.22
#Sta/Elev= 30
  4686.7  368.95  4702.5  368.91  4708.3  367.53  4713.6  368.09  4769.8  365.57
  4795.1  363.64  4825.9  362.42  4831.2  363.08  4855.5  361.25  4895.0  356.53
  4904.4  356.34  4974.1  350.23  4992.7  350.00  4993.6  348.45  4996.3  347.95
  4999.6  348.45  5003.4  348.83  5025.8  349.26  5074.7  350.90  5117.6  354.85
  5132.0  355.29  5167.1  358.24  5187.9  361.36  5210.1  362.71  5230.9  364.61
  5237.4  366.07  5251.7  366.57  5280.4  369.25  5352.0  378.04  5379.9  379.97
#Mann=7,-1,0
  4686.7    0.16       0  4855.5    0.05       0  4895.0    0.16       0
  4993.6    0.07       0  4999.6    0.16       0  5003.4    0.05       0
  5025.8    0.16       0
Bank Sta=4993.6,4999.6
Exp/Cntr=0.3,0.1

Type RM Length L Ch R = 1,8742,316,316,316
BEGIN DESCRIPTION:
UNT 051 IN CACR 14.0
END DESCRIPTION:
XS GIS Cut Line= 3
      3681599.58     10741660.15      3681349.61     10741360.19
      3681299.61     10741060.19
#Sta/Elev= 30
  4590.2  373.70  4625.9  369.35  4661.1  367.23  4675.4  365.47  4681.9  365.54
  4710.6  363.34  4739.2  360.76  4746.4  359.56  4767.8  357.87  4774.3  358.07
  4799.3  355.75  4860.3  350.23  4903.9  348.25  4952.7  346.18  4983.2  346.39
  4990.8  345.71  4997.9  342.06  5000.7  341.56  5003.9  342.06  5013.6  342.93
  5022.5  344.96  5122.5  354.47  5135.3  355.47  5142.9  356.95  5173.3  359.11
  5222.5  363.87  5234.1  364.55  5244.2  366.17  5251.9  366.30  5284.8  371.38
#Mann=8,-1,0
  4590.2    0.16       0  4799.3    0.05       0  4903.9     0.1       0
  4997.9    0.07       0  5003.9     0.1       0  5022.5    0.05       0
  5122.5    0.16       0  5222.5    0.05       0
Bank Sta=4997.9,5003.9
Exp/Cntr=0.3,0.1

Type RM Length L Ch R = 1,8426,49,49,49
BEGIN DESCRIPTION:
Mapping XS 638b7da2
END DESCRIPTION:
XS GIS Cut Line= 2
      3681739.08     10741442.36      3681515.15     10740981.49
#Sta/Elev= 30
  4764.3  361.62  4789.0  360.07  4801.5  358.06  4886.7  353.84  4919.4  347.89
  4931.3  347.31  4936.9  344.02  4953.9  343.78  4959.4  341.59  4976.4  341.52
  4982.0  340.32  4989.1  341.47  5008.3  339.58  5011.1  339.08  5014.3  339.58
  5021.5  341.26  5108.9  346.55  5122.9  346.86  5145.5  351.14  5162.5  352.25
  5168.0  354.39  5207.6  359.41  5213.1  361.27  5222.6  361.11  5230.1  359.18
  5235.7  361.10  5258.3  362.00  5267.0  364.03  5274.7  368.26  5276.7  368.26
#Mann=6,-1,0
  4764.3    0.16       0  4886.7    0.05       0  4919.4    0.16       0
  5008.3    0.07       0  5014.3    0.16       0  5108.9    0.05       0
Bank Sta=5008.3,5014.3
Exp/Cntr=0.3,0.1

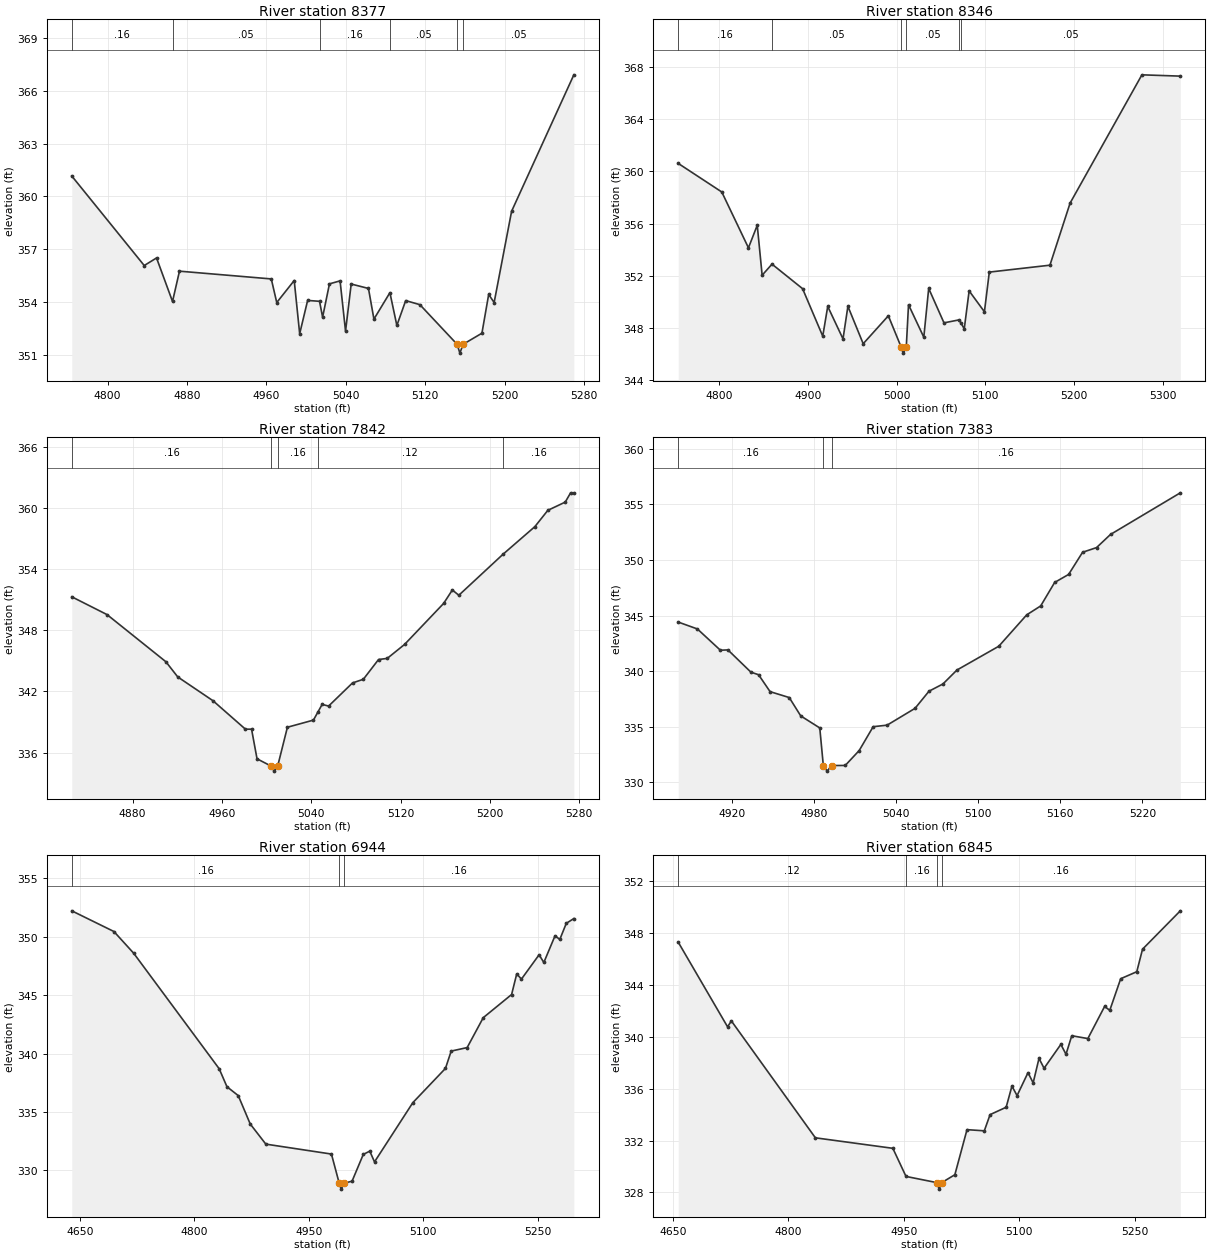
Type RM Length L Ch R = 1,8377,31,31,31
BEGIN DESCRIPTION:
Mapping XS 1234c6a7
END DESCRIPTION:
XS GIS Cut Line= 2
      3681778.13     10741426.71      3681569.81     10740965.80
#Sta/Elev= 30
  4763.9  361.16  4836.9  356.08  4849.3  356.51  4865.4  354.04  4872.4  355.76
  4964.9  355.32  4970.4  353.98  4988.0  355.23  4993.5  352.21  5001.5  354.10
  5013.5  354.05  5016.6  353.15  5023.5  355.04  5034.2  355.21  5039.7  352.36
  5045.4  355.03  5062.8  354.78  5068.3  353.04  5084.4  354.54  5091.4  352.68
  5100.3  354.09  5114.6  353.86  5152.1  351.61  5154.9  351.11  5158.1  351.61
  5177.1  352.24  5183.9  354.44  5189.4  353.98  5207.0  359.16  5269.7  366.90
#Mann=6,-1,0
  4763.9    0.16       0  4865.4    0.05       0  5013.5    0.16       0
  5084.4    0.05       0  5152.1    0.03       0  5158.1    0.05       0
Bank Sta=5152.1,5158.1
Exp/Cntr=0.3,0.1

Type RM Length L Ch R = 1,8346,504,504,504
BEGIN DESCRIPTION:
UNT 051 IN CACR 13.0
END DESCRIPTION:
XS GIS Cut Line= 2
      3681814.60     10741421.53      3681572.44     10740911.17
#Sta/Elev= 30
  4754.4  360.61  4803.4  358.42  4833.4  354.14  4843.3  355.87  4848.8  352.04
  4859.9  352.89  4894.3  351.01  4917.0  347.37  4922.6  349.65  4939.8  347.16
  4945.3  349.66  4962.5  346.79  4990.8  348.93  5005.0  346.57  5007.7  346.07
  5011.0  346.57  5013.5  349.78  5030.7  347.29  5036.2  351.03  5053.4  348.39
  5070.5  348.62  5072.5  348.38  5076.2  347.93  5081.7  350.84  5098.9  349.24
  5104.4  352.28  5172.6  352.81  5195.3  357.57  5276.1  367.40  5319.3  367.30
#Mann=6,-1,0
  4754.4    0.16       0  4859.9    0.05       0  5005.0    0.03       0
  5011.0    0.05       0  5070.5    0.16       0  5072.5    0.05       0
Bank Sta=5005,5011
Exp/Cntr=0.3,0.1

Type RM Length L Ch R = 1,7842,459,459,459
BEGIN DESCRIPTION:
UNT 051 IN CACR 12.0
END DESCRIPTION:
XS GIS Cut Line= 3
      3682149.61     10741260.17      3682199.61     10741110.19
      3682049.63     10740860.23
#Sta/Elev= 30
  4825.6  351.30  4857.2  349.55  4909.9  344.92  4920.5  343.43  4952.1  341.09
  4981.1  338.30  4986.6  338.30  4991.5  335.39  5004.0  334.68  5006.8  334.18
  5010.0  334.68  5018.7  338.49  5042.0  339.19  5045.9  339.96  5049.8  340.73
  5055.6  340.57  5077.0  342.84  5086.7  343.20  5100.3  345.14  5108.1  345.25
  5123.6  346.62  5158.6  350.65  5166.4  351.97  5172.2  351.45  5211.7  355.47
  5240.3  358.19  5251.9  359.79  5267.5  360.60  5272.3  361.51  5275.2  361.51
#Mann=5,-1,0
  4825.6    0.16       0  5004.0    0.07       0  5010.0    0.16       0
  5045.9    0.12       0  5211.7    0.16       0
Bank Sta=5004,5010
Exp/Cntr=0.3,0.1

Type RM Length L Ch R = 1,7383,439,439,439
BEGIN DESCRIPTION:
UNT 051 IN CACR 11.0
END DESCRIPTION:
XS GIS Cut Line= 3
      3682549.60     10741310.20      3682599.61     10741210.19
      3682649.62     10740960.16
#Sta/Elev= 30
  4880.9  344.41  4894.9  343.79  4911.7  341.88  4917.2  341.91  4934.0  339.91
  4939.6  339.68  4948.0  338.16  4962.0  337.63  4970.4  335.98  4984.3  334.90
  4986.9  331.52  4989.7  331.02  4992.9  331.52  5002.9  331.53  5013.1  332.87
  5023.3  335.01  5033.5  335.15  5053.9  336.66  5064.1  338.20  5074.3  338.85
  5084.5  340.10  5115.1  342.24  5135.5  345.06  5145.7  345.86  5155.9  347.97
  5166.1  348.69  5176.3  350.68  5186.5  351.10  5196.7  352.28  5247.7  356.02
#Mann=3,-1,0
  4880.9    0.16       0  4986.9    0.07       0  4992.9    0.16       0
Bank Sta=4986.9,4992.9
Exp/Cntr=0.3,0.1

Type RM Length L Ch R = 1,6944,99,99,99
BEGIN DESCRIPTION:
UNT 051 IN CACR 10.0
END DESCRIPTION:
XS GIS Cut Line= 3
      3683004.53     10741459.93      3683056.62     10741182.14
      3682753.72     10740961.45
#Sta/Elev= 30
  4639.6  352.21  4694.8  350.44  4720.7  348.58  4832.6  338.70  4842.8  337.16
  4857.6  336.40  4873.3  333.97  4893.7  332.25  4979.6  331.40  4989.8  328.90
  4992.5  328.40  4995.8  328.90  5006.6  329.08  5021.3  331.37  5029.8  331.65
  5036.0  330.73  5086.2  335.80  5128.9  338.73  5136.4  340.21  5157.3  340.51
  5178.4  343.07  5215.5  345.05  5222.2  346.81  5228.4  346.37  5251.5  348.45
  5257.7  347.79  5272.4  350.08  5278.6  349.76  5287.1  351.14  5297.0  351.55
#Mann=3,-1,0
  4639.6    0.16       0  4989.8    0.07       0  4995.8    0.16       0
Bank Sta=4989.8,4995.8
Exp/Cntr=0.3,0.1

Type RM Length L Ch R = 1,6845,398,398,398
BEGIN DESCRIPTION:
Mapping XS 88464fc9
END DESCRIPTION:
XS GIS Cut Line= 3
      3683336.55     10741093.16      3682963.30     10741047.59
      3682756.15     10740864.18
#Sta/Elev= 30
  4656.8  347.31  4720.9  340.78  4725.9  341.23  4835.1  332.21  4935.8  331.40
  4952.9  329.23  4993.2  328.75  4996.0  328.25  4999.2  328.75  5016.4  329.36
  5032.2  332.84  5054.7  332.75  5062.2  334.00  5083.1  334.57  5090.6  336.20
  5097.3  335.47  5111.5  337.24  5118.2  336.45  5125.8  338.34  5132.4  337.58
  5154.2  339.42  5160.9  338.66  5168.4  340.09  5189.3  339.87  5211.1  342.35
  5217.8  342.05  5232.0  344.49  5252.9  345.03  5260.4  346.77  5309.5  349.73
#Mann=4,-1,0
  4656.8    0.12       0  4952.9    0.16       0  4993.2    0.07       0
  4999.2    0.16       0
Bank Sta=4993.2,4999.2
Exp/Cntr=0.3,0.1

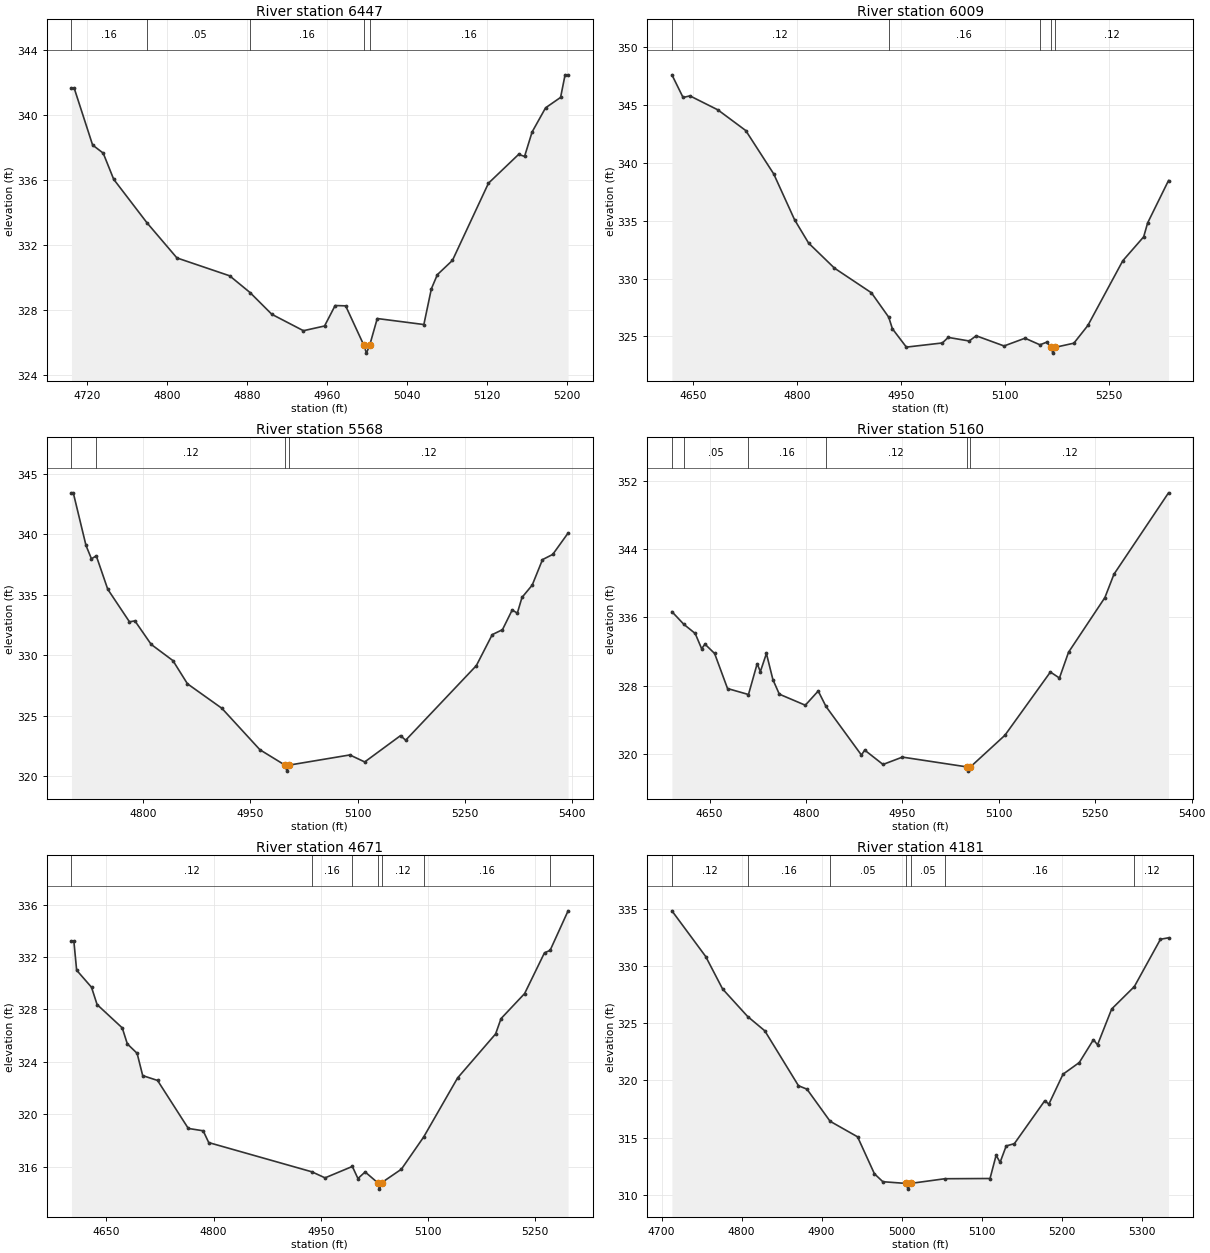
Type RM Length L Ch R = 1,6447,438,438,438
BEGIN DESCRIPTION:
UNT 051 IN CACR 9.0
END DESCRIPTION:
XS GIS Cut Line= 3
      3683249.64     10740760.20      3682949.61     10740660.19
      3682799.64     10740760.17
#Sta/Elev= 30
  4704.5  341.68  4707.2  341.68  4725.6  338.18  4736.2  337.68  4746.7  336.07
  4780.0  333.39  4809.9  331.23  4862.6  330.13  4883.0  329.10  4904.8  327.76
  4936.4  326.75  4957.5  327.04  4968.1  328.30  4978.6  328.28  4996.7  325.87
  4999.4  325.37  5002.7  325.87  5010.2  327.50  5056.8  327.13  5064.3  329.33
  5070.3  330.20  5085.4  331.08  5121.4  335.83  5151.5  337.60  5157.5  337.48
  5165.0  338.98  5178.5  340.47  5193.5  341.11  5198.0  342.50  5201.0  342.50
#Mann=5,-1,0
  4704.5    0.16       0  4780.0    0.05       0  4883.0    0.16       0
  4996.7    0.07       0  5002.7    0.16       0
Bank Sta=4996.7,5002.7
Exp/Cntr=0.3,0.1

Type RM Length L Ch R = 1,6009,441,441,441
BEGIN DESCRIPTION:
UNT 051 IN CACR 8.0
END DESCRIPTION:
XS GIS Cut Line= 2
      3683295.38     10740283.69      3682584.05     10740379.12
#Sta/Elev= 30
  4618.9  347.63  4635.0  345.67  4644.9  345.81  4685.3  344.60  4725.6  342.81
  4766.0  339.06  4796.2  335.09  4816.4  333.08  4853.8  330.91  4907.2  328.78
  4932.2  326.67  4937.5  325.67  4957.7  324.08  5009.7  324.44  5018.2  324.92
  5048.5  324.61  5058.6  325.06  5098.9  324.18  5129.2  324.85  5150.8  324.28
  5160.6  324.51  5166.6  324.06  5169.3  323.56  5172.6  324.06  5199.8  324.42
  5220.0  325.95  5270.5  331.55  5300.7  333.62  5306.4  334.82  5336.6  338.49
#Mann=5,-1,0
  4618.9    0.12       0  4932.2    0.16       0  5150.8    0.12       0
  5166.6    0.07       0  5172.6    0.12       0
Bank Sta=5166.6,5172.6
Exp/Cntr=0.3,0.1

Type RM Length L Ch R = 1,5568,408,408,408
BEGIN DESCRIPTION:
UNT 051 IN CACR 7.0
END DESCRIPTION:
XS GIS Cut Line= 3
      3683049.61     10739910.19      3682749.61     10739960.19
      3682499.58     10740260.23
#Sta/Elev= 30
  4699.7  343.44  4702.2  343.44  4720.0  339.08  4727.6  337.98  4734.4  338.22
  4750.4  335.46  4780.8  332.76  4788.4  332.84  4811.2  330.89  4841.6  329.55
  4861.9  327.63  4910.1  325.60  4963.3  322.17  4998.3  320.90  5001.1  320.40
  5004.3  320.90  5089.1  321.74  5109.9  321.16  5160.0  323.34  5167.2  322.96
  5266.1  329.14  5288.3  331.70  5302.6  332.11  5316.2  333.74  5323.4  333.48
  5329.9  334.78  5344.2  335.80  5358.6  337.91  5372.9  338.34  5394.4  340.11
#Mann=4,-1,0
  4699.7    0.16       0  4734.4    0.12       0  4998.3    0.07       0
  5004.3    0.12       0
Bank Sta=4998.3,5004.3
Exp/Cntr=0.3,0.1

Type RM Length L Ch R = 1,5160,489,489,489
BEGIN DESCRIPTION:
UNT 051 IN CACR 6.0
END DESCRIPTION:
XS GIS Cut Line= 3
      3682965.50     10739558.87      3682549.61     10739610.19
      3682299.61     10739860.19
#Sta/Elev= 30
  4591.4  336.68  4609.8  335.21  4627.6  334.13  4637.6  332.35  4642.8  332.88
  4657.8  331.79  4677.9  327.69  4710.5  326.99  4724.0  330.59  4729.0  329.67
  4738.4  331.79  4748.5  328.73  4758.5  327.03  4798.9  325.74  4819.0  327.40
  4831.1  325.59  4886.2  319.91  4891.3  320.49  4919.8  318.81  4950.0  319.67
  5049.9  318.53  5052.6  318.03  5055.9  318.53  5109.4  322.22  5180.2  329.62
  5194.3  328.92  5208.4  331.93  5265.0  338.33  5279.1  341.06  5364.0  350.58
#Mann=6,-1,0
  4591.4    0.16       0  4609.8    0.05       0  4710.5    0.16       0
  4831.1    0.12       0  5049.9    0.07       0  5055.9    0.12       0
Bank Sta=5049.9,5055.9
Exp/Cntr=0.3,0.1

Type RM Length L Ch R = 1,4671,490,490,490
BEGIN DESCRIPTION:
UNT 051 IN CACR 5.0
END DESCRIPTION:
XS GIS Cut Line= 3
      3682749.63     10738910.17      3682449.61     10739160.19
      3682149.59     10739110.19
#Sta/Elev= 30
  4601.3  333.22  4604.6  333.22  4608.5  330.99  4629.3  329.69  4637.1  328.37
  4672.3  326.59  4679.4  325.37  4693.1  324.65  4700.9  322.95  4721.7  322.58
  4764.7  318.92  4785.5  318.74  4793.3  317.84  4937.6  315.61  4956.0  315.15
  4994.2  316.02  5002.0  315.10  5012.1  315.60  5029.4  314.79  5032.1  314.29
  5035.4  314.79  5062.8  315.81  5094.0  318.27  5141.4  322.77  5194.6  326.13
  5202.2  327.30  5235.2  329.21  5263.0  332.32  5270.8  332.50  5296.0  335.52
#Mann=7,-1,0
  4601.3    0.12       0  4937.6    0.16       0  4994.2    0.12       0
  5029.4    0.07       0  5035.4    0.12       0  5094.0    0.16       0
  5270.8    0.12       0
Bank Sta=5029.4,5035.4
Exp/Cntr=0.3,0.1

Type RM Length L Ch R = 1,4181,468,468,468
BEGIN DESCRIPTION:
UNT 051 IN CACR 4.0
END DESCRIPTION:
XS GIS Cut Line= 3
      3682749.63     10738810.20      3682449.61     10738710.19
      3682149.60     10738760.19
#Sta/Elev= 30
  4713.0  334.85  4755.2  330.85  4776.3  328.01  4807.6  325.60  4829.0  324.35
  4871.1  319.54  4881.7  319.24  4910.6  316.43  4944.9  315.07  4966.0  311.83
  4976.5  311.14  5005.2  310.99  5007.9  310.49  5011.2  310.99  5054.0  311.40
  5110.4  311.42  5118.0  313.45  5123.0  312.84  5130.6  314.27  5140.8  314.47
  5178.8  318.23  5183.9  317.93  5201.6  320.55  5221.9  321.57  5239.6  323.57
  5244.7  323.12  5262.4  326.26  5290.7  328.22  5323.3  332.36  5333.4  332.49
#Mann=7,-1,0
  4713.0    0.12       0  4807.6    0.16       0  4910.6    0.05       0
  5005.2   0.035       0  5011.2    0.05       0  5054.0    0.16       0
  5290.7    0.12       0
Bank Sta=5005.2,5011.2
Exp/Cntr=0.3,0.1

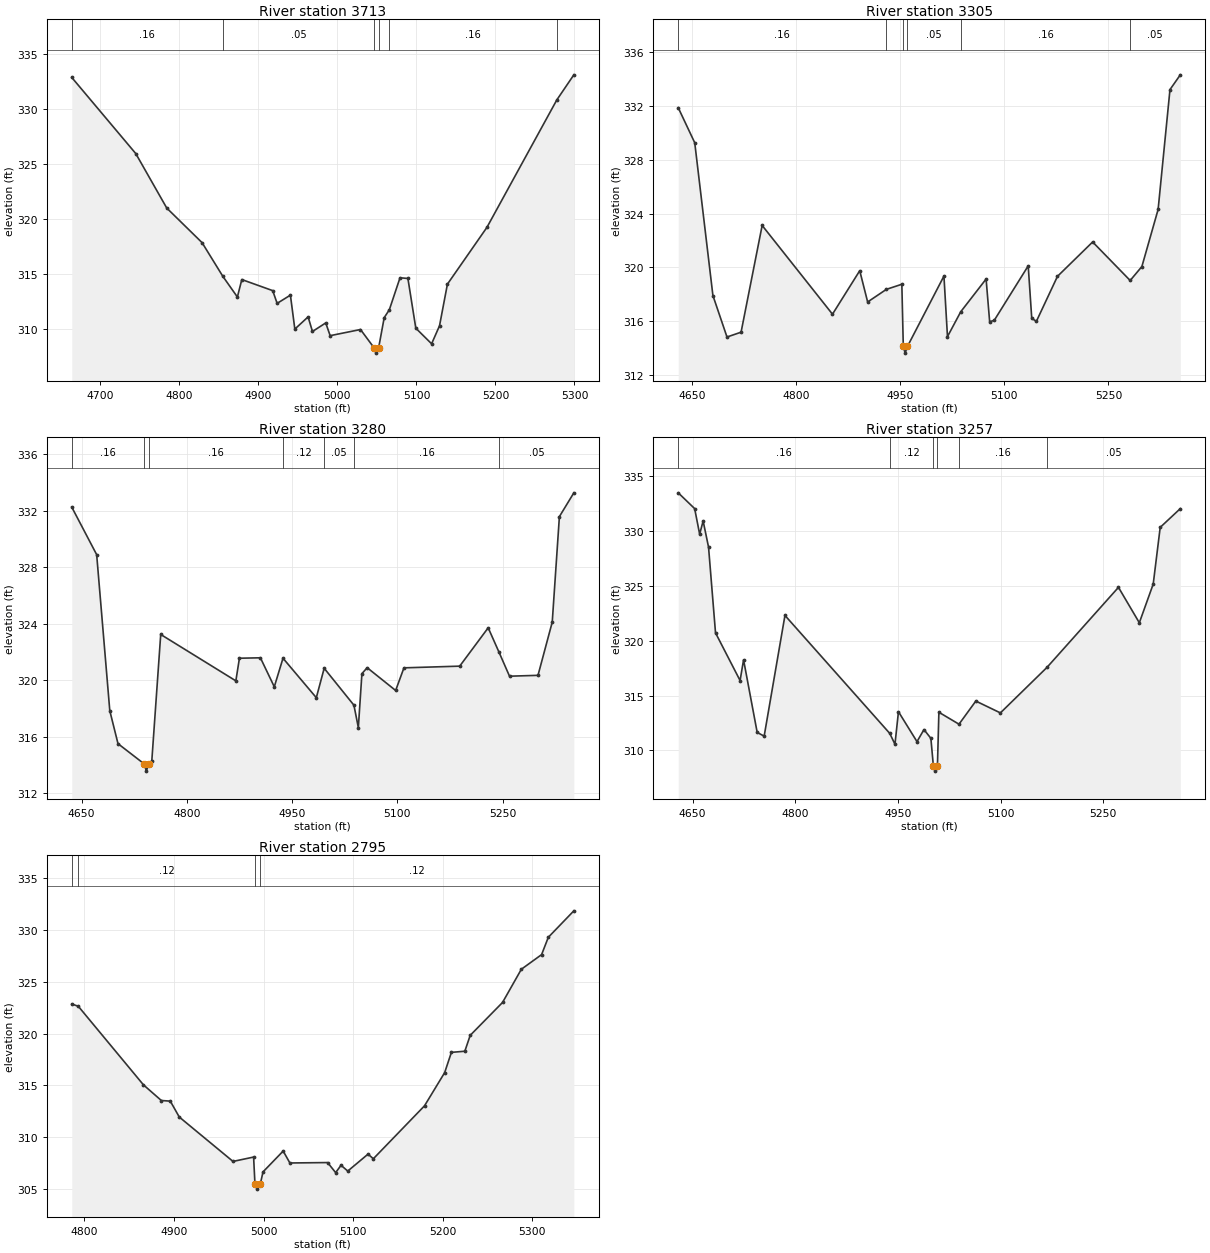
Type RM Length L Ch R = 1,3713,408,408,408
BEGIN DESCRIPTION:
UNT 051 IN CACR 3.0
END DESCRIPTION:
XS GIS Cut Line= 3
      3682749.59     10738410.18      3682449.61     10738260.19
      3682149.60     10738260.19
#Sta/Elev= 30
  4663.8  332.86  4744.8  325.93  4784.0  320.97  4828.7  317.82  4855.0  314.75
  4873.4  312.87  4879.0  314.46  4918.1  313.45  4923.7  312.29  4940.5  313.04
  4946.1  309.95  4962.9  311.06  4968.4  309.73  4985.2  310.51  4990.8  309.35
  5029.2  309.91  5046.2  308.26  5048.9  307.76  5052.2  308.26  5059.2  310.99
  5065.7  311.71  5079.2  314.62  5089.2  314.56  5099.2  310.03  5119.2  308.61
  5129.2  310.25  5139.2  314.04  5189.2  319.21  5277.6  330.81  5299.2  333.10
#Mann=6,-1,0
  4663.8    0.16       0  4855.0    0.05       0  5046.2   0.033       0
  5052.2    0.05       0  5065.7    0.16       0  5277.6    0.12       0
Bank Sta=5046.2,5052.2
Exp/Cntr=0.3,0.1

Type RM Length L Ch R = 1,3305,25,25,25
BEGIN DESCRIPTION:
Mapping XS 6d92875d
END DESCRIPTION:
XS GIS Cut Line= 2
      3682898.95     10737801.42      3682184.96     10737920.78
#Sta/Elev= 30
  4629.7  331.88  4653.5  329.27  4679.7  317.89  4700.0  314.80  4720.3  315.16
  4750.7  323.11  4852.1  316.50  4891.4  319.74  4902.8  317.41  4929.8  318.35
  4952.1  318.73  4954.2  314.10  4956.9  313.60  4960.2  314.10  5012.8  319.34
  5017.9  314.83  5037.0  316.68  5073.6  319.12  5078.7  315.94  5085.3  316.04
  5134.3  320.10  5139.4  316.19  5146.1  315.97  5176.5  319.32  5227.2  321.88
  5281.3  319.01  5298.2  320.05  5321.6  324.30  5338.7  333.23  5353.6  334.33
#Mann=6,-1,0
  4629.7    0.16       0  4929.8    0.05       0  4954.2   0.033       0
  4960.2    0.05       0  5037.0    0.16       0  5281.3    0.05       0
Bank Sta=4954.2,4960.2
Exp/Cntr=0.3,0.1

Type RM Length L Ch R = 1,3280,23,23,23
BEGIN DESCRIPTION:
Mapping XS 10ccded7
END DESCRIPTION:
XS GIS Cut Line= 2
      3682894.59     10737775.38      3682189.29     10737896.91
#Sta/Elev= 30
  4636.0  332.24  4671.5  328.88  4690.2  317.85  4701.9  315.52  4739.5  314.08
  4742.3  313.58  4745.5  314.08  4750.1  314.31  4762.8  323.24  4869.9  319.96
  4875.0  321.56  4904.9  321.59  4924.7  319.54  4937.1  321.56  4984.6  318.77
  4995.8  320.85  5038.2  318.24  5044.5  316.66  5049.6  320.47  5057.1  320.89
  5097.7  319.28  5109.5  320.88  5189.0  321.00  5229.6  323.71  5245.0  321.99
  5260.0  320.29  5300.6  320.35  5320.9  324.11  5331.1  331.57  5351.7  333.25
#Mann=7,-1,0
  4636.0    0.16       0  4739.5   0.033       0  4745.5    0.16       0
  4937.1    0.12       0  4995.8    0.05       0  5038.2    0.16       0
  5245.0    0.05       0
Bank Sta=4739.5,4745.5
Exp/Cntr=0.3,0.1

Type RM Length L Ch R = 1,3257,462,462,462
BEGIN DESCRIPTION:
UNT 051 IN CACR 2.0
END DESCRIPTION:
XS GIS Cut Line= 2
      3682903.26     10737749.34      3682180.62     10737877.38
#Sta/Elev= 30
  4628.9  333.49  4652.9  332.05  4660.2  329.72  4665.3  330.92  4673.2  328.54
  4683.4  320.72  4719.3  316.37  4724.4  318.26  4744.3  311.64  4754.5  311.30
  4784.9  322.31  4938.1  311.55  4945.7  310.56  4950.8  313.53  4977.9  310.80
  4988.1  311.90  4998.2  311.10  5001.8  308.61  5004.6  308.11  5007.8  308.61
  5009.9  313.48  5039.3  312.39  5063.9  314.50  5099.8  313.42  5167.9  317.57
  5272.4  324.87  5302.9  321.64  5323.2  325.17  5333.4  330.34  5362.8  332.05
#Mann=6,-1,0
  4628.9    0.16       0  4938.1    0.12       0  5001.8    0.07       0
  5007.8    0.12       0  5039.3    0.16       0  5167.9    0.05       0
Bank Sta=5001.8,5007.8
Exp/Cntr=0.3,0.1

Type RM Length L Ch R = 1,2795,0,0,0
BEGIN DESCRIPTION:
UNT 051 IN CACR 1.0
END DESCRIPTION:
XS GIS Cut Line= 3
      3682699.57     10737360.19      3682499.61     10737360.19
      3682199.62     10737560.18
#Sta/Elev= 30
  4785.9  322.85  4793.2  322.63  4865.9  315.06  4885.9  313.55  4895.9  313.49
  4905.9  311.96  4965.9  307.68  4988.9  308.10  4990.4  305.51  4993.1  305.01
  4996.4  305.51  4999.4  306.67  5021.9  308.68  5029.4  307.53  5071.5  307.57
  5080.5  306.60  5086.5  307.31  5094.0  306.75  5116.6  308.38  5122.6  307.94
  5179.7  313.04  5202.2  316.24  5209.7  318.19  5224.7  318.30  5230.7  319.83
  5266.8  323.00  5287.8  326.20  5310.4  327.61  5317.9  329.28  5346.4  331.83
#Mann=4,-1,0
  4785.9    0.05       0  4793.2    0.12       0  4990.4    0.07       0
  4996.4    0.12       0
Bank Sta=4990.4,4996.4
Exp/Cntr=0.3,0.1

Chan Stop Cuts=-1