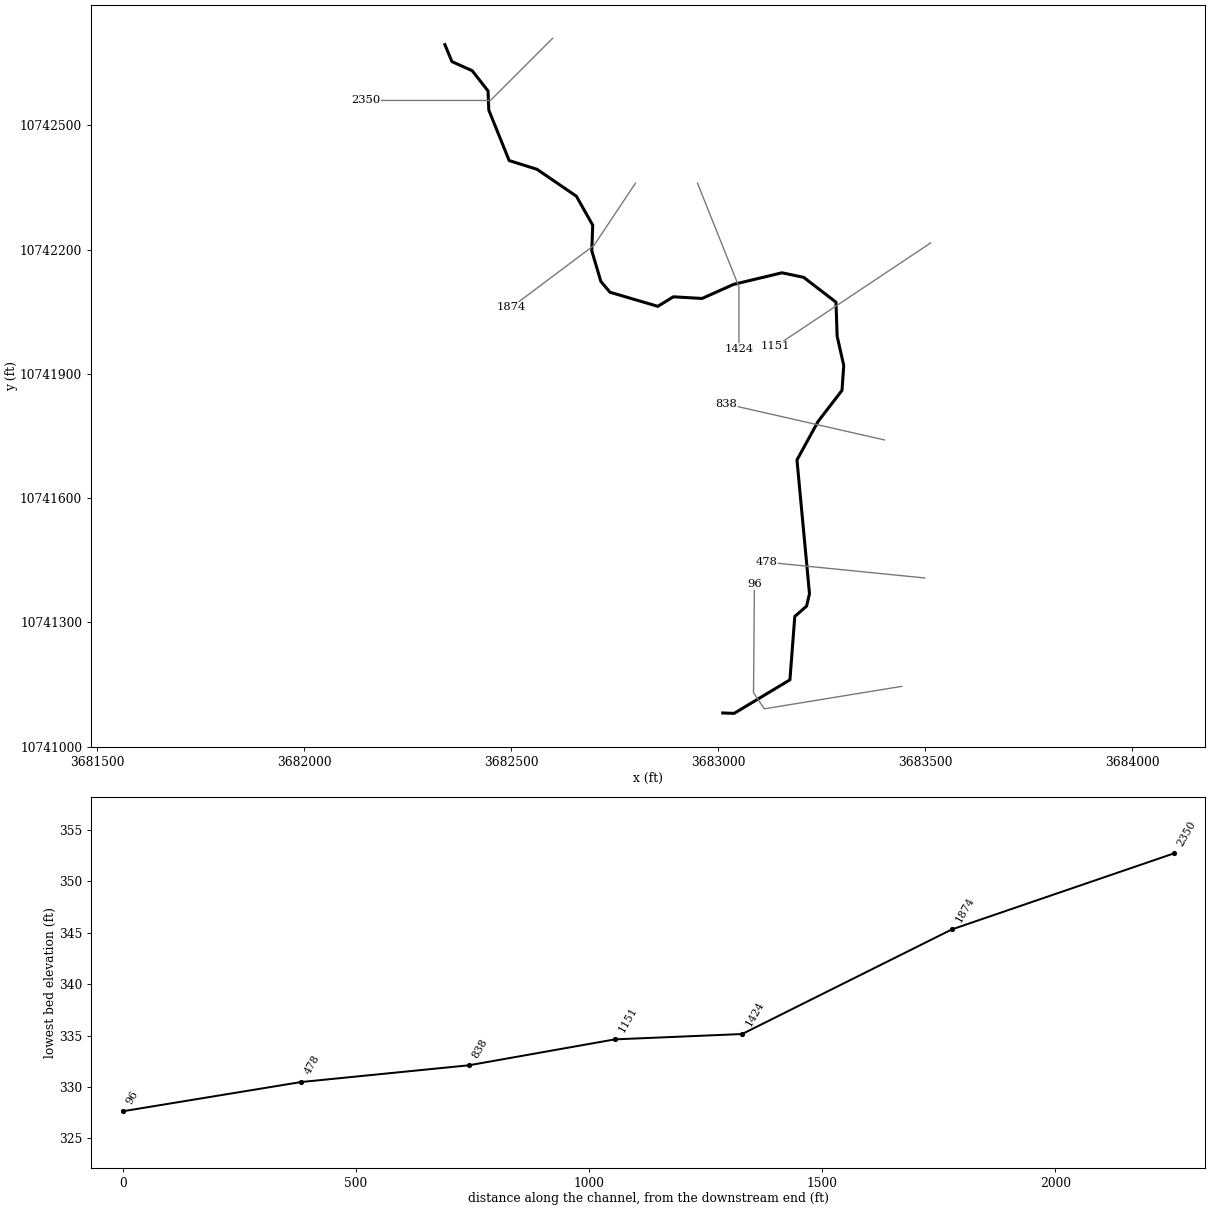
--- UNT 052 IN CACR.prj (project) ---

Proj Title=UNT 052 IN CACR Base Level Engineering
Current Plan=p01
Default Exp/Contr=0.3,0.1
English Units
Geom File=g01
Flow File=f01
Plan File=p01
BEGIN DESCRIPTION:
UNT 052 IN CACR
END DESCRIPTION:

--- UNT 052 IN CACR.p01 (plan) ---

Plan Title=Multiple Run
Short Identifier=Multiple
Geom File=g01
Flow File=f01
Subcritical Flow
K Sum by GR= 0
Std Step Tol= 0.01
Critical Tol= 0.01
Num of Std Step Trials= 20
Max Error Tol= 0.3
Flow Tol Ratio= 0.001
Split Flow NTrial= 30
Split Flow Tol= 0.02
Split Flow Ratio= 0.02
Log Output Level= 0
Friction Slope Method= 1
Unsteady Friction Slope Method= 2
Unsteady Bridges Friction Slope Method= 1
Parabolic Critical Depth
Global Vel Dist=  1 , 1 , 1
Global Log Level= 0
CheckData=True
Encroach Param= -1, 0, 0, 0
BEGIN DESCRIPTION:
Multiple Run
END DESCRIPTION:

--- UNT 052 IN CACR.f01 (steady flow) ---

Flow Title=Multiple
Number of Profiles=7
Profile Names=10-year,25-year,50-year,1pct_min,100-year,1pct_plu,500-year
River Rch & RM= UNT 052 IN CACR,Reach-1,2350
     215     273     317     272     369     498     496
Boundary for River Rch & Prof#=UNT 052 IN CACR,Reach-1,1
Up Type=0
Dn Type=3
Dn Slope=0.005
Boundary for River Rch & Prof#=UNT 052 IN CACR,Reach-1,2
Up Type=0
Dn Type=3
Dn Slope=0.005
Boundary for River Rch & Prof#=UNT 052 IN CACR,Reach-1,3
Up Type=0
Dn Type=3
Dn Slope=0.005
Boundary for River Rch & Prof#=UNT 052 IN CACR,Reach-1,4
Up Type=0
Dn Type=3
Dn Slope=0.005
Boundary for River Rch & Prof#=UNT 052 IN CACR,Reach-1,5
Up Type=0
Dn Type=3
Dn Slope=0.005
Boundary for River Rch & Prof#=UNT 052 IN CACR,Reach-1,6
Up Type=0
Dn Type=3
Dn Slope=0.005
Boundary for River Rch & Prof#=UNT 052 IN CACR,Reach-1,7
Up Type=0
Dn Type=3
Dn Slope=0.005

--- UNT 052 IN CACR.g01 (geometry) ---

Geom Title=Existing Conditions

River Reach=UNT 052 IN CACR,Reach-1
Reach XY= 30
      3682339.50     10742695.00      3682356.50     10742654.00
      3682405.50     10742632.00      3682443.75     10742583.00
      3682445.50     10742537.00      3682494.75     10742415.00
      3682561.75     10742394.00      3682657.00     10742329.00
      3682696.50     10742259.00      3682694.25     10742197.00
      3682716.25     10742123.00      3682738.25     10742097.00
      3682853.75     10742063.00      3682891.25     10742086.00
      3682960.50     10742082.00      3683036.75     10742116.00
      3683153.50     10742144.00      3683206.00     10742133.00
      3683284.00     10742073.00      3683286.75     10741991.00
      3683302.75     10741920.00      3683298.50     10741860.00
      3683240.75     10741785.00      3683189.75     10741692.00
      3683220.00     10741369.00      3683213.00     10741339.00
      3683184.50     10741314.00      3683172.75     10741161.00
      3683038.00     10741080.00      3683010.50     10741081.00

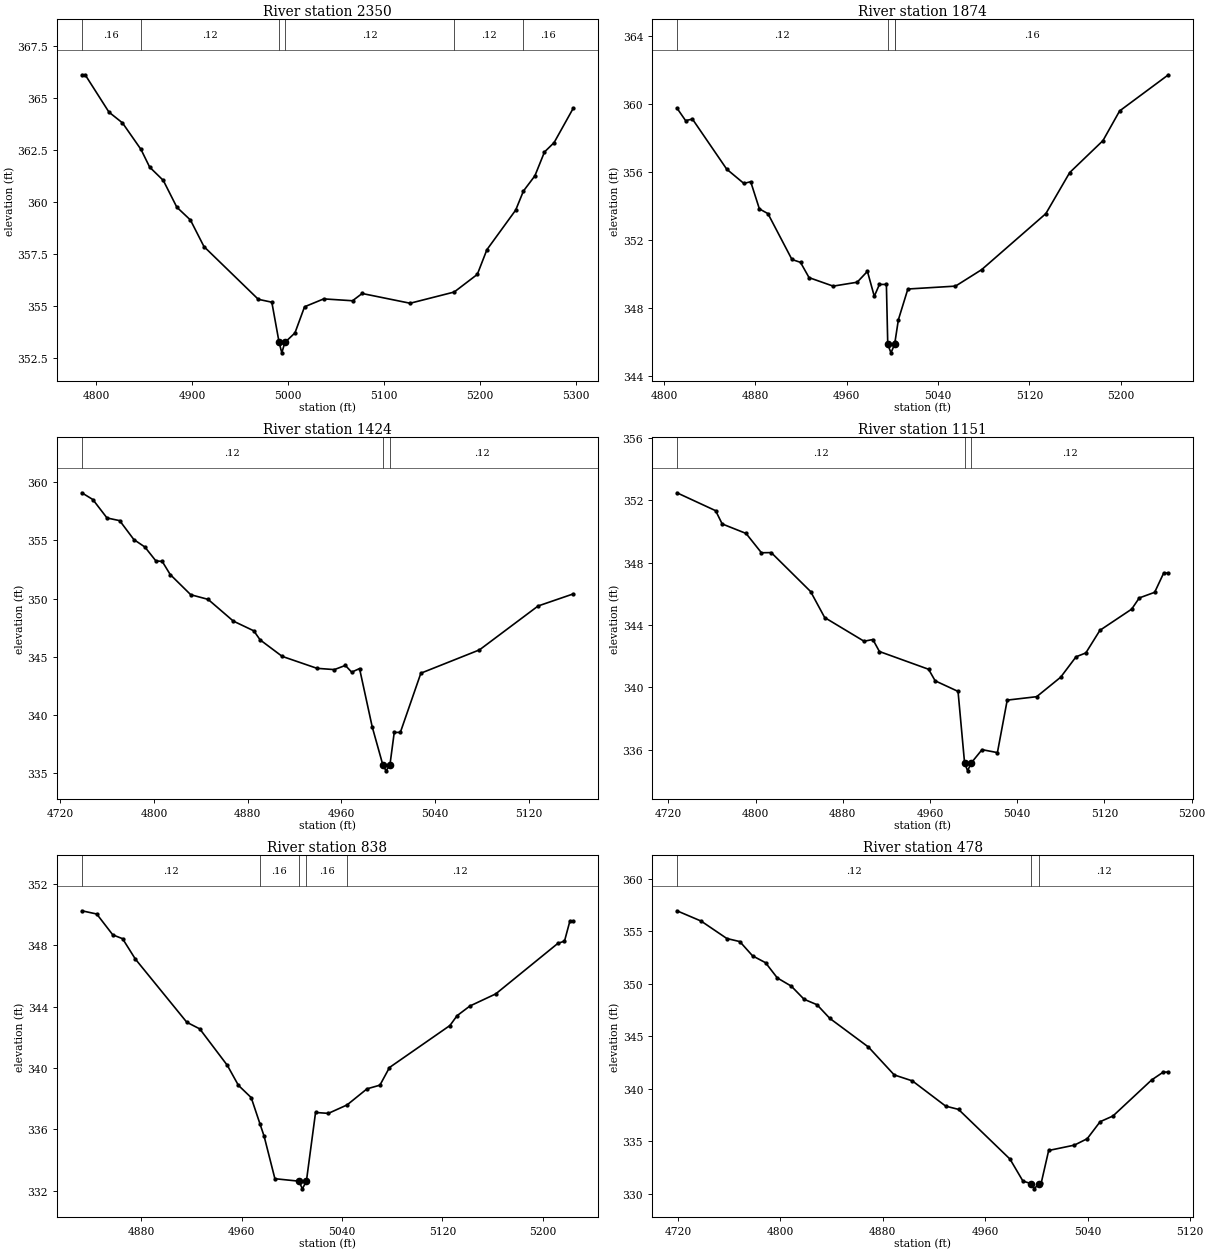
Type RM Length L Ch R = 1,2350,476,476,476
BEGIN DESCRIPTION:
UNT 052 IN CACR 5.0
END DESCRIPTION:
XS GIS Cut Line= 3
      3682599.62     10742710.20      3682449.61     10742560.19
      3682149.65     10742560.19
#Sta/Elev= 30
  4784.8  366.13  4788.3  366.13  4813.1  364.33  4827.2  363.81  4846.5  362.53
  4855.5  361.68  4869.7  361.04  4883.8  359.75  4898.0  359.13  4912.1  357.85
  4968.7  355.31  4982.8  355.17  4990.4  353.23  4993.2  352.73  4996.4  353.23
  5006.9  353.69  5016.9  354.95  5036.9  355.33  5066.9  355.24  5076.9  355.59
  5126.9  355.12  5172.8  355.66  5196.9  356.51  5206.9  357.70  5236.9  359.61
  5245.0  360.53  5256.9  361.26  5266.9  362.41  5276.9  362.86  5296.9  364.52
#Mann=6,-1,0
  4784.8    0.16       0  4846.5    0.12       0  4990.4    0.07       0
  4996.4    0.12       0  5172.8    0.12       0  5245.0    0.16       0
Bank Sta=4990.4,4996.4
Exp/Cntr=0.3,0.1

Type RM Length L Ch R = 1,1874,450,450,450
BEGIN DESCRIPTION:
UNT 052 IN CACR 4.0
END DESCRIPTION:
XS GIS Cut Line= 3
      3682799.63     10742360.22      3682699.61     10742210.19
      3682499.63     10742060.20
#Sta/Elev= 30
  4811.4  359.76  4819.0  359.02  4825.0  359.11  4855.0  356.16  4870.0  355.32
  4876.0  355.42  4883.6  353.82  4891.1  353.54  4912.1  350.84  4919.6  350.67
  4927.1  349.77  4948.2  349.27  4969.2  349.50  4978.2  350.14  4984.2  348.67
  4988.7  349.37  4994.8  349.37  4996.0  345.84  4998.8  345.34  5002.0  345.84
  5002.3  345.97  5005.3  347.29  5013.6  349.10  5055.3  349.27  5078.2  350.24
  5134.4  353.54  5155.3  355.96  5184.4  357.84  5199.0  359.59  5241.7  361.72
#Mann=4,-1,0
  4811.4    0.12       0  4996.0    0.07       0  5002.0    0.12       0
  5002.3    0.16       0
Bank Sta=4996,5002
Exp/Cntr=0.3,0.1

Type RM Length L Ch R = 1,1424,273,273,273
BEGIN DESCRIPTION:
UNT 052 IN CACR 3.0
END DESCRIPTION:
XS GIS Cut Line= 3
      3682949.62     10742360.15      3683049.61     10742110.19
      3683049.61     10741960.21
#Sta/Elev= 30
  4738.5  359.11  4747.9  358.53  4760.0  356.94  4770.8  356.71  4782.9  355.08
  4792.3  354.44  4801.7  353.24  4807.1  353.20  4813.9  352.07  4831.4  350.33
  4846.2  349.93  4867.7  348.06  4885.2  347.22  4890.6  346.44  4909.4  345.02
  4939.1  343.99  4953.9  343.88  4963.3  344.24  4968.7  343.66  4975.4  343.97
  4986.2  338.95  4995.3  335.66  4998.0  335.16  5001.3  335.66  5005.0  338.47
  5010.2  338.47  5027.7  343.57  5077.7  345.58  5127.7  349.36  5157.7  350.40
#Mann=3,-1,0
  4738.5    0.12       0  4995.3    0.07       0  5001.3    0.12       0
Bank Sta=4995.3,5001.3
Exp/Cntr=0.3,0.1

Type RM Length L Ch R = 1,1151,313,313,313
BEGIN DESCRIPTION:
Mapping XS b06450d1
END DESCRIPTION:
XS GIS Cut Line= 2
      3683512.38     10742216.01      3683137.38     10741966.01
#Sta/Elev= 30
  4727.9  352.49  4763.4  351.34  4769.4  350.49  4791.3  349.88  4805.4  348.64
  4814.4  348.65  4850.5  346.15  4863.4  344.48  4899.5  342.96  4907.6  343.07
  4913.6  342.30  4958.7  341.16  4964.7  340.42  4985.7  339.74  4991.7  335.14
  4994.5  334.64  4997.7  335.14  5007.7  336.00  5021.8  335.81  5030.8  339.18
  5057.8  339.40  5079.8  340.65  5093.9  341.96  5102.9  342.21  5115.8  343.66
  5144.9  345.02  5151.9  345.74  5166.0  346.10  5174.3  347.34  5178.6  347.34
#Mann=3,-1,0
  4727.9    0.12       0  4991.7    0.07       0  4997.7    0.12       0
Bank Sta=4991.7,4997.7
Exp/Cntr=0.3,0.1

Type RM Length L Ch R = 1,838,360,360,360
BEGIN DESCRIPTION:
Mapping XS eef435fe
END DESCRIPTION:
XS GIS Cut Line= 2
      3683401.26     10741740.29      3683019.30     10741827.10
#Sta/Elev= 30
  4832.6  350.25  4844.5  350.04  4857.3  348.68  4865.1  348.43  4875.3  347.10
  4916.3  342.98  4926.6  342.55  4948.6  340.17  4957.4  338.87  4967.6  338.07
  4974.5  336.38  4977.9  335.55  4986.5  332.78  5005.6  332.62  5008.4  332.12
  5011.6  332.62  5018.9  337.10  5029.1  337.04  5044.0  337.59  5059.9  338.64
  5070.2  338.88  5077.8  340.03  5126.0  342.77  5131.7  343.41  5141.9  344.04
  5162.5  344.83  5212.1  348.13  5217.3  348.27  5221.6  349.58  5224.3  349.58
#Mann=5,-1,0
  4832.6    0.12       0  4974.5    0.16       0  5005.6    0.07       0
  5011.6    0.16       0  5044.0    0.12       0
Bank Sta=5005.6,5011.6
Exp/Cntr=0.3,0.1

Type RM Length L Ch R = 1,478,382,382,382
BEGIN DESCRIPTION:
UNT 052 IN CACR 2.0
END DESCRIPTION:
XS GIS Cut Line= 2
      3683498.44     10741406.97      3683116.54     10741445.16
#Sta/Elev= 30
  4719.3  356.95  4738.2  355.97  4758.3  354.31  4768.4  354.02  4778.4  352.66
  4788.5  352.01  4797.7  350.56  4808.6  349.78  4818.6  348.53  4828.7  348.01
  4838.7  346.71  4868.9  343.98  4889.0  341.33  4903.2  340.76  4929.2  338.36
  4939.2  338.05  4979.4  333.32  4989.5  331.23  4995.7  330.99  4998.5  330.49
  5001.7  330.99  5003.7  331.00  5009.6  334.14  5029.7  334.65  5039.7  335.26
  5049.8  336.88  5059.8  337.42  5090.0  340.85  5099.1  341.60  5103.1  341.60
#Mann=3,-1,0
  4719.3    0.12       0  4995.7    0.07       0  5001.7    0.12       0
Bank Sta=4995.7,5001.7
Exp/Cntr=0.3,0.1

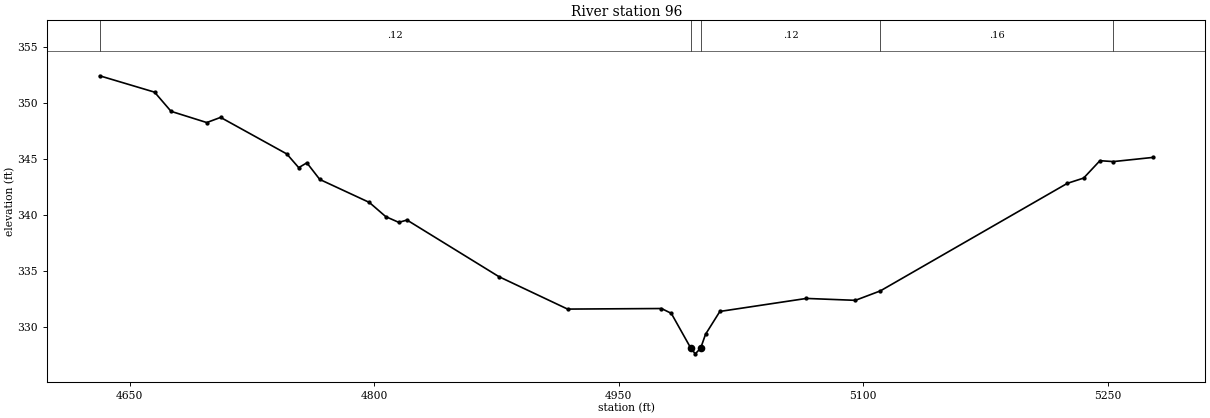
Type RM Length L Ch R = 1,96,0,0,0
BEGIN DESCRIPTION:
UNT 052 IN CACR 1.0
END DESCRIPTION:
XS GIS Cut Line= 4
      3683442.86     10741145.24      3683110.87     10741090.99
      3683084.83     10741130.05      3683087.00     10741392.61
#Sta/Elev= 30
  4631.6  352.44  4665.3  350.98  4675.4  349.27  4697.3  348.27  4705.8  348.73
  4746.4  345.47  4753.7  344.25  4758.7  344.68  4766.6  343.20  4797.0  341.15
  4807.1  339.88  4815.1  339.37  4820.1  339.58  4876.5  334.53  4918.6  331.64
  4976.2  331.69  4982.2  331.26  4994.2  328.15  4996.9  327.65  5000.2  328.15
  5003.2  329.39  5012.0  331.43  5065.1  332.59  5095.1  332.42  5110.4  333.26
  5225.1  342.85  5235.1  343.32  5245.1  344.87  5253.3  344.79  5277.5  345.16
#Mann=5,-1,0
  4631.6    0.12       0  4994.2    0.07       0  5000.2    0.12       0
  5110.4    0.16       0  5253.3    0.12       0
Bank Sta=4994.2,5000.2
Exp/Cntr=0.3,0.1

Chan Stop Cuts=-1