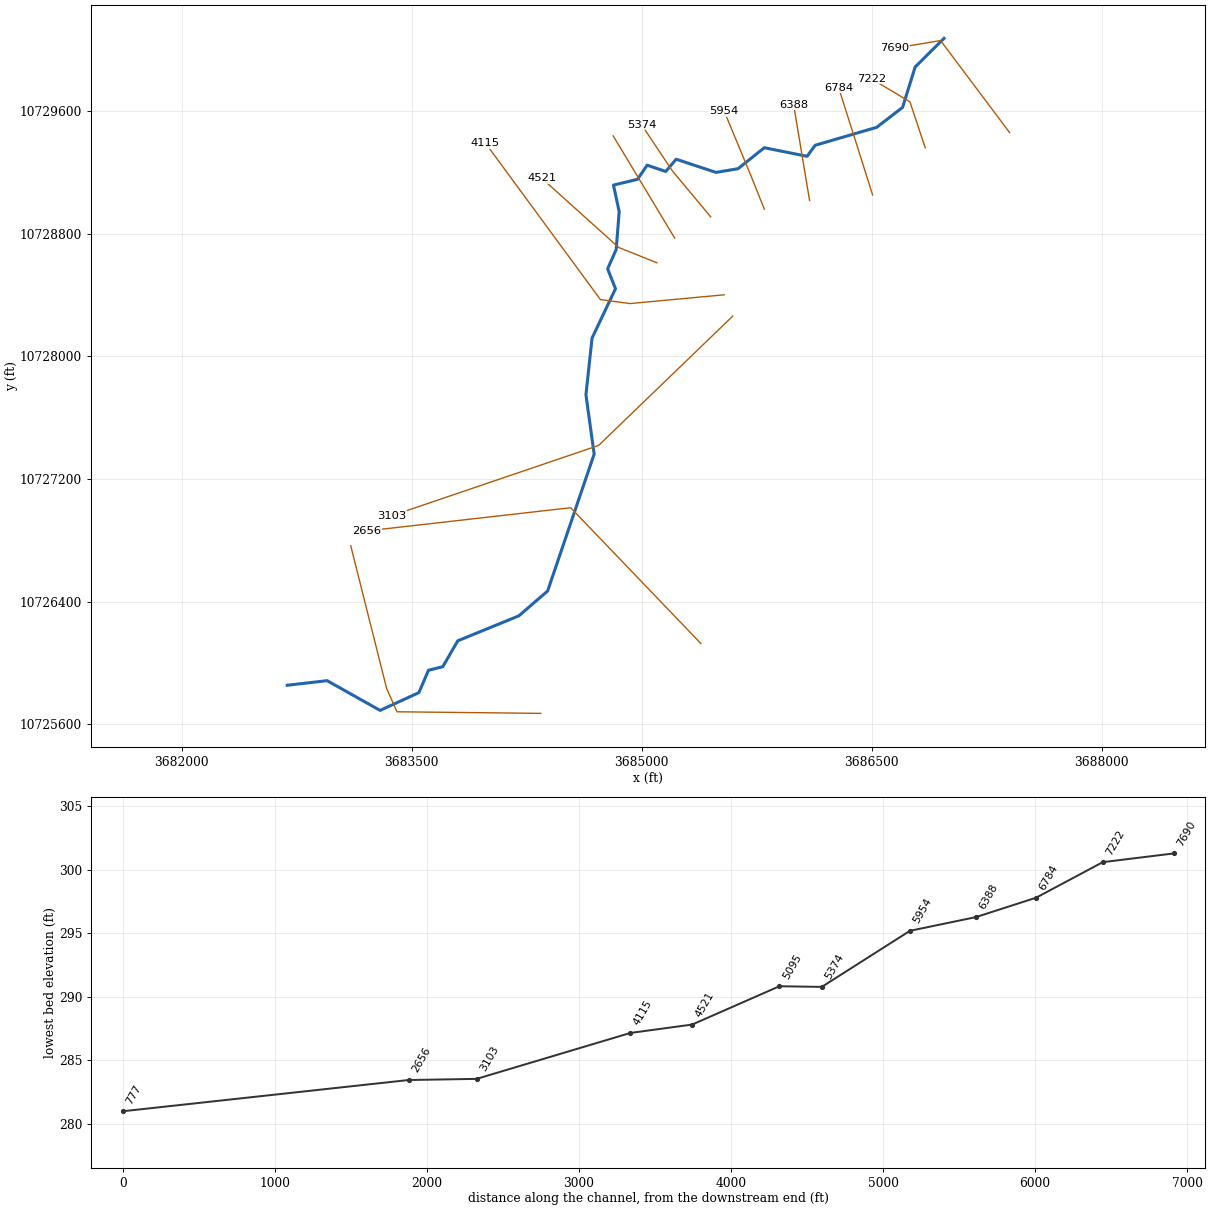
--- UNT 053 IN CACR.prj (project) ---

Proj Title=UNT 053 IN CACR Base Level Engineering
Current Plan=p01
Default Exp/Contr=0.3,0.1
English Units
Geom File=g01
Flow File=f01
Plan File=p01
BEGIN DESCRIPTION:
UNT 053 IN CACR
END DESCRIPTION:

--- UNT 053 IN CACR.p01 (plan) ---

Plan Title=Multiple Run
Short Identifier=Multiple
Geom File=g01
Flow File=f01
Subcritical Flow
K Sum by GR= 0
Std Step Tol= 0.01
Critical Tol= 0.01
Num of Std Step Trials= 20
Max Error Tol= 0.3
Flow Tol Ratio= 0.001
Split Flow NTrial= 30
Split Flow Tol= 0.02
Split Flow Ratio= 0.02
Log Output Level= 0
Friction Slope Method= 1
Unsteady Friction Slope Method= 2
Unsteady Bridges Friction Slope Method= 1
Parabolic Critical Depth
Global Vel Dist=  1 , 1 , 1
Global Log Level= 0
CheckData=True
Encroach Param= -1, 0, 0, 0
BEGIN DESCRIPTION:
Multiple Run
END DESCRIPTION:

--- UNT 053 IN CACR.f01 (steady flow) ---

Flow Title=Multiple
Number of Profiles=7
Profile Names=10-year,25-year,50-year,1pct_min,100-year,1pct_plu,500-year
River Rch & RM= UNT 053 IN CACR,Reach-1,7690
     531     717     869     774    1046    1415    1520
River Rch & RM= UNT 053 IN CACR,Reach-1,4115
     763    1046    1281    1150    1556    2104    2300
Boundary for River Rch & Prof#=UNT 053 IN CACR,Reach-1,1
Up Type=0
Dn Type=3
Dn Slope=0.005
Boundary for River Rch & Prof#=UNT 053 IN CACR,Reach-1,2
Up Type=0
Dn Type=3
Dn Slope=0.005
Boundary for River Rch & Prof#=UNT 053 IN CACR,Reach-1,3
Up Type=0
Dn Type=3
Dn Slope=0.005
Boundary for River Rch & Prof#=UNT 053 IN CACR,Reach-1,4
Up Type=0
Dn Type=3
Dn Slope=0.005
Boundary for River Rch & Prof#=UNT 053 IN CACR,Reach-1,5
Up Type=0
Dn Type=3
Dn Slope=0.005
Boundary for River Rch & Prof#=UNT 053 IN CACR,Reach-1,6
Up Type=0
Dn Type=3
Dn Slope=0.005
Boundary for River Rch & Prof#=UNT 053 IN CACR,Reach-1,7
Up Type=0
Dn Type=3
Dn Slope=0.005

--- UNT 053 IN CACR.g01 (geometry) ---

Geom Title=Existing Conditions

River Reach=UNT 053 IN CACR,Reach-1
Reach XY= 30
      3686972.00     10730074.65      3686783.75     10729888.00
      3686701.50     10729624.00      3686532.50     10729494.00
      3686131.25     10729377.00      3686078.75     10729305.00
      3685799.50     10729361.00      3685628.25     10729224.00
      3685484.25     10729200.00      3685224.50     10729286.00
      3685156.75     10729206.00      3685035.25     10729247.00
      3684972.50     10729155.00      3684815.50     10729117.00
      3684853.00     10728944.00      3684833.25     10728697.00
      3684777.50     10728571.00      3684828.75     10728441.00
      3684675.75     10728119.00      3684636.00     10727749.00
      3684689.50     10727362.00      3684386.00     10726469.00
      3684198.50     10726307.00      3683800.00     10726144.00
      3683702.00     10725975.00      3683609.00     10725952.00
      3683546.50     10725806.00      3683293.00     10725690.00
      3682947.50     10725884.00      3682687.50     10725854.00

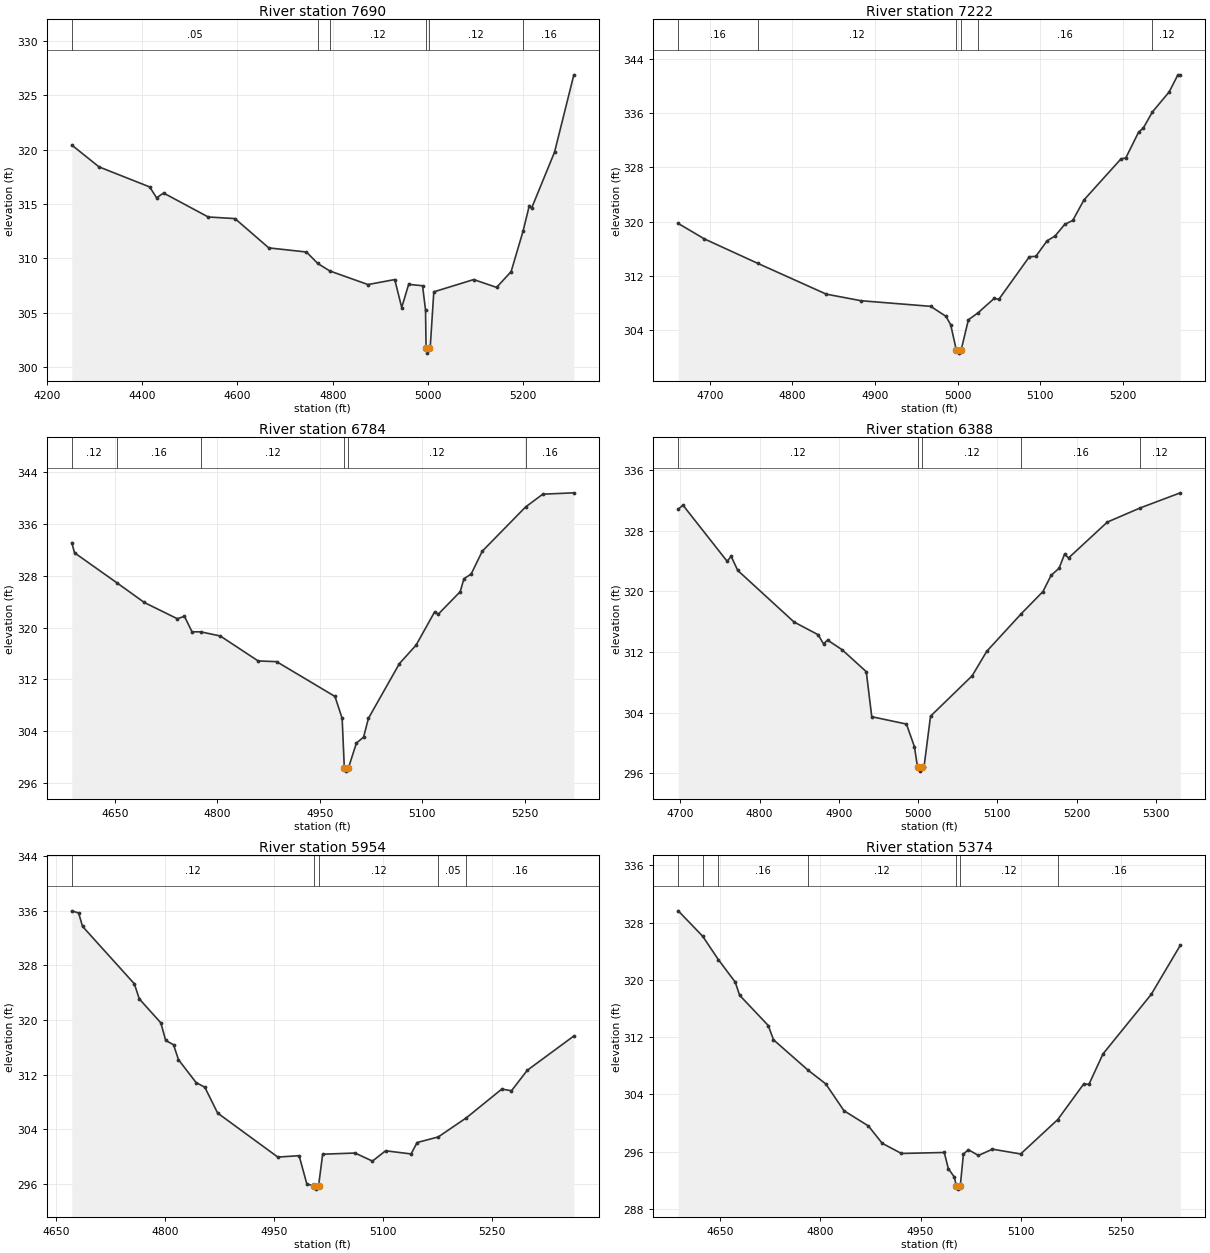
Type RM Length L Ch R = 1,7690,468,468,468
BEGIN DESCRIPTION:
UNT 053 IN CACR 12.0
END DESCRIPTION:
XS GIS Cut Line= 3
      3687399.61     10729460.18      3686949.61     10730060.19
      3686649.66     10730010.20
#Sta/Elev= 30
  4252.1  320.42  4309.4  318.41  4415.7  316.57  4430.2  315.57  4444.8  316.01
  4538.6  313.81  4594.8  313.66  4665.7  310.97  4744.8  310.59  4768.5  309.54
  4793.8  308.85  4874.0  307.60  4930.2  308.06  4944.8  305.49  4959.4  307.62
  4988.6  307.49  4994.8  305.27  4996.0  301.80  4998.7  301.30  5002.0  301.80
  5004.6  301.80  5012.2  306.93  5095.9  308.06  5144.0  307.34  5174.5  308.79
  5199.6  312.51  5212.5  314.82  5217.5  314.62  5265.7  319.77  5306.2  326.87
#Mann=6,-1,0
  4252.1    0.05       0  4768.5    0.16       0  4793.8    0.12       0
  4996.0    0.07       0  5002.0    0.12       0  5199.6    0.16       0
Bank Sta=4996,5002
Exp/Cntr=0.3,0.1

Type RM Length L Ch R = 1,7222,438,438,438
BEGIN DESCRIPTION:
UNT 053 IN CACR 11.0
END DESCRIPTION:
XS GIS Cut Line= 3
      3686849.60     10729360.23      3686749.61     10729660.19
      3686499.64     10729810.17
#Sta/Elev= 30
  4661.8  319.74  4693.4  317.46  4758.1  313.85  4841.0  309.31  4883.1  308.34
  4967.4  307.51  4985.8  306.04  4991.6  304.79  4998.3  301.11  5001.1  300.61
  5004.3  301.11  5013.0  305.53  5024.8  306.57  5044.1  308.67  5049.9  308.55
  5086.8  314.83  5094.6  314.88  5108.2  317.17  5117.9  317.89  5129.6  319.60
  5139.3  320.18  5152.9  323.21  5197.6  329.25  5203.5  329.40  5219.0  333.20
  5224.8  333.83  5235.8  336.20  5255.9  339.12  5266.6  341.66  5269.5  341.66
#Mann=6,-1,0
  4661.8    0.16       0  4758.1    0.12       0  4998.3    0.07       0
  5004.3    0.12       0  5024.8    0.16       0  5235.8    0.12       0
Bank Sta=4998.3,5004.3
Exp/Cntr=0.3,0.1

Type RM Length L Ch R = 1,6784,396,396,396
BEGIN DESCRIPTION:
Mapping XS 84a49fa2
END DESCRIPTION:
XS GIS Cut Line= 2
      3686506.34     10729052.92      3686284.35     10729753.59
#Sta/Elev= 30
  4586.8  333.15  4590.9  331.57  4652.8  326.94  4693.0  323.89  4741.3  321.38
  4751.8  321.75  4762.8  319.36  4775.7  319.35  4804.2  318.71  4859.7  314.85
  4886.7  314.74  4972.1  309.36  4982.6  305.98  4985.8  298.31  4988.6  297.81
  4991.8  298.31  5003.5  302.15  5014.0  303.07  5021.1  305.98  5066.5  314.45
  5090.9  317.30  5118.0  322.44  5123.2  322.07  5155.5  325.57  5160.9  327.57
  5171.4  328.28  5187.8  331.83  5251.2  338.67  5276.3  340.64  5321.8  340.85
#Mann=6,-1,0
  4586.8    0.12       0  4652.8    0.16       0  4775.7    0.12       0
  4985.8    0.07       0  4991.8    0.12       0  5251.2    0.16       0
Bank Sta=4985.8,4991.8
Exp/Cntr=0.3,0.1

Type RM Length L Ch R = 1,6388,434,434,434
BEGIN DESCRIPTION:
UNT 053 IN CACR 9.0
END DESCRIPTION:
XS GIS Cut Line= 2
      3686095.06     10729016.10      3685990.89     10729641.08
#Sta/Elev= 30
  4697.3  330.85  4703.3  331.37  4759.0  323.97  4764.1  324.62  4772.4  322.76
  4843.4  315.96  4873.8  314.28  4880.7  313.07  4885.7  313.57  4904.2  312.29
  4934.6  309.40  4941.5  303.46  4985.3  302.49  4995.4  299.49  4999.3  296.78
  5002.1  296.28  5005.3  296.78  5007.4  296.79  5015.7  303.53  5068.2  308.86
  5086.7  312.10  5130.2  317.05  5157.6  319.98  5167.8  322.11  5177.9  323.05
  5184.8  324.90  5189.9  324.41  5238.8  329.14  5280.1  331.00  5330.9  333.00
#Mann=5,-1,0
  4697.3    0.12       0  4999.3    0.07       0  5005.3    0.12       0
  5130.2    0.16       0  5280.1    0.12       0
Bank Sta=4999.3,5005.3
Exp/Cntr=0.3,0.1

Type RM Length L Ch R = 1,5954,580,580,580
BEGIN DESCRIPTION:
UNT 053 IN CACR 8.0
END DESCRIPTION:
XS GIS Cut Line= 3
      3685799.60     10728960.20      3685714.85     10729172.33
      3685537.76     10729599.44
#Sta/Elev= 30
  4671.8  336.00  4681.2  335.69  4686.6  333.72  4757.9  325.30  4764.7  323.09
  4794.4  319.57  4801.0  317.00  4811.8  316.37  4818.6  314.18  4842.8  310.83
  4854.9  310.13  4872.5  306.35  4955.3  299.90  4984.6  300.10  4995.3  295.93
  5005.4  295.70  5008.2  295.20  5011.4  295.70  5017.0  300.32  5061.6  300.49
  5085.5  299.31  5103.6  300.82  5138.7  300.36  5146.9  302.03  5176.0  302.85
  5214.8  305.66  5263.5  309.87  5276.8  309.62  5298.5  312.62  5362.6  317.65
#Mann=5,-1,0
  4671.8    0.12       0  5005.4    0.07       0  5011.4    0.12       0
  5176.0    0.05       0  5214.8    0.16       0
Bank Sta=5005.4,5011.4
Exp/Cntr=0.3,0.1

Type RM Length L Ch R = 1,5374,279,279,279
BEGIN DESCRIPTION:
UNT 053 IN CACR 7.0
END DESCRIPTION:
XS GIS Cut Line= 3
      3685449.60     10728910.20      3685199.61     10729210.19
      3684999.59     10729510.22
#Sta/Elev= 30
  4587.4  329.65  4623.9  326.11  4647.4  322.84  4672.7  319.69  4679.2  317.86
  4722.1  313.63  4729.9  311.64  4781.7  307.39  4808.0  305.49  4835.4  301.73
  4871.8  299.61  4892.6  297.18  4921.3  295.76  4985.4  295.90  4991.4  293.65
  5000.4  292.47  5003.4  291.28  5006.2  290.78  5009.4  291.28  5014.0  295.68
  5021.5  296.28  5036.5  295.48  5057.5  296.36  5099.6  295.69  5155.1  300.49
  5194.2  305.50  5201.7  305.40  5222.8  309.66  5294.9  317.97  5338.5  324.84
#Mann=7,-1,0
  4587.4    0.16       0  4623.9    0.12       0  4647.4    0.16       0
  4781.7    0.12       0  5003.4    0.07       0  5009.4    0.12       0
  5155.1    0.16       0
Bank Sta=5003.4,5009.4
Exp/Cntr=0.3,0.1

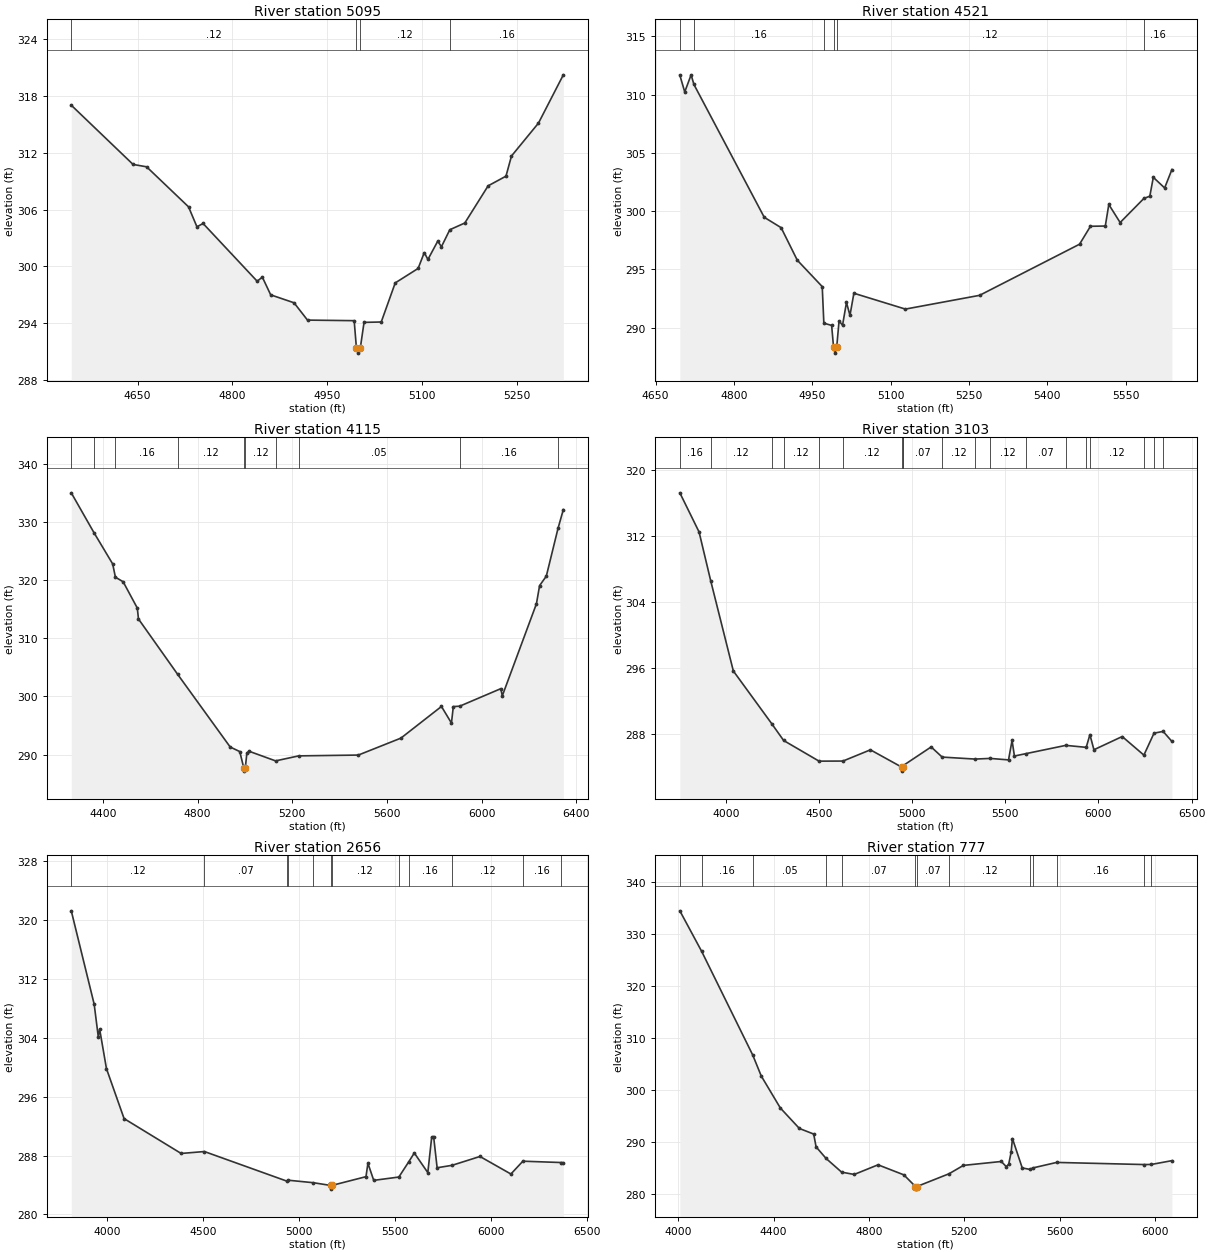
Type RM Length L Ch R = 1,5095,574,574,574
BEGIN DESCRIPTION:
UNT 053 IN CACR 6.0
END DESCRIPTION:
XS GIS Cut Line= 2
      3685214.85     10728771.28      3684813.81     10729437.95
#Sta/Elev= 30
  4545.1  317.03  4642.8  310.77  4664.2  310.52  4730.5  306.29  4743.8  304.18
  4753.5  304.53  4839.0  298.43  4847.2  298.86  4860.4  296.99  4897.3  296.15
  4918.6  294.32  4992.4  294.26  4996.0  291.33  4998.7  290.83  5002.0  291.33
  5008.0  294.08  5035.2  294.12  5057.3  298.25  5093.5  299.78  5103.2  301.45
  5109.0  300.73  5124.5  302.66  5130.4  302.08  5143.6  303.87  5167.3  304.58
  5204.2  308.51  5232.4  309.53  5241.1  311.66  5283.8  315.14  5323.1  320.24
#Mann=4,-1,0
  4545.1    0.12       0  4996.0    0.07       0  5002.0    0.12       0
  5143.6    0.16       0
Bank Sta=4996,5002
Exp/Cntr=0.3,0.1

Type RM Length L Ch R = 1,4521,406,406,406
BEGIN DESCRIPTION:
UNT 053 IN CACR 5.0
END DESCRIPTION:
XS GIS Cut Line= 3
      3685099.62     10728610.18      3684849.61     10728710.19
      3684349.57     10729160.22
#Sta/Elev= 30
  4696.4  311.67  4705.8  310.23  4718.0  311.70  4723.4  310.87  4858.0  299.47
  4890.3  298.58  4921.2  295.79  4969.0  293.52  4972.1  290.38  4987.0  290.19
  4990.7  288.31  4993.4  287.81  4996.7  288.31  5001.2  290.57  5007.9  290.21
  5015.4  292.16  5022.1  291.05  5029.6  292.95  5128.2  291.59  5270.2  292.77
  5461.6  297.16  5482.5  298.70  5510.9  298.72  5517.6  300.57  5539.3  299.02
  5584.8  301.09  5596.1  301.28  5602.8  302.90  5624.5  301.99  5638.4  303.57
#Mann=6,-1,0
  4696.4    0.12       0  4723.4    0.16       0  4972.1    0.12       0
  4990.7    0.03       0  4996.7    0.12       0  5584.8    0.16       0
Bank Sta=4990.7,4996.7
Exp/Cntr=0.3,0.1

Type RM Length L Ch R = 1,4115,1012,1012,1012
BEGIN DESCRIPTION:
UNT 053 IN CACR 4.0
END DESCRIPTION:
XS GIS Cut Line= 4
      3685537.77     10728401.49      3684923.19     10728344.20
      3684730.48     10728370.24      3683980.50     10729391.05
#Sta/Elev= 30
  4266.3  334.97  4361.8  328.15  4441.1  322.76  4452.8  320.47  4485.4  319.69
  4545.2  315.17  4550.2  313.29  4715.3  303.80  4937.6  291.29  4978.0  290.51
  4995.2  287.65  4997.9  287.15  5001.2  287.65  5008.2  290.30  5018.3  290.55
  5129.3  288.91  5227.0  289.77  5478.8  289.91  5658.6  292.82  5829.9  298.26
  5872.1  295.41  5880.0  298.24  5907.0  298.31  6080.6  301.32  6086.8  300.08
  6231.1  315.91  6244.4  319.03  6272.8  320.65  6322.2  328.86  6344.7  332.09
#Mann=10,-1,0
  4266.3    0.16       0  4361.8    0.12       0  4452.8    0.16       0
  4715.3    0.12       0  4995.2    0.07       0  5001.2    0.12       0
  5129.3    0.07       0  5227.0    0.05       0  5907.0    0.16       0
  6322.2    0.12       0
Bank Sta=4995.2,5001.2
Exp/Cntr=0.3,0.1

Type RM Length L Ch R = 1,3103,447,447,447
BEGIN DESCRIPTION:
UNT 053 IN CACR 3.0
END DESCRIPTION:
XS GIS Cut Line= 3
      3685593.54     10728262.28      3684718.56     10727418.56
      3683369.61     10726960.23
#Sta/Elev= 30
  3753.8  317.24  3857.0  312.50  3919.2  306.61  4040.9  295.66  4248.3  289.23
  4310.8  287.24  4500.7  284.74  4629.1  284.75  4776.4  286.11  4943.2  284.03
  4945.9  283.53  4949.2  284.03  4950.7  284.18  5102.2  286.46  5161.4  285.23
  5338.0  284.99  5418.9  285.07  5517.4  284.89  5536.3  287.24  5549.1  285.36
  5613.4  285.66  5824.6  286.65  5934.2  286.41  5954.1  287.95  5975.6  286.12
  6127.3  287.72  6243.7  285.47  6298.1  288.13  6346.9  288.34  6394.0  287.13
#Mann=19,-1,0
  3753.8    0.16       0  3919.2    0.12       0  4248.3    0.07       0
  4310.8    0.12       0  4500.7    0.07       0  4629.1    0.12       0
  4943.2    0.07       0  4949.2    0.12       0  4950.7    0.07       0
  5161.4    0.12       0  5338.0    0.08       0  5418.9    0.12       0
  5613.4    0.07       0  5824.6    0.12       0  5934.2    0.16       0
  5954.1    0.12       0  6243.7    0.16       0  6298.1    0.12       0
  6346.9    0.16       0
Bank Sta=4943.2,4949.2
Exp/Cntr=0.3,0.1

Type RM Length L Ch R = 1,2656,1879,1879,1879
BEGIN DESCRIPTION:
UNT 053 IN CACR 2.0
END DESCRIPTION:
XS GIS Cut Line= 3
      3685385.26     10726126.86      3684536.27     10727012.31
      3683208.13     10726861.27
#Sta/Elev= 30
  3811.8  321.20  3931.2  308.52  3952.6  304.09  3959.6  305.15  3995.1  299.79
  4086.9  293.01  4384.1  288.28  4505.4  288.54  4937.5  284.50  4941.8  284.65
  5073.3  284.31  5163.0  283.94  5165.7  283.44  5169.0  283.94  5347.1  285.13
  5357.2  286.95  5387.4  284.63  5518.3  285.08  5569.2  287.12  5598.8  288.34
  5669.2  285.68  5689.3  290.47  5699.4  290.58  5717.7  286.34  5795.5  286.67
  5940.9  287.87  6102.0  285.49  6164.3  287.23  6362.6  287.05  6375.2  287.02
#Mann=12,-1,0
  3811.8    0.12       0  4505.4    0.07       0  4937.5    0.12       0
  4941.8    0.07       0  5073.3    0.12       0  5163.0    0.07       0
  5169.0    0.12       0  5518.3    0.07       0  5569.2    0.16       0
  5795.5    0.12       0  6164.3    0.16       0  6362.6     0.1       0
Bank Sta=5163,5169
Exp/Cntr=0.3,0.1

Type RM Length L Ch R = 1,777,0,0,0
BEGIN DESCRIPTION:
UNT 053 IN CACR 1.0
END DESCRIPTION:
XS GIS Cut Line= 4
      3684341.17     10725670.59      3683403.65     10725681.01
      3683335.95     10725832.05      3683101.57     10726764.35
#Sta/Elev= 30
  4006.5  334.44  4098.1  326.65  4312.6  306.71  4348.1  302.71  4428.1  296.57
  4508.1  292.63  4568.1  291.56  4578.1  289.10  4620.1  286.87  4685.3  284.24
  4738.1  283.80  4838.1  285.65  4946.4  283.72  4995.0  281.48  4997.7  280.98
  5001.0  281.48  5135.8  283.93  5196.2  285.54  5355.1  286.29  5375.8  285.31
  5386.1  285.74  5396.4  288.06  5401.9  290.69  5443.0  285.05  5475.2  284.77
  5487.4  285.05  5587.5  286.11  5955.2  285.70  5984.8  285.72  6070.9  286.45
#Mann=13,-1,0
  4006.5    0.12       0  4098.1    0.16       0  4312.6    0.05       0
  4620.1    0.12       0  4685.3    0.07       0  4995.0    0.07       0
  5001.0    0.07       0  5135.8    0.12       0  5475.2    0.16       0
  5487.4    0.12       0  5587.5    0.16       0  5955.2     0.1       0
  5984.8    0.05       0
Bank Sta=4995,5001
Exp/Cntr=0.3,0.1

Chan Stop Cuts=-1