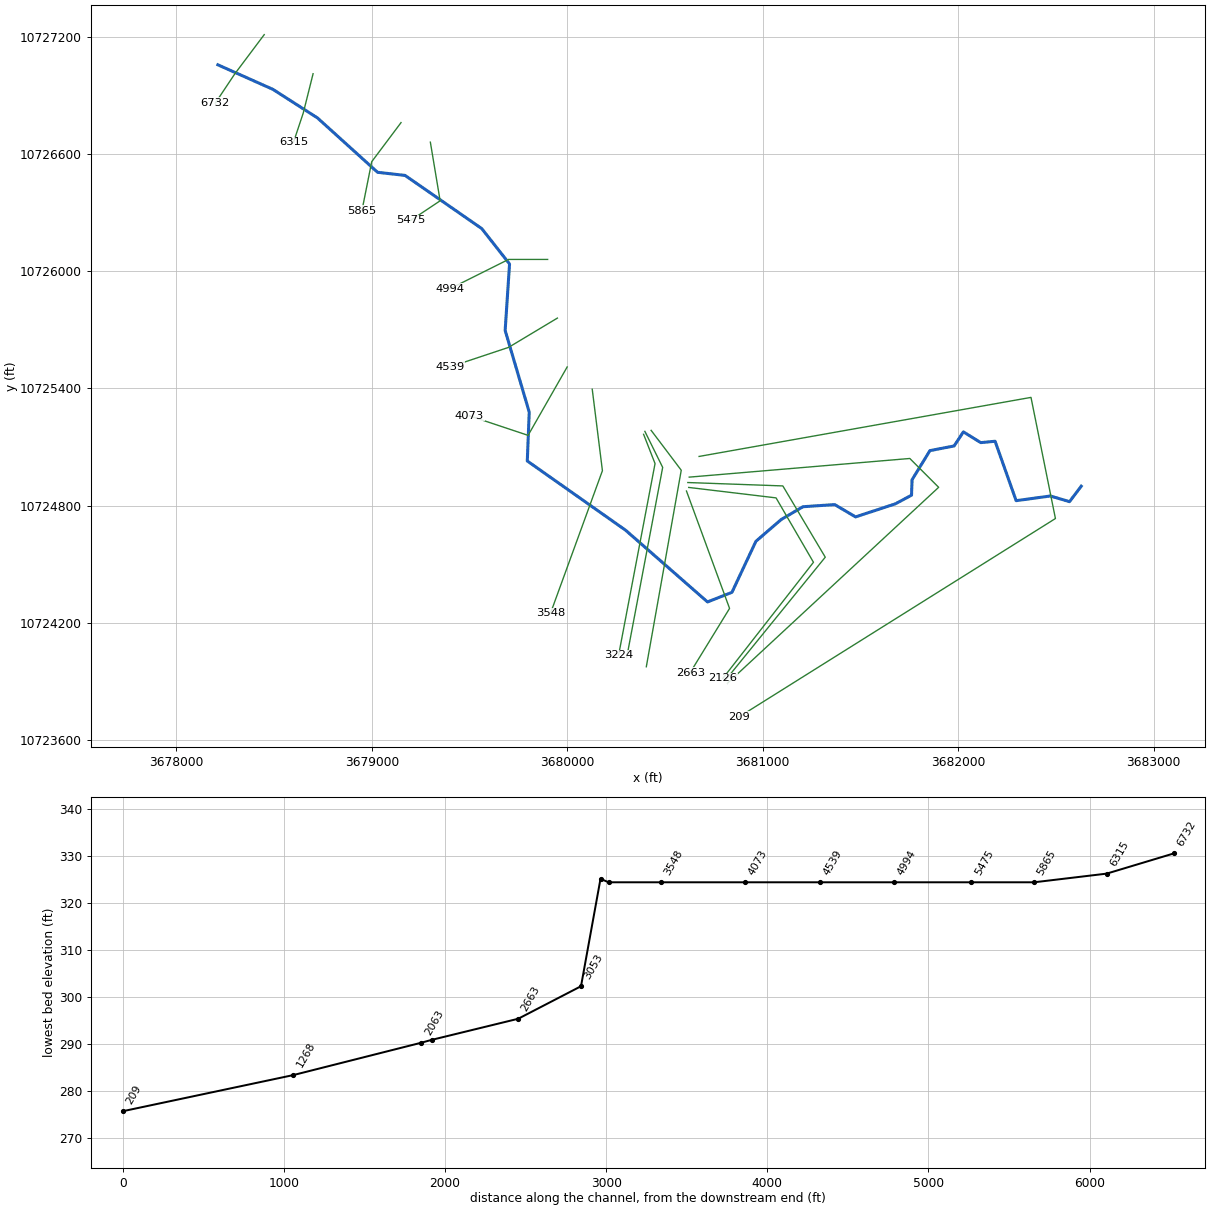
--- UNT 054 IN CACR.prj (project) ---

Proj Title=UNT 054 IN CACR Base Level Engineering
Current Plan=p01
Default Exp/Contr=0.3,0.1
English Units
Geom File=g01
Flow File=f01
Plan File=p01
BEGIN DESCRIPTION:
UNT 054 IN CACR
END DESCRIPTION:

--- UNT 054 IN CACR.p01 (plan) ---

Plan Title=Multiple Run
Short Identifier=Multiple
Geom File=g01
Flow File=f01
Subcritical Flow
K Sum by GR= 0
Std Step Tol= 0.01
Critical Tol= 0.01
Num of Std Step Trials= 20
Max Error Tol= 0.3
Flow Tol Ratio= 0.001
Split Flow NTrial= 30
Split Flow Tol= 0.02
Split Flow Ratio= 0.02
Log Output Level= 0
Friction Slope Method= 1
Unsteady Friction Slope Method= 2
Unsteady Bridges Friction Slope Method= 1
Parabolic Critical Depth
Global Vel Dist=  1 , 1 , 1
Global Log Level= 0
CheckData=True
Encroach Param= -1, 0, 0, 0
BEGIN DESCRIPTION:
Multiple Run
END DESCRIPTION:

--- UNT 054 IN CACR.f01 (steady flow) ---

Flow Title=Multiple
Number of Profiles=7
Profile Names=10-year,25-year,50-year,1pct_min,100-year,1pct_plu,500-year
River Rch & RM= UNT 054 IN CACR,Reach-1,6732
     592     808     988     887    1199    1622    1770
River Rch & RM= UNT 054 IN CACR,Reach-1,4073
     947    1328    1652    1507    2037    2755    3108
River Rch & RM= UNT 054 IN CACR,Reach-1,3053
    1029    1450    1809    1655    2239    3028    3436
Boundary for River Rch & Prof#=UNT 054 IN CACR,Reach-1,1
Up Type=0
Dn Type=3
Dn Slope=0.005
Boundary for River Rch & Prof#=UNT 054 IN CACR,Reach-1,2
Up Type=0
Dn Type=3
Dn Slope=0.005
Boundary for River Rch & Prof#=UNT 054 IN CACR,Reach-1,3
Up Type=0
Dn Type=3
Dn Slope=0.005
Boundary for River Rch & Prof#=UNT 054 IN CACR,Reach-1,4
Up Type=0
Dn Type=3
Dn Slope=0.005
Boundary for River Rch & Prof#=UNT 054 IN CACR,Reach-1,5
Up Type=0
Dn Type=3
Dn Slope=0.005
Boundary for River Rch & Prof#=UNT 054 IN CACR,Reach-1,6
Up Type=0
Dn Type=3
Dn Slope=0.005
Boundary for River Rch & Prof#=UNT 054 IN CACR,Reach-1,7
Up Type=0
Dn Type=3
Dn Slope=0.005

--- UNT 054 IN CACR.g01 (geometry) ---

Geom Title=Existing Conditions

River Reach=UNT 054 IN CACR,Reach-1
Reach XY= 30
      3678212.62     10727055.88      3678494.75     10726930.00
      3678722.25     10726784.00      3679029.50     10726506.00
      3679170.25     10726490.00      3679562.50     10726218.00
      3679704.75     10726037.00      3679682.25     10725697.00
      3679805.50     10725279.00      3679795.50     10725029.00
      3680298.25     10724675.00      3680717.50     10724308.00
      3680842.50     10724357.00      3680965.00     10724618.00
      3681095.00     10724730.00      3681205.75     10724795.00
      3681368.25     10724806.00      3681475.00     10724743.00
      3681679.00     10724810.00      3681761.25     10724854.00
      3681764.00     10724933.00      3681855.25     10725082.00
      3681979.25     10725106.00      3682026.50     10725178.00
      3682115.50     10725123.00      3682188.75     10725130.00
      3682296.50     10724826.00      3682471.50     10724850.00
      3682569.50     10724821.00      3682629.50     10724900.00

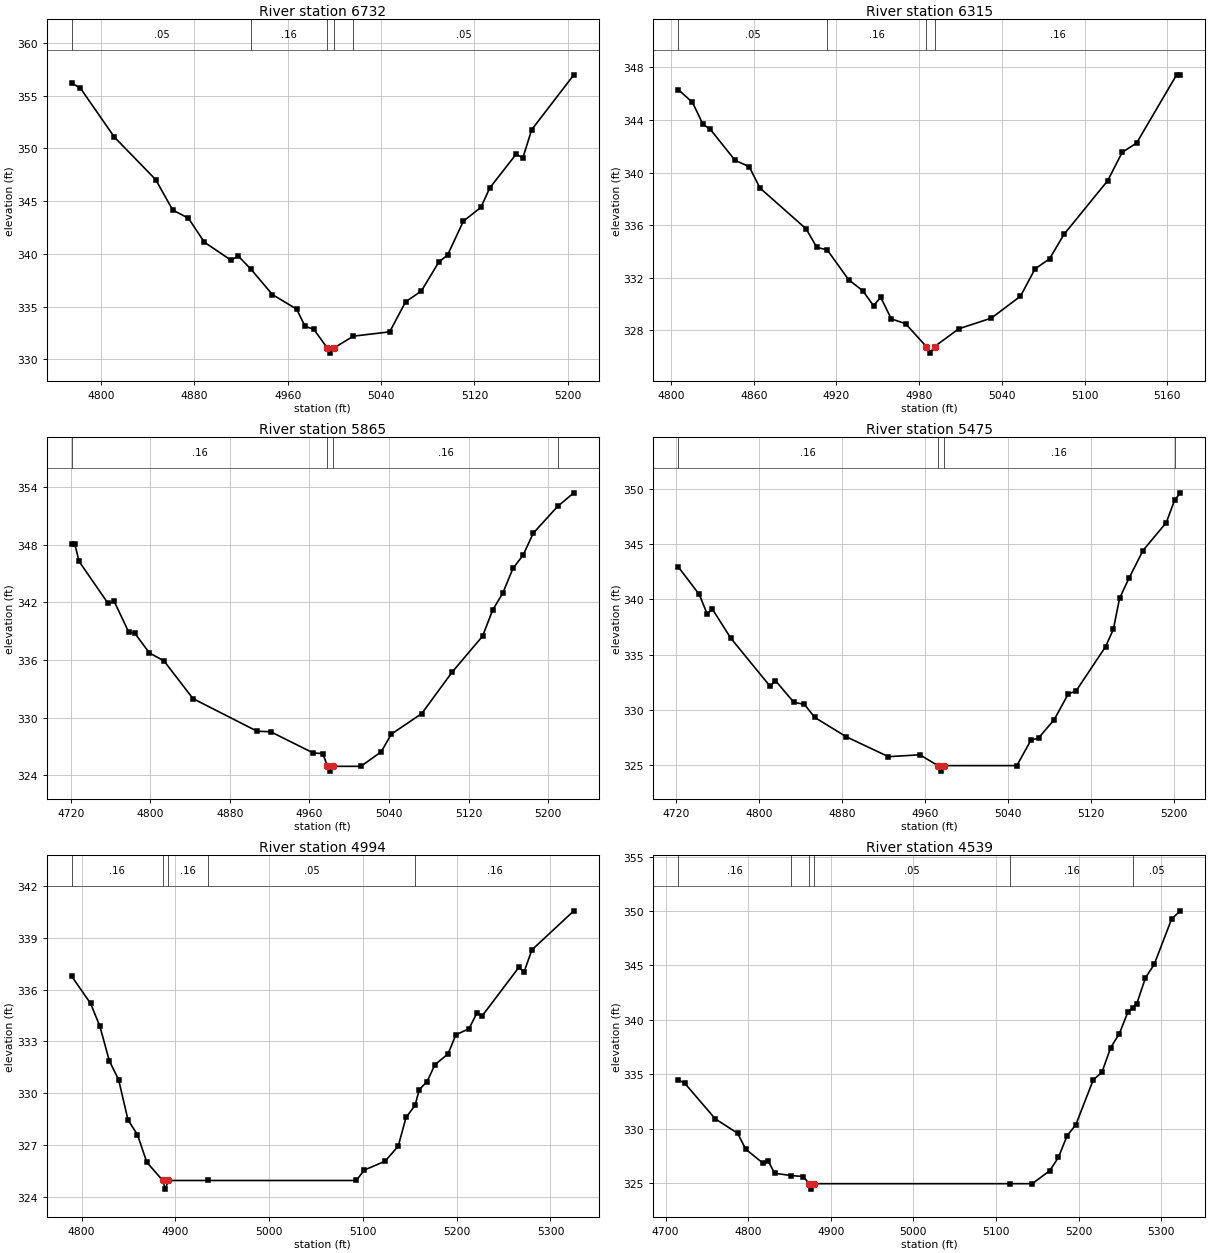
Type RM Length L Ch R = 1,6732,417,417,417
BEGIN DESCRIPTION:
UNT 054 IN CACR 11.0
END DESCRIPTION:
XS GIS Cut Line= 3
      3678449.62     10727210.20      3678299.61     10727010.19
      3678199.60     10726860.18
#Sta/Elev= 30
  4774.9  356.20  4782.2  355.74  4811.4  351.08  4846.8  347.05  4861.4  344.16
  4874.9  343.38  4888.5  341.11  4911.4  339.40  4917.6  339.79  4928.6  338.53
  4946.8  336.14  4967.6  334.76  4974.9  333.11  4982.2  332.86  4993.8  331.08
  4996.5  330.58  4999.8  331.08  5016.2  332.19  5047.4  332.60  5061.0  335.45
  5074.5  336.47  5089.5  339.23  5097.0  339.89  5110.5  343.10  5125.6  344.42
  5133.1  346.25  5155.6  349.44  5161.6  349.14  5169.1  351.79  5205.2  356.99
#Mann=5,-1,0
  4774.9    0.05       0  4928.6    0.16       0  4993.8    0.07       0
  4999.8    0.16       0  5016.2    0.05       0
Bank Sta=4993.8,4999.8
Exp/Cntr=0.3,0.1

Type RM Length L Ch R = 1,6315,450,450,450
BEGIN DESCRIPTION:
UNT 054 IN CACR 10.0
END DESCRIPTION:
XS GIS Cut Line= 3
      3678699.61     10727010.19      3678649.61     10726810.19
      3678599.60     10726660.16
#Sta/Elev= 30
  4805.2  346.30  4815.5  345.33  4823.2  343.65  4828.4  343.29  4846.4  340.93
  4856.7  340.44  4864.5  338.82  4898.0  335.72  4905.7  334.32  4913.3  334.12
  4928.9  331.85  4939.2  331.01  4946.9  329.88  4952.1  330.52  4959.8  328.88
  4970.1  328.52  4985.2  326.78  4987.9  326.28  4991.2  326.78  5008.8  328.13
  5032.4  328.94  5053.5  330.60  5064.1  332.68  5074.6  333.44  5085.1  335.30
  5116.8  339.38  5127.3  341.53  5137.8  342.24  5166.8  347.42  5169.5  347.42
#Mann=4,-1,0
  4805.2    0.05       0  4913.3    0.16       0  4985.2    0.07       0
  4991.2    0.16       0
Bank Sta=4985.2,4991.2
Exp/Cntr=0.3,0.1

Type RM Length L Ch R = 1,5865,390,390,390
BEGIN DESCRIPTION:
UNT 054 IN CACR 9.0
END DESCRIPTION:
XS GIS Cut Line= 3
      3679149.61     10726760.19      3678999.61     10726560.19
      3678949.60     10726310.14
#Sta/Elev= 30
  4720.9  348.06  4724.0  348.06  4728.2  346.28  4757.4  341.90  4763.6  342.10
  4778.2  338.91  4784.4  338.78  4799.0  336.74  4813.6  335.92  4842.8  331.99
  4907.4  328.59  4920.9  328.54  4963.6  326.34  4973.5  326.26  4978.1  324.94
  4980.8  324.44  4984.1  324.94  5011.7  324.94  5032.1  326.45  5042.3  328.29
  5072.9  330.43  5103.5  334.75  5134.1  338.49  5144.3  341.22  5154.5  342.99
  5164.7  345.55  5174.9  346.93  5185.1  349.21  5209.6  352.00  5225.9  353.41
#Mann=4,-1,0
  4720.9    0.16       0  4978.1    0.07       0  4984.1    0.16       0
  5209.6    0.05       0
Bank Sta=4978.1,4984.1
Exp/Cntr=0.3,0.1

Type RM Length L Ch R = 1,5475,481,481,481
BEGIN DESCRIPTION:
UNT 054 IN CACR 8.0
END DESCRIPTION:
XS GIS Cut Line= 3
      3679299.61     10726660.19      3679349.61     10726360.19
      3679199.62     10726260.20
#Sta/Elev= 30
  4721.7  342.95  4742.0  340.45  4749.6  338.68  4754.7  339.11  4772.4  336.49
  4810.4  332.12  4815.5  332.64  4833.2  330.68  4843.4  330.49  4853.5  329.30
  4883.9  327.55  4924.5  325.75  4954.9  325.92  4972.2  324.94  4974.9  324.44
  4978.2  324.94  5048.4  324.94  5061.9  327.23  5069.4  327.45  5084.4  329.10
  5098.0  331.44  5105.5  331.70  5134.0  335.72  5141.5  337.29  5147.5  340.10
  5156.5  341.91  5170.1  344.43  5192.6  346.97  5200.6  349.00  5206.1  349.66
#Mann=4,-1,0
  4721.7    0.16       0  4972.2    0.07       0  4978.2    0.16       0
  5200.6    0.05       0
Bank Sta=4972.2,4978.2
Exp/Cntr=0.3,0.1

Type RM Length L Ch R = 1,4994,455,455,455
BEGIN DESCRIPTION:
UNT 054 IN CACR 7.0
END DESCRIPTION:
XS GIS Cut Line= 3
      3679899.61     10726060.19      3679699.61     10726060.19
      3679399.62     10725910.19
#Sta/Elev= 30
  4789.5  336.76  4809.5  335.20  4819.5  333.87  4829.5  331.88  4839.5  330.77
  4849.5  328.44  4859.5  327.60  4869.5  326.00  4886.5  324.94  4889.2  324.44
  4892.5  324.94  4934.8  324.94  5092.9  324.94  5101.3  325.54  5123.7  326.06
  5137.6  326.93  5146.0  328.60  5155.6  329.29  5160.0  330.20  5168.4  330.67
  5176.8  331.65  5190.7  332.27  5199.1  333.38  5213.1  333.73  5221.5  334.64
  5227.1  334.47  5266.2  337.28  5271.8  337.02  5280.2  338.30  5324.9  340.56
#Mann=5,-1,0
  4789.5    0.16       0  4886.5   0.033       0  4892.5    0.16       0
  4934.8    0.05       0  5155.6    0.16       0
Bank Sta=4886.5,4892.5
Exp/Cntr=0.3,0.1

Type RM Length L Ch R = 1,4539,466,466,466
BEGIN DESCRIPTION:
UNT 054 IN CACR 6.0
END DESCRIPTION:
XS GIS Cut Line= 3
      3679949.62     10725760.20      3679699.61     10725610.19
      3679399.60     10725510.19
#Sta/Elev= 30
  4715.4  334.48  4723.2  334.18  4760.1  330.91  4787.3  329.57  4797.1  328.11
  4818.4  326.80  4824.3  327.04  4832.0  325.90  4851.8  325.69  4867.0  325.60
  4873.7  324.94  4876.5  324.44  4879.7  324.94  5117.6  324.94  5144.0  324.94
  5165.1  326.13  5175.6  327.35  5186.2  329.35  5196.7  330.36  5217.8  334.48
  5228.3  335.18  5238.9  337.44  5249.4  338.73  5259.9  340.75  5265.4  341.13
  5270.5  341.48  5281.0  343.86  5291.6  345.10  5312.7  349.27  5323.2  350.02
#Mann=6,-1,0
  4715.4    0.16       0  4851.8    0.05       0  4873.7   0.033       0
  4879.7    0.05       0  5117.6    0.16       0  5265.4    0.05       0
Bank Sta=4873.7,4879.7
Exp/Cntr=0.3,0.1

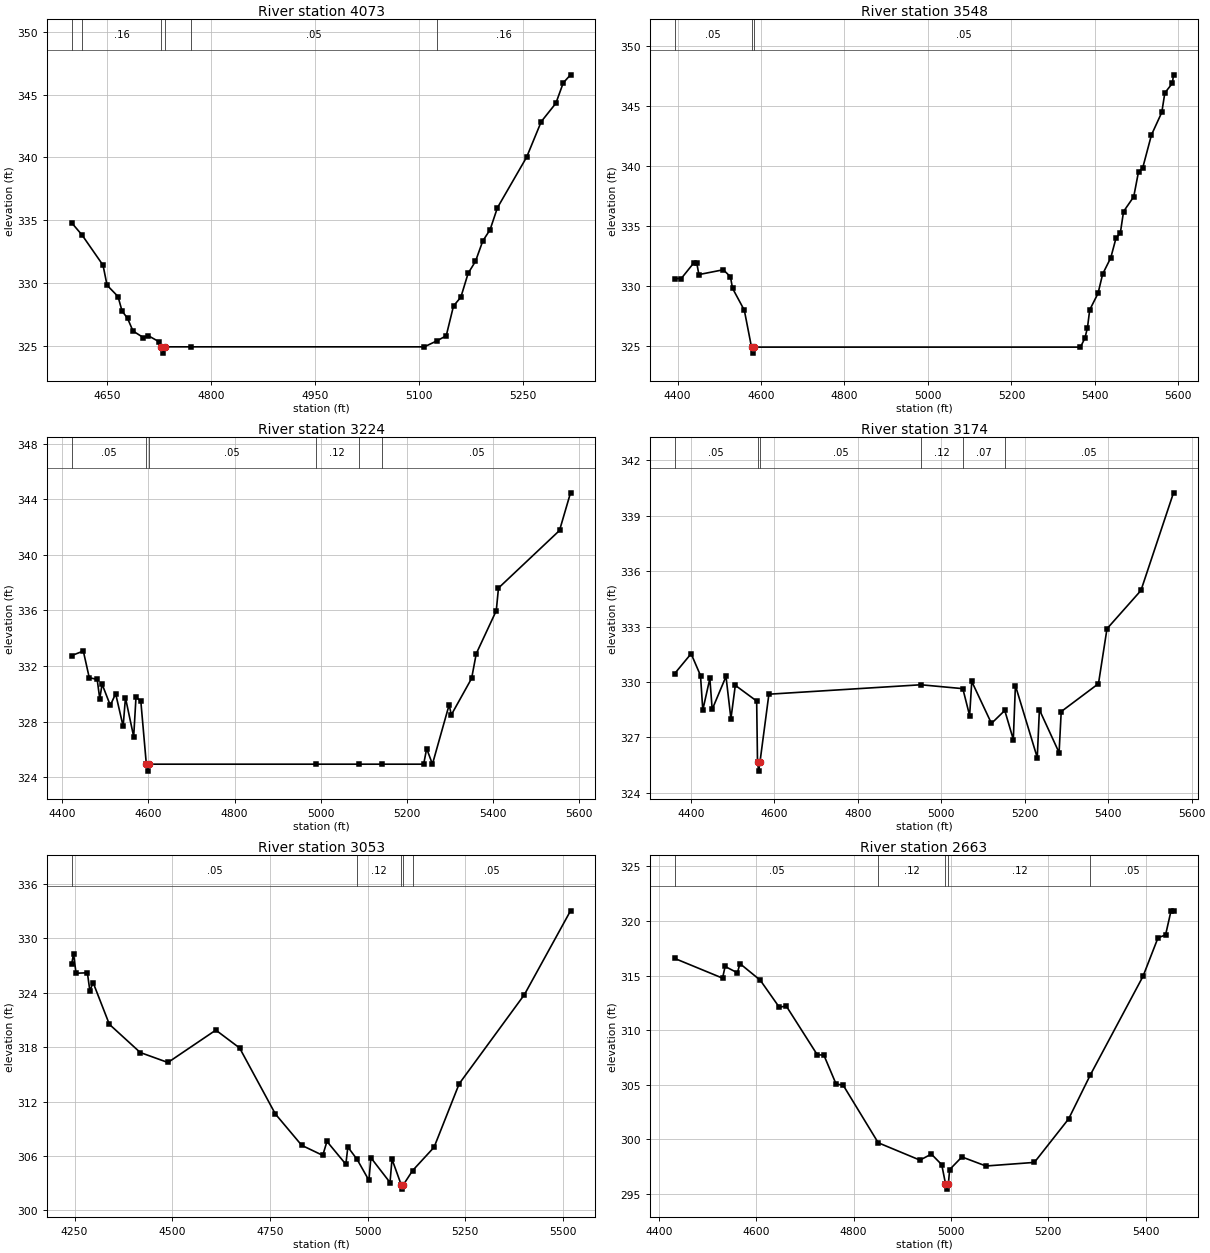
Type RM Length L Ch R = 1,4073,525,525,525
BEGIN DESCRIPTION:
UNT 054 IN CACR 5.0
END DESCRIPTION:
XS GIS Cut Line= 3
      3679999.59     10725510.15      3679799.61     10725160.19
      3679499.60     10725260.19
#Sta/Elev= 30
  4599.4  334.81  4614.6  333.82  4644.7  331.43  4650.5  329.84  4666.3  328.94
  4672.1  327.79  4680.0  327.21  4687.9  326.20  4703.0  325.67  4709.5  325.84
  4725.3  325.35  4728.1  324.94  4730.8  324.44  4734.1  324.94  4771.9  324.94
  5107.9  324.94  5125.8  325.41  5139.5  325.82  5150.0  328.19  5160.6  328.89
  5171.1  330.79  5181.7  331.74  5192.2  333.36  5202.7  334.25  5213.3  336.00
  5255.4  340.02  5276.5  342.85  5297.6  344.31  5308.2  345.93  5318.7  346.57
#Mann=6,-1,0
  4599.4    0.05       0  4614.6    0.16       0  4728.1   0.033       0
  4734.1    0.16       0  4771.9    0.05       0  5125.8    0.16       0
Bank Sta=4728.1,4734.1
Exp/Cntr=0.3,0.1

Type RM Length L Ch R = 1,3548,324,324,324
BEGIN DESCRIPTION:
UNT 054 IN CACR 4.0
END DESCRIPTION:
XS GIS Cut Line= 3
      3680127.78     10725396.01      3680179.87     10724979.30
      3679914.42     10724250.60
#Sta/Elev= 30
  4392.9  330.65  4408.8  330.65  4439.1  331.96  4446.0  331.95  4451.1  330.98
  4509.6  331.38  4526.7  330.80  4531.7  329.84  4560.0  328.01  4577.2  324.94
  4579.9  324.44  4583.2  324.94  5365.3  324.94  5376.0  325.67  5382.3  326.57
  5387.6  328.04  5407.6  329.42  5418.6  331.02  5438.1  332.38  5450.5  334.00
  5461.1  334.46  5468.7  336.23  5493.1  337.46  5504.6  339.55  5514.3  339.82
  5535.6  342.61  5560.4  344.49  5567.6  346.10  5585.7  346.91  5588.4  347.61
#Mann=3,-1,0
  4392.9    0.05       0  4577.2   0.033       0  4583.2    0.05       0
Bank Sta=4577.2,4583.2
Exp/Cntr=0.3,0.1

Type RM Length L Ch R = 1,3224,50,50,50
BEGIN DESCRIPTION:
Mapping XS a0fd69b7
END DESCRIPTION:
XS GIS Cut Line= 3
      3680390.52     10725165.50      3680449.11     10725015.77
      3680262.51     10724035.04
#Sta/Elev= 30
  4421.4  332.75  4448.6  333.08  4462.4  331.16  4480.8  331.04  4486.8  329.64
  4492.2  330.70  4511.3  329.17  4523.7  330.01  4541.1  327.66  4546.5  329.72
  4565.6  326.92  4571.0  329.76  4582.2  329.47  4595.0  324.94  4597.8  324.44
  4601.0  324.94  4988.4  324.94  5089.0  324.94  5143.4  324.94  5239.3  324.94
  5246.3  326.06  5259.7  324.94  5298.5  329.21  5303.6  328.49  5350.7  331.11
  5361.5  332.89  5408.0  335.98  5413.1  337.61  5554.9  341.75  5580.5  344.46
#Mann=6,-1,0
  4421.4    0.05       0  4595.0    0.07       0  4601.0    0.05       0
  4988.4    0.12       0  5089.0    0.07       0  5143.4    0.05       0
Bank Sta=4595,4601
Exp/Cntr=0.3,0.1

Type RM Length L Ch R = 1,3174,121,121,121
BEGIN DESCRIPTION:
Mapping XS b997b6b0
END DESCRIPTION:
XS GIS Cut Line= 3
      3680397.04     10725180.68      3680488.17     10724996.24
      3680304.03     10724023.54
#Sta/Elev= 30
  4360.8  330.45  4400.4  331.53  4422.9  330.35  4428.4  328.48  4445.3  330.19
  4450.9  328.52  4484.0  330.30  4495.8  328.01  4506.3  329.82  4557.5  328.97
  4559.5  325.68  4562.3  325.18  4565.5  325.68  4586.8  329.34  4951.1  329.85
  5051.6  329.64  5067.9  328.18  5073.0  330.03  5120.2  327.76  5152.1  328.46
  5172.6  326.89  5177.6  329.81  5230.0  325.91  5235.1  328.50  5282.3  326.18
  5287.4  328.40  5376.7  329.91  5397.1  332.88  5478.5  334.95  5556.5  340.23
#Mann=6,-1,0
  4360.8    0.05       0  4559.5    0.07       0  4565.5    0.05       0
  4951.1    0.12       0  5051.6    0.07       0  5152.1    0.05       0
Bank Sta=4559.5,4565.5
Exp/Cntr=0.3,0.1

Type RM Length L Ch R = 1,3053,390,390,390
BEGIN DESCRIPTION:
UNT 054 IN CACR 3.0
END DESCRIPTION:
XS GIS Cut Line= 3
      3680429.07     10725185.84      3680583.17     10724981.81
      3680404.45     10723976.36
#Sta/Elev= 30
  4242.3  327.13  4247.3  328.28  4253.6  326.14  4282.7  326.19  4289.0  324.20
  4297.3  325.11  4338.9  320.51  4418.0  317.40  4488.8  316.30  4611.4  319.87
  4672.3  317.90  4763.7  310.63  4831.2  307.17  4885.1  306.06  4895.8  307.60
  4944.2  305.08  4949.3  306.98  4973.1  305.61  5003.2  303.31  5008.3  305.80
  5057.2  303.07  5062.3  305.64  5085.7  302.84  5088.5  302.34  5091.7  302.84
  5115.1  304.39  5170.0  306.96  5234.3  313.96  5401.3  323.79  5519.2  333.02
#Mann=5,-1,0
  4242.3    0.05       0  4973.1    0.12       0  5085.7    0.07       0
  5091.7    0.12       0  5115.1    0.05       0
Bank Sta=5085.7,5091.7
Exp/Cntr=0.3,0.1

Type RM Length L Ch R = 1,2663,537,537,537
BEGIN DESCRIPTION:
Mapping XS e6a56d85
END DESCRIPTION:
XS GIS Cut Line= 3
      3680609.86     10724875.42      3680830.34     10724274.75
      3680628.93     10723946.58
#Sta/Elev= 30
  4432.3  316.57  4530.8  314.76  4536.1  315.83  4561.3  315.25  4566.6  316.09
  4608.3  314.57  4647.4  312.09  4661.6  312.21  4725.5  307.73  4738.9  307.71
  4764.0  305.06  4778.7  304.94  4850.6  299.67  4936.3  298.08  4959.8  298.63
  4981.1  297.66  4988.8  295.92  4991.5  295.42  4994.8  295.92  4997.3  297.21
  5022.5  298.37  5071.9  297.54  5171.4  297.87  5241.8  301.86  5286.5  305.90
  5394.6  314.93  5425.4  318.46  5440.9  318.72  5452.1  320.93  5457.2  320.93
#Mann=5,-1,0
  4432.3    0.05       0  4850.6    0.12       0  4988.8    0.07       0
  4994.8    0.12       0  5286.5    0.05       0
Bank Sta=4988.8,4994.8
Exp/Cntr=0.3,0.1

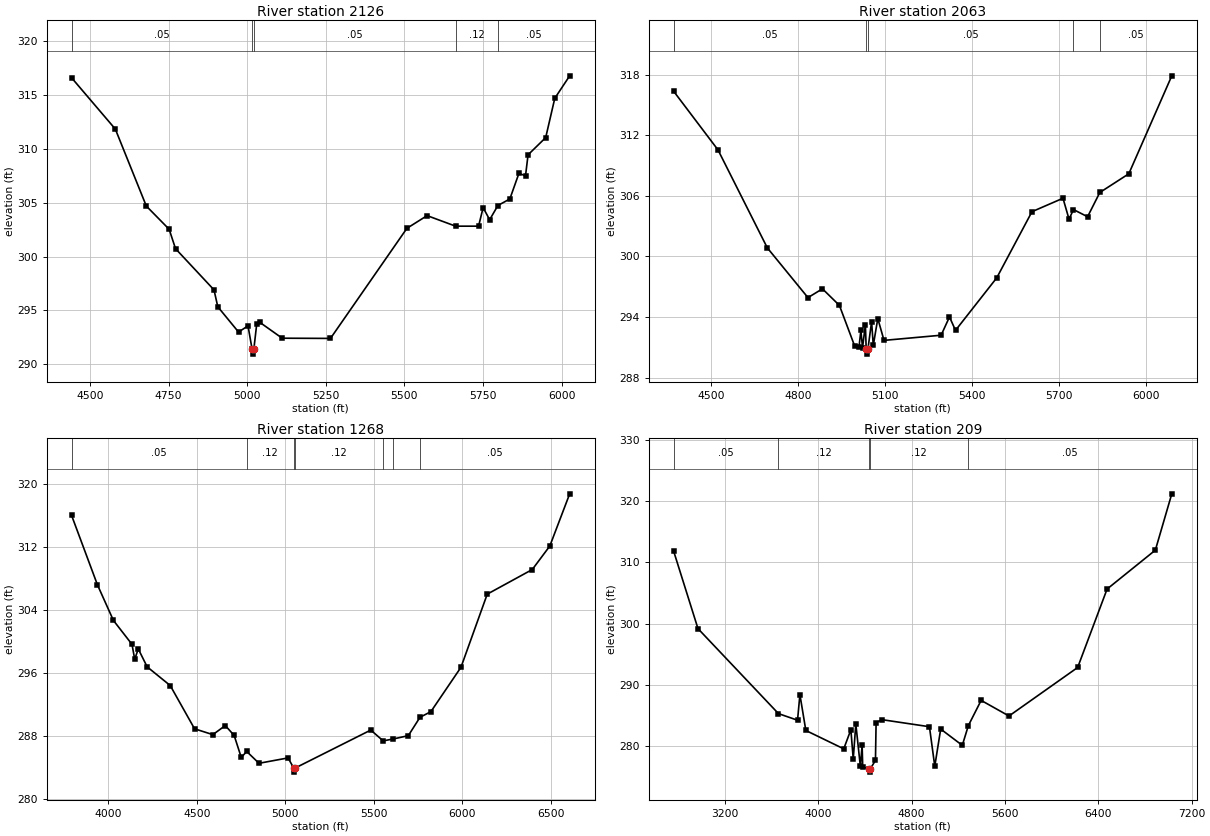
Type RM Length L Ch R = 1,2126,63,63,63
BEGIN DESCRIPTION:
Mapping XS b43e6733
END DESCRIPTION:
XS GIS Cut Line= 4
      3680621.36     10724893.75      3681068.19     10724840.29
      3681259.59     10724510.86      3680796.03     10723917.09
#Sta/Elev= 30
  4441.3  316.61  4580.5  311.84  4679.0  304.69  4751.7  302.53  4771.9  300.73
  4894.3  296.90  4906.4  295.33  4972.4  292.98  5002.5  293.56  5015.2  291.43
  5017.9  290.93  5021.2  291.43  5030.2  293.73  5039.7  293.89  5111.2  292.41
  5264.8  292.39  5507.9  302.62  5572.1  303.80  5662.8  302.82  5735.8  302.82
  5750.3  304.54  5771.1  303.42  5797.3  304.74  5835.3  305.35  5864.3  307.74
  5885.1  307.49  5893.2  309.45  5949.3  311.05  5978.2  314.70  6025.6  316.79
#Mann=5,-1,0
  4441.3    0.05       0  5015.2    0.03       0  5021.2    0.05       0
  5662.8    0.12       0  5797.3    0.05       0
Bank Sta=5015.2,5021.2
Exp/Cntr=0.3,0.1

Type RM Length L Ch R = 1,2063,795,795,795
BEGIN DESCRIPTION:
Mapping XS 31d49c88
END DESCRIPTION:
XS GIS Cut Line= 4
      3680616.81     10724918.84      3681102.91     10724901.48
      3681319.92     10724536.90      3680811.23     10723910.15
#Sta/Elev= 30
  4369.7  316.34  4522.6  310.54  4692.7  300.85  4832.8  295.93  4882.8  296.80
  4941.3  295.16  4993.9  291.14  5008.9  291.04  5015.3  292.69  5021.1  290.98
  5030.9  293.26  5033.7  290.84  5036.4  290.34  5039.7  290.84  5052.3  293.56
  5058.1  291.20  5073.7  293.86  5095.1  291.70  5292.1  292.21  5320.9  294.02
  5341.7  292.69  5484.0  297.89  5605.4  304.43  5712.4  305.76  5733.2  303.69
  5748.6  304.64  5797.2  303.93  5839.4  306.33  5939.4  308.18  6087.6  317.87
#Mann=5,-1,0
  4369.7    0.05       0  5033.7    0.03       0  5039.7    0.05       0
  5748.6    0.12       0  5839.4    0.05       0
Bank Sta=5033.7,5039.7
Exp/Cntr=0.3,0.1

Type RM Length L Ch R = 1,1268,1059,1059,1059
BEGIN DESCRIPTION:
UNT 054 IN CACR 2.0
END DESCRIPTION:
XS GIS Cut Line= 4
      3680623.95     10724946.42      3681752.45     10725041.91
      3681900.02     10724894.34      3680819.29     10723891.74
#Sta/Elev= 30
  3791.3  315.98  3937.5  307.18  4027.8  302.67  4132.8  299.64  4148.2  297.75
  4168.3  299.06  4218.5  296.79  4348.9  294.42  4486.4  288.94  4589.8  288.20
  4660.1  289.35  4710.2  288.10  4750.4  285.31  4781.1  286.07  4850.7  284.57
  5015.0  285.25  5047.3  283.95  5050.1  283.45  5053.3  283.95  5482.5  288.78
  5552.6  287.41  5609.3  287.65  5694.6  288.07  5760.7  290.40  5822.1  291.11
  5992.2  296.73  6140.7  306.00  6395.3  309.12  6494.5  312.10  6606.7  318.71
#Mann=7,-1,0
  3791.3    0.05       0  4781.1    0.12       0  5047.3    0.07       0
  5053.3    0.12       0  5552.6    0.05       0  5609.3    0.12       0
  5760.7    0.05       0
Bank Sta=5047.3,5053.3
Exp/Cntr=0.3,0.1

Type RM Length L Ch R = 1,209,0,0,0
BEGIN DESCRIPTION:
UNT 054 IN CACR 1.0
END DESCRIPTION:
XS GIS Cut Line= 4
      3680674.50     10725052.32      3682372.45     10725354.41
      3682497.45     10724734.62      3680877.62     10723718.97
#Sta/Elev= 30
  2760.3  311.81  2968.6  299.18  3658.2  285.31  3821.8  284.23  3842.1  288.42
  3892.9  282.56  4217.9  279.56  4278.9  282.68  4299.2  277.89  4321.3  283.62
  4360.1  276.72  4375.3  280.15  4380.5  276.57  4438.4  276.26  4441.1  275.76
  4444.4  276.26  4489.6  277.68  4495.1  283.84  4545.9  284.32  4952.2  283.17
  4997.9  276.72  5048.7  282.79  5233.8  280.13  5285.7  283.35  5395.3  287.47
  5634.0  284.92  6222.5  292.84  6474.7  305.64  6888.3  311.99  7029.1  321.18
#Mann=5,-1,0
  2760.3    0.05       0  3658.2    0.12       0  4438.4    0.07       0
  4444.4    0.12       0  5285.7    0.05       0
Bank Sta=4438.4,4444.4
Exp/Cntr=0.3,0.1

Chan Stop Cuts=-1