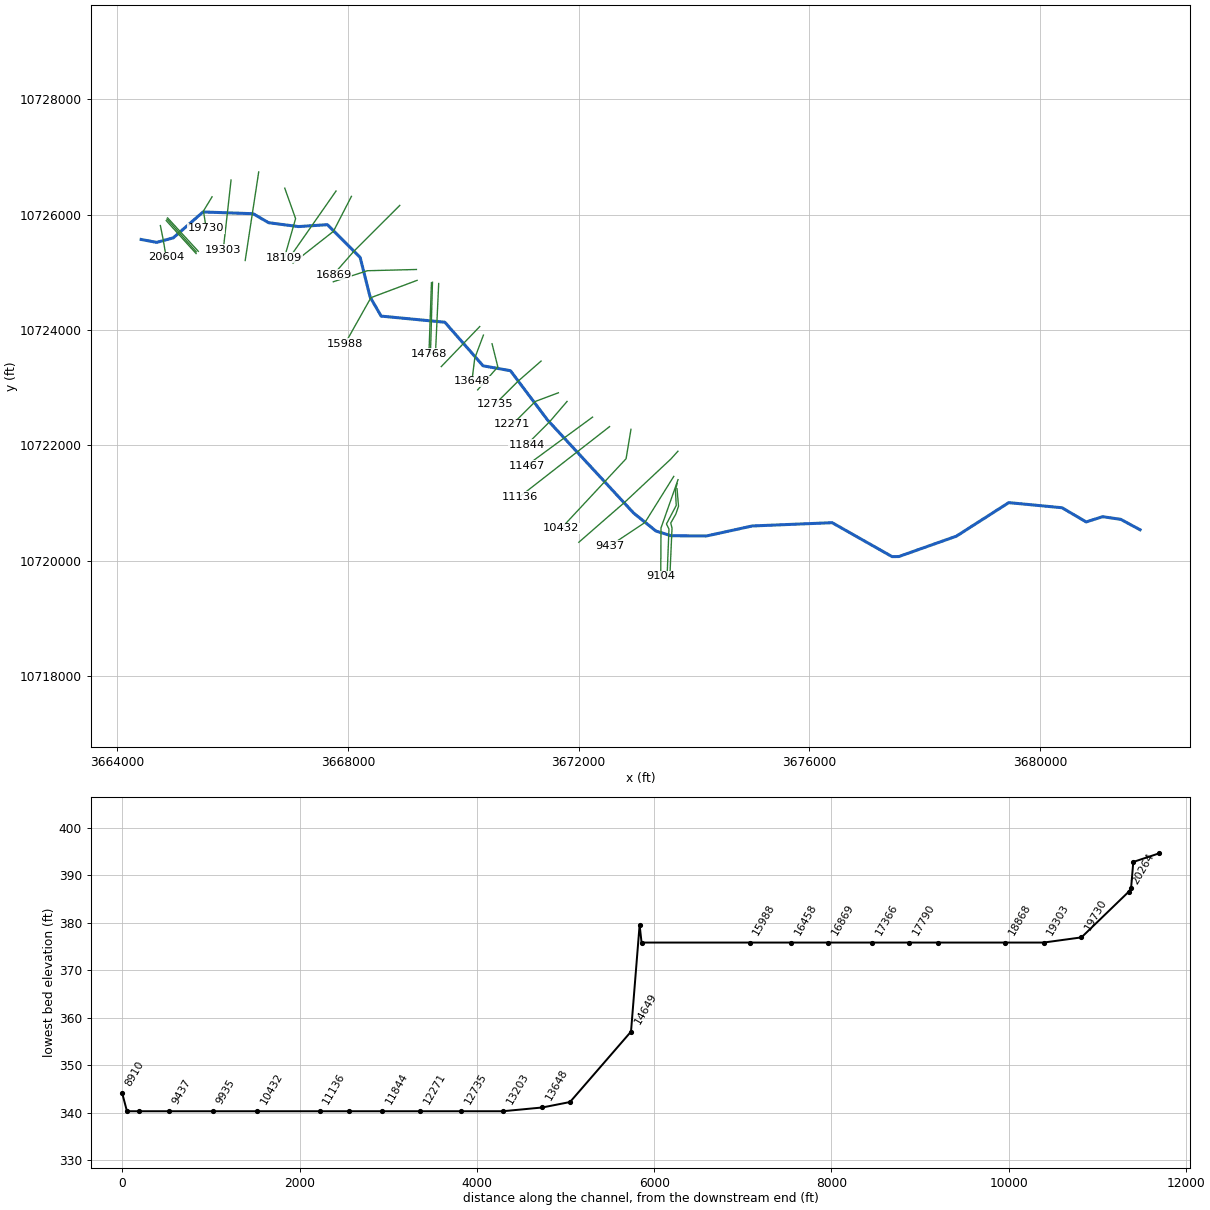
--- UNT 055 IN CACR.prj (project) ---

Proj Title=UNT 055 IN CACR Base Level Engineering
Current Plan=p01
Default Exp/Contr=0.3,0.1
English Units
Geom File=g01
Flow File=f01
Plan File=p01
BEGIN DESCRIPTION:
UNT 055 IN CACR
END DESCRIPTION:

--- UNT 055 IN CACR.p01 (plan) ---

Plan Title=Multiple Run
Short Identifier=Multiple
Geom File=g01
Flow File=f01
Subcritical Flow
K Sum by GR= 0
Std Step Tol= 0.01
Critical Tol= 0.01
Num of Std Step Trials= 20
Max Error Tol= 0.3
Flow Tol Ratio= 0.001
Split Flow NTrial= 30
Split Flow Tol= 0.02
Split Flow Ratio= 0.02
Log Output Level= 0
Friction Slope Method= 1
Unsteady Friction Slope Method= 2
Unsteady Bridges Friction Slope Method= 1
Parabolic Critical Depth
Global Vel Dist=  1 , 1 , 1
Global Log Level= 0
CheckData=True
Encroach Param= -1, 0, 0, 0
BEGIN DESCRIPTION:
Multiple Run
END DESCRIPTION:

--- UNT 055 IN CACR.f01 (steady flow) ---

Flow Title=Multiple
Number of Profiles=7
Profile Names=10-year,25-year,50-year,1pct_min,100-year,1pct_plu,500-year
River Rch & RM= UNT 055 IN CACR,Reach-1,20604
     634     869    1064     957    1294    1751    1919
River Rch & RM= UNT 055 IN CACR,Reach-1,17366
    1140    1612    2016    1848    2499    3379    3849
River Rch & RM= UNT 055 IN CACR,Reach-1,14746
    1506    2154    2715    2505    3388    4582    5291
River Rch & RM= UNT 055 IN CACR,Reach-1,9104
    2573    3782    4856    4558    6164    8336    9969
River Rch & RM= UNT 055 IN CACR,Reach-1,5505
    2668    3912    5014    4696    6351    8589   10228
Boundary for River Rch & Prof#=UNT 055 IN CACR,Reach-1,1
Up Type=0
Dn Type=3
Dn Slope=0.005
Boundary for River Rch & Prof#=UNT 055 IN CACR,Reach-1,2
Up Type=0
Dn Type=3
Dn Slope=0.005
Boundary for River Rch & Prof#=UNT 055 IN CACR,Reach-1,3
Up Type=0
Dn Type=3
Dn Slope=0.005
Boundary for River Rch & Prof#=UNT 055 IN CACR,Reach-1,4
Up Type=0
Dn Type=3
Dn Slope=0.005
Boundary for River Rch & Prof#=UNT 055 IN CACR,Reach-1,5
Up Type=0
Dn Type=3
Dn Slope=0.005
Boundary for River Rch & Prof#=UNT 055 IN CACR,Reach-1,6
Up Type=0
Dn Type=3
Dn Slope=0.005
Boundary for River Rch & Prof#=UNT 055 IN CACR,Reach-1,7
Up Type=0
Dn Type=3
Dn Slope=0.005

--- UNT 055 IN CACR.g01 (geometry) ---

Geom Title=Existing Conditions

River Reach=UNT 055 IN CACR,Reach-1
Reach XY= 30
      3664415.53     10725569.36      3664686.00     10725519.00
      3664972.50     10725597.00      3665489.96     10726046.50
      3666358.00     10726016.00      3666626.25     10725860.00
      3667141.75     10725793.00      3667644.00     10725826.00
      3668213.00     10725257.00      3668386.00     10724570.00
      3668576.75     10724240.00      3669681.25     10724134.00
      3670343.50     10723378.00      3670818.75     10723293.00
      3671461.25     10722438.00      3672952.50     10720825.00
      3673341.25     10720512.00      3673602.75     10720431.00
      3674214.75     10720426.00      3675009.75     10720600.00
      3676395.00     10720657.00      3677435.00     10720068.00
      3677552.00     10720070.00      3678549.00     10720423.00
      3679457.00     10721005.00      3680380.75     10720916.00
      3680799.00     10720670.00      3681083.75     10720761.00
      3681398.50     10720715.00      3681733.25     10720534.00

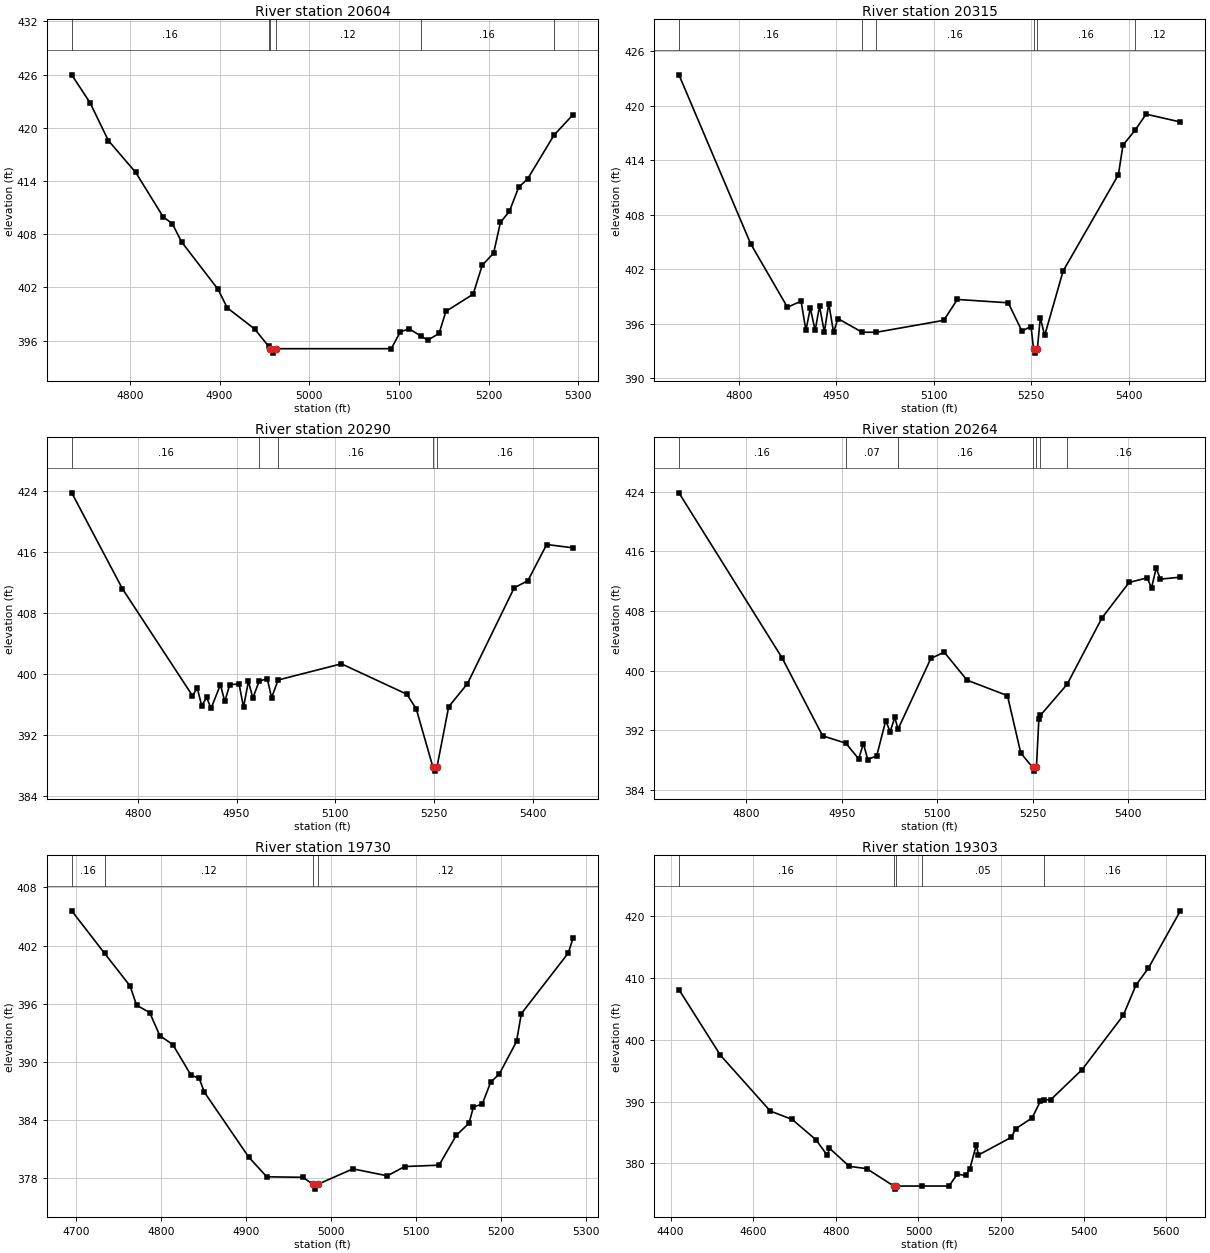
Type RM Length L Ch R = 1,20604,289,289,289
BEGIN DESCRIPTION:
UNT 055 IN CACR 44.0
END DESCRIPTION:
XS GIS Cut Line= 3
      3664749.61     10725810.19      3664799.61     10725560.19
      3664849.61     10725260.18
#Sta/Elev= 30
  4735.1  425.98  4755.5  422.83  4775.9  418.57  4806.5  414.96  4837.1  409.95
  4847.3  409.18  4857.5  407.14  4898.3  401.77  4908.5  399.69  4939.1  397.30
  4954.6  395.35  4956.5  395.08  4959.2  394.58  4962.5  395.08  5091.4  395.08
  5101.6  397.01  5111.7  397.30  5124.3  396.52  5132.0  396.04  5144.7  396.80
  5152.3  399.29  5182.7  401.23  5192.8  404.49  5205.5  405.86  5213.1  409.32
  5223.2  410.60  5233.4  413.28  5243.5  414.25  5272.8  419.17  5294.2  421.50
#Mann=6,-1,0
  4735.1    0.16       0  4954.6    0.12       0  4956.5    0.07       0
  4962.5    0.12       0  5124.3    0.16       0  5272.8    0.12       0
Bank Sta=4956.5,4962.5
Exp/Cntr=0.3,0.1

Type RM Length L Ch R = 1,20315,25,25,25
BEGIN DESCRIPTION:
Mapping XS f838420c
END DESCRIPTION:
XS GIS Cut Line= 2
      3664850.63     10725897.11      3665368.81     10725324.72
#Sta/Elev= 30
  4707.5  423.42  4817.9  404.83  4874.6  397.83  4895.6  398.50  4903.0  395.28
  4909.8  397.74  4917.2  395.28  4924.0  397.95  4931.4  395.08  4938.2  398.24
  4945.6  395.08  4952.4  396.58  4989.6  395.08  5011.7  395.08  5115.3  396.39
  5136.2  398.69  5214.6  398.32  5235.6  395.22  5249.7  395.71  5253.5  393.28
  5256.2  392.78  5259.5  393.28  5263.9  396.68  5270.7  394.73  5299.1  401.82
  5384.2  412.42  5391.3  415.68  5410.0  417.33  5426.8  419.09  5479.6  418.23
#Mann=6,-1,0
  4707.5    0.16       0  4989.6    0.05       0  5011.7    0.16       0
  5253.5   0.033       0  5259.5    0.16       0  5410.0    0.12       0
Bank Sta=5253.5,5259.5
Exp/Cntr=0.3,0.1

Type RM Length L Ch R = 1,20290,26,26,26
BEGIN DESCRIPTION:
Mapping XS 7a658525
END DESCRIPTION:
XS GIS Cut Line= 2
      3664863.65     10725923.14      3665371.18     10725354.89
#Sta/Elev= 30
  4699.6  423.75  4776.7  411.16  4882.9  397.17  4890.4  398.12  4897.1  395.84
  4904.6  396.92  4911.3  395.48  4925.5  398.59  4932.2  396.39  4939.7  398.60
  4953.9  398.68  4960.6  395.63  4968.1  399.04  4974.8  396.84  4984.3  399.03
  4996.6  399.40  5003.3  396.89  5013.2  399.21  5109.4  401.33  5208.9  397.34
  5223.1  395.42  5248.5  387.76  5251.3  387.26  5254.5  387.76  5272.4  395.71
  5300.9  398.73  5371.9  411.29  5392.8  412.24  5421.2  416.97  5461.5  416.54
#Mann=5,-1,0
  4699.6    0.16       0  4984.3    0.07       0  5013.2    0.16       0
  5248.5    0.07       0  5254.5    0.16       0
Bank Sta=5248.5,5254.5
Exp/Cntr=0.3,0.1

Type RM Length L Ch R = 1,20264,534,534,534
BEGIN DESCRIPTION:
UNT 055 IN CACR 43.0
END DESCRIPTION:
XS GIS Cut Line= 2
      3664874.50     10725944.13      3665407.16     10725363.83
#Sta/Elev= 30
  4694.1  423.87  4856.2  401.71  4919.8  391.26  4956.2  390.27  4976.5  388.17
  4983.9  390.22  4990.7  388.08  5004.8  388.56  5019.0  393.31  5025.8  391.80
  5033.2  393.73  5038.3  392.15  5089.9  401.65  5110.9  402.48  5146.7  398.73
  5210.2  396.65  5231.1  388.96  5249.7  387.02  5252.5  386.52  5255.7  387.02
  5259.5  393.45  5261.9  394.00  5303.9  398.17  5358.8  407.10  5401.3  411.84
  5429.7  412.46  5436.5  411.10  5443.8  413.75  5450.6  412.29  5481.8  412.55
#Mann=7,-1,0
  4694.1    0.16       0  4956.2    0.07       0  5038.3    0.16       0
  5249.7    0.07       0  5255.7    0.16       0  5261.9    0.12       0
  5303.9    0.16       0
Bank Sta=5249.7,5255.7
Exp/Cntr=0.3,0.1

Type RM Length L Ch R = 1,19730,427,427,427
BEGIN DESCRIPTION:
Mapping XS e7462bf9
END DESCRIPTION:
XS GIS Cut Line= 3
      3665645.15     10726308.85      3665495.83     10726062.29
      3665544.31     10725764.46
#Sta/Elev= 30
  4695.0  405.59  4733.7  401.20  4763.6  397.85  4771.3  395.86  4786.8  395.09
  4798.6  392.72  4814.0  391.79  4835.4  388.63  4845.0  388.32  4850.9  386.91
  4903.2  380.20  4924.5  378.16  4967.2  378.11  4978.6  377.39  4981.3  376.89
  4984.6  377.39  5025.9  378.98  5066.4  378.26  5086.7  379.22  5127.2  379.36
  5147.5  382.44  5162.5  383.69  5167.7  385.38  5177.9  385.64  5188.0  387.92
  5198.1  388.76  5218.4  392.12  5224.0  394.98  5279.2  401.23  5285.0  402.80
#Mann=4,-1,0
  4695.0    0.16       0  4733.7    0.12       0  4978.6    0.07       0
  4984.6    0.12       0
Bank Sta=4978.6,4984.6
Exp/Cntr=0.3,0.1

Type RM Length L Ch R = 1,19303,435,435,435
BEGIN DESCRIPTION:
Mapping XS ce879919
END DESCRIPTION:
XS GIS Cut Line= 2
      3665974.90     10726600.13      3665839.67     10725393.49
#Sta/Elev= 30
  4420.0  408.13  4520.6  397.49  4641.3  388.45  4694.3  387.09  4752.0  383.79
  4779.5  381.25  4784.5  382.43  4832.5  379.49  4874.7  379.12  4940.2  376.30
  4943.0  375.80  4946.2  376.30  5008.0  376.30  5074.0  376.30  5094.1  378.23
  5114.3  378.01  5124.3  379.05  5140.2  383.01  5145.2  381.33  5225.0  384.20
  5235.4  385.58  5275.3  387.34  5295.4  390.07  5305.2  390.27  5320.5  390.30
  5396.0  395.15  5495.8  403.94  5526.8  408.87  5557.0  411.63  5634.2  420.90
#Mann=5,-1,0
  4420.0    0.16       0  4940.2    0.07       0  4946.2    0.16       0
  5008.0    0.05       0  5305.2    0.16       0
Bank Sta=4940.2,4946.2
Exp/Cntr=0.3,0.1

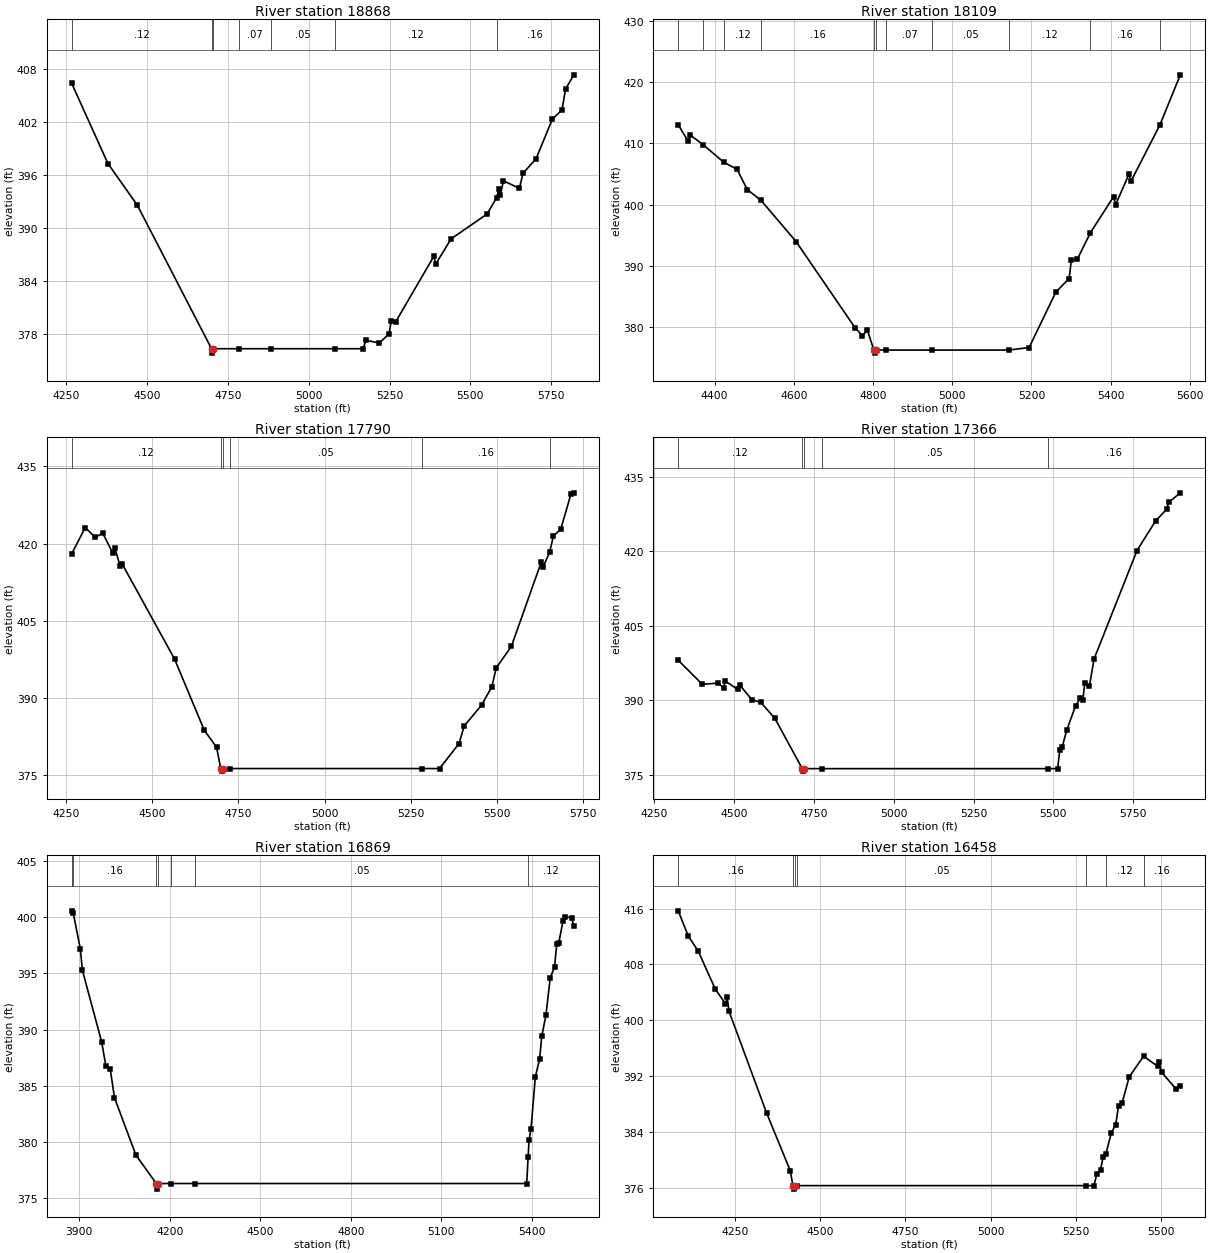
Type RM Length L Ch R = 1,18868,759,759,759
BEGIN DESCRIPTION:
Mapping XS 4fa37311
END DESCRIPTION:
XS GIS Cut Line= 2
      3666454.06     10726740.76      3666219.75     10725204.72
#Sta/Elev= 30
  4266.5  406.33  4378.3  397.27  4469.4  392.55  4699.0  376.30  4701.8  375.80
  4705.0  376.30  4783.1  376.30  4882.9  376.30  5082.4  376.30  5167.4  376.30
  5177.5  377.25  5217.9  376.95  5248.3  377.97  5255.5  379.49  5268.5  379.32
  5387.5  386.79  5392.6  385.87  5440.5  388.74  5551.8  391.55  5581.2  393.39
  5588.2  394.35  5593.2  393.76  5602.3  395.31  5651.7  394.46  5663.0  396.16
  5703.5  397.82  5754.1  402.32  5783.7  403.33  5794.5  405.69  5820.3  407.31
#Mann=7,-1,0
  4266.5    0.12       0  4699.0   0.033       0  4705.0    0.12       0
  4783.1    0.07       0  4882.9    0.05       0  5082.4    0.12       0
  5581.2    0.16       0
Bank Sta=4699,4705
Exp/Cntr=0.3,0.1

Type RM Length L Ch R = 1,18109,319,319,319
BEGIN DESCRIPTION:
UNT 055 IN CACR 39.0
END DESCRIPTION:
XS GIS Cut Line= 3
      3666906.04     10726458.59      3667093.54     10725930.82
      3666899.08     10725250.24
#Sta/Elev= 30
  4308.0  413.04  4333.2  410.36  4338.5  411.36  4370.4  409.83  4423.1  406.93
  4456.6  405.78  4482.2  402.49  4517.1  400.72  4605.6  394.00  4754.6  379.93
  4773.2  378.64  4785.4  379.58  4802.1  376.30  4804.8  375.80  4808.1  376.30
  4833.6  376.30  4949.9  376.30  5142.7  376.30  5194.1  376.71  5261.7  385.77
  5295.1  387.96  5300.7  390.97  5315.9  391.13  5348.9  395.44  5407.3  401.32
  5412.5  400.03  5446.3  404.99  5451.5  403.85  5524.5  413.05  5575.9  421.20
#Mann=11,-1,0
  4308.0    0.12       0  4370.4    0.16       0  4423.1    0.12       0
  4517.1    0.16       0  4802.1   0.033       0  4808.1    0.16       0
  4833.6    0.07       0  4949.9    0.05       0  5142.7    0.12       0
  5348.9    0.16       0  5524.5    0.12       0
Bank Sta=4802.1,4808.1
Exp/Cntr=0.3,0.1

Type RM Length L Ch R = 1,17790,424,424,424
BEGIN DESCRIPTION:
UNT 055 IN CACR 38.0
END DESCRIPTION:
XS GIS Cut Line= 2
      3667794.92     10726409.98      3666961.60     10725215.55
#Sta/Elev= 30
  4266.4  418.07  4305.4  423.11  4335.0  421.23  4356.0  422.07  4385.6  418.14
  4391.7  419.11  4406.6  415.61  4412.7  416.05  4564.5  397.59  4650.8  383.74
  4686.6  380.41  4698.4  376.30  4701.2  375.80  4704.4  376.30  4726.3  376.30
  5282.9  376.30  5333.1  376.30  5389.7  381.14  5404.6  384.56  5455.2  388.64
  5484.9  392.18  5497.7  395.88  5541.6  400.04  5627.9  416.35  5634.0  415.51
  5652.2  418.30  5663.7  421.51  5684.6  422.77  5714.3  429.60  5722.8  429.88
#Mann=6,-1,0
  4266.4    0.12       0  4698.4   0.033       0  4704.4    0.12       0
  4726.3    0.05       0  5282.9    0.16       0  5652.2    0.12       0
Bank Sta=4698.4,4704.4
Exp/Cntr=0.3,0.1

Type RM Length L Ch R = 1,17366,497,497,497
BEGIN DESCRIPTION:
UNT 055 IN CACR 37.0
END DESCRIPTION:
XS GIS Cut Line= 3
      3668061.69     10726317.13      3667749.61     10725710.19
      3667049.61     10725160.19
#Sta/Elev= 30
  4325.1  398.09  4400.4  393.26  4450.5  393.50  4467.0  392.52  4472.6  393.91
  4511.4  392.22  4517.0  393.16  4555.7  390.18  4583.5  389.64  4627.9  386.40
  4713.6  376.30  4716.3  375.80  4719.6  376.30  4774.2  376.30  5483.8  376.30
  5513.7  376.30  5520.0  380.02  5528.1  380.69  5541.7  383.99  5569.7  388.92
  5584.2  390.43  5592.3  390.03  5598.7  393.57  5613.1  392.92  5627.6  398.35
  5762.2  420.15  5820.1  426.08  5855.3  428.46  5861.7  429.84  5897.8  431.75
#Mann=5,-1,0
  4325.1    0.12       0  4713.6   0.033       0  4719.6    0.12       0
  4774.2    0.05       0  5483.8    0.16       0
Bank Sta=4713.6,4719.6
Exp/Cntr=0.3,0.1

Type RM Length L Ch R = 1,16869,411,411,411
BEGIN DESCRIPTION:
UNT 055 IN CACR 36.0
END DESCRIPTION:
XS GIS Cut Line= 3
      3668899.64     10726160.22      3668099.61     10725360.19
      3667749.62     10724960.20
#Sta/Elev= 30
  3875.8  400.57  3880.8  400.36  3904.1  397.18  3911.2  395.26  3974.8  388.90
  3989.0  386.72  4003.1  386.49  4017.3  383.94  4088.0  378.84  4155.7  376.30
  4158.4  375.80  4161.7  376.30  4205.8  376.30  4285.0  376.30  5382.6  376.30
  5387.2  378.62  5390.2  380.14  5396.8  381.13  5411.1  385.79  5425.3  387.38
  5432.4  389.40  5446.2  391.27  5460.4  394.59  5474.7  395.57  5482.2  397.63
  5488.9  397.74  5503.1  399.70  5510.7  400.02  5531.6  399.96  5538.7  399.18
#Mann=7,-1,0
  3875.8    0.07       0  3880.8    0.16       0  4155.7   0.033       0
  4161.7    0.16       0  4205.8    0.07       0  4285.0    0.05       0
  5387.2    0.12       0
Bank Sta=4155.7,4161.7
Exp/Cntr=0.3,0.1

Type RM Length L Ch R = 1,16458,470,470,470
BEGIN DESCRIPTION:
UNT 055 IN CACR 35.0
END DESCRIPTION:
XS GIS Cut Line= 3
      3669188.28     10725048.84      3668337.55     10725027.14
      3667747.28     10724836.17
#Sta/Elev= 30
  4084.2  415.69  4112.9  412.14  4142.9  409.90  4192.9  404.45  4222.7  402.37
  4227.7  403.30  4232.9  401.31  4343.0  386.74  4413.0  378.38  4420.0  376.30
  4422.7  375.80  4426.0  376.30  4432.1  376.30  5279.8  376.30  5302.5  376.30
  5311.4  378.04  5321.9  378.59  5329.3  380.40  5337.3  380.80  5353.5  383.89
  5366.5  385.06  5374.5  387.77  5385.0  388.18  5406.0  391.90  5448.0  394.85
  5489.3  393.40  5494.6  393.96  5500.6  392.57  5542.6  390.18  5555.6  390.56
#Mann=7,-1,0
  4084.2    0.16       0  4420.0   0.033       0  4426.0    0.16       0
  4432.1    0.05       0  5279.8    0.16       0  5337.3    0.12       0
  5448.0    0.16       0
Bank Sta=4420,4426
Exp/Cntr=0.3,0.1

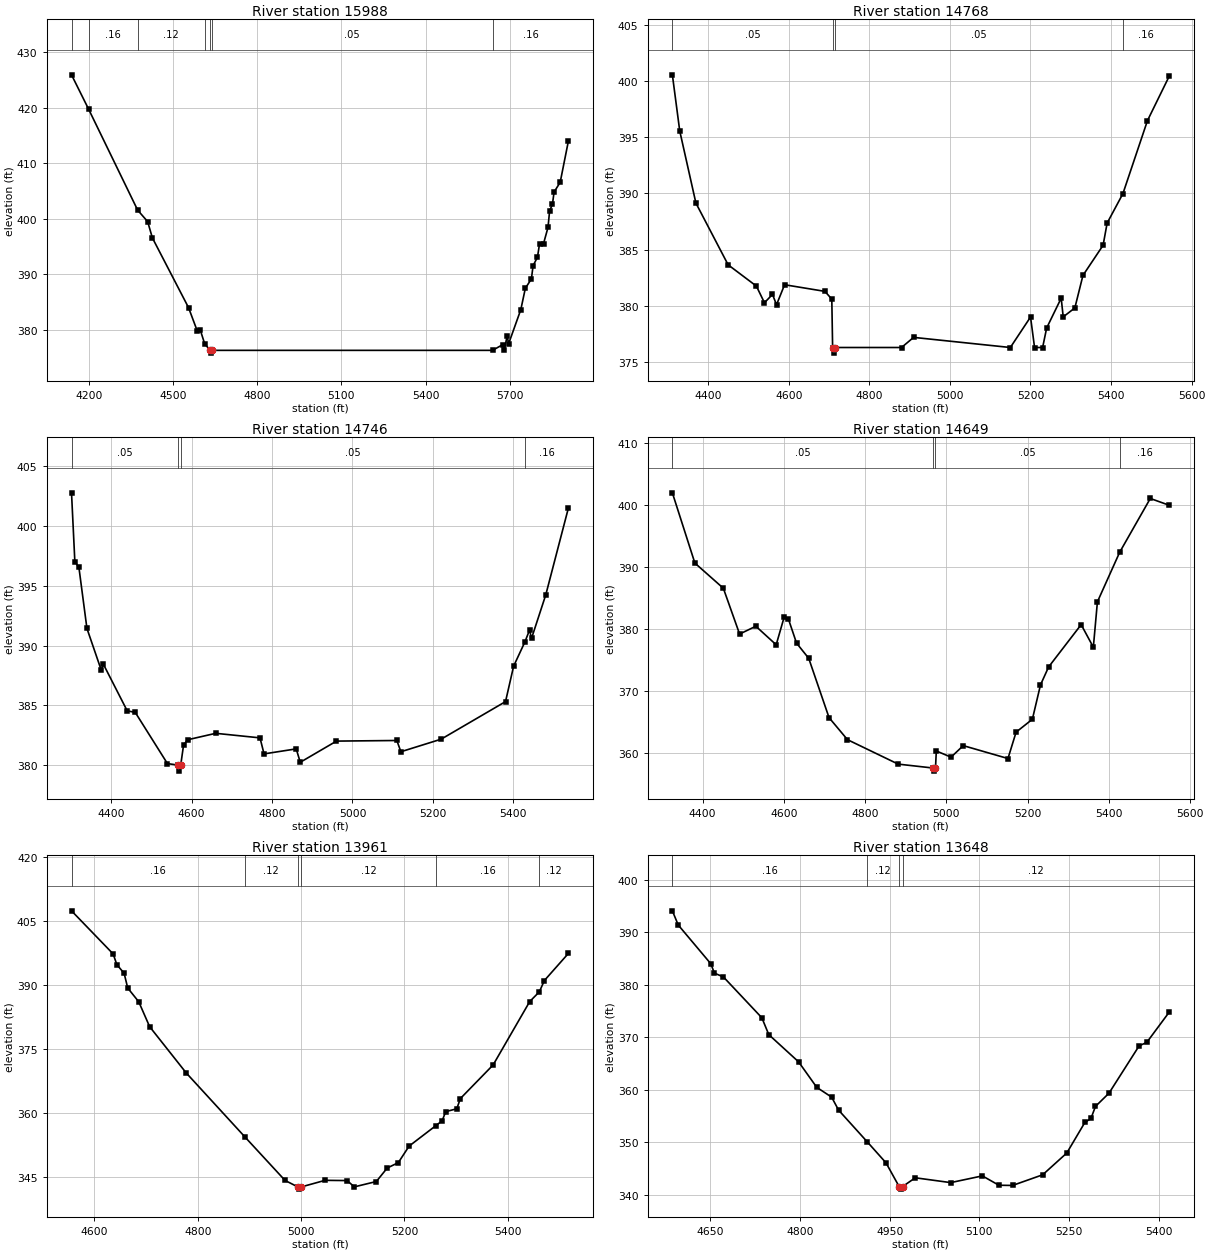
Type RM Length L Ch R = 1,15988,1220,1220,1220
BEGIN DESCRIPTION:
UNT 055 IN CACR 34.0
END DESCRIPTION:
XS GIS Cut Line= 3
      3669199.62     10724860.19      3668399.61     10724560.19
      3667949.61     10723760.18
#Sta/Elev= 30
  4137.6  425.94  4198.8  419.73  4373.5  401.56  4409.1  399.50  4426.0  396.56
  4555.0  383.99  4586.2  379.77  4596.9  379.95  4612.5  377.48  4632.1  376.30
  4634.9  375.80  4638.1  376.30  5639.1  376.30  5675.0  377.32  5680.7  376.30
  5690.9  378.85  5696.7  377.53  5740.0  383.66  5756.0  387.48  5777.6  389.17
  5783.7  391.56  5799.3  393.09  5806.6  395.47  5821.0  395.55  5836.9  398.46
  5842.6  401.45  5852.5  402.58  5858.6  404.83  5880.3  406.58  5909.9  414.10
#Mann=7,-1,0
  4137.6    0.05       0  4198.8    0.16       0  4373.5    0.12       0
  4612.5    0.05       0  4632.1   0.033       0  4638.1    0.05       0
  5639.1    0.16       0
Bank Sta=4632.1,4638.1
Exp/Cntr=0.3,0.1

Type RM Length L Ch R = 1,14768,22,22,22
BEGIN DESCRIPTION:
UNT 055 IN CACR 33.0
END DESCRIPTION:
XS GIS Cut Line= 2
      3669448.61     10724818.52      3669405.20     10723585.88
#Sta/Elev= 30
  4311.2  400.54  4329.5  395.55  4369.6  389.14  4449.6  383.65  4519.7  381.76
  4539.7  380.28  4559.7  381.02  4569.7  380.10  4589.7  381.88  4689.8  381.29
  4706.9  380.60  4708.9  376.30  4711.6  375.80  4714.9  376.30  4879.9  376.30
  4909.9  377.20  5150.0  376.30  5200.1  379.01  5210.1  376.30  5230.1  376.30
  5240.1  378.03  5276.2  380.69  5281.2  379.02  5310.1  379.82  5330.2  382.71
  5380.2  385.39  5390.2  387.36  5429.4  389.98  5490.3  396.47  5544.6  400.44
#Mann=4,-1,0
  4311.2    0.05       0  4708.9    0.03       0  4714.9    0.05       0
  5429.4    0.16       0
Bank Sta=4708.9,4714.9
Exp/Cntr=0.3,0.1

Type RM Length L Ch R = 1,14746,97,97,97
BEGIN DESCRIPTION:
UNT 055 IN CACR 32.0
END DESCRIPTION:
XS GIS Cut Line= 2
      3669466.70     10724828.51      3669432.02     10723593.80
#Sta/Elev= 30
  4301.7  402.77  4310.0  397.01  4320.0  396.56  4340.0  391.44  4375.7  387.94
  4380.7  388.46  4440.1  384.55  4460.1  384.42  4540.1  380.14  4567.1  380.01
  4569.9  379.51  4573.1  380.01  4580.1  381.67  4590.1  382.13  4660.2  382.67
  4770.2  382.29  4780.2  380.95  4860.2  381.37  4870.2  380.25  4960.3  382.02
  5110.3  382.07  5120.3  381.13  5220.4  382.18  5380.4  385.32  5400.5  388.28
  5428.6  390.31  5440.1  391.30  5445.1  390.61  5480.5  394.25  5536.9  401.53
#Mann=4,-1,0
  4301.7    0.05       0  4567.1    0.03       0  4573.1    0.05       0
  5428.6    0.16       0
Bank Sta=4567.1,4573.1
Exp/Cntr=0.3,0.1

Type RM Length L Ch R = 1,14649,688,688,688
BEGIN DESCRIPTION:
UNT 055 IN CACR 31.0
END DESCRIPTION:
XS GIS Cut Line= 2
      3669574.48     10724805.52      3669518.13     10723583.31
#Sta/Elev= 30
  4325.7  401.89  4381.1  390.57  4451.2  386.51  4491.2  379.13  4531.2  380.39
  4581.3  377.40  4601.3  381.95  4611.3  381.57  4631.4  377.67  4661.4  375.22
  4711.4  365.66  4756.8  362.11  4881.6  358.17  4967.5  357.54  4970.2  357.04
  4973.5  357.54  4975.5  360.29  5011.8  359.29  5041.8  361.15  5151.9  359.07
  5171.9  363.32  5212.0  365.40  5232.0  370.94  5252.0  373.83  5332.1  380.65
  5362.1  377.01  5372.1  384.32  5426.9  392.31  5502.3  400.98  5549.2  399.88
#Mann=4,-1,0
  4325.7    0.05       0  4967.5    0.03       0  4973.5    0.05       0
  5426.9    0.16       0
Bank Sta=4967.5,4973.5
Exp/Cntr=0.3,0.1

Type RM Length L Ch R = 1,13961,313,313,313
BEGIN DESCRIPTION:
UNT 055 IN CACR 30.0
END DESCRIPTION:
XS GIS Cut Line= 2
      3670285.41     10724058.36      3669619.33     10723364.53
#Sta/Elev= 30
  4555.6  407.31  4636.2  397.22  4643.3  394.73  4657.4  392.70  4664.4  389.25
  4685.7  386.04  4706.8  380.21  4777.6  369.39  4890.8  354.47  4968.8  344.25
  4993.8  342.71  4996.5  342.21  4999.8  342.71  5046.4  344.27  5088.9  344.21
  5103.0  342.74  5145.5  343.99  5166.6  347.15  5188.0  348.40  5209.0  352.28
  5260.8  357.07  5272.9  358.20  5279.8  360.34  5301.2  361.00  5308.1  363.39
  5371.6  371.27  5442.4  386.09  5461.0  388.37  5470.7  391.00  5517.4  397.37
#Mann=6,-1,0
  4555.6    0.16       0  4890.8    0.12       0  4993.8    0.07       0
  4999.8    0.12       0  5260.8    0.16       0  5461.0    0.12       0
Bank Sta=4993.8,4999.8
Exp/Cntr=0.3,0.1

Type RM Length L Ch R = 1,13648,445,445,445
BEGIN DESCRIPTION:
UNT 055 IN CACR 29.0
END DESCRIPTION:
XS GIS Cut Line= 3
      3670349.61     10723910.19      3670199.61     10723510.19
      3670149.61     10723110.21
#Sta/Elev= 30
  4587.0  394.04  4596.8  391.34  4651.1  383.98  4657.3  382.18  4672.4  381.44
  4736.5  373.68  4748.1  370.47  4797.9  365.29  4828.2  360.44  4853.1  358.57
  4864.7  356.10  4913.0  350.01  4943.9  346.07  4965.8  341.56  4968.6  341.06
  4971.8  341.56  4992.8  343.22  5052.0  342.30  5104.9  343.58  5132.6  341.80
  5155.3  341.76  5205.7  343.79  5246.0  347.94  5276.2  353.76  5286.3  354.51
  5293.9  356.81  5316.5  359.33  5366.9  368.35  5379.5  368.98  5417.3  374.79
#Mann=4,-1,0
  4587.0    0.16       0  4913.0    0.12       0  4965.8    0.07       0
  4971.8    0.12       0
Bank Sta=4965.8,4971.8
Exp/Cntr=0.3,0.1

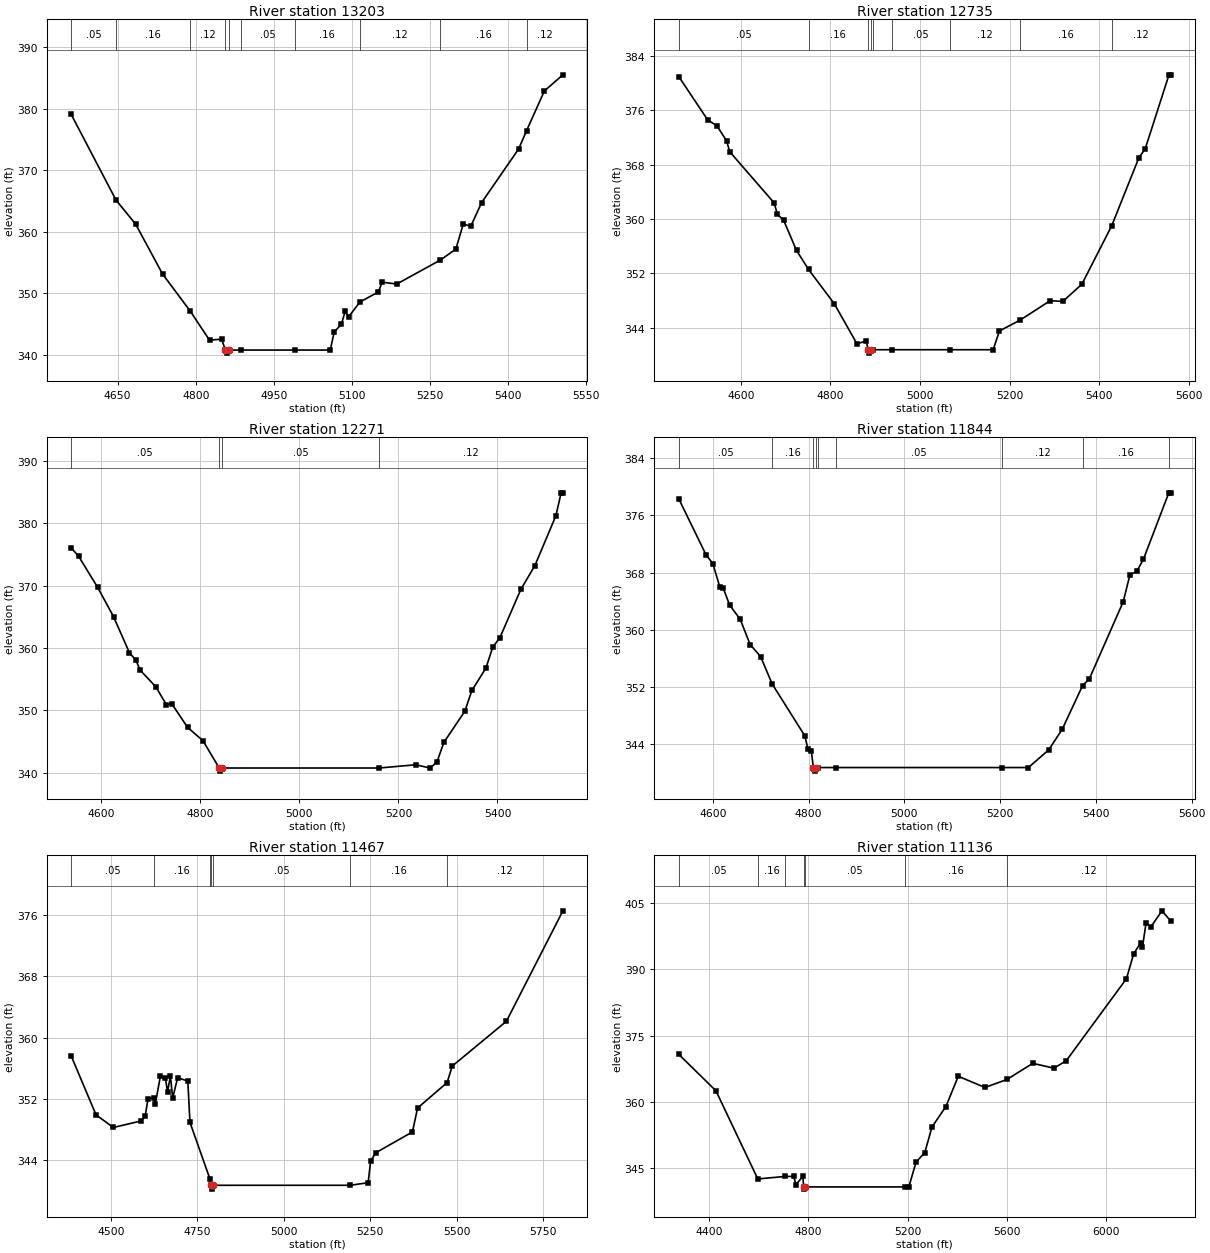
Type RM Length L Ch R = 1,13203,468,468,468
BEGIN DESCRIPTION:
UNT 055 IN CACR 28.0
END DESCRIPTION:
XS GIS Cut Line= 3
      3670499.61     10723760.18      3670599.61     10723360.19
      3670249.61     10722960.19
#Sta/Elev= 30
  4561.1  379.07  4647.0  365.16  4684.8  361.23  4736.3  353.14  4789.3  347.13
  4826.5  342.38  4849.7  342.54  4857.0  340.77  4859.8  340.27  4863.0  340.77
  4887.1  340.77  4989.8  340.77  5058.3  340.77  5065.9  343.71  5079.7  344.96
  5086.8  347.05  5093.5  346.16  5115.2  348.58  5150.4  350.20  5158.0  351.80
  5186.0  351.51  5269.9  355.41  5299.4  357.19  5313.7  361.29  5327.9  360.87
  5348.8  364.74  5420.0  373.48  5435.0  376.41  5469.3  382.90  5504.9  385.52
#Mann=10,-1,0
  4561.1    0.05       0  4647.0    0.16       0  4789.3    0.12       0
  4857.0    0.07       0  4863.0    0.12       0  4887.1    0.05       0
  4989.8    0.16       0  5115.2    0.12       0  5269.9    0.16       0
  5435.0    0.12       0
Bank Sta=4857,4863
Exp/Cntr=0.3,0.1

Type RM Length L Ch R = 1,12735,464,464,464
BEGIN DESCRIPTION:
UNT 055 IN CACR 27.0
END DESCRIPTION:
XS GIS Cut Line= 3
      3671349.58     10723460.17      3670949.61     10723110.19
      3670549.58     10722710.16
#Sta/Elev= 30
  4462.1  380.94  4526.1  374.61  4547.0  373.71  4568.4  371.53  4575.5  369.91
  4674.7  362.37  4681.8  360.70  4696.0  359.80  4724.5  355.38  4751.4  352.58
  4809.0  347.52  4859.3  341.65  4880.2  342.05  4884.3  340.77  4887.0  340.27
  4890.3  340.77  4894.3  340.77  4936.6  340.77  5068.0  340.77  5163.3  340.77
  5177.4  343.54  5223.8  345.14  5290.6  347.99  5318.8  347.88  5361.3  350.41
  5428.0  359.03  5488.5  369.02  5502.7  370.35  5555.7  381.23  5559.3  381.23
#Mann=9,-1,0
  4462.1    0.05       0  4751.4    0.16       0  4884.3   0.033       0
  4890.3    0.16       0  4894.3     0.1       0  4936.6    0.05       0
  5068.0    0.12       0  5223.8    0.16       0  5428.0    0.12       0
Bank Sta=4884.3,4890.3
Exp/Cntr=0.3,0.1

Type RM Length L Ch R = 1,12271,427,427,427
BEGIN DESCRIPTION:
UNT 055 IN CACR 26.0
END DESCRIPTION:
XS GIS Cut Line= 3
      3671649.58     10722910.18      3671249.61     10722760.19
      3670849.58     10722360.16
#Sta/Elev= 30
  4539.3  376.04  4554.4  374.67  4592.7  369.70  4624.7  365.02  4656.8  359.24
  4670.1  358.02  4678.1  356.48  4710.2  353.77  4731.5  350.90  4742.2  351.08
  4774.2  347.28  4805.4  345.14  4838.0  340.77  4840.7  340.27  4844.0  340.77
  5161.3  340.77  5235.2  341.29  5263.5  340.77  5277.6  341.68  5291.7  344.86
  5334.2  349.87  5348.3  353.19  5376.6  356.76  5390.7  360.17  5404.9  361.64
  5447.3  369.40  5475.6  373.20  5518.0  381.19  5528.6  384.86  5532.2  384.86
#Mann=4,-1,0
  4539.3    0.05       0  4838.0   0.033       0  4844.0    0.05       0
  5161.3    0.12       0
Bank Sta=4838,4844
Exp/Cntr=0.3,0.1

Type RM Length L Ch R = 1,11844,377,377,377
BEGIN DESCRIPTION:
UNT 055 IN CACR 25.0
END DESCRIPTION:
XS GIS Cut Line= 3
      3671799.62     10722760.20      3671499.61     10722410.19
      3671099.59     10722010.17
#Sta/Elev= 30
  4529.3  378.27  4585.8  370.50  4600.1  369.27  4614.4  366.06  4621.5  365.89
  4635.2  363.47  4657.2  361.49  4678.0  357.96  4700.0  356.26  4723.8  352.47
  4792.2  345.20  4798.8  343.33  4805.9  343.05  4810.0  340.77  4812.8  340.27
  4816.0  340.77  4820.7  340.77  4857.3  340.77  5204.9  340.77  5259.0  340.77
  5301.4  343.23  5329.7  346.12  5372.3  352.23  5386.3  353.16  5457.0  363.92
  5471.1  367.70  5485.3  368.17  5499.4  369.89  5551.8  379.06  5556.0  379.15
#Mann=9,-1,0
  4529.3    0.05       0  4723.8    0.16       0  4810.0   0.033       0
  4816.0    0.16       0  4820.7     0.1       0  4857.3    0.05       0
  5204.9    0.12       0  5372.3    0.16       0  5551.8    0.12       0
Bank Sta=4810,4816
Exp/Cntr=0.3,0.1

Type RM Length L Ch R = 1,11467,331,331,331
BEGIN DESCRIPTION:
UNT 055 IN CACR 24.0
END DESCRIPTION:
XS GIS Cut Line= 2
      3672241.56     10722488.25      3671095.76     10721646.26
#Sta/Elev= 30
  4385.3  357.60  4457.0  349.94  4507.1  348.30  4586.3  349.14  4599.0  349.74
  4607.4  352.05  4623.5  352.17  4628.3  351.36  4643.0  354.95  4657.6  354.70
  4663.8  352.97  4672.2  354.98  4678.5  352.13  4693.1  354.79  4722.4  354.34
  4728.6  348.97  4786.7  341.55  4790.4  340.77  4793.2  340.27  4796.4  340.77
  5192.1  340.77  5244.0  341.11  5251.0  343.91  5265.6  345.00  5372.1  347.72
  5386.8  350.83  5472.3  354.15  5487.1  356.30  5643.7  362.13  5807.2  376.52
#Mann=7,-1,0
  4385.3    0.05       0  4623.5    0.16       0  4786.7    0.05       0
  4790.4   0.033       0  4796.4    0.05       0  5192.1    0.16       0
  5472.3    0.12       0
Bank Sta=4790.4,4796.4
Exp/Cntr=0.3,0.1

Type RM Length L Ch R = 1,11136,704,704,704
BEGIN DESCRIPTION:
UNT 055 IN CACR 23.0
END DESCRIPTION:
XS GIS Cut Line= 2
      3672536.70     10722323.32      3670975.49     10721105.03
#Sta/Elev= 30
  4279.0  370.75  4428.1  362.53  4596.6  342.58  4707.0  343.14  4742.8  343.16
  4749.2  341.22  4778.1  343.15  4781.4  340.77  4784.2  340.27  4787.4  340.77
  5189.4  340.77  5205.1  340.77  5234.0  346.38  5269.3  348.54  5298.2  354.33
  5354.3  358.97  5404.2  365.82  5511.7  363.28  5600.4  365.10  5704.3  368.75
  5789.4  367.65  5839.1  369.34  6081.5  387.90  6110.5  393.52  6139.4  396.09
  6145.8  394.98  6160.2  400.42  6181.0  399.72  6224.5  403.27  6259.3  401.01
#Mann=7,-1,0
  4279.0    0.05       0  4596.6    0.16       0  4707.0    0.05       0
  4781.4   0.033       0  4787.4    0.05       0  5189.4    0.16       0
  5600.4    0.12       0
Bank Sta=4781.4,4787.4
Exp/Cntr=0.3,0.1

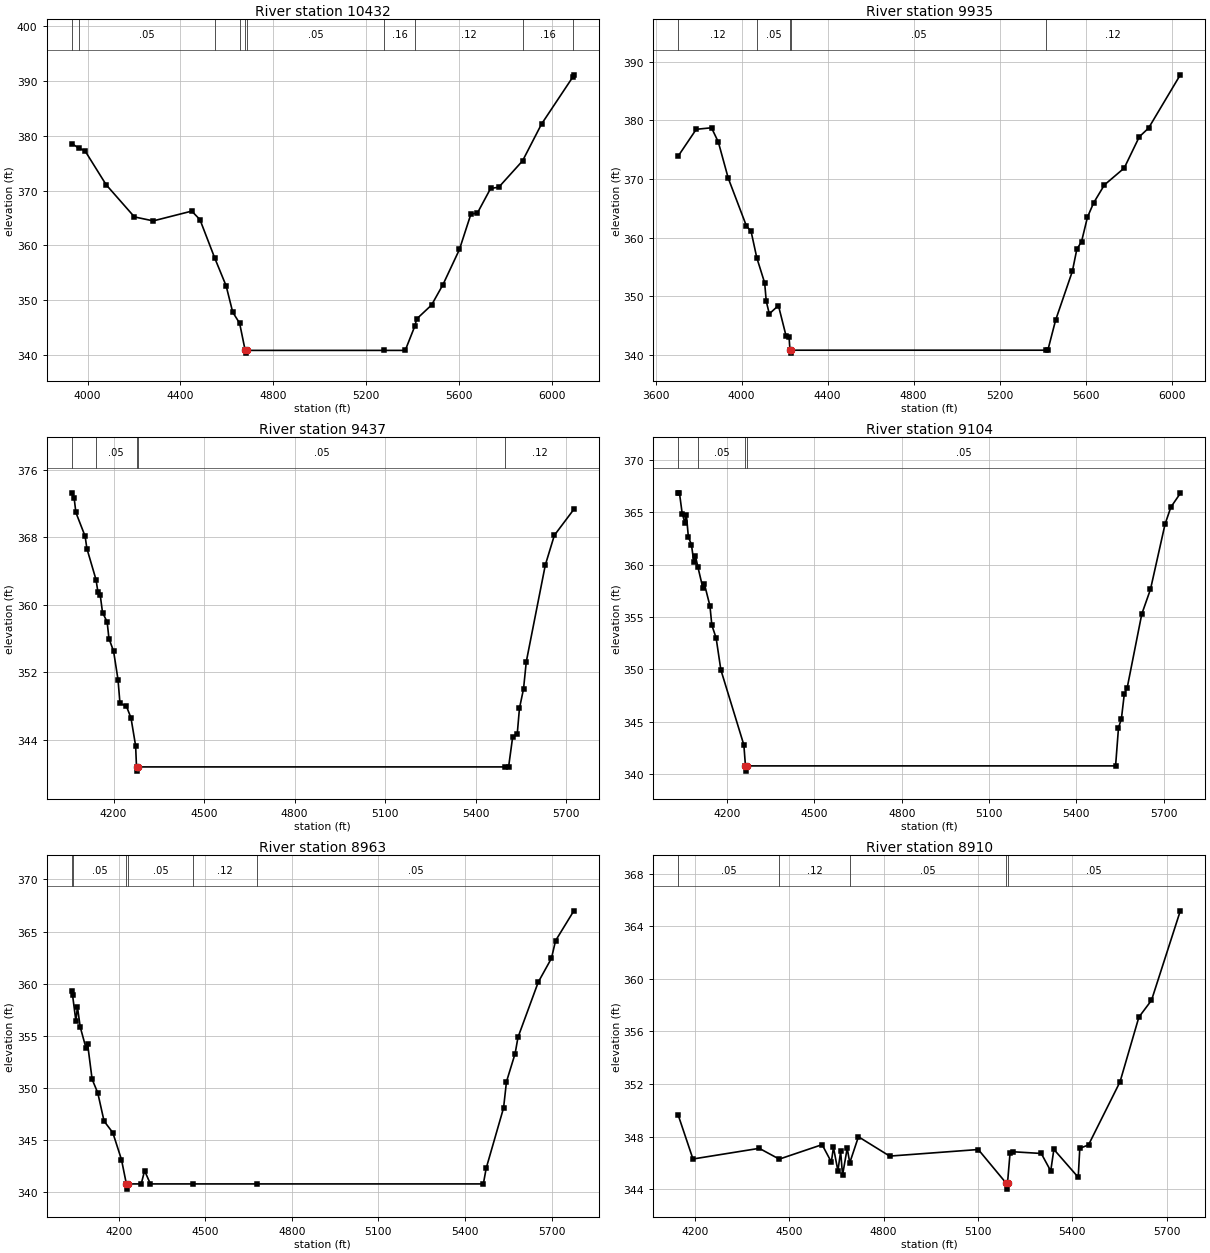
Type RM Length L Ch R = 1,10432,497,497,497
BEGIN DESCRIPTION:
Mapping XS 88d9b825
END DESCRIPTION:
XS GIS Cut Line= 3
      3672907.55     10722276.31      3672822.92     10721766.38
      3671700.99     10720561.99
#Sta/Elev= 30
  3932.0  378.59  3962.7  377.75  3988.9  377.27  4080.1  371.06  4201.8  365.18
  4282.9  364.45  4448.9  366.24  4484.2  364.68  4547.4  357.71  4597.0  352.57
  4625.3  347.76  4655.1  345.74  4679.0  340.77  4681.8  340.27  4685.0  340.77
  5278.7  340.77  5368.5  340.77  5409.8  345.20  5417.8  346.52  5481.8  349.06
  5531.1  352.80  5602.0  359.22  5651.3  365.68  5679.7  365.91  5736.3  370.38
  5771.5  370.61  5873.8  375.42  5955.7  382.16  6091.9  390.85  6094.9  391.16
#Mann=10,-1,0
  3932.0    0.16       0  3962.7    0.05       0  4547.4    0.16       0
  4655.1    0.05       0  4679.0   0.033       0  4685.0    0.05       0
  5278.7    0.16       0  5409.8    0.12       0  5873.8    0.16       0
  6091.9    0.12       0
Bank Sta=4679,4685
Exp/Cntr=0.3,0.1

Type RM Length L Ch R = 1,9935,498,498,498
BEGIN DESCRIPTION:
Mapping XS fa7852e2
END DESCRIPTION:
XS GIS Cut Line= 4
      3673721.35     10721896.57      3673597.66     10721759.87
      3672803.39     10721015.51      3672003.59     10720317.58
#Sta/Elev= 30
  3705.4  373.92  3789.1  378.48  3860.1  378.74  3891.8  376.31  3937.8  370.15
  4022.7  361.95  4043.8  361.11  4070.5  356.57  4107.3  352.25  4114.6  349.14
  4128.8  346.97  4171.2  348.40  4206.4  343.26  4220.6  343.05  4224.9  340.77
  4227.7  340.27  4230.9  340.77  5414.2  340.77  5423.9  340.77  5460.0  345.90
  5537.8  354.23  5558.7  358.01  5580.5  359.30  5608.1  363.48  5636.5  365.90
  5686.7  368.98  5778.9  371.86  5849.2  377.21  5891.9  378.67  6039.8  387.78
#Mann=5,-1,0
  3705.4    0.12       0  4070.5    0.05       0  4224.9   0.033       0
  4230.9    0.05       0  5414.2    0.12       0
Bank Sta=4224.9,4230.9
Exp/Cntr=0.3,0.1

Type RM Length L Ch R = 1,9437,333,333,333
BEGIN DESCRIPTION:
UNT 055 IN CACR 20.0
END DESCRIPTION:
XS GIS Cut Line= 3
      3673649.61     10721460.18      3673149.61     10720660.19
      3672549.61     10720260.19
#Sta/Elev= 30
  4061.4  373.30  4069.1  372.74  4075.0  370.97  4105.6  368.15  4111.5  366.69
  4141.8  362.99  4148.1  361.53  4155.7  361.17  4163.4  359.09  4178.7  357.98
  4184.6  356.01  4200.0  354.51  4214.7  351.13  4221.2  348.31  4242.4  347.99
  4257.7  346.59  4273.1  343.27  4276.0  340.77  4278.7  340.27  4282.0  340.77
  5498.4  340.77  5509.6  340.77  5523.1  344.33  5538.1  344.62  5545.6  347.73
  5559.1  350.03  5568.2  353.25  5631.3  364.73  5661.3  368.26  5725.9  371.34
#Mann=5,-1,0
  4061.4    0.12       0  4141.8    0.05       0  4276.0   0.033       0
  4282.0    0.05       0  5498.4    0.12       0
Bank Sta=4276,4282
Exp/Cntr=0.3,0.1

Type RM Length L Ch R = 1,9104,141,141,141
BEGIN DESCRIPTION:
UNT 055 IN CACR 19.0
END DESCRIPTION:
XS GIS Cut Line= 3
      3673723.42     10721403.00      3673428.29     10720565.35
      3673423.95     10719727.68
#Sta/Elev= 30
  4031.7  366.87  4035.8  366.87  4045.3  364.89  4054.4  364.03  4059.7  364.77
  4066.5  362.66  4077.1  361.92  4085.3  360.25  4090.6  360.85  4099.0  359.81
  4116.3  357.78  4121.6  358.16  4140.7  356.06  4147.2  354.22  4161.9  353.00
  4178.2  349.95  4257.3  342.77  4262.7  340.77  4265.5  340.27  4268.7  340.77
  5535.0  340.77  5545.0  344.41  5555.0  345.27  5565.0  347.65  5575.0  348.25
  5625.0  355.28  5655.0  357.65  5705.0  363.87  5725.0  365.50  5757.5  366.82
#Mann=4,-1,0
  4031.7    0.12       0  4099.0    0.05       0  4262.7   0.033       0
  4268.7    0.05       0
Bank Sta=4262.7,4268.7
Exp/Cntr=0.3,0.1

Type RM Length L Ch R = 1,8963,53,53,53
BEGIN DESCRIPTION:
UNT 055 IN CACR 18.0
END DESCRIPTION:
XS GIS Cut Line= 6
      3673708.44     10721338.41      3673678.03     10721222.24
      3673692.18     10720955.97      3673522.91     10720634.79
      3673566.31     10720547.99      3673531.59     10719666.86
#Sta/Elev= 30
  4037.5  359.32  4040.2  358.91  4051.9  356.39  4057.1  357.78  4066.7  355.85
  4087.1  353.78  4092.3  354.22  4108.0  350.82  4127.6  349.51  4149.4  346.80
  4179.7  345.69  4209.7  343.11  4226.7  340.77  4229.5  340.27  4232.7  340.77
  4278.2  340.77  4289.8  342.04  4309.9  340.77  4456.0  340.77  4679.4  340.77
  5463.7  340.77  5473.7  342.29  5533.8  348.07  5543.8  350.58  5573.8  353.29
  5583.8  354.85  5653.9  360.14  5699.7  362.43  5713.9  364.12  5777.3  366.99
#Mann=6,-1,0
  4037.5    0.12       0  4040.2    0.05       0  4226.7    0.03       0
  4232.7    0.05       0  4456.0    0.12       0  4679.4    0.05       0
Bank Sta=4226.7,4232.7
Exp/Cntr=0.3,0.1

Type RM Length L Ch R = 1,8910,91,91,91
BEGIN DESCRIPTION:
Mapping XS 6c0a16b9
END DESCRIPTION:
XS GIS Cut Line= 6
      3673706.06     10721246.81      3673732.11     10720942.95
      3673684.37     10720804.06      3673597.56     10720652.15
      3673619.26     10720561.01      3673580.20     10719688.66
#Sta/Elev= 30
  4147.1  349.64  4193.9  346.31  4404.7  347.12  4468.2  346.30  4604.4  347.40
  4633.7  346.08  4640.5  347.19  4654.6  345.41  4663.3  346.88  4669.4  345.08
  4684.2  347.13  4692.3  346.02  4719.9  348.00  4819.2  346.53  5100.8  347.03
  5187.9  344.52  5190.7  344.02  5193.9  344.52  5201.7  346.73  5210.9  346.86
  5301.0  346.73  5331.1  345.40  5341.1  347.04  5418.5  344.92  5423.5  347.12
  5451.2  347.38  5551.3  352.17  5611.3  357.09  5651.4  358.37  5743.0  365.17
#Mann=5,-1,0
  4147.1    0.05       0  4468.2    0.12       0  4692.3    0.05       0
  5187.9    0.03       0  5193.9    0.05       0
Bank Sta=5187.9,5193.9
Exp/Cntr=0.3,0.1