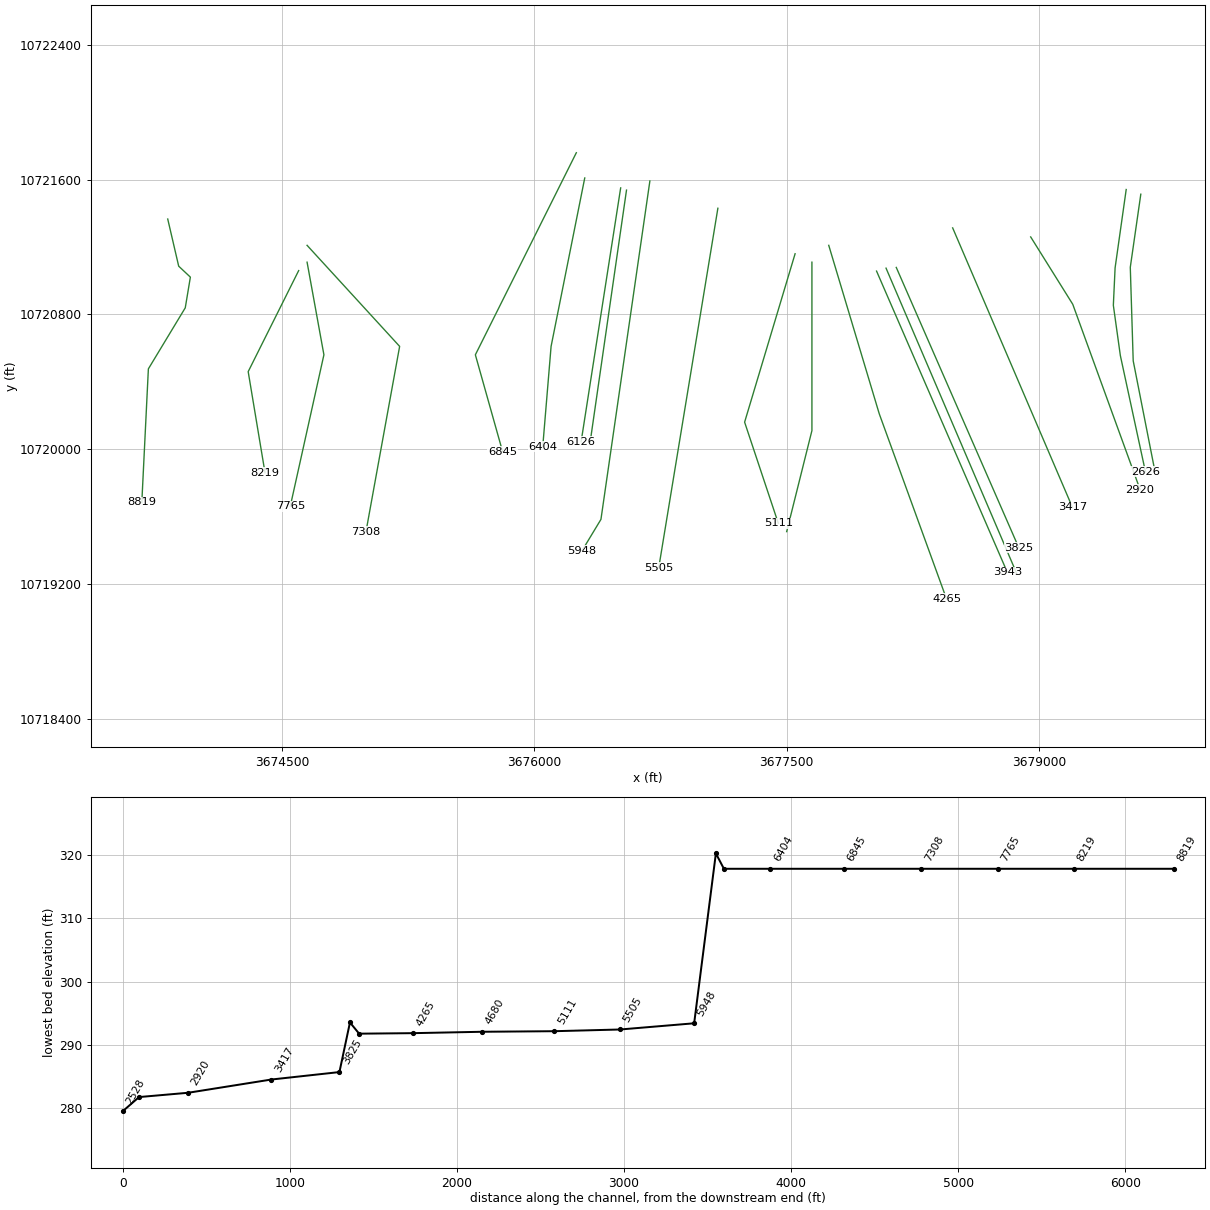
HEC-RAS study UNT 055 IN CACR.prj: UNT 055 IN CACR Base Level Engineering

--- UNT 055 IN CACR.g01 (geometry) --- (continued)

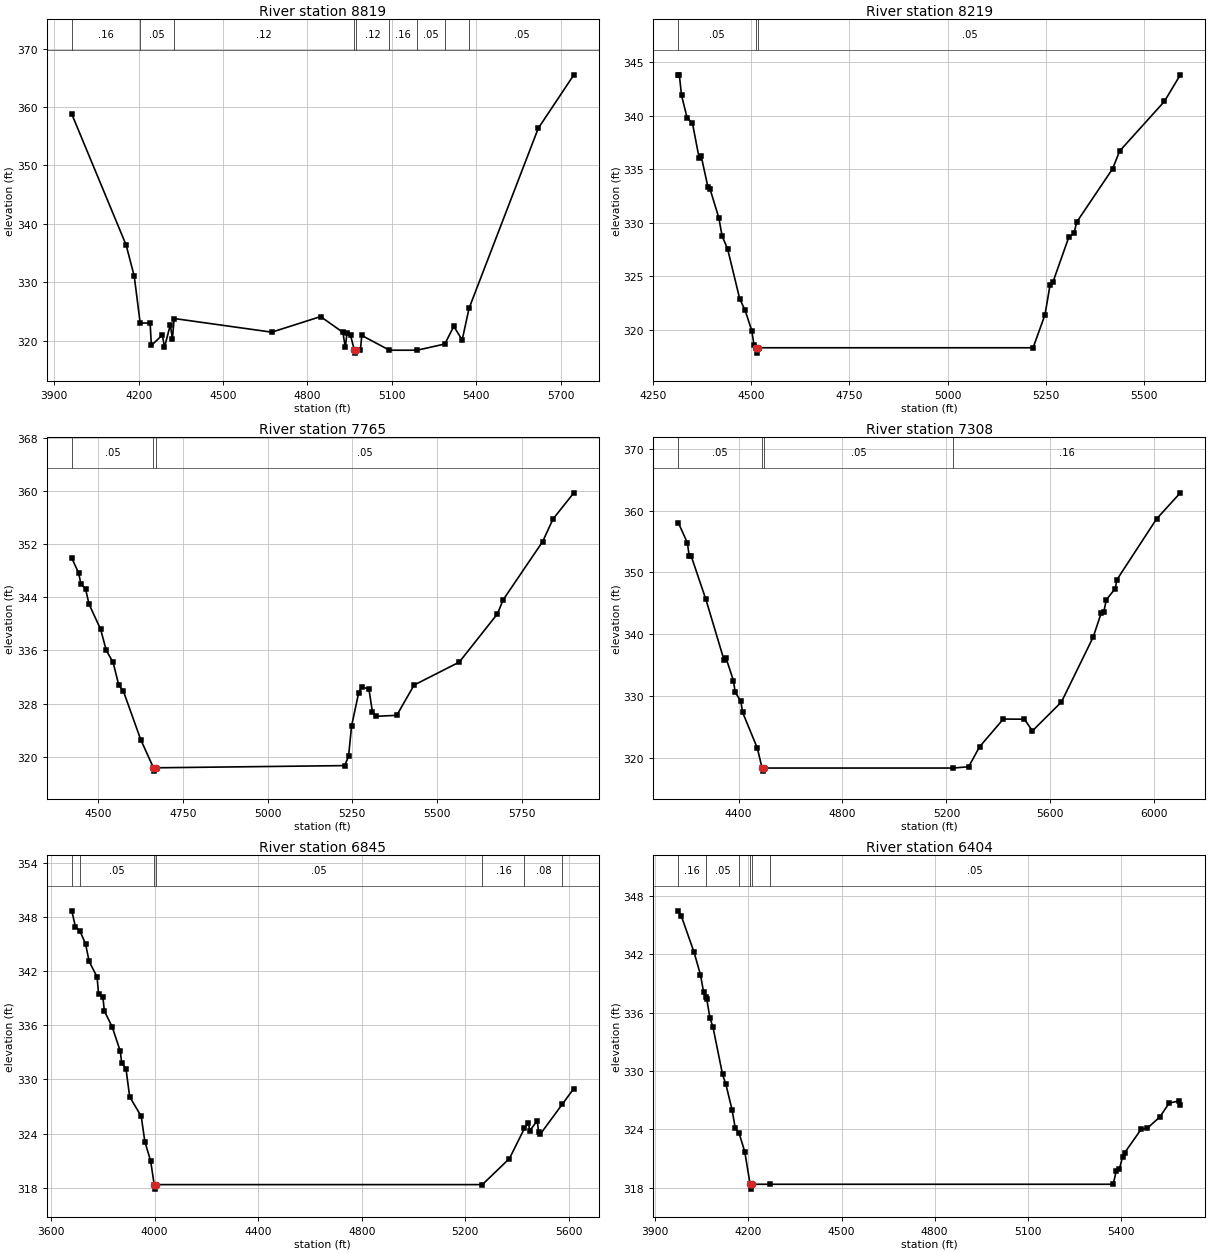
Type RM Length L Ch R = 1,8819,600,600,600
BEGIN DESCRIPTION:
Mapping XS 9f9f7cbf
END DESCRIPTION:
XS GIS Cut Line= 6
      3673821.51     10721366.47      3673886.62     10721086.50
      3673956.06     10721021.40      3673925.68     10720839.11
      3673706.49     10720476.70      3673667.50     10719683.77
#Sta/Elev= 30
  3962.3  358.81  4155.6  336.36  4184.4  331.03  4205.5  323.00  4240.9  323.01
  4245.3  319.16  4284.5  320.96  4291.8  318.83  4312.8  322.72  4320.1  320.25
  4326.3  323.78  4673.3  321.44  4847.0  324.11  4926.0  321.42  4935.0  318.83
  4941.0  321.36  4953.4  320.91  4966.9  318.35  4969.7  317.85  4972.9  318.35
  4988.4  318.35  4993.4  320.88  5091.8  318.35  5190.2  318.35  5288.5  319.41
  5320.4  322.43  5350.4  320.11  5374.6  325.51  5620.7  356.36  5747.3  365.53
#Mann=9,-1,0
  3962.3    0.16       0  4205.5    0.05       0  4326.3    0.12       0
  4966.9    0.07       0  4972.9    0.12       0  5091.8    0.16       0
  5190.2    0.05       0  5288.5    0.16       0  5374.6    0.05       0
Bank Sta=4966.9,4972.9
Exp/Cntr=0.3,0.1

Type RM Length L Ch R = 1,8219,454,454,454
BEGIN DESCRIPTION:
UNT 055 IN CACR 17.0
END DESCRIPTION:
XS GIS Cut Line= 3
      3674599.61     10721060.19      3674299.61     10720460.19
      3674399.61     10719860.19
#Sta/Elev= 30
  4313.9  343.79  4316.7  343.79  4322.3  341.90  4336.3  339.82  4350.2  339.28
  4367.0  336.08  4372.6  336.20  4389.4  333.37  4395.0  333.15  4417.3  330.47
  4425.7  328.77  4439.7  327.57  4470.4  322.93  4484.4  321.83  4501.2  319.95
  4506.8  318.64  4512.2  318.35  4514.9  317.85  4518.2  318.35  5217.9  318.35
  5248.3  321.44  5261.0  324.18  5268.6  324.48  5309.1  328.69  5321.8  329.01
  5329.4  330.09  5420.7  335.06  5438.4  336.70  5552.5  341.33  5593.0  343.81
#Mann=3,-1,0
  4313.9    0.05       0  4512.2   0.033       0  4518.2    0.05       0
Bank Sta=4512.2,4518.2
Exp/Cntr=0.3,0.1

Type RM Length L Ch R = 1,7765,457,457,457
BEGIN DESCRIPTION:
UNT 055 IN CACR 16.0
END DESCRIPTION:
XS GIS Cut Line= 3
      3674649.60     10721110.23      3674749.61     10720560.19
      3674549.61     10719660.20
#Sta/Elev= 30
  4422.5  349.91  4442.9  347.64  4449.2  346.04  4463.2  345.25  4473.4  342.98
  4507.7  339.17  4524.2  336.02  4544.5  334.20  4561.0  330.81  4575.0  329.85
  4625.8  322.60  4663.5  318.35  4666.2  317.85  4669.5  318.35  5227.4  318.68
  5238.9  320.07  5247.9  324.64  5268.4  329.55  5277.4  330.55  5299.1  330.17
  5309.4  326.74  5319.6  326.10  5381.1  326.24  5432.3  330.80  5565.5  334.25
  5678.1  341.51  5694.8  343.61  5811.3  352.37  5842.1  355.78  5903.5  359.72
#Mann=3,-1,0
  4422.5    0.05       0  4663.5   0.033       0  4669.5    0.05       0
Bank Sta=4663.5,4669.5
Exp/Cntr=0.3,0.1

Type RM Length L Ch R = 1,7308,463,463,463
BEGIN DESCRIPTION:
Mapping XS 2057b011
END DESCRIPTION:
XS GIS Cut Line= 3
      3674649.62     10721210.18      3675199.61     10720610.19
      3674999.60     10719510.15
#Sta/Elev= 30
  4168.0  358.08  4203.4  354.78  4210.2  352.65  4217.6  352.68  4274.4  345.64
  4344.6  335.77  4352.0  336.14  4380.4  332.50  4387.2  330.60  4408.8  329.20
  4415.6  327.37  4472.3  321.58  4490.6  318.35  4493.3  317.85  4496.6  318.35
  5226.9  318.35  5285.6  318.56  5327.5  321.79  5419.0  326.28  5500.3  326.25
  5530.8  324.36  5642.6  329.04  5764.5  339.52  5796.3  343.52  5805.2  343.57
  5815.4  345.60  5849.7  347.39  5856.0  348.83  6008.5  358.66  6100.0  362.89
#Mann=4,-1,0
  4168.0    0.05       0  4490.6   0.033       0  4496.6    0.05       0
  5226.9    0.16       0
Bank Sta=4490.6,4496.6
Exp/Cntr=0.3,0.1

Type RM Length L Ch R = 1,6845,441,441,441
BEGIN DESCRIPTION:
UNT 055 IN CACR 14.0
END DESCRIPTION:
XS GIS Cut Line= 3
      3676249.60     10721760.17      3675649.61     10720560.19
      3675811.63     10719984.58
#Sta/Elev= 30
  3679.8  348.66  3693.8  346.92  3711.9  346.38  3732.9  345.02  3746.9  343.06
  3777.6  341.33  3783.2  339.49  3800.0  339.11  3805.6  337.59  3836.3  335.78
  3867.1  333.13  3872.6  331.85  3889.4  331.15  3903.4  328.08  3948.1  325.91
  3962.1  323.10  3984.4  320.98  3998.2  318.35  4001.0  317.85  4004.2  318.35
  5265.9  318.35  5370.7  321.24  5428.6  324.58  5444.0  325.19  5449.2  324.32
  5478.0  325.42  5483.2  324.12  5488.9  323.90  5574.5  327.24  5619.4  328.99
#Mann=7,-1,0
  3679.8    0.16       0  3711.9    0.05       0  3998.2   0.033       0
  4004.2    0.05       0  5265.9    0.16       0  5428.6    0.08       0
  5574.5    0.05       0
Bank Sta=3998.2,4004.2
Exp/Cntr=0.3,0.1

Type RM Length L Ch R = 1,6404,278,278,278
BEGIN DESCRIPTION:
UNT 055 IN CACR 13.0
END DESCRIPTION:
XS GIS Cut Line= 3
      3676299.62     10721610.23      3676099.61     10720610.19
      3676049.98     10720014.59
#Sta/Elev= 30
  3974.0  346.45  3984.2  345.89  4025.0  342.19  4045.4  339.90  4055.6  338.12
  4063.2  337.58  4065.8  337.39  4076.0  335.46  4086.2  334.46  4116.8  329.63
  4127.0  328.68  4147.4  326.00  4157.6  324.14  4169.8  323.62  4188.2  321.71
  4205.6  318.35  4208.3  317.85  4211.6  318.35  4270.6  318.35  5375.2  318.35
  5385.2  319.72  5395.2  319.92  5405.3  321.13  5412.8  321.61  5465.5  324.01
  5485.5  324.12  5525.7  325.27  5555.8  326.70  5585.9  326.90  5591.5  326.46
#Mann=6,-1,0
  3974.0    0.16       0  4063.2    0.05       0  4169.8    0.16       0
  4205.6    0.03       0  4211.6    0.16       0  4270.6    0.05       0
Bank Sta=4205.6,4211.6
Exp/Cntr=0.3,0.1

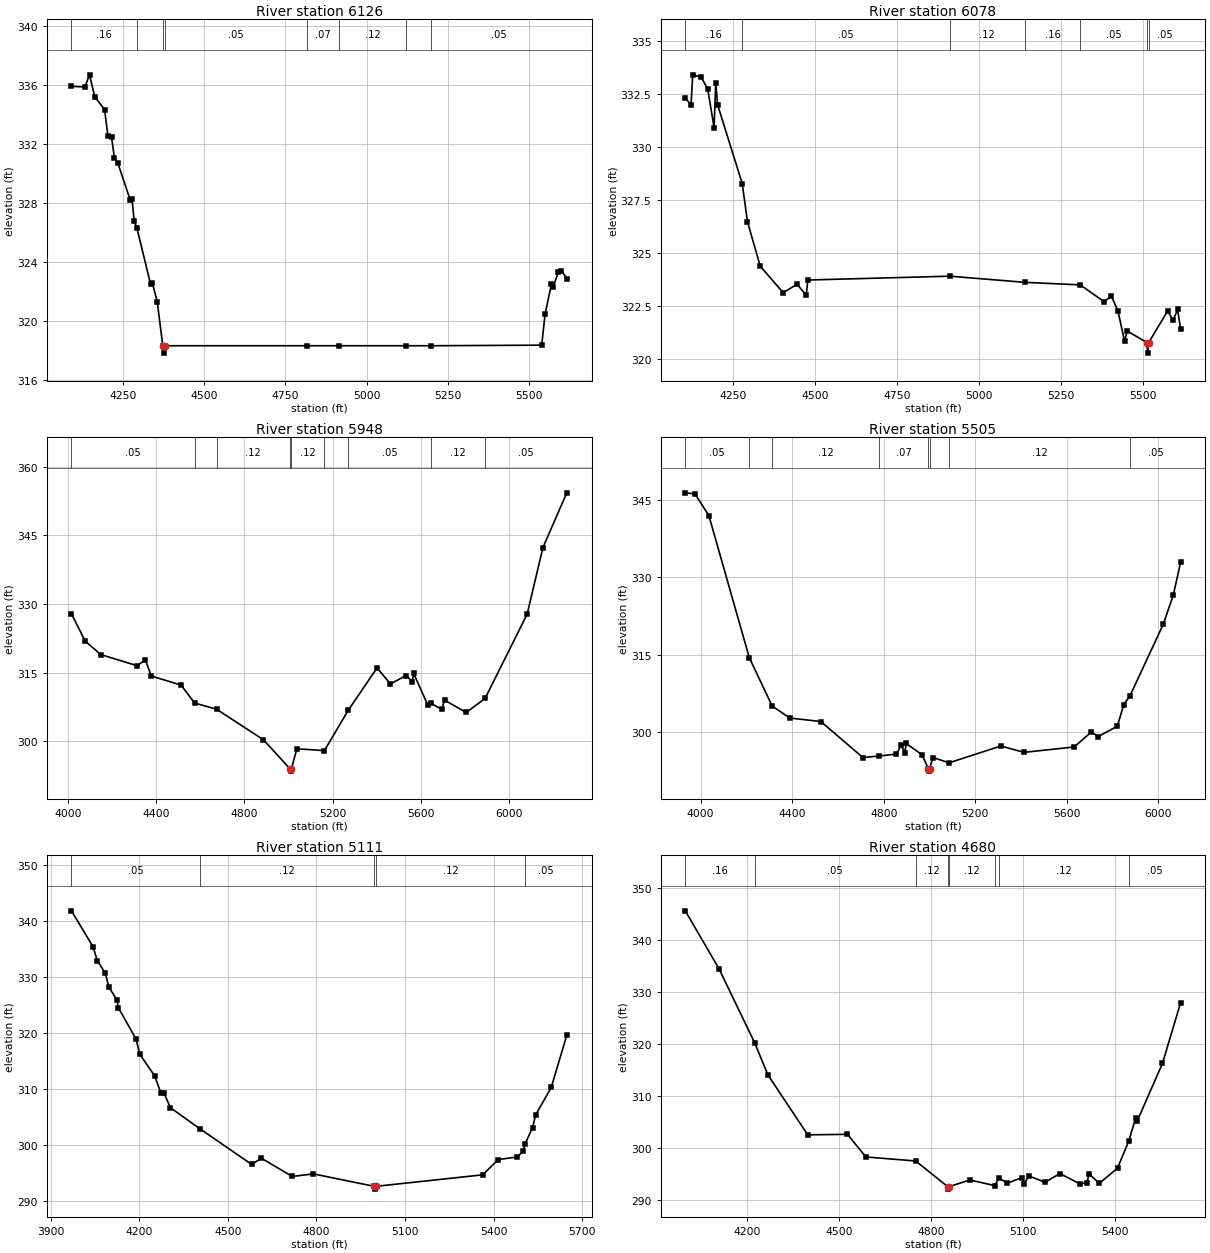
Type RM Length L Ch R = 1,6126,48,48,48
BEGIN DESCRIPTION:
Mapping XS 43a54700
END DESCRIPTION:
XS GIS Cut Line= 2
      3676513.06     10721551.15      3676278.07     10720043.96
#Sta/Elev= 30
  4090.9  335.91  4132.4  335.87  4146.6  336.69  4162.7  335.21  4193.1  334.33
  4203.2  332.56  4214.5  332.46  4223.4  331.03  4233.6  330.73  4272.3  328.19
  4277.3  328.31  4284.2  326.78  4292.8  326.29  4334.8  322.50  4340.2  322.59
  4355.0  321.34  4372.3  318.35  4375.0  317.85  4378.3  318.35  4815.2  318.35
  4915.1  318.35  5122.1  318.35  5197.7  318.35  5539.1  318.39  5549.3  320.48
  5569.1  322.53  5574.2  322.30  5589.8  323.31  5599.9  323.43  5616.3  322.90
#Mann=8,-1,0
  4090.9    0.16       0  4292.8    0.05       0  4372.3    0.07       0
  4378.3    0.05       0  4815.2    0.07       0  4915.1    0.12       0
  5122.1    0.16       0  5197.7    0.05       0
Bank Sta=4372.3,4378.3
Exp/Cntr=0.3,0.1

Type RM Length L Ch R = 1,6078,130,130,130
BEGIN DESCRIPTION:
Mapping XS fc35f1a4
END DESCRIPTION:
XS GIS Cut Line= 2
      3676547.78     10721538.11      3676331.61     10720040.83
#Sta/Elev= 30
  4103.3  332.31  4120.9  331.99  4126.0  333.41  4151.7  333.31  4171.9  332.73
  4191.3  330.92  4196.3  333.04  4202.2  331.99  4277.2  328.28  4293.2  326.48
  4332.0  324.39  4402.3  323.13  4444.7  323.53  4472.7  323.01  4477.7  323.73
  4911.1  323.91  5140.2  323.62  5309.5  323.50  5382.2  322.71  5404.6  322.97
  5424.8  322.26  5445.0  320.83  5452.6  321.33  5512.7  320.78  5515.5  320.28
  5518.7  320.78  5576.3  322.27  5593.3  321.83  5606.6  322.34  5616.1  321.42
#Mann=7,-1,0
  4103.3    0.16       0  4277.2    0.05       0  4911.1    0.12       0
  5140.2    0.16       0  5309.5    0.05       0  5512.7    0.07       0
  5518.7    0.05       0
Bank Sta=5512.7,5518.7
Exp/Cntr=0.3,0.1

Type RM Length L Ch R = 1,5948,443,443,443
BEGIN DESCRIPTION:
Mapping XS 38a92d27
END DESCRIPTION:
XS GIS Cut Line= 3
      3676686.66     10721592.29      3676395.86     10719582.79
      3676283.81     10719397.47
#Sta/Elev= 30
  4015.5  327.86  4078.2  321.86  4149.0  318.93  4312.4  316.51  4351.1  317.74
  4377.6  314.25  4512.7  312.26  4574.1  308.33  4673.7  306.98  4886.6  300.29
  5007.1  293.93  5009.9  293.43  5013.1  293.93  5038.1  298.32  5162.9  297.92
  5271.4  306.77  5401.9  316.02  5462.5  312.51  5533.2  314.35  5562.2  313.02
  5567.3  314.86  5632.5  307.83  5647.7  308.25  5694.9  306.93  5707.8  308.97
  5806.1  306.27  5891.7  309.33  6082.6  327.77  6154.1  342.35  6262.5  354.33
#Mann=9,-1,0
  4015.5    0.05       0  4574.1    0.08       0  4673.7    0.12       0
  5007.1    0.07       0  5013.1    0.12       0  5162.9    0.16       0
  5271.4    0.05       0  5647.7    0.12       0  5891.7    0.05       0
Bank Sta=5007.1,5013.1
Exp/Cntr=0.3,0.1

Type RM Length L Ch R = 1,5505,394,394,394
BEGIN DESCRIPTION:
Mapping XS 18d89355
END DESCRIPTION:
XS GIS Cut Line= 2
      3677090.75     10721430.51      3676739.20     10719295.15
#Sta/Elev= 30
  3933.1  346.38  3975.0  346.19  4036.1  341.98  4212.8  314.43  4312.8  305.06
  4389.5  302.74  4525.6  302.06  4709.2  295.08  4781.1  295.39  4855.7  295.76
  4875.9  297.47  4892.7  296.04  4897.8  297.81  4967.2  295.64  4994.6  292.95
  4997.3  292.45  5000.6  292.95  5015.1  295.09  5085.4  294.06  5311.7  297.32
  5413.1  296.09  5632.0  297.13  5707.0  300.03  5737.4  299.15  5820.6  301.16
  5848.9  305.36  5876.0  307.06  6021.2  320.91  6065.3  326.62  6097.2  332.96
#Mann=8,-1,0
  3933.1    0.05       0  4212.8    0.08       0  4312.8    0.12       0
  4781.1    0.07       0  4994.6    0.07       0  5000.6    0.07       0
  5085.4    0.12       0  5876.0    0.05       0
Bank Sta=4994.6,5000.6
Exp/Cntr=0.3,0.1

Type RM Length L Ch R = 1,5111,431,431,431
BEGIN DESCRIPTION:
UNT 055 IN CACR 10.0
END DESCRIPTION:
XS GIS Cut Line= 3
      3677549.60     10721160.15      3677249.61     10720160.19
      3677449.60     10719560.23
#Sta/Elev= 30
  3970.7  341.85  4043.7  335.46  4058.5  332.92  4085.5  330.73  4096.8  328.30
  4124.7  325.93  4129.9  324.52  4189.9  318.91  4201.2  316.32  4252.5  312.38
  4273.4  309.32  4283.9  309.32  4305.6  306.72  4404.1  303.00  4580.5  296.60
  4613.6  297.69  4718.0  294.44  4789.4  294.90  4995.2  292.68  4997.9  292.18
  5001.2  292.68  5362.5  294.73  5415.2  297.46  5478.5  297.91  5499.6  298.94
  5506.0  300.27  5531.2  303.16  5541.7  305.43  5594.4  310.32  5647.1  319.66
#Mann=5,-1,0
  3970.7    0.05       0  4404.1    0.12       0  4995.2    0.07       0
  5001.2    0.12       0  5506.0    0.05       0
Bank Sta=4995.2,5001.2
Exp/Cntr=0.3,0.1

Type RM Length L Ch R = 1,4680,415,415,415
BEGIN DESCRIPTION:
UNT 055 IN CACR 9.0
END DESCRIPTION:
XS GIS Cut Line= 3
      3677649.61     10721110.22      3677649.61     10720110.19
      3677499.61     10719510.18
#Sta/Elev= 30
  3997.5  345.66  4107.5  334.53  4223.8  320.31  4267.5  314.08  4397.5  302.54
  4527.5  302.64  4587.5  298.28  4750.3  297.51  4854.5  292.59  4857.3  292.09
  4860.5  292.59  4927.5  293.85  5008.5  292.77  5022.2  294.27  5049.1  293.23
  5098.0  294.32  5103.2  293.09  5121.2  294.61  5172.8  293.41  5221.7  295.09
  5286.1  293.12  5309.3  293.32  5317.1  294.99  5350.6  293.21  5409.8  296.14
  5446.6  301.35  5469.1  305.84  5474.3  305.24  5556.7  316.30  5616.0  328.00
#Mann=8,-1,0
  3997.5    0.16       0  4223.8    0.05       0  4750.3    0.12       0
  4854.5    0.07       0  4860.5    0.12       0  5008.5    0.07       0
  5022.2    0.12       0  5446.6    0.05       0
Bank Sta=4854.5,4860.5
Exp/Cntr=0.3,0.1

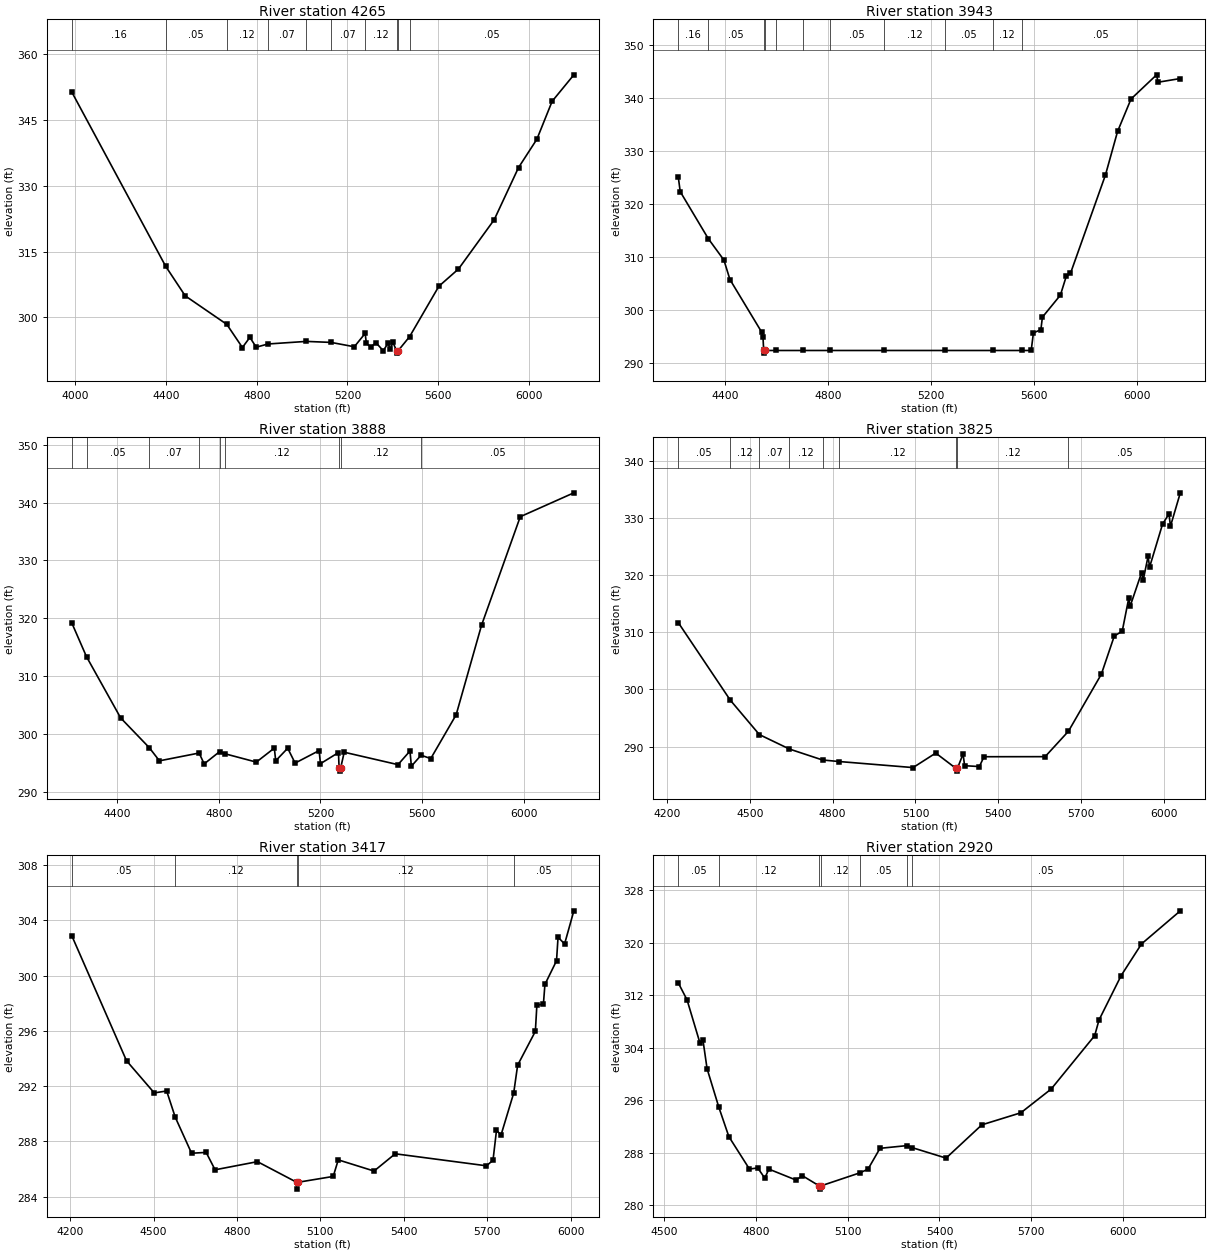
Type RM Length L Ch R = 1,4265,322,322,322
BEGIN DESCRIPTION:
UNT 055 IN CACR 8.0
END DESCRIPTION:
XS GIS Cut Line= 3
      3677749.61     10721210.18      3678049.61     10720210.19
      3678449.61     10719110.18
#Sta/Elev= 30
  3984.1  351.34  4398.1  311.66  4484.4  304.92  4667.9  298.42  4736.7  293.15
  4769.7  295.46  4797.6  293.22  4849.3  293.95  5018.6  294.54  5127.9  294.31
  5230.3  293.32  5278.1  296.36  5283.5  294.10  5302.8  293.29  5326.1  294.22
  5358.0  292.42  5379.3  294.15  5389.2  292.70  5400.5  294.34  5416.8  292.37
  5419.6  291.87  5422.8  292.37  5474.1  295.62  5603.4  307.11  5689.8  311.03
  5847.5  322.27  5954.5  334.12  6035.7  340.60  6102.8  349.22  6198.6  355.25
#Mann=10,-1,0
  3984.1    0.16       0  4398.1    0.05       0  4667.9    0.12       0
  4849.3    0.07       0  5018.6    0.12       0  5127.9    0.07       0
  5278.1    0.12       0  5416.8    0.07       0  5422.8    0.12       0
  5474.1    0.05       0
Bank Sta=5416.8,5422.8
Exp/Cntr=0.3,0.1

Type RM Length L Ch R = 1,3943,55,55,55
BEGIN DESCRIPTION:
Mapping XS 79623b1d
END DESCRIPTION:
XS GIS Cut Line= 2
      3678033.68     10721057.27      3678810.60     10719269.05
#Sta/Elev= 30
  4217.9  325.15  4225.6  322.32  4334.6  313.43  4395.3  309.38  4418.7  305.70
  4541.4  295.80  4546.9  294.93  4549.7  292.29  4552.5  291.79  4555.7  292.29
  4598.1  292.29  4703.2  292.29  4808.3  292.29  5016.6  292.29  5255.0  292.29
  5438.6  292.29  5552.4  292.29  5588.5  292.29  5597.2  295.62  5626.1  296.22
  5632.1  298.59  5701.9  302.75  5725.4  306.42  5741.1  306.87  5877.0  325.48
  5923.9  333.69  5976.2  339.83  6075.5  344.40  6080.9  343.00  6167.6  343.70
#Mann=11,-1,0
  4217.9    0.16       0  4334.6    0.05       0  4549.7   0.033       0
  4555.7    0.05       0  4598.1    0.07       0  4703.2    0.12       0
  4808.3    0.05       0  5016.6    0.12       0  5255.0    0.05       0
  5438.6    0.12       0  5552.4    0.05       0
Bank Sta=4549.7,4555.7
Exp/Cntr=0.3,0.1

Type RM Length L Ch R = 1,3888,63,63,63
BEGIN DESCRIPTION:
Mapping XS 711166c7
END DESCRIPTION:
XS GIS Cut Line= 2
      3678090.10     10721074.65      3678867.02     10719260.40
#Sta/Elev= 30
  4222.3  319.20  4280.2  313.35  4414.5  302.76  4526.9  297.62  4566.9  295.34
  4722.8  296.69  4742.8  294.81  4803.4  296.93  4824.6  296.56  4947.8  295.12
  5018.5  297.54  5024.0  295.35  5071.1  297.52  5100.2  294.95  5194.5  297.11
  5199.9  294.85  5270.7  296.77  5273.1  294.06  5275.8  293.56  5279.1  294.06
  5293.2  296.83  5504.6  294.68  5551.8  297.04  5557.2  294.41  5595.4  296.31
  5633.4  295.73  5733.2  303.30  5832.9  318.77  5985.3  337.56  6195.9  341.69
#Mann=9,-1,0
  4222.3    0.16       0  4280.2    0.05       0  4526.9    0.07       0
  4722.8    0.12       0  4803.4    0.07       0  4824.6    0.12       0
  5273.1    0.07       0  5279.1    0.12       0  5595.4    0.05       0
Bank Sta=5273.1,5279.1
Exp/Cntr=0.3,0.1

Type RM Length L Ch R = 1,3825,408,408,408
BEGIN DESCRIPTION:
Mapping XS a5048943
END DESCRIPTION:
XS GIS Cut Line= 2
      3678150.87     10721078.98      3678879.40     10719413.77
#Sta/Elev= 30
  4241.1  311.71  4429.6  298.13  4534.8  292.11  4643.8  289.58  4763.4  287.67
  4823.3  287.40  5091.2  286.34  5173.3  288.88  5245.9  286.22  5248.7  285.72
  5251.9  286.22  5272.3  288.73  5277.8  286.67  5331.3  286.52  5347.9  288.24
  5569.3  288.25  5653.8  292.70  5772.8  302.67  5819.6  309.34  5848.5  310.21
  5871.9  315.92  5877.3  314.59  5918.6  320.45  5924.1  319.07  5942.0  323.29
  5947.5  321.41  5994.3  328.91  6017.6  330.71  6023.1  328.56  6058.7  334.40
#Mann=9,-1,0
  4241.1    0.05       0  4429.6    0.12       0  4534.8    0.07       0
  4643.8    0.12       0  4763.4    0.07       0  4823.3    0.12       0
  5245.9    0.07       0  5251.9    0.12       0  5653.8    0.05       0
Bank Sta=5245.9,5251.9
Exp/Cntr=0.3,0.1

Type RM Length L Ch R = 1,3417,497,497,497
BEGIN DESCRIPTION:
UNT 055 IN CACR 6.0
END DESCRIPTION:
XS GIS Cut Line= 3
      3678485.98     10721313.80      3678723.31     10720760.47
      3679197.67     10719654.48
#Sta/Elev= 30
  4205.9  302.90  4402.8  293.84  4502.5  291.51  4547.1  291.65  4578.0  289.75
  4636.7  287.14  4689.2  287.20  4721.2  285.94  4873.6  286.53  5014.4  285.04
  5017.1  284.54  5020.4  285.04  5146.1  285.46  5164.2  286.66  5292.9  285.85
  5369.0  287.10  5697.1  286.23  5720.7  286.63  5733.2  288.79  5749.7  288.47
  5795.0  291.49  5809.3  293.52  5873.0  295.97  5878.4  297.85  5902.0  297.96
  5907.4  299.37  5949.1  301.08  5954.6  302.79  5978.1  302.30  6011.4  304.70
#Mann=5,-1,0
  4205.9    0.05       0  4578.0    0.12       0  5014.4    0.07       0
  5020.4    0.12       0  5795.0    0.05       0
Bank Sta=5014.4,5020.4
Exp/Cntr=0.3,0.1

Type RM Length L Ch R = 1,2920,294,294,294
BEGIN DESCRIPTION:
UNT 055 IN CACR 5.0
END DESCRIPTION:
XS GIS Cut Line= 3
      3678949.63     10721260.15      3679199.61     10720860.19
      3679599.60     10719760.21
#Sta/Elev= 30
  4545.7  313.90  4574.5  311.30  4617.0  304.68  4626.4  305.22  4640.0  300.81
  4678.2  294.97  4711.3  290.45  4778.6  285.51  4805.7  285.68  4828.7  284.13
  4842.2  285.50  4930.7  283.84  4951.9  284.49  5006.7  282.95  5009.4  282.45
  5012.7  282.95  5140.2  284.94  5166.3  285.49  5205.6  288.67  5295.3  289.09
  5309.8  288.79  5421.7  287.18  5538.7  292.25  5666.4  294.09  5765.5  297.71
  5907.8  305.85  5921.8  308.22  5994.3  315.00  6060.8  319.82  6187.8  324.87
#Mann=7,-1,0
  4545.7    0.05       0  4678.2    0.12       0  5006.7    0.07       0
  5012.7    0.12       0  5140.2    0.05       0  5295.3    0.12       0
  5309.8    0.05       0
Bank Sta=5006.7,5012.7
Exp/Cntr=0.3,0.1

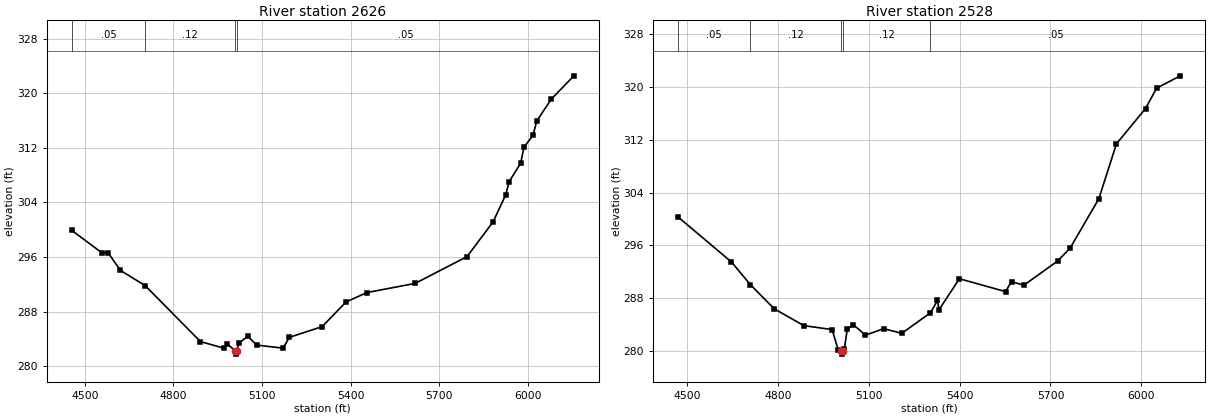
Type RM Length L Ch R = 1,2626,98,98,98
BEGIN DESCRIPTION:
Mapping XS 32dce70e
END DESCRIPTION:
XS GIS Cut Line= 5
      3679517.19     10721541.70      3679451.21     10721076.38
      3679440.80     10720854.16      3679482.46     10720555.54
      3679631.69     10719864.93
#Sta/Elev= 30
  4455.6  299.91  4558.1  296.61  4578.3  296.66  4620.1  294.05  4703.8  291.83
  4891.4  283.61  4971.8  282.63  4981.8  283.28  5008.9  282.27  5011.6  281.77
  5014.9  282.27  5021.9  283.39  5051.9  284.39  5081.9  283.09  5171.4  282.65
  5192.4  284.23  5303.5  285.80  5384.3  289.41  5454.8  290.79  5618.7  292.14
  5794.4  296.07  5882.7  301.17  5925.6  305.15  5937.1  307.07  5976.1  309.76
  5987.0  312.09  6017.7  313.85  6030.5  315.94  6079.7  319.16  6156.1  322.57
#Mann=4,-1,0
  4455.6    0.05       0  4703.8    0.12       0  5008.9    0.07       0
  5014.9    0.05       0
Bank Sta=5008.9,5014.9
Exp/Cntr=0.3,0.1

Type RM Length L Ch R = 1,2528,559,559,559
BEGIN DESCRIPTION:
Mapping XS eb598a27
END DESCRIPTION:
XS GIS Cut Line= 4
      3679604.00     10721513.92      3679541.49     10721079.85
      3679558.85     10720524.29      3679686.96     10719873.36
#Sta/Elev= 30
  4470.9  300.30  4646.4  293.51  4709.0  290.07  4787.9  286.40  4885.7  283.85
  4979.1  283.25  4999.2  280.15  5008.7  280.03  5011.5  279.53  5014.7  280.03
  5019.2  280.26  5029.2  283.36  5049.2  283.99  5089.2  282.41  5149.2  283.39
  5209.3  282.69  5303.8  285.80  5326.9  287.68  5331.9  286.25  5399.3  290.96
  5551.5  289.01  5571.4  290.53  5612.1  289.97  5724.3  293.67  5765.0  295.62
  5859.7  303.09  5917.9  311.42  6013.8  316.76  6050.4  319.85  6128.7  321.72
#Mann=5,-1,0
  4470.9    0.05       0  4709.0    0.12       0  5008.7    0.07       0
  5014.7    0.12       0  5303.8    0.05       0
Bank Sta=5008.7,5014.7
Exp/Cntr=0.3,0.1