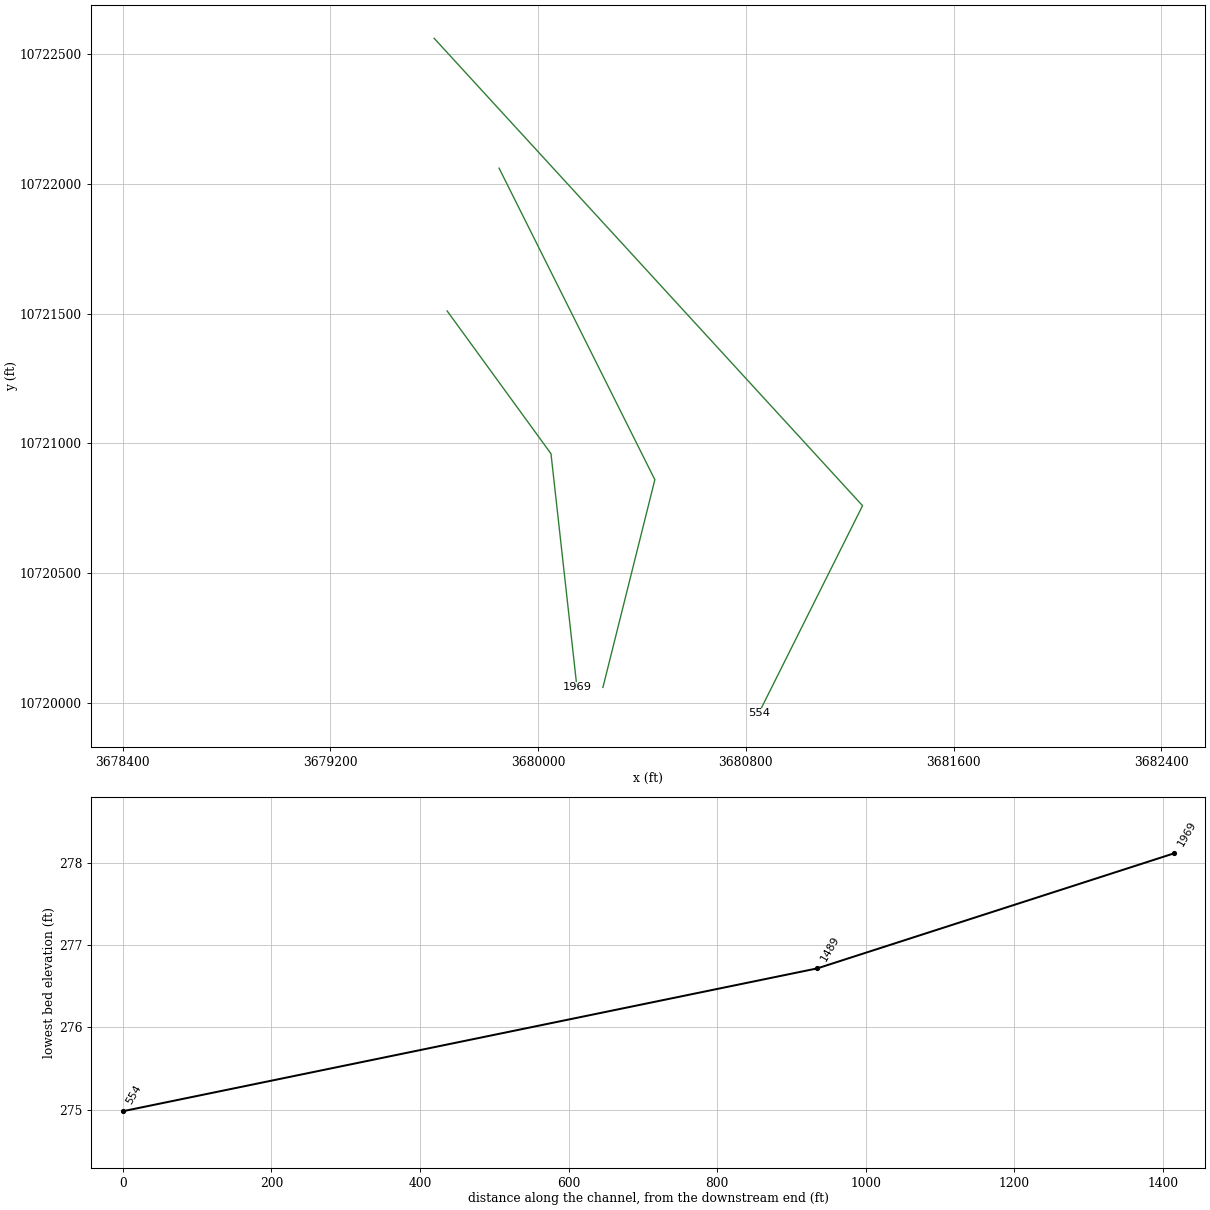
HEC-RAS study UNT 055 IN CACR.prj: UNT 055 IN CACR Base Level Engineering

--- UNT 055 IN CACR.g01 (geometry) --- (continued)

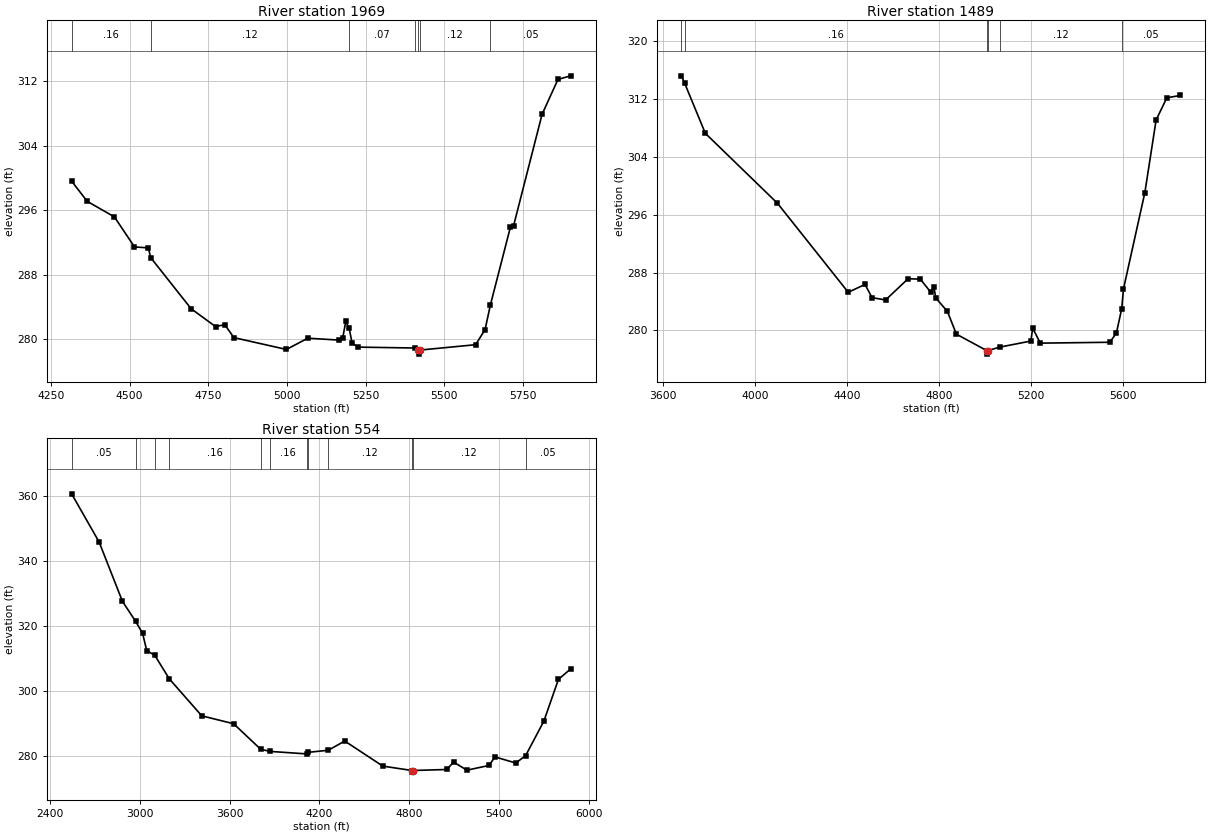
Type RM Length L Ch R = 1,1969,480,480,480
BEGIN DESCRIPTION:
UNT 055 IN CACR 3.0
END DESCRIPTION:
XS GIS Cut Line= 3
      3679649.62     10721510.18      3680049.61     10720960.19
      3680149.61     10720060.19
#Sta/Elev= 30
  4316.0  299.62  4365.4  297.11  4452.0  295.17  4515.8  291.44  4559.8  291.32
  4567.3  290.11  4695.8  283.76  4773.5  281.54  4802.5  281.78  4831.8  280.17
  4998.6  278.70  5066.5  280.10  5167.1  279.86  5177.2  280.07  5187.2  282.18
  5198.1  281.32  5207.4  279.46  5227.5  278.99  5407.5  278.88  5415.6  278.62
  5418.4  278.12  5421.6  278.62  5599.8  279.29  5629.9  281.18  5646.7  284.22
  5710.4  293.91  5720.5  294.08  5811.0  307.92  5861.4  312.25  5901.6  312.70
#Mann=7,-1,0
  4316.0    0.16       0  4567.3    0.12       0  5198.1    0.07       0
  5407.5    0.12       0  5415.6    0.07       0  5421.6    0.12       0
  5646.7    0.05       0
Bank Sta=5415.6,5421.6
Exp/Cntr=0.3,0.1

Type RM Length L Ch R = 1,1489,935,935,935
BEGIN DESCRIPTION:
UNT 055 IN CACR 2.0
END DESCRIPTION:
XS GIS Cut Line= 3
      3679849.60     10722060.21      3680449.61     10720860.19
      3680249.61     10720060.18
#Sta/Elev= 30
  3681.6  315.21  3695.5  314.18  3785.0  307.26  4098.1  297.59  4405.6  285.27
  4478.2  286.36  4509.0  284.53  4567.7  284.21  4665.5  287.15  4718.6  287.09
  4763.3  285.30  4777.3  286.00  4785.7  284.48  4836.0  282.63  4875.1  279.48
  5006.3  277.22  5009.0  276.72  5012.3  277.22  5063.5  277.69  5198.5  278.53
  5206.2  280.31  5239.7  278.24  5541.2  278.36  5569.6  279.62  5592.9  283.02
  5600.5  285.74  5693.3  299.06  5742.2  309.10  5788.6  312.17  5847.9  312.50
#Mann=6,-1,0
  3681.6    0.05       0  3695.5    0.16       0  5006.3    0.07       0
  5012.3    0.16       0  5063.5    0.12       0  5592.9    0.05       0
Bank Sta=5006.3,5012.3
Exp/Cntr=0.3,0.1

Type RM Length L Ch R = 1,554,0,0,0
BEGIN DESCRIPTION:
UNT 055 IN CACR 1.0
END DESCRIPTION:
XS GIS Cut Line= 3
      3679599.58     10722560.22      3681249.61     10720760.19
      3680849.61     10719960.19
#Sta/Elev= 30
  2543.3  360.62  2727.4  345.78  2882.8  327.56  2970.7  321.41  3017.8  317.71
  3045.6  312.35  3099.2  310.95  3196.2  303.69  3413.7  292.30  3626.4  289.87
  3808.0  282.00  3869.7  281.36  4113.9  280.59  4126.5  281.08  4259.8  281.71
  4369.5  284.55  4624.1  276.83  4819.4  275.48  4822.1  274.98  4825.4  275.48
  5052.3  275.79  5097.0  278.07  5186.4  275.58  5334.6  277.04  5373.7  279.67
  5513.4  277.78  5579.1  280.07  5700.7  290.65  5798.5  303.55  5879.6  306.71
#Mann=12,-1,0
  2543.3    0.05       0  2970.7    0.08       0  3099.2    0.05       0
  3196.2    0.16       0  3808.0    0.12       0  3869.7    0.16       0
  4113.9    0.12       0  4126.5    0.16       0  4259.8    0.12       0
  4819.4    0.07       0  4825.4    0.12       0  5579.1    0.05       0
Bank Sta=4819.4,4825.4
Exp/Cntr=0.3,0.1

Chan Stop Cuts=-1