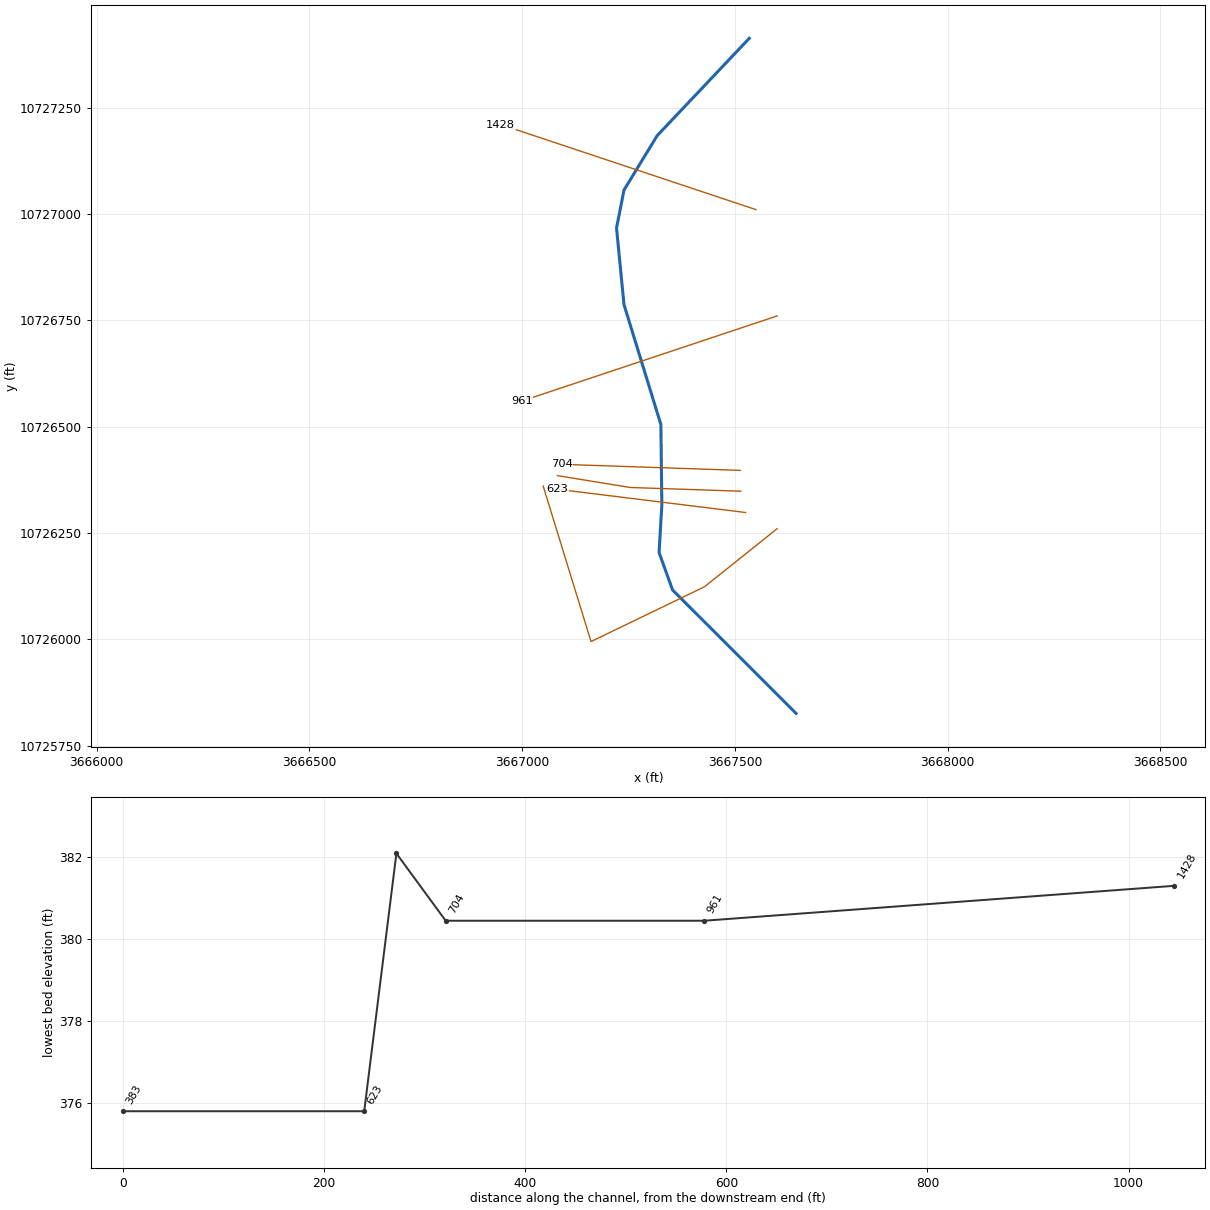
--- UNT 056 IN CACR.prj (project) ---

Proj Title=UNT 056 IN CACR Base Level Engineering
Current Plan=p01
Default Exp/Contr=0.3,0.1
English Units
Geom File=g01
Flow File=f01
Plan File=p01
BEGIN DESCRIPTION:
UNT 056 IN CACR
END DESCRIPTION:

--- UNT 056 IN CACR.p01 (plan) ---

Plan Title=Multiple Run
Short Identifier=Multiple
Geom File=g01
Flow File=f01
Subcritical Flow
K Sum by GR= 0
Std Step Tol= 0.01
Critical Tol= 0.01
Num of Std Step Trials= 20
Max Error Tol= 0.3
Flow Tol Ratio= 0.001
Split Flow NTrial= 30
Split Flow Tol= 0.02
Split Flow Ratio= 0.02
Log Output Level= 0
Friction Slope Method= 1
Unsteady Friction Slope Method= 2
Unsteady Bridges Friction Slope Method= 1
Parabolic Critical Depth
Global Vel Dist=  1 , 1 , 1
Global Log Level= 0
CheckData=True
Encroach Param= -1, 0, 0, 0
BEGIN DESCRIPTION:
Multiple Run
END DESCRIPTION:

--- UNT 056 IN CACR.f01 (steady flow) ---

Flow Title=Multiple
Number of Profiles=7
Profile Names=10-year,25-year,50-year,1pct_min,100-year,1pct_plu,500-year
River Rch & RM= UNT 056 IN CACR,Reach-1,1428
     615     842    1032     929    1256    1699    1864
River Rch & RM= UNT 056 IN CACR,Reach-1,383
     634     869    1064     957    1294    1751    1919
Boundary for River Rch & Prof#=UNT 056 IN CACR,Reach-1,1
Up Type=0
Dn Type=3
Dn Slope=0.005
Boundary for River Rch & Prof#=UNT 056 IN CACR,Reach-1,2
Up Type=0
Dn Type=3
Dn Slope=0.005
Boundary for River Rch & Prof#=UNT 056 IN CACR,Reach-1,3
Up Type=0
Dn Type=3
Dn Slope=0.005
Boundary for River Rch & Prof#=UNT 056 IN CACR,Reach-1,4
Up Type=0
Dn Type=3
Dn Slope=0.005
Boundary for River Rch & Prof#=UNT 056 IN CACR,Reach-1,5
Up Type=0
Dn Type=3
Dn Slope=0.005
Boundary for River Rch & Prof#=UNT 056 IN CACR,Reach-1,6
Up Type=0
Dn Type=3
Dn Slope=0.005
Boundary for River Rch & Prof#=UNT 056 IN CACR,Reach-1,7
Up Type=0
Dn Type=3
Dn Slope=0.005

--- UNT 056 IN CACR.g01 (geometry) ---

Geom Title=Existing Conditions

River Reach=UNT 056 IN CACR,Reach-1
Reach XY= 10
      3667533.95     10727412.76      3667317.50     10727184.00
      3667239.50     10727056.00      3667222.00     10726967.00
      3667239.50     10726787.00      3667326.25     10726505.00
      3667328.50     10726316.00      3667322.00     10726204.00
      3667353.75     10726116.00      3667644.00     10725826.00

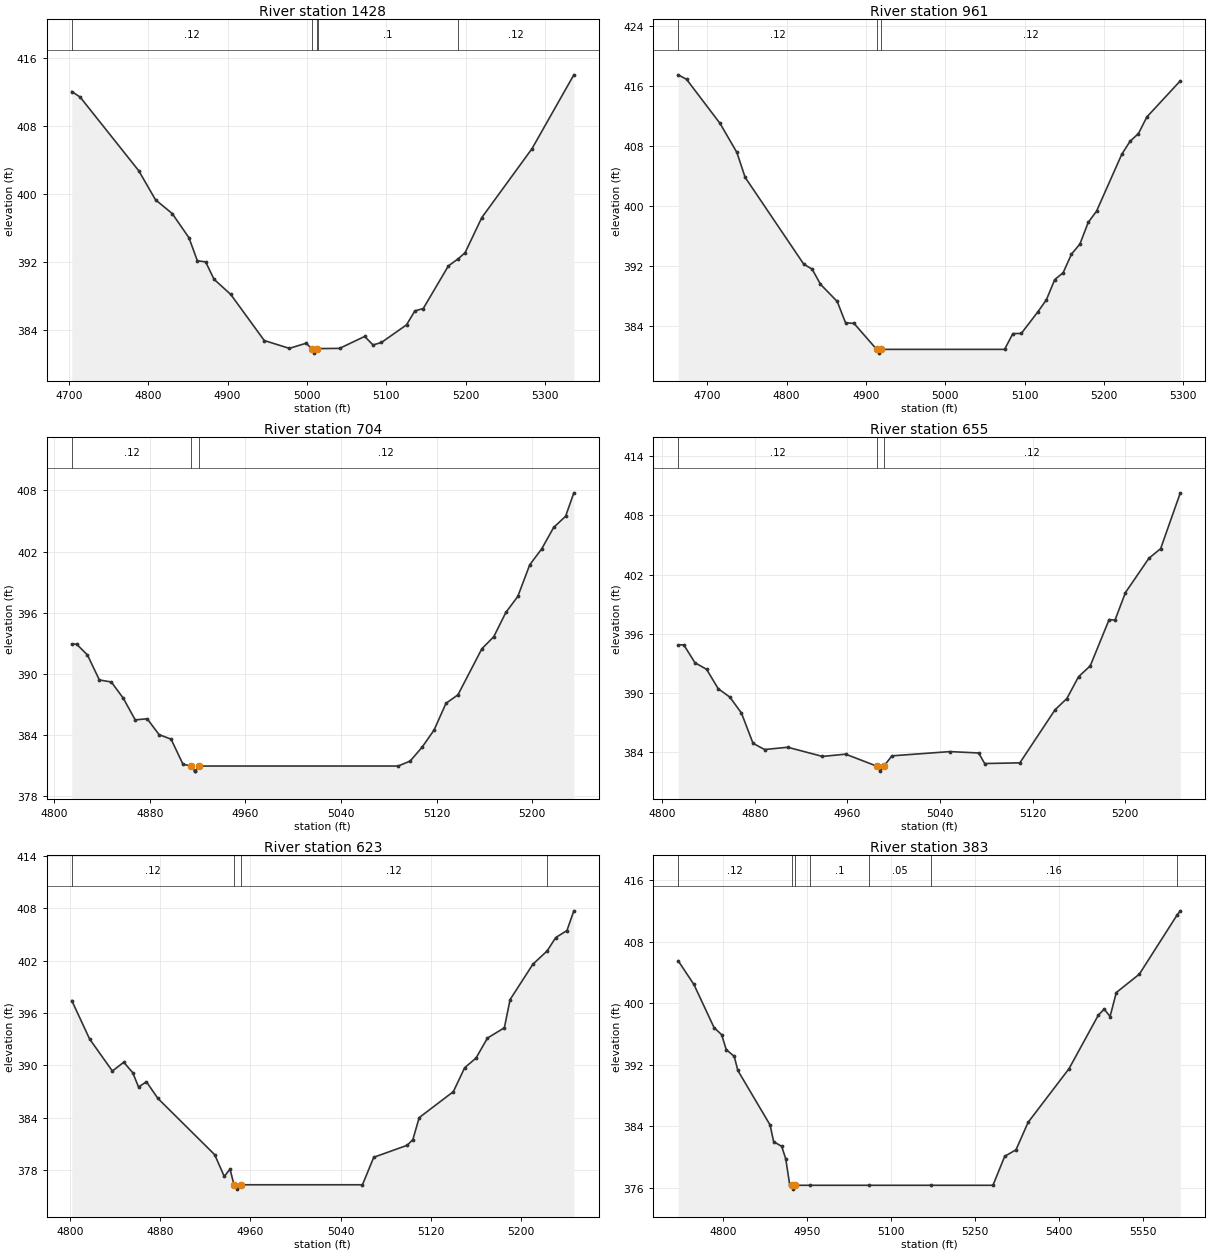
Type RM Length L Ch R = 1,1428,467,467,467
BEGIN DESCRIPTION:
UNT 056 IN CACR 3.0
END DESCRIPTION:
XS GIS Cut Line= 3
      3667549.65     10727010.17      3667249.61     10727110.19
      3666949.61     10727210.19
#Sta/Elev= 30
  4703.8  412.02  4714.4  411.36  4788.2  402.71  4809.3  399.30  4830.3  397.69
  4851.4  394.85  4862.0  392.14  4872.5  392.00  4883.0  389.97  4904.1  388.18
  4946.3  382.77  4977.9  381.85  4999.0  382.45  5006.5  381.79  5009.3  381.29
  5012.5  381.79  5013.4  381.82  5041.2  381.85  5072.8  383.25  5083.3  382.25
  5093.9  382.54  5125.5  384.61  5136.0  386.25  5146.6  386.53  5178.2  391.53
  5190.7  392.38  5199.3  393.09  5220.4  397.22  5283.6  405.31  5336.3  413.98
#Mann=5,-1,0
  4703.8    0.12       0  5006.5    0.07       0  5012.5    0.12       0
  5013.4     0.1       0  5190.7    0.12       0
Bank Sta=5006.5,5012.5
Exp/Cntr=0.3,0.1

Type RM Length L Ch R = 1,961,257,257,257
BEGIN DESCRIPTION:
UNT 056 IN CACR 2.0
END DESCRIPTION:
XS GIS Cut Line= 3
      3667599.61     10726760.19      3667299.61     10726660.19
      3666999.57     10726560.17
#Sta/Elev= 30
  4663.6  417.46  4674.1  416.86  4716.3  410.99  4737.4  407.15  4747.9  403.82
  4821.7  392.28  4832.3  391.61  4842.8  389.60  4863.9  387.31  4874.4  384.47
  4885.0  384.40  4913.6  380.94  4916.3  380.44  4919.6  380.94  5074.7  380.94
  5085.2  383.04  5095.8  383.06  5116.9  385.97  5127.4  387.54  5137.9  390.22
  5148.5  391.14  5159.0  393.61  5169.6  394.95  5180.1  397.83  5190.6  399.33
  5222.3  406.88  5232.8  408.62  5243.4  409.65  5253.9  411.85  5296.1  416.66
#Mann=3,-1,0
  4663.6    0.12       0  4913.6    0.07       0  4919.6    0.12       0
Bank Sta=4913.6,4919.6
Exp/Cntr=0.3,0.1

Type RM Length L Ch R = 1,704,49,49,49
BEGIN DESCRIPTION:
Mapping XS 5648b540
END DESCRIPTION:
XS GIS Cut Line= 2
      3667512.65     10726397.19      3667092.69     10726411.45
#Sta/Elev= 30
  4814.7  392.91  4818.7  392.91  4827.8  391.85  4837.8  389.39  4847.8  389.19
  4857.8  387.60  4867.8  385.47  4877.8  385.58  4887.8  384.02  4897.8  383.58
  4907.8  381.11  4914.8  380.94  4917.6  380.44  4918.1  380.44  4920.8  380.94
  5087.9  380.94  5097.9  381.43  5107.9  382.79  5117.9  384.47  5127.9  387.10
  5137.9  387.93  5157.9  392.45  5167.9  393.64  5178.0  396.02  5188.0  397.59
  5198.0  400.70  5208.0  402.26  5218.0  404.36  5228.0  405.46  5234.9  407.76
#Mann=3,-1,0
  4814.7    0.12       0  4914.8    0.07       0  4920.8    0.12       0
Bank Sta=4914.8,4920.8
Exp/Cntr=0.3,0.1

Type RM Length L Ch R = 1,655,32,32,32
BEGIN DESCRIPTION:
Mapping XS b6f3adda
END DESCRIPTION:
XS GIS Cut Line= 3
      3667514.14     10726348.25      3667254.76     10726356.94
      3667082.84     10726384.87
#Sta/Elev= 30
  4813.8  394.88  4818.6  394.88  4828.3  393.06  4838.3  392.40  4848.3  390.44
  4858.4  389.58  4868.4  387.97  4878.4  384.90  4888.4  384.27  4908.4  384.50
  4938.4  383.57  4958.4  383.80  4985.4  382.58  4988.2  382.08  4991.4  382.58
  4998.4  383.63  5048.5  384.06  5073.3  383.92  5078.5  382.85  5108.9  382.92
  5139.3  388.30  5149.5  389.44  5159.6  391.65  5169.7  392.75  5186.0  397.44
  5191.1  397.39  5200.1  400.18  5220.4  403.66  5230.5  404.63  5247.5  410.29
#Mann=3,-1,0
  4813.8    0.12       0  4985.4    0.07       0  4991.4    0.12       0
Bank Sta=4985.4,4991.4
Exp/Cntr=0.3,0.1

Type RM Length L Ch R = 1,623,240,240,240
BEGIN DESCRIPTION:
Mapping XS 90b302b7
END DESCRIPTION:
XS GIS Cut Line= 2
      3667525.33     10726298.18      3667083.58     10726352.75
#Sta/Elev= 30
  4801.6  397.42  4817.4  393.02  4837.6  389.34  4847.7  390.35  4855.7  389.14
  4860.8  387.51  4867.8  388.11  4877.9  386.21  4928.3  379.75  4936.8  377.25
  4941.9  378.10  4945.4  376.30  4948.2  375.80  4951.4  376.30  5059.3  376.30
  5069.3  379.45  5099.0  380.83  5104.0  381.49  5109.6  384.00  5139.9  386.98
  5149.9  389.72  5160.0  390.83  5170.1  393.12  5185.1  394.30  5190.2  397.54
  5210.4  401.59  5223.1  403.12  5230.6  404.64  5240.6  405.45  5246.7  407.71
#Mann=4,-1,0
  4801.6    0.12       0  4945.4    0.07       0  4951.4    0.12       0
  5223.1    0.16       0
Bank Sta=4945.4,4951.4
Exp/Cntr=0.3,0.1

Type RM Length L Ch R = 1,383,0,0,0
BEGIN DESCRIPTION:
UNT 056 IN CACR 1.0
END DESCRIPTION:
XS GIS Cut Line= 4
      3667599.61     10726260.19      3667428.96     10726123.70
      3667162.04     10725994.80      3667049.62     10726360.15
#Sta/Elev= 30
  4719.4  405.50  4747.4  402.43  4783.4  396.82  4797.0  395.89  4805.1  393.96
  4819.5  393.07  4825.9  391.24  4883.5  384.15  4889.9  381.98  4904.3  381.36
  4911.5  379.74  4918.7  376.32  4922.1  376.30  4924.9  375.80  4928.1  376.30
  4955.6  376.30  5060.1  376.30  5171.4  376.30  5281.8  376.30  5302.8  380.07
  5323.0  380.92  5344.6  384.49  5417.8  391.48  5470.2  398.45  5480.6  399.22
  5491.1  398.26  5502.2  401.38  5543.4  403.77  5610.5  411.43  5616.6  412.01
#Mann=7,-1,0
  4719.4    0.12       0  4922.1    0.07       0  4928.1    0.12       0
  4955.6     0.1       0  5060.1    0.05       0  5171.4    0.16       0
  5610.5    0.12       0
Bank Sta=4922.1,4928.1
Exp/Cntr=0.3,0.1

Chan Stop Cuts=-1