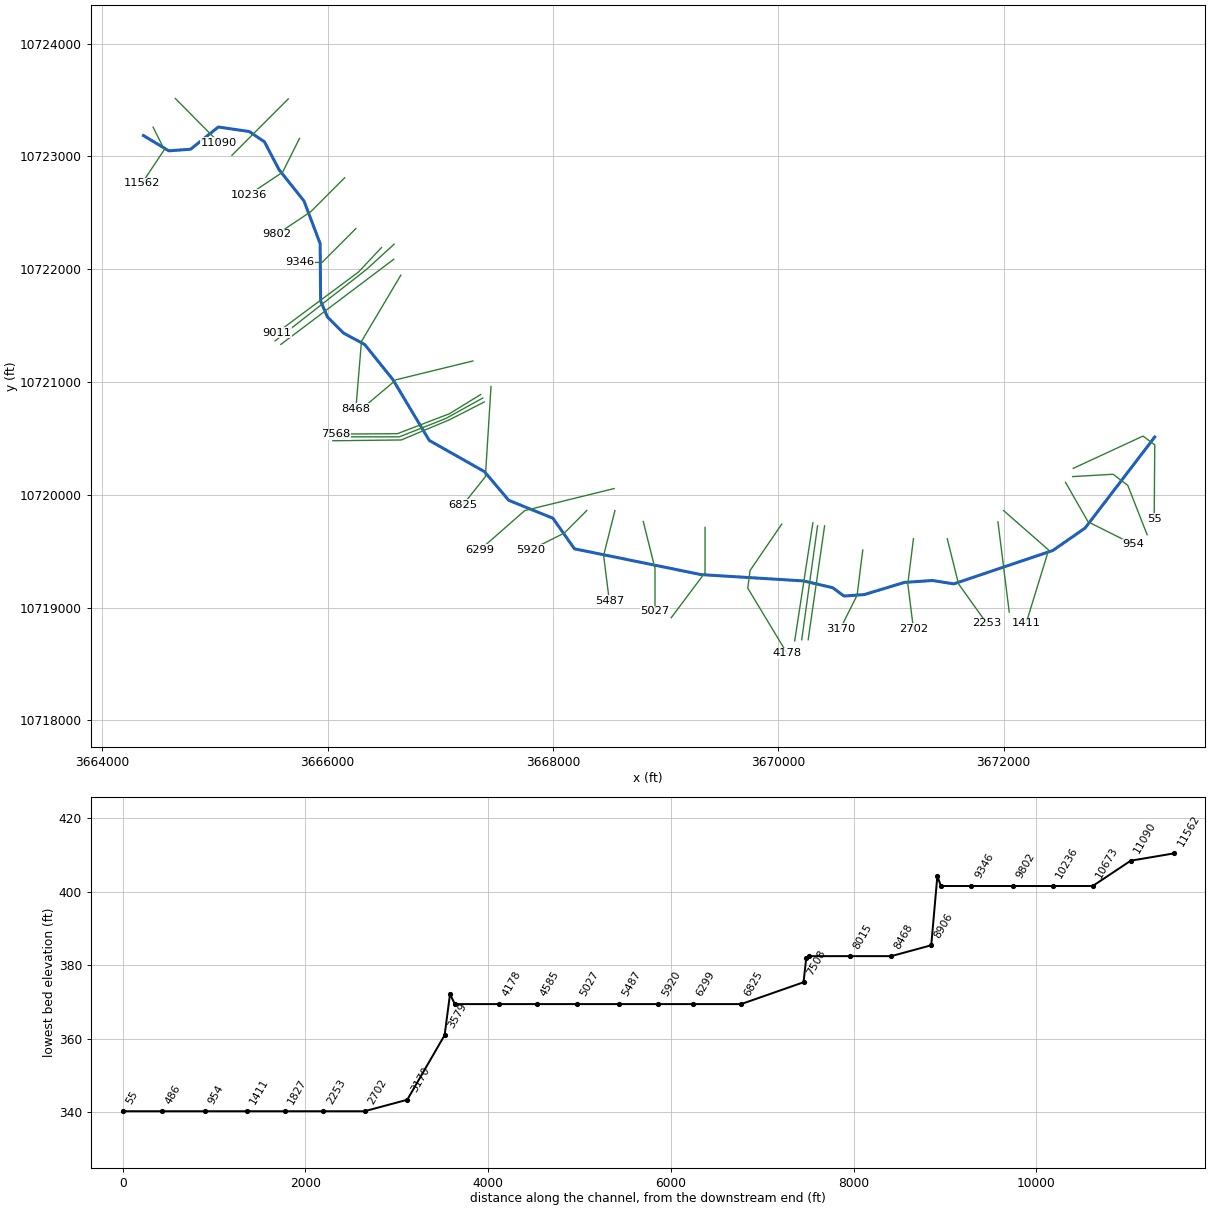
--- UNT 057 IN CACR.prj (project) ---

Proj Title=UNT 057 IN CACR Base Level Engineering
Current Plan=p01
Default Exp/Contr=0.3,0.1
English Units
Geom File=g01
Flow File=f01
Plan File=p01
BEGIN DESCRIPTION:
UNT 057 IN CACR
END DESCRIPTION:

--- UNT 057 IN CACR.p01 (plan) ---

Plan Title=Multiple Run
Short Identifier=Multiple
Geom File=g01
Flow File=f01
Subcritical Flow
K Sum by GR= 0
Std Step Tol= 0.01
Critical Tol= 0.01
Num of Std Step Trials= 20
Max Error Tol= 0.3
Flow Tol Ratio= 0.001
Split Flow NTrial= 30
Split Flow Tol= 0.02
Split Flow Ratio= 0.02
Log Output Level= 0
Friction Slope Method= 1
Unsteady Friction Slope Method= 2
Unsteady Bridges Friction Slope Method= 1
Parabolic Critical Depth
Global Vel Dist=  1 , 1 , 1
Global Log Level= 0
CheckData=True
Encroach Param= -1, 0, 0, 0
BEGIN DESCRIPTION:
Multiple Run
END DESCRIPTION:

--- UNT 057 IN CACR.f01 (steady flow) ---

Flow Title=Multiple
Number of Profiles=7
Profile Names=10-year,25-year,50-year,1pct_min,100-year,1pct_plu,500-year
River Rch & RM= UNT 057 IN CACR,Reach-1,11562
     553     753     919     824    1115    1508    1644
River Rch & RM= UNT 057 IN CACR,Reach-1,7568
     910    1282    1601    1468    1985    2685    3061
River Rch & RM= UNT 057 IN CACR,Reach-1,6825
     977    1373    1711    1564    2115    2860    3242
River Rch & RM= UNT 057 IN CACR,Reach-1,4178
    1145    1625    2037    1873    2533    3425    3929
River Rch & RM= UNT 057 IN CACR,Reach-1,954
    1152    1629    2037    1868    2527    3417    3901
Boundary for River Rch & Prof#=UNT 057 IN CACR,Reach-1,1
Up Type=0
Dn Type=3
Dn Slope=0.005
Boundary for River Rch & Prof#=UNT 057 IN CACR,Reach-1,2
Up Type=0
Dn Type=3
Dn Slope=0.005
Boundary for River Rch & Prof#=UNT 057 IN CACR,Reach-1,3
Up Type=0
Dn Type=3
Dn Slope=0.005
Boundary for River Rch & Prof#=UNT 057 IN CACR,Reach-1,4
Up Type=0
Dn Type=3
Dn Slope=0.005
Boundary for River Rch & Prof#=UNT 057 IN CACR,Reach-1,5
Up Type=0
Dn Type=3
Dn Slope=0.005
Boundary for River Rch & Prof#=UNT 057 IN CACR,Reach-1,6
Up Type=0
Dn Type=3
Dn Slope=0.005
Boundary for River Rch & Prof#=UNT 057 IN CACR,Reach-1,7
Up Type=0
Dn Type=3
Dn Slope=0.005

--- UNT 057 IN CACR.g01 (geometry) ---

Geom Title=Existing Conditions

River Reach=UNT 057 IN CACR,Reach-1
Reach XY= 30
      3664364.50     10723185.00      3664589.25     10723050.00
      3664782.50     10723064.00      3665028.50     10723261.00
      3665303.25     10723221.00      3665438.00     10723130.00
      3665568.00     10722882.00      3665789.50     10722605.00
      3665932.75     10722227.00      3665937.00     10721719.00
      3665997.75     10721576.00      3666141.00     10721433.00
      3666327.75     10721333.00      3666578.00     10721022.00
      3666901.25     10720482.00      3667391.50     10720205.00
      3667606.75     10719951.00      3667999.00     10719792.00
      3668190.00     10719521.00      3669315.00     10719292.00
      3670224.75     10719236.00      3670482.50     10719176.00
      3670583.50     10719102.00      3670762.75     10719115.00
      3671119.75     10719223.00      3671368.00     10719240.00
      3671557.25     10719210.00      3672437.00     10719506.00
      3672723.50     10719705.00      3673341.25     10720512.00

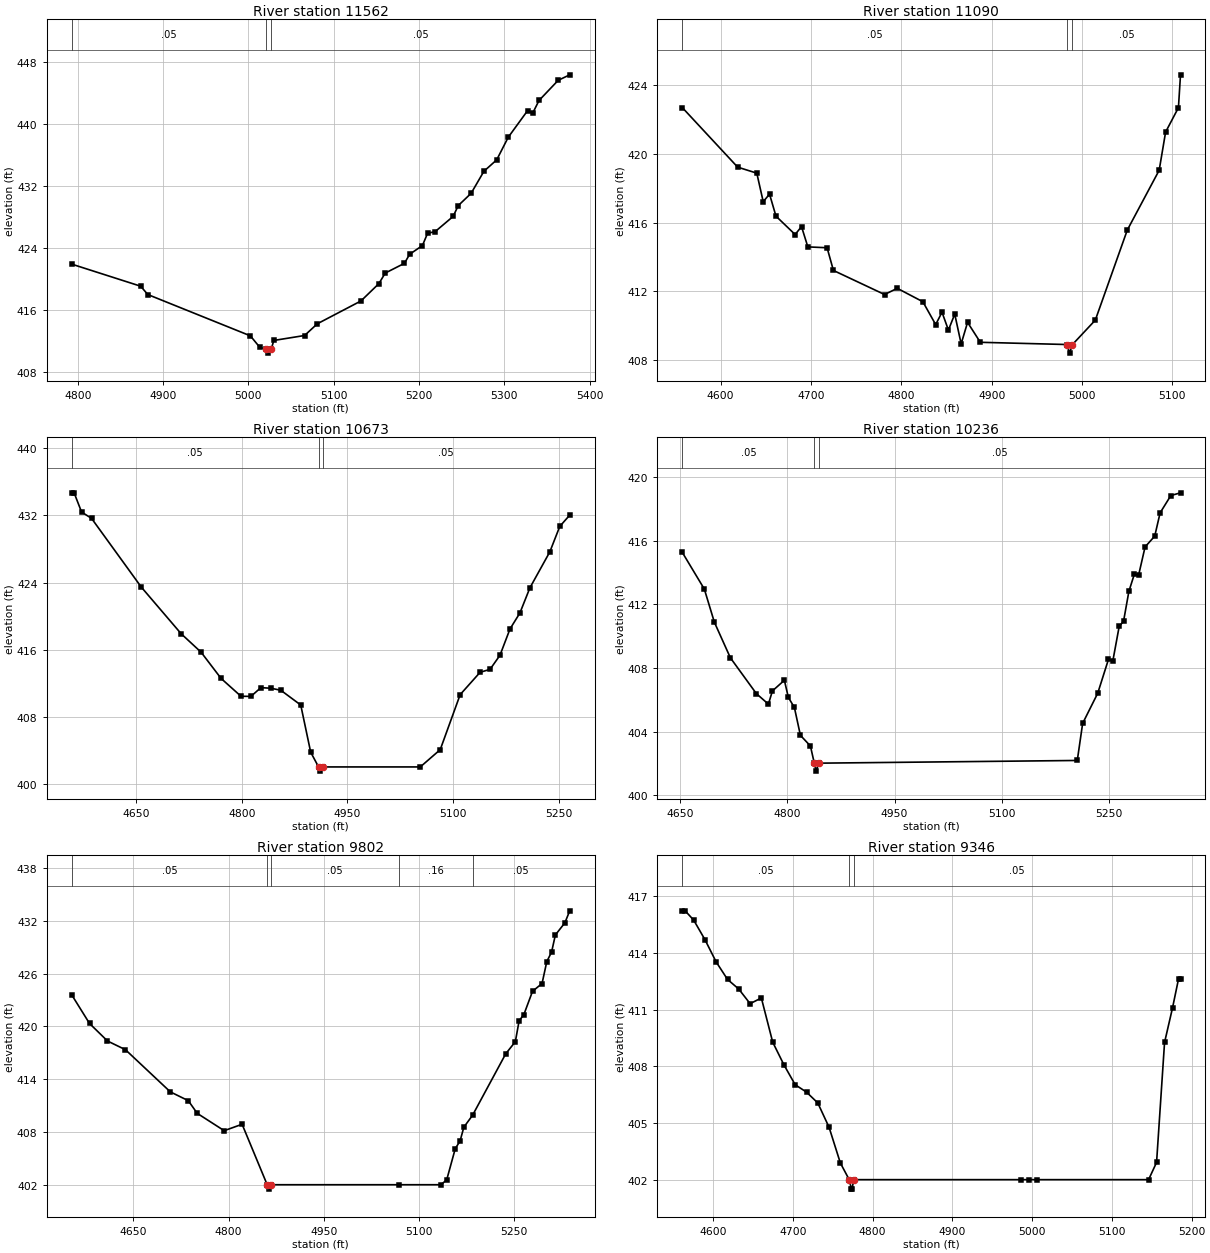
Type RM Length L Ch R = 1,11562,472,472,472
BEGIN DESCRIPTION:
Mapping XS 3fa41f84
END DESCRIPTION:
XS GIS Cut Line= 3
      3664449.62     10723260.17      3664549.61     10723060.19
      3664349.63     10722760.22
#Sta/Elev= 30
  4792.7  421.91  4873.7  419.05  4882.1  417.97  5002.3  412.63  5013.5  411.13
  5020.8  410.89  5023.5  410.39  5026.8  410.89  5029.8  412.03  5065.9  412.67
  5080.9  414.19  5132.0  417.14  5153.0  419.38  5160.5  420.75  5183.0  422.01
  5189.1  423.18  5204.1  424.31  5210.1  425.89  5219.1  426.12  5240.1  428.08
  5246.1  429.48  5261.2  431.07  5276.2  433.92  5291.2  435.40  5304.7  438.32
  5327.3  441.75  5333.3  441.42  5340.8  443.08  5363.3  445.69  5376.8  446.40
#Mann=3,-1,0
  4792.7    0.05       0  5020.8    0.03       0  5026.8    0.05       0
Bank Sta=5020.8,5026.8
Exp/Cntr=0.3,0.1

Type RM Length L Ch R = 1,11090,417,417,417
BEGIN DESCRIPTION:
Mapping XS 691cfdc2
END DESCRIPTION:
XS GIS Cut Line= 2
      3664647.10     10723514.15      3665035.26     10723122.52
#Sta/Elev= 30
  4557.6  422.69  4618.8  419.23  4640.0  418.88  4647.1  417.22  4654.1  417.66
  4661.2  416.38  4682.4  415.31  4689.5  415.77  4696.5  414.59  4717.8  414.54
  4724.8  413.22  4781.4  411.82  4795.5  412.18  4823.8  411.40  4838.0  410.07
  4845.0  410.79  4852.1  409.75  4859.1  410.68  4866.2  408.95  4873.3  410.20
  4887.4  409.04  4983.4  408.91  4986.2  408.41  4989.4  408.91  5014.7  410.33
  5050.1  415.57  5085.4  419.05  5092.5  421.27  5106.7  422.69  5109.0  424.60
#Mann=3,-1,0
  4557.6    0.05       0  4983.4    0.03       0  4989.4    0.05       0
Bank Sta=4983.4,4989.4
Exp/Cntr=0.3,0.1

Type RM Length L Ch R = 1,10673,437,437,437
BEGIN DESCRIPTION:
UNT 057 IN CACR 24.0
END DESCRIPTION:
XS GIS Cut Line= 3
      3665649.63     10723510.21      3665349.61     10723210.19
      3665149.64     10723010.22
#Sta/Elev= 30
  4558.4  434.69  4562.0  434.69  4572.6  432.40  4586.7  431.65  4657.4  423.45
  4714.0  417.89  4742.3  415.69  4770.6  412.57  4798.9  410.44  4813.0  410.43
  4827.1  411.47  4841.3  411.40  4855.4  411.16  4883.7  409.40  4897.8  403.78
  4909.0  402.02  4911.7  401.52  4915.0  402.02  5053.4  402.02  5081.7  404.08
  5110.0  410.64  5138.3  413.30  5152.4  413.65  5166.5  415.33  5180.7  418.46
  5194.8  420.37  5209.0  423.37  5237.3  427.66  5251.4  430.69  5265.5  432.03
#Mann=3,-1,0
  4558.4    0.05       0  4909.0   0.035       0  4915.0    0.05       0
Bank Sta=4909,4915
Exp/Cntr=0.3,0.1

Type RM Length L Ch R = 1,10236,434,434,434
BEGIN DESCRIPTION:
UNT 057 IN CACR 23.0
END DESCRIPTION:
XS GIS Cut Line= 3
      3665749.60     10723160.17      3665599.61     10722860.19
      3665299.65     10722660.22
#Sta/Elev= 30
  4653.5  415.26  4684.2  412.96  4698.2  410.88  4720.6  408.64  4756.9  406.39
  4773.7  405.73  4779.3  406.56  4796.0  407.23  4801.6  406.15  4810.0  405.52
  4818.4  403.77  4832.4  403.10  4837.8  402.02  4840.5  401.52  4843.8  402.02
  5205.2  402.19  5212.7  404.52  5233.8  406.42  5248.8  408.55  5254.8  408.43
  5263.8  410.63  5269.8  410.93  5277.3  412.82  5284.8  413.88  5290.9  413.84
  5299.9  415.61  5313.4  416.29  5320.9  417.75  5335.9  418.84  5349.4  419.01
#Mann=3,-1,0
  4653.5    0.05       0  4837.8   0.033       0  4843.8    0.05       0
Bank Sta=4837.8,4843.8
Exp/Cntr=0.3,0.1

Type RM Length L Ch R = 1,9802,456,456,456
BEGIN DESCRIPTION:
UNT 057 IN CACR 22.0
END DESCRIPTION:
XS GIS Cut Line= 3
      3666149.64     10722810.22      3665849.61     10722510.19
      3665549.57     10722310.16
#Sta/Elev= 30
  4552.5  423.62  4580.8  420.34  4609.1  418.35  4637.4  417.36  4708.1  412.57
  4736.4  411.57  4750.5  410.13  4793.0  408.16  4821.2  408.89  4860.7  402.02
  4863.4  401.52  4866.7  402.02  5068.4  402.02  5134.5  402.02  5143.6  402.58
  5157.1  406.13  5164.6  406.98  5170.6  408.56  5184.3  409.91  5236.7  416.91
  5251.7  418.27  5257.7  420.65  5265.2  421.36  5278.8  424.00  5293.8  424.88
  5301.3  427.38  5308.8  428.45  5314.8  430.40  5329.8  431.78  5337.4  433.14
#Mann=5,-1,0
  4552.5    0.05       0  4860.7   0.033       0  4866.7    0.05       0
  5068.4    0.16       0  5184.3    0.05       0
Bank Sta=4860.7,4866.7
Exp/Cntr=0.3,0.1

Type RM Length L Ch R = 1,9346,335,335,335
BEGIN DESCRIPTION:
UNT 057 IN CACR 21.0
END DESCRIPTION:
XS GIS Cut Line= 3
      3666249.62     10722360.20      3665949.61     10722060.19
      3665749.59     10722060.19
#Sta/Elev= 29
  4561.7  416.21  4565.2  416.21  4575.9  415.72  4590.0  414.69  4604.1  413.51
  4618.3  412.59  4632.4  412.08  4646.6  411.31  4660.7  411.61  4674.9  409.28
  4689.0  408.08  4703.1  407.03  4717.3  406.64  4731.4  406.07  4745.6  404.78
  4759.7  402.90  4770.8  402.02  4773.6  401.52  4774.1  401.52  4776.8  402.02
  4986.0  402.02  4996.0  402.02  5006.0  402.02  5146.0  402.02  5156.0  402.93
  5166.0  409.26  5176.0  411.09  5183.5  412.61  5186.0  412.61
#Mann=3,-1,0
  4561.7    0.05       0  4770.8   0.033       0  4776.8    0.05       0
Bank Sta=4770.8,4776.8
Exp/Cntr=0.3,0.1

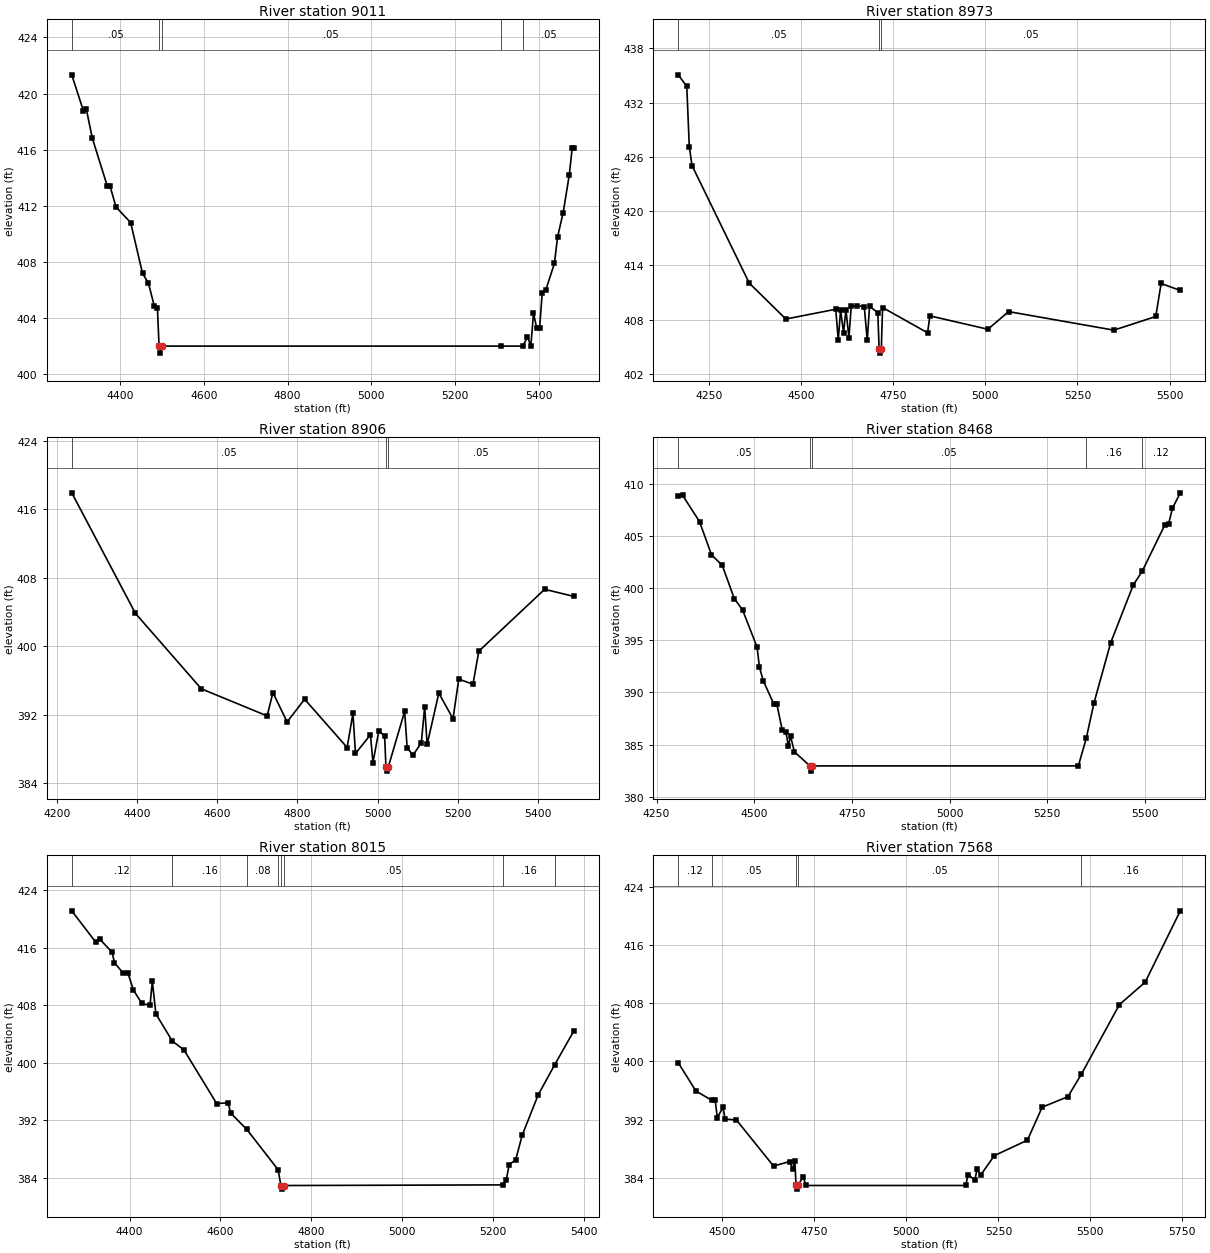
Type RM Length L Ch R = 1,9011,38,38,38
BEGIN DESCRIPTION:
Mapping XS b3060719
END DESCRIPTION:
XS GIS Cut Line= 3
      3666477.11     10722192.02      3666273.13     10721975.02
      3665548.31     10721436.83
#Sta/Elev= 30
  4283.7  421.34  4311.7  418.76  4318.5  418.90  4332.7  416.84  4368.3  413.45
  4375.2  413.42  4389.4  411.93  4424.5  410.82  4452.9  407.20  4467.0  406.51
  4481.2  404.85  4488.5  404.75  4492.4  402.02  4495.1  401.52  4498.4  402.02
  5309.8  402.02  5362.8  402.02  5373.2  402.68  5381.6  402.05  5387.8  404.35
  5395.5  403.32  5402.5  403.34  5408.7  405.79  5417.1  406.00  5437.9  407.92
  5445.3  409.78  5458.8  411.53  5473.4  414.21  5480.4  416.15  5484.3  416.15
#Mann=5,-1,0
  4283.7    0.05       0  4492.4    0.03       0  4498.4    0.05       0
  5309.8    0.16       0  5362.8    0.05       0
Bank Sta=4492.4,4498.4
Exp/Cntr=0.3,0.1

Type RM Length L Ch R = 1,8973,67,67,67
BEGIN DESCRIPTION:
Mapping XS c634a58e
END DESCRIPTION:
XS GIS Cut Line= 3
      3666589.99     10722222.44      3666342.57     10721996.72
      3665532.30     10721364.10
#Sta/Elev= 30
  4166.3  435.06  4189.5  433.78  4196.3  427.12  4203.7  425.03  4359.1  412.03
  4458.4  408.06  4593.8  409.14  4600.7  405.75  4607.0  409.05  4615.1  406.55
  4621.5  409.10  4629.6  406.00  4635.9  409.47  4650.4  409.54  4671.2  409.44
  4679.3  405.73  4685.7  409.46  4708.0  408.77  4711.6  404.79  4714.4  404.29
  4717.6  404.79  4721.0  409.33  4843.1  406.54  4849.4  408.41  5006.8  406.93
  5063.2  408.88  5348.7  406.83  5462.6  408.34  5477.1  411.99  5529.2  411.22
#Mann=3,-1,0
  4166.3    0.05       0  4711.6    0.03       0  4717.6    0.05       0
Bank Sta=4711.6,4717.6
Exp/Cntr=0.3,0.1

Type RM Length L Ch R = 1,8906,438,438,438
BEGIN DESCRIPTION:
UNT 057 IN CACR 20.0
END DESCRIPTION:
XS GIS Cut Line= 2
      3666585.62     10722087.86      3665583.82     10721333.25
#Sta/Elev= 30
  4236.2  417.92  4395.2  403.84  4559.7  395.03  4724.2  391.86  4738.7  394.58
  4774.1  391.16  4817.9  393.81  4924.1  388.17  4938.6  392.16  4944.9  387.47
  4982.3  389.66  4988.6  386.40  5003.2  390.10  5017.7  389.52  5021.0  385.91
  5023.7  385.41  5027.0  385.91  5067.7  392.38  5074.0  388.15  5088.5  387.27
  5109.4  388.72  5117.7  392.93  5123.9  388.53  5153.1  394.52  5188.5  391.53
  5203.0  396.16  5238.4  395.56  5253.0  399.42  5417.5  406.65  5490.4  405.82
#Mann=3,-1,0
  4236.2    0.05       0  5021.0    0.03       0  5027.0    0.05       0
Bank Sta=5021,5027
Exp/Cntr=0.3,0.1

Type RM Length L Ch R = 1,8468,453,453,453
BEGIN DESCRIPTION:
Mapping XS bbfeb395
END DESCRIPTION:
XS GIS Cut Line= 3
      3666648.81     10721947.01      3666299.61     10721360.19
      3666249.61     10720760.23
#Sta/Elev= 30
  4305.5  408.85  4316.5  408.89  4360.0  406.36  4390.5  403.19  4418.2  402.17
  4448.9  398.99  4470.3  397.88  4507.3  394.33  4513.2  392.44  4522.9  391.13
  4550.2  388.87  4557.8  388.88  4571.6  386.38  4581.1  386.21  4587.2  384.88
  4593.0  385.79  4602.8  384.30  4642.6  382.95  4645.4  382.45  4648.6  382.95
  5329.5  382.95  5349.7  385.60  5369.7  389.02  5412.3  394.76  5470.0  400.29
  5492.7  401.59  5550.3  406.01  5560.3  406.14  5570.4  407.65  5590.4  409.12
#Mann=5,-1,0
  4305.5    0.05       0  4642.6   0.033       0  4648.6    0.05       0
  5349.7    0.16       0  5492.7    0.12       0
Bank Sta=4642.6,4648.6
Exp/Cntr=0.3,0.1

Type RM Length L Ch R = 1,8015,447,447,447
BEGIN DESCRIPTION:
Mapping XS 95c52d29
END DESCRIPTION:
XS GIS Cut Line= 3
      3667289.44     10721186.62      3666607.16     10721019.95
      3666299.62     10720760.20
#Sta/Elev= 30
  4272.7  421.13  4325.0  416.81  4334.3  417.20  4361.5  415.37  4366.7  413.91
  4385.8  412.47  4396.1  412.53  4408.3  410.12  4426.9  408.27  4444.8  407.99
  4450.0  411.32  4457.8  406.81  4493.9  403.03  4519.6  401.80  4591.6  394.34
  4616.6  394.45  4622.5  393.01  4658.0  390.74  4726.9  385.14  4732.8  382.95
  4735.5  382.45  4738.8  382.95  5221.9  383.04  5228.7  383.68  5235.3  385.86
  5249.6  386.52  5263.9  389.93  5299.1  395.55  5335.5  399.74  5377.6  404.44
#Mann=8,-1,0
  4272.7    0.12       0  4493.9    0.16       0  4658.0    0.08       0
  4726.9    0.05       0  4732.8   0.033       0  4738.8    0.05       0
  5221.9    0.16       0  5335.5    0.12       0
Bank Sta=4732.8,4738.8
Exp/Cntr=0.3,0.1

Type RM Length L Ch R = 1,7568,30,30,30
BEGIN DESCRIPTION:
UNT 057 IN CACR 17.0
END DESCRIPTION:
XS GIS Cut Line= 4
      3667358.19     10720888.79      3667080.42     10720718.65
      3666618.61     10720541.57      3666074.05     10720538.10
#Sta/Elev= 30
  4379.7  399.81  4427.8  395.92  4470.4  394.66  4480.0  394.71  4485.9  392.27
  4501.3  393.68  4507.2  392.07  4538.0  391.94  4638.7  385.62  4682.9  386.24
  4690.9  385.17  4696.7  386.25  4700.0  382.95  4702.7  382.45  4706.0  382.95
  4718.7  384.16  4727.7  382.95  5161.7  382.95  5167.1  384.44  5186.4  383.71
  5191.8  385.19  5202.0  384.39  5239.0  387.05  5329.0  389.17  5369.0  393.70
  5439.0  395.14  5475.8  398.24  5579.0  407.78  5649.0  410.86  5744.6  420.66
#Mann=5,-1,0
  4379.7    0.12       0  4470.4    0.05       0  4700.0   0.033       0
  4706.0    0.05       0  5475.8    0.16       0
Bank Sta=4700,4706
Exp/Cntr=0.3,0.1

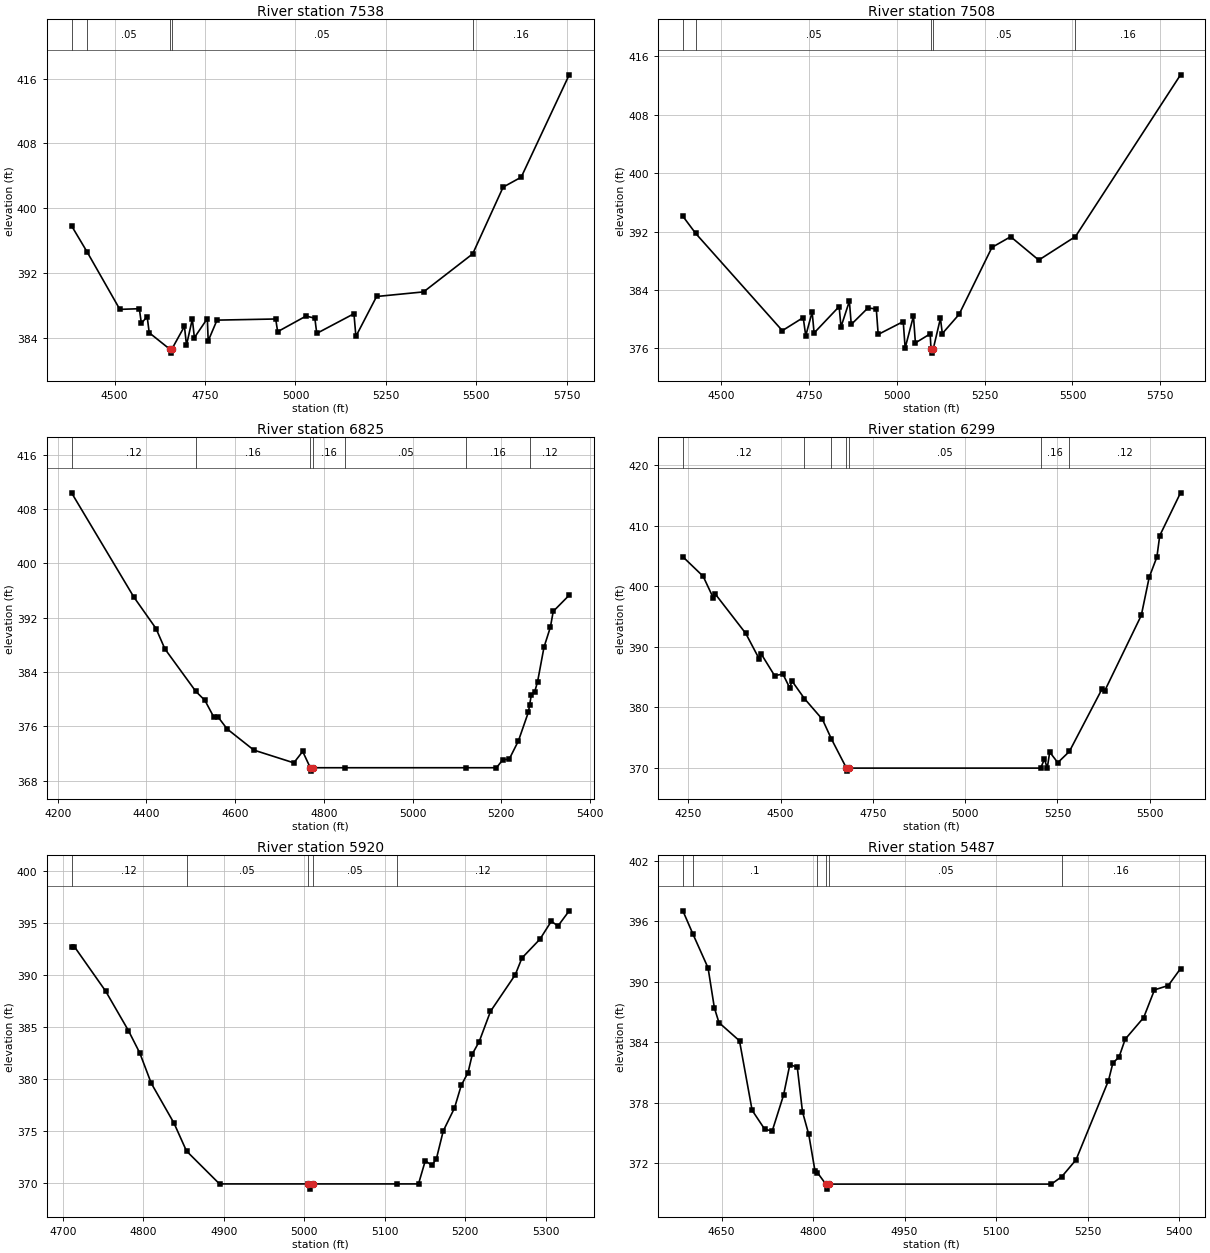
Type RM Length L Ch R = 1,7538,30,30,30
BEGIN DESCRIPTION:
Mapping XS 8156bc90
END DESCRIPTION:
XS GIS Cut Line= 4
      3667375.57     10720857.55      3667049.17     10720676.98
      3666635.98     10720513.79      3666076.94     10720513.79
#Sta/Elev= 30
  4380.8  397.81  4424.2  394.55  4514.3  387.48  4568.2  387.56  4573.9  385.75
  4589.9  386.59  4595.6  384.59  4652.2  382.57  4655.0  382.07  4658.2  382.57
  4693.0  385.38  4698.7  383.05  4714.8  386.28  4720.5  383.98  4756.3  386.34
  4758.7  383.58  4783.1  386.15  4945.4  386.29  4950.8  384.72  5029.2  386.65
  5053.6  386.39  5059.0  384.51  5161.8  386.94  5167.2  384.14  5224.4  389.07
  5354.4  389.64  5490.2  394.34  5574.4  402.59  5624.4  403.82  5757.1  416.47
#Mann=5,-1,0
  4380.8    0.12       0  4424.2    0.05       0  4652.2   0.033       0
  4658.2    0.05       0  5490.2    0.16       0
Bank Sta=4652.2,4658.2
Exp/Cntr=0.3,0.1

Type RM Length L Ch R = 1,7508,683,683,683
BEGIN DESCRIPTION:
UNT 057 IN CACR 16.0
END DESCRIPTION:
XS GIS Cut Line= 4
      3667389.43     10720822.81      3667083.89     10720666.57
      3666653.34     10720486.01      3666045.73     10720479.07
#Sta/Elev= 30
  4390.2  394.10  4426.7  391.75  4673.5  378.43  4733.0  380.22  4740.2  377.74
  4758.5  380.98  4764.0  378.11  4835.3  381.73  4840.7  378.95  4864.5  382.46
  4869.9  379.28  4917.4  381.54  4941.2  381.40  4946.6  377.91  5017.9  379.67
  5023.4  376.05  5047.1  380.43  5052.6  376.75  5094.7  377.99  5097.1  375.85
  5099.9  375.35  5103.1  375.85  5123.9  380.12  5129.3  378.03  5176.9  380.65
  5270.7  389.84  5324.0  391.30  5404.0  388.10  5508.5  391.32  5807.9  413.48
#Mann=5,-1,0
  4390.2    0.12       0  4426.7    0.05       0  5097.1    0.03       0
  5103.1    0.05       0  5508.5    0.16       0
Bank Sta=5097.1,5103.1
Exp/Cntr=0.3,0.1

Type RM Length L Ch R = 1,6825,526,526,526
BEGIN DESCRIPTION:
UNT 057 IN CACR 15.0
END DESCRIPTION:
XS GIS Cut Line= 3
      3667449.61     10720960.21      3667399.61     10720160.19
      3667199.64     10719910.22
#Sta/Elev= 30
  4231.3  410.40  4371.6  395.06  4421.7  390.41  4441.7  387.41  4511.3  381.16
  4531.9  379.83  4551.9  377.37  4562.0  377.34  4582.0  375.62  4642.1  372.51
  4732.3  370.63  4752.3  372.31  4769.4  369.91  4772.1  369.41  4775.4  369.91
  4847.6  369.91  5120.6  369.91  5189.0  369.91  5203.4  371.09  5217.8  371.17
  5238.6  373.88  5261.0  378.10  5263.8  379.17  5267.4  380.55  5275.4  381.13
  5281.8  382.61  5296.2  387.67  5310.6  390.62  5317.0  392.94  5353.0  395.32
#Mann=7,-1,0
  4231.3    0.12       0  4511.3    0.16       0  4769.4   0.033       0
  4775.4    0.16       0  4847.6    0.05       0  5120.6    0.16       0
  5263.8    0.12       0
Bank Sta=4769.4,4775.4
Exp/Cntr=0.3,0.1

Type RM Length L Ch R = 1,6299,379,379,379
BEGIN DESCRIPTION:
Mapping XS b828f849
END DESCRIPTION:
XS GIS Cut Line= 3
      3668542.91     10720055.25      3667749.61     10719860.19
      3667349.64     10719510.21
#Sta/Elev= 30
  4235.1  404.85  4290.0  401.63  4317.4  398.06  4322.6  398.72  4405.6  392.17
  4442.0  387.95  4447.2  388.80  4483.6  385.20  4506.2  385.46  4525.1  383.11
  4530.3  384.35  4564.5  381.40  4613.3  377.96  4637.4  374.75  4678.3  369.91
  4681.1  369.41  4684.3  369.91  5204.5  369.91  5214.8  371.40  5222.4  369.91
  5229.0  372.57  5250.9  370.81  5282.3  372.66  5370.9  383.01  5378.1  382.69
  5477.2  395.17  5498.6  401.46  5519.5  404.83  5527.1  408.34  5583.5  415.43
#Mann=7,-1,0
  4235.1    0.12       0  4564.5    0.16       0  4637.4    0.05       0
  4678.3   0.033       0  4684.3    0.05       0  5204.5    0.16       0
  5282.3    0.12       0
Bank Sta=4678.3,4684.3
Exp/Cntr=0.3,0.1

Type RM Length L Ch R = 1,5920,433,433,433
BEGIN DESCRIPTION:
Mapping XS 5172c94b
END DESCRIPTION:
XS GIS Cut Line= 3
      3668299.60     10719860.18      3668099.61     10719660.19
      3667799.64     10719510.21
#Sta/Elev= 30
  4710.8  392.70  4714.3  392.70  4753.2  388.42  4781.5  384.63  4795.6  382.48
  4809.8  379.58  4838.1  375.74  4853.6  373.07  4894.6  369.91  5004.6  369.91
  5007.4  369.41  5010.6  369.91  5115.2  369.91  5141.8  369.91  5150.2  372.13
  5158.5  371.69  5164.1  372.35  5172.5  374.99  5186.5  377.20  5194.9  379.38
  5203.3  380.60  5208.8  382.41  5217.2  383.58  5231.2  386.48  5262.0  390.00
  5270.3  391.61  5292.7  393.42  5306.7  395.13  5315.1  394.69  5329.0  396.14
#Mann=5,-1,0
  4710.8    0.12       0  4853.6    0.05       0  5004.6   0.033       0
  5010.6    0.05       0  5115.2    0.12       0
Bank Sta=5004.6,5010.6
Exp/Cntr=0.3,0.1

Type RM Length L Ch R = 1,5487,460,460,460
BEGIN DESCRIPTION:
Mapping XS 144fa1e7
END DESCRIPTION:
XS GIS Cut Line= 3
      3668549.61     10719860.20      3668449.17     10719461.50
      3668499.61     10719060.22
#Sta/Elev= 30
  4586.7  397.05  4603.2  394.74  4628.0  391.38  4638.3  387.42  4645.8  385.95
  4679.5  384.14  4700.2  377.24  4720.8  375.36  4733.1  375.18  4751.7  378.75
  4762.0  381.78  4774.2  381.51  4782.7  377.10  4793.0  374.84  4803.3  371.19
  4807.3  371.04  4820.9  369.91  4823.7  369.41  4826.9  369.91  5190.7  369.91
  5207.7  370.65  5231.0  372.32  5284.2  380.19  5291.5  381.95  5301.5  382.52
  5311.6  384.30  5341.9  386.45  5359.6  389.20  5382.2  389.63  5402.3  391.31
#Mann=6,-1,0
  4586.7    0.12       0  4603.2     0.1       0  4807.3    0.05       0
  4820.9   0.033       0  4826.9    0.05       0  5207.7    0.16       0
Bank Sta=4820.9,4826.9
Exp/Cntr=0.3,0.1

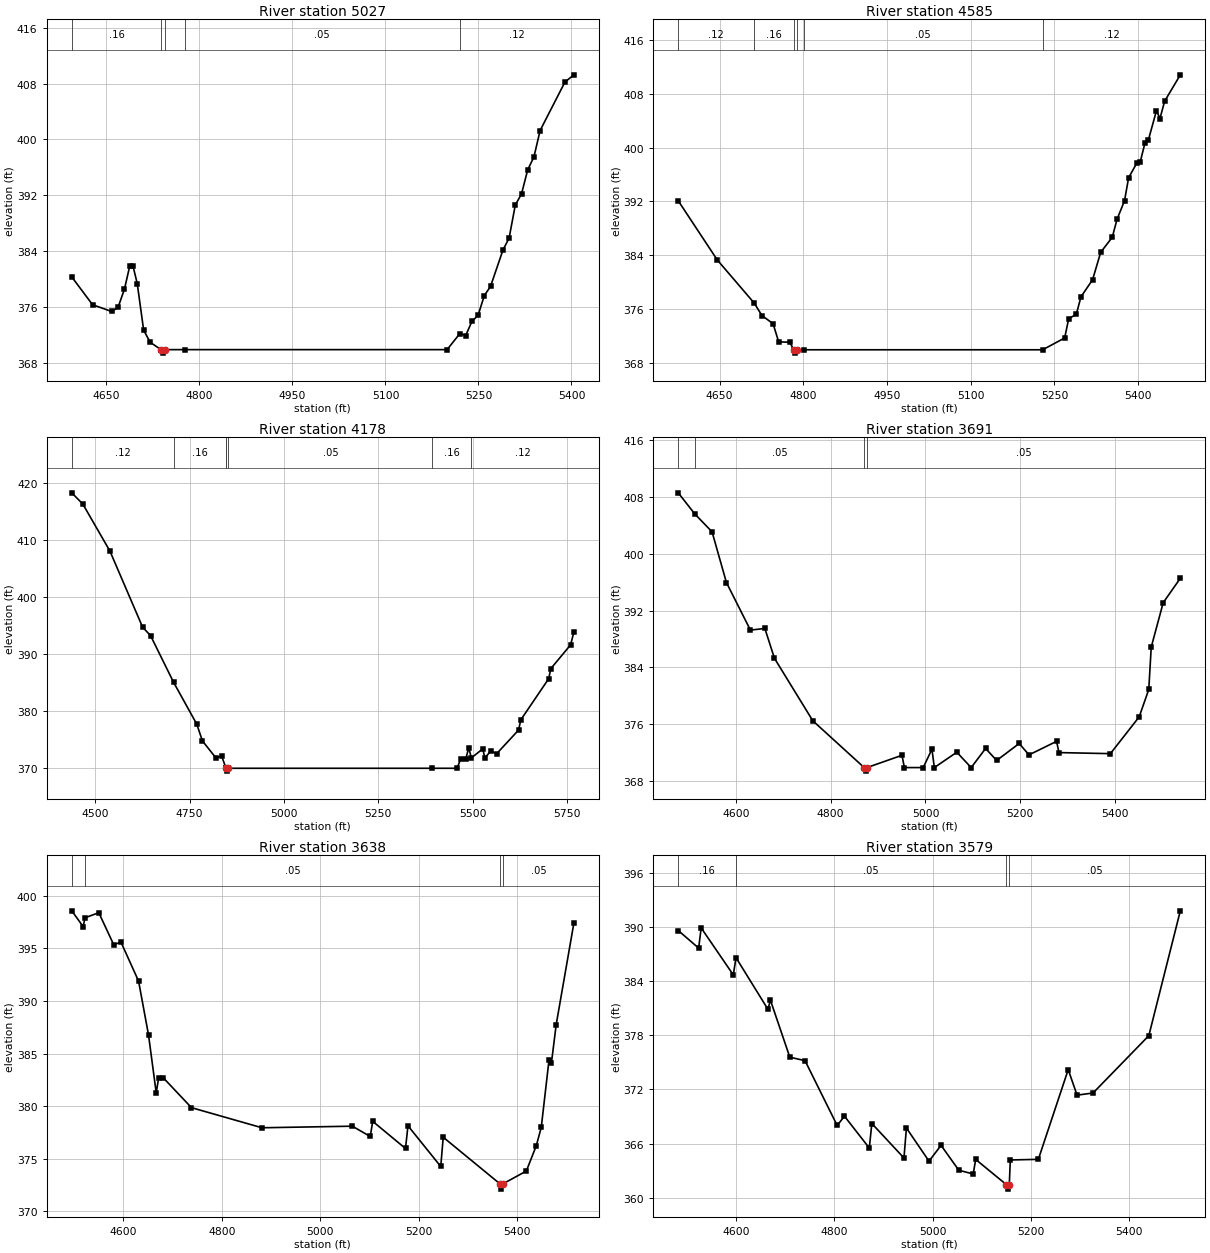
Type RM Length L Ch R = 1,5027,442,442,442
BEGIN DESCRIPTION:
Mapping XS 981e7bb7
END DESCRIPTION:
XS GIS Cut Line= 3
      3668801.18     10719762.68      3668905.33     10719346.05
      3668905.33     10718965.80
#Sta/Elev= 30
  4594.1  380.32  4627.6  376.34  4658.5  375.37  4668.8  375.97  4679.1  378.59
  4687.5  381.84  4692.7  381.94  4699.7  379.36  4710.0  372.71  4720.4  370.97
  4738.0  369.91  4740.7  369.41  4744.0  369.91  4776.2  369.91  5199.4  369.91
  5220.0  372.21  5229.4  371.93  5239.4  373.95  5249.4  374.83  5259.4  377.65
  5269.4  378.95  5289.4  384.15  5299.4  385.89  5309.4  390.62  5319.4  392.20
  5329.4  395.66  5339.4  397.49  5349.4  401.28  5389.4  408.21  5403.8  409.25
#Mann=5,-1,0
  4594.1    0.16       0  4738.0   0.033       0  4744.0    0.16       0
  4776.2    0.05       0  5220.0    0.12       0
Bank Sta=4738,4744
Exp/Cntr=0.3,0.1

Type RM Length L Ch R = 1,4585,407,407,407
BEGIN DESCRIPTION:
Mapping XS b963938d
END DESCRIPTION:
XS GIS Cut Line= 3
      3669349.61     10719710.19      3669349.61     10719310.19
      3669049.61     10718910.19
#Sta/Elev= 30
  4575.7  392.09  4645.7  383.28  4712.0  376.85  4725.7  375.01  4745.7  373.79
  4755.7  371.09  4775.7  371.03  4782.7  369.91  4785.4  369.41  4788.7  369.91
  4800.8  369.91  5229.0  369.91  5268.4  371.67  5275.7  374.56  5289.2  375.17
  5297.6  377.79  5318.4  380.33  5333.0  384.42  5353.8  386.67  5362.2  389.32
  5375.7  392.10  5383.0  395.51  5397.6  397.69  5403.8  397.86  5412.2  400.65
  5418.4  401.12  5433.0  405.52  5439.2  404.33  5447.6  406.91  5475.7  410.84
#Mann=6,-1,0
  4575.7    0.12       0  4712.0    0.16       0  4782.7   0.033       0
  4788.7    0.16       0  4800.8    0.05       0  5229.0    0.12       0
Bank Sta=4782.7,4788.7
Exp/Cntr=0.3,0.1

Type RM Length L Ch R = 1,4178,487,487,487
BEGIN DESCRIPTION:
Mapping XS e8396d20
END DESCRIPTION:
XS GIS Cut Line= 4
      3670030.60     10719740.18      3669749.34     10719328.72
      3669728.51     10719172.47      3670077.20     10718594.78
#Sta/Elev= 30
  4437.8  418.20  4467.1  416.23  4538.9  407.99  4625.6  394.64  4646.6  393.17
  4707.7  384.98  4769.1  377.65  4784.1  374.71  4819.9  371.72  4834.9  372.08
  4846.5  369.93  4846.6  369.91  4849.4  369.41  4852.6  369.91  5393.6  369.91
  5459.2  369.91  5468.9  371.62  5482.0  371.54  5490.2  373.51  5496.8  371.72
  5527.1  373.31  5532.9  371.69  5548.5  372.98  5563.7  372.44  5622.1  376.61
  5628.0  378.40  5701.8  385.60  5707.6  387.38  5760.0  391.55  5768.6  393.77
#Mann=7,-1,0
  4437.8    0.12       0  4707.7    0.16       0  4846.5    0.05       0
  4846.6   0.033       0  4852.6    0.05       0  5393.6    0.16       0
  5496.8    0.12       0
Bank Sta=4846.6,4852.6
Exp/Cntr=0.3,0.1

Type RM Length L Ch R = 1,3691,53,53,53
BEGIN DESCRIPTION:
UNT 057 IN CACR 9.0
END DESCRIPTION:
XS GIS Cut Line= 2
      3670306.64     10719750.61      3670145.29     10718704.48
#Sta/Elev= 30
  4478.8  408.59  4513.4  405.64  4550.1  403.10  4580.4  395.96  4631.0  389.26
  4661.4  389.50  4681.6  385.30  4762.5  376.50  4870.8  369.91  4873.6  369.41
  4876.8  369.91  4950.5  371.64  4955.6  369.91  4995.3  369.91  5013.7  372.50
  5018.7  369.91  5066.1  372.07  5096.4  369.91  5126.8  372.60  5150.1  370.91
  5197.6  373.30  5218.3  371.70  5276.4  373.60  5281.5  372.02  5389.9  371.87
  5450.6  377.05  5470.8  380.91  5476.0  386.87  5501.2  393.12  5537.3  396.56
#Mann=4,-1,0
  4478.8    0.16       0  4513.4    0.05       0  4870.8    0.03       0
  4876.8    0.05       0
Bank Sta=4870.8,4876.8
Exp/Cntr=0.3,0.1

Type RM Length L Ch R = 1,3638,59,59,59
BEGIN DESCRIPTION:
Mapping XS 077baba4
END DESCRIPTION:
XS GIS Cut Line= 2
      3670348.31     10719724.58      3670207.74     10718714.61
#Sta/Elev= 30
  4495.5  398.56  4518.7  397.06  4522.3  397.90  4550.4  398.38  4580.7  395.34
  4595.4  395.59  4631.2  391.88  4651.4  386.76  4667.0  381.27  4672.0  382.71
  4681.7  382.68  4738.6  379.86  4881.8  377.95  5065.3  378.10  5101.7  377.12
  5106.7  378.56  5173.3  375.98  5178.3  378.14  5244.9  374.27  5249.9  377.05
  5365.2  372.62  5368.0  372.12  5371.2  372.62  5418.7  373.84  5438.9  376.24
  5449.0  377.98  5464.8  384.40  5469.8  384.14  5479.3  387.74  5515.2  397.38
#Mann=4,-1,0
  4495.5    0.16       0  4522.3    0.05       0  5365.2    0.03       0
  5371.2    0.05       0
Bank Sta=5365.2,5371.2
Exp/Cntr=0.3,0.1

Type RM Length L Ch R = 1,3579,409,409,409
BEGIN DESCRIPTION:
UNT 057 IN CACR 8.0
END DESCRIPTION:
XS GIS Cut Line= 2
      3670410.80     10719724.53      3670265.05     10718714.69
#Sta/Elev= 30
  4483.1  389.61  4524.6  387.66  4529.7  389.90  4595.0  384.69  4600.5  386.60
  4665.4  380.88  4670.4  381.90  4709.8  375.58  4740.8  375.19  4806.1  368.01
  4820.9  369.04  4871.4  365.51  4876.5  368.23  4941.8  364.41  4946.8  367.73
  4992.7  364.06  5017.2  365.81  5053.3  363.05  5082.5  362.64  5087.6  364.25
  5149.9  361.46  5152.6  360.96  5155.9  361.46  5157.9  364.19  5214.9  364.26
  5275.6  374.20  5293.6  371.37  5326.1  371.61  5439.4  377.96  5503.4  391.79
#Mann=4,-1,0
  4483.1    0.16       0  4600.5    0.05       0  5149.9    0.03       0
  5155.9    0.05       0
Bank Sta=5149.9,5155.9
Exp/Cntr=0.3,0.1

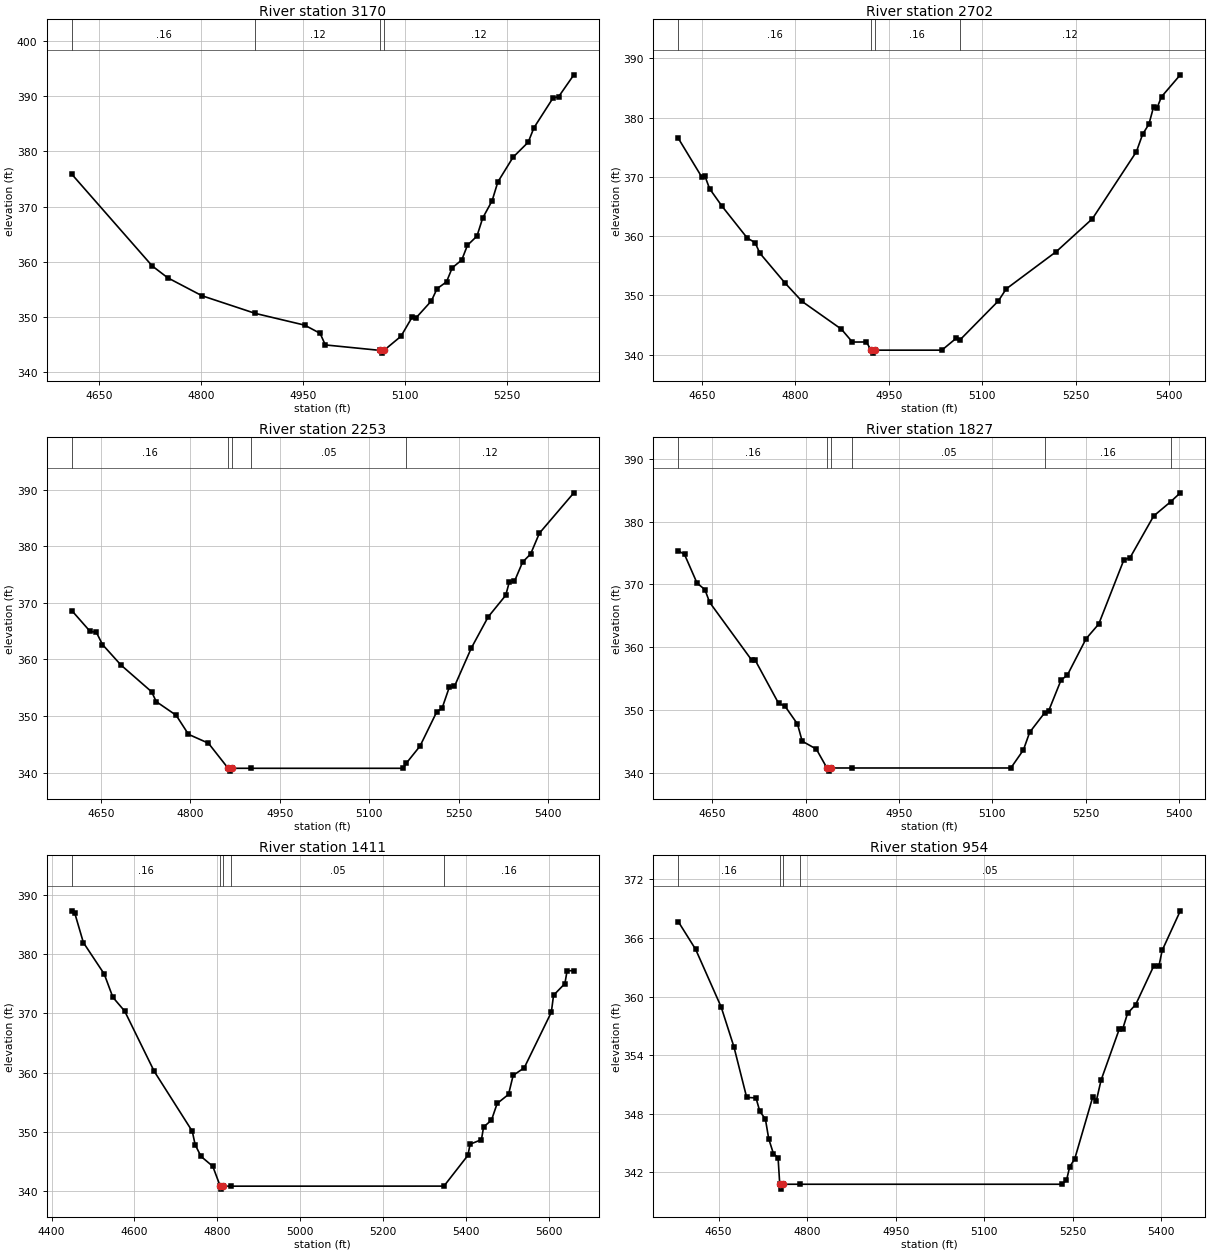
Type RM Length L Ch R = 1,3170,468,468,468
BEGIN DESCRIPTION:
UNT 057 IN CACR 7.0
END DESCRIPTION:
XS GIS Cut Line= 3
      3670749.61     10719510.18      3670699.61     10719110.19
      3670549.62     10718810.20
#Sta/Elev= 30
  4609.5  375.88  4727.9  359.21  4750.6  357.07  4801.0  353.81  4879.5  350.60
  4952.1  348.47  4974.8  346.98  4982.4  344.88  5062.7  343.89  5065.5  343.39
  5068.7  343.89  5093.7  346.45  5110.4  349.97  5116.0  349.81  5138.4  352.86
  5146.8  355.09  5160.7  356.33  5169.1  358.88  5183.1  360.30  5191.5  362.97
  5205.5  364.64  5213.9  367.91  5227.8  371.06  5236.2  374.47  5258.6  378.96
  5280.9  381.69  5289.3  384.31  5317.3  389.70  5325.7  389.96  5348.0  393.92
#Mann=4,-1,0
  4609.5    0.16       0  4879.5    0.12       0  5062.7    0.07       0
  5068.7    0.12       0
Bank Sta=5062.7,5068.7
Exp/Cntr=0.3,0.1

Type RM Length L Ch R = 1,2702,449,449,449
BEGIN DESCRIPTION:
UNT 057 IN CACR 6.0
END DESCRIPTION:
XS GIS Cut Line= 3
      3671199.61     10719610.18      3671149.61     10719210.19
      3671199.61     10718810.20
#Sta/Elev= 30
  4612.0  376.53  4649.8  369.98  4654.8  370.15  4662.4  368.00  4682.5  365.03
  4722.8  359.69  4735.4  358.91  4743.0  357.14  4783.3  352.12  4811.0  348.98
  4874.0  344.31  4891.6  342.14  4914.3  342.15  4921.4  340.77  4924.2  340.27
  4927.4  340.77  5035.3  340.77  5057.9  342.74  5064.3  342.49  5126.0  349.07
  5138.6  351.10  5219.2  357.41  5277.1  362.95  5347.7  374.25  5357.7  377.20
  5367.8  378.90  5375.4  381.85  5380.4  381.54  5388.0  383.52  5418.2  387.22
#Mann=4,-1,0
  4612.0    0.16       0  4921.4    0.07       0  4927.4    0.16       0
  5064.3    0.12       0
Bank Sta=4921.4,4927.4
Exp/Cntr=0.3,0.1

Type RM Length L Ch R = 1,2253,426,426,426
BEGIN DESCRIPTION:
UNT 057 IN CACR 5.0
END DESCRIPTION:
XS GIS Cut Line= 3
      3671499.62     10719610.15      3671599.61     10719210.19
      3671849.62     10718860.18
#Sta/Elev= 30
  4601.1  368.63  4632.0  364.93  4642.3  364.80  4652.6  362.63  4683.5  359.02
  4735.1  354.28  4742.8  352.55  4776.3  350.13  4796.9  346.77  4830.4  345.20
  4863.5  340.77  4866.2  340.27  4869.5  340.77  4902.5  340.77  5157.2  340.77
  5162.1  341.63  5185.4  344.69  5213.7  350.79  5222.3  351.34  5234.6  355.11
  5243.2  355.24  5271.4  361.99  5299.7  367.50  5329.2  371.32  5335.3  373.71
  5343.9  373.80  5357.5  377.18  5371.0  378.62  5385.7  382.29  5443.5  389.42
#Mann=5,-1,0
  4601.1    0.16       0  4863.5   0.033       0  4869.5    0.16       0
  4902.5    0.05       0  5162.1    0.12       0
Bank Sta=4863.5,4869.5
Exp/Cntr=0.3,0.1

Type RM Length L Ch R = 1,1827,416,416,416
BEGIN DESCRIPTION:
UNT 057 IN CACR 4.0
END DESCRIPTION:
XS GIS Cut Line= 3
      3671949.61     10719760.17      3671999.61     10719360.19
      3672049.61     10718960.19
#Sta/Elev= 30
  4595.6  375.36  4605.7  374.76  4625.8  370.20  4638.4  369.17  4646.0  367.14
  4714.0  357.88  4719.0  357.96  4756.8  351.05  4766.9  350.63  4787.1  347.76
  4794.6  345.04  4817.3  343.78  4834.4  340.77  4837.2  340.27  4840.4  340.77
  4875.3  340.77  5129.7  340.77  5149.9  343.65  5159.9  346.45  5183.8  349.53
  5190.2  349.81  5210.3  354.77  5220.4  355.55  5250.6  361.36  5270.8  363.68
  5311.1  373.88  5321.2  374.26  5359.0  380.88  5386.3  383.15  5401.8  384.57
#Mann=6,-1,0
  4595.6    0.16       0  4834.4   0.033       0  4840.4    0.16       0
  4875.3    0.05       0  5183.8    0.16       0  5386.3    0.12       0
Bank Sta=4834.4,4840.4
Exp/Cntr=0.3,0.1

Type RM Length L Ch R = 1,1411,457,457,457
BEGIN DESCRIPTION:
UNT 057 IN CACR 3.0
END DESCRIPTION:
XS GIS Cut Line= 3
      3671999.59     10719860.20      3672399.61     10719510.19
      3672199.61     10718860.19
#Sta/Elev= 30
  4448.9  387.36  4456.0  387.00  4476.9  381.99  4527.2  376.67  4548.1  372.73
  4576.6  370.39  4647.8  360.21  4739.8  350.05  4746.5  347.81  4760.7  345.81
  4789.2  344.13  4807.1  340.77  4809.8  340.27  4813.1  340.77  4833.4  340.77
  5347.0  340.78  5404.8  345.98  5410.1  347.87  5437.5  348.64  5442.7  350.79
  5461.7  351.93  5475.4  354.76  5502.9  356.30  5514.0  359.51  5540.8  360.80
  5606.2  370.21  5611.5  373.07  5638.9  375.05  5644.2  377.22  5660.5  377.23
#Mann=5,-1,0
  4448.9    0.16       0  4807.1   0.033       0  4813.1    0.16       0
  4833.4    0.05       0  5347.0    0.16       0
Bank Sta=4807.1,4813.1
Exp/Cntr=0.3,0.1

Type RM Length L Ch R = 1,954,468,468,468
BEGIN DESCRIPTION:
UNT 057 IN CACR 2.0
END DESCRIPTION:
XS GIS Cut Line= 3
      3672549.62     10720110.18      3672749.61     10719760.19
      3673149.60     10719560.19
#Sta/Elev= 30
  4581.7  367.68  4611.2  364.83  4654.4  358.93  4676.0  354.85  4697.6  349.67
  4713.4  349.61  4719.9  348.23  4729.3  347.45  4735.0  345.41  4742.9  343.91
  4750.8  343.48  4753.6  340.77  4756.4  340.27  4759.6  340.77  4787.6  340.77
  5230.8  340.77  5239.2  341.16  5244.7  342.57  5253.1  343.35  5283.9  349.75
  5289.5  349.25  5297.8  351.43  5328.6  356.66  5334.2  356.63  5342.6  358.27
  5356.5  359.18  5387.3  363.17  5395.7  363.10  5401.3  364.73  5432.0  368.78
#Mann=4,-1,0
  4581.7    0.16       0  4753.6   0.033       0  4759.6    0.16       0
  4787.6    0.05       0
Bank Sta=4753.6,4759.6
Exp/Cntr=0.3,0.1

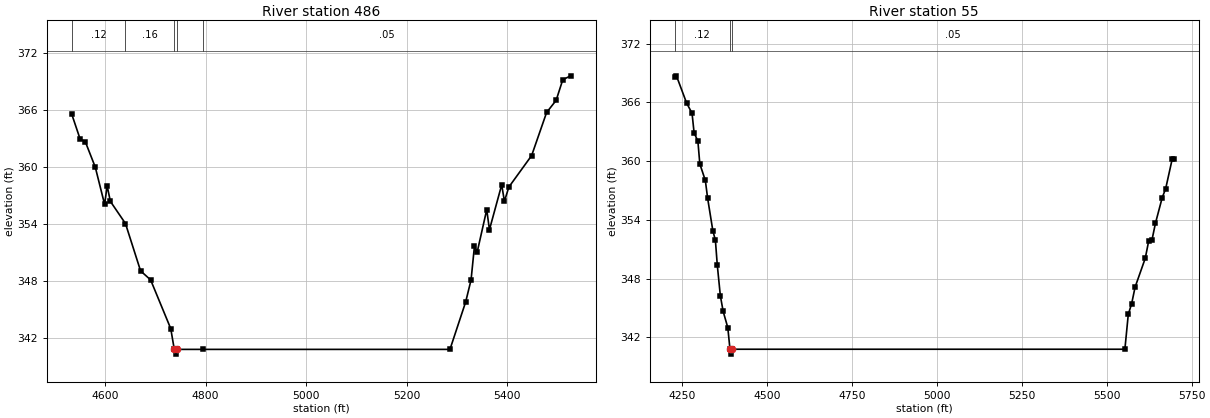
Type RM Length L Ch R = 1,486,431,431,431
BEGIN DESCRIPTION:
Mapping XS ec9f5e80
END DESCRIPTION:
XS GIS Cut Line= 4
      3672612.58     10720161.18      3672972.00     10720182.02
      3673102.21     10720083.06      3673274.08     10719645.58
#Sta/Elev= 30
  4533.1  365.59  4550.2  362.90  4560.2  362.67  4580.2  359.97  4598.8  356.04
  4603.8  358.00  4610.3  356.36  4640.3  354.03  4670.4  349.04  4690.4  348.09
  4730.5  342.95  4737.5  340.77  4740.2  340.27  4743.5  340.77  4794.2  340.77
  5286.4  340.77  5317.6  345.76  5328.4  348.09  5335.2  351.67  5340.6  351.02
  5359.6  355.49  5365.0  353.38  5389.4  358.11  5394.8  356.37  5403.6  357.87
  5449.0  361.19  5478.8  365.73  5497.8  367.01  5511.0  369.18  5526.7  369.59
#Mann=5,-1,0
  4533.1    0.12       0  4640.3    0.16       0  4737.5   0.033       0
  4743.5    0.16       0  4794.2    0.05       0
Bank Sta=4737.5,4743.5
Exp/Cntr=0.3,0.1

Type RM Length L Ch R = 1,55,0,0,0
BEGIN DESCRIPTION:
UNT 057 IN CACR 1.0
END DESCRIPTION:
XS GIS Cut Line= 4
      3672617.84     10720234.10      3673237.62     10720520.56
      3673341.79     10720442.44      3673336.58     10719786.15
#Sta/Elev= 30
  4228.1  368.59  4233.1  368.72  4263.1  365.93  4279.0  364.90  4285.1  362.89
  4296.2  362.05  4301.9  359.72  4318.2  358.02  4324.9  356.21  4340.2  352.90
  4347.8  351.90  4353.3  349.39  4362.3  346.25  4370.7  344.63  4384.3  342.98
  4390.7  340.77  4393.4  340.27  4396.7  340.77  5553.4  340.77  5563.4  344.33
  5573.4  345.44  5583.4  347.11  5613.4  350.07  5623.4  351.82  5633.4  351.98
  5643.4  353.65  5663.4  356.28  5673.4  357.17  5692.9  360.24  5697.4  360.24
#Mann=3,-1,0
  4228.1    0.12       0  4390.7   0.033       0  4396.7    0.05       0
Bank Sta=4390.7,4396.7
Exp/Cntr=0.3,0.1

Chan Stop Cuts=-1