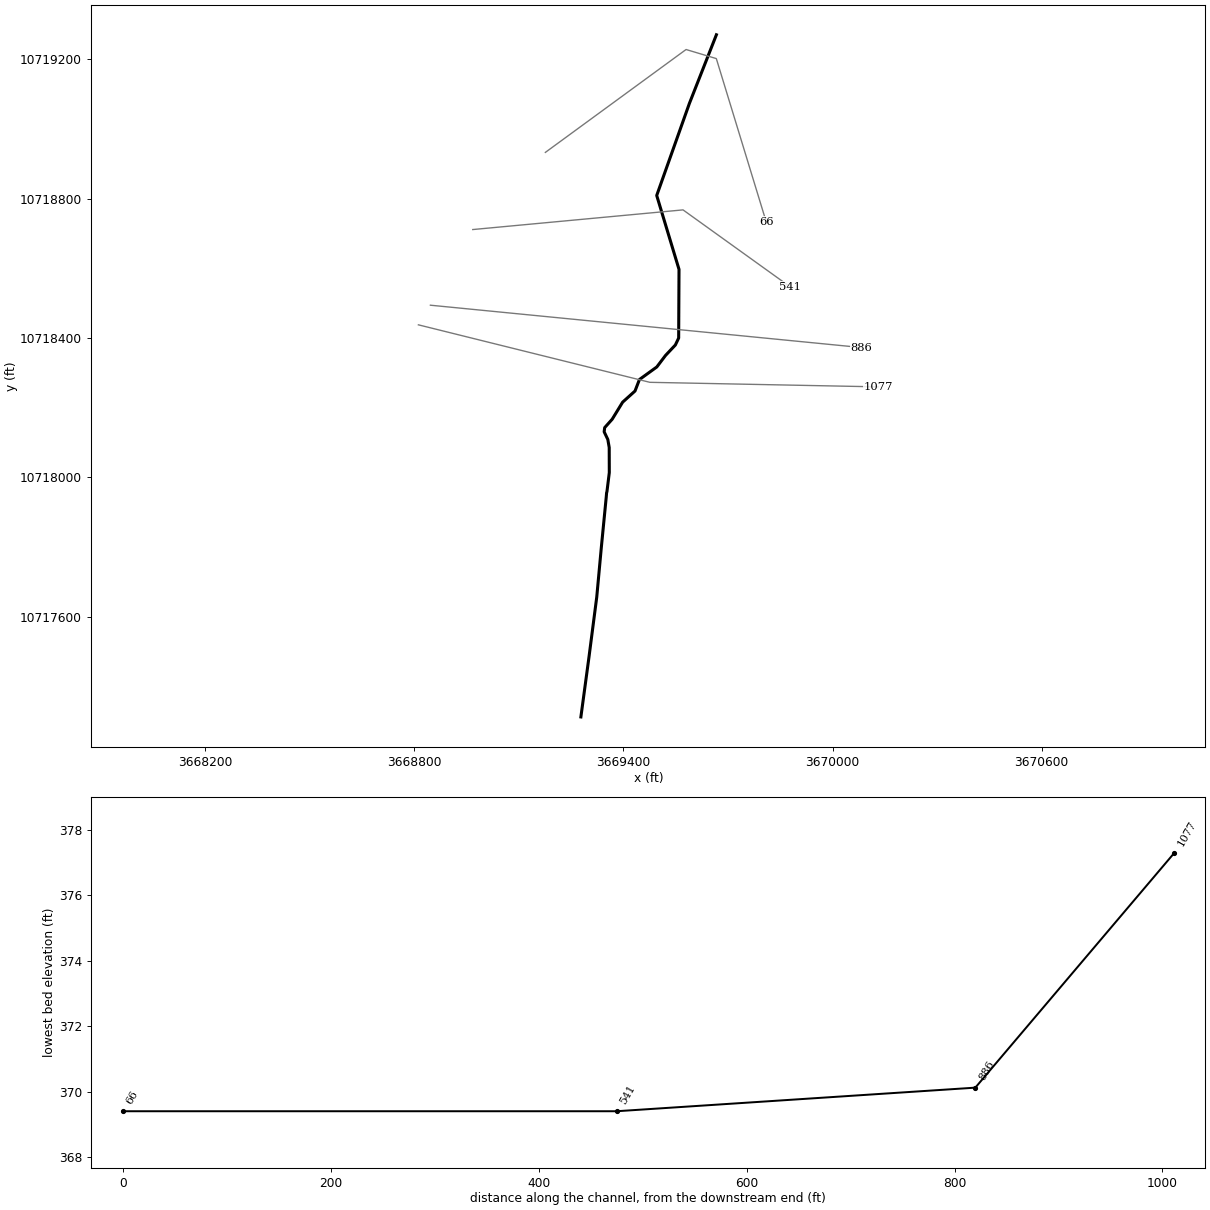
--- UNT 058 IN CACR.prj (project) ---

Proj Title=UNT 058 IN CACR Base Level Engineering
Current Plan=p01
Default Exp/Contr=0.3,0.1
English Units
Geom File=g01
Flow File=f01
Plan File=p01
BEGIN DESCRIPTION:
UNT 058 IN CACR
END DESCRIPTION:

--- UNT 058 IN CACR.p01 (plan) ---

Plan Title=Multiple Run
Short Identifier=Multiple
Geom File=g01
Flow File=f01
Subcritical Flow
K Sum by GR= 0
Std Step Tol= 0.01
Critical Tol= 0.01
Num of Std Step Trials= 20
Max Error Tol= 0.3
Flow Tol Ratio= 0.001
Split Flow NTrial= 30
Split Flow Tol= 0.02
Split Flow Ratio= 0.02
Log Output Level= 0
Friction Slope Method= 1
Unsteady Friction Slope Method= 2
Unsteady Bridges Friction Slope Method= 1
Parabolic Critical Depth
Global Vel Dist=  1 , 1 , 1
Global Log Level= 0
CheckData=True
Encroach Param= -1, 0, 0, 0
BEGIN DESCRIPTION:
Multiple Run
END DESCRIPTION:

--- UNT 058 IN CACR.f01 (steady flow) ---

Flow Title=Multiple
Number of Profiles=7
Profile Names=10-year,25-year,50-year,1pct_min,100-year,1pct_plu,500-year
River Rch & RM= UNT 058 IN CACR,Reach-1,1077
     213     275     324     282     382     516     531
Boundary for River Rch & Prof#=UNT 058 IN CACR,Reach-1,1
Up Type=0
Dn Type=3
Dn Slope=0.005
Boundary for River Rch & Prof#=UNT 058 IN CACR,Reach-1,2
Up Type=0
Dn Type=3
Dn Slope=0.005
Boundary for River Rch & Prof#=UNT 058 IN CACR,Reach-1,3
Up Type=0
Dn Type=3
Dn Slope=0.005
Boundary for River Rch & Prof#=UNT 058 IN CACR,Reach-1,4
Up Type=0
Dn Type=3
Dn Slope=0.005
Boundary for River Rch & Prof#=UNT 058 IN CACR,Reach-1,5
Up Type=0
Dn Type=3
Dn Slope=0.005
Boundary for River Rch & Prof#=UNT 058 IN CACR,Reach-1,6
Up Type=0
Dn Type=3
Dn Slope=0.005
Boundary for River Rch & Prof#=UNT 058 IN CACR,Reach-1,7
Up Type=0
Dn Type=3
Dn Slope=0.005

--- UNT 058 IN CACR.g01 (geometry) ---

Geom Title=Existing Conditions

River Reach=UNT 058 IN CACR,Reach-1
Reach XY= 24
      3669278.00     10717313.00      3669301.25     10717485.00
      3669323.50     10717657.00      3669336.50     10717798.00
      3669350.75     10717944.00      3669351.75     10717956.00
      3669352.75     10717959.34      3669359.50     10718014.00
      3669359.25     10718086.00      3669355.25     10718109.00
      3669344.75     10718131.00      3669346.25     10718143.00
      3669367.75     10718167.00      3669397.75     10718216.00
      3669433.25     10718248.00      3669446.00     10718281.00
      3669495.75     10718317.00      3669520.75     10718350.00
      3669549.00     10718380.00      3669558.50     10718400.00
      3669559.50     10718597.00      3669495.50     10718809.00
      3669589.25     10719073.00      3669666.75     10719270.00

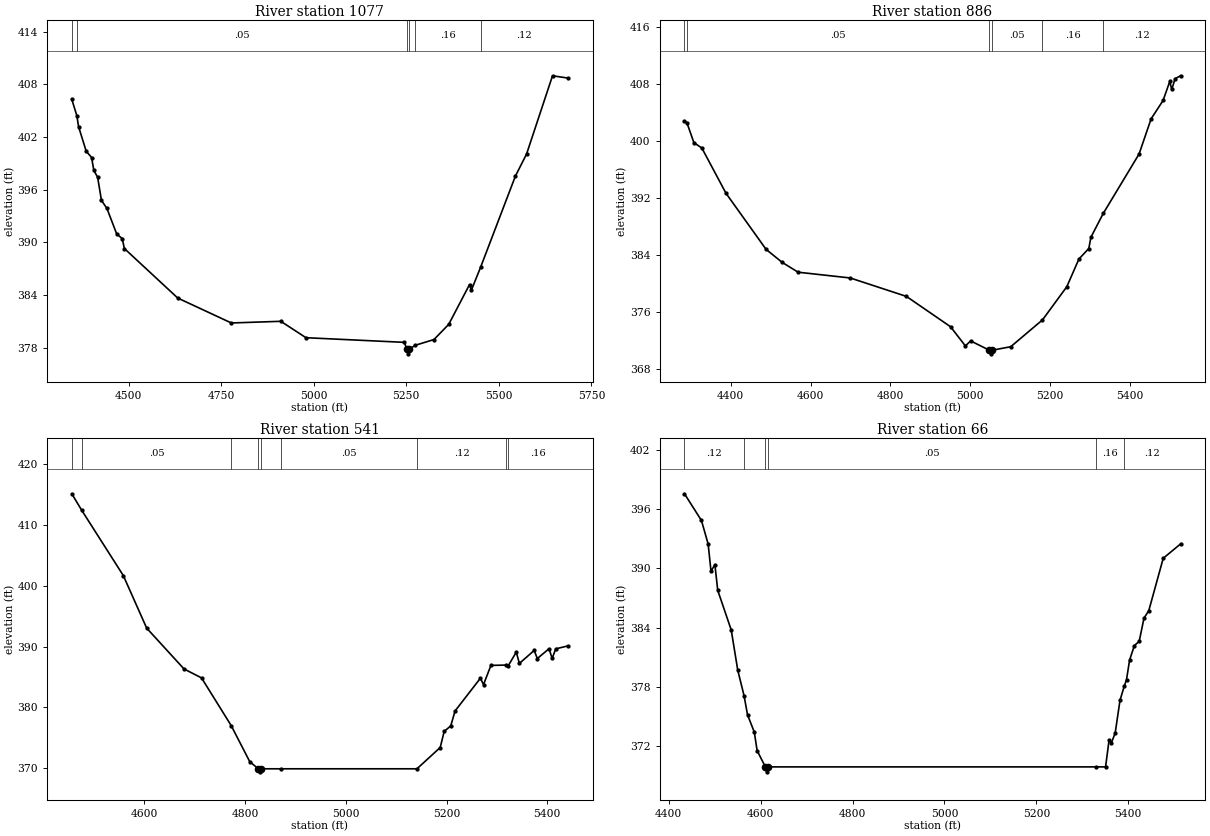
Type RM Length L Ch R = 1,1077,191,191,191
BEGIN DESCRIPTION:
UNT 058 IN CACR 3.0
END DESCRIPTION:
XS GIS Cut Line= 3
      3668811.84     10718437.88      3669475.89     10718272.95
      3670131.24     10718259.93
#Sta/Elev= 30
  4346.8  406.31  4360.6  404.42  4365.1  403.19  4385.7  400.39  4400.3  399.67
  4406.3  398.20  4416.6  397.42  4426.9  394.78  4441.7  393.86  4468.1  390.95
  4483.0  390.42  4488.8  389.29  4633.0  383.64  4777.6  380.80  4911.2  380.99
  4979.2  379.12  5244.8  378.59  5251.8  377.78  5254.5  377.28  5257.8  377.78
  5273.8  378.25  5324.8  378.91  5364.8  380.65  5420.8  385.18  5425.8  384.54
  5450.5  387.13  5544.8  397.56  5574.9  400.07  5644.9  408.99  5686.5  408.73
#Mann=6,-1,0
  4346.8    0.16       0  4360.6    0.05       0  5251.8    0.03       0
  5257.8    0.05       0  5273.8    0.16       0  5450.5    0.12       0
Bank Sta=5251.8,5257.8
Exp/Cntr=0.3,0.1

Type RM Length L Ch R = 1,886,345,345,345
BEGIN DESCRIPTION:
Mapping XS 2fd1891a
END DESCRIPTION:
XS GIS Cut Line= 2
      3668846.25     10718494.20      3670083.20     10718372.67
#Sta/Elev= 30
  4284.2  402.80  4290.2  402.62  4307.7  399.81  4327.8  399.04  4388.1  392.70
  4488.5  384.82  4528.7  382.99  4568.9  381.60  4699.5  380.79  4840.2  378.20
  4950.7  373.94  4988.0  371.24  5001.0  371.95  5048.2  370.63  5051.0  370.13
  5054.2  370.63  5101.5  371.13  5181.1  374.90  5242.1  379.57  5272.3  383.45
  5297.1  384.93  5302.4  386.51  5333.3  389.86  5423.0  398.20  5453.2  403.15
  5483.3  405.74  5499.9  408.40  5504.9  407.28  5513.4  408.80  5527.1  409.20
#Mann=6,-1,0
  4284.2    0.16       0  4290.2    0.05       0  5048.2    0.03       0
  5054.2    0.05       0  5181.1    0.16       0  5333.3    0.12       0
Bank Sta=5048.2,5054.2
Exp/Cntr=0.3,0.1

Type RM Length L Ch R = 1,541,475,475,475
BEGIN DESCRIPTION:
UNT 058 IN CACR 2.0
END DESCRIPTION:
XS GIS Cut Line= 3
      3668967.78     10718711.22      3669571.04     10718767.64
      3669879.19     10718546.29
#Sta/Elev= 30
  4455.7  415.12  4475.1  412.45  4558.0  401.68  4604.4  393.04  4678.5  386.33
  4713.4  384.85  4772.3  377.01  4809.1  371.09  4826.1  369.91  4828.9  369.41
  4832.1  369.91  4871.3  369.91  5141.2  369.91  5187.4  373.41  5195.3  376.06
  5208.3  376.96  5216.9  379.42  5267.2  384.80  5273.4  383.75  5288.1  386.91
  5318.5  386.96  5321.6  386.73  5338.5  389.09  5344.6  387.23  5374.1  389.37
  5380.2  388.03  5403.5  389.65  5409.7  388.06  5416.9  389.63  5441.0  390.11
#Mann=9,-1,0
  4455.7    0.12       0  4475.1    0.05       0  4772.3    0.12       0
  4826.1   0.033       0  4832.1    0.12       0  4871.3    0.05       0
  5141.2    0.12       0  5318.5    0.05       0  5321.6    0.16       0
Bank Sta=4826.1,4832.1
Exp/Cntr=0.3,0.1

Type RM Length L Ch R = 1,66,0,0,0
BEGIN DESCRIPTION:
UNT 058 IN CACR 1.0
END DESCRIPTION:
XS GIS Cut Line= 4
      3669176.05     10718932.55      3669579.73     10719227.71
      3669666.53     10719201.67      3669809.43     10718734.01
#Sta/Elev= 30
  4434.2  397.53  4471.1  394.83  4485.7  392.45  4491.9  389.70  4500.4  390.36
  4506.6  387.76  4535.9  383.76  4550.1  379.70  4563.8  377.12  4571.4  375.18
  4586.1  373.43  4592.3  371.56  4610.2  369.91  4612.9  369.41  4616.2  369.91
  5328.9  369.91  5350.6  369.91  5358.2  372.62  5363.4  372.36  5371.5  373.33
  5382.0  376.64  5391.1  378.05  5396.2  378.74  5402.9  380.72  5413.3  382.18
  5423.8  382.61  5434.2  384.95  5444.7  385.72  5476.1  391.01  5513.9  392.46
#Mann=6,-1,0
  4434.2    0.12       0  4563.8    0.05       0  4610.2   0.033       0
  4616.2    0.05       0  5328.9    0.16       0  5391.1    0.12       0
Bank Sta=4610.2,4616.2
Exp/Cntr=0.3,0.1

Chan Stop Cuts=-1