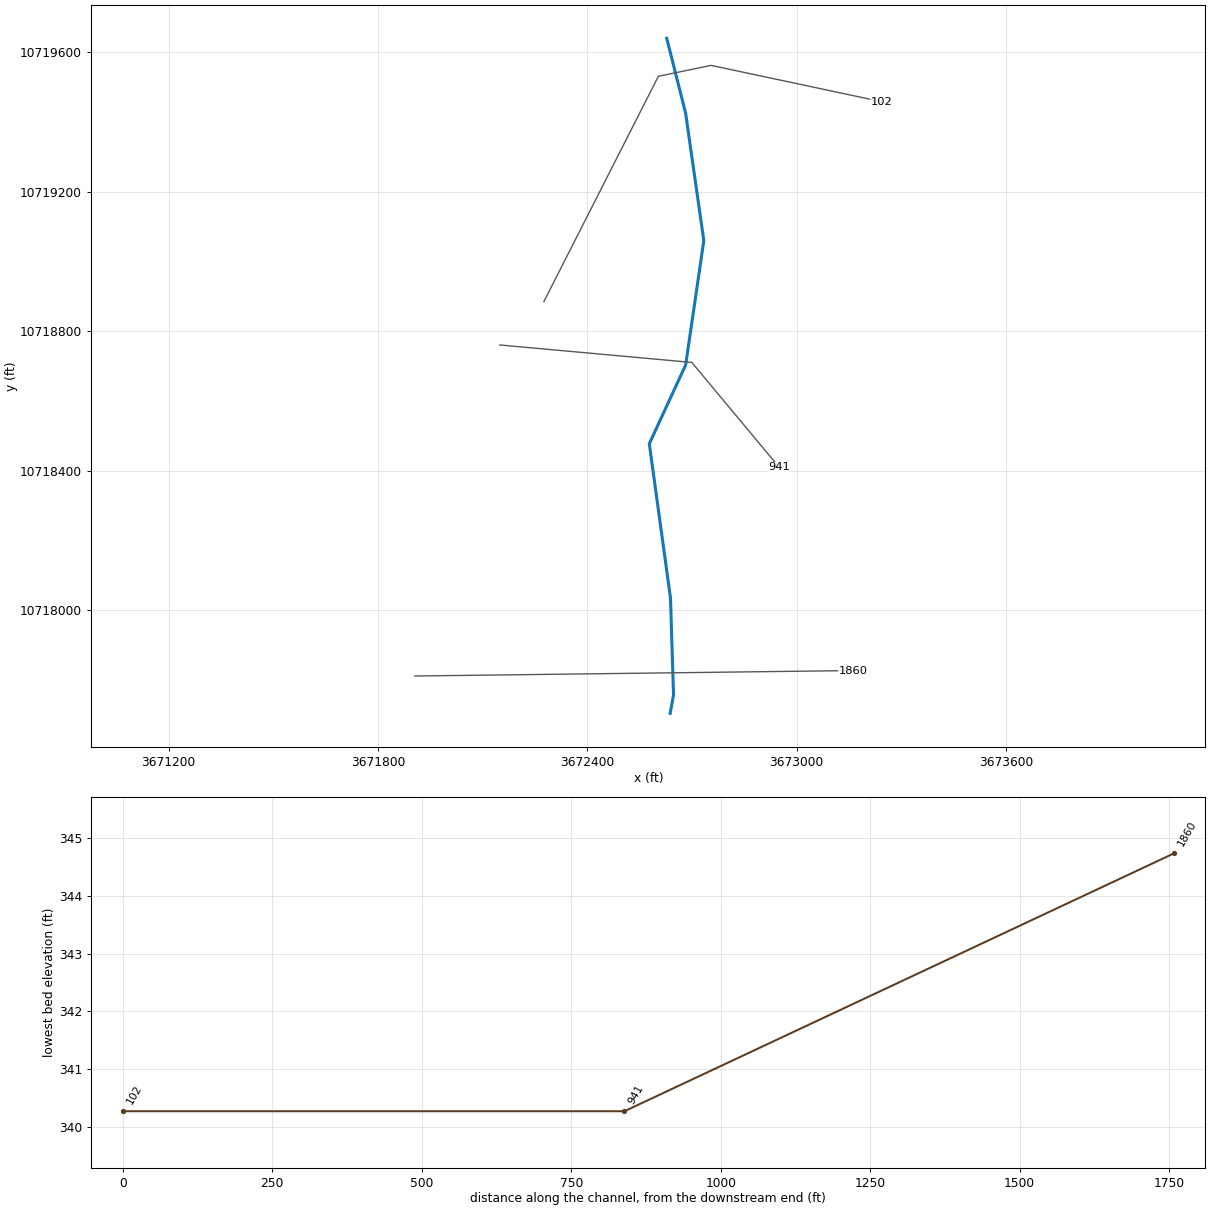
--- UNT 059 IN CACR.prj (project) ---

Proj Title=UNT 059 IN CACR Base Level Engineering
Current Plan=p01
Default Exp/Contr=0.3,0.1
English Units
Geom File=g01
Flow File=f01
Plan File=p01
BEGIN DESCRIPTION:
UNT 059 IN CACR
END DESCRIPTION:

--- UNT 059 IN CACR.p01 (plan) ---

Plan Title=Multiple Run
Short Identifier=Multiple
Geom File=g01
Flow File=f01
Subcritical Flow
K Sum by GR= 0
Std Step Tol= 0.01
Critical Tol= 0.01
Num of Std Step Trials= 20
Max Error Tol= 0.3
Flow Tol Ratio= 0.001
Split Flow NTrial= 30
Split Flow Tol= 0.02
Split Flow Ratio= 0.02
Log Output Level= 0
Friction Slope Method= 1
Unsteady Friction Slope Method= 2
Unsteady Bridges Friction Slope Method= 1
Parabolic Critical Depth
Global Vel Dist=  1 , 1 , 1
Global Log Level= 0
CheckData=True
Encroach Param= -1, 0, 0, 0
BEGIN DESCRIPTION:
Multiple Run
END DESCRIPTION:

--- UNT 059 IN CACR.f01 (steady flow) ---

Flow Title=Multiple
Number of Profiles=7
Profile Names=10-year,25-year,50-year,1pct_min,100-year,1pct_plu,500-year
River Rch & RM= UNT 059 IN CACR,Reach-1,1860
     195     251     294     256     346     467     476
Boundary for River Rch & Prof#=UNT 059 IN CACR,Reach-1,1
Up Type=0
Dn Type=3
Dn Slope=0.005
Boundary for River Rch & Prof#=UNT 059 IN CACR,Reach-1,2
Up Type=0
Dn Type=3
Dn Slope=0.005
Boundary for River Rch & Prof#=UNT 059 IN CACR,Reach-1,3
Up Type=0
Dn Type=3
Dn Slope=0.005
Boundary for River Rch & Prof#=UNT 059 IN CACR,Reach-1,4
Up Type=0
Dn Type=3
Dn Slope=0.005
Boundary for River Rch & Prof#=UNT 059 IN CACR,Reach-1,5
Up Type=0
Dn Type=3
Dn Slope=0.005
Boundary for River Rch & Prof#=UNT 059 IN CACR,Reach-1,6
Up Type=0
Dn Type=3
Dn Slope=0.005
Boundary for River Rch & Prof#=UNT 059 IN CACR,Reach-1,7
Up Type=0
Dn Type=3
Dn Slope=0.005

--- UNT 059 IN CACR.g01 (geometry) ---

Geom Title=Existing Conditions

River Reach=UNT 059 IN CACR,Reach-1
Reach XY= 8
      3672637.57     10717704.40      3672647.25     10717757.00
      3672638.50     10718035.00      3672577.75     10718477.00
      3672682.00     10718703.00      3672734.00     10719059.00
      3672682.00     10719424.00      3672627.75     10719639.00

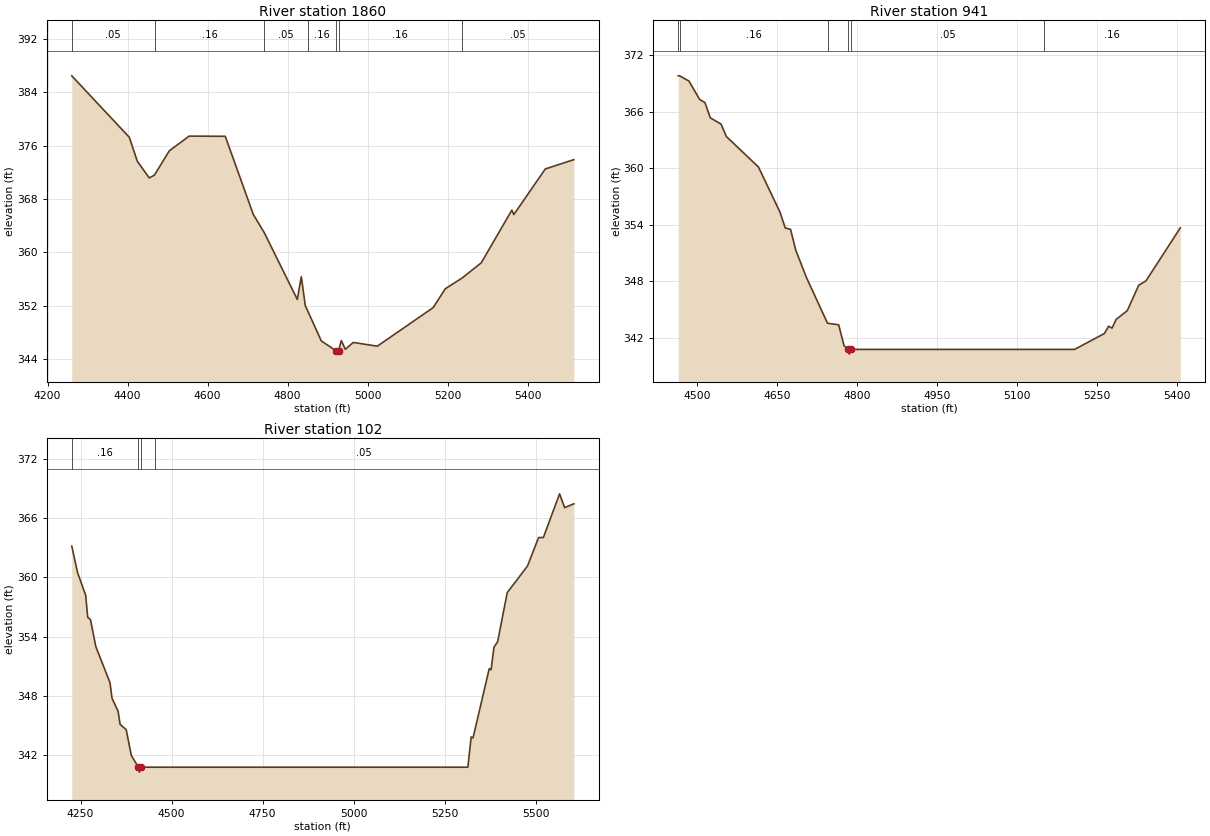
Type RM Length L Ch R = 1,1860,919,919,919
BEGIN DESCRIPTION:
UNT 059 IN CACR 3.0
END DESCRIPTION:
XS GIS Cut Line= 2
      3671905.80     10717811.48      3673161.01     10717827.10
#Sta/Elev= 30
  4260.5  386.48  4404.3  377.27  4424.3  373.68  4454.3  371.16  4467.4  371.61
  4504.3  375.23  4554.1  377.44  4644.3  377.41  4714.3  365.70  4741.7  362.97
  4824.4  352.94  4834.4  356.36  4844.4  352.00  4851.8  351.04  4884.4  346.72
  4921.4  345.24  4924.1  344.74  4927.4  345.24  4934.4  346.78  4944.4  345.47
  4964.4  346.49  5024.4  345.93  5164.4  351.73  5194.4  354.55  5236.4  356.15
  5284.4  358.44  5360.8  366.34  5365.8  365.67  5444.4  372.51  5515.8  373.91
#Mann=7,-1,0
  4260.5    0.05       0  4467.4    0.16       0  4741.7    0.05       0
  4851.8    0.16       0  4921.4    0.07       0  4927.4    0.16       0
  5236.4    0.05       0
Bank Sta=4921.4,4927.4
Exp/Cntr=0.3,0.1

Type RM Length L Ch R = 1,941,839,839,839
BEGIN DESCRIPTION:
UNT 059 IN CACR 2.0
END DESCRIPTION:
XS GIS Cut Line= 3
      3672149.57     10718760.19      3672699.61     10718710.19
      3672949.60     10718410.21
#Sta/Elev= 30
  4464.1  369.80  4466.7  369.80  4484.2  369.25  4504.3  367.29  4514.3  366.96
  4524.4  365.34  4544.5  364.68  4554.5  363.36  4614.8  360.12  4654.9  355.37
  4665.0  353.66  4675.0  353.51  4685.0  351.26  4705.1  348.37  4744.4  343.55
  4765.4  343.38  4775.4  341.18  4782.5  340.77  4785.2  340.27  4788.5  340.77
  5151.6  340.77  5208.4  340.77  5264.4  342.46  5272.2  343.23  5278.7  343.03
  5286.5  343.96  5307.3  344.88  5328.8  347.58  5342.5  348.05  5406.9  353.67
#Mann=6,-1,0
  4464.1    0.12       0  4466.7    0.16       0  4744.4    0.05       0
  4782.5   0.033       0  4788.5    0.05       0  5151.6    0.16       0
Bank Sta=4782.5,4788.5
Exp/Cntr=0.3,0.1

Type RM Length L Ch R = 1,102,0,0,0
BEGIN DESCRIPTION:
UNT 059 IN CACR 1.0
END DESCRIPTION:
XS GIS Cut Line= 4
      3672275.64     10718884.43      3672603.74     10719530.23
      3672754.78     10719561.48      3673244.32     10719457.32
#Sta/Elev= 30
  4225.7  363.18  4241.6  360.50  4263.9  358.20  4269.5  355.97  4277.0  355.74
  4291.8  352.99  4330.7  349.34  4336.3  347.76  4352.9  346.44  4358.5  345.11
  4375.2  344.58  4389.2  341.97  4408.6  340.77  4411.4  340.27  4414.6  340.77
  4453.0  340.77  5313.7  340.77  5322.8  343.84  5327.9  343.74  5372.4  350.76
  5377.5  350.65  5385.3  352.92  5395.5  353.50  5421.9  358.47  5477.3  361.15
  5508.0  364.05  5521.1  364.05  5565.6  368.48  5579.5  367.08  5604.8  367.47
#Mann=4,-1,0
  4225.7    0.16       0  4408.6   0.033       0  4414.6    0.16       0
  4453.0    0.05       0
Bank Sta=4408.6,4414.6
Exp/Cntr=0.3,0.1

Chan Stop Cuts=-1