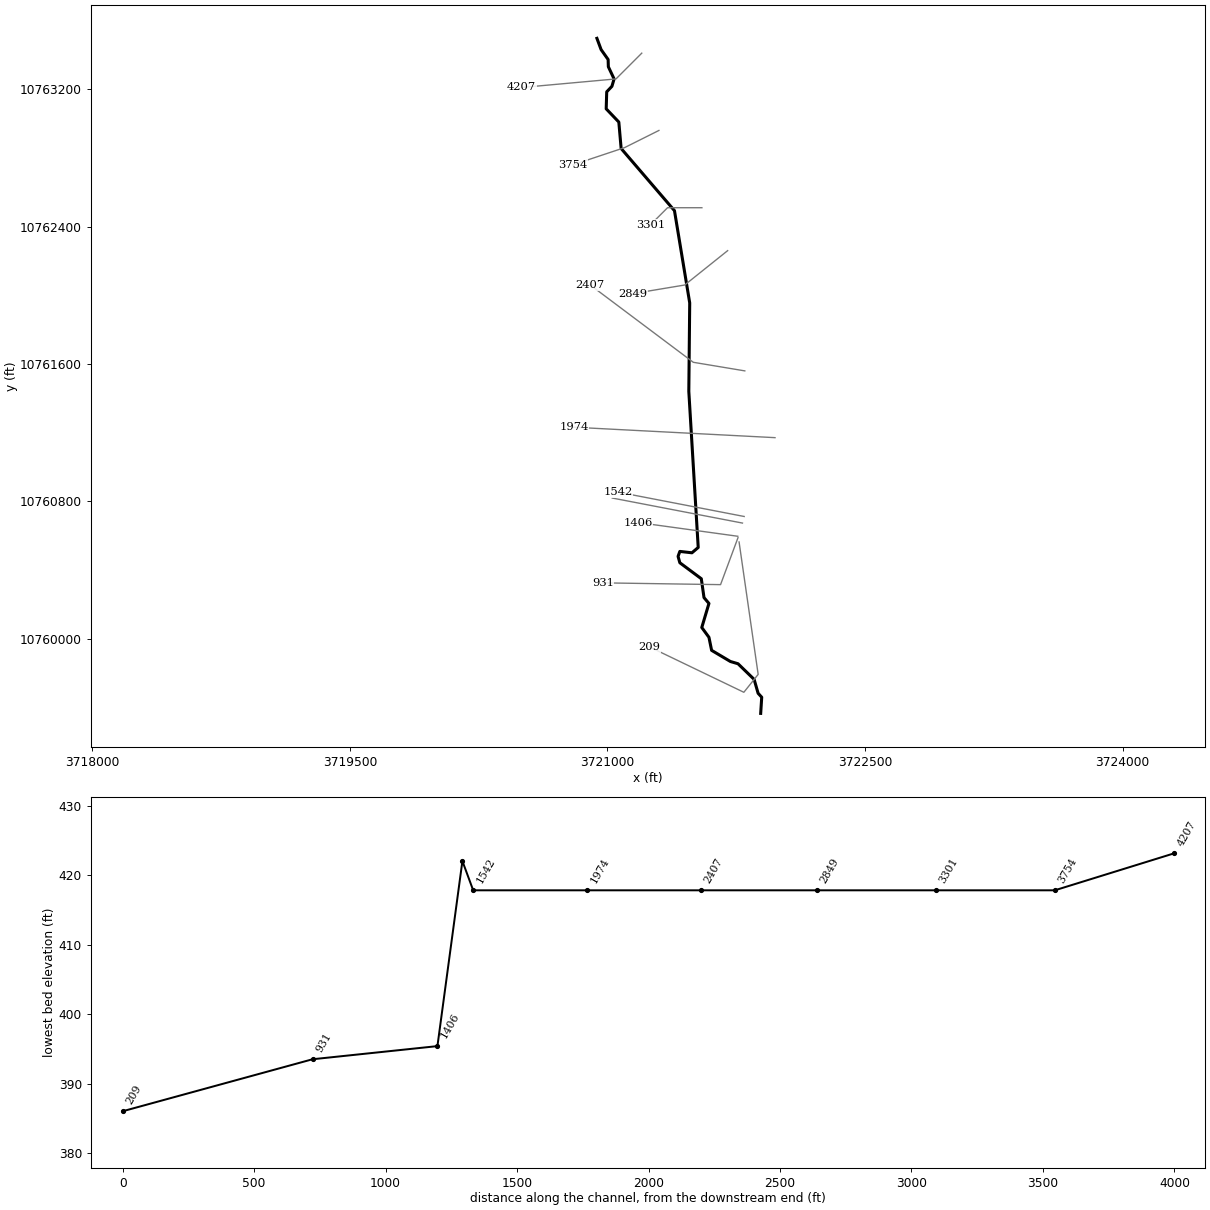
--- UNT 061 IN CACR.prj (project) ---

Proj Title=UNT 061 IN CACR Base Level Engineering
Current Plan=p01
Default Exp/Contr=0.3,0.1
English Units
Geom File=g01
Flow File=f01
Plan File=p01
BEGIN DESCRIPTION:
UNT 061 IN CACR
END DESCRIPTION:

--- UNT 061 IN CACR.p01 (plan) ---

Plan Title=Multiple Run
Short Identifier=Multiple
Geom File=g01
Flow File=f01
Subcritical Flow
K Sum by GR= 0
Std Step Tol= 0.01
Critical Tol= 0.01
Num of Std Step Trials= 20
Max Error Tol= 0.3
Flow Tol Ratio= 0.001
Split Flow NTrial= 30
Split Flow Tol= 0.02
Split Flow Ratio= 0.02
Log Output Level= 0
Friction Slope Method= 1
Unsteady Friction Slope Method= 2
Unsteady Bridges Friction Slope Method= 1
Parabolic Critical Depth
Global Vel Dist=  1 , 1 , 1
Global Log Level= 0
CheckData=True
Encroach Param= -1, 0, 0, 0
BEGIN DESCRIPTION:
Multiple Run
END DESCRIPTION:

--- UNT 061 IN CACR.f01 (steady flow) ---

Flow Title=Multiple
Number of Profiles=7
Profile Names=10-year,25-year,50-year,1pct_min,100-year,1pct_plu,500-year
River Rch & RM= UNT 061 IN CACR,Reach-1,4207
     289     376     445     388     525     709     729
River Rch & RM= UNT 061 IN CACR,Reach-1,3754
     452     604     728     645     872    1180    1254
Boundary for River Rch & Prof#=UNT 061 IN CACR,Reach-1,1
Up Type=0
Dn Type=3
Dn Slope=0.005
Boundary for River Rch & Prof#=UNT 061 IN CACR,Reach-1,2
Up Type=0
Dn Type=3
Dn Slope=0.005
Boundary for River Rch & Prof#=UNT 061 IN CACR,Reach-1,3
Up Type=0
Dn Type=3
Dn Slope=0.005
Boundary for River Rch & Prof#=UNT 061 IN CACR,Reach-1,4
Up Type=0
Dn Type=3
Dn Slope=0.005
Boundary for River Rch & Prof#=UNT 061 IN CACR,Reach-1,5
Up Type=0
Dn Type=3
Dn Slope=0.005
Boundary for River Rch & Prof#=UNT 061 IN CACR,Reach-1,6
Up Type=0
Dn Type=3
Dn Slope=0.005
Boundary for River Rch & Prof#=UNT 061 IN CACR,Reach-1,7
Up Type=0
Dn Type=3
Dn Slope=0.005

--- UNT 061 IN CACR.g01 (geometry) ---

Geom Title=Existing Conditions

River Reach=UNT 061 IN CACR,Reach-1
Reach XY= 30
      3720938.45     10763496.45      3720962.75     10763431.00
      3721003.75     10763373.00      3721005.00     10763331.00
      3721038.50     10763260.00      3721025.75     10763217.00
      3720995.50     10763185.00      3720992.50     10763086.00
      3721066.00     10763009.00      3721079.50     10762855.00
      3721390.00     10762493.00      3721478.75     10761956.00
      3721473.50     10761441.00      3721528.25     10760532.00
      3721491.75     10760501.00      3721421.25     10760509.00
      3721411.00     10760480.00      3721421.25     10760443.00
      3721546.25     10760350.00      3721562.00     10760240.00
      3721590.75     10760206.00      3721549.00     10760066.00
      3721590.75     10760009.00      3721606.25     10759933.00
      3721715.75     10759868.00      3721760.00     10759855.00
      3721853.75     10759764.00      3721877.00     10759683.00
      3721898.00     10759660.00      3721892.00     10759566.00

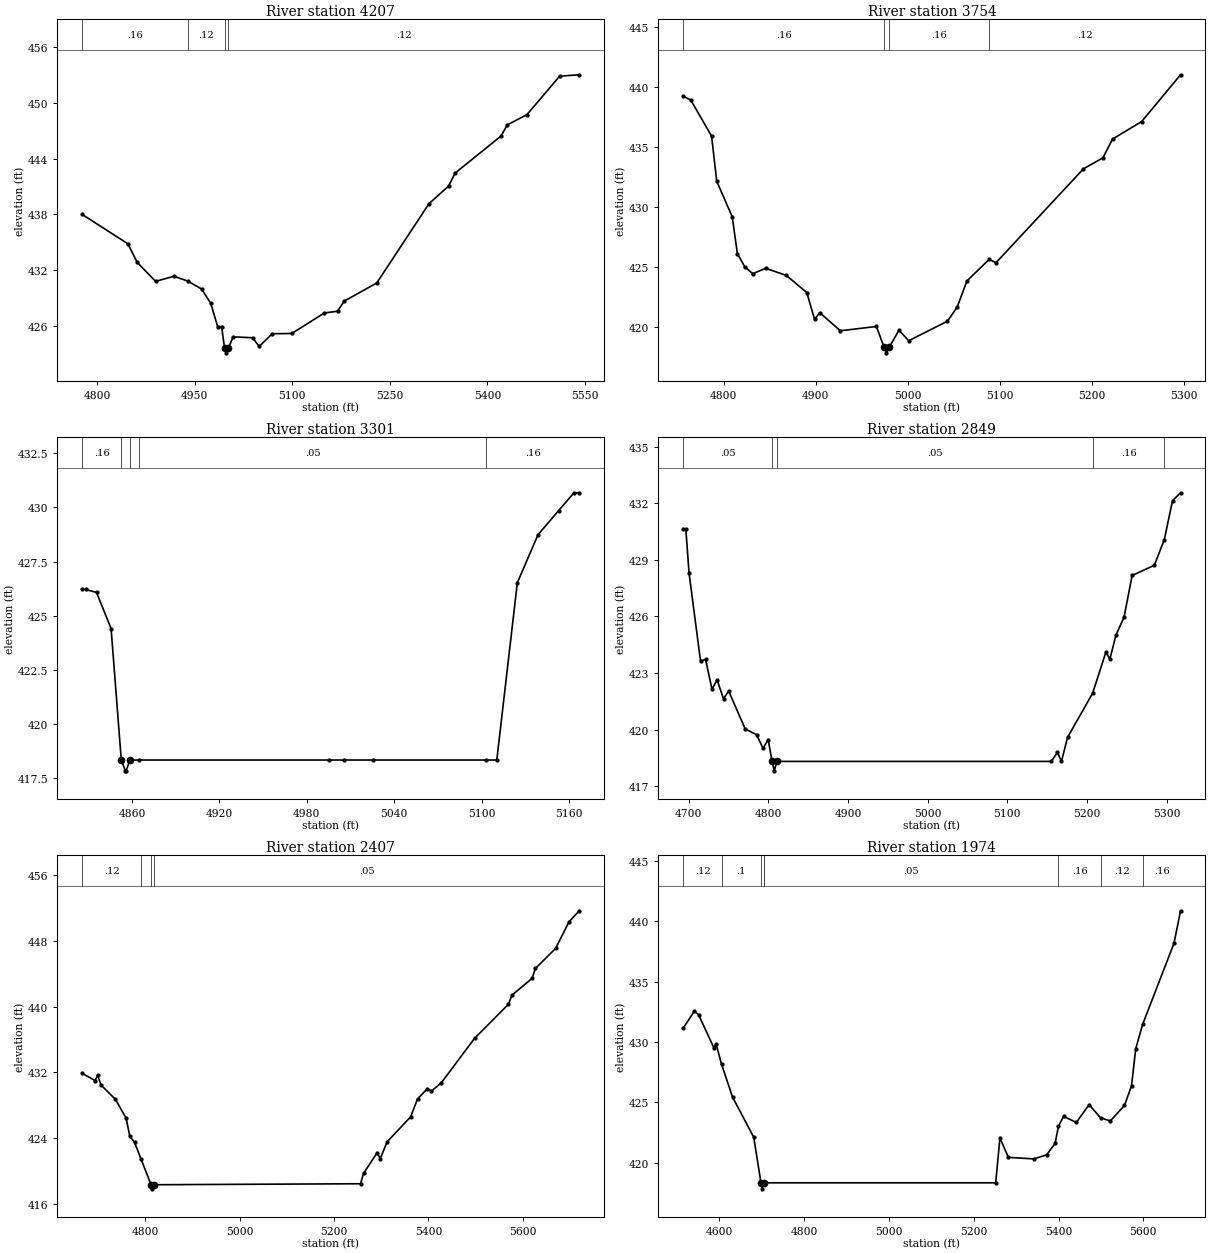
Type RM Length L Ch R = 1,4207,453,453,453
BEGIN DESCRIPTION:
UNT 061 IN CACR 8.0
END DESCRIPTION:
XS GIS Cut Line= 3
      3721199.63     10763410.21      3721049.61     10763260.19
      3720499.65     10763210.19
#Sta/Elev= 30
  4776.6  438.02  4847.3  434.84  4861.5  432.85  4889.8  430.81  4918.1  431.36
  4939.2  430.84  4960.5  429.99  4974.6  428.44  4985.2  425.95  4991.3  425.95
  4995.8  423.63  4998.6  423.13  5001.8  423.63  5008.9  424.85  5039.0  424.75
  5049.0  423.82  5069.1  425.18  5099.2  425.21  5149.4  427.42  5169.5  427.60
  5179.6  428.68  5229.8  430.64  5310.1  439.16  5340.2  441.05  5350.3  442.45
  5420.5  446.41  5430.6  447.63  5460.7  448.73  5510.9  452.86  5541.0  453.01
#Mann=4,-1,0
  4776.6    0.16       0  4939.2    0.12       0  4995.8    0.07       0
  5001.8    0.12       0
Bank Sta=4995.8,5001.8
Exp/Cntr=0.3,0.1

Type RM Length L Ch R = 1,3754,453,453,453
BEGIN DESCRIPTION:
UNT 061 IN CACR 7.0
END DESCRIPTION:
XS GIS Cut Line= 3
      3721299.57     10762960.17      3721099.61     10762860.19
      3720799.61     10762760.19
#Sta/Elev= 30
  4756.3  439.23  4764.6  438.88  4787.0  435.89  4792.6  432.13  4809.4  429.17
  4815.0  426.09  4823.3  424.97  4831.7  424.42  4845.7  424.87  4868.1  424.28
  4890.4  422.84  4898.8  420.61  4904.4  421.17  4926.8  419.66  4965.9  420.02
  4974.1  418.32  4976.8  417.82  4980.1  418.32  4990.4  419.70  5001.0  418.83
  5043.1  420.46  5053.7  421.65  5064.2  423.82  5088.3  425.61  5095.8  425.34
  5190.7  433.17  5211.8  434.08  5222.3  435.65  5253.9  437.11  5296.1  441.01
#Mann=4,-1,0
  4756.3    0.16       0  4974.1    0.07       0  4980.1    0.16       0
  5088.3    0.12       0
Bank Sta=4974.1,4980.1
Exp/Cntr=0.3,0.1

Type RM Length L Ch R = 1,3301,452,452,452
BEGIN DESCRIPTION:
UNT 061 IN CACR 6.0
END DESCRIPTION:
XS GIS Cut Line= 3
      3721549.66     10762510.19      3721349.61     10762510.19
      3721249.59     10762410.17
#Sta/Elev= 19
  4825.6  426.21  4828.1  426.21  4835.6  426.07  4845.6  424.40  4852.6  418.32
  4855.4  417.82  4855.9  417.82  4858.6  418.32  4865.0  418.32  4995.6  418.32
  5005.6  418.32  5025.6  418.32  5103.0  418.32  5110.5  418.32  5124.6  426.52
  5138.8  428.74  5152.9  429.85  5163.5  430.68  5167.1  430.68
#Mann=5,-1,0
  4825.6    0.16       0  4852.6   0.033       0  4858.6    0.16       0
  4865.0    0.05       0  5103.0    0.16       0
Bank Sta=4852.6,4858.6
Exp/Cntr=0.3,0.1

Type RM Length L Ch R = 1,2849,442,442,442
BEGIN DESCRIPTION:
UNT 061 IN CACR 5.0
END DESCRIPTION:
XS GIS Cut Line= 3
      3721699.63     10762260.21      3721449.61     10762060.19
      3721149.63     10762010.19
#Sta/Elev= 30
  4693.3  430.62  4696.5  430.62  4700.5  428.30  4714.9  423.64  4721.3  423.72
  4729.3  422.14  4735.7  422.64  4743.8  421.63  4750.2  422.05  4771.0  420.04
  4785.4  419.73  4793.4  419.01  4799.8  419.48  4804.8  418.32  4807.5  417.82
  4810.8  418.32  5155.4  418.32  5163.0  418.80  5168.1  418.32  5175.7  419.59
  5207.2  421.93  5223.8  424.10  5228.9  423.75  5236.5  425.01  5246.7  425.97
  5256.8  428.17  5284.7  428.71  5297.2  430.07  5307.5  432.13  5317.6  432.55
#Mann=5,-1,0
  4693.3    0.05       0  4804.8   0.033       0  4810.8    0.05       0
  5207.2    0.16       0  5297.2    0.05       0
Bank Sta=4804.8,4810.8
Exp/Cntr=0.3,0.1

Type RM Length L Ch R = 1,2407,433,433,433
BEGIN DESCRIPTION:
UNT 061 IN CACR 4.0
END DESCRIPTION:
XS GIS Cut Line= 3
      3721799.62     10761560.19      3721499.61     10761610.19
      3720899.57     10762060.22
#Sta/Elev= 30
  4665.6  431.91  4693.5  431.00  4698.6  431.67  4706.2  430.45  4736.6  428.72
  4759.4  426.40  4767.0  424.22  4777.1  423.49  4791.0  421.42  4812.1  418.32
  4814.9  417.82  4818.1  418.32  5256.2  418.44  5262.5  419.69  5291.6  422.24
  5297.9  421.48  5312.5  423.54  5362.5  426.60  5377.0  428.77  5397.9  430.02
  5406.2  429.72  5427.0  430.70  5497.9  436.15  5569.8  440.30  5577.0  441.40
  5619.8  443.45  5627.0  444.66  5669.8  447.11  5697.9  450.32  5719.8  451.69
#Mann=4,-1,0
  4665.6    0.12       0  4791.0    0.05       0  4812.1   0.033       0
  4818.1    0.05       0
Bank Sta=4812.1,4818.1
Exp/Cntr=0.3,0.1

Type RM Length L Ch R = 1,1974,432,432,432
BEGIN DESCRIPTION:
Mapping XS 8e3577f7
END DESCRIPTION:
XS GIS Cut Line= 2
      3721975.51     10761171.38      3720804.08     10761232.12
#Sta/Elev= 30
  4514.9  431.15  4540.8  432.54  4550.8  432.27  4587.2  429.49  4592.2  429.84
  4605.2  428.14  4631.0  425.43  4681.0  422.10  4698.1  418.32  4700.8  417.82
  4704.1  418.32  4704.5  418.32  5251.8  418.32  5261.8  422.03  5281.8  420.43
  5341.9  420.30  5372.0  420.64  5392.0  421.59  5399.8  423.01  5412.0  423.83
  5442.0  423.32  5472.1  424.80  5499.1  423.71  5522.2  423.45  5555.6  424.73
  5572.2  426.36  5582.2  429.44  5598.4  431.45  5672.4  438.17  5687.9  440.87
#Mann=8,-1,0
  4514.9    0.12       0  4605.2     0.1       0  4698.1   0.033       0
  4704.1     0.1       0  4704.5    0.05       0  5399.8    0.16       0
  5499.1    0.12       0  5598.4    0.16       0
Bank Sta=4698.1,4704.1
Exp/Cntr=0.3,0.1

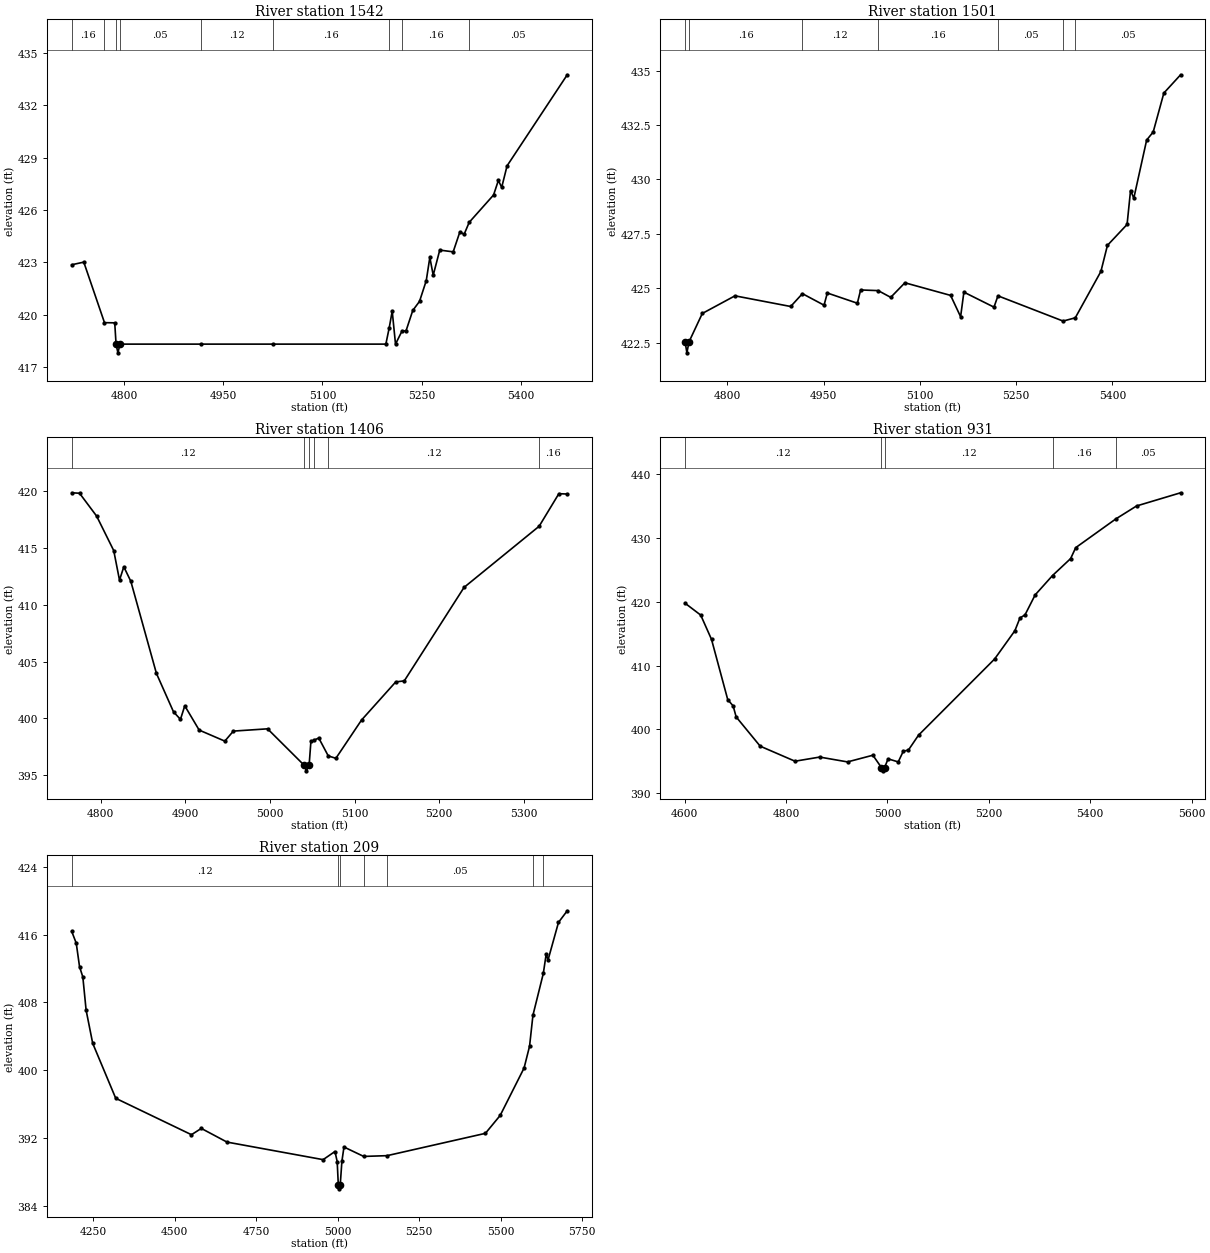
Type RM Length L Ch R = 1,1542,41,41,41
BEGIN DESCRIPTION:
Mapping XS b9d3f5c7
END DESCRIPTION:
XS GIS Cut Line= 2
      3721795.96     10760712.40      3721060.27     10760854.57
#Sta/Elev= 30
  4721.0  422.87  4739.2  423.02  4770.5  419.55  4786.0  419.54  4788.0  418.32
  4790.8  417.82  4794.0  418.32  4915.7  418.32  5025.6  418.32  5196.0  418.32
  5201.1  419.26  5205.6  420.21  5210.6  418.32  5220.4  419.07  5226.5  419.08
  5236.7  420.25  5246.9  420.77  5257.1  421.96  5262.5  423.29  5267.6  422.27
  5277.5  423.71  5297.8  423.61  5308.0  424.76  5314.3  424.61  5322.0  425.30
  5358.9  426.87  5366.1  427.70  5371.2  427.31  5379.3  428.54  5470.3  433.76
#Mann=9,-1,0
  4721.0    0.16       0  4770.5    0.05       0  4788.0    0.07       0
  4794.0    0.05       0  4915.7    0.12       0  5025.6    0.16       0
  5201.1    0.05       0  5220.4    0.16       0  5322.0    0.05       0
Bank Sta=4788,4794
Exp/Cntr=0.3,0.1

Type RM Length L Ch R = 1,1501,95,95,95
BEGIN DESCRIPTION:
Mapping XS feb27c10
END DESCRIPTION:
XS GIS Cut Line= 2
      3721785.90     10760674.07      3721027.69     10760819.85
#Sta/Elev= 30
  4734.3  422.53  4737.1  422.03  4740.3  422.53  4761.1  423.84  4812.0  424.65
  4898.8  424.16  4917.1  424.75  4950.8  424.22  4955.9  424.78  5002.7  424.31
  5007.8  424.92  5035.2  424.89  5054.7  424.58  5076.8  425.25  5148.0  424.67
  5163.6  423.69  5168.7  424.82  5215.6  424.13  5221.8  424.65  5323.3  423.49
  5342.3  423.64  5382.2  425.77  5392.4  426.97  5423.0  427.93  5428.4  429.49
  5433.5  429.14  5453.5  431.81  5463.7  432.18  5480.3  433.97  5506.4  434.81
#Mann=7,-1,0
  4734.3    0.07       0  4740.3    0.16       0  4917.1    0.12       0
  5035.2    0.16       0  5221.8    0.05       0  5323.3    0.16       0
  5342.3    0.05       0
Bank Sta=4734.3,4740.3
Exp/Cntr=0.3,0.1

Type RM Length L Ch R = 1,1406,475,475,475
BEGIN DESCRIPTION:
UNT 061 IN CACR 2.0
END DESCRIPTION:
XS GIS Cut Line= 2
      3721758.72     10760597.24      3721178.89     10760677.09
#Sta/Elev= 30
  4765.9  419.82  4775.1  419.78  4795.3  417.77  4815.5  414.74  4822.3  412.15
  4827.4  413.32  4835.7  412.04  4865.9  403.96  4886.1  400.58  4894.3  399.92
  4899.4  401.11  4916.4  398.98  4946.7  398.01  4956.8  398.89  4997.2  399.09
  5040.3  395.90  5043.1  395.40  5046.3  395.90  5048.4  397.98  5052.4  398.11
  5057.7  398.28  5068.9  396.71  5077.9  396.50  5108.2  399.86  5148.6  403.21
  5158.7  403.30  5229.3  411.51  5318.0  416.88  5341.3  419.74  5351.2  419.71
#Mann=6,-1,0
  4765.9    0.12       0  5040.3    0.07       0  5046.3    0.12       0
  5052.4    0.16       0  5068.9    0.12       0  5318.0    0.16       0
Bank Sta=5040.3,5046.3
Exp/Cntr=0.3,0.1

Type RM Length L Ch R = 1,931,722,722,722
BEGIN DESCRIPTION:
Mapping XS dbc179fd
END DESCRIPTION:
XS GIS Cut Line= 3
      3721759.89     10760589.03      3721658.31     10760315.56
      3720972.71     10760325.95
#Sta/Elev= 30
  4600.9  419.80  4631.7  417.94  4653.0  414.13  4685.0  404.68  4695.7  403.69
  4701.6  401.97  4749.0  397.38  4817.7  395.02  4866.4  395.67  4921.3  394.91
  4971.3  395.96  4988.3  394.01  4991.1  393.51  4994.3  394.01  5001.3  395.39
  5021.3  394.91  5031.3  396.59  5041.3  396.76  5061.3  399.10  5211.4  411.05
  5251.4  415.49  5261.4  417.49  5271.4  417.98  5291.4  421.11  5325.7  424.15
  5361.4  426.81  5371.4  428.52  5450.2  433.01  5491.4  435.06  5578.3  437.13
#Mann=5,-1,0
  4600.9    0.12       0  4988.3    0.07       0  4994.3    0.12       0
  5325.7    0.16       0  5450.2    0.05       0
Bank Sta=4988.3,4994.3
Exp/Cntr=0.3,0.1

Type RM Length L Ch R = 1,209,0,0,0
BEGIN DESCRIPTION:
UNT 061 IN CACR 1.0
END DESCRIPTION:
XS GIS Cut Line= 4
      3721766.20     10760563.85      3721877.31     10759792.98
      3721793.98     10759688.81      3721245.38     10759952.70
#Sta/Elev= 30
  4183.6  416.36  4197.4  414.98  4207.5  412.21  4217.6  411.00  4227.7  407.08
  4247.9  403.18  4318.6  396.70  4551.0  392.41  4581.3  393.15  4660.1  391.54
  4955.2  389.47  4991.6  390.43  4998.4  389.24  5001.8  386.53  5004.6  386.03
  5007.8  386.53  5012.8  389.26  5019.2  390.96  5079.8  389.85  5151.6  389.94
  5453.4  392.57  5498.7  394.68  5572.1  400.27  5588.9  402.84  5599.3  406.49
  5631.1  411.41  5640.0  413.71  5645.6  413.00  5677.7  417.43  5704.6  418.80
#Mann=7,-1,0
  4183.6    0.12       0  5001.8    0.07       0  5007.8    0.12       0
  5079.8    0.16       0  5151.6    0.05       0  5599.3    0.16       0
  5631.1    0.12       0
Bank Sta=5001.8,5007.8
Exp/Cntr=0.3,0.1

Chan Stop Cuts=-1