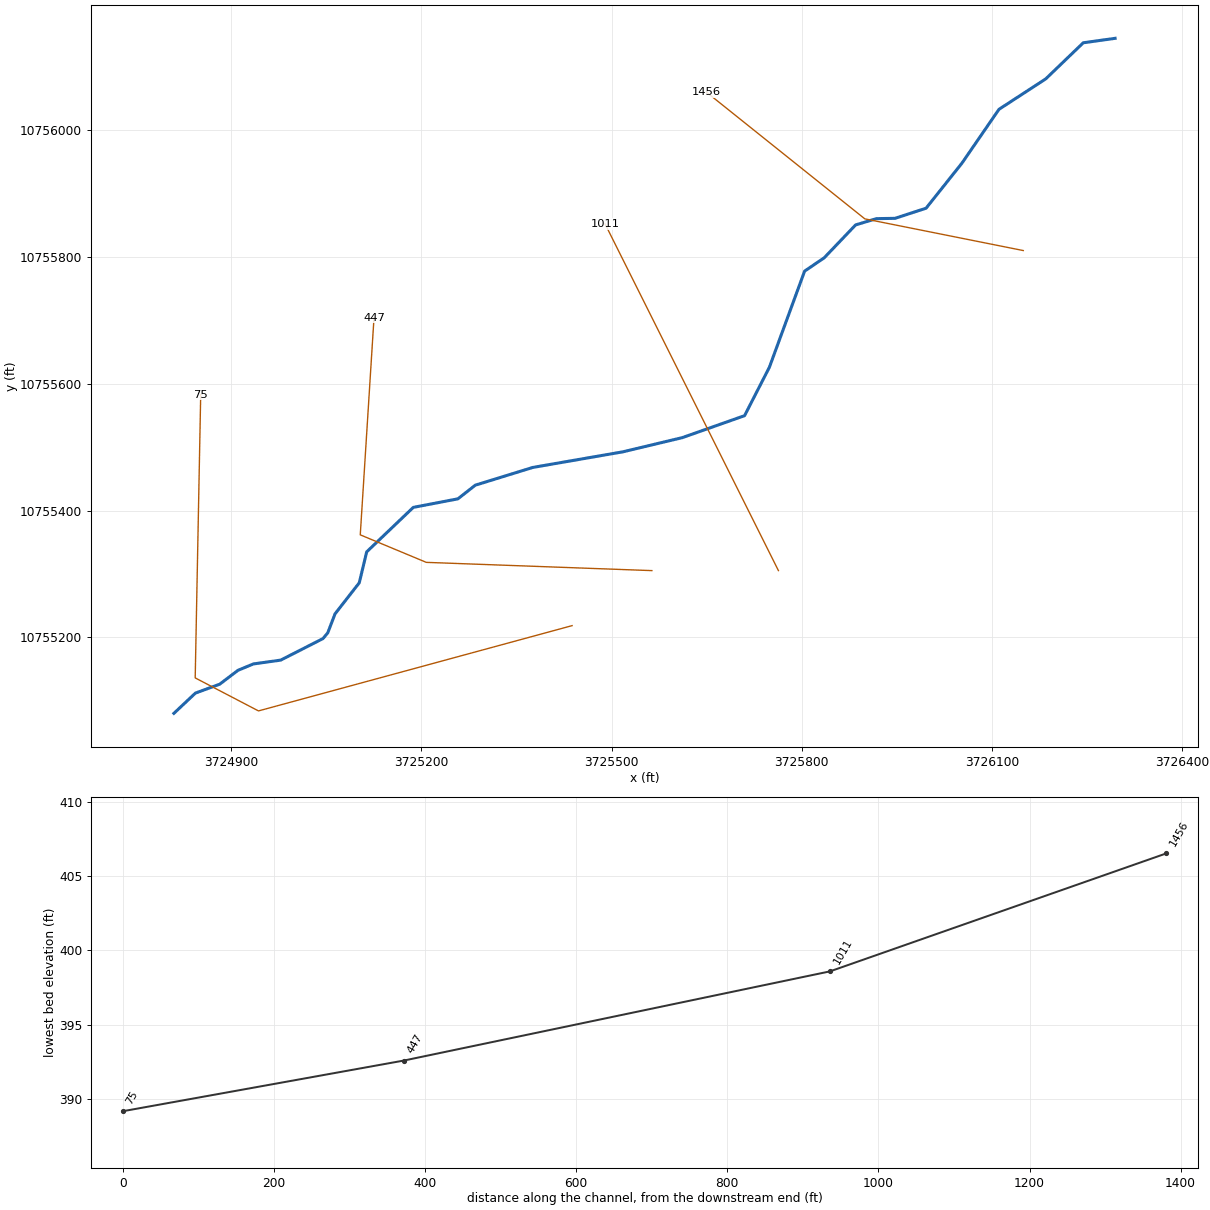
--- UNT 064 IN CACR.prj (project) ---

Proj Title=UNT 064 IN CACR Base Level Engineering
Current Plan=p01
Default Exp/Contr=0.3,0.1
English Units
Geom File=g01
Flow File=f01
Plan File=p01
Y Axis Title=Elevation
X Axis Title(PF)=Main Channel Distance
X Axis Title(XS)=Station
BEGIN DESCRIPTION:
UNT 064 IN CACR
END DESCRIPTION:
DSS Export Rating Curves= 0
DSS Export Rating Curve Sorted= 0
DSS Export Volume Flow Curves= 0
DXF OffsetX= 0
DXF OffsetY= 0
DXF ScaleX= 1
DXF ScaleY= 10

--- UNT 064 IN CACR.p01 (plan) ---

Plan Title=Multiple Run
Short Identifier=Multiple
Geom File=g01
Flow File=f01
Subcritical Flow
K Sum by GR= 0
Std Step Tol= 0.01
Critical Tol= 0.01
Num of Std Step Trials= 20
Max Error Tol= 0.3
Flow Tol Ratio= 0.001
Split Flow NTrial= 30
Split Flow Tol= 0.02
Split Flow Ratio= 0.02
Log Output Level= 0
Friction Slope Method= 1
Unsteady Friction Slope Method= 2
Unsteady Bridges Friction Slope Method= 1
Parabolic Critical Depth
Global Vel Dist=  1 , 1 , 1
Global Log Level= 0
CheckData=True
Encroach Param= -1, 0, 0, 0
BEGIN DESCRIPTION:
Multiple Run
END DESCRIPTION:

--- UNT 064 IN CACR.f01 (steady flow) ---

Flow Title=Multiple
Program Version=4.10
Number of Profiles= 7
Profile Names=10-year,25-year,50-year,1pct_min,100-year,1pct_plu,500-year
River Rch & RM=UNT 064 IN CACR,Reach-1         ,1456
     258     334     394     343     463     627     641
Boundary for River Rch & Prof#=UNT 064 IN CACR,Reach-1         , 1
Up Type= 0
Dn Type= 3
Dn Slope=0.005
Boundary for River Rch & Prof#=UNT 064 IN CACR,Reach-1         , 2
Up Type= 0
Dn Type= 3
Dn Slope=0.005
Boundary for River Rch & Prof#=UNT 064 IN CACR,Reach-1         , 3
Up Type= 0
Dn Type= 3
Dn Slope=0.005
Boundary for River Rch & Prof#=UNT 064 IN CACR,Reach-1         , 4
Up Type= 0
Dn Type= 3
Dn Slope=0.005
Boundary for River Rch & Prof#=UNT 064 IN CACR,Reach-1         , 5
Up Type= 0
Dn Type= 3
Dn Slope=0.005
Boundary for River Rch & Prof#=UNT 064 IN CACR,Reach-1         , 6
Up Type= 0
Dn Type= 3
Dn Slope=0.005
Boundary for River Rch & Prof#=UNT 064 IN CACR,Reach-1         , 7
Up Type= 0
Dn Type= 3
Dn Slope=0.005
DSS Import GetInterval= 0
DSS Import GetPeak= 0
DSS Import FillOption= 0

--- UNT 064 IN CACR.g01 (geometry) ---

Geom Title=Existing Conditions
Program Version=4.10

River Reach=UNT 064 IN CACR ,Reach-1
Reach XY= 30
       3726294.5       10756145.      3726244.25       10756138.
        3726185.       10756081.      3726111.25       10756033.
      3726052.75       10755948.      3725996.25       10755877.
      3725947.29     10755861.03      3725917.86     10755860.51
      3725885.05     10755850.61      3725835.57     10755798.79
      3725804.58      10755777.7        3725749.       10755626.
      3725709.89     10755549.68      3725611.61     10755515.02
      3725517.86     10755492.63      3725375.75       10755468.
      3725285.05     10755440.02      3725257.57     10755418.46
      3725187.25       10755405.       3725113.7     10755334.81
        3725102.       10755286.      3725063.75       10755237.
      3725052.25       10755207.      3725044.75       10755198.
        3724978.       10755164.        3724935.       10755158.
      3724910.75       10755148.      3724881.75       10755126.
       3724843.5       10755112.       3724809.5       10755080.

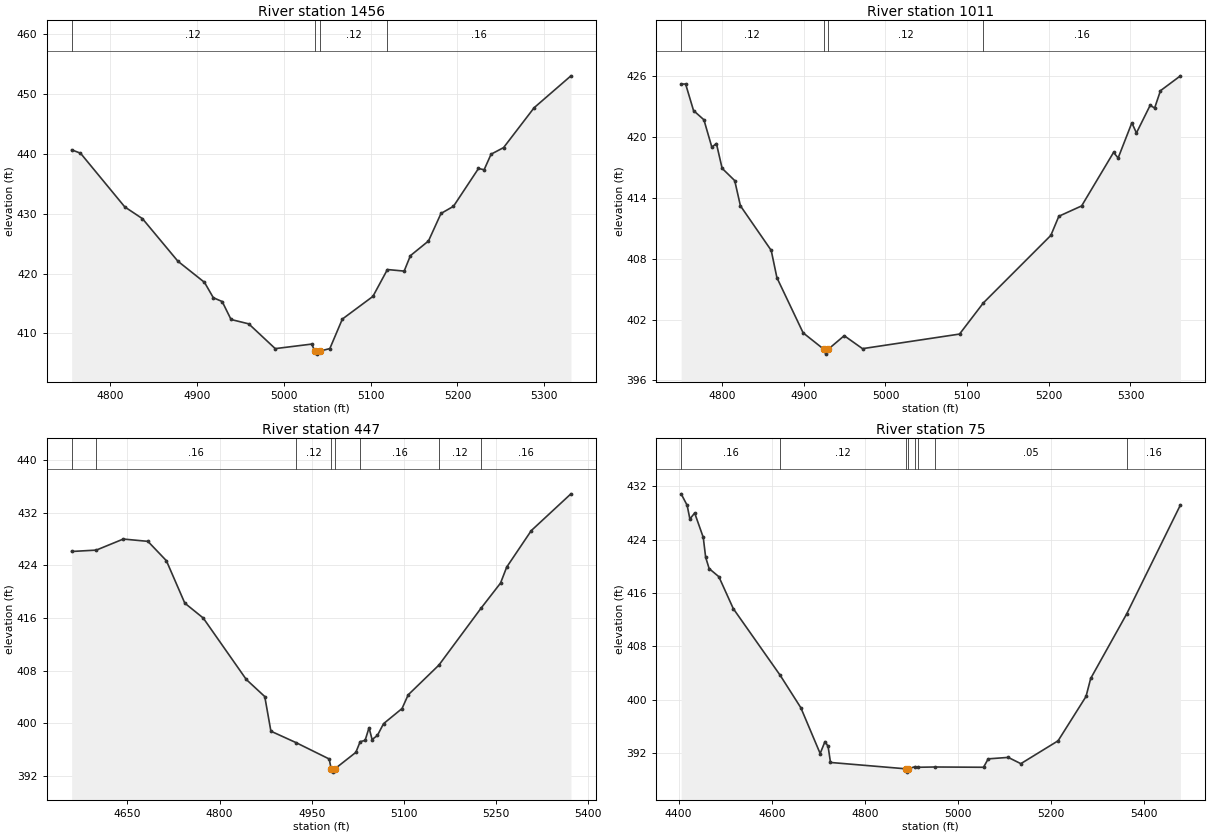
Type RM Length L Ch R = 1 ,1456    ,445,445,445
BEGIN DESCRIPTION:
UNT 064 IN CACR 3.0
END DESCRIPTION:
XS GIS Cut Line= 3
       3726149.6     10755810.19      3725899.61     10755860.19
      3725649.61     10756060.19
#Sta/Elev= 30
  4755.6   440.7  4765.8  440.14  4816.8  431.16  4837.2  429.19    4878  422.08
  4908.6  418.55  4918.8  415.98    4929  415.34  4939.2  412.34  4959.6  411.61
  4990.1  407.47  5032.2  408.23  5035.6  407.05  5038.3  406.55  5041.6  407.05
    5053  407.48  5067.4  412.41  5102.6   416.2  5119.3  420.69  5138.6  420.43
  5145.8  423.01  5166.6  425.46    5181  430.06  5195.4  431.26  5224.2  437.58
  5230.7  437.37  5238.7  439.97  5253.1  441.07  5288.3  447.74  5330.7  453.07
#Mann= 4 ,-1 , 0
  4755.6     .12       0  5035.6     .07       0  5041.6     .12       0
  5119.3     .16       0
Bank Sta=5035.6,5041.6
XS Rating Curve= 0 ,0
Exp/Cntr=0.3,0.1

Type RM Length L Ch R = 1 ,1011    ,564,564,564
BEGIN DESCRIPTION:
Mapping XS 9702eb86
END DESCRIPTION:
XS GIS Cut Line= 2
      3725763.28     10755305.26      3725489.85     10755852.11
#Sta/Elev= 30
  4749.8  425.25  4755.3  425.25    4765  422.63  4777.7  421.72  4787.4  419.02
    4793  419.38    4800  416.93  4815.4  415.72  4822.4  413.23  4860.1  408.83
  4867.1  406.13  4899.2  400.69  4924.2  399.09  4926.9  398.59  4930.2  399.09
  4949.5  400.41  4971.9  399.13  5090.7  400.57  5119.9  403.65  5202.5  410.31
  5212.3   412.2  5240.2  413.22  5279.3   418.5  5284.9  417.95  5301.7  421.42
  5307.3  420.42  5324.1  423.15  5329.6  422.88  5336.7  424.59  5361.2  426.06
#Mann= 4 ,-1 , 0
  4749.8     .12       0  4924.2     .07       0  4930.2     .12       0
  5119.9     .16       0
Bank Sta=4924.2,4930.2
XS Rating Curve= 0 ,0
Exp/Cntr=0.3,0.1

Type RM Length L Ch R = 1 ,447     ,372,372,372
BEGIN DESCRIPTION:
UNT 064 IN CACR 2.0
END DESCRIPTION:
XS GIS Cut Line= 4
      3725563.66     10755305.23      3725207.74     10755318.25
      3725103.57     10755361.66      3725125.27     10755704.56
#Sta/Elev= 30
  4559.3  426.09  4599.4   426.3  4643.4  427.98  4683.4  427.63  4713.5  424.69
  4743.5  418.24  4773.5  415.98  4843.5  406.65  4873.6  404.05  4883.6  398.79
  4924.1  397.07  4978.4  394.57  4981.7  393.07  4984.4  392.57  4987.7  393.07
  5021.8  395.57  5028.9   397.2  5036.9  397.39  5043.3  399.32  5048.3  397.52
  5056.9  398.14  5066.9  399.93    5097  402.23    5107  404.31    5157  408.83
  5225.3  417.44  5257.3  421.29  5267.3  423.71  5307.4  429.27  5371.9  434.85
#Mann= 8 ,-1 , 0
  4559.3     .12       0  4599.4     .16       0  4924.1     .12       0
  4981.7     .07       0  4987.7     .12       0  5028.9     .16       0
    5157     .12       0  5225.3     .16       0
Bank Sta=4981.7,4987.7
XS Rating Curve= 0 ,0
Exp/Cntr=0.3,0.1

Type RM Length L Ch R = 1 ,75      ,0,0,0
BEGIN DESCRIPTION:
UNT 064 IN CACR 1.0
END DESCRIPTION:
XS GIS Cut Line= 4
      3725437.72     10755218.41      3724942.98     10755083.88
      3724843.15     10755135.96      3724851.83     10755582.97
#Sta/Elev= 30
  4405.3   430.9  4418.2  429.18  4424.1  427.13  4434.4  428.02  4452.8  424.37
    4458  421.37  4465.5  419.68  4486.3  418.47  4517.3  413.68  4617.9  403.69
  4662.4  398.81  4703.9  391.94  4714.2  393.73  4720.9  393.02  4726.1   390.6
  4887.4  389.65  4890.2  389.15  4893.4  389.65  4907.6  389.97  4914.9  389.88
  4949.9  389.92  5054.8  389.88  5064.8  391.14  5107.8  391.36  5134.9  390.42
  5214.9  393.85  5274.9   400.5  5284.9   403.2  5362.1  412.87  5477.7  429.24
#Mann= 8 ,-1 , 0
  4405.3     .16       0  4617.9     .12       0  4887.4     .03       0
  4893.4     .12       0  4907.6     .05       0  4914.9     .12       0
  4949.9     .05       0  5362.1     .16       0
Bank Sta=4887.4,4893.4
XS Rating Curve= 0 ,0
Exp/Cntr=0.3,0.1

Chan Stop Cuts=-1
Use User Specified Reach Order=0
Composite Channel Slope=5