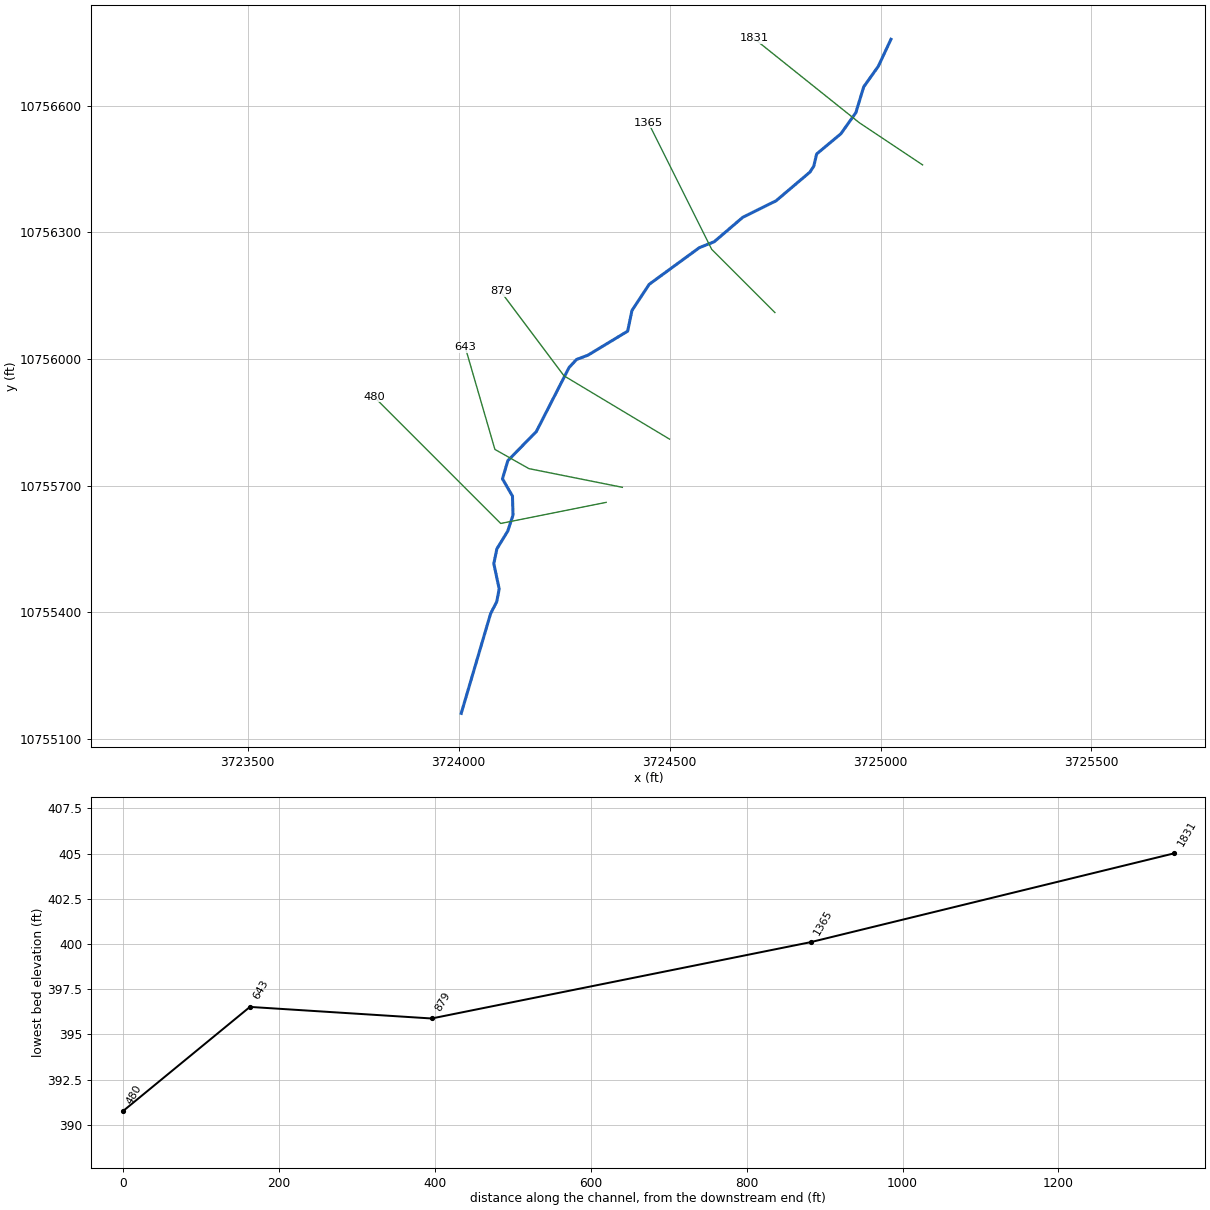
--- UNT 065 IN CACR.prj (project) ---

Proj Title=UNT 065 IN CACR Base Level Engineering
Current Plan=p01
Default Exp/Contr=0.3,0.1
English Units
Geom File=g01
Flow File=f01
Plan File=p01
Y Axis Title=Elevation
X Axis Title(PF)=Main Channel Distance
X Axis Title(XS)=Station
BEGIN DESCRIPTION:
UNT 065 IN CACR
END DESCRIPTION:
DSS Export Rating Curves= 0
DSS Export Rating Curve Sorted= 0
DSS Export Volume Flow Curves= 0
DXF OffsetX= 0
DXF OffsetY= 0
DXF ScaleX= 1
DXF ScaleY= 10

--- UNT 065 IN CACR.p01 (plan) ---

Plan Title=Multiple Run
Short Identifier=Multiple
Geom File=g01
Flow File=f01
Subcritical Flow
K Sum by GR= 0
Std Step Tol= 0.01
Critical Tol= 0.01
Num of Std Step Trials= 20
Max Error Tol= 0.3
Flow Tol Ratio= 0.001
Split Flow NTrial= 30
Split Flow Tol= 0.02
Split Flow Ratio= 0.02
Log Output Level= 0
Friction Slope Method= 1
Unsteady Friction Slope Method= 2
Unsteady Bridges Friction Slope Method= 1
Parabolic Critical Depth
Global Vel Dist=  1 , 1 , 1
Global Log Level= 0
CheckData=True
Encroach Param= -1, 0, 0, 0
BEGIN DESCRIPTION:
Multiple Run
END DESCRIPTION:

--- UNT 065 IN CACR.f01 (steady flow) ---

Flow Title=Multiple
Program Version=4.10
Number of Profiles= 7
Profile Names=10-year,25-year,50-year,1pct_min,100-year,1pct_plu,500-year
River Rch & RM=UNT 065 IN CACR,Reach-1         ,1831
     398     528     633     559     755    1022    1076
Boundary for River Rch & Prof#=UNT 065 IN CACR,Reach-1         , 1
Up Type= 0
Dn Type= 3
Dn Slope=0.012
Boundary for River Rch & Prof#=UNT 065 IN CACR,Reach-1         , 2
Up Type= 0
Dn Type= 3
Dn Slope=0.012
Boundary for River Rch & Prof#=UNT 065 IN CACR,Reach-1         , 3
Up Type= 0
Dn Type= 3
Dn Slope=0.012
Boundary for River Rch & Prof#=UNT 065 IN CACR,Reach-1         , 4
Up Type= 0
Dn Type= 3
Dn Slope=0.012
Boundary for River Rch & Prof#=UNT 065 IN CACR,Reach-1         , 5
Up Type= 0
Dn Type= 3
Dn Slope=0.012
Boundary for River Rch & Prof#=UNT 065 IN CACR,Reach-1         , 6
Up Type= 0
Dn Type= 3
Dn Slope=0.012
Boundary for River Rch & Prof#=UNT 065 IN CACR,Reach-1         , 7
Up Type= 0
Dn Type= 3
Dn Slope=0.012
DSS Import GetInterval= 0
DSS Import GetPeak= 0
DSS Import FillOption= 0

--- UNT 065 IN CACR.g01 (geometry) ---

Geom Title=Existing Conditions
Program Version=4.10

River Reach=UNT 065 IN CACR ,Reach-1
Reach XY= 30
      3725024.65      10756757.9      3724994.75       10756694.
        3724960.       10756645.       3724941.5       10756584.
        3724906.       10756534.       3724848.5       10756486.
      3724841.75       10756457.       3724832.5       10756443.
      3724752.25       10756375.       3724673.5       10756336.
      3724605.75       10756278.       3724570.5       10756264.
       3724451.5       10756177.      3724410.75       10756115.
       3724400.5       10756066.      3724306.25       10756009.
       3724279.5       10755999.      3724261.75       10755980.
        3724184.       10755828.       3724116.5       10755759.
      3724103.75       10755716.       3724127.5       10755675.
      3724128.75       10755630.      3724116.25       10755592.
       3724090.5       10755550.      3724083.25       10755515.
        3724096.       10755455.      3724090.25       10755425.
       3724075.5       10755396.        3724006.       10755160.

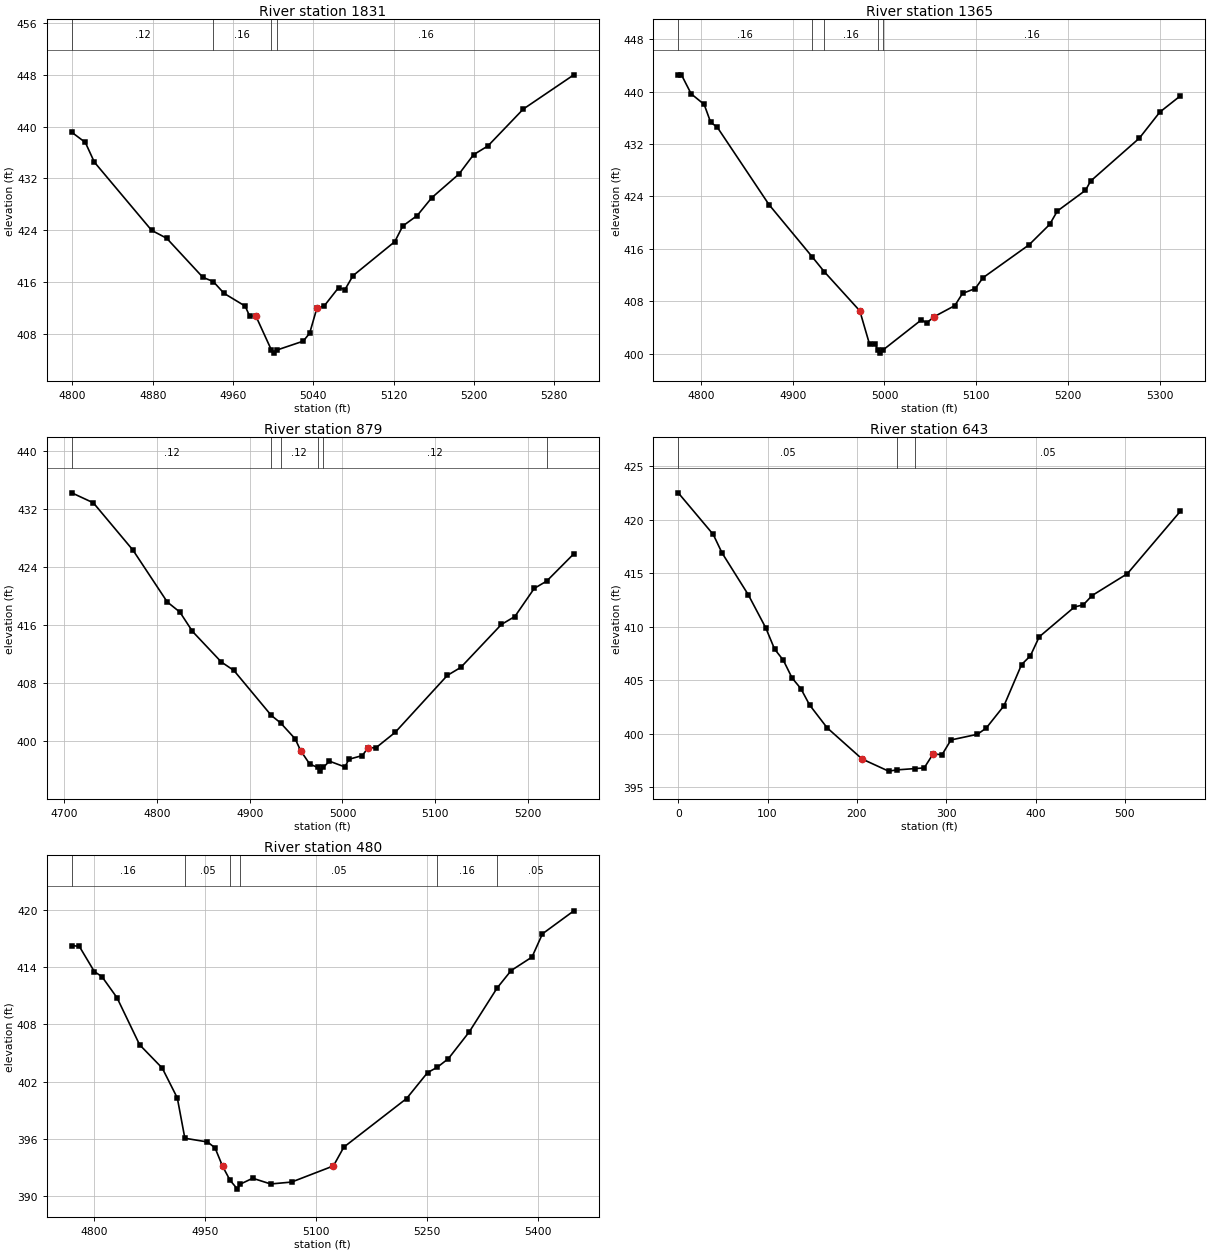
Type RM Length L Ch R = 1 ,1831    ,466,466,466
BEGIN DESCRIPTION:
UNT 065 IN CACR 4.0
END DESCRIPTION:
XS GIS Cut Line= 3
       3725099.6     10756460.19      3724949.61     10756560.19
      3724699.63     10756760.17
#Sta/Elev= 30
  4799.3  439.12  4812.8  437.55  4821.8  434.51  4878.9  423.97  4893.9  422.75
    4930  416.71  4940.3  416.07    4951  414.25  4972.1  412.27  4976.6  410.73
  4982.8  410.73  4998.2  405.51  5000.9  405.01  5004.2  405.51    5030  406.86
  5036.4  408.09  5043.6  411.96  5050.8  412.28  5065.2  415.12  5071.6  414.83
  5079.6  416.97  5121.2  422.22  5129.2  424.64  5143.6  426.26  5158.1  429.01
  5185.3  432.68  5199.7  435.65  5214.1  437.01  5249.3   442.7  5299.7  447.99
#Mann= 4 ,-1 , 0
  4799.3     .12       0  4940.3     .16       0  4998.2     .07       0
  5004.2     .16       0
Bank Sta=4982.8,5043.6
XS Rating Curve= 0 ,0
Exp/Cntr=0.3,0.1

Type RM Length L Ch R = 1 ,1365    ,486,486,486
BEGIN DESCRIPTION:
UNT 065 IN CACR 3.0
END DESCRIPTION:
XS GIS Cut Line= 3
      3724749.61     10756110.19      3724599.61     10756260.19
      3724449.63     10756560.15
#Sta/Elev= 30
  4775.1  442.56  4778.6  442.56  4789.2  439.66  4803.4  438.04  4810.5   435.3
  4817.5   434.6  4874.1  422.75  4920.9  414.84  4934.3  412.53  4973.1  406.55
  4983.7  401.46    4990  401.46  4992.6   400.6  4995.4   400.1  4998.6   400.6
  5040.3  405.18  5045.9   404.7  5054.3  405.67  5076.7  407.35  5085.1  409.21
    5099  409.95  5107.4   411.6  5157.7  416.63  5180.1  419.73  5188.5  421.78
  5219.2  424.94  5224.8  426.35  5277.9  432.89  5300.3  436.88  5322.6  439.34
#Mann= 5 ,-1 , 0
  4775.1     .16       0  4920.9     .12       0  4934.3     .16       0
  4992.6     .07       0  4998.6     .16       0
Bank Sta=4973.1,5054.3
XS Rating Curve= 0 ,0
Exp/Cntr=0.3,0.1

Type RM Length L Ch R = 1 ,879     ,233,233,233
BEGIN DESCRIPTION:
UNT 065 IN CACR 2.0
END DESCRIPTION:
XS GIS Cut Line= 3
      3724499.63     10755810.18      3724249.61     10755960.19
      3724099.59     10756160.22
#Sta/Elev= 30
    4708  434.18  4731.3   432.8  4774.1  426.28    4811  419.16  4824.6  417.77
  4838.2  415.11  4869.3   410.9  4882.9  409.73  4923.2  403.55  4933.3  402.51
    4949  400.32  4954.9  398.69  4964.6  396.87  4973.2  396.38    4976  395.88
  4979.2  396.38    4986  397.25  5002.7  396.45  5006.9  397.51  5021.4  398.02
  5027.7  399.11    5036  399.08  5056.9  401.22  5113.1  409.05  5127.7  410.16
  5171.4  416.06    5186  417.16  5206.9  421.03  5220.3  422.03  5249.6  425.79
#Mann= 6 ,-1 , 0
    4708     .12       0  4923.2     .16       0  4933.3     .12       0
  4973.2     .07       0  4979.2     .12       0  5220.3     .16       0
Bank Sta=4954.9,5027.7
XS Rating Curve= 0 ,0
Exp/Cntr=0.3,0.1

Type RM Length L Ch R = 1 ,643     ,163,163,163
XS GIS Cut Line= 4
     3724387.928    10755695.855     3724166.574    10755740.125
     3724085.845    10755785.698     3724015.532    10756027.886
#Sta/Elev= 30
       0  422.51   39.21  418.62   49.02   416.9   78.43  412.99   98.04  409.89
  107.84  407.92  117.64  406.88  127.45  405.22  137.25  404.23  147.06   402.7
  166.66  400.57  205.88  397.65  235.46  396.52  245.44  396.64   265.4  396.76
  275.37  396.82  285.35  398.13  295.33  398.05  305.31  399.43  335.03  399.96
   344.9  400.55  364.65  402.62  384.39  406.47  394.27  407.29  404.14  409.06
  443.63  411.85   453.5  412.05  463.38  412.92  502.87  414.96  562.11  420.78
#Mann= 3 ,-1 , 0
       0     .05       0  245.44     .03       0   265.4     .05       0
Bank Sta=205.88,285.35
XS Rating Curve= 0 ,0
Exp/Cntr=0.3,0.1

Type RM Length L Ch R = 1 ,480     ,0,0,0
BEGIN DESCRIPTION:
UNT 065 IN CACR 1.0
END DESCRIPTION:
XS GIS Cut Line= 3
      3724349.65      10755660.2      3724099.61     10755610.19
      3723799.58     10755910.22
#Sta/Elev= 30
  4769.7  416.26  4779.9  416.18  4800.3  413.53  4810.5  413.01  4830.9   410.8
  4861.5  405.87  4892.1  403.43  4912.5   400.3  4922.7  396.08  4953.3  395.69
  4963.5  395.08  4973.7  393.15  4983.9  391.67  4993.9  390.75  4997.1  391.25
  5014.5  391.89  5038.8  391.29  5067.1  391.49  5123.7  393.18  5137.8  395.15
  5222.7  400.24    5251  402.95  5264.5  403.53  5279.3  404.42  5307.5  407.22
  5345.3  411.83  5364.1  413.64  5392.4  415.06  5406.5  417.49    5449   419.9
#Mann= 6 ,-1 , 0
  4769.7     .16       0  4922.7     .05       0  4983.9     .03       0
  4997.1     .05       0  5264.5     .16       0  5345.3     .05       0
Bank Sta=4973.7,5123.7
XS Rating Curve= 0 ,0
Exp/Cntr=0.3,0.1

Chan Stop Cuts=-1
Use User Specified Reach Order=0
Composite Channel Slope=5