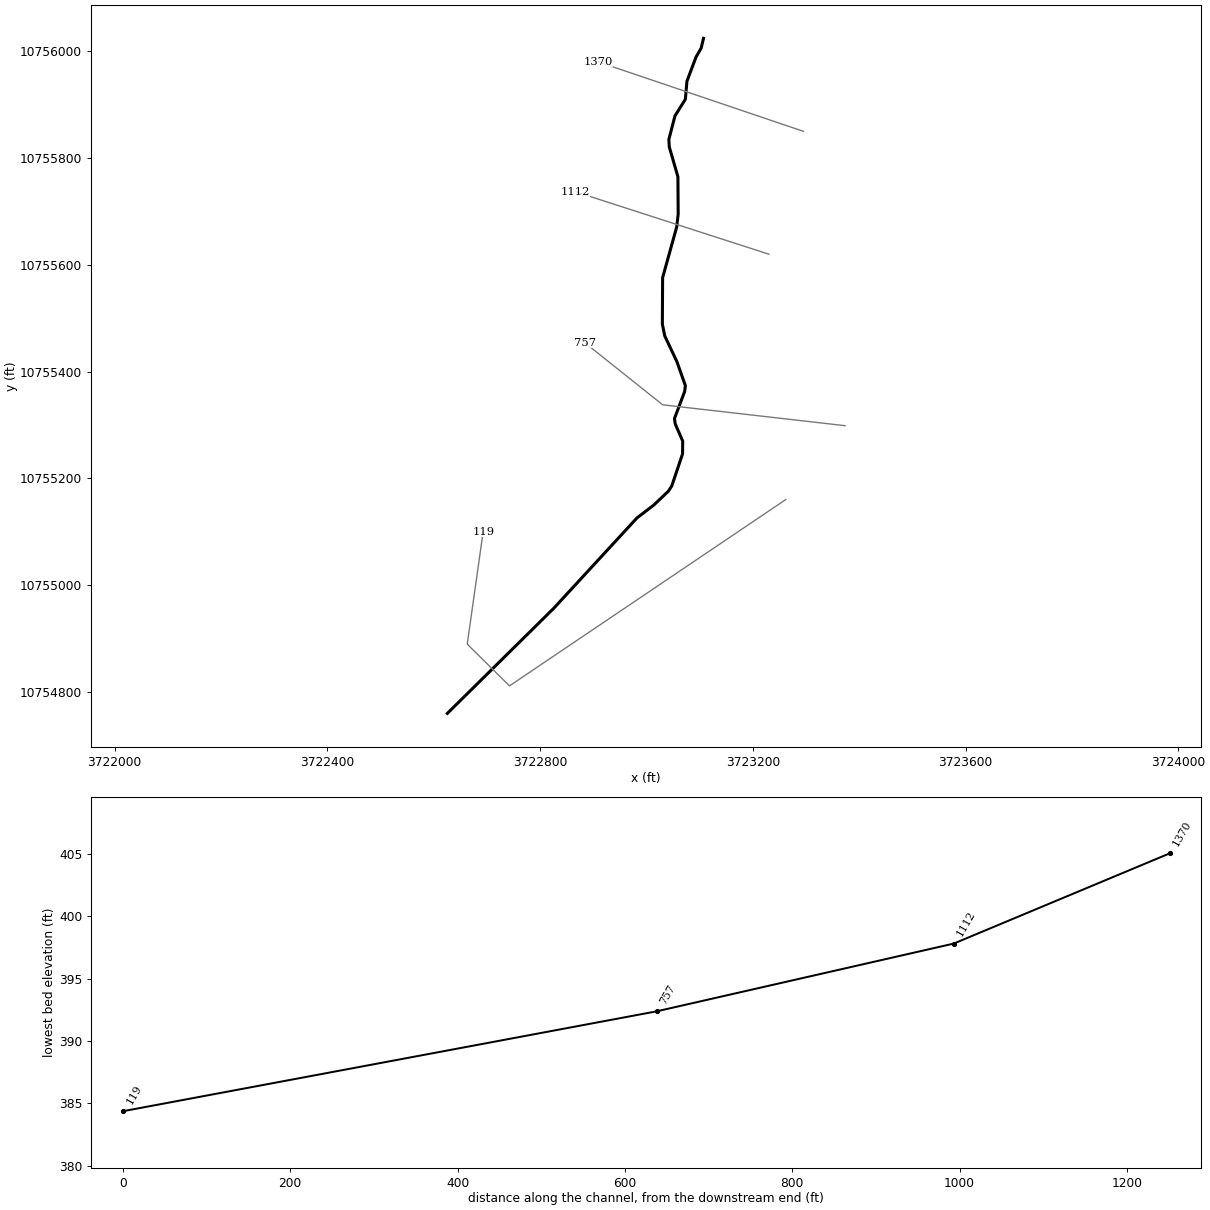
--- UNT 066 IN CACR.prj (project) ---

Proj Title=UNT 066 IN CACR Base Level Engineering
Current Plan=p01
Default Exp/Contr=0.3,0.1
English Units
Geom File=g01
Flow File=f01
Plan File=p01
BEGIN DESCRIPTION:
UNT 066 IN CACR
END DESCRIPTION:

--- UNT 066 IN CACR.p01 (plan) ---

Plan Title=Multiple Run
Short Identifier=Multiple
Geom File=g01
Flow File=f01
Subcritical Flow
K Sum by GR= 0
Std Step Tol= 0.01
Critical Tol= 0.01
Num of Std Step Trials= 20
Max Error Tol= 0.3
Flow Tol Ratio= 0.001
Split Flow NTrial= 30
Split Flow Tol= 0.02
Split Flow Ratio= 0.02
Log Output Level= 0
Friction Slope Method= 1
Unsteady Friction Slope Method= 2
Unsteady Bridges Friction Slope Method= 1
Parabolic Critical Depth
Global Vel Dist=  1 , 1 , 1
Global Log Level= 0
CheckData=True
Encroach Param= -1, 0, 0, 0
BEGIN DESCRIPTION:
Multiple Run
END DESCRIPTION:

--- UNT 066 IN CACR.f01 (steady flow) ---

Flow Title=Multiple
Number of Profiles=7
Profile Names=10-year,25-year,50-year,1pct_min,100-year,1pct_plu,500-year
River Rch & RM= UNT 066 IN CACR,Reach-1,1370
     189     238     275     235     318     430     424
Boundary for River Rch & Prof#=UNT 066 IN CACR,Reach-1,1
Up Type=0
Dn Type=3
Dn Slope=0.005
Boundary for River Rch & Prof#=UNT 066 IN CACR,Reach-1,2
Up Type=0
Dn Type=3
Dn Slope=0.005
Boundary for River Rch & Prof#=UNT 066 IN CACR,Reach-1,3
Up Type=0
Dn Type=3
Dn Slope=0.005
Boundary for River Rch & Prof#=UNT 066 IN CACR,Reach-1,4
Up Type=0
Dn Type=3
Dn Slope=0.005
Boundary for River Rch & Prof#=UNT 066 IN CACR,Reach-1,5
Up Type=0
Dn Type=3
Dn Slope=0.005
Boundary for River Rch & Prof#=UNT 066 IN CACR,Reach-1,6
Up Type=0
Dn Type=3
Dn Slope=0.005
Boundary for River Rch & Prof#=UNT 066 IN CACR,Reach-1,7
Up Type=0
Dn Type=3
Dn Slope=0.005

--- UNT 066 IN CACR.g01 (geometry) ---

Geom Title=Existing Conditions

River Reach=UNT 066 IN CACR,Reach-1
Reach XY= 27
      3723107.10     10756024.22      3723102.75     10756006.00
      3723093.00     10755989.00      3723076.00     10755944.00
      3723073.00     10755910.00      3723053.50     10755879.00
      3723042.00     10755835.00      3723042.75     10755821.00
      3723059.00     10755765.00      3723059.50     10755695.00
      3723056.75     10755671.00      3723030.25     10755576.00
      3723029.75     10755489.00      3723034.25     10755467.00
      3723057.00     10755419.00      3723073.00     10755374.00
      3723071.75     10755363.00      3723052.50     10755312.00
      3723054.00     10755302.00      3723068.00     10755270.00
      3723067.75     10755246.00      3723047.50     10755186.00
      3723041.00     10755176.00      3723013.50     10755150.00
      3722982.00     10755126.00      3722825.75     10754957.00
      3722625.50     10754760.00

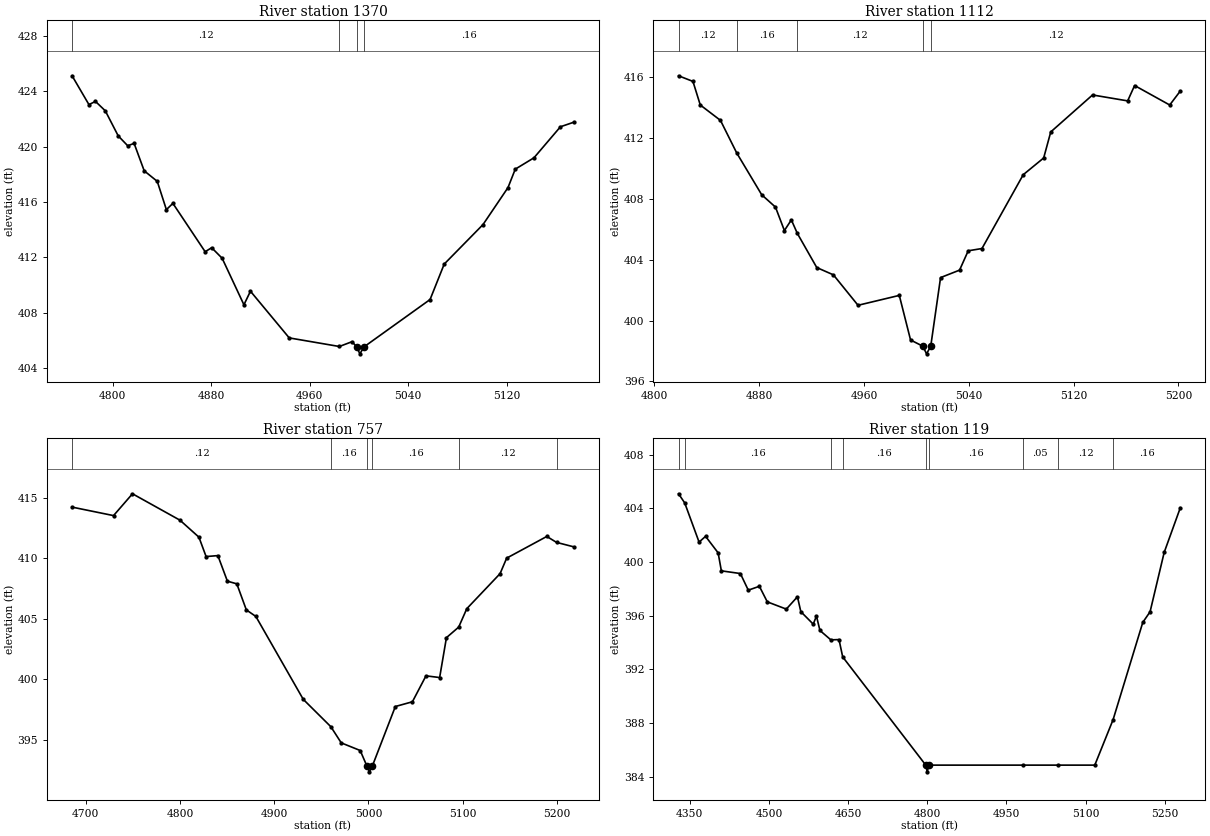
Type RM Length L Ch R = 1,1370,258,258,258
BEGIN DESCRIPTION:
UNT 066 IN CACR 2.0
END DESCRIPTION:
XS GIS Cut Line= 2
      3723295.16     10755850.01      3722908.92     10755980.20
#Sta/Elev= 30
  4766.9  425.11  4780.6  423.03  4785.9  423.26  4793.9  422.58  4804.4  420.77
  4812.1  420.06  4817.3  420.23  4825.5  418.25  4836.1  417.49  4843.5  415.45
  4848.8  415.90  4875.0  412.41  4880.3  412.70  4888.8  411.94  4906.5  408.58
  4911.8  409.56  4943.3  406.19  4984.0  405.57  4994.4  405.92  4998.0  405.54
  5000.7  405.04  5004.0  405.54  5057.7  408.96  5069.2  411.52  5100.7  414.37
  5121.0  417.04  5126.9  418.37  5142.1  419.19  5163.6  421.43  5174.5  421.76
#Mann=4,-1,0
  4766.9    0.12       0  4984.0    0.16       0  4998.0    0.07       0
  5004.0    0.16       0
Bank Sta=4998,5004
Exp/Cntr=0.3,0.1

Type RM Length L Ch R = 1,1112,355,355,355
BEGIN DESCRIPTION:
Mapping XS 94499402
END DESCRIPTION:
XS GIS Cut Line= 2
      3723230.06     10755619.97      3722865.43     10755737.17
#Sta/Elev= 30
  4818.5  416.08  4829.5  415.71  4835.1  414.16  4850.5  413.15  4862.9  411.01
  4882.0  408.26  4892.5  407.45  4899.3  405.91  4904.6  406.61  4909.2  405.72
  4924.0  403.48  4936.7  403.00  4955.5  401.00  4987.0  401.65  4995.6  398.72
  5005.0  398.31  5007.8  397.81  5011.0  398.31  5018.5  402.82  5033.0  403.31
  5039.6  404.58  5050.1  404.73  5081.6  409.58  5097.2  410.68  5102.6  412.39
  5134.5  414.82  5161.3  414.43  5166.6  415.44  5193.4  414.16  5201.5  415.08
#Mann=5,-1,0
  4818.5    0.12       0  4862.9    0.16       0  4909.2    0.12       0
  5005.0    0.07       0  5011.0    0.12       0
Bank Sta=5005,5011
Exp/Cntr=0.3,0.1

Type RM Length L Ch R = 1,757,638,638,638
BEGIN DESCRIPTION:
Mapping XS 37fd1c3c
END DESCRIPTION:
XS GIS Cut Line= 3
      3723373.33     10755298.79      3723030.40     10755337.86
      3722883.76     10755454.31
#Sta/Elev= 30
  4685.6  414.22  4729.6  413.52  4749.7  415.32  4800.1  413.14  4820.2  411.74
  4827.8  410.14  4840.3  410.22  4850.4  408.11  4860.4  407.89  4870.5  405.74
  4880.6  405.20  4930.9  398.36  4960.2  396.10  4971.2  394.77  4991.3  394.14
  4998.3  392.88  5001.1  392.38  5004.3  392.88  5028.6  397.77  5046.7  398.16
  5061.1  400.30  5075.6  400.16  5082.8  403.45  5095.8  404.32  5104.4  405.84
  5139.7  408.73  5146.7  410.01  5189.3  411.80  5199.6  411.31  5218.0  410.94
#Mann=6,-1,0
  4685.6    0.12       0  4960.2    0.16       0  4998.3    0.07       0
  5004.3    0.16       0  5095.8    0.12       0  5199.6    0.16       0
Bank Sta=4998.3,5004.3
Exp/Cntr=0.3,0.1

Type RM Length L Ch R = 1,119,0,0,0
BEGIN DESCRIPTION:
UNT 066 IN CACR 1.0
END DESCRIPTION:
XS GIS Cut Line= 4
      3723261.89     10755160.48      3722742.34     10754811.51
      3722662.91     10754889.63      3722692.85     10755100.53
#Sta/Elev= 30
  4328.9  405.08  4340.6  404.40  4367.8  401.48  4380.1  401.91  4403.9  400.68
  4410.0  399.34  4446.0  399.14  4461.0  397.90  4482.0  398.19  4497.0  397.03
  4533.0  396.49  4554.1  397.41  4560.5  396.30  4584.0  395.37  4590.1  395.97
  4596.7  394.90  4617.3  394.20  4632.8  394.22  4639.8  392.93  4797.1  384.87
  4799.8  384.37  4803.1  384.87  4980.7  384.87  5047.4  384.87  5117.2  384.87
  5151.9  388.26  5208.1  395.50  5221.9  396.29  5248.6  400.71  5279.2  404.04
#Mann=9,-1,0
  4328.9    0.12       0  4340.6    0.16       0  4617.3    0.12       0
  4639.8    0.16       0  4797.1   0.033       0  4803.1    0.16       0
  4980.7    0.05       0  5047.4    0.12       0  5151.9    0.16       0
Bank Sta=4797.1,4803.1
Exp/Cntr=0.3,0.1

Chan Stop Cuts=-1