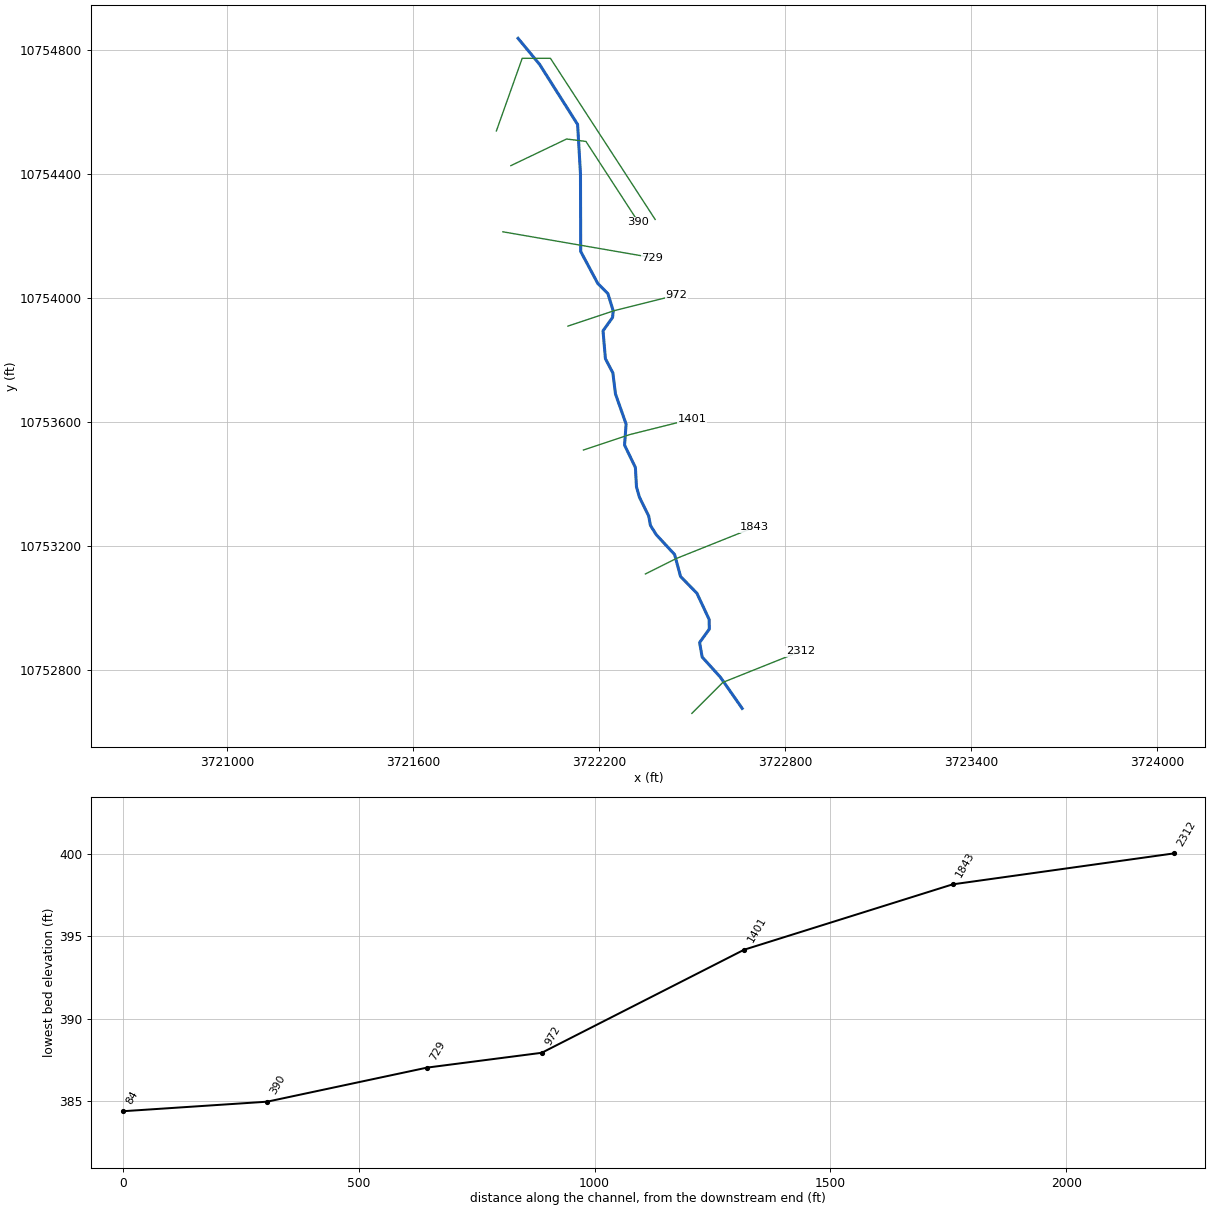
--- UNT 067 IN CACR.prj (project) ---

Proj Title=UNT 067 IN CACR Base Level Engineering
Current Plan=p01
Default Exp/Contr=0.3,0.1
English Units
Geom File=g01
Flow File=f01
Plan File=p01
BEGIN DESCRIPTION:
UNT 067 IN CACR
END DESCRIPTION:

--- UNT 067 IN CACR.p01 (plan) ---

Plan Title=Multiple Run
Short Identifier=Multiple
Geom File=g01
Flow File=f01
Subcritical Flow
K Sum by GR= 0
Std Step Tol= 0.01
Critical Tol= 0.01
Num of Std Step Trials= 20
Max Error Tol= 0.3
Flow Tol Ratio= 0.001
Split Flow NTrial= 30
Split Flow Tol= 0.02
Split Flow Ratio= 0.02
Log Output Level= 0
Friction Slope Method= 1
Unsteady Friction Slope Method= 2
Unsteady Bridges Friction Slope Method= 1
Parabolic Critical Depth
Global Vel Dist=  1 , 1 , 1
Global Log Level= 0
CheckData=True
Encroach Param= -1, 0, 0, 0
BEGIN DESCRIPTION:
Multiple Run
END DESCRIPTION:

--- UNT 067 IN CACR.f01 (steady flow) ---

Flow Title=Multiple
Number of Profiles=7
Profile Names=10-year,25-year,50-year,1pct_min,100-year,1pct_plu,500-year
River Rch & RM= UNT 067 IN CACR,Reach-1,2312
     304     394     466     406     549     743     761
Boundary for River Rch & Prof#=UNT 067 IN CACR,Reach-1,1
Up Type=0
Dn Type=3
Dn Slope=0.005
Boundary for River Rch & Prof#=UNT 067 IN CACR,Reach-1,2
Up Type=0
Dn Type=3
Dn Slope=0.005
Boundary for River Rch & Prof#=UNT 067 IN CACR,Reach-1,3
Up Type=0
Dn Type=3
Dn Slope=0.005
Boundary for River Rch & Prof#=UNT 067 IN CACR,Reach-1,4
Up Type=0
Dn Type=3
Dn Slope=0.005
Boundary for River Rch & Prof#=UNT 067 IN CACR,Reach-1,5
Up Type=0
Dn Type=3
Dn Slope=0.005
Boundary for River Rch & Prof#=UNT 067 IN CACR,Reach-1,6
Up Type=0
Dn Type=3
Dn Slope=0.005
Boundary for River Rch & Prof#=UNT 067 IN CACR,Reach-1,7
Up Type=0
Dn Type=3
Dn Slope=0.005

--- UNT 067 IN CACR.g01 (geometry) ---

Geom Title=Existing Conditions

River Reach=UNT 067 IN CACR,Reach-1
Reach XY= 30
      3722661.98     10752676.15      3722591.50     10752777.00
      3722532.75     10752842.00      3722524.50     10752889.00
      3722555.75     10752932.00      3722555.50     10752963.00
      3722515.75     10753048.00      3722463.00     10753102.00
      3722443.75     10753173.00      3722384.50     10753237.00
      3722365.75     10753267.00      3722360.25     10753297.00
      3722330.25     10753358.00      3722320.75     10753391.00
      3722317.25     10753454.00      3722282.25     10753526.00
      3722287.25     10753594.00      3722253.00     10753691.00
      3722244.50     10753759.00      3722220.50     10753805.00
      3722212.75     10753895.00      3722243.50     10753938.00
      3722245.75     10753959.00      3722228.50     10754015.00
      3722195.75     10754048.00      3722140.75     10754151.00
      3722140.00     10754401.00      3722130.75     10754561.00
      3722008.00     10754755.00      3721938.50     10754839.00

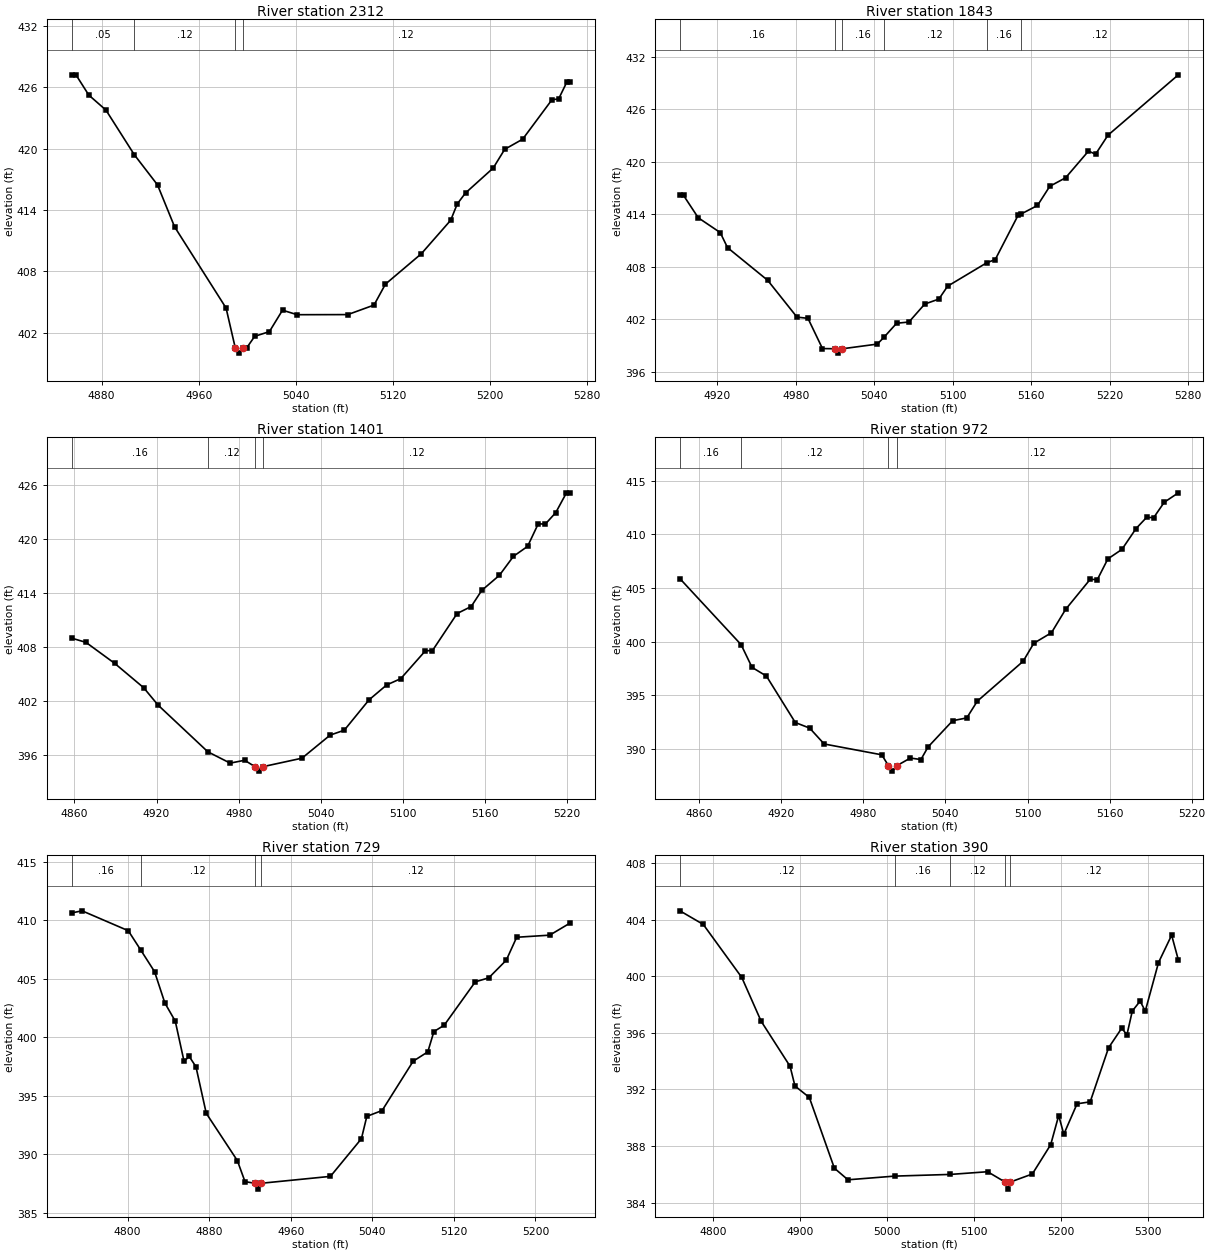
Type RM Length L Ch R = 1,2312,469,469,469
BEGIN DESCRIPTION:
UNT 067 IN CACR 5.0
END DESCRIPTION:
XS GIS Cut Line= 3
      3722499.58     10752660.16      3722599.61     10752760.19
      3722849.59     10752860.18
#Sta/Elev= 30
  4855.2  427.19  4858.8  427.19  4869.4  425.21  4883.5  423.75  4906.9  419.39
  4926.0  416.45  4940.1  412.35  4982.5  404.43  4990.1  400.53  4992.9  400.03
  4996.1  400.53  4999.4  400.53  5006.1  401.67  5018.2  402.13  5029.0  404.22
  5041.1  403.78  5082.8  403.79  5104.4  404.72  5113.8  406.76  5143.4  409.73
  5167.6  413.00  5173.0  414.59  5179.8  415.66  5202.6  418.09  5212.1  419.92
  5226.9  420.91  5251.1  424.77  5256.5  424.83  5263.2  426.46  5265.9  426.46
#Mann=4,-1,0
  4855.2    0.05       0  4906.9    0.12       0  4990.1    0.07       0
  4996.1    0.12       0
Bank Sta=4990.1,4996.1
Exp/Cntr=0.3,0.1

Type RM Length L Ch R = 1,1843,442,442,442
BEGIN DESCRIPTION:
UNT 067 IN CACR 4.0
END DESCRIPTION:
XS GIS Cut Line= 3
      3722349.57     10753110.17      3722449.61     10753160.19
      3722699.61     10753260.19
#Sta/Elev= 30
  4891.3  416.14  4894.1  416.14  4905.3  413.60  4922.1  411.91  4927.7  410.19
  4958.4  406.46  4980.8  402.26  4989.2  402.12  5000.3  398.67  5009.6  398.65
  5012.3  398.15  5015.6  398.65  5042.2  399.18  5047.2  399.94  5057.0  401.56
  5066.4  401.70  5078.5  403.75  5089.3  404.32  5096.0  405.79  5126.0  408.47
  5132.4  408.83  5149.9  413.89  5152.2  414.03  5164.7  415.00  5174.1  417.19
  5186.2  418.16  5203.7  421.21  5209.1  420.85  5218.6  423.02  5272.4  429.91
#Mann=6,-1,0
  4891.3    0.16       0  5009.6    0.07       0  5015.6    0.16       0
  5047.2    0.12       0  5126.0    0.16       0  5152.2    0.12       0
Bank Sta=5009.6,5015.6
Exp/Cntr=0.3,0.1

Type RM Length L Ch R = 1,1401,429,429,429
BEGIN DESCRIPTION:
UNT 067 IN CACR 3.0
END DESCRIPTION:
XS GIS Cut Line= 3
      3722149.62     10753510.19      3722299.61     10753560.19
      3722499.65     10753610.20
#Sta/Elev= 30
  4857.9  408.98  4868.4  408.51  4889.5  406.16  4910.6  403.46  4921.1  401.53
  4957.5  396.33  4973.8  395.07  4984.4  395.39  4991.9  394.68  4994.7  394.18
  4997.9  394.68  5026.3  395.62  5046.9  398.19  5057.2  398.73  5075.3  402.11
  5088.2  403.77  5098.5  404.47  5116.5  407.57  5121.7  407.60  5139.7  411.72
  5150.0  412.50  5157.7  414.29  5170.6  415.97  5180.9  418.09  5191.2  419.19
  5199.0  421.71  5204.1  421.66  5211.8  422.95  5219.6  425.15  5222.2  425.15
#Mann=4,-1,0
  4857.9    0.16       0  4957.5    0.12       0  4991.9    0.07       0
  4997.9    0.12       0
Bank Sta=4991.9,4997.9
Exp/Cntr=0.3,0.1

Type RM Length L Ch R = 1,972,243,243,243
BEGIN DESCRIPTION:
UNT 067 IN CACR 2.0
END DESCRIPTION:
XS GIS Cut Line= 3
      3722099.64     10753910.20      3722249.61     10753960.19
      3722449.58     10754010.18
#Sta/Elev= 30
  4846.0  405.86  4890.7  399.71  4898.7  397.59  4909.2  396.78  4930.3  392.45
  4940.8  391.93  4951.4  390.45  4993.5  389.44  4998.4  388.42  5001.2  387.92
  5004.4  388.42  5014.4  389.14  5022.1  389.00  5027.3  390.17  5045.3  392.62
  5055.6  392.88  5063.3  394.44  5096.8  398.16  5104.6  399.84  5117.5  400.82
  5127.8  402.99  5145.8  405.80  5151.0  405.77  5158.7  407.70  5169.0  408.59
  5179.3  410.53  5187.0  411.57  5192.2  411.55  5199.9  412.98  5210.2  413.86
#Mann=4,-1,0
  4846.0    0.16       0  4890.7    0.12       0  4998.4    0.07       0
  5004.4    0.12       0
Bank Sta=4998.4,5004.4
Exp/Cntr=0.3,0.1

Type RM Length L Ch R = 1,729,339,339,339
BEGIN DESCRIPTION:
Mapping XS 3ba18e32
END DESCRIPTION:
XS GIS Cut Line= 2
      3721889.42     10754214.59      3722371.17     10754131.26
#Sta/Elev= 30
  4745.0  410.63  4755.3  410.81  4800.6  409.11  4812.6  407.49  4826.4  405.61
  4836.5  402.93  4846.7  401.38  4855.3  397.95  4860.4  398.36  4867.0  397.48
  4877.1  393.50  4907.6  389.46  4915.1  387.66  4924.9  387.52  4927.6  387.02
  4930.9  387.52  4998.9  388.11  5029.3  391.33  5034.6  393.24  5049.6  393.74
  5080.1  397.96  5094.4  398.75  5100.4  400.49  5110.5  401.03  5141.0  404.74
  5154.2  405.08  5171.4  406.59  5181.6  408.55  5214.0  408.73  5233.9  409.76
#Mann=4,-1,0
  4745.0    0.16       0  4812.6    0.12       0  4924.9    0.07       0
  4930.9    0.12       0
Bank Sta=4924.9,4930.9
Exp/Cntr=0.3,0.1

Type RM Length L Ch R = 1,390,306,306,306
BEGIN DESCRIPTION:
Mapping XS 98ba45b9
END DESCRIPTION:
XS GIS Cut Line= 4
      3721915.44     10754428.14      3722095.12     10754514.07
      3722157.62     10754506.26      3722326.91     10754245.81
#Sta/Elev= 30
  4761.9  404.62  4788.7  403.66  4833.0  399.91  4855.2  396.82  4888.5  393.63
  4894.1  392.24  4910.6  391.43  4939.4  386.43  4955.0  385.61  5008.6  385.87
  5072.8  385.99  5115.5  386.18  5135.6  385.45  5138.4  384.95  5141.6  385.45
  5166.9  386.02  5188.0  388.09  5197.2  390.15  5203.1  388.83  5218.3  390.98
  5233.4  391.12  5254.5  394.94  5269.7  396.33  5275.6  395.85  5281.8  397.54
  5290.8  398.24  5296.7  397.53  5311.9  400.96  5327.0  402.90  5334.7  401.15
#Mann=5,-1,0
  4761.9    0.12       0  5008.6    0.16       0  5072.8    0.12       0
  5135.6    0.07       0  5141.6    0.12       0
Bank Sta=5135.6,5141.6
Exp/Cntr=0.3,0.1

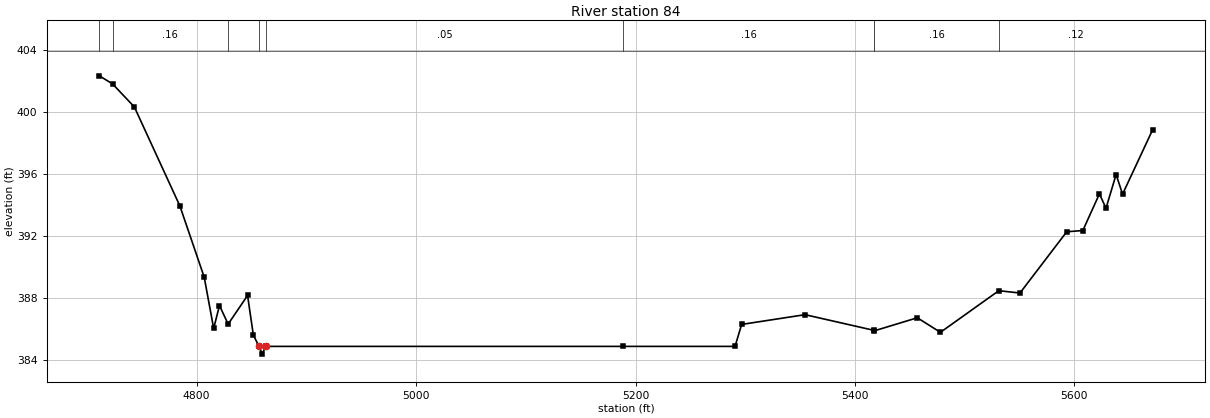
Type RM Length L Ch R = 1,84,0,0,0
BEGIN DESCRIPTION:
UNT 067 IN CACR 1.0
END DESCRIPTION:
XS GIS Cut Line= 4
      3721868.57     10754540.15      3721951.89     10754774.49
      3722043.04     10754774.49      3722381.06     10754254.45
#Sta/Elev= 30
  4711.3  402.36  4723.3  401.84  4743.2  400.35  4784.7  393.95  4806.9  389.34
  4815.5  386.03  4820.8  387.51  4828.7  386.31  4846.4  388.16  4851.7  385.59
  4856.9  384.87  4859.7  384.37  4862.9  384.87  5189.0  384.87  5290.7  384.87
  5296.7  386.29  5354.5  386.92  5417.1  385.91  5417.8  385.88  5456.8  386.72
  5477.9  385.78  5531.1  388.47  5550.4  388.32  5593.0  392.28  5607.7  392.36
  5622.8  394.73  5628.8  393.80  5638.0  395.98  5643.9  394.71  5671.4  398.89
#Mann=9,-1,0
  4711.3    0.12       0  4723.3    0.16       0  4828.7    0.05       0
  4856.9   0.033       0  4862.9    0.05       0  5189.0    0.16       0
  5417.1    0.12       0  5417.8    0.16       0  5531.1    0.12       0
Bank Sta=4856.9,4862.9
Exp/Cntr=0.3,0.1

Chan Stop Cuts=-1