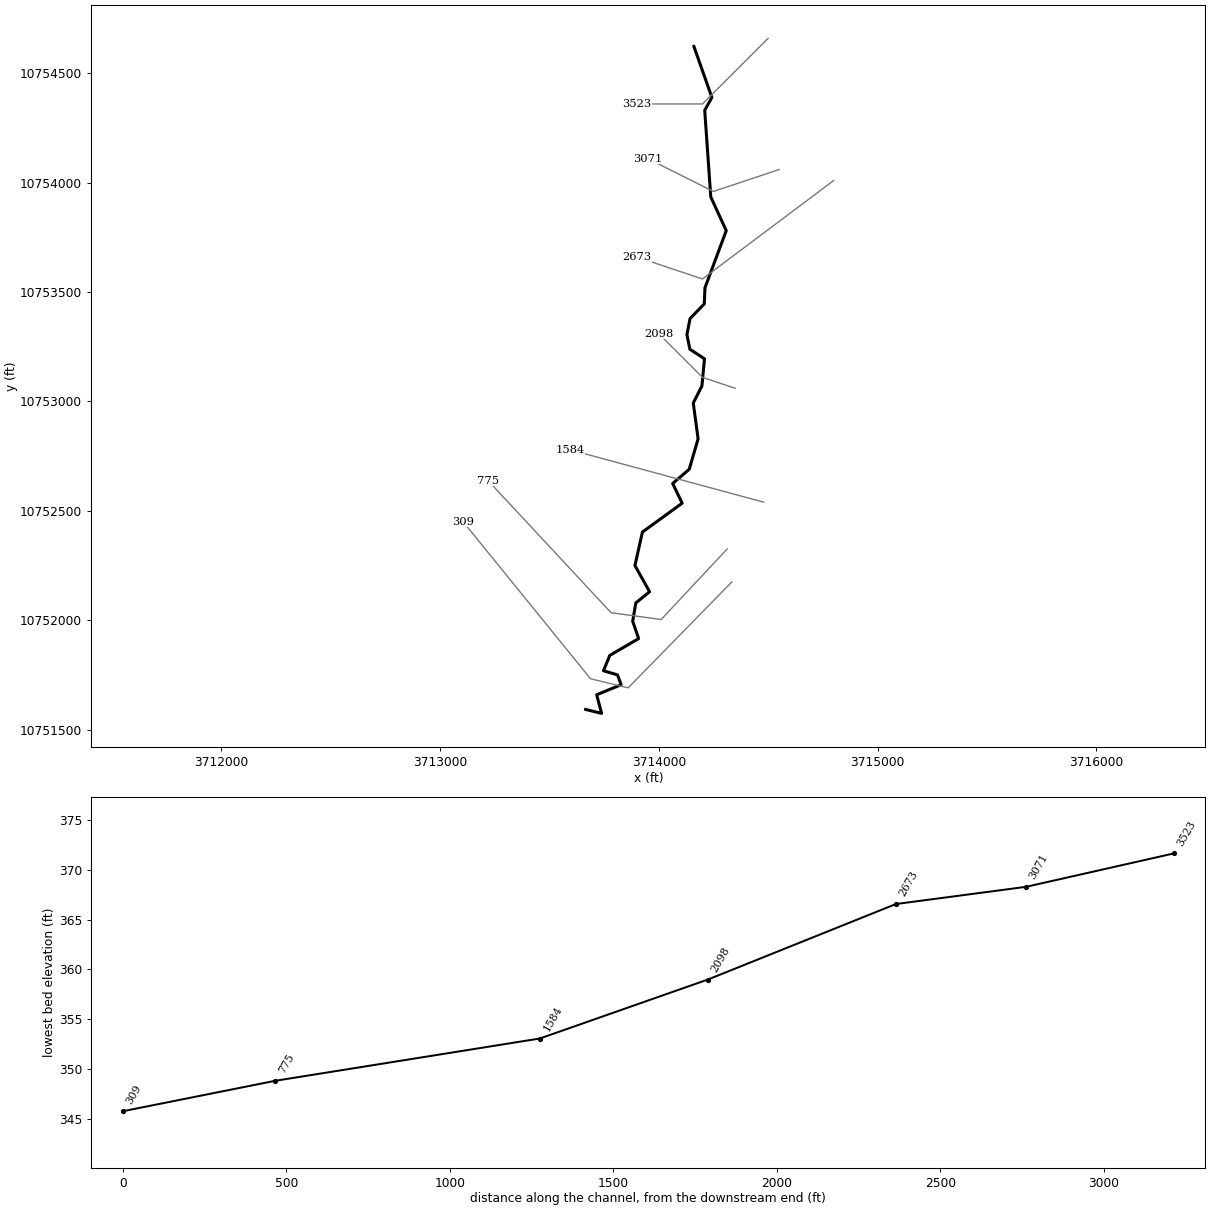
--- UNT 070 IN CACR.prj (project) ---

Proj Title=UNT 070 IN CACR Base Level Engineering
Current Plan=p01
Default Exp/Contr=0.3,0.1
English Units
Geom File=g01
Flow File=f01
Plan File=p01
BEGIN DESCRIPTION:
UNT 070 IN CACR
END DESCRIPTION:

--- UNT 070 IN CACR.p01 (plan) ---

Plan Title=Multiple Run
Short Identifier=Multiple
Geom File=g01
Flow File=f01
Subcritical Flow
K Sum by GR= 0
Std Step Tol= 0.01
Critical Tol= 0.01
Num of Std Step Trials= 20
Max Error Tol= 0.3
Flow Tol Ratio= 0.001
Split Flow NTrial= 30
Split Flow Tol= 0.02
Split Flow Ratio= 0.02
Log Output Level= 0
Friction Slope Method= 1
Unsteady Friction Slope Method= 2
Unsteady Bridges Friction Slope Method= 1
Parabolic Critical Depth
Global Vel Dist=  1 , 1 , 1
Global Log Level= 0
CheckData=True
Encroach Param= -1, 0, 0, 0
BEGIN DESCRIPTION:
Multiple Run
END DESCRIPTION:

--- UNT 070 IN CACR.f01 (steady flow) ---

Flow Title=Multiple
Number of Profiles=7
Profile Names=10-year,25-year,50-year,1pct_min,100-year,1pct_plu,500-year
River Rch & RM= UNT 070 IN CACR,Reach-1,3523
     567     769     935     837    1132    1530    1657
Boundary for River Rch & Prof#=UNT 070 IN CACR,Reach-1,1
Up Type=0
Dn Type=3
Dn Slope=0.005
Boundary for River Rch & Prof#=UNT 070 IN CACR,Reach-1,2
Up Type=0
Dn Type=3
Dn Slope=0.005
Boundary for River Rch & Prof#=UNT 070 IN CACR,Reach-1,3
Up Type=0
Dn Type=3
Dn Slope=0.005
Boundary for River Rch & Prof#=UNT 070 IN CACR,Reach-1,4
Up Type=0
Dn Type=3
Dn Slope=0.005
Boundary for River Rch & Prof#=UNT 070 IN CACR,Reach-1,5
Up Type=0
Dn Type=3
Dn Slope=0.005
Boundary for River Rch & Prof#=UNT 070 IN CACR,Reach-1,6
Up Type=0
Dn Type=3
Dn Slope=0.005
Boundary for River Rch & Prof#=UNT 070 IN CACR,Reach-1,7
Up Type=0
Dn Type=3
Dn Slope=0.005

--- UNT 070 IN CACR.g01 (geometry) ---

Geom Title=Existing Conditions

River Reach=UNT 070 IN CACR,Reach-1
Reach XY= 30
      3714160.31     10754623.17      3714242.50     10754390.00
      3714209.75     10754331.00      3714237.50     10753935.00
      3714308.25     10753781.00      3714211.00     10753520.00
      3714207.75     10753446.00      3714142.75     10753379.00
      3714128.42     10753305.77      3714141.88     10753238.93
      3714208.72     10753195.09      3714197.00     10753071.00
      3714157.50     10752993.00      3714179.50     10752829.00
      3714139.00     10752690.00      3714063.25     10752625.00
      3714106.75     10752535.00      3713925.00     10752403.00
      3713890.75     10752250.00      3713957.75     10752130.00
      3713894.75     10752079.00      3713880.50     10751995.00
      3713907.75     10751916.00      3713775.75     10751839.00
      3713747.00     10751769.00      3713811.00     10751750.00
      3713827.75     10751705.00      3713715.75     10751659.00
      3713738.25     10751574.00      3713665.25     10751592.00

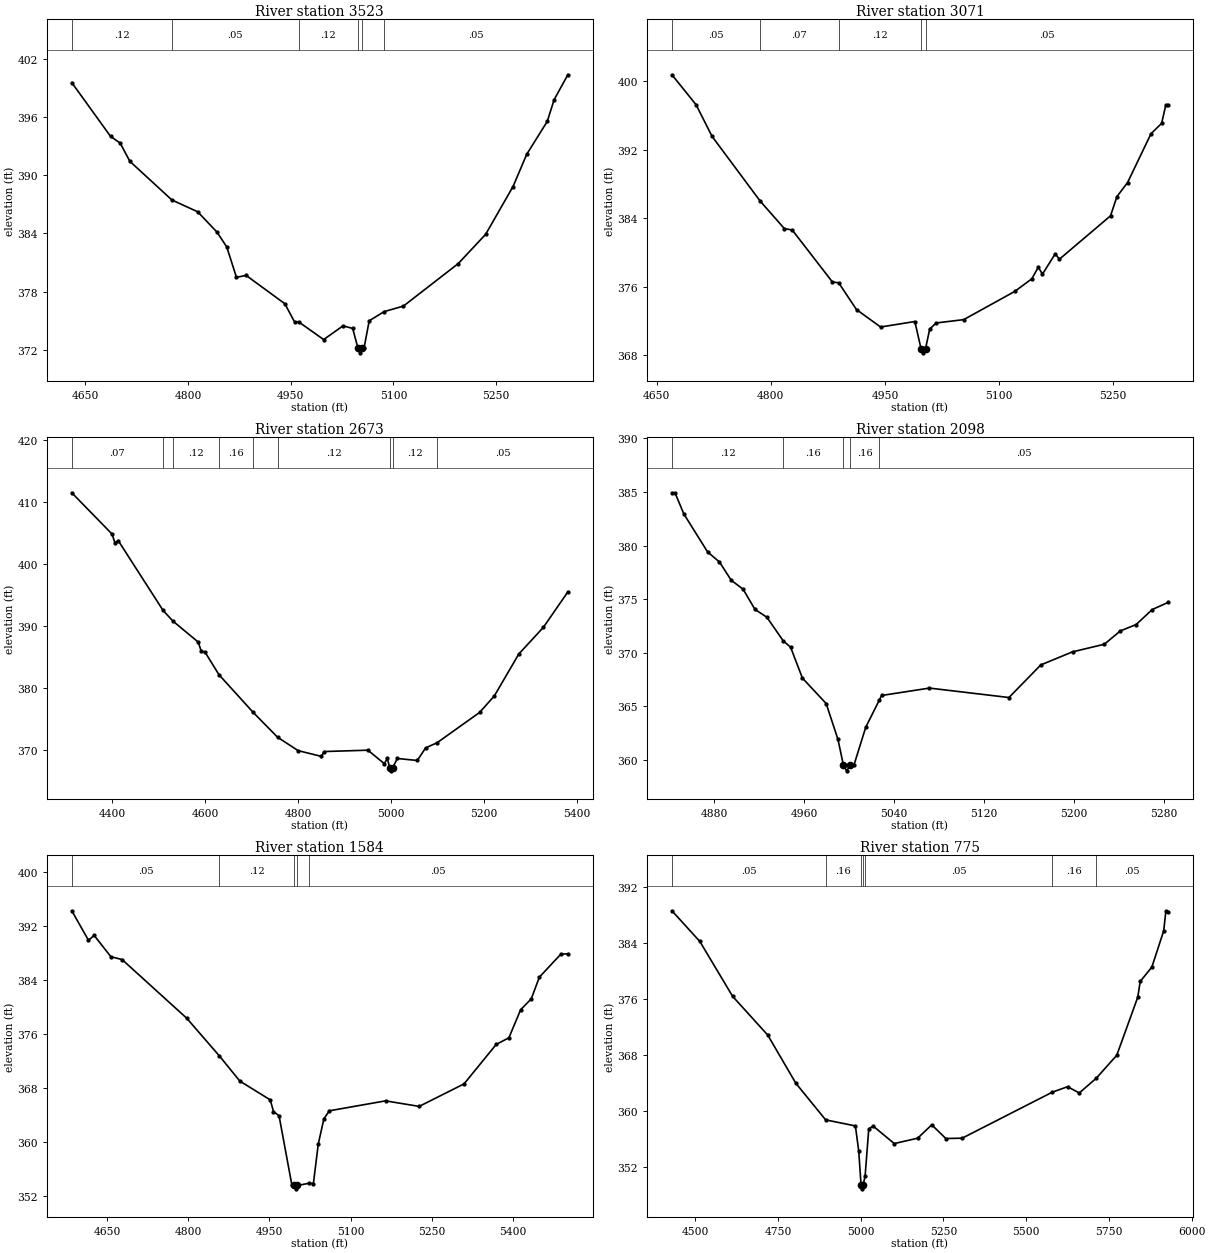
Type RM Length L Ch R = 1,3523,452,452,452
BEGIN DESCRIPTION:
UNT 070 IN CACR 7.0
END DESCRIPTION:
XS GIS Cut Line= 3
      3714499.60     10754660.18      3714199.61     10754360.19
      3713899.66     10754360.19
#Sta/Elev= 30
  4630.5  399.58  4687.1  394.03  4701.2  393.33  4715.3  391.45  4776.6  387.46
  4814.3  386.24  4842.6  384.13  4856.8  382.60  4870.9  379.47  4885.0  379.67
  4941.6  376.74  4955.8  374.85  4961.5  374.88  4998.2  373.04  5026.5  374.46
  5040.6  374.19  5048.2  372.17  5051.0  371.67  5054.2  372.17  5057.2  372.17
  5064.7  374.98  5086.6  375.93  5114.7  376.50  5194.7  380.89  5234.7  383.91
  5274.7  388.85  5294.7  392.18  5324.7  395.58  5334.7  397.82  5354.7  400.39
#Mann=6,-1,0
  4630.5    0.12       0  4776.6    0.05       0  4961.5    0.12       0
  5048.2    0.07       0  5054.2    0.12       0  5086.6    0.05       0
Bank Sta=5048.2,5054.2
Exp/Cntr=0.3,0.1

Type RM Length L Ch R = 1,3071,398,398,398
BEGIN DESCRIPTION:
UNT 070 IN CACR 6.0
END DESCRIPTION:
XS GIS Cut Line= 3
      3714549.64     10754060.20      3714249.61     10753960.19
      3713949.58     10754110.20
#Sta/Elev= 30
  4670.2  400.72  4701.9  397.23  4722.9  393.54  4786.1  386.00  4817.8  382.80
  4828.3  382.62  4881.1  376.56  4889.2  376.48  4912.7  373.35  4944.3  371.32
  4989.3  371.96  4997.4  368.81  5000.2  368.31  5003.4  368.81  5008.8  371.07
  5017.2  371.79  5053.5  372.18  5120.6  375.47  5143.0  376.94  5151.4  378.28
  5157.0  377.49  5173.7  379.84  5179.3  379.23  5246.4  384.28  5254.8  386.52
  5268.8  388.16  5299.5  393.84  5313.5  395.06  5319.1  397.22  5321.9  397.22
#Mann=5,-1,0
  4670.2    0.05       0  4786.1    0.07       0  4889.2    0.12       0
  4997.4    0.03       0  5003.4    0.05       0
Bank Sta=4997.4,5003.4
Exp/Cntr=0.3,0.1

Type RM Length L Ch R = 1,2673,575,575,575
BEGIN DESCRIPTION:
UNT 070 IN CACR 5.0
END DESCRIPTION:
XS GIS Cut Line= 3
      3714799.64     10754010.21      3714199.61     10753560.19
      3713899.58     10753660.20
#Sta/Elev= 30
  4313.6  411.42  4400.1  404.77  4406.3  403.37  4413.6  403.69  4509.8  392.45
  4531.3  390.71  4585.5  387.34  4591.8  385.87  4600.1  385.72  4630.0  382.08
  4703.6  376.00  4756.1  371.99  4800.1  369.84  4850.1  368.91  4856.3  369.69
  4950.1  369.91  4985.5  367.73  4991.8  368.59  4997.1  367.08  4999.8  366.58
  5003.1  367.08  5013.6  368.57  5056.3  368.25  5074.2  370.28  5099.0  371.12
  5190.1  375.99  5221.8  378.65  5274.5  385.42  5327.2  389.71  5379.9  395.43
#Mann=9,-1,0
  4313.6    0.07       0  4509.8    0.05       0  4531.3    0.12       0
  4630.0    0.16       0  4703.6    0.05       0  4756.1    0.12       0
  4997.1    0.07       0  5003.1    0.12       0  5099.0    0.05       0
Bank Sta=4997.1,5003.1
Exp/Cntr=0.3,0.1

Type RM Length L Ch R = 1,2098,514,514,514
BEGIN DESCRIPTION:
UNT 070 IN CACR 4.0
END DESCRIPTION:
XS GIS Cut Line= 3
      3714349.65     10753060.17      3714199.61     10753110.19
      3713999.61     10753310.19
#Sta/Elev= 30
  4842.7  384.93  4845.4  384.93  4853.3  382.95  4874.4  379.41  4884.9  378.48
  4895.4  376.77  4906.0  375.93  4916.5  374.05  4927.1  373.32  4941.6  371.12
  4948.2  370.52  4958.7  367.64  4979.8  365.27  4990.3  361.92  4995.2  359.49
  4998.0  358.99  5001.2  359.49  5004.4  359.49  5015.0  363.06  5027.0  365.58
  5029.1  366.02  5071.6  366.71  5142.3  365.83  5170.6  368.87  5198.8  370.09
  5227.1  370.80  5241.3  372.04  5255.4  372.64  5269.6  374.03  5283.7  374.70
#Mann=5,-1,0
  4842.7    0.12       0  4941.6    0.16       0  4995.2    0.07       0
  5001.2    0.16       0  5027.0    0.05       0
Bank Sta=4995.2,5001.2
Exp/Cntr=0.3,0.1

Type RM Length L Ch R = 1,1584,809,809,809
BEGIN DESCRIPTION:
UNT 070 IN CACR 3.0
END DESCRIPTION:
XS GIS Cut Line= 2
      3714479.43     10752539.56      3713594.36     10752779.05
#Sta/Elev= 30
  4584.8  394.21  4615.7  389.84  4626.1  390.57  4657.1  387.41  4677.8  386.99
  4797.4  378.30  4857.5  372.74  4895.4  369.01  4951.7  366.22  4957.6  364.50
  4967.9  363.88  4991.5  353.67  4996.0  353.56  4998.7  353.06  5002.0  353.56
  5022.9  353.88  5031.4  353.85  5040.4  359.69  5050.8  363.43  5060.9  364.61
  5164.8  366.08  5226.9  365.26  5309.8  368.59  5369.4  374.44  5392.7  375.41
  5414.5  379.57  5434.1  381.18  5449.1  384.39  5489.0  387.81  5501.7  387.84
#Mann=5,-1,0
  4584.8    0.05       0  4857.5    0.12       0  4996.0    0.07       0
  5002.0    0.12       0  5022.9    0.05       0
Bank Sta=4996,5002
Exp/Cntr=0.3,0.1

Type RM Length L Ch R = 1,775,466,466,466
BEGIN DESCRIPTION:
UNT 070 IN CACR 2.0
END DESCRIPTION:
XS GIS Cut Line= 4
      3714312.78     10752325.99      3714010.72     10752003.09
      3713781.55     10752034.34      3713219.07     10752638.48
#Sta/Elev= 30
  4429.6  388.55  4513.8  384.17  4613.0  376.32  4719.0  370.79  4804.0  363.90
  4894.0  358.67  4983.9  357.80  4994.0  354.23  5001.1  349.31  5003.8  348.81
  5007.1  349.31  5013.3  350.65  5024.3  357.38  5037.4  357.78  5101.5  355.28
  5172.2  356.05  5214.7  357.96  5257.2  356.00  5306.6  356.05  5578.7  362.62
  5625.1  363.41  5660.3  362.51  5711.6  364.61  5773.7  367.90  5837.2  376.21
  5844.5  378.45  5879.7  380.50  5915.4  385.67  5922.2  388.55  5928.5  388.34
#Mann=7,-1,0
  4429.6    0.05       0  4894.0    0.16       0  5001.1    0.07       0
  5007.1    0.16       0  5013.3    0.05       0  5578.7    0.16       0
  5711.6    0.05       0
Bank Sta=5001.1,5007.1
Exp/Cntr=0.3,0.1

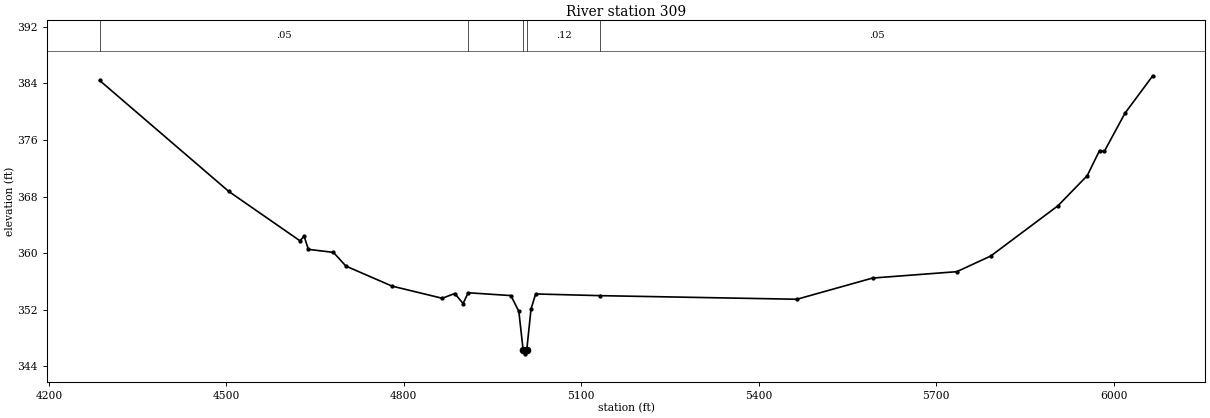
Type RM Length L Ch R = 1,309,0,0,0
BEGIN DESCRIPTION:
UNT 070 IN CACR 1.0
END DESCRIPTION:
XS GIS Cut Line= 4
      3714333.64     10752174.97      3713859.67     10751690.59
      3713687.80     10751732.26      3713104.55     10752450.91
#Sta/Elev= 30
  4285.8  384.42  4504.1  368.72  4624.4  361.74  4631.4  362.39  4638.6  360.53
  4681.0  360.10  4702.1  358.16  4780.0  355.33  4864.9  353.61  4886.0  354.28
  4900.2  352.87  4908.7  354.39  4981.0  353.99  4994.4  351.74  5001.7  346.25
  5004.5  345.75  5007.7  346.25  5015.0  352.10  5022.8  354.22  5132.1  353.98
  5464.4  353.47  5592.3  356.47  5734.6  357.37  5792.1  359.59  5905.6  366.69
  5955.1  370.95  5975.9  374.50  5983.9  374.37  6019.0  379.79  6065.9  385.08
#Mann=5,-1,0
  4285.8    0.05       0  4908.7    0.12       0  5001.7    0.07       0
  5007.7    0.12       0  5132.1    0.05       0
Bank Sta=5001.7,5007.7
Exp/Cntr=0.3,0.1

Chan Stop Cuts=-1