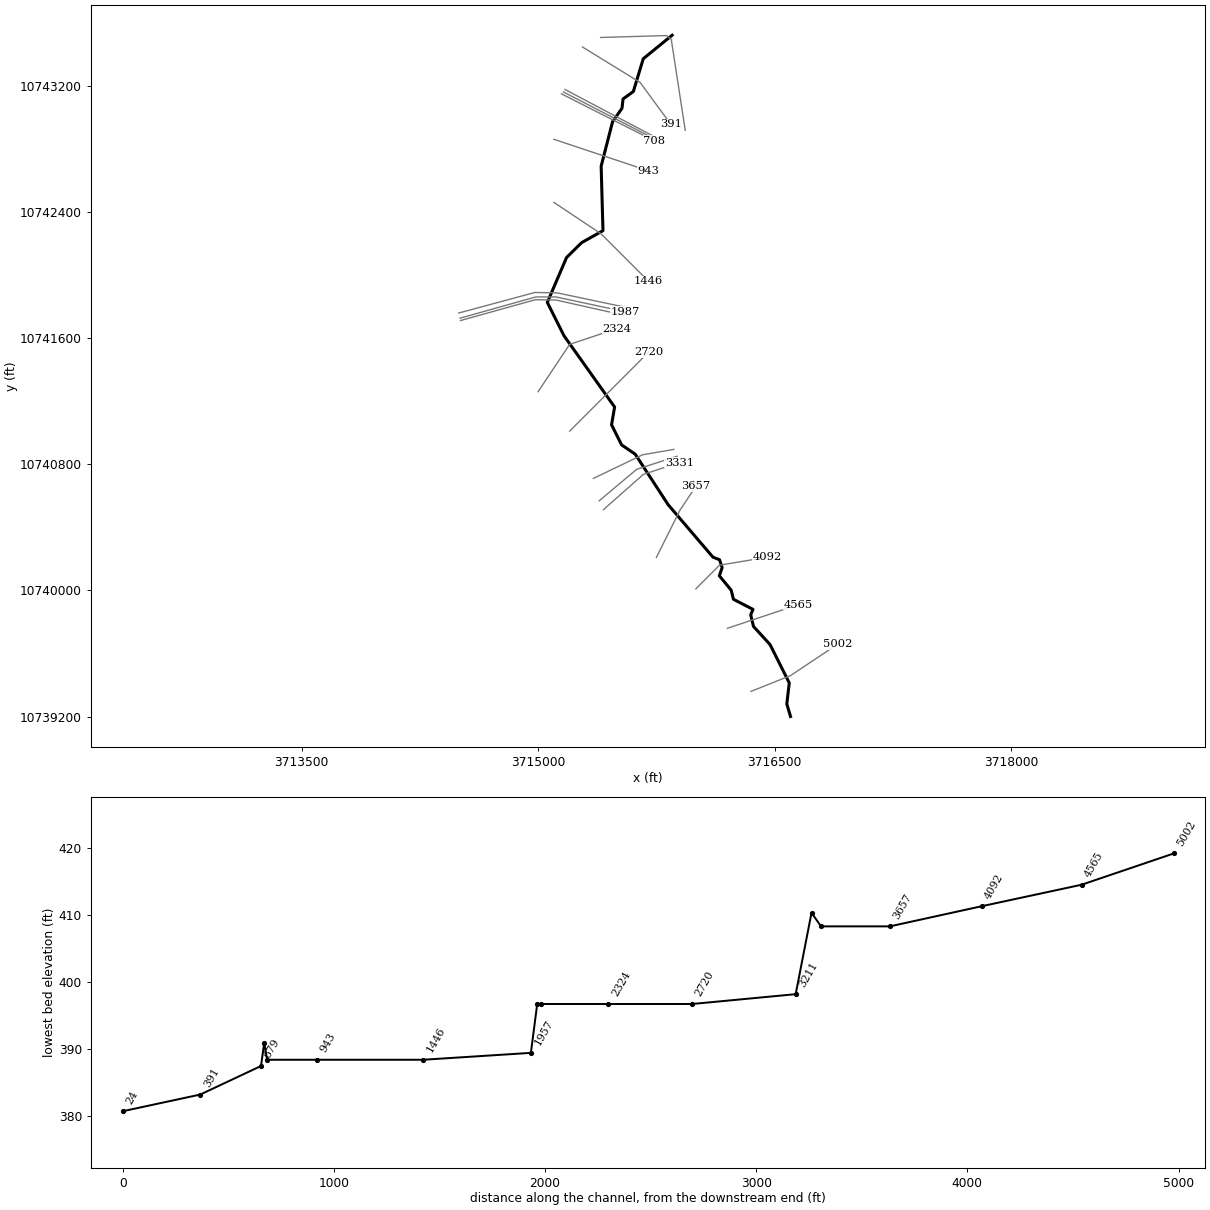
--- UNT 072 IN CACR.prj (project) ---

Proj Title=UNT 072 IN CACR Base Level Engineering
Current Plan=p01
Default Exp/Contr=0.3,0.1
English Units
Geom File=g01
Flow File=f01
Plan File=p01
Y Axis Title=Elevation
X Axis Title(PF)=Main Channel Distance
X Axis Title(XS)=Station
BEGIN DESCRIPTION:
UNT 072 IN CACR
END DESCRIPTION:
DSS Export Rating Curves= 0
DSS Export Rating Curve Sorted= 0
DSS Export Volume Flow Curves= 0
DXF OffsetX= 0
DXF OffsetY= 0
DXF ScaleX= 1
DXF ScaleY= 10

--- UNT 072 IN CACR.p01 (plan) ---

Plan Title=Multiple Run
Short Identifier=Multiple
Geom File=g01
Flow File=f01
Subcritical Flow
K Sum by GR= 0
Std Step Tol= 0.01
Critical Tol= 0.01
Num of Std Step Trials= 20
Max Error Tol= 0.3
Flow Tol Ratio= 0.001
Split Flow NTrial= 30
Split Flow Tol= 0.02
Split Flow Ratio= 0.02
Log Output Level= 0
Friction Slope Method= 1
Unsteady Friction Slope Method= 2
Unsteady Bridges Friction Slope Method= 1
Parabolic Critical Depth
Global Vel Dist=  1 , 1 , 1
Global Log Level= 0
CheckData=True
Encroach Param= -1, 0, 0, 0
BEGIN DESCRIPTION:
Multiple Run
END DESCRIPTION:

--- UNT 072 IN CACR.f01 (steady flow) ---

Flow Title=Multiple
Program Version=4.10
Number of Profiles= 7
Profile Names=10-year,25-year,50-year,1pct_min,100-year,1pct_plu,500-year
River Rch & RM=UNT 072 IN CACR,Reach-1         ,5002
     478     639     769     680     920    1245    1319
Boundary for River Rch & Prof#=UNT 072 IN CACR,Reach-1         , 1
Up Type= 0
Dn Type= 3
Dn Slope=0.00687
Boundary for River Rch & Prof#=UNT 072 IN CACR,Reach-1         , 2
Up Type= 0
Dn Type= 3
Dn Slope=0.00687
Boundary for River Rch & Prof#=UNT 072 IN CACR,Reach-1         , 3
Up Type= 0
Dn Type= 3
Dn Slope=0.00687
Boundary for River Rch & Prof#=UNT 072 IN CACR,Reach-1         , 4
Up Type= 0
Dn Type= 3
Dn Slope=0.00687
Boundary for River Rch & Prof#=UNT 072 IN CACR,Reach-1         , 5
Up Type= 0
Dn Type= 3
Dn Slope=0.00687
Boundary for River Rch & Prof#=UNT 072 IN CACR,Reach-1         , 6
Up Type= 0
Dn Type= 3
Dn Slope=0.00687
Boundary for River Rch & Prof#=UNT 072 IN CACR,Reach-1         , 7
Up Type= 0
Dn Type= 3
Dn Slope=0.00687
DSS Import GetInterval= 0
DSS Import GetPeak= 0
DSS Import FillOption= 0

--- UNT 072 IN CACR.g01 (geometry) ---

Geom Title=Existing Conditions
Program Version=4.10

River Reach=UNT 072 IN CACR ,Reach-1
Reach XY= 30
      3716599.75       10739201.      3716576.25       10739280.
      3716591.75       10739414.        3716470.       10739657.
        3716365.       10739772.       3716347.5       10739846.
        3716362.       10739880.        3716238.       10739944.
       3716223.5       10740002.       3716148.5       10740093.
      3716166.25       10740145.      3716149.75       10740195.
        3716108.       10740211.      3715823.75       10740544.
      3715615.25       10740864.      3715528.75       10740923.
      3715465.25       10741050.       3715484.5       10741163.
       3715163.5       10741615.        3715058.       10741826.
       3715179.5       10742110.       3715275.5       10742205.
      3715410.75       10742281.      3715399.25       10742690.
      3715471.75       10742972.       3715531.5       10743057.
        3715538.       10743116.      3715603.25       10743163.
      3715666.25       10743371.      3715849.25       10743520.

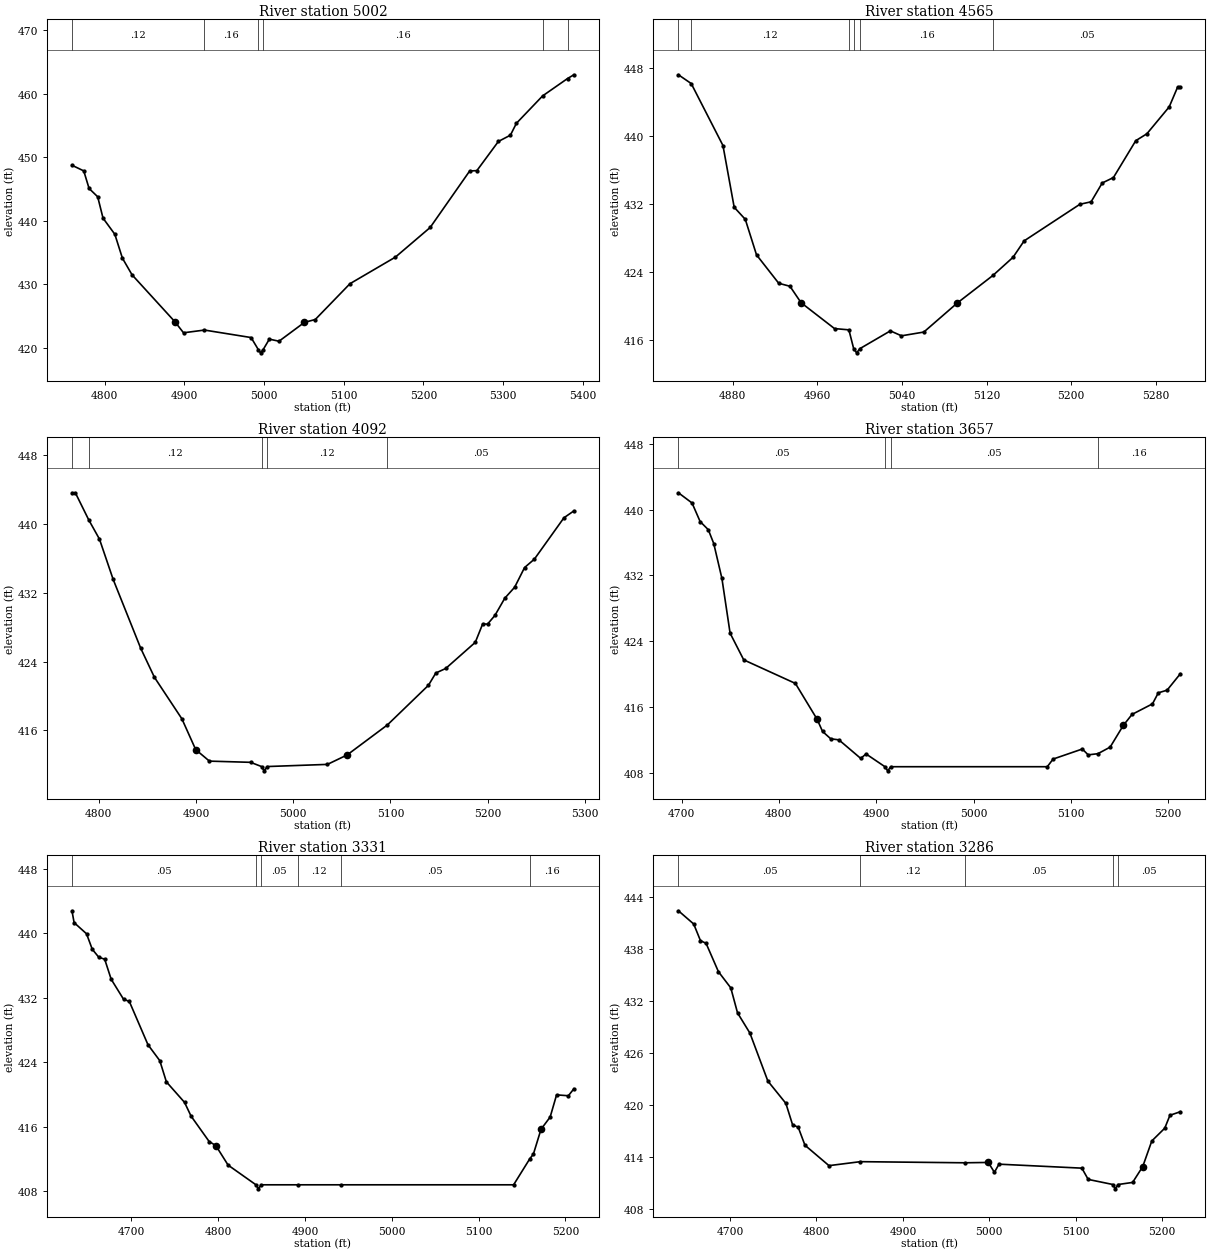
Type RM Length L Ch R = 1 ,5002    ,437,437,437
BEGIN DESCRIPTION:
UNT 072 IN CACR 11.0
END DESCRIPTION:
XS GIS Cut Line= 3
      3716349.63      10739360.2      3716599.61     10739460.19
      3716899.62     10739660.19
#Sta/Elev= 30
    4759  448.76  4773.8  447.87  4780.5   445.1  4791.3  443.79    4798  440.42
  4812.8  437.88  4822.3  434.12  4834.4  431.49  4888.2  424.09    4899  422.35
  4925.3  422.78  4983.8   421.6  4992.9  419.69  4995.7  419.19  4998.9  419.69
  5006.7  421.35  5018.8  421.02  5050.8     424  5064.3  424.44  5107.9  430.09
  5164.9  434.28  5208.5  438.95  5258.1  447.86  5267.1  447.91  5294.1  452.51
  5309.2   453.5  5316.7  455.37  5349.6  459.69  5380.9  462.43  5388.8  463.02
#Mann= 6 ,-1 , 0
    4759     .12       0  4925.3     .16       0  4992.9     .07       0
  4998.9     .16       0  5349.6     .12       0  5380.9     .05       0
Bank Sta=4888.2,5050.8
XS Rating Curve= 0 ,0
Exp/Cntr=0.3,0.1

Type RM Length L Ch R = 1 ,4565    ,473,473,473
BEGIN DESCRIPTION:
UNT 072 IN CACR 10.0
END DESCRIPTION:
XS GIS Cut Line= 3
      3716199.63      10739760.2      3716349.61     10739810.19
      3716649.59     10739910.18
#Sta/Elev= 30
  4828.8  447.17  4840.9  446.14  4870.9  438.86  4881.5  431.61    4892  430.19
  4902.6  426.02  4923.6  422.68  4934.2  422.33  4944.7   420.4  4976.3  417.36
  4989.9  417.21  4994.4  415.01  4997.2  414.51  5000.4  415.01  5029.1  417.09
  5039.6  416.51  5060.7  416.95  5092.3  420.36    5126   423.6    5145  425.73
  5155.5  427.66  5208.2  431.96  5218.8  432.25  5229.3  434.46  5239.9   435.1
    5261  439.43  5271.5  440.24  5292.6   443.4  5300.5  445.71  5303.1  445.71
#Mann= 6 ,-1 , 0
  4828.8     .05       0  4840.9     .12       0  4989.9     .16       0
  4994.4     .07       0  5000.4     .16       0    5126     .05       0
Bank Sta=4944.7,5092.3
XS Rating Curve= 0 ,0
Exp/Cntr=0.3,0.1

Type RM Length L Ch R = 1 ,4092    ,435,435,435
BEGIN DESCRIPTION:
UNT 072 IN CACR 9.0
END DESCRIPTION:
XS GIS Cut Line= 3
      3715999.62      10740010.2      3716149.61     10740160.19
      3716449.66      10740210.2
#Sta/Elev= 30
  4772.4  443.65  4775.9  443.65  4789.7  440.49  4800.7  438.26  4814.8  433.57
  4843.1  425.57  4857.2  422.19  4885.5  417.35  4899.7  413.77  4913.8  412.43
  4956.2  412.29  4967.4   411.8  4970.1   411.3  4973.4   411.8  5035.2  412.05
  5055.5  413.15  5096.9  416.64  5139.1  421.25  5146.7  422.68  5156.9  423.21
  5187.3  426.25  5194.9  428.39  5199.9  428.37  5207.5  429.38  5217.7  431.39
  5227.8  432.66    5238  434.95  5248.1  435.93  5278.5  440.74  5288.7  441.54
#Mann= 5 ,-1 , 0
  4772.4     .05       0  4789.7     .12       0  4967.4     .07       0
  4973.4     .12       0  5096.9     .05       0
Bank Sta=4899.7,5055.5
XS Rating Curve= 0 ,0
Exp/Cntr=0.3,0.1

Type RM Length L Ch R = 1 ,3657    ,326,326,326
BEGIN DESCRIPTION:
UNT 072 IN CACR 8.0
END DESCRIPTION:
XS GIS Cut Line= 3
      3715749.62     10740210.21      3715899.61     10740510.19
      3715999.63     10740660.22
#Sta/Elev= 30
  4696.8  442.04  4710.8   440.8  4719.1  438.55  4727.5  437.56  4733.1  435.88
  4741.5  431.64  4749.9     425  4763.9  421.76    4817   418.9  4839.3  414.55
  4844.9  413.07  4853.3  412.18  4861.7  412.05  4884.1   409.8  4889.6  410.34
    4909  408.79  4911.8  408.29    4915  408.79  5075.8  408.79  5081.8  409.72
  5111.8  410.94  5117.8  410.23  5127.8  410.37  5140.4  411.17  5153.9   413.8
  5162.9  415.14  5183.9  416.42  5189.9  417.76  5198.9  418.08  5212.5  420.07
#Mann= 4 ,-1 , 0
  4696.8     .05       0    4909    .033       0    4915     .05       0
  5127.8     .16       0
Bank Sta=4839.3,5153.9
XS Rating Curve= 0 ,0
Exp/Cntr=0.3,0.1

Type RM Length L Ch R = 1 ,3331    ,45,45,45
BEGIN DESCRIPTION:
Mapping XS 7b052bdf
END DESCRIPTION:
XS GIS Cut Line= 3
      3715413.95     10740512.41      3715667.41     10740736.36
      3715895.58     10740810.69
#Sta/Elev= 30
  4631.6  442.76  4634.1  441.29  4648.4  439.91    4655  437.99  4662.6  436.99
  4669.3  436.76  4676.8  434.27    4691   431.8  4697.7  431.52  4719.2  426.15
  4732.8  424.18  4740.4  421.55  4761.3  419.01  4768.8  417.31  4789.7  414.15
  4797.3  413.66  4811.5  411.23  4843.6  408.79  4846.4  408.29  4849.6  408.79
  4891.5  408.79    4941  408.79  5140.4  408.79    5159  412.01  5163.2   412.6
    5172  415.68  5182.5  417.19  5189.9  419.94  5203.5  419.83  5209.8  420.69
#Mann= 6 ,-1 , 0
  4631.6     .05       0  4843.6    .033       0  4849.6     .05       0
  4891.5     .12       0    4941     .05       0    5159     .16       0
Bank Sta=4797.3,5172
XS Rating Curve= 0 ,0
Exp/Cntr=0.3,0.1

Type RM Length L Ch R = 1 ,3286    ,75,75,75
BEGIN DESCRIPTION:
Mapping XS 4a54ece1
END DESCRIPTION:
XS GIS Cut Line= 3
      3715386.15     10740567.95      3715624.01     10740767.61
      3715880.98     10740850.96
#Sta/Elev= 30
  4640.3  442.45    4658  440.92  4665.8     439  4672.3  438.69  4686.6  435.41
  4700.9  433.54  4708.7  430.65    4723  428.32  4743.8  422.77  4764.6   420.2
  4772.4  417.72  4778.9  417.44  4786.7  415.36  4814.5     413  4850.8  413.46
  4971.4  413.33  4998.8  413.37  5005.9  412.23  5011.2  413.17  5107.1  412.71
  5114.4  411.41    5143  410.82  5145.7  410.32    5149  410.82  5165.8  411.06
  5177.5  412.89    5188  415.85    5203  417.33    5209  418.82    5221  419.23
#Mann= 5 ,-1 , 0
  4640.3     .05       0  4850.8     .12       0  4971.4     .05       0
    5143    .033       0    5149     .05       0
Bank Sta=4998.8,5177.5
XS Rating Curve= 0 ,0
Exp/Cntr=0.3,0.1

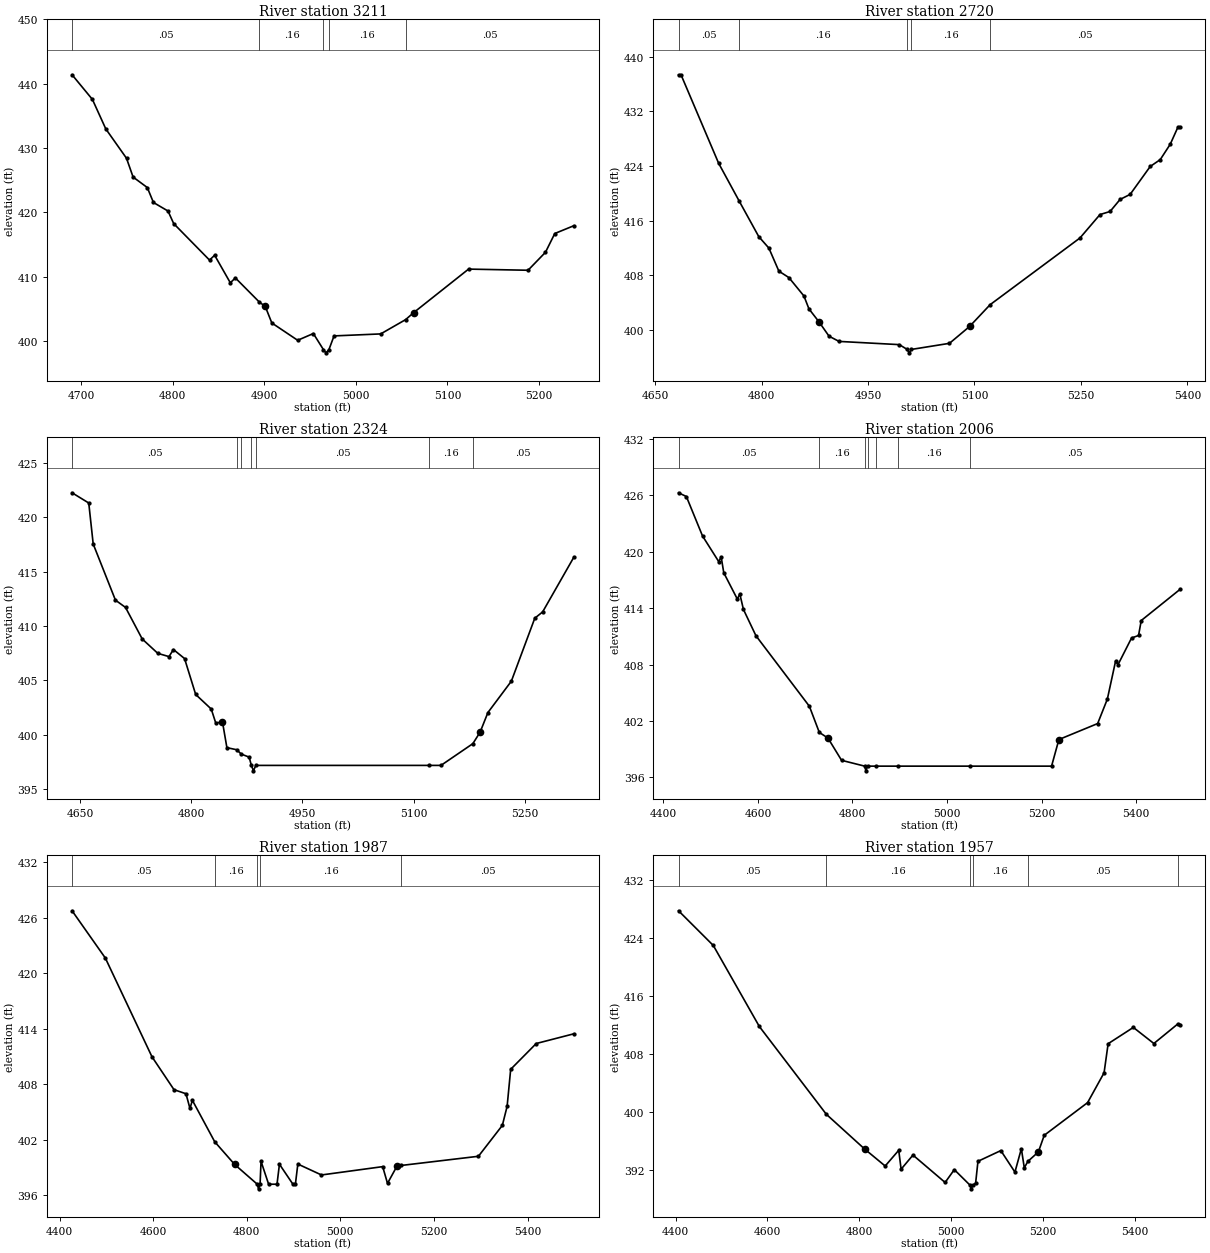
Type RM Length L Ch R = 1 ,3211    ,491,491,491
BEGIN DESCRIPTION:
UNT 072 IN CACR 7.0
END DESCRIPTION:
XS GIS Cut Line= 3
      3715349.59     10740710.18       3715662.2     10740860.19
      3715860.14     10740894.35
#Sta/Elev= 30
  4690.3  441.36  4712.5  437.53  4727.1  432.95  4749.7  428.39  4756.9  425.47
  4772.4  423.84  4779.1  421.52    4795  420.19  4801.2  418.24  4840.3  412.57
  4845.9  413.32    4863  409.04  4868.5   409.8  4894.8  406.03  4901.1  405.38
  4908.3   402.8  4936.5  400.11  4953.6  401.16  4964.6  398.66  4967.4  398.16
  4970.6  398.66  4976.2  400.79  5027.1   401.1  5054.3  403.32  5063.1  404.41
    5123  411.17  5187.9  410.99  5206.9  413.78  5217.1   416.7  5237.9  417.91
#Mann= 5 ,-1 , 0
  4690.3     .05       0  4894.8     .16       0  4964.6     .07       0
  4970.6     .16       0  5054.3     .05       0
Bank Sta=4901.1,5063.1
XS Rating Curve= 0 ,0
Exp/Cntr=0.3,0.1

Type RM Length L Ch R = 1 ,2720    ,396,396,396
BEGIN DESCRIPTION:
UNT 072 IN CACR 6.0
END DESCRIPTION:
XS GIS Cut Line= 3
      3715199.63     10741010.21      3715399.61     10741210.19
      3715699.62      10741510.2
#Sta/Elev= 30
    4683  437.33  4686.5  437.33  4739.5   424.4  4768.7  418.83  4796.1  413.67
  4810.3     412  4824.4  408.63  4838.5  407.69  4859.7     405  4866.8  403.11
    4881  401.21  4895.1  399.12  4909.2  398.36  4994.1  397.89  5005.2  397.19
    5008  396.69  5011.2  397.19  5064.8  398.08  5093.1  400.54  5122.1  403.73
  5248.7  413.48  5276.9   416.9  5291.1  417.35  5305.2  419.11  5319.4  419.85
  5347.7  423.93  5361.8  424.93  5375.9  427.18  5386.5  429.63  5390.1  429.63
#Mann= 5 ,-1 , 0
    4683     .05       0  4768.7     .16       0  5005.2     .07       0
  5011.2     .16       0  5122.1     .05       0
Bank Sta=4881,5093.1
XS Rating Curve= 0 ,0
Exp/Cntr=0.3,0.1

Type RM Length L Ch R = 1 ,2324    ,318,318,318
BEGIN DESCRIPTION:
UNT 072 IN CACR 5.0
END DESCRIPTION:
XS GIS Cut Line= 3
      3714999.63     10741260.22      3715199.61     10741560.19
      3715499.57     10741660.18
#Sta/Elev= 30
  4639.3  422.25  4661.8  421.31  4667.8  417.54  4697.8  412.38  4711.4  411.71
  4733.9  408.81  4754.9  407.49    4770  407.19    4776  407.84    4791  407.01
    4806  403.71    4827  402.37  4833.1  401.08  4842.1   401.2  4848.1  398.82
  4861.3  398.63  4867.5  398.23  4878.1  397.95  4881.1  397.19  4883.9  396.69
  4887.1  397.19  5121.3  397.19  5136.8  397.19  5179.8  399.19  5189.6  400.25
  5200.1  402.05  5231.7  404.93  5263.3  410.72  5273.9   411.3    5316  416.33
#Mann= 7 ,-1 , 0
  4639.3     .05       0  4861.3     .16       0  4867.5     .05       0
  4881.1    .033       0  4887.1     .05       0  5121.3     .16       0
  5179.8     .05       0
Bank Sta=4842.1,5189.6
XS Rating Curve= 0 ,0
Exp/Cntr=0.3,0.1

Type RM Length L Ch R = 1 ,2006    ,19,19,19
BEGIN DESCRIPTION:
UNT 072 IN CACR 4.0
END DESCRIPTION:
XS GIS Cut Line= 4
      3714507.38     10741711.06      3714982.62     10741843.44
      3715112.83     10741841.27      3715540.34     10741745.78
#Sta/Elev= 30
    4432  426.27  4448.6  425.87  4482.8  421.67    4517  418.95  4522.2  419.45
  4527.7  417.76  4556.4  414.96  4561.6  415.52  4569.3  413.86  4595.8  411.06
  4708.8  403.56  4729.8  400.78  4748.2  400.17  4776.9  397.81  4825.8  397.19
  4828.5  396.69  4831.8  397.19  4850.2  397.19  4895.8  397.19  5048.7  397.19
  5221.2  397.19  5236.7  400.02  5318.7  401.72  5339.2  404.32  5356.6  408.36
  5361.7  407.98  5390.4  410.82  5405.2  411.09  5410.9  412.68  5493.6  416.02
#Mann= 7 ,-1 , 0
    4432     .05       0  4729.8     .16       0  4825.8     .07       0
  4831.8     .16       0  4850.2     .05       0  4895.8     .16       0
  5048.7     .05       0
Bank Sta=4748.2,5236.7
XS Rating Curve= 0 ,0
Exp/Cntr=0.3,0.1

Type RM Length L Ch R = 1 ,1987    ,30,30,30
BEGIN DESCRIPTION:
Mapping XS ddc860a4
END DESCRIPTION:
XS GIS Cut Line= 4
      3714505.22     10741726.26      3714984.79      10741860.8
      3715112.83      10741860.8      3715549.04     10741767.48
#Sta/Elev= 30
  4426.7  426.75  4497.8  421.64  4597.4  410.97  4644.5  407.41  4670.1  406.97
  4678.6  405.38  4683.8  406.26  4731.5  401.78    4774  399.33  4822.4  397.19
  4825.1  396.69  4828.4  397.19  4830.5  399.66  4846.7  397.19  4864.6  397.19
  4869.8  399.35  4898.6  397.19  4903.9  397.19  4909.1  399.37  4959.6  398.19
  5090.4  399.09  5100.7  397.28  5121.1  399.16  5130.4  399.22    5295  400.21
  5346.1  403.55  5356.3  405.61  5363.9  409.61  5418.5   412.4  5498.9  413.45
#Mann= 5 ,-1 , 0
  4426.7     .05       0  4731.5     .16       0  4822.4     .07       0
  4828.4     .16       0  5130.4     .05       0
Bank Sta=4774,5121.1
XS Rating Curve= 0 ,0
Exp/Cntr=0.3,0.1

Type RM Length L Ch R = 1 ,1957    ,511,511,511
BEGIN DESCRIPTION:
Mapping XS 70451b0a
END DESCRIPTION:
XS GIS Cut Line= 4
      3714496.53     10741758.81      3714978.28     10741889.01
      3715119.34     10741886.84      3715562.01     10741793.53
#Sta/Elev= 30
  4406.4  427.77  4482.1  422.98  4582.3   411.8  4728.2  399.68  4811.3   394.9
  4856.3  392.54  4885.8  394.71    4891   392.1  4916.8  394.05  4986.8  390.27
  5006.8  392.04  5041.1  389.89  5043.9  389.39  5047.1  389.89  5053.2  390.16
  5058.3  393.19  5108.1  394.67  5138.8   391.7  5152.8  394.93  5159.2  392.29
  5166.9  393.17  5189.9  394.49  5202.6  396.78    5297  401.29  5332.9  405.41
  5341.7  409.42  5396.6  411.67  5441.3  409.45    5494  412.18  5498.9  412.05
#Mann= 6 ,-1 , 0
  4406.4     .05       0  4728.2     .16       0  5041.1     .07       0
  5047.1     .16       0  5166.9     .05       0    5494     .12       0
Bank Sta=4811.3,5189.9
XS Rating Curve= 0 ,0
Exp/Cntr=0.3,0.1

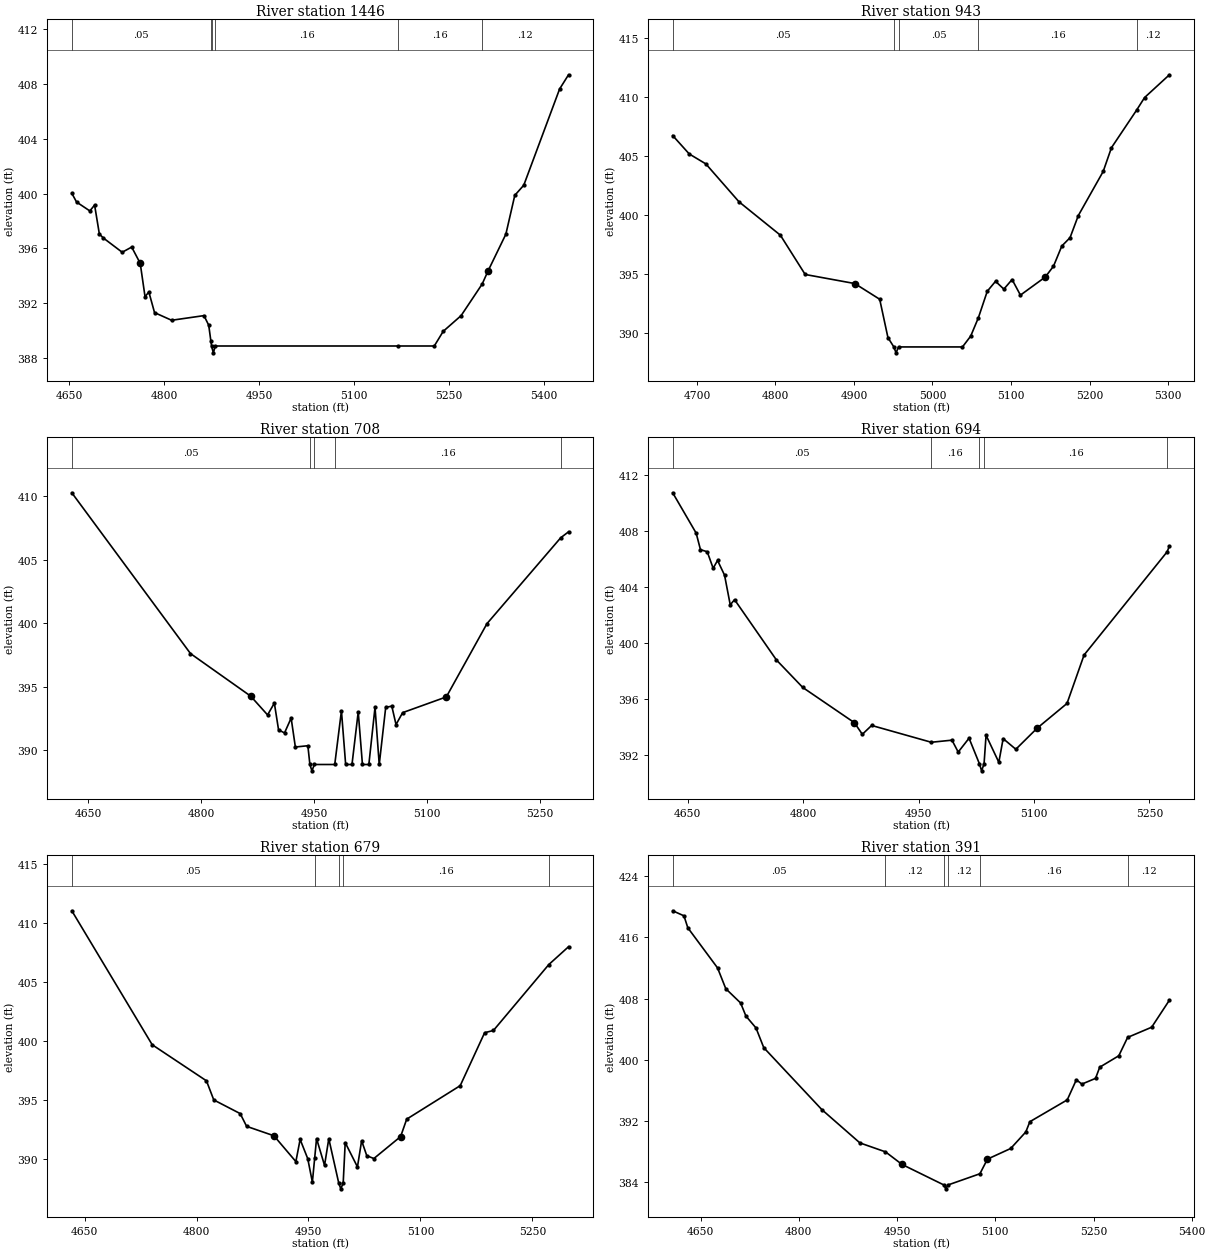
Type RM Length L Ch R = 1 ,1446    ,503,503,503
BEGIN DESCRIPTION:
UNT 072 IN CACR 3.0
END DESCRIPTION:
XS GIS Cut Line= 3
      3715099.63     10742460.18      3715399.61     10742260.19
      3715699.61     10741960.19
#Sta/Elev= 30
  4653.7  400.02  4661.2  399.38  4682.2  398.73  4689.7  399.16  4697.2  397.05
  4703.3  396.76  4733.3  395.71  4748.3  396.09  4761.8   394.9  4769.4  392.46
  4775.4  392.81  4784.4   391.3  4811.4  390.74  4862.5  391.08    4870  390.38
  4873.4  389.23  4874.5  388.86  4877.3  388.36  4880.5  388.86  5168.6  388.86
  5226.4  388.86  5240.5  389.93  5268.8  391.08  5302.1  393.39  5311.2  394.33
  5339.5  397.03  5353.6  399.87  5367.8  400.61  5424.4  407.64  5438.5  408.68
#Mann= 6 ,-1 , 0
  4653.7     .05       0  4873.4     .16       0  4874.5    .035       0
  4880.5     .16       0  5168.6     .16       0  5302.1     .12       0
Bank Sta=4761.8,5311.2
XS Rating Curve= 0 ,0
Exp/Cntr=0.3,0.1

Type RM Length L Ch R = 1 ,943     ,235,235,235
BEGIN DESCRIPTION:
UNT 072 IN CACR 2.0
END DESCRIPTION:
XS GIS Cut Line= 3
      3715099.57      10742860.2      3715399.61     10742760.19
      3715699.62     10742660.19
#Sta/Elev= 30
  4669.2  406.77  4690.3  405.21  4711.4  404.37  4753.6  401.16  4806.3  398.33
  4837.9     395  4901.1  394.23  4932.8   392.9  4943.3  389.65  4950.8  388.86
  4953.6  388.36  4956.8  388.86  5038.2  388.86  5048.7  389.78  5058.5  391.34
  5069.8  393.58  5080.3  394.42  5090.9  393.76  5101.4  394.57    5112  393.25
  5143.6  394.78  5154.1   395.7  5164.7  397.41  5175.2  398.12  5185.7  399.99
  5217.4  403.73  5227.9  405.74  5259.9  408.92  5270.1  409.99  5301.7  411.92
#Mann= 5 ,-1 , 0
  4669.2     .05       0  4950.8    .033       0  4956.8     .05       0
  5058.5     .16       0  5259.9     .12       0
Bank Sta=4901.1,5143.6
XS Rating Curve= 0 ,0
Exp/Cntr=0.3,0.1

Type RM Length L Ch R = 1 ,708     ,14,14,14
BEGIN DESCRIPTION:
Mapping XS fc5bf446
END DESCRIPTION:
XS GIS Cut Line= 2
      3715147.57     10743148.11      3715736.23     10742850.32
#Sta/Elev= 30
  4628.5  410.29  4786.1  397.61  4866.1  394.25  4888.5  392.77  4897.5   393.7
  4903.1  391.59    4911  391.35  4919.8  392.52  4925.4  390.24    4942  390.34
  4944.7  388.86  4947.4  388.36  4950.7  388.86  4977.7  388.86  4986.6  393.09
  4992.2  388.86  5000.6  388.86  5008.9  393.01  5014.5  388.86    5023  388.86
  5031.2  393.37  5036.8  388.86  5045.4  393.37  5053.5  393.46  5059.1  392.01
  5067.9  392.95  5125.9  394.19  5179.9  399.97  5277.8  406.74  5288.2  407.21
#Mann= 5 ,-1 , 0
  4628.5     .05       0  4944.7     .07       0  4950.7     .05       0
  4977.7     .16       0  5277.8     .12       0
Bank Sta=4866.1,5125.9
XS Rating Curve= 0 ,0
Exp/Cntr=0.3,0.1

Type RM Length L Ch R = 1 ,694     ,15,15,15
BEGIN DESCRIPTION:
Mapping XS 07e803e1
END DESCRIPTION:
XS GIS Cut Line= 2
      3715159.71     10743160.27      3715733.66     10742864.65
#Sta/Elev= 30
  4630.4  410.73  4660.9  407.85  4666.5  406.67  4675.3  406.52    4683  405.34
  4688.7   405.9  4697.8  404.85  4705.2  402.73  4710.8   403.1  4765.3  398.79
  4799.5  396.83  4866.5  394.32  4876.9  393.49    4889  394.12  4966.5  392.92
  4993.4  393.07  5001.5  392.22  5015.6  393.21  5029.1  391.38  5031.9  390.88
  5035.1  391.38  5037.7  393.42  5054.3  391.49  5059.9  393.18  5076.4  392.42
  5104.2  393.93  5142.9  395.69  5165.1  399.15  5273.1  406.52    5276  406.93
#Mann= 5 ,-1 , 0
  4630.4     .05       0  4966.5     .16       0  5029.1     .07       0
  5035.1     .16       0  5273.1     .12       0
Bank Sta=4866.5,5104.2
XS Rating Curve= 0 ,0
Exp/Cntr=0.3,0.1

Type RM Length L Ch R = 1 ,679     ,288,288,288
BEGIN DESCRIPTION:
Mapping XS 638a6461
END DESCRIPTION:
XS GIS Cut Line= 2
      3715170.11     10743175.91      3715758.61     10742865.16
#Sta/Elev= 30
  4632.9  411.01  4740.6  399.65  4813.3  396.59  4823.1  394.97  4858.5  393.81
  4867.1  392.73  4903.7  391.93  4933.1  389.74  4938.8  391.62    4949  389.99
  4955.2     388  4958.3  390.04  4960.8  391.69  4971.5  389.42  4977.2  391.68
  4990.5  387.93  4993.3  387.43  4996.5  387.93  4999.2  391.35  5015.6  389.29
  5021.2  391.51  5028.1  390.24  5037.6     390  5073.4  391.86  5081.6  393.34
  5153.3  396.18    5186  400.67  5197.8  400.86    5272  406.45  5298.4  407.96
#Mann= 5 ,-1 , 0
  4632.9     .05       0  4958.3     .16       0  4990.5     .07       0
  4996.5     .16       0    5272     .12       0
Bank Sta=4903.7,5073.4
XS Rating Curve= 0 ,0
Exp/Cntr=0.3,0.1

Type RM Length L Ch R = 1 ,391     ,367,367,367
BEGIN DESCRIPTION:
Mapping XS 416daa6b
END DESCRIPTION:
XS GIS Cut Line= 3
      3715281.23       10743445.      3715645.81     10743221.04
      3715841.46      10742954.4
#Sta/Elev= 30
  4607.3  419.48  4624.5  418.82  4630.4  417.26  4675.8  412.02  4688.4   409.3
    4711  407.44  4719.2  405.72  4734.5  404.18  4746.4   401.6  4835.2   393.5
  4893.2  389.16  4932.3  387.99  4957.5  386.35  5021.6  383.66  5024.4  383.16
  5027.6  383.66  5076.5  385.13    5088  387.04  5123.5  388.43  5146.6  390.59
  5152.8  391.93  5209.9  394.78  5223.8  397.41  5232.2  396.84  5253.1  397.59
  5259.5  399.05  5288.6  400.54  5302.1  402.94  5338.8  404.27  5365.9   407.8
#Mann= 6 ,-1 , 0
  4607.3     .05       0  4932.3     .12       0  5021.6     .07       0
  5027.6     .12       0  5076.5     .16       0  5302.1     .12       0
Bank Sta=4957.5,5088
XS Rating Curve= 0 ,0
Exp/Cntr=0.3,0.1

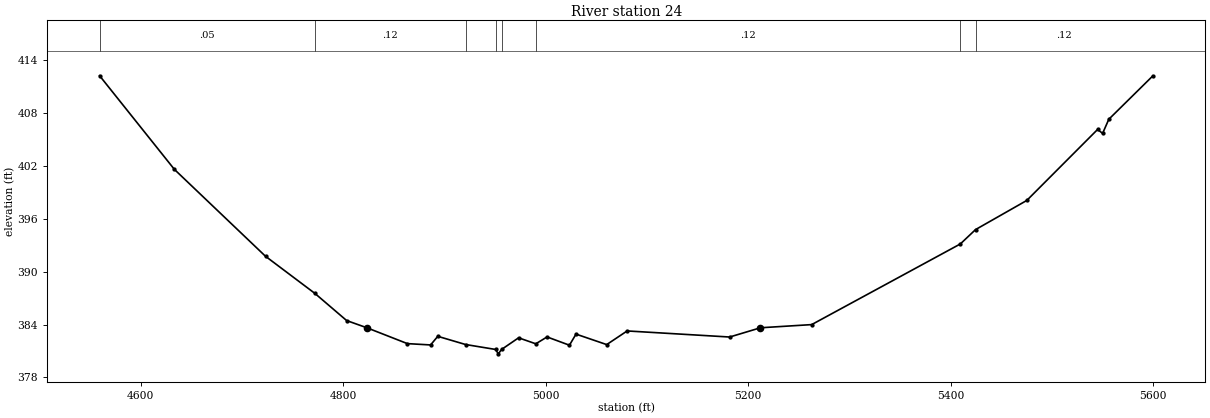
Type RM Length L Ch R = 1 ,24      ,0,0,0
BEGIN DESCRIPTION:
UNT 072 IN CACR 1.0
END DESCRIPTION:
XS GIS Cut Line= 4
      3715395.84     10743505.76      3715814.22     10743517.91
      3715843.73     10743493.61      3715932.27     10742917.25
#Sta/Elev= 30
  4559.5  412.25  4633.3  401.62  4723.3  391.75  4772.1  387.53  4803.4  384.45
  4823.4  383.63  4863.4  381.83  4886.3  381.68  4893.4  382.66  4920.8  381.73
  4950.4  381.17  4953.2  380.67  4956.4  381.17  4973.2  382.49  4990.2  381.81
  5001.3  382.59  5023.4  381.65  5029.9  382.91  5060.2  381.72  5080.4  383.27
  5181.6  382.58    5212  383.63  5262.6  383.99  5409.4  393.15  5424.4  394.78
    5475  398.09  5544.9  406.15  5549.9  405.71    5556  407.31  5599.4  412.23
#Mann= 8 ,-1 , 0
  4559.5     .05       0  4772.1     .12       0  4920.8     .07       0
  4950.4     .07       0  4956.4     .07       0  4990.2     .12       0
  5409.4     .16       0  5424.4     .12       0
Bank Sta=4823.4,5212
XS Rating Curve= 0 ,0
Exp/Cntr=0.3,0.1

Chan Stop Cuts=-1
Use User Specified Reach Order=0
Composite Channel Slope=5