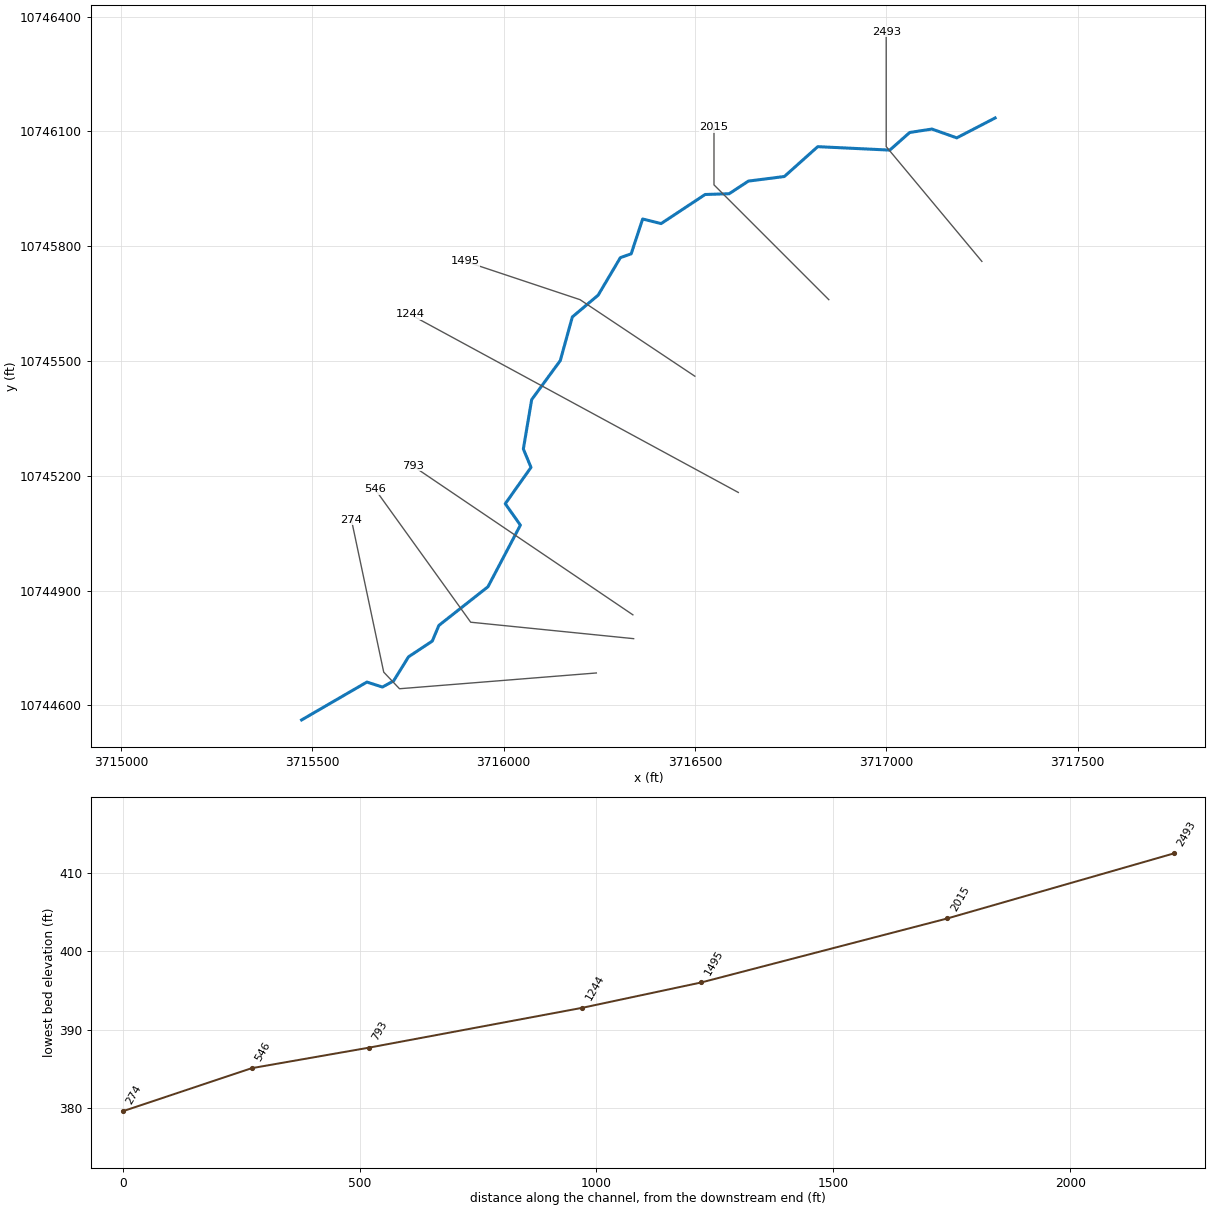
--- UNT 073 IN CACR.prj (project) ---

Proj Title=UNT 073 IN CACR Base Level Engineering
Current Plan=p01
Default Exp/Contr=0.3,0.1
English Units
Geom File=g01
Flow File=f01
Plan File=p01
BEGIN DESCRIPTION:
UNT 073 IN CACR
END DESCRIPTION:

--- UNT 073 IN CACR.p01 (plan) ---

Plan Title=Multiple Run
Short Identifier=Multiple
Geom File=g01
Flow File=f01
Subcritical Flow
K Sum by GR= 0
Std Step Tol= 0.01
Critical Tol= 0.01
Num of Std Step Trials= 20
Max Error Tol= 0.3
Flow Tol Ratio= 0.001
Split Flow NTrial= 30
Split Flow Tol= 0.02
Split Flow Ratio= 0.02
Log Output Level= 0
Friction Slope Method= 1
Unsteady Friction Slope Method= 2
Unsteady Bridges Friction Slope Method= 1
Parabolic Critical Depth
Global Vel Dist=  1 , 1 , 1
Global Log Level= 0
CheckData=True
Encroach Param= -1, 0, 0, 0
BEGIN DESCRIPTION:
Multiple Run
END DESCRIPTION:

--- UNT 073 IN CACR.f01 (steady flow) ---

Flow Title=Multiple
Number of Profiles=7
Profile Names=10-year,25-year,50-year,1pct_min,100-year,1pct_plu,500-year
River Rch & RM= UNT 073 IN CACR,Reach-1,2493
     285     370     437     382     516     698     717
Boundary for River Rch & Prof#=UNT 073 IN CACR,Reach-1,1
Up Type=0
Dn Type=3
Dn Slope=0.005
Boundary for River Rch & Prof#=UNT 073 IN CACR,Reach-1,2
Up Type=0
Dn Type=3
Dn Slope=0.005
Boundary for River Rch & Prof#=UNT 073 IN CACR,Reach-1,3
Up Type=0
Dn Type=3
Dn Slope=0.005
Boundary for River Rch & Prof#=UNT 073 IN CACR,Reach-1,4
Up Type=0
Dn Type=3
Dn Slope=0.005
Boundary for River Rch & Prof#=UNT 073 IN CACR,Reach-1,5
Up Type=0
Dn Type=3
Dn Slope=0.005
Boundary for River Rch & Prof#=UNT 073 IN CACR,Reach-1,6
Up Type=0
Dn Type=3
Dn Slope=0.005
Boundary for River Rch & Prof#=UNT 073 IN CACR,Reach-1,7
Up Type=0
Dn Type=3
Dn Slope=0.005

--- UNT 073 IN CACR.g01 (geometry) ---

Geom Title=Existing Conditions

River Reach=UNT 073 IN CACR,Reach-1
Reach XY= 30
      3717284.25     10746135.00      3717184.00     10746083.00
      3717119.00     10746106.00      3717061.00     10746097.00
      3717009.00     10746051.00      3716820.75     10746060.00
      3716733.50     10745982.00      3716639.50     10745970.00
      3716589.25     10745937.00      3716526.50     10745935.00
      3716411.50     10745859.00      3716363.25     10745871.00
      3716333.25     10745780.00      3716305.00     10745770.00
      3716247.00     10745672.00      3716179.50     10745615.00
      3716148.00     10745501.00      3716073.25     10745399.00
      3716051.50     10745270.00      3716071.50     10745222.00
      3716004.25     10745127.00      3716043.75     10745071.00
      3715959.00     10744910.00      3715830.75     10744809.00
      3715813.50     10744768.00      3715751.50     10744727.00
      3715712.50     10744664.00      3715683.25     10744648.00
      3715642.75     10744661.00      3715472.00     10744562.00

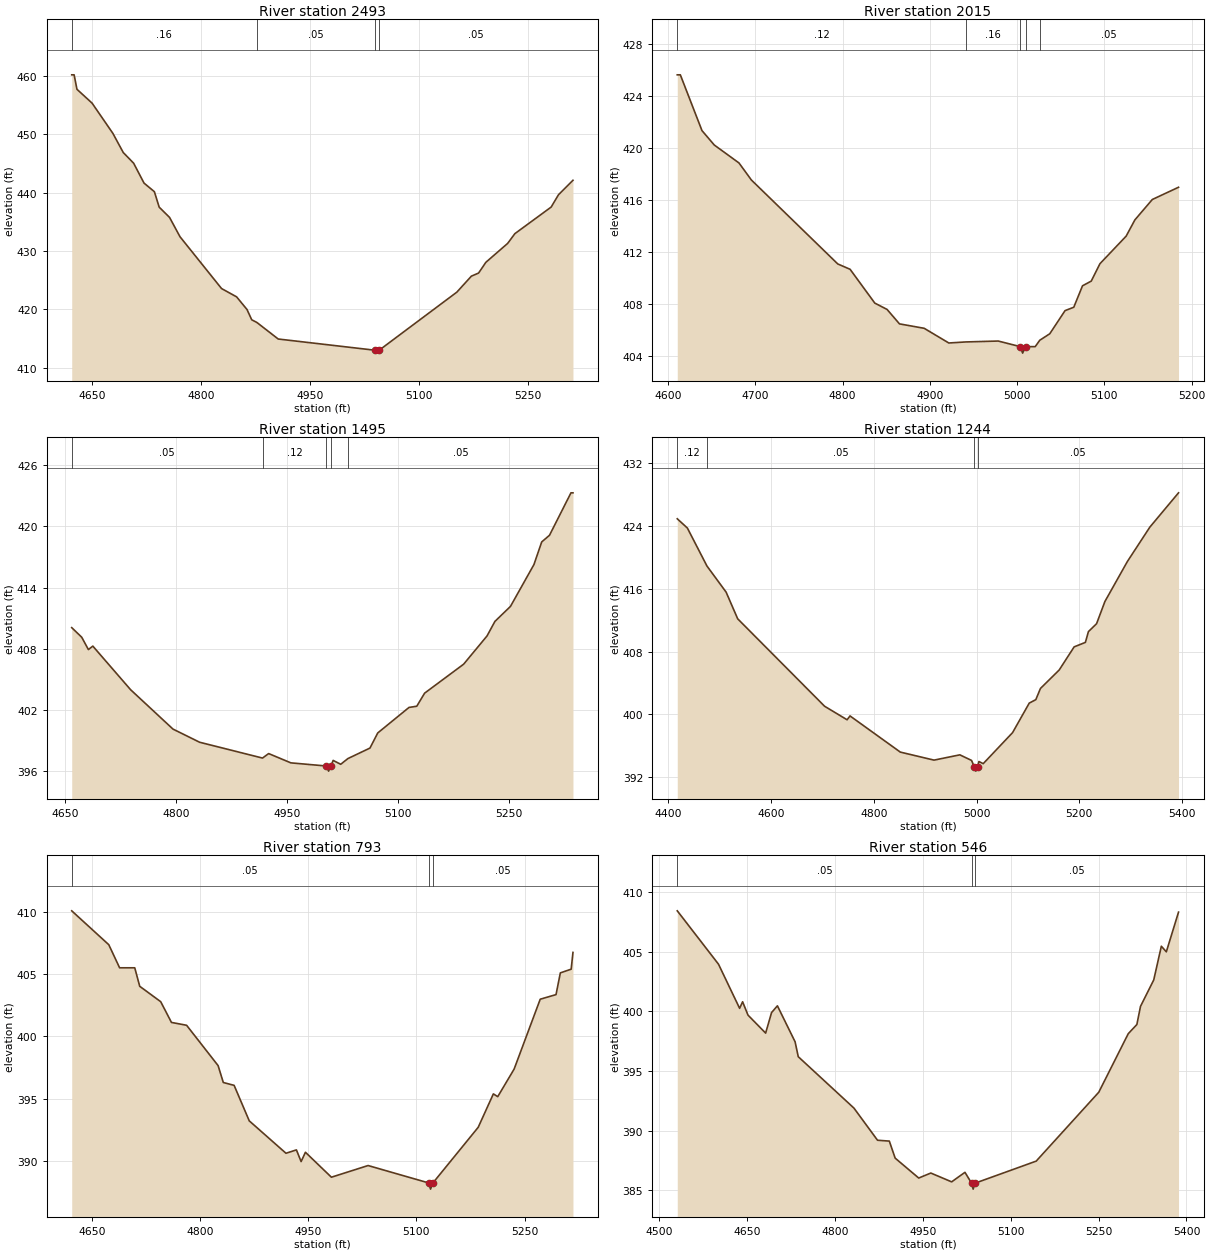
Type RM Length L Ch R = 1,2493,478,478,478
BEGIN DESCRIPTION:
UNT 073 IN CACR 5.0
END DESCRIPTION:
XS GIS Cut Line= 3
      3717249.64     10745760.15      3716999.61     10746060.19
      3716999.61     10746360.23
#Sta/Elev= 30
  4621.4  460.22  4624.7  460.22  4628.6  457.74  4649.4  455.37  4678.1  450.18
  4692.4  446.89  4706.7  445.06  4721.0  441.65  4735.3  440.17  4741.9  437.52
  4756.2  435.76  4770.5  432.46  4827.8  423.56  4848.6  422.13  4862.9  419.96
  4869.4  418.20  4876.5  417.74  4905.9  414.90  5039.0  412.98  5041.7  412.48
  5045.0  412.98  5152.0  422.94  5172.0  425.68  5182.0  426.22  5192.0  428.06
  5222.0  431.30  5232.0  432.98  5282.0  437.54  5292.0  439.64  5312.0  442.13
#Mann=4,-1,0
  4621.4    0.16       0  4876.5    0.05       0  5039.0    0.03       0
  5045.0    0.05       0
Bank Sta=5039,5045
Exp/Cntr=0.3,0.1

Type RM Length L Ch R = 1,2015,520,520,520
BEGIN DESCRIPTION:
UNT 073 IN CACR 4.0
END DESCRIPTION:
XS GIS Cut Line= 3
      3716849.62     10745660.18      3716549.61     10745960.19
      3716549.61     10746110.21
#Sta/Elev= 30
  4610.6  425.60  4614.1  425.60  4638.9  421.31  4653.0  420.20  4681.3  418.82
  4695.5  417.51  4794.5  411.05  4808.6  410.64  4836.9  408.04  4851.0  407.55
  4865.2  406.44  4893.5  406.10  4921.7  404.97  4941.0  405.05  4978.3  405.12
  5003.6  404.69  5006.3  404.19  5009.6  404.69  5020.7  404.69  5025.9  405.18
  5037.4  405.68  5054.9  407.46  5064.9  407.72  5074.9  409.37  5084.9  409.73
  5094.9  411.07  5124.9  413.19  5134.9  414.44  5154.9  416.01  5184.9  416.95
#Mann=5,-1,0
  4610.6    0.12       0  4941.0    0.16       0  5003.6    0.07       0
  5009.6    0.16       0  5025.9    0.05       0
Bank Sta=5003.6,5009.6
Exp/Cntr=0.3,0.1

Type RM Length L Ch R = 1,1495,251,251,251
BEGIN DESCRIPTION:
UNT 073 IN CACR 3.0
END DESCRIPTION:
XS GIS Cut Line= 3
      3716499.59     10745460.20      3716199.61     10745660.19
      3715899.58     10745760.20
#Sta/Elev= 30
  4659.1  410.08  4672.6  409.14  4681.6  407.93  4687.6  408.27  4738.7  403.99
  4795.8  400.14  4831.8  398.85  4916.7  397.30  4925.0  397.74  4955.0  396.83
  5003.1  396.52  5005.9  396.02  5009.1  396.52  5012.1  397.07  5022.3  396.69
  5032.0  397.25  5061.8  398.28  5072.3  399.76  5114.5  402.26  5125.0  402.38
  5135.6  403.66  5188.3  406.50  5219.9  409.27  5230.5  410.69  5251.5  412.16
  5283.2  416.26  5293.7  418.48  5304.2  419.13  5333.2  423.29  5335.9  423.29
#Mann=5,-1,0
  4659.1    0.05       0  4916.7    0.12       0  5003.1    0.07       0
  5009.1    0.12       0  5032.0    0.05       0
Bank Sta=5003.1,5009.1
Exp/Cntr=0.3,0.1

Type RM Length L Ch R = 1,1244,451,451,451
BEGIN DESCRIPTION:
Mapping XS a5c4b058
END DESCRIPTION:
XS GIS Cut Line= 2
      3716613.16     10745156.46      3715755.45     10745621.78
#Sta/Elev= 30
  4417.4  424.88  4437.1  423.70  4475.2  418.87  4512.5  415.55  4535.0  412.16
  4704.2  401.04  4748.0  399.32  4753.7  399.81  4851.6  395.21  4917.2  394.19
  4967.5  394.86  4990.3  394.15  4995.9  393.29  4998.7  392.79  5001.9  393.29
  5004.6  394.01  5013.0  393.74  5070.2  397.69  5102.6  401.44  5115.4  401.88
  5124.4  403.30  5160.9  405.65  5190.0  408.59  5211.9  409.16  5217.8  410.53
  5233.7  411.54  5249.9  414.36  5293.6  419.44  5337.4  423.82  5393.2  428.18
#Mann=4,-1,0
  4417.4    0.12       0  4475.2    0.05       0  4995.9    0.03       0
  5001.9    0.05       0
Bank Sta=4995.9,5001.9
Exp/Cntr=0.3,0.1

Type RM Length L Ch R = 1,793,247,247,247
BEGIN DESCRIPTION:
UNT 073 IN CACR 2.0
END DESCRIPTION:
XS GIS Cut Line= 2
      3716337.70     10744836.68      3715762.02     10745226.24
#Sta/Elev= 30
  4622.0  410.12  4673.4  407.39  4688.4  405.53  4709.4  405.53  4716.3  404.04
  4745.4  402.80  4760.3  401.13  4781.3  400.90  4825.0  397.65  4832.2  396.29
  4847.2  396.06  4868.2  393.20  4919.1  390.59  4933.6  390.86  4940.1  389.92
  4946.1  390.67  4982.1  388.66  5033.0  389.60  5116.9  388.20  5119.6  387.70
  5122.9  388.20  5185.7  392.68  5206.7  395.37  5212.8  395.15  5235.5  397.37
  5271.7  403.00  5293.6  403.37  5299.6  405.12  5314.6  405.42  5317.1  406.77
#Mann=3,-1,0
  4622.0    0.05       0  5116.9    0.03       0  5122.9    0.05       0
Bank Sta=5116.9,5122.9
Exp/Cntr=0.3,0.1

Type RM Length L Ch R = 1,546,272,272,272
BEGIN DESCRIPTION:
Mapping XS 0981fd52
END DESCRIPTION:
XS GIS Cut Line= 3
      3716339.67     10744774.42      3715913.94     10744817.38
      3715664.29     10745164.54
#Sta/Elev= 30
  4530.9  408.44  4601.3  403.96  4637.3  400.26  4642.4  400.81  4651.6  399.69
  4681.7  398.18  4691.8  399.90  4701.8  400.47  4732.0  397.45  4737.4  396.20
  4832.4  391.89  4872.7  389.19  4892.8  389.12  4902.8  387.69  4943.0  386.02
  4963.6  386.44  4999.2  385.70  5021.9  386.50  5033.2  385.59  5035.9  385.09
  5039.2  385.59  5143.5  387.44  5250.3  393.22  5300.6  398.13  5315.3  398.90
  5321.5  400.42  5344.1  402.64  5357.1  405.47  5365.6  405.00  5386.4  408.33
#Mann=3,-1,0
  4530.9    0.05       0  5033.2    0.03       0  5039.2    0.05       0
Bank Sta=5033.2,5039.2
Exp/Cntr=0.3,0.1

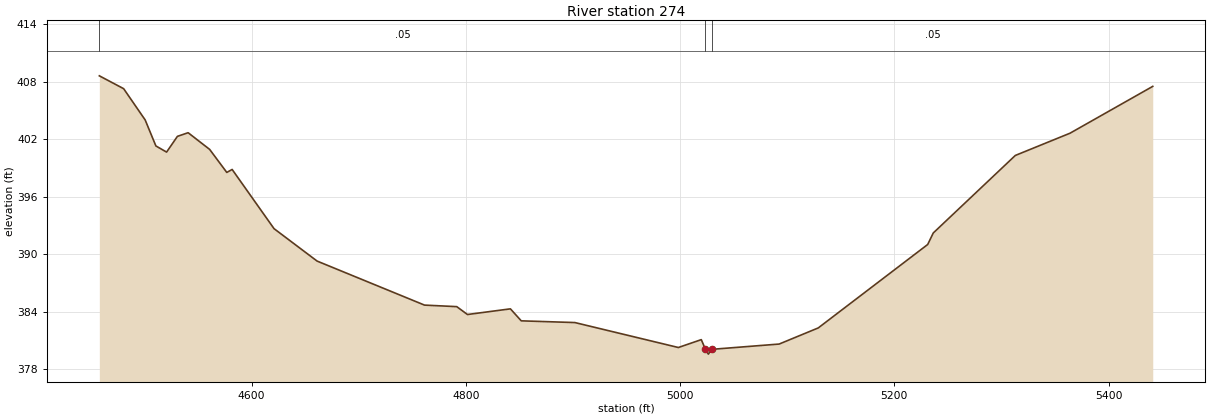
Type RM Length L Ch R = 1,274,0,0,0
BEGIN DESCRIPTION:
UNT 073 IN CACR 1.0
END DESCRIPTION:
XS GIS Cut Line= 4
      3716242.23     10744684.78      3715727.89     10744643.54
      3715686.65     10744686.95      3715602.13     10745085.73
#Sta/Elev= 30
  4457.8  408.61  4480.5  407.27  4500.6  404.01  4510.6  401.30  4520.6  400.66
  4530.7  402.30  4540.7  402.68  4560.8  400.94  4576.8  398.54  4581.8  398.85
  4620.9  392.68  4661.1  389.30  4761.4  384.71  4791.5  384.55  4801.5  383.73
  4841.6  384.32  4851.7  383.07  4901.8  382.89  4998.4  380.29  5019.8  381.11
  5023.7  380.10  5026.4  379.60  5029.7  380.10  5092.5  380.65  5129.0  382.33
  5231.2  391.03  5236.4  392.23  5313.0  400.31  5364.1  402.63  5441.3  407.51
#Mann=3,-1,0
  4457.8    0.05       0  5023.7    0.03       0  5029.7    0.05       0
Bank Sta=5023.7,5029.7
Exp/Cntr=0.3,0.1

Chan Stop Cuts=-1