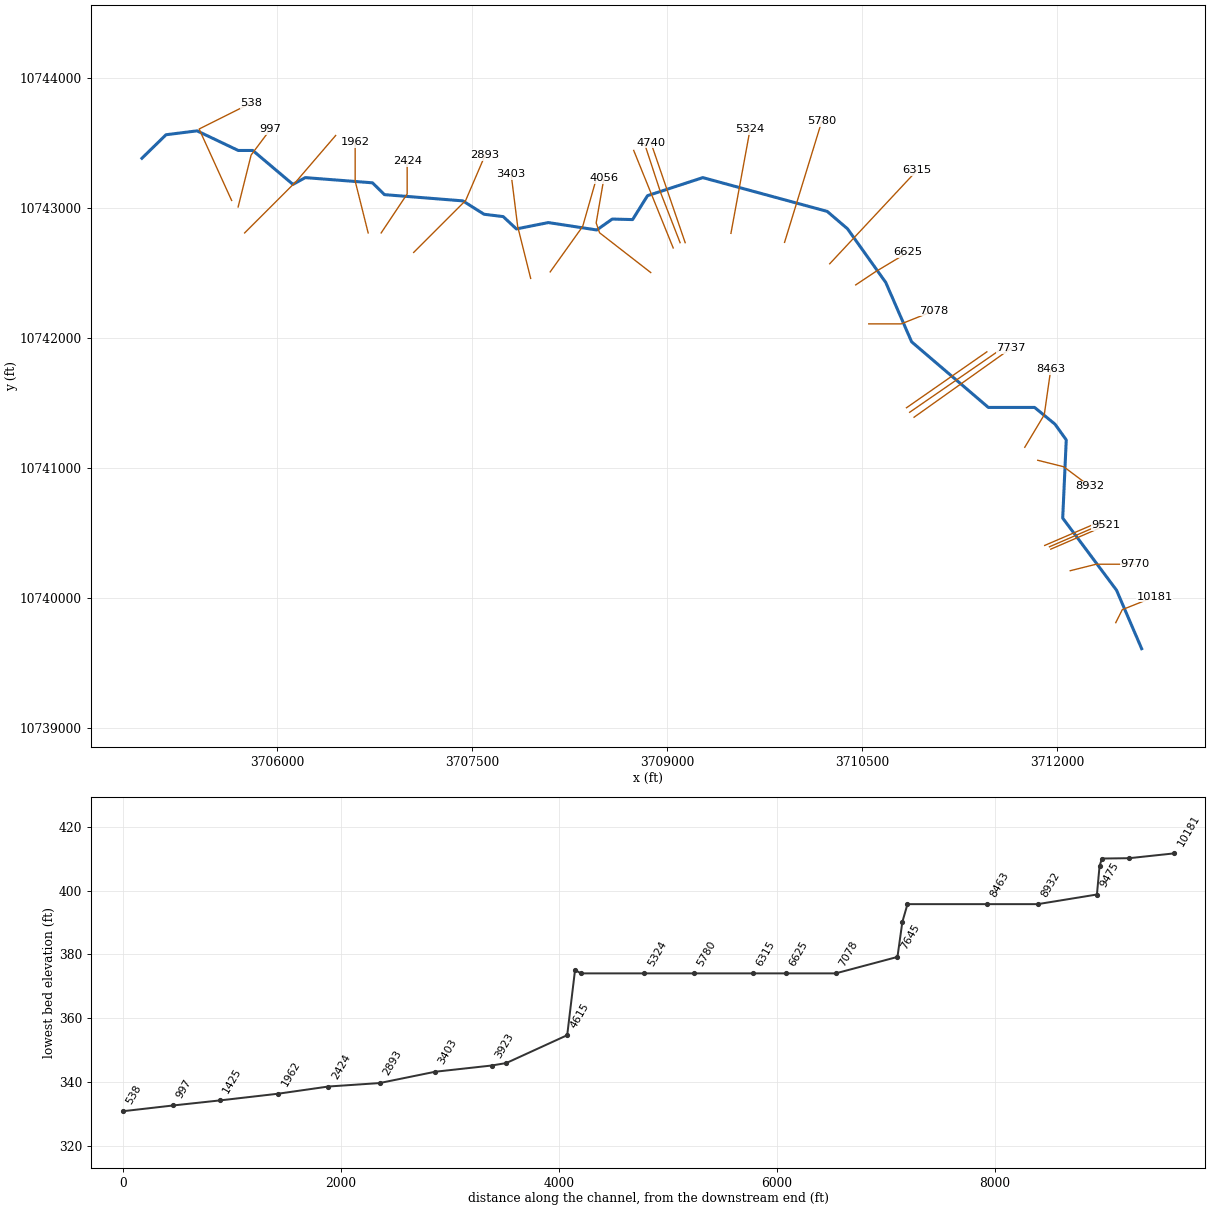
--- UNT 074 IN CACR.prj (project) ---

Proj Title=UNT 074 IN CACR Base Level Engineering
Current Plan=p01
Default Exp/Contr=0.3,0.1
English Units
Geom File=g01
Flow File=f01
Plan File=p01
BEGIN DESCRIPTION:
UNT 074 IN CACR
END DESCRIPTION:

--- UNT 074 IN CACR.p01 (plan) ---

Plan Title=Multiple Run
Short Identifier=Multiple
Geom File=g01
Flow File=f01
Subcritical Flow
K Sum by GR= 0
Std Step Tol= 0.01
Critical Tol= 0.01
Num of Std Step Trials= 20
Max Error Tol= 0.3
Flow Tol Ratio= 0.001
Split Flow NTrial= 30
Split Flow Tol= 0.02
Split Flow Ratio= 0.02
Log Output Level= 0
Friction Slope Method= 1
Unsteady Friction Slope Method= 2
Unsteady Bridges Friction Slope Method= 1
Parabolic Critical Depth
Global Vel Dist=  1 , 1 , 1
Global Log Level= 0
CheckData=True
Encroach Param= -1, 0, 0, 0
BEGIN DESCRIPTION:
Multiple Run
END DESCRIPTION:

--- UNT 074 IN CACR.f01 (steady flow) ---

Flow Title=Multiple
Number of Profiles=7
Profile Names=10-year,25-year,50-year,1pct_min,100-year,1pct_plu,500-year
River Rch & RM= UNT 074 IN CACR,Reach-1,10181
     557     749     906     804    1088    1471    1570
River Rch & RM= UNT 074 IN CACR,Reach-1,3923
     714     972    1186    1061    1435    1940    2103
Boundary for River Rch & Prof#=UNT 074 IN CACR,Reach-1,1
Up Type=0
Dn Type=3
Dn Slope=0.005
Boundary for River Rch & Prof#=UNT 074 IN CACR,Reach-1,2
Up Type=0
Dn Type=3
Dn Slope=0.005
Boundary for River Rch & Prof#=UNT 074 IN CACR,Reach-1,3
Up Type=0
Dn Type=3
Dn Slope=0.005
Boundary for River Rch & Prof#=UNT 074 IN CACR,Reach-1,4
Up Type=0
Dn Type=3
Dn Slope=0.005
Boundary for River Rch & Prof#=UNT 074 IN CACR,Reach-1,5
Up Type=0
Dn Type=3
Dn Slope=0.005
Boundary for River Rch & Prof#=UNT 074 IN CACR,Reach-1,6
Up Type=0
Dn Type=3
Dn Slope=0.005
Boundary for River Rch & Prof#=UNT 074 IN CACR,Reach-1,7
Up Type=0
Dn Type=3
Dn Slope=0.005

--- UNT 074 IN CACR.g01 (geometry) ---

Geom Title=Existing Conditions

River Reach=UNT 074 IN CACR,Reach-1
Reach XY= 30
      3712648.71     10739609.86      3712455.50     10740060.00
      3712041.50     10740615.00      3712068.75     10741217.00
      3711982.25     10741338.00      3711825.25     10741467.00
      3711469.50     10741467.00      3710879.50     10741972.00
      3710680.50     10742429.00      3710386.50     10742842.00
      3710230.25     10742976.00      3709273.50     10743236.00
      3708848.25     10743097.00      3708733.50     10742913.00
      3708577.00     10742917.00      3708458.00     10742833.00
      3708085.50     10742890.00      3707839.75     10742841.00
      3707738.25     10742936.00      3707591.00     10742954.00
      3707428.00     10743057.00      3706825.00     10743105.00
      3706733.00     10743196.00      3706216.00     10743236.00
      3706121.00     10743184.00      3705812.25     10743445.00
      3705700.50     10743445.00      3705383.75     10743596.00
      3705145.00     10743566.00      3704959.75     10743385.00

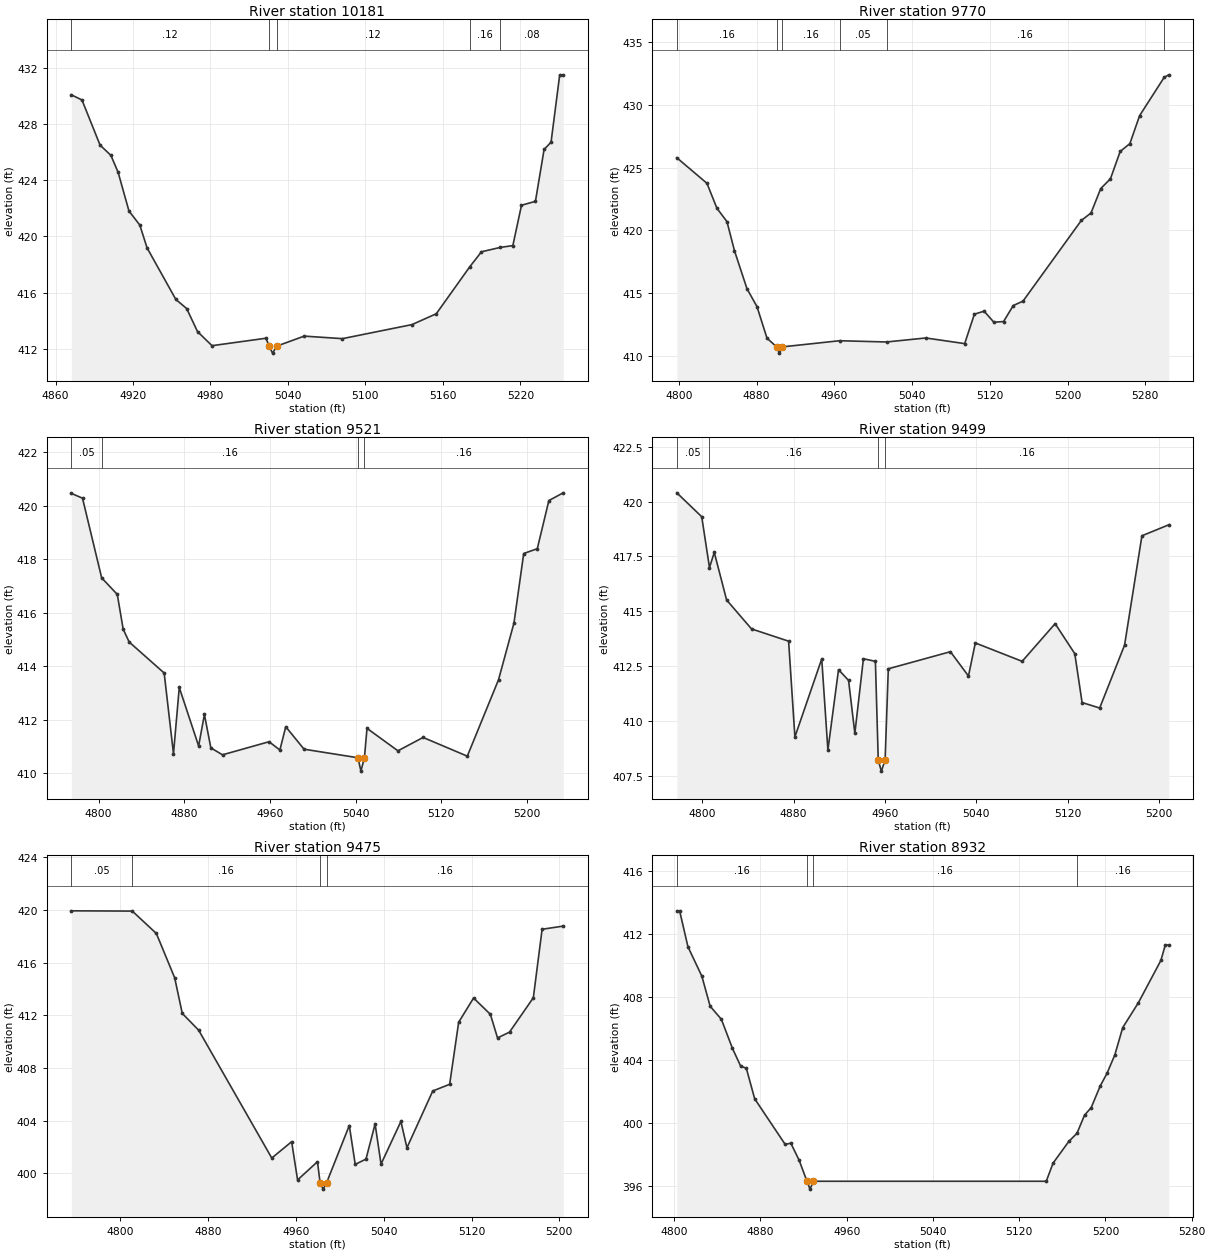
Type RM Length L Ch R = 1,10181,411,411,411
BEGIN DESCRIPTION:
UNT 074 IN CACR 22.0
END DESCRIPTION:
XS GIS Cut Line= 3
      3712449.63     10739810.22      3712499.61     10739910.19
      3712749.59     10740010.18
#Sta/Elev= 30
  4872.2  430.07  4880.5  429.70  4894.5  426.49  4902.9  425.76  4908.5  424.55
  4916.9  421.80  4925.3  420.80  4930.9  419.18  4953.2  415.51  4961.6  414.86
  4970.0  413.22  4981.2  412.22  5023.0  412.75  5025.4  412.19  5028.1  411.69
  5031.4  412.19  5052.6  412.90  5082.2  412.72  5136.1  413.72  5154.9  414.49
  5180.9  417.84  5189.9  418.90  5204.4  419.21  5214.2  419.34  5220.9  422.21
  5231.7  422.49  5238.4  426.18  5243.8  426.70  5250.5  431.49  5253.2  431.49
#Mann=5,-1,0
  4872.2    0.12       0  5025.4    0.07       0  5031.4    0.12       0
  5180.9    0.16       0  5204.4    0.08       0
Bank Sta=5025.4,5031.4
Exp/Cntr=0.3,0.1

Type RM Length L Ch R = 1,9770,249,249,249
BEGIN DESCRIPTION:
UNT 074 IN CACR 21.0
END DESCRIPTION:
XS GIS Cut Line= 3
      3712099.58     10740210.18      3712299.61     10740260.19
      3712599.62     10740260.19
#Sta/Elev= 30
  4797.9  425.79  4828.9  423.75  4839.2  421.75  4849.5  420.69  4857.2  418.37
  4870.1  415.33  4880.4  413.90  4890.7  411.38  4900.6  410.69  4903.3  410.19
  4906.6  410.69  4965.4  411.18  5013.7  411.08  5054.1  411.40  5094.1  410.95
  5104.1  413.30  5114.1  413.54  5124.1  412.66  5134.1  412.71  5144.1  413.99
  5154.1  414.34  5214.1  420.78  5224.1  421.38  5234.1  423.33  5244.1  424.11
  5254.1  426.29  5264.1  426.92  5274.1  429.15  5299.4  432.21  5304.1  432.41
#Mann=6,-1,0
  4797.9    0.16       0  4900.6   0.033       0  4906.6    0.16       0
  4965.4    0.05       0  5013.7    0.16       0  5299.4    0.05       0
Bank Sta=4900.6,4906.6
Exp/Cntr=0.3,0.1

Type RM Length L Ch R = 1,9521,22,22,22
BEGIN DESCRIPTION:
Mapping XS cecf9fa5
END DESCRIPTION:
XS GIS Cut Line= 2
      3711949.94     10740376.04      3712371.84     10740558.34
#Sta/Elev= 30
  4774.4  420.47  4784.9  420.29  4802.8  417.31  4817.4  416.69  4822.9  415.39
  4828.5  414.91  4861.2  413.75  4869.9  410.73  4875.3  413.21  4893.4  411.02
  4898.8  412.20  4904.8  410.95  4915.7  410.69  4959.2  411.18  4969.3  410.87
  4974.8  411.74  4991.9  410.90  5042.3  410.58  5045.0  410.08  5048.3  410.58
  5050.7  411.68  5079.6  410.84  5103.1  411.34  5144.4  410.64  5173.6  413.50
  5188.0  415.62  5197.1  418.22  5209.8  418.40  5220.6  420.20  5234.0  420.49
#Mann=4,-1,0
  4774.4    0.05       0  4802.8    0.16       0  5042.3    0.07       0
  5048.3    0.16       0
Bank Sta=5042.3,5048.3
Exp/Cntr=0.3,0.1

Type RM Length L Ch R = 1,9499,24,24,24
BEGIN DESCRIPTION:
Mapping XS 0278a28d
END DESCRIPTION:
XS GIS Cut Line= 2
      3711939.57     10740394.29      3712335.13     10740564.93
#Sta/Elev= 30
  4777.8  420.40  4799.6  419.31  4806.4  416.99  4810.6  417.68  4821.4  415.51
  4843.2  414.19  4875.7  413.63  4881.2  409.26  4904.7  412.82  4910.1  408.66
  4919.4  412.33  4928.2  411.84  4933.7  409.42  4941.2  412.83  4951.7  412.71
  4954.2  408.20  4956.9  407.70  4960.2  408.20  4963.0  412.37  5017.4  413.15
  5033.2  412.04  5039.2  413.55  5080.2  412.71  5109.1  414.43  5126.3  413.06
  5132.7  410.83  5148.1  410.58  5169.9  413.45  5185.1  418.44  5208.6  418.94
#Mann=4,-1,0
  4777.8    0.05       0  4806.4    0.16       0  4954.2    0.07       0
  4960.2    0.16       0
Bank Sta=4954.2,4960.2
Exp/Cntr=0.3,0.1

Type RM Length L Ch R = 1,9475,543,543,543
BEGIN DESCRIPTION:
UNT 074 IN CACR 20.0
END DESCRIPTION:
XS GIS Cut Line= 2
      3711903.05     10740404.68      3712314.56     10740581.79
#Sta/Elev= 30
  4755.5  419.93  4811.1  419.91  4833.0  418.21  4849.7  414.84  4856.6  412.14
  4871.5  410.87  4938.1  401.16  4956.2  402.40  4961.6  399.50  4979.7  400.88
  4982.1  399.30  4984.9  398.80  4988.1  399.30  5008.7  403.63  5014.1  400.68
  5023.9  401.08  5032.2  403.75  5037.6  400.70  5055.7  403.94  5061.2  401.94
  5084.7  406.25  5100.1  406.76  5108.3  411.47  5121.9  413.31  5137.2  412.07
  5143.7  410.28  5154.6  410.72  5176.3  413.33  5184.3  418.53  5203.5  418.77
#Mann=4,-1,0
  4755.5    0.05       0  4811.1    0.16       0  4982.1    0.07       0
  4988.1    0.16       0
Bank Sta=4982.1,4988.1
Exp/Cntr=0.3,0.1

Type RM Length L Ch R = 1,8932,469,469,469
BEGIN DESCRIPTION:
UNT 074 IN CACR 19.0
END DESCRIPTION:
XS GIS Cut Line= 3
      3711849.59     10741060.19      3712049.61     10741010.19
      3712249.63     10740860.17
#Sta/Elev= 30
  4802.5  413.46  4805.1  413.46  4812.8  411.18  4825.7  409.31  4833.4  407.40
  4843.8  406.57  4854.1  404.72  4861.8  403.58  4866.9  403.47  4874.7  401.52
  4903.0  398.62  4908.2  398.70  4915.9  397.62  4923.2  396.28  4926.0  395.78
  4929.2  396.28  5145.1  396.28  5151.4  397.43  5166.0  398.81  5173.6  399.33
  5180.6  400.48  5186.8  400.96  5195.1  402.33  5201.4  403.13  5208.7  404.31
  5216.0  406.04  5230.6  407.63  5251.4  410.31  5255.5  411.29  5258.7  411.29
#Mann=4,-1,0
  4802.5    0.16       0  4923.2   0.033       0  4929.2    0.16       0
  5173.6    0.16       0
Bank Sta=4923.2,4929.2
Exp/Cntr=0.3,0.1

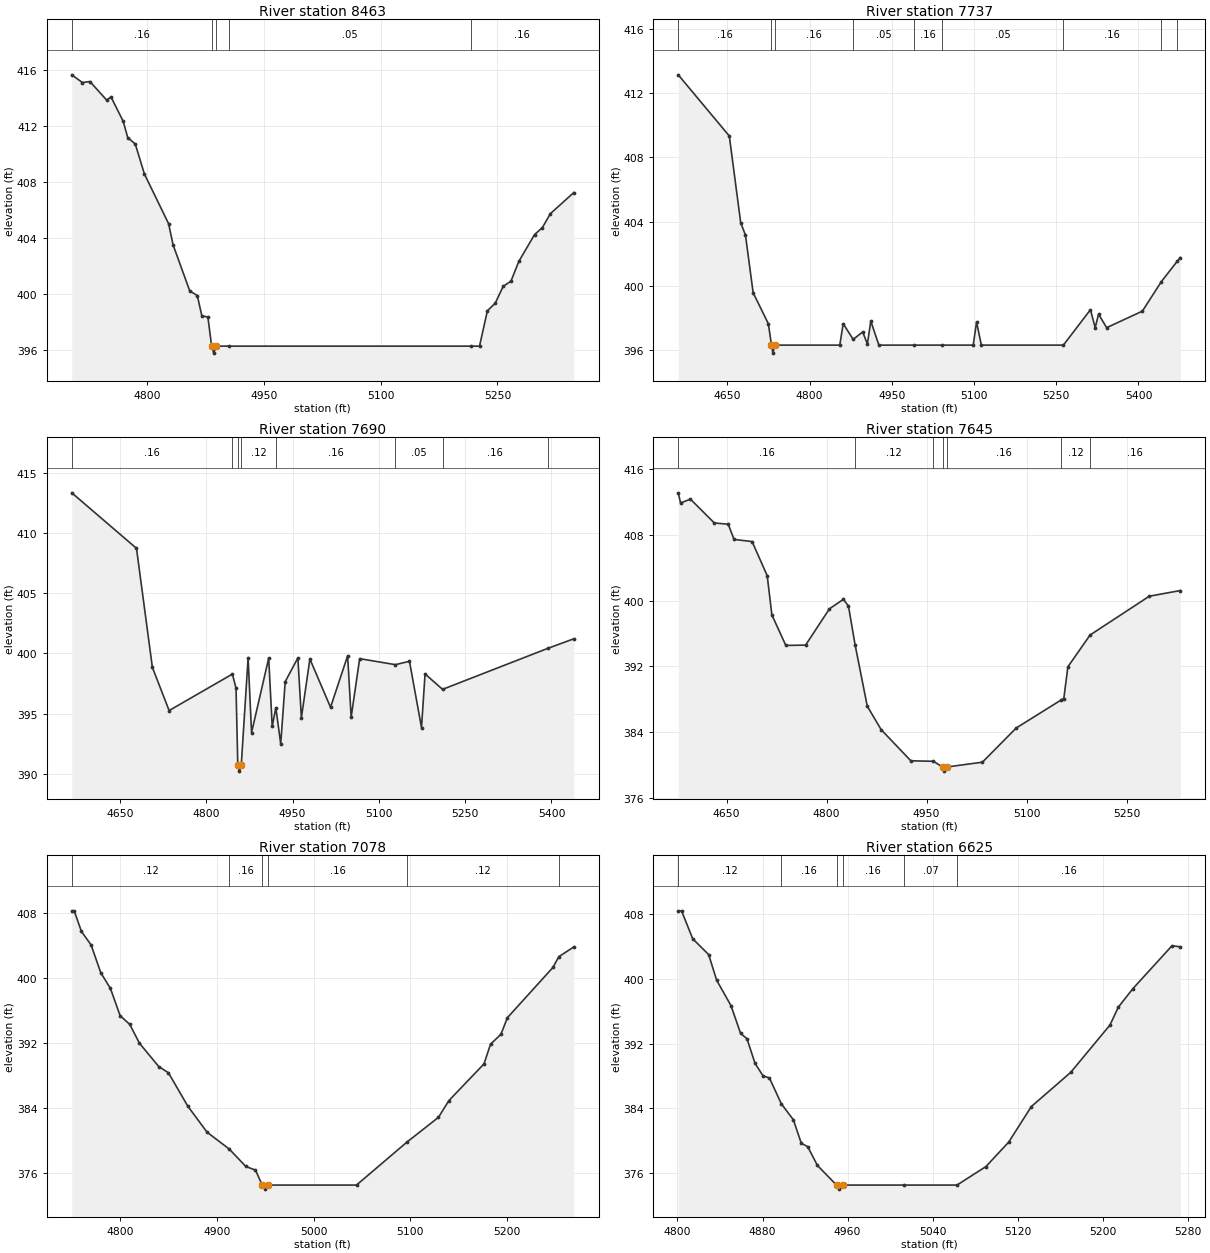
Type RM Length L Ch R = 1,8463,726,726,726
BEGIN DESCRIPTION:
UNT 074 IN CACR 18.0
END DESCRIPTION:
XS GIS Cut Line= 3
      3711749.62     10741160.20      3711899.61     10741410.19
      3711949.61     10741760.21
#Sta/Elev= 30
  4703.0  415.69  4716.6  415.14  4726.3  415.21  4747.7  413.89  4753.5  414.10
  4769.1  412.36  4774.9  411.20  4784.6  410.74  4796.3  408.60  4827.4  405.04
  4833.2  403.52  4854.6  400.23  4864.3  399.90  4870.1  398.45  4877.9  398.36
  4882.7  396.28  4885.4  395.78  4888.7  396.28  4905.0  396.28  5215.8  396.28
  5226.9  396.28  5237.0  398.81  5247.1  399.35  5257.2  400.55  5267.3  400.93
  5277.4  402.34  5297.6  404.26  5307.7  404.76  5317.8  405.75  5348.1  407.27
#Mann=5,-1,0
  4703.0    0.16       0  4882.7   0.033       0  4888.7    0.16       0
  4905.0    0.05       0  5215.8    0.16       0
Bank Sta=4882.7,4888.7
Exp/Cntr=0.3,0.1

Type RM Length L Ch R = 1,7737,47,47,47
BEGIN DESCRIPTION:
UNT 074 IN CACR 17.0
END DESCRIPTION:
XS GIS Cut Line= 2
      3710898.24     10741391.51      3711644.72     10741922.73
#Sta/Elev= 30
  4560.2  413.16  4653.4  409.34  4674.2  403.92  4682.9  403.15  4696.9  399.55
  4724.7  397.61  4730.3  396.28  4733.0  395.78  4736.3  396.28  4855.0  396.28
  4861.2  397.62  4879.4  396.64  4896.8  397.10  4905.4  396.35  4911.6  397.78
  4926.3  396.28  4990.0  396.28  5042.0  396.28  5098.5  396.28  5104.6  397.73
  5113.3  396.28  5263.0  396.28  5312.4  398.49  5321.1  397.37  5327.2  398.21
  5342.0  397.37  5407.1  398.40  5441.7  400.24  5470.6  401.51  5476.4  401.75
#Mann=9,-1,0
  4560.2    0.16       0  4730.3    0.07       0  4736.3    0.16       0
  4879.4    0.05       0  4990.0    0.16       0  5042.0    0.05       0
  5263.0    0.16       0  5441.7    0.05       0  5470.6    0.16       0
Bank Sta=4730.3,4736.3
Exp/Cntr=0.3,0.1

Type RM Length L Ch R = 1,7690,45,45,45
BEGIN DESCRIPTION:
Mapping XS a3390357
END DESCRIPTION:
XS GIS Cut Line= 2
      3710864.37     10741429.70      3711582.40     10741925.72
#Sta/Elev= 30
  4566.2  413.34  4678.7  408.73  4706.3  398.85  4735.4  395.26  4845.4  398.29
  4851.7  397.12  4854.8  390.73  4857.5  390.23  4860.8  390.73  4872.7  399.63
  4878.7  393.43  4908.5  399.61  4914.6  393.94  4920.9  395.50  4929.4  392.49
  4937.2  397.66  4959.2  399.63  4965.3  394.66  4980.1  399.54  5016.0  395.53
  5045.7  399.81  5051.8  394.70  5066.6  399.57  5128.7  399.07  5153.2  399.35
  5174.1  393.85  5180.3  398.30  5210.7  397.02  5393.4  400.42  5438.9  401.22
#Mann=8,-1,0
  4566.2    0.16       0  4845.4    0.12       0  4854.8    0.07       0
  4860.8    0.12       0  4920.9    0.16       0  5128.7    0.05       0
  5210.7    0.16       0  5393.4    0.05       0
Bank Sta=4854.8,4860.8
Exp/Cntr=0.3,0.1

Type RM Length L Ch R = 1,7645,567,567,567
BEGIN DESCRIPTION:
UNT 074 IN CACR 16.0
END DESCRIPTION:
XS GIS Cut Line= 2
      3710840.04     10741464.40      3711458.14     10741894.99
#Sta/Elev= 30
  4577.4  413.15  4580.9  411.91  4595.7  412.38  4631.5  409.48  4652.4  409.32
  4661.2  407.47  4688.2  407.21  4710.9  403.05  4717.9  398.27  4738.8  394.55
  4768.5  394.59  4804.3  399.02  4825.2  400.17  4832.8  399.35  4842.8  394.61
  4861.0  387.15  4881.9  384.28  4926.4  380.49  4960.3  380.43  4974.1  379.73
  4976.8  379.23  4980.1  379.73  5033.8  380.32  5084.4  384.48  5152.0  387.91
  5155.9  388.07  5162.0  391.94  5195.3  395.82  5284.2  400.55  5330.7  401.24
#Mann=7,-1,0
  4577.4    0.16       0  4842.8    0.12       0  4960.3    0.16       0
  4974.1    0.07       0  4980.1    0.16       0  5152.0    0.12       0
  5195.3    0.16       0
Bank Sta=4974.1,4980.1
Exp/Cntr=0.3,0.1

Type RM Length L Ch R = 1,7078,453,453,453
BEGIN DESCRIPTION:
UNT 074 IN CACR 15.0
END DESCRIPTION:
XS GIS Cut Line= 3
      3710549.56     10742110.19      3710799.61     10742110.19
      3711049.61     10742210.19
#Sta/Elev= 30
  4749.9  408.32  4752.4  408.32  4759.9  405.78  4769.9  404.12  4779.9  400.70
  4789.9  398.77  4799.9  395.42  4809.9  394.34  4819.9  392.03  4839.9  389.15
  4849.9  388.39  4869.9  384.28  4889.9  381.07  4912.8  379.00  4929.9  376.86
  4939.9  376.41  4946.9  374.57  4949.7  374.07  4952.9  374.57  5044.4  374.57
  5096.6  379.86  5129.2  382.91  5140.0  384.97  5176.3  389.49  5183.0  391.90
  5193.8  393.13  5200.5  395.17  5247.7  401.37  5253.6  402.67  5269.2  403.88
#Mann=6,-1,0
  4749.9    0.12       0  4912.8    0.16       0  4946.9    0.07       0
  4952.9    0.16       0  5096.6    0.12       0  5253.6    0.16       0
Bank Sta=4946.9,4952.9
Exp/Cntr=0.3,0.1

Type RM Length L Ch R = 1,6625,310,310,310
BEGIN DESCRIPTION:
UNT 074 IN CACR 14.0
END DESCRIPTION:
XS GIS Cut Line= 3
      3710449.57     10742410.16      3710599.61     10742510.19
      3710849.63     10742660.20
#Sta/Elev= 30
  4800.8  408.34  4803.9  408.34  4814.4  404.90  4829.4  402.95  4836.9  399.80
  4850.4  396.66  4859.4  393.25  4865.4  392.59  4873.0  389.55  4880.5  388.02
  4886.5  387.76  4897.7  384.58  4909.0  382.61  4916.5  379.71  4922.5  379.30
  4931.6  376.99  4949.6  374.57  4952.3  374.07  4955.6  374.57  5012.8  374.57
  5062.8  374.57  5090.0  376.85  5111.4  379.86  5132.7  384.24  5169.7  388.45
  5206.6  394.28  5214.4  396.47  5228.0  398.74  5264.9  404.04  5272.7  403.91
#Mann=6,-1,0
  4800.8    0.12       0  4897.7    0.16       0  4949.6    0.07       0
  4955.6    0.16       0  5012.8    0.07       0  5062.8    0.16       0
Bank Sta=4949.6,4955.6
Exp/Cntr=0.3,0.1

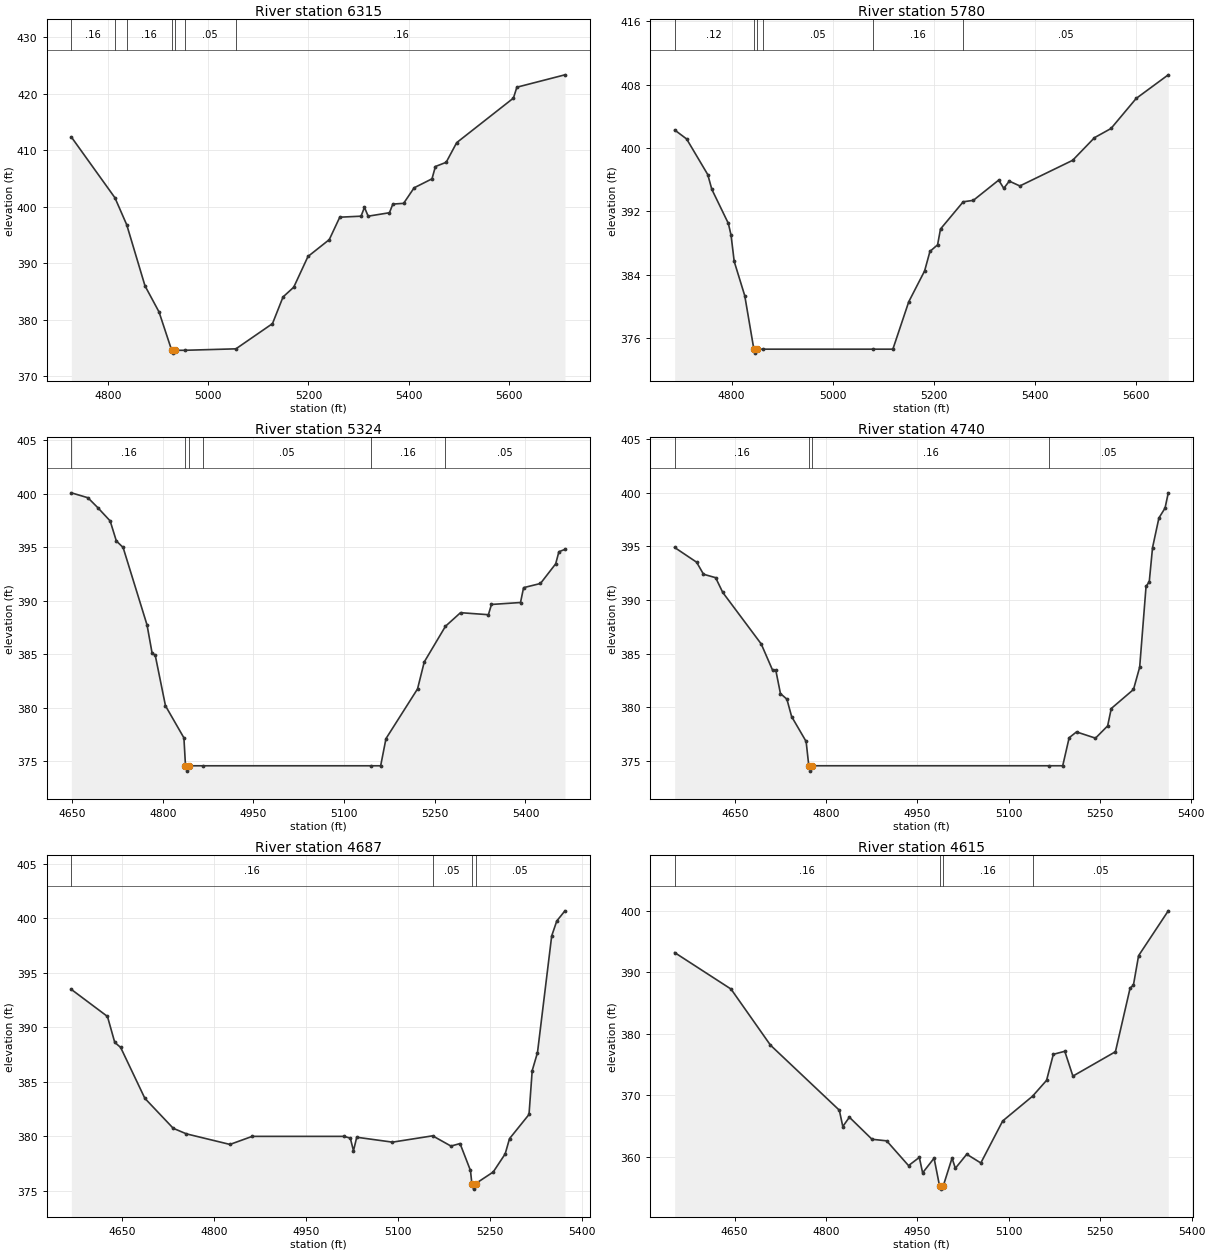
Type RM Length L Ch R = 1,6315,535,535,535
BEGIN DESCRIPTION:
UNT 074 IN CACR 13.0
END DESCRIPTION:
XS GIS Cut Line= 2
      3710249.39     10742572.66      3710922.18     10743293.19
#Sta/Elev= 30
  4726.6  412.31  4813.7  401.55  4837.2  396.78  4873.7  385.97  4901.7  381.36
  4927.0  374.57  4929.8  374.07  4933.0  374.57  4952.8  374.57  5055.3  374.83
  5128.3  379.29  5149.4  384.01  5170.8  385.74  5199.2  391.17  5241.7  394.15
  5262.7  398.12  5305.2  398.30  5312.0  399.86  5319.4  398.30  5361.9  398.91
  5368.7  400.44  5390.2  400.57  5411.2  403.32  5446.9  404.91  5453.7  407.09
  5475.2  407.83  5496.2  411.31  5609.5  419.19  5616.4  421.12  5712.4  423.31
#Mann=7,-1,0
  4726.6    0.16       0  4813.7    0.12       0  4837.2    0.16       0
  4927.0   0.033       0  4933.0    0.16       0  4952.8    0.05       0
  5055.3    0.16       0
Bank Sta=4927,4933
Exp/Cntr=0.3,0.1

Type RM Length L Ch R = 1,5780,456,456,456
BEGIN DESCRIPTION:
UNT 074 IN CACR 12.0
END DESCRIPTION:
XS GIS Cut Line= 2
      3709902.20     10742737.65      3710188.64     10743670.77
#Sta/Elev= 30
  4687.6  402.26  4711.2  401.13  4753.0  396.63  4761.1  394.76  4793.8  390.45
  4799.1  388.97  4805.3  385.66  4826.2  381.32  4844.2  374.57  4846.9  374.07
  4850.2  374.57  4862.2  374.57  5079.0  374.57  5119.1  374.57  5150.5  380.56
  5181.9  384.46  5192.4  386.92  5207.5  387.75  5213.3  389.75  5258.2  393.19
  5278.2  393.37  5328.4  395.93  5338.4  394.89  5349.3  395.80  5370.2  395.19
  5474.6  398.43  5517.8  401.29  5550.5  402.45  5600.3  406.25  5663.7  409.23
#Mann=6,-1,0
  4687.6    0.12       0  4844.2   0.033       0  4850.2    0.12       0
  4862.2    0.05       0  5079.0    0.16       0  5258.2    0.05       0
Bank Sta=4844.2,4850.2
Exp/Cntr=0.3,0.1

Type RM Length L Ch R = 1,5324,584,584,584
BEGIN DESCRIPTION:
UNT 074 IN CACR 11.0
END DESCRIPTION:
XS GIS Cut Line= 2
      3709489.86     10742807.06      3709637.43     10743610.01
#Sta/Elev= 30
  4648.9  400.10  4676.3  399.64  4692.7  398.71  4713.1  397.47  4723.3  395.60
  4734.5  394.99  4774.1  387.74  4782.5  385.10  4787.6  384.92  4804.6  380.18
  4835.1  377.18  4837.7  374.57  4840.4  374.07  4843.7  374.57  4866.2  374.57
  5144.3  374.57  5160.5  374.57  5169.3  377.11  5221.5  381.76  5232.6  384.28
  5267.7  387.62  5292.6  388.89  5338.7  388.70  5343.8  389.66  5391.8  389.84
  5396.9  391.23  5424.8  391.62  5450.0  393.46  5455.3  394.59  5465.3  394.81
#Mann=6,-1,0
  4648.9    0.16       0  4837.7   0.033       0  4843.7    0.16       0
  4866.2    0.05       0  5144.3    0.16       0  5267.7    0.05       0
Bank Sta=4837.7,4843.7
Exp/Cntr=0.3,0.1

Type RM Length L Ch R = 1,4740,53,53,53
BEGIN DESCRIPTION:
UNT 074 IN CACR 10.0
END DESCRIPTION:
XS GIS Cut Line= 2
      3709137.81     10742735.26      3708874.45     10743504.74
#Sta/Elev= 30
  4549.9  394.89  4586.1  393.52  4597.4  392.40  4617.4  392.08  4629.1  390.71
  4692.5  385.91  4711.3  383.46  4716.6  383.44  4724.2  381.29  4734.8  380.77
  4742.6  379.15  4766.5  376.83  4770.9  374.57  4773.6  374.07  4776.9  374.57
  5166.7  374.57  5189.3  374.57  5199.9  377.18  5212.0  377.72  5243.3  377.14
  5263.3  378.28  5269.3  379.90  5305.9  381.67  5316.1  383.75  5326.6  391.26
  5331.9  391.71  5337.3  394.88  5347.8  397.64  5357.9  398.56  5363.2  399.98
#Mann=4,-1,0
  4549.9    0.16       0  4770.9    0.07       0  4776.9    0.16       0
  5166.7    0.05       0
Bank Sta=4770.9,4776.9
Exp/Cntr=0.3,0.1

Type RM Length L Ch R = 1,4687,72,72,72
BEGIN DESCRIPTION:
Mapping XS bf3455d0
END DESCRIPTION:
XS GIS Cut Line= 3
      3709098.75     10742735.26      3708950.37     10743117.16
      3708826.91     10743492.78
#Sta/Elev= 30
  4567.0  393.48  4625.9  391.00  4637.8  388.62  4647.4  388.16  4686.9  383.49
  4733.2  380.74  4754.7  380.23  4825.7  379.26  4862.0  380.00  5011.5  380.00
  5022.0  379.84  5027.2  378.68  5032.5  379.92  5090.8  379.47  5156.3  380.05
  5186.2  379.11  5201.0  379.34  5218.0  376.87  5220.3  375.66  5223.1  375.16
  5226.3  375.66  5255.1  376.73  5274.6  378.39  5281.7  379.79  5313.5  382.01
  5318.7  386.03  5327.3  387.68  5350.5  398.39  5358.8  399.76  5372.1  400.69
#Mann=4,-1,0
  4567.0    0.16       0  5156.3    0.05       0  5220.3    0.07       0
  5226.3    0.05       0
Bank Sta=5220.3,5226.3
Exp/Cntr=0.3,0.1

Type RM Length L Ch R = 1,4615,559,559,559
BEGIN DESCRIPTION:
Mapping XS 026f0738
END DESCRIPTION:
XS GIS Cut Line= 2
      3709045.81     10742694.43      3708741.99     10743445.29
#Sta/Elev= 30
  4551.6  393.20  4644.1  387.26  4708.8  378.13  4821.8  367.54  4827.5  364.88
  4838.3  366.40  4875.4  362.81  4899.5  362.55  4935.4  358.52  4953.1  359.86
  4958.5  357.34  4977.3  359.73  4986.3  355.19  4989.1  354.69  4992.3  355.19
  5006.8  359.75  5012.2  358.08  5030.9  360.37  5054.0  358.95  5089.9  365.79
  5138.9  369.82  5161.9  372.40  5173.0  376.64  5191.8  377.13  5205.1  373.09
  5274.9  377.06  5299.0  387.43  5304.4  387.89  5312.9  392.70  5361.6  400.00
#Mann=4,-1,0
  4551.6    0.16       0  4986.3    0.07       0  4992.3    0.16       0
  5138.9    0.05       0
Bank Sta=4986.3,4992.3
Exp/Cntr=0.3,0.1

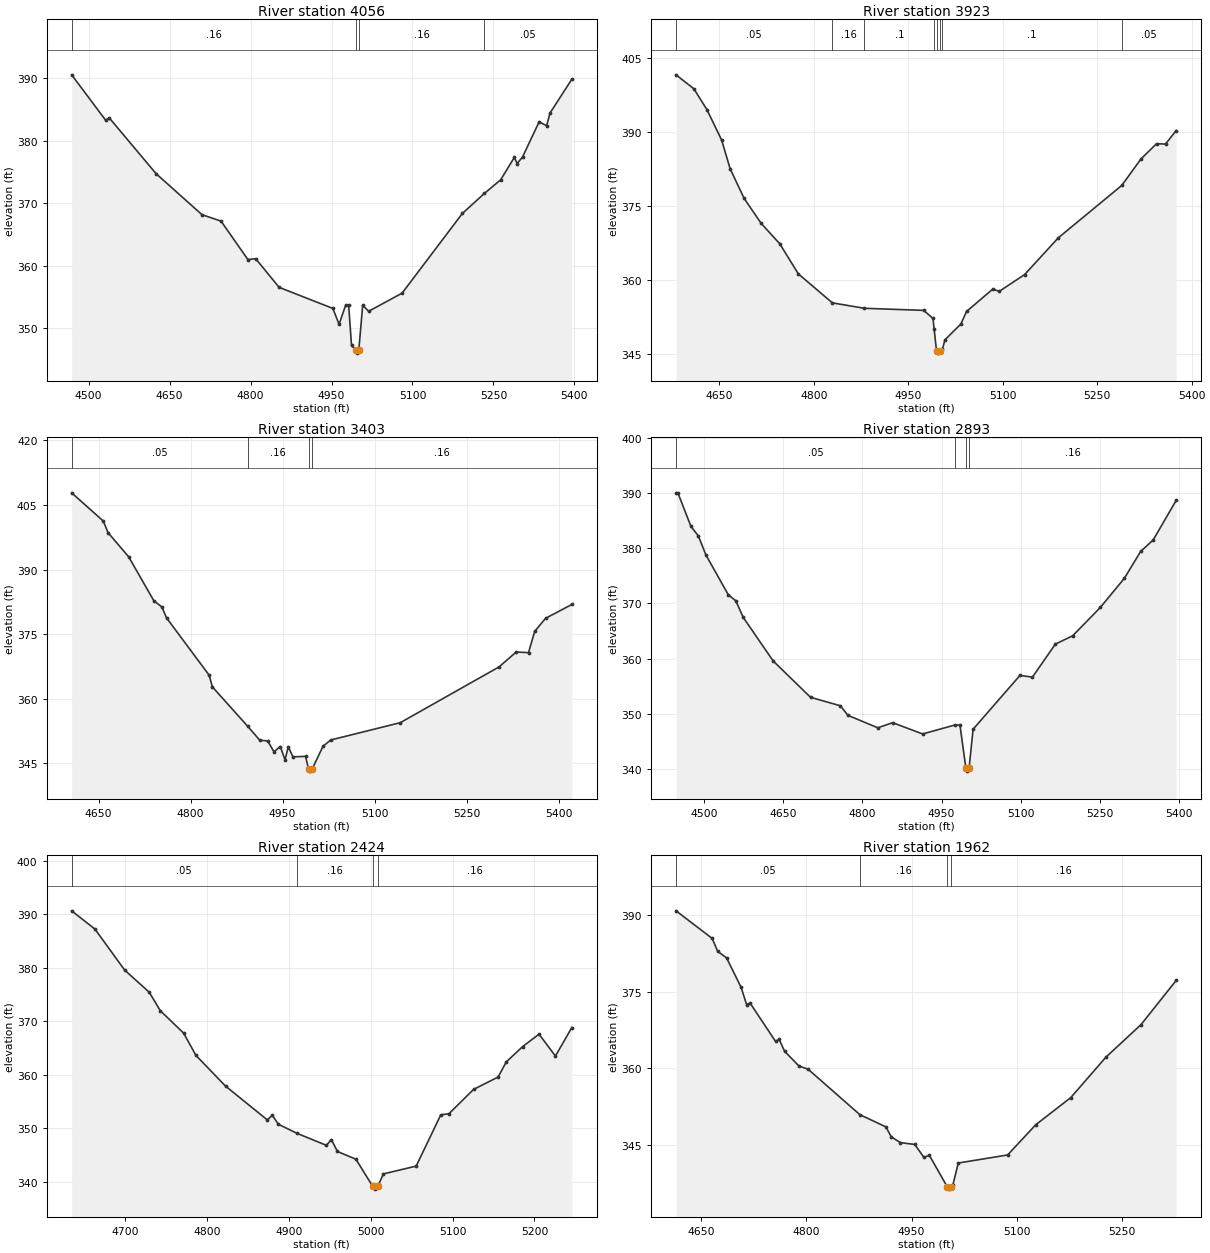
Type RM Length L Ch R = 1,4056,133,133,133
BEGIN DESCRIPTION:
UNT 074 IN CACR 9.0
END DESCRIPTION:
XS GIS Cut Line= 4
      3708873.03     10742505.24      3708479.32     10742811.53
      3708453.28     10742887.48      3708512.81     10743230.04
#Sta/Elev= 30
  4468.5  390.58  4531.7  383.27  4538.0  383.69  4624.9  374.73  4710.0  368.15
  4745.3  367.12  4795.0  360.96  4809.5  361.09  4852.9  356.50  4952.5  353.12
  4964.0  350.56  4976.5  353.71  4981.8  353.60  4987.1  347.19  4994.6  346.45
  4997.4  345.95  5000.6  346.45  5007.8  353.65  5018.8  352.66  5080.8  355.57
  5192.5  368.35  5233.3  371.56  5263.5  373.75  5288.9  377.35  5294.0  376.35
  5304.1  377.42  5334.6  383.02  5348.6  382.43  5354.9  384.45  5395.3  389.87
#Mann=4,-1,0
  4468.5    0.16       0  4994.6    0.07       0  5000.6    0.16       0
  5233.3    0.05       0
Bank Sta=4994.6,5000.6
Exp/Cntr=0.3,0.1

Type RM Length L Ch R = 1,3923,520,520,520
BEGIN DESCRIPTION:
UNT 074 IN CACR 8.0
END DESCRIPTION:
XS GIS Cut Line= 3
      3708099.61     10742510.19      3708349.61     10742860.19
      3708449.60     10743210.17
#Sta/Elev= 30
  4581.3  401.61  4609.6  398.79  4630.5  394.53  4653.8  388.36  4667.3  382.54
  4689.4  376.57  4716.5  371.49  4746.0  367.36  4775.5  361.25  4829.6  355.37
  4880.5  354.27  4974.5  353.85  4989.3  352.22  4991.2  350.00  4994.9  345.68
  4997.6  345.18  5000.9  345.68  5004.4  346.01  5008.3  347.88  5033.5  351.07
  5042.6  353.63  5084.2  358.16  5094.6  357.71  5134.9  361.12  5188.2  368.55
  5289.1  379.19  5319.5  384.55  5344.2  387.64  5358.5  387.57  5375.4  390.32
#Mann=8,-1,0
  4581.3    0.05       0  4829.6    0.16       0  4880.5     0.1       0
  4991.2    0.16       0  4994.9    0.07       0  5000.9    0.16       0
  5004.4     0.1       0  5289.1    0.05       0
Bank Sta=4994.9,5000.9
Exp/Cntr=0.3,0.1

Type RM Length L Ch R = 1,3403,510,510,510
BEGIN DESCRIPTION:
UNT 074 IN CACR 7.0
END DESCRIPTION:
XS GIS Cut Line= 3
      3707949.62     10742460.15      3707849.61     10742860.19
      3707799.60     10743260.22
#Sta/Elev= 30
  4606.2  407.84  4657.8  401.28  4665.5  398.59  4699.0  393.01  4740.2  382.77
  4753.1  381.37  4760.9  378.80  4830.4  365.49  4835.6  362.79  4893.1  353.65
  4912.9  350.40  4925.8  350.23  4936.1  347.71  4946.4  348.93  4954.1  345.81
  4959.3  348.89  4967.0  346.54  4987.6  346.64  4992.4  343.72  4995.1  343.22
  4998.4  343.72  5016.0  349.00  5028.6  350.45  5142.0  354.47  5303.3  367.44
  5331.0  370.88  5351.1  370.73  5361.2  375.68  5378.8  378.69  5421.7  381.92
#Mann=4,-1,0
  4606.2    0.05       0  4893.1    0.16       0  4992.4    0.07       0
  4998.4    0.16       0
Bank Sta=4992.4,4998.4
Exp/Cntr=0.3,0.1

Type RM Length L Ch R = 1,2893,469,469,469
BEGIN DESCRIPTION:
UNT 074 IN CACR 6.0
END DESCRIPTION:
XS GIS Cut Line= 3
      3707049.60     10742660.18      3707449.61     10743060.19
      3707599.62     10743410.21
#Sta/Elev= 30
  4447.5  390.00  4451.0  390.00  4475.8  383.92  4489.9  382.19  4504.1  378.76
  4546.5  371.56  4560.6  370.48  4574.8  367.46  4631.4  359.59  4702.1  353.02
  4758.6  351.49  4772.8  349.76  4829.3  347.51  4857.6  348.43  4914.2  346.39
  4975.5  348.02  4984.9  347.99  4996.1  340.17  4998.8  339.67  5002.1  340.17
  5009.7  347.24  5098.4  356.98  5122.0  356.67  5165.5  362.65  5198.1  364.14
  5250.7  369.29  5296.1  374.56  5326.9  379.41  5350.5  381.47  5394.0  388.63
#Mann=4,-1,0
  4447.5    0.05       0  4975.5    0.16       0  4996.1    0.07       0
  5002.1    0.16       0
Bank Sta=4996.1,5002.1
Exp/Cntr=0.3,0.1

Type RM Length L Ch R = 1,2424,462,462,462
BEGIN DESCRIPTION:
UNT 074 IN CACR 5.0
END DESCRIPTION:
XS GIS Cut Line= 3
      3706799.61     10742810.19      3706999.61     10743110.19
      3706999.61     10743360.23
#Sta/Elev= 30
  4635.0  390.65  4663.5  387.22  4699.6  379.58  4729.6  375.44  4743.2  371.97
  4771.7  367.77  4786.7  363.61  4822.8  357.87  4873.9  351.53  4879.9  352.41
  4887.4  350.72  4909.9  349.04  4946.0  346.78  4952.0  347.86  4959.5  345.63
  4982.0  344.19  5002.6  339.09  5005.3  338.59  5008.6  339.09  5015.6  341.44
  5055.6  342.90  5085.6  352.48  5095.6  352.70  5125.6  357.24  5155.6  359.56
  5165.6  362.39  5185.6  365.26  5205.6  367.58  5225.6  363.48  5245.6  368.82
#Mann=4,-1,0
  4635.0    0.05       0  4909.9    0.16       0  5002.6    0.07       0
  5008.6    0.16       0
Bank Sta=5002.6,5008.6
Exp/Cntr=0.3,0.1

Type RM Length L Ch R = 1,1962,537,537,537
BEGIN DESCRIPTION:
UNT 074 IN CACR 4.0
END DESCRIPTION:
XS GIS Cut Line= 3
      3706699.61     10742810.20      3706599.61     10743210.19
      3706599.61     10743510.19
#Sta/Elev= 30
  4614.6  390.81  4666.1  385.41  4673.9  382.89  4686.7  381.58  4707.4  375.81
  4715.1  372.46  4720.2  372.73  4756.3  365.26  4761.5  365.64  4769.2  363.32
  4789.8  360.42  4802.7  359.81  4876.4  350.91  4913.5  348.52  4921.2  346.56
  4934.1  345.44  4954.7  345.07  4967.6  342.55  4975.4  342.95  5000.7  336.83
  5003.5  336.33  5006.7  336.83  5008.9  337.13  5016.6  341.44  5086.9  343.02
  5126.9  348.93  5176.9  354.26  5226.9  362.17  5276.9  368.54  5326.9  377.18
#Mann=4,-1,0
  4614.6    0.05       0  4876.4    0.16       0  5000.7    0.07       0
  5006.7    0.16       0
Bank Sta=5000.7,5006.7
Exp/Cntr=0.3,0.1

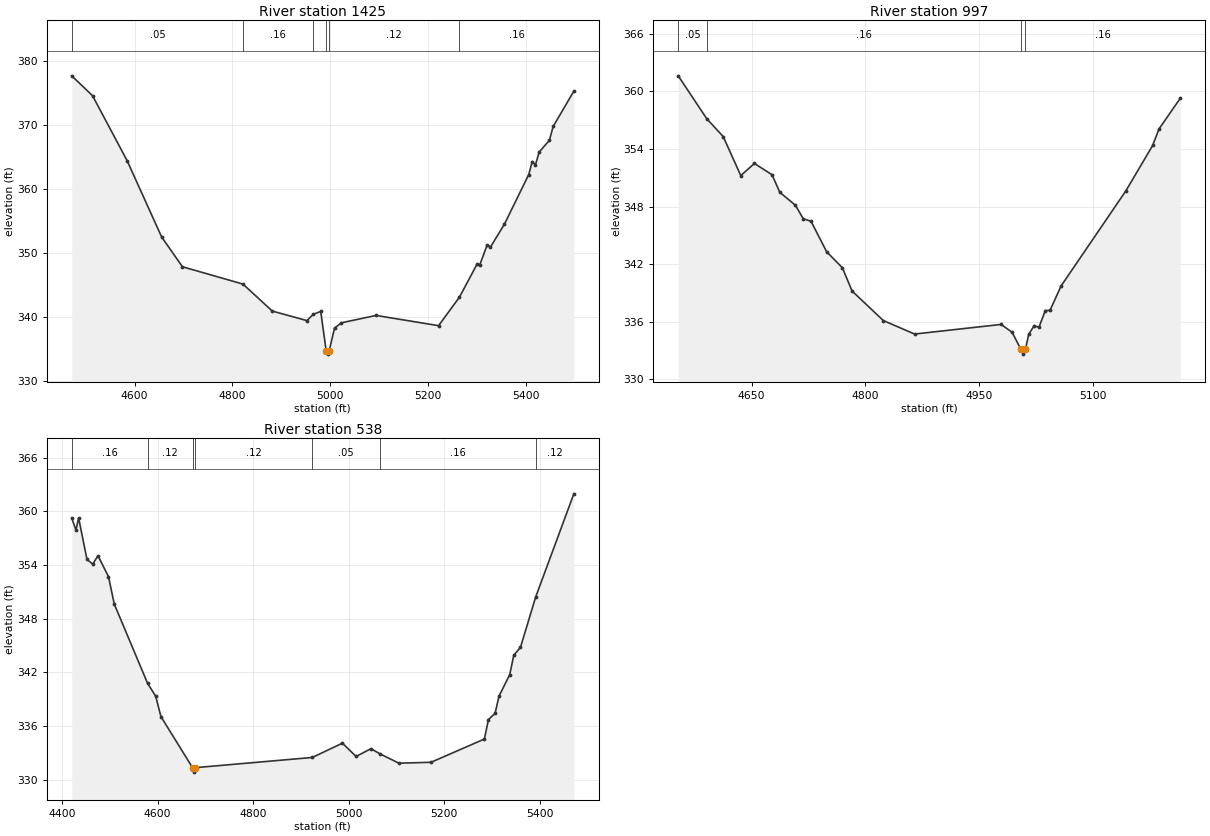
Type RM Length L Ch R = 1,1425,428,428,428
BEGIN DESCRIPTION:
UNT 074 IN CACR 3.0
END DESCRIPTION:
XS GIS Cut Line= 3
      3705749.61     10742810.19      3706149.61     10743210.19
      3706449.64     10743560.22
#Sta/Elev= 30
  4471.6  377.73  4514.0  374.63  4584.7  364.48  4655.4  352.53  4697.9  347.88
  4821.7  345.17  4881.7  340.95  4952.4  339.46  4965.6  340.45  4980.7  340.89
  4991.9  334.72  4994.6  334.22  4997.9  334.72  5009.0  338.30  5023.1  339.12
  5093.8  340.27  5221.7  338.67  5264.4  343.13  5300.1  348.25  5306.2  348.22
  5321.0  351.29  5327.6  350.94  5356.1  354.50  5406.1  362.30  5413.2  364.32
  5419.8  363.81  5427.5  365.83  5448.3  367.64  5456.0  369.81  5498.3  375.34
#Mann=6,-1,0
  4471.6    0.05       0  4821.7    0.16       0  4965.6    0.12       0
  4991.9    0.07       0  4997.9    0.12       0  5264.4    0.16       0
Bank Sta=4991.9,4997.9
Exp/Cntr=0.3,0.1

Type RM Length L Ch R = 1,997,459,459,459
BEGIN DESCRIPTION:
UNT 074 IN CACR 2.0
END DESCRIPTION:
XS GIS Cut Line= 3
      3705699.61     10743010.20      3705799.61     10743410.19
      3705949.61     10743610.19
#Sta/Elev= 30
  4553.3  361.60  4590.9  357.14  4612.6  355.28  4635.8  351.22  4653.8  352.48
  4677.0  351.31  4687.3  349.48  4707.9  348.13  4718.2  346.73  4728.5  346.46
  4749.1  343.29  4769.8  341.63  4782.6  339.21  4823.9  336.13  4865.1  334.73
  4979.1  335.73  4993.7  334.92  5005.3  333.14  5008.1  332.64  5011.3  333.14
  5015.6  334.70  5022.9  335.61  5029.1  335.43  5037.5  337.17  5043.7  337.19
  5058.3  339.73  5143.7  349.62  5179.1  354.35  5187.5  356.07  5215.6  359.27
#Mann=4,-1,0
  4553.3    0.05       0  4590.9    0.16       0  5005.3    0.07       0
  5011.3    0.16       0
Bank Sta=5005.3,5011.3
Exp/Cntr=0.3,0.1

Type RM Length L Ch R = 1,538,0,0,0
BEGIN DESCRIPTION:
UNT 074 IN CACR 1.0
END DESCRIPTION:
XS GIS Cut Line= 3
      3705649.61     10743060.19      3705399.61     10743610.19
      3705799.64     10743810.20
#Sta/Elev= 30
  4420.4  359.24  4429.2  357.91  4434.7  359.27  4452.3  354.62  4464.3  354.10
  4475.3  355.04  4497.3  352.70  4509.4  349.63  4579.1  340.78  4596.2  339.32
  4607.1  337.05  4673.3  331.34  4676.1  330.84  4679.3  331.34  4924.1  332.48
  4987.2  334.08  5015.8  332.59  5046.9  333.46  5066.3  332.87  5105.6  331.84
  5172.7  331.94  5284.5  334.54  5292.9  336.71  5306.9  337.42  5315.2  339.35
  5337.6  341.75  5346.0  343.91  5360.0  344.79  5392.0  350.44  5471.8  361.96
#Mann=7,-1,0
  4420.4    0.16       0  4579.1    0.12       0  4673.3    0.04       0
  4679.3    0.12       0  4924.1    0.05       0  5066.3    0.16       0
  5392.0    0.12       0
Bank Sta=4673.3,4679.3
Exp/Cntr=0.3,0.1

Chan Stop Cuts=-1