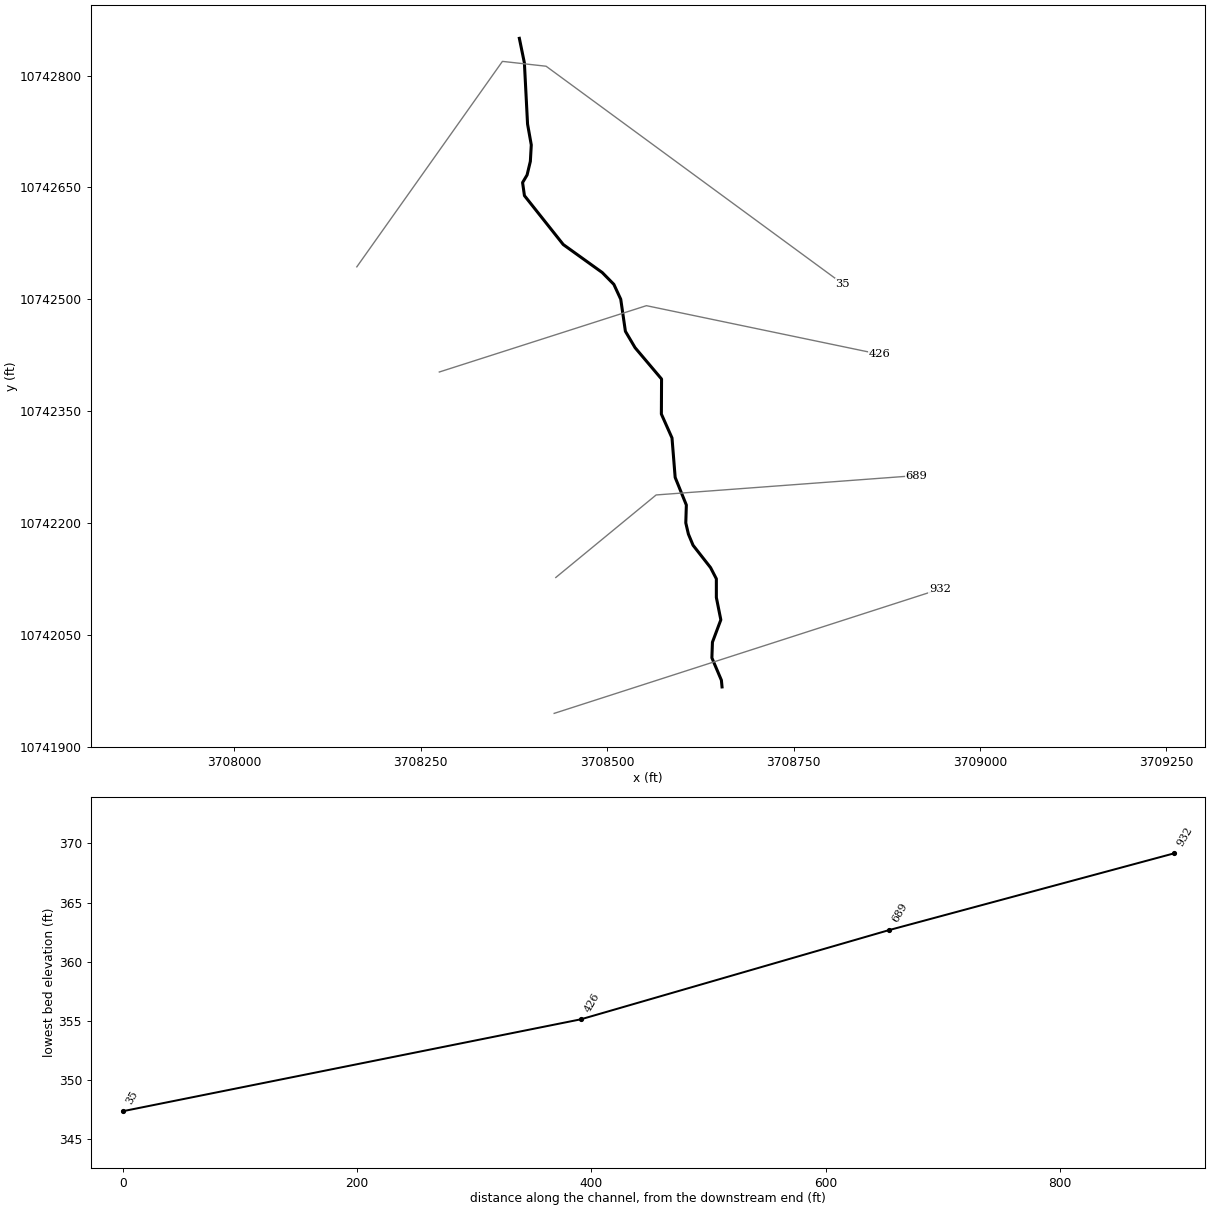
--- UNT 075 IN CACR.prj (project) ---

Proj Title=UNT 075 IN CACR Base Level Engineering
Current Plan=p01
Default Exp/Contr=0.3,0.1
English Units
Geom File=g01
Flow File=f01
Plan File=p01
Y Axis Title=Elevation
X Axis Title(PF)=Main Channel Distance
X Axis Title(XS)=Station
BEGIN DESCRIPTION:
UNT 075 IN CACR
END DESCRIPTION:
DSS Export Rating Curves= 0
DSS Export Rating Curve Sorted= 0
DSS Export Volume Flow Curves= 0
DXF OffsetX= 0
DXF OffsetY= 0
DXF ScaleX= 1
DXF ScaleY= 10

--- UNT 075 IN CACR.p01 (plan) ---

Plan Title=Multiple Run
Short Identifier=Multiple
Geom File=g01
Flow File=f01
Subcritical Flow
K Sum by GR= 0
Std Step Tol= 0.01
Critical Tol= 0.01
Num of Std Step Trials= 20
Max Error Tol= 0.3
Flow Tol Ratio= 0.001
Split Flow NTrial= 30
Split Flow Tol= 0.02
Split Flow Ratio= 0.02
Log Output Level= 0
Friction Slope Method= 1
Unsteady Friction Slope Method= 2
Unsteady Bridges Friction Slope Method= 1
Parabolic Critical Depth
Global Vel Dist=  1 , 1 , 1
Global Log Level= 0
CheckData=True
Encroach Param= -1, 0, 0, 0
BEGIN DESCRIPTION:
Multiple Run
END DESCRIPTION:

--- UNT 075 IN CACR.f01 (steady flow) ---

Flow Title=Multiple
Program Version=4.10
Number of Profiles= 7
Profile Names=10-year,25-year,50-year,1pct_min,100-year,1pct_plu,500-year
River Rch & RM=UNT 075 IN CACR,Reach-1         ,932
     209     266     311     268     363     491     492
River Rch & RM=UNT 075 IN CACR,Reach-1         ,35
     714     972    1186    1061    1435    1940    2103
Boundary for River Rch & Prof#=UNT 075 IN CACR,Reach-1         , 1
Up Type= 0
Dn Type= 3
Dn Slope=0.01987
Boundary for River Rch & Prof#=UNT 075 IN CACR,Reach-1         , 2
Up Type= 0
Dn Type= 3
Dn Slope=0.01987
Boundary for River Rch & Prof#=UNT 075 IN CACR,Reach-1         , 3
Up Type= 0
Dn Type= 3
Dn Slope=0.01987
Boundary for River Rch & Prof#=UNT 075 IN CACR,Reach-1         , 4
Up Type= 0
Dn Type= 3
Dn Slope=0.01987
Boundary for River Rch & Prof#=UNT 075 IN CACR,Reach-1         , 5
Up Type= 0
Dn Type= 3
Dn Slope=0.01987
Boundary for River Rch & Prof#=UNT 075 IN CACR,Reach-1         , 6
Up Type= 0
Dn Type= 3
Dn Slope=0.01987
Boundary for River Rch & Prof#=UNT 075 IN CACR,Reach-1         , 7
Up Type= 0
Dn Type= 3
Dn Slope=0.01987
DSS Import GetInterval= 0
DSS Import GetPeak= 0
DSS Import FillOption= 0

--- UNT 075 IN CACR.g01 (geometry) ---

Geom Title=Existing Conditions
Program Version=4.10

River Reach=UNT 075 IN CACR ,Reach-1
Reach XY= 30
      3708654.12     10741979.99      3708653.25       10741989.
       3708640.5       10742019.      3708641.25       10742040.
       3708652.5       10742070.       3708646.5       10742100.
       3708646.5       10742125.      3708638.75       10742140.
      3708615.25       10742170.        3708609.       10742185.
       3708605.5       10742200.      3708606.25       10742224.
      3708591.25       10742261.        3708587.       10742314.
      3708572.75       10742346.        3708573.       10742393.
       3708537.5       10742435.       3708524.5       10742457.
      3708518.25       10742500.        3708509.       10742520.
       3708493.4     10742535.87      3708441.16     10742573.37
      3708389.07     10742638.99      3708386.57     10742656.52
      3708392.62     10742666.73        3708397.       10742685.
      3708398.25       10742707.      3708393.25       10742735.
        3708389.       10742817.      3708382.25       10742850.

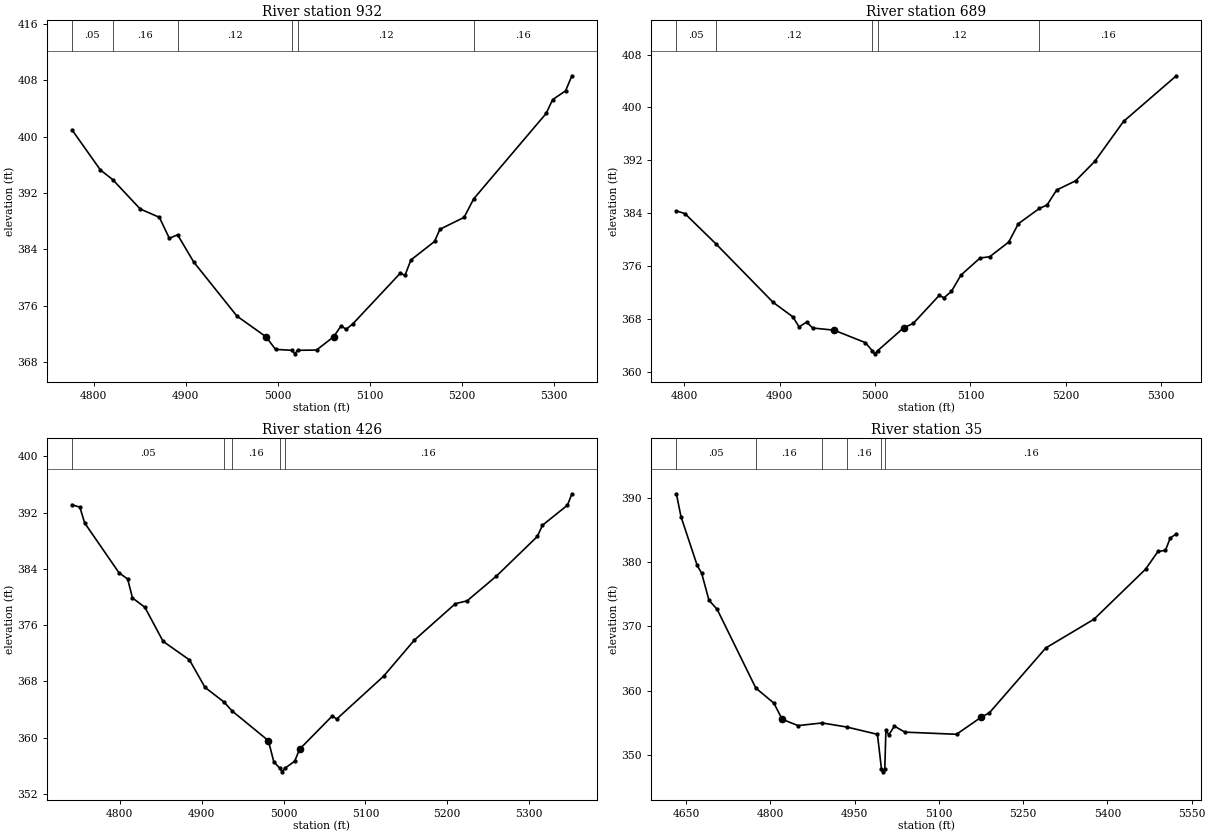
Type RM Length L Ch R = 1 ,932     ,243,243,243
BEGIN DESCRIPTION:
UNT 075 IN CACR 2.0
END DESCRIPTION:
XS GIS Cut Line= 2
      3708428.95     10741944.51      3708946.17     10742111.15
#Sta/Elev= 30
  4776.3  400.96  4807.2  395.26  4820.5   393.9  4850.5  389.72  4871.3  388.54
  4882.1  385.56  4891.1  386.06  4908.6   382.2  4955.6  374.52  4987.1  371.59
  4997.6  369.79  5015.6  369.66  5018.4  369.16  5021.6  369.66  5042.1   369.7
  5060.7  371.58    5069  373.16  5074.2  372.63  5081.7  373.43  5133.1   380.6
  5138.3  380.31  5144.7  382.48  5170.4  385.11  5176.2  386.84  5202.5  388.53
    5213  391.17  5291.8   403.3  5298.7  405.24  5312.8  406.49  5319.7  408.63
#Mann= 6 ,-1 , 0
  4776.3     .05       0  4820.5     .16       0  4891.1     .12       0
  5015.6     .07       0  5021.6     .12       0    5213     .16       0
Bank Sta=4987.1,5060.7
XS Rating Curve= 0 ,0
Exp/Cntr=0.3,0.1

Type RM Length L Ch R = 1 ,689     ,263,263,263
BEGIN DESCRIPTION:
Mapping XS a883b031
END DESCRIPTION:
XS GIS Cut Line= 3
      3708431.13     10742126.79      3708565.71     10742237.49
      3708914.88     10742263.51
#Sta/Elev= 30
  4791.6  384.33  4800.5  383.93  4833.5  379.28    4893  370.49  4913.8  368.28
  4920.3  366.76  4928.2  367.49  4934.6  366.59  4956.9  366.27  4989.8  364.38
  4996.9  363.18  4999.6  362.68  5002.9  363.18  5029.9  366.61    5040  367.28
  5067.2  371.52  5072.3  371.18  5080.1  372.14  5090.1  374.61  5110.2   377.2
  5120.2  377.38  5140.2  379.61  5150.3  382.39  5172.4  384.71  5180.4  385.22
  5190.4  387.49  5210.4  388.89  5230.5  391.84  5260.6  397.88    5316   404.8
#Mann= 5 ,-1 , 0
  4791.6     .05       0  4833.5     .12       0  4996.9     .07       0
  5002.9     .12       0  5172.4     .16       0
Bank Sta=4956.9,5029.9
XS Rating Curve= 0 ,0
Exp/Cntr=0.3,0.1

Type RM Length L Ch R = 1 ,426     ,391,391,391
BEGIN DESCRIPTION:
Mapping XS 7bc99964
END DESCRIPTION:
XS GIS Cut Line= 3
      3708274.89     10742402.42      3708552.68      10742491.4
      3708864.89     10742426.35
#Sta/Elev= 30
  4741.6  393.13  4751.2  392.79  4757.1  390.54  4799.1  383.44  4809.6  382.57
  4815.5  379.87  4830.6  378.55  4852.9   373.7  4885.1  371.06  4904.1  367.15
  4927.2  365.08  4937.2   363.8  4981.5  359.57  4988.1  356.57  4995.6  355.64
  4998.3  355.14  5001.6  355.64  5013.6  356.65  5019.6  358.36  5059.7  363.11
  5064.8  362.64  5122.1  368.73  5159.8  373.88  5209.9  379.06  5224.2  379.46
  5259.9  382.97    5310  388.62  5316.2  390.21  5346.8  393.07  5352.2  394.69
#Mann= 5 ,-1 , 0
  4741.6     .05       0  4927.2     .12       0  4937.2     .16       0
  4995.6     .07       0  5001.6     .16       0
Bank Sta=4981.5,5019.6
XS Rating Curve= 0 ,0
Exp/Cntr=0.3,0.1

Type RM Length L Ch R = 1 ,35      ,0,0,0
BEGIN DESCRIPTION:
UNT 075 IN CACR 1.0
END DESCRIPTION:
XS GIS Cut Line= 4
      3708164.23     10742543.48      3708359.54     10742819.09
      3708418.14     10742812.58      3708815.99     10742520.68
#Sta/Elev= 30
  4632.5   390.6  4640.7  387.04  4669.6  379.45  4677.5  378.24  4690.5  374.05
  4705.2  372.62  4773.9   360.4  4806.1  358.05  4820.9  355.54  4849.1  354.56
  4892.1  354.97  4936.3  354.33  4990.5   353.2  4997.6  347.87  5000.3  347.37
  5003.6  347.87  5005.6  353.94  5010.6  353.11  5020.7  354.47  5039.5  353.54
  5131.4  353.21  5175.3  355.87    5190  356.56  5290.3  366.63    5376  371.09
  5467.9  378.87    5490  381.63  5503.4  381.81  5511.8  383.71  5522.7  384.37
#Mann= 6 ,-1 , 0
  4632.5     .05       0  4773.9     .16       0  4892.1      .1       0
  4936.3     .16       0  4997.6     .07       0  5003.6     .16       0
Bank Sta=4820.9,5175.3
XS Rating Curve= 0 ,0
Exp/Cntr=0.3,0.1

Chan Stop Cuts=-1
Use User Specified Reach Order=0
Composite Channel Slope=5