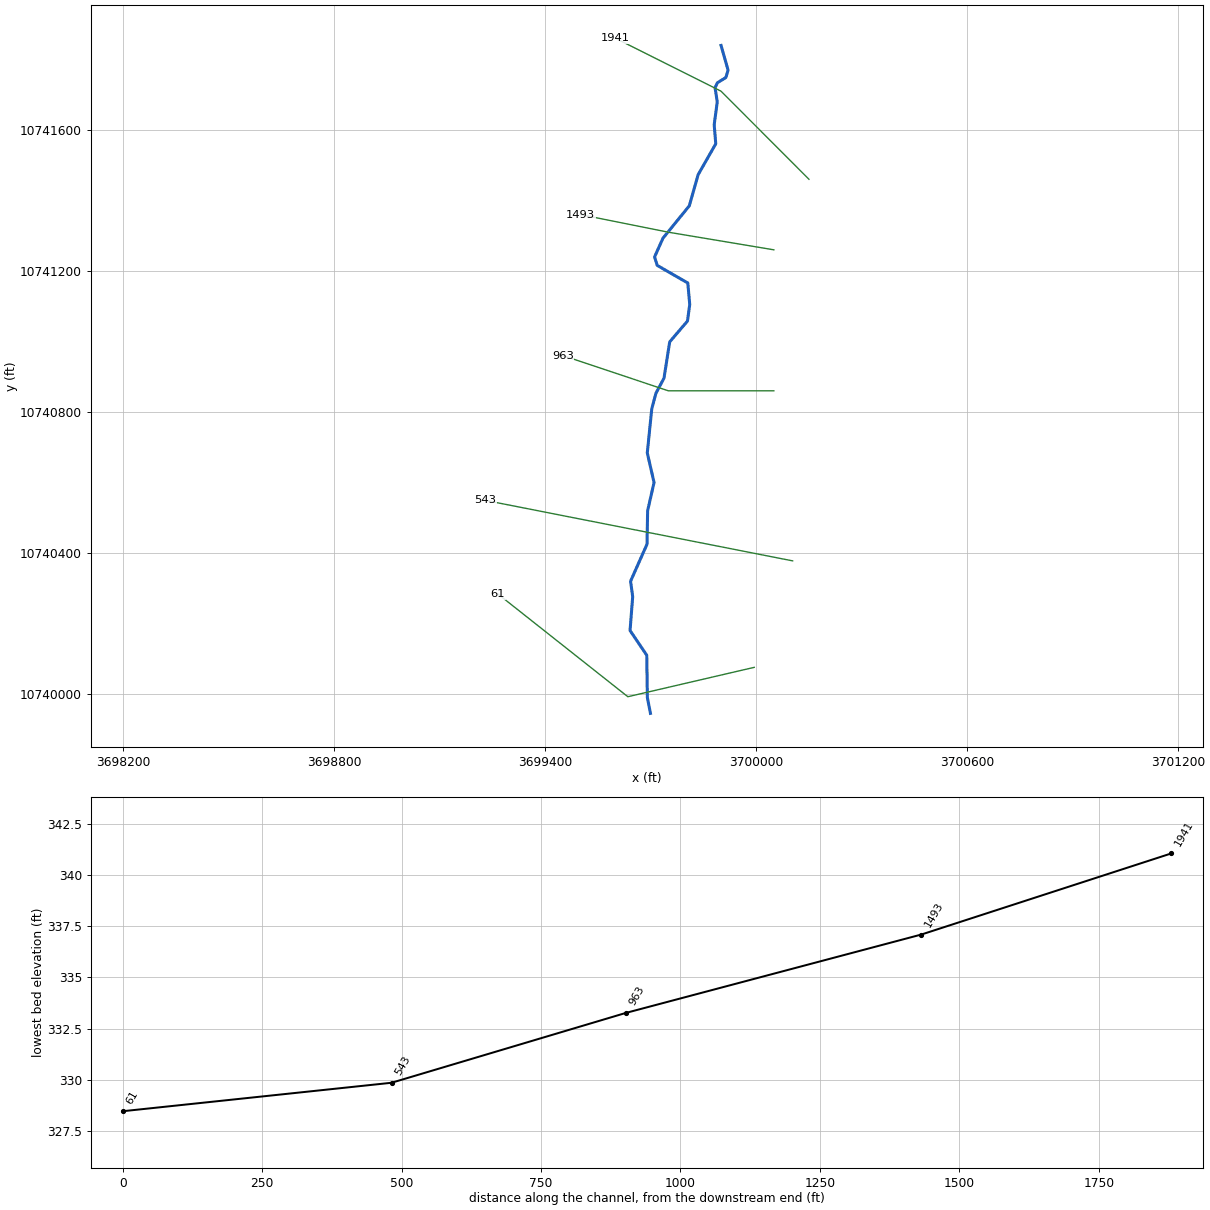
--- UNT 077 IN CACR.prj (project) ---

Proj Title=UNT 077 IN CACR Base Level Engineering
Current Plan=p01
Default Exp/Contr=0.3,0.1
English Units
Geom File=g01
Flow File=f01
Plan File=p01
BEGIN DESCRIPTION:
UNT 077 IN CACR
END DESCRIPTION:

--- UNT 077 IN CACR.p01 (plan) ---

Plan Title=Multiple Run
Short Identifier=Multiple
Geom File=g01
Flow File=f01
Subcritical Flow
K Sum by GR= 0
Std Step Tol= 0.01
Critical Tol= 0.01
Num of Std Step Trials= 20
Max Error Tol= 0.3
Flow Tol Ratio= 0.001
Split Flow NTrial= 30
Split Flow Tol= 0.02
Split Flow Ratio= 0.02
Log Output Level= 0
Friction Slope Method= 1
Unsteady Friction Slope Method= 2
Unsteady Bridges Friction Slope Method= 1
Parabolic Critical Depth
Global Vel Dist=  1 , 1 , 1
Global Log Level= 0
CheckData=True
Encroach Param= -1, 0, 0, 0
BEGIN DESCRIPTION:
Multiple Run
END DESCRIPTION:

--- UNT 077 IN CACR.f01 (steady flow) ---

Flow Title=Multiple
Number of Profiles=7
Profile Names=10-year,25-year,50-year,1pct_min,100-year,1pct_plu,500-year
River Rch & RM= UNT 077 IN CACR,Reach-1,1941
     441     586     702     619     836    1131    1189
Boundary for River Rch & Prof#=UNT 077 IN CACR,Reach-1,1
Up Type=0
Dn Type=3
Dn Slope=0.005
Boundary for River Rch & Prof#=UNT 077 IN CACR,Reach-1,2
Up Type=0
Dn Type=3
Dn Slope=0.005
Boundary for River Rch & Prof#=UNT 077 IN CACR,Reach-1,3
Up Type=0
Dn Type=3
Dn Slope=0.005
Boundary for River Rch & Prof#=UNT 077 IN CACR,Reach-1,4
Up Type=0
Dn Type=3
Dn Slope=0.005
Boundary for River Rch & Prof#=UNT 077 IN CACR,Reach-1,5
Up Type=0
Dn Type=3
Dn Slope=0.005
Boundary for River Rch & Prof#=UNT 077 IN CACR,Reach-1,6
Up Type=0
Dn Type=3
Dn Slope=0.005
Boundary for River Rch & Prof#=UNT 077 IN CACR,Reach-1,7
Up Type=0
Dn Type=3
Dn Slope=0.005

--- UNT 077 IN CACR.g01 (geometry) ---

Geom Title=Existing Conditions

River Reach=UNT 077 IN CACR,Reach-1
Reach XY= 30
      3699899.50     10741840.00      3699919.50     10741770.00
      3699913.25     10741749.00      3699889.00     10741734.00
      3699882.50     10741720.00      3699888.75     10741680.00
      3699880.00     10741615.00      3699884.50     10741561.00
      3699834.25     10741473.00      3699809.25     10741385.00
      3699734.25     10741293.00      3699710.50     10741240.00
      3699718.00     10741216.00      3699805.00     10741166.00
      3699810.50     10741105.00      3699804.00     10741058.00
      3699753.50     10740999.00      3699737.25     10740896.00
      3699714.25     10740853.00      3699702.50     10740809.00
      3699689.75     10740684.00      3699709.00     10740600.00
      3699690.75     10740520.00      3699689.00     10740425.00
      3699642.25     10740320.00      3699648.25     10740276.00
      3699640.75     10740180.00      3699688.25     10740110.00
      3699690.00     10739990.00      3699698.75     10739945.00

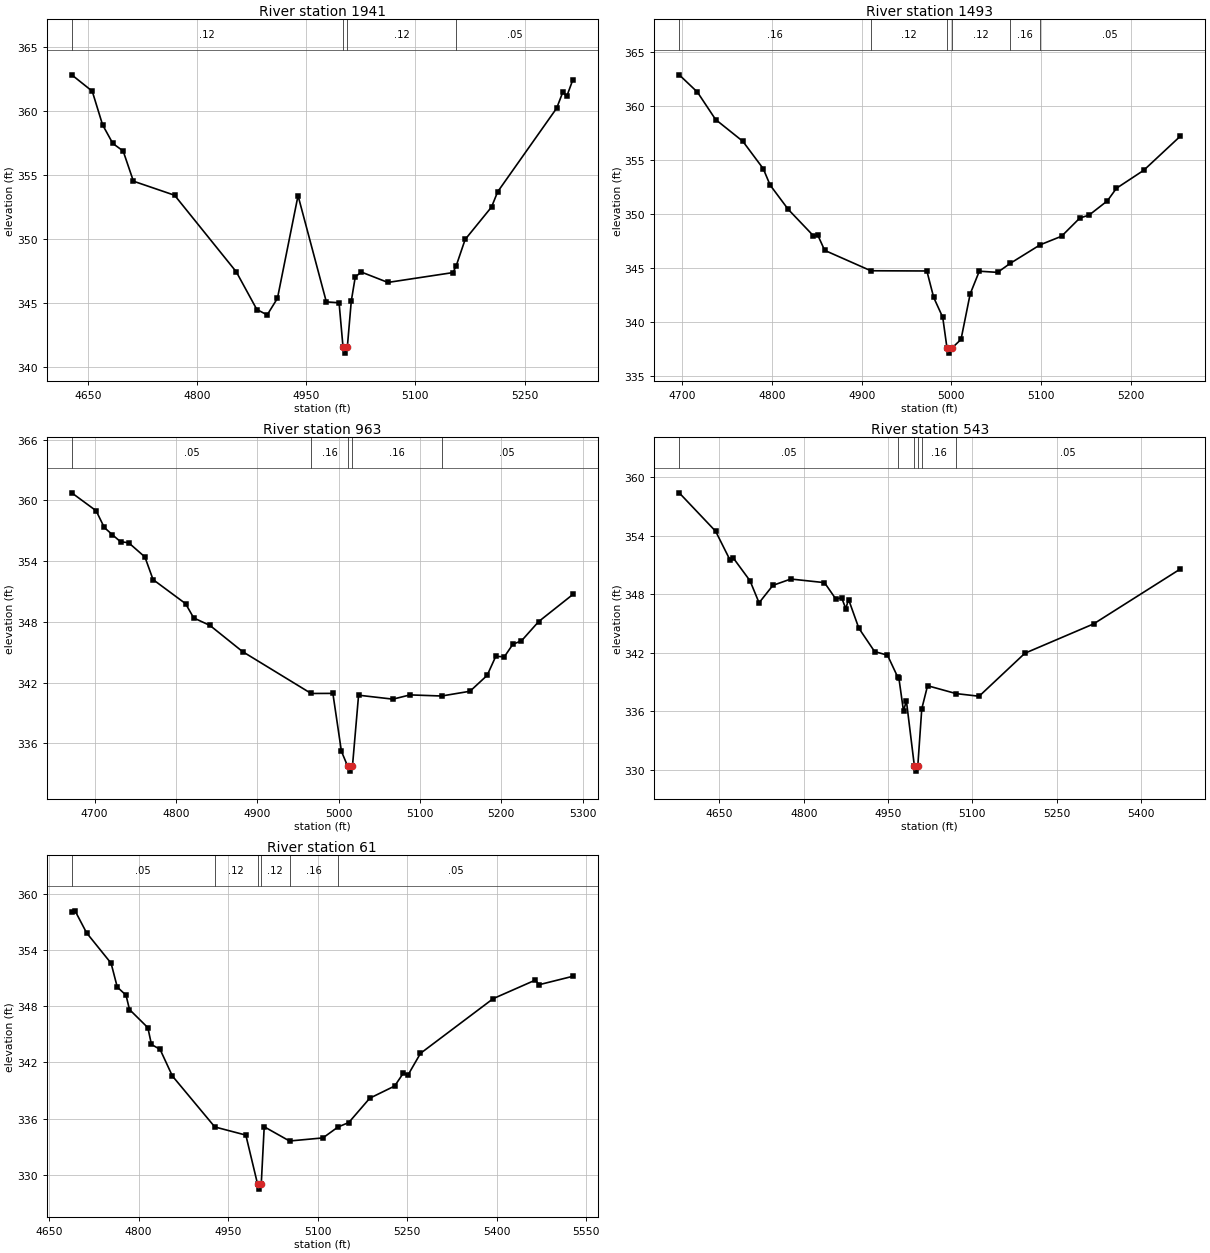
Type RM Length L Ch R = 1,1941,448,448,448
BEGIN DESCRIPTION:
UNT 077 IN CACR 4.0
END DESCRIPTION:
XS GIS Cut Line= 3
      3700149.58     10741460.22      3699899.61     10741710.19
      3699599.63     10741860.18
#Sta/Elev= 30
  4627.6  362.82  4655.8  361.54  4670.0  358.91  4684.1  357.45  4698.3  356.86
  4712.4  354.50  4769.0  353.40  4853.8  347.41  4882.1  344.46  4896.3  344.04
  4910.4  345.34  4938.7  353.37  4977.6  345.06  4995.1  344.99  5000.5  341.55
  5003.2  341.05  5006.5  341.55  5011.9  345.13  5017.4  347.02  5025.8  347.39
  5062.2  346.58  5151.6  347.35  5156.0  347.86  5168.4  349.94  5204.7  352.48
  5213.1  353.67  5294.2  360.21  5302.5  361.44  5308.1  361.14  5316.5  362.44
#Mann=4,-1,0
  4627.6    0.12       0  5000.5    0.07       0  5006.5    0.12       0
  5156.0    0.05       0
Bank Sta=5000.5,5006.5
Exp/Cntr=0.3,0.1

Type RM Length L Ch R = 1,1493,530,530,530
BEGIN DESCRIPTION:
UNT 077 IN CACR 3.0
END DESCRIPTION:
XS GIS Cut Line= 3
      3700049.66     10741260.18      3699749.61     10741310.19
      3699499.65     10741360.18
#Sta/Elev= 30
  4696.4  362.87  4716.7  361.27  4737.0  358.73  4767.4  356.71  4790.2  354.17
  4797.8  352.66  4818.1  350.40  4846.0  347.97  4851.1  348.00  4858.7  346.61
  4910.2  344.72  4972.7  344.70  4980.3  342.25  4990.4  340.41  4995.1  337.59
  4997.8  337.09  5001.1  337.59  5010.8  338.36  5021.0  342.57  5031.2  344.68
  5051.6  344.57  5065.6  345.40  5099.0  347.12  5123.0  347.92  5143.4  349.61
  5153.6  349.87  5174.0  351.19  5184.2  352.36  5214.7  354.03  5255.5  357.19
#Mann=6,-1,0
  4696.4    0.16       0  4910.2    0.12       0  4995.1    0.07       0
  5001.1    0.12       0  5065.6    0.16       0  5099.0    0.05       0
Bank Sta=4995.1,5001.1
Exp/Cntr=0.3,0.1

Type RM Length L Ch R = 1,963,420,420,420
BEGIN DESCRIPTION:
UNT 077 IN CACR 2.0
END DESCRIPTION:
XS GIS Cut Line= 3
      3700049.62     10740860.19      3699749.61     10740860.19
      3699449.64     10740960.18
#Sta/Elev= 30
  4671.8  360.75  4701.8  358.98  4711.8  357.33  4721.8  356.61  4731.8  355.92
  4741.8  355.82  4761.8  354.41  4771.8  352.18  4811.8  349.80  4821.8  348.39
  4841.8  347.65  4881.8  345.07  4966.2  340.93  4992.9  340.94  5003.4  335.22
  5011.0  333.76  5013.7  333.26  5017.0  333.76  5024.5  340.76  5066.7  340.37
  5087.8  340.79  5126.5  340.68  5161.5  341.15  5182.6  342.72  5193.2  344.60
  5203.7  344.55  5214.2  345.79  5224.8  346.13  5245.9  348.03  5288.0  350.71
#Mann=5,-1,0
  4671.8    0.05       0  4966.2    0.16       0  5011.0    0.07       0
  5017.0    0.16       0  5126.5    0.05       0
Bank Sta=5011,5017
Exp/Cntr=0.3,0.1

Type RM Length L Ch R = 1,543,482,482,482
BEGIN DESCRIPTION:
Mapping XS d180c48b
END DESCRIPTION:
XS GIS Cut Line= 2
      3700103.22     10740377.66      3699228.24     10740549.53
#Sta/Elev= 30
  4578.5  358.39  4643.3  354.45  4669.1  351.48  4674.2  351.75  4704.5  349.37
  4720.6  347.11  4745.2  348.90  4777.1  349.55  4837.0  349.18  4857.3  347.49
  4867.5  347.64  4874.8  346.52  4879.9  347.45  4898.1  344.51  4926.2  342.11
  4949.1  341.74  4967.2  339.51  4969.4  339.38  4977.6  336.01  4982.7  337.08
  4997.0  330.35  4999.8  329.85  5003.0  330.35  5010.1  336.24  5020.4  338.61
  5071.2  337.80  5112.1  337.53  5193.6  341.94  5315.9  344.95  5470.2  350.58
#Mann=6,-1,0
  4578.5    0.05       0  4967.2    0.12       0  4997.0    0.07       0
  5003.0    0.12       0  5010.1    0.16       0  5071.2    0.05       0
Bank Sta=4997,5003
Exp/Cntr=0.3,0.1

Type RM Length L Ch R = 1,61,0,0,0
BEGIN DESCRIPTION:
UNT 077 IN CACR 1.0
END DESCRIPTION:
XS GIS Cut Line= 3
      3699993.91     10740075.58      3699634.49     10739992.23
      3699264.72     10740283.88
#Sta/Elev= 30
  4687.8  358.08  4693.4  358.18  4712.7  355.83  4753.8  352.58  4764.1  350.04
  4778.8  349.17  4784.6  347.64  4815.4  345.70  4821.4  343.91  4835.9  343.38
  4856.5  340.54  4927.6  335.10  4979.6  334.23  4999.4  328.96  5002.1  328.46
  5005.4  328.96  5010.4  335.12  5052.8  333.60  5108.8  333.93  5134.2  335.10
  5152.1  335.57  5187.3  338.17  5229.0  339.47  5243.4  340.83  5251.5  340.66
  5272.3  342.96  5394.1  348.80  5464.7  350.78  5471.1  350.29  5527.7  351.19
#Mann=6,-1,0
  4687.8    0.05       0  4927.6    0.12       0  4999.4    0.07       0
  5005.4    0.12       0  5052.8    0.16       0  5134.2    0.05       0
Bank Sta=4999.4,5005.4
Exp/Cntr=0.3,0.1

Chan Stop Cuts=-1