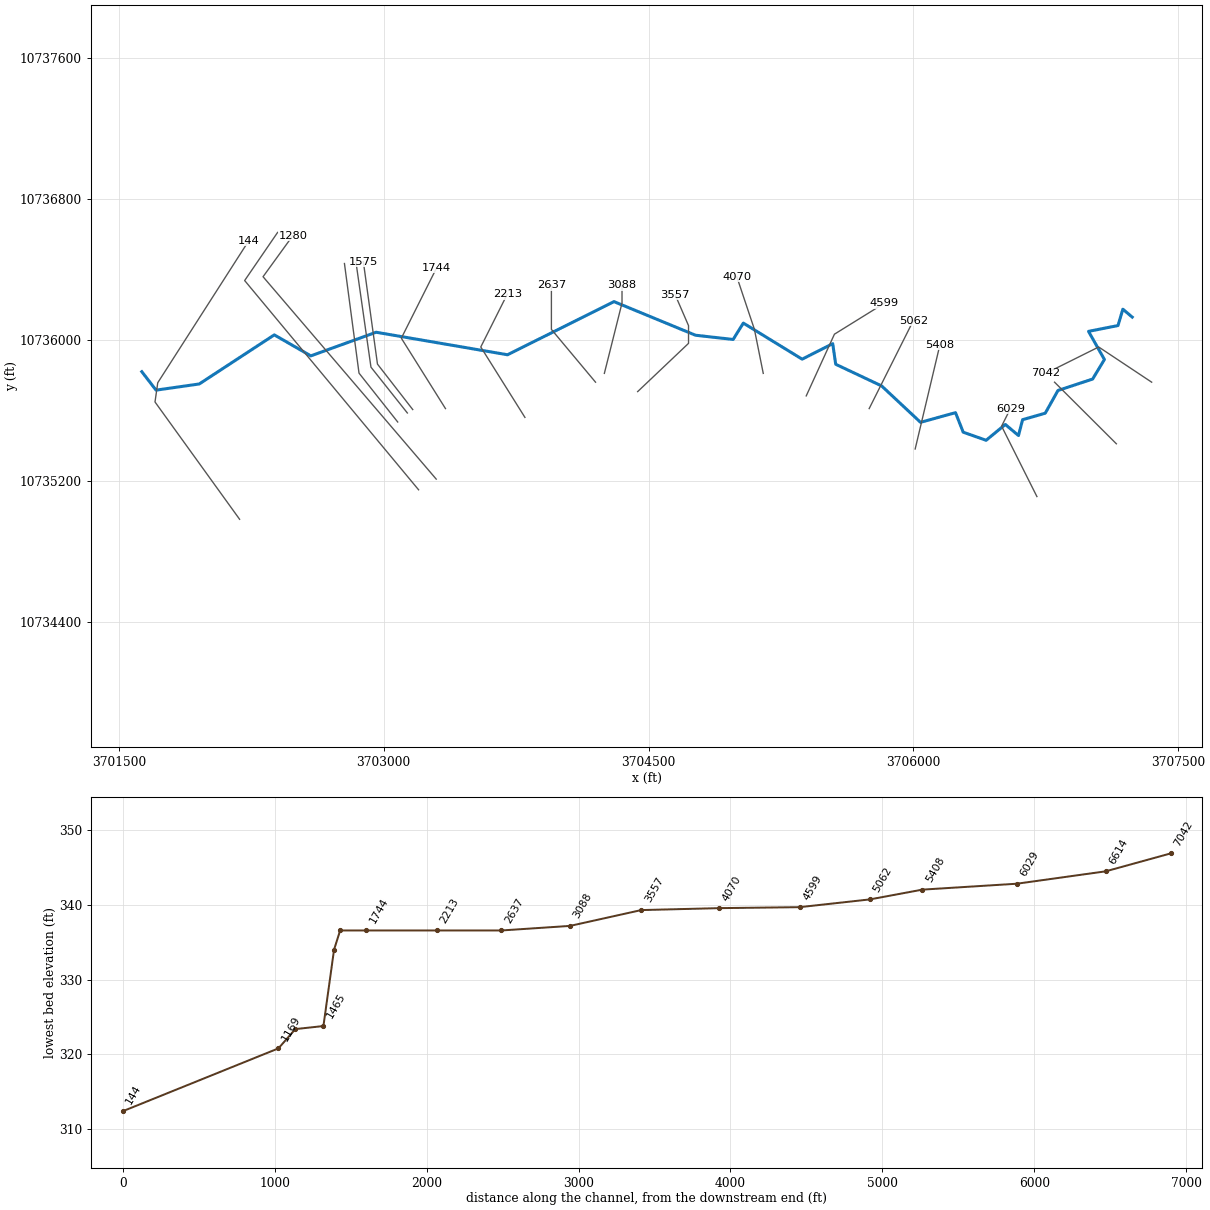
--- UNT 078 IN CACR.prj (project) ---

Proj Title=UNT 078 IN CACR Base Level Engineering
Current Plan=p01
Default Exp/Contr=0.3,0.1
English Units
Geom File=g01
Flow File=f01
Plan File=p01
BEGIN DESCRIPTION:
UNT 078 IN CACR
END DESCRIPTION:

--- UNT 078 IN CACR.p01 (plan) ---

Plan Title=Multiple Run
Short Identifier=Multiple
Geom File=g01
Flow File=f01
Subcritical Flow
K Sum by GR= 0
Std Step Tol= 0.01
Critical Tol= 0.01
Num of Std Step Trials= 20
Max Error Tol= 0.3
Flow Tol Ratio= 0.001
Split Flow NTrial= 30
Split Flow Tol= 0.02
Split Flow Ratio= 0.02
Log Output Level= 0
Friction Slope Method= 1
Unsteady Friction Slope Method= 2
Unsteady Bridges Friction Slope Method= 1
Parabolic Critical Depth
Global Vel Dist=  1 , 1 , 1
Global Log Level= 0
CheckData=True
Encroach Param= -1, 0, 0, 0
BEGIN DESCRIPTION:
Multiple Run
END DESCRIPTION:

--- UNT 078 IN CACR.f01 (steady flow) ---

Flow Title=Multiple
Number of Profiles=7
Profile Names=10-year,25-year,50-year,1pct_min,100-year,1pct_plu,500-year
River Rch & RM= UNT 078 IN CACR,Reach-1,7042
     719     986    1208    1086    1468    1985    2173
River Rch & RM= UNT 078 IN CACR,Reach-1,6029
     858    1183    1455    1312    1775    2400    2644
Boundary for River Rch & Prof#=UNT 078 IN CACR,Reach-1,1
Up Type=0
Dn Type=3
Dn Slope=0.005
Boundary for River Rch & Prof#=UNT 078 IN CACR,Reach-1,2
Up Type=0
Dn Type=3
Dn Slope=0.005
Boundary for River Rch & Prof#=UNT 078 IN CACR,Reach-1,3
Up Type=0
Dn Type=3
Dn Slope=0.005
Boundary for River Rch & Prof#=UNT 078 IN CACR,Reach-1,4
Up Type=0
Dn Type=3
Dn Slope=0.005
Boundary for River Rch & Prof#=UNT 078 IN CACR,Reach-1,5
Up Type=0
Dn Type=3
Dn Slope=0.005
Boundary for River Rch & Prof#=UNT 078 IN CACR,Reach-1,6
Up Type=0
Dn Type=3
Dn Slope=0.005
Boundary for River Rch & Prof#=UNT 078 IN CACR,Reach-1,7
Up Type=0
Dn Type=3
Dn Slope=0.005

--- UNT 078 IN CACR.g01 (geometry) ---

Geom Title=Existing Conditions

River Reach=UNT 078 IN CACR,Reach-1
Reach XY= 30
      3707239.50     10736130.00      3707186.50     10736175.00
      3707159.00     10736082.00      3706992.00     10736049.00
      3707082.00     10735889.00      3707015.25     10735778.00
      3706818.75     10735713.00      3706747.00     10735584.00
      3706618.50     10735547.00      3706595.25     10735457.00
      3706520.75     10735520.00      3706412.00     10735430.00
      3706282.25     10735476.00      3706238.50     10735587.00
      3706040.50     10735532.00      3705820.00     10735739.00
      3705560.00     10735862.00      3705543.00     10735979.00
      3705369.75     10735891.00      3705036.75     10736096.00
      3704979.00     10736003.00      3704765.75     10736027.00
      3704304.25     10736218.00      3703701.00     10735916.00
      3702956.75     10736044.00      3702586.94     10735909.75
      3702380.00     10736029.00      3701955.00     10735750.00
      3701710.25     10735715.00      3701629.50     10735820.00

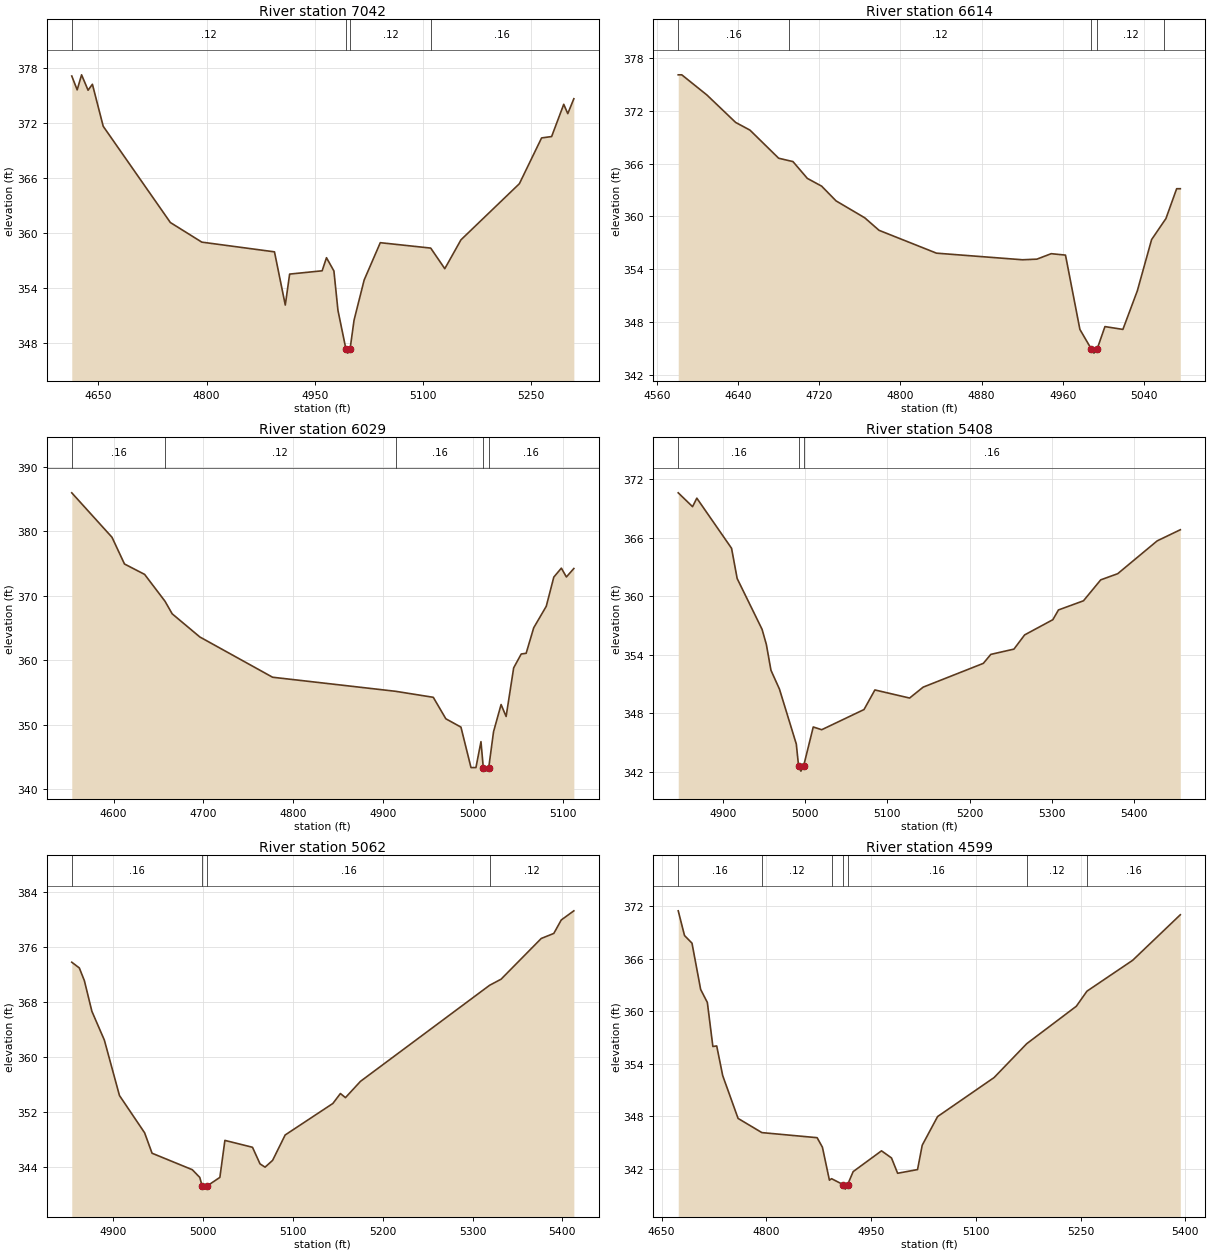
Type RM Length L Ch R = 1,7042,428,428,428
BEGIN DESCRIPTION:
UNT 078 IN CACR 15.0
END DESCRIPTION:
XS GIS Cut Line= 3
      3707349.63     10735760.17      3707049.61     10735960.19
      3706749.60     10735810.19
#Sta/Elev= 30
  4613.1  377.16  4620.6  375.65  4626.7  377.29  4635.7  375.61  4641.7  376.26
  4656.7  371.67  4749.8  361.16  4793.4  359.02  4894.1  357.96  4909.1  352.15
  4915.1  355.53  4960.2  355.89  4966.2  357.32  4976.5  355.87  4982.1  351.57
  4993.0  347.40  4995.8  346.90  4999.0  347.40  5004.4  350.49  5018.4  354.88
  5040.8  358.96  5110.7  358.37  5130.2  356.12  5152.6  359.27  5233.6  365.40
  5264.4  370.40  5278.3  370.55  5295.1  374.07  5300.7  373.05  5309.1  374.68
#Mann=4,-1,0
  4613.1    0.12       0  4993.0    0.07       0  4999.0    0.12       0
  5110.7    0.16       0
Bank Sta=4993,4999
Exp/Cntr=0.3,0.1

Type RM Length L Ch R = 1,6614,585,585,585
BEGIN DESCRIPTION:
UNT 078 IN CACR 14.0
END DESCRIPTION:
XS GIS Cut Line= 3
      3707149.62     10735410.18      3706849.61     10735710.19
      3706799.60     10735760.20
#Sta/Elev= 30
  4581.0  376.07  4584.5  376.07  4609.3  373.78  4637.6  370.67  4651.7  369.80
  4680.0  366.61  4690.3  366.33  4694.1  366.23  4708.3  364.32  4722.4  363.44
  4736.6  361.77  4764.9  359.85  4779.0  358.43  4835.6  355.84  4920.4  355.09
  4934.6  355.16  4948.7  355.78  4962.8  355.62  4977.0  347.19  4988.1  345.00
  4990.9  344.50  4994.1  345.00  5001.7  347.51  5019.4  347.19  5033.6  351.56
  5047.7  357.38  5059.7  359.41  5061.8  359.76  5072.4  363.15  5076.0  363.15
#Mann=5,-1,0
  4581.0    0.16       0  4690.3    0.12       0  4988.1    0.07       0
  4994.1    0.12       0  5059.7    0.16       0
Bank Sta=4988.1,4994.1
Exp/Cntr=0.3,0.1

Type RM Length L Ch R = 1,6029,621,621,621
BEGIN DESCRIPTION:
UNT 078 IN CACR 13.0
END DESCRIPTION:
XS GIS Cut Line= 3
      3706699.62     10735110.16      3706499.61     10735510.19
      3706549.59     10735610.14
#Sta/Elev= 30
  4553.5  385.97  4598.3  379.08  4612.2  374.94  4634.6  373.33  4657.3  369.17
  4665.3  367.22  4696.1  363.63  4777.1  357.39  4914.1  355.21  4956.0  354.28
  4970.0  350.95  4986.8  349.66  4998.0  343.39  5003.5  343.39  5009.1  347.41
  5011.7  343.34  5014.5  342.84  5017.7  343.34  5023.1  348.95  5031.5  353.16
  5037.1  351.31  5045.5  358.84  5053.9  360.99  5059.4  361.10  5067.8  365.05
  5081.8  368.39  5090.2  372.91  5098.6  374.30  5104.2  372.93  5112.5  374.24
#Mann=5,-1,0
  4553.5    0.16       0  4657.3    0.12       0  4914.1    0.16       0
  5011.7    0.07       0  5017.7    0.16       0
Bank Sta=5011.7,5017.7
Exp/Cntr=0.3,0.1

Type RM Length L Ch R = 1,5408,346,346,346
BEGIN DESCRIPTION:
UNT 078 IN CACR 12.0
END DESCRIPTION:
XS GIS Cut Line= 2
      3706010.05     10735380.51      3706150.68     10735974.29
#Sta/Elev= 30
  4846.0  370.61  4863.4  369.19  4868.6  370.06  4910.8  364.92  4917.6  361.82
  4947.9  356.60  4953.1  355.05  4958.7  352.40  4969.0  350.47  4989.5  344.83
  4992.3  342.55  4995.1  342.05  4998.3  342.55  5010.1  346.58  5020.4  346.30
  5071.8  348.37  5085.0  350.38  5127.2  349.55  5143.7  350.67  5216.8  353.11
  5225.9  354.03  5254.0  354.57  5267.0  356.03  5301.3  357.59  5308.1  358.59
  5338.5  359.53  5359.5  361.68  5380.1  362.31  5428.1  365.68  5456.2  366.82
#Mann=3,-1,0
  4846.0    0.16       0  4992.3    0.07       0  4998.3    0.16       0
Bank Sta=4992.3,4998.3
Exp/Cntr=0.3,0.1

Type RM Length L Ch R = 1,5062,463,463,463
BEGIN DESCRIPTION:
UNT 078 IN CACR 11.0
END DESCRIPTION:
XS GIS Cut Line= 3
      3705749.61     10735610.19      3705799.61     10735710.19
      3705999.60     10736110.17
#Sta/Elev= 30
  4853.8  373.80  4862.2  372.97  4867.8  371.13  4876.2  366.65  4890.1  362.45
  4906.9  354.38  4934.9  348.95  4943.2  345.97  4988.0  343.57  4996.3  342.45
  4998.9  341.24  5001.7  340.74  5004.9  341.24  5018.7  342.45  5024.3  347.84
  5055.0  346.84  5063.4  344.42  5069.0  343.94  5077.4  344.93  5091.4  348.63
  5144.5  353.22  5152.9  354.67  5158.5  354.07  5175.2  356.44  5319.0  370.44
  5331.8  371.33  5376.5  377.26  5390.5  378.00  5398.8  379.96  5412.8  381.29
#Mann=4,-1,0
  4853.8    0.16       0  4998.9    0.07       0  5004.9    0.16       0
  5319.0    0.12       0
Bank Sta=4998.9,5004.9
Exp/Cntr=0.3,0.1

Type RM Length L Ch R = 1,4599,529,529,529
BEGIN DESCRIPTION:
UNT 078 IN CACR 10.0
END DESCRIPTION:
XS GIS Cut Line= 3
      3705393.03     10735682.23      3705552.75     10736032.92
      3705836.07     10736209.14
#Sta/Elev= 30
  4673.9  371.46  4682.9  368.64  4693.6  367.77  4706.0  362.49  4715.6  361.00
  4723.5  355.98  4729.0  356.04  4737.6  352.65  4759.6  347.77  4793.7  346.15
  4872.8  345.57  4880.4  344.48  4890.4  340.72  4893.5  340.89  4910.4  340.20
  4913.1  339.70  4916.4  340.20  4924.4  341.70  4965.0  344.07  4979.3  343.26
  4988.1  341.51  5016.6  341.93  5023.3  344.71  5045.3  347.98  5126.2  352.43
  5173.0  356.30  5244.0  360.57  5259.2  362.29  5324.6  365.81  5392.9  371.01
#Mann=7,-1,0
  4673.9    0.16       0  4793.7    0.12       0  4893.5    0.16       0
  4910.4    0.07       0  4916.4    0.16       0  5173.0    0.12       0
  5259.2    0.16       0
Bank Sta=4910.4,4916.4
Exp/Cntr=0.3,0.1

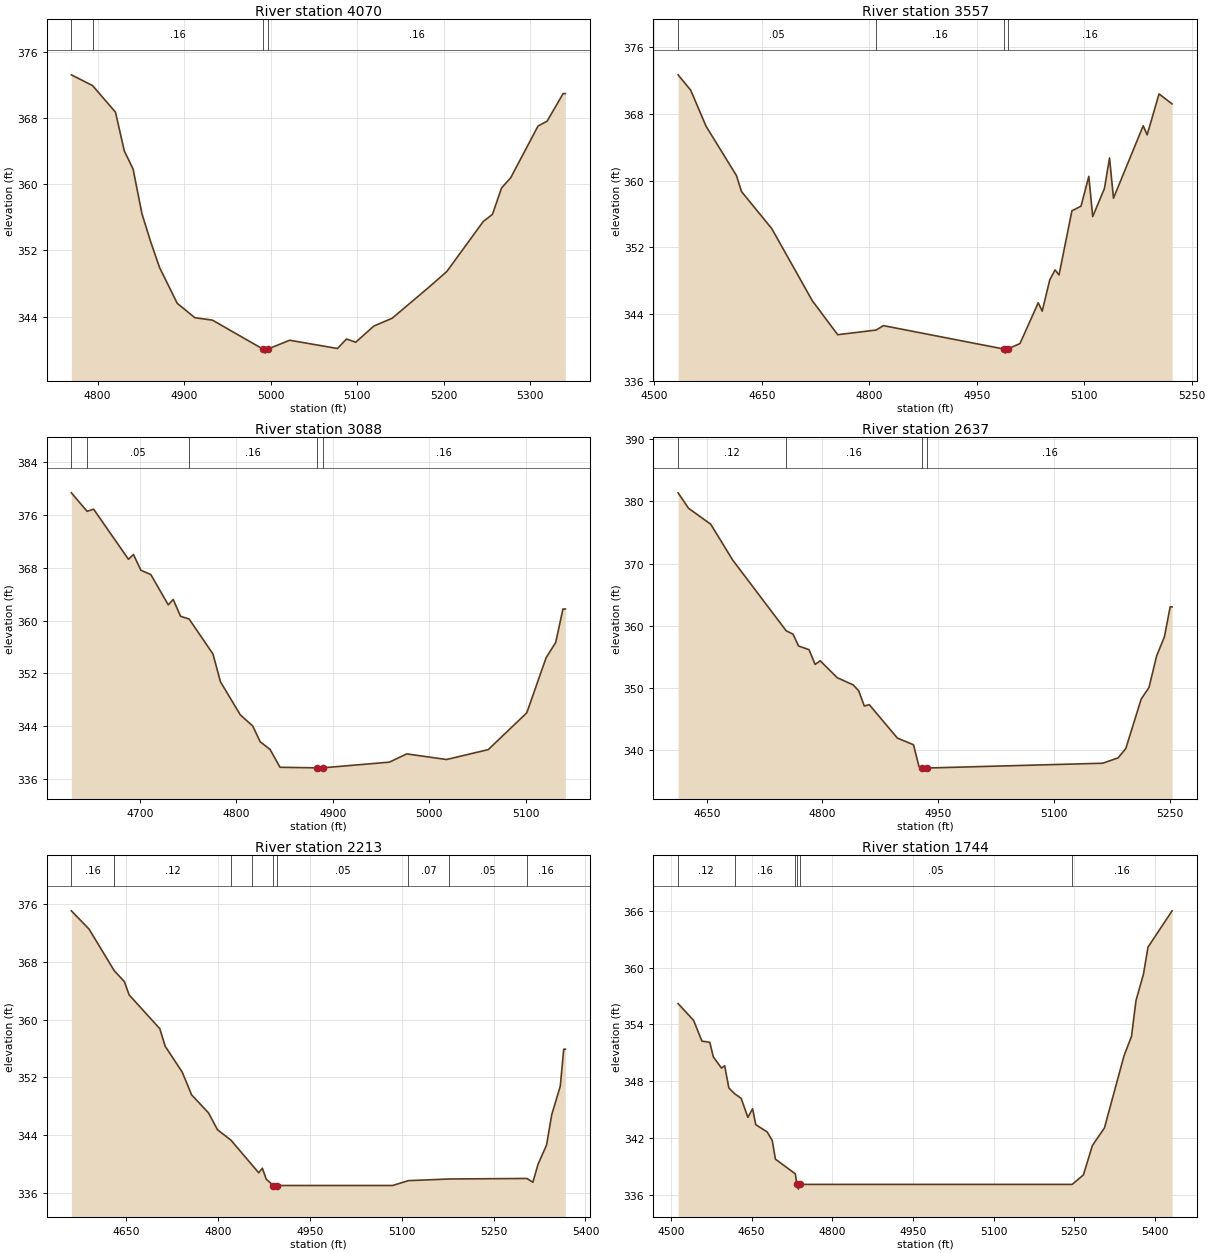
Type RM Length L Ch R = 1,4070,513,513,513
BEGIN DESCRIPTION:
UNT 078 IN CACR 9.0
END DESCRIPTION:
XS GIS Cut Line= 3
      3705149.61     10735810.16      3705099.61     10736060.19
      3704999.61     10736360.19
#Sta/Elev= 30
  4769.7  373.26  4794.2  371.96  4820.7  368.74  4830.9  364.06  4841.1  361.84
  4851.3  356.45  4861.5  353.02  4871.7  349.93  4892.1  345.60  4912.5  343.86
  4932.9  343.56  4991.1  340.07  4993.8  339.57  4997.1  340.07  5022.1  341.13
  5077.4  340.13  5087.9  341.28  5098.5  340.89  5119.5  342.85  5140.6  343.79
  5182.8  347.52  5203.9  349.46  5246.0  355.51  5256.6  356.37  5267.1  359.56
  5277.7  360.80  5309.3  367.06  5319.8  367.65  5338.3  370.99  5340.9  370.99
#Mann=4,-1,0
  4769.7    0.12       0  4794.2    0.16       0  4991.1    0.07       0
  4997.1    0.16       0
Bank Sta=4991.1,4997.1
Exp/Cntr=0.3,0.1

Type RM Length L Ch R = 1,3557,469,469,469
BEGIN DESCRIPTION:
UNT 078 IN CACR 8.0
END DESCRIPTION:
XS GIS Cut Line= 4
      3704438.20     10735706.57      3704726.36     10735980.84
      3704726.36     10736081.54      3704650.71     10736256.90
#Sta/Elev= 30
  4533.1  372.70  4550.7  370.86  4572.1  366.54  4614.6  360.61  4621.5  358.71
  4663.9  354.24  4720.5  345.59  4755.9  341.52  4809.6  342.08  4819.6  342.61
  4987.3  339.81  4990.0  339.31  4993.3  339.81  5010.3  340.46  5035.8  345.35
  5041.3  344.35  5051.9  348.11  5059.3  349.29  5064.8  348.69  5082.8  356.39
  5095.5  356.94  5106.4  360.52  5111.8  355.69  5128.2  359.07  5135.3  362.73
  5140.8  357.90  5182.3  366.59  5187.8  365.50  5204.4  370.41  5222.6  369.21
#Mann=4,-1,0
  4533.1    0.05       0  4809.6    0.16       0  4987.3    0.07       0
  4993.3    0.16       0
Bank Sta=4987.3,4993.3
Exp/Cntr=0.3,0.1

Type RM Length L Ch R = 1,3088,451,451,451
BEGIN DESCRIPTION:
UNT 078 IN CACR 7.0
END DESCRIPTION:
XS GIS Cut Line= 3
      3704249.62     10735810.24      3704349.61     10736210.19
      3704349.61     10736310.23
#Sta/Elev= 30
  4628.8  379.37  4645.1  376.57  4651.9  376.89  4688.0  369.30  4693.2  370.02
  4700.9  367.64  4711.2  366.98  4729.3  362.39  4734.4  363.21  4742.1  360.65
  4750.9  360.25  4775.6  354.96  4783.4  350.74  4804.0  345.72  4816.9  344.03
  4824.6  341.64  4834.9  340.47  4845.2  337.77  4883.4  337.69  4886.2  337.19
  4889.4  337.69  4958.6  338.55  4976.6  339.80  5017.9  338.95  5061.1  340.45
  5101.1  346.03  5121.1  354.36  5131.1  356.70  5138.6  361.76  5141.1  361.76
#Mann=5,-1,0
  4628.8    0.12       0  4645.1    0.05       0  4750.9    0.16       0
  4883.4    0.07       0  4889.4    0.16       0
Bank Sta=4883.4,4889.4
Exp/Cntr=0.3,0.1

Type RM Length L Ch R = 1,2637,424,424,424
BEGIN DESCRIPTION:
UNT 078 IN CACR 6.0
END DESCRIPTION:
XS GIS Cut Line= 3
      3704199.59     10735760.21      3703949.61     10736060.19
      3703949.61     10736310.20
#Sta/Elev= 30
  4612.8  381.38  4626.4  378.89  4655.1  376.33  4683.7  370.54  4753.0  359.17
  4761.8  358.63  4769.0  356.72  4782.6  356.13  4790.5  353.75  4797.0  354.35
  4819.1  351.62  4839.9  350.46  4847.1  349.49  4854.2  347.06  4860.7  347.28
  4897.2  341.89  4918.0  340.83  4925.2  337.29  4929.3  337.08  4932.1  336.58
  4935.3  337.08  5163.3  337.85  5183.3  338.71  5193.3  340.22  5213.3  348.20
  5223.3  350.02  5233.3  355.14  5243.3  358.17  5250.8  363.01  5253.3  363.01
#Mann=4,-1,0
  4612.8    0.12       0  4753.0    0.16       0  4929.3    0.07       0
  4935.3    0.16       0
Bank Sta=4929.3,4935.3
Exp/Cntr=0.3,0.1

Type RM Length L Ch R = 1,2213,469,469,469
BEGIN DESCRIPTION:
UNT 078 IN CACR 5.0
END DESCRIPTION:
XS GIS Cut Line= 3
      3703799.63     10735560.15      3703549.61     10735960.19
      3703699.59     10736260.14
#Sta/Elev= 30
  4560.1  375.02  4589.0  372.50  4630.1  366.76  4646.8  365.23  4654.5  363.41
  4704.6  358.74  4713.4  356.31  4741.2  352.75  4756.5  349.61  4784.2  347.11
  4798.9  344.78  4820.9  343.34  4855.8  339.87  4866.2  338.84  4872.1  339.47
  4878.5  337.95  4890.3  337.08  4893.0  336.58  4896.3  337.08  5084.9  337.08
  5110.6  337.75  5177.5  337.98  5304.6  338.05  5314.1  337.52  5322.5  340.00
  5336.5  342.68  5344.9  346.85  5358.9  350.81  5364.5  355.91  5367.2  355.91
#Mann=9,-1,0
  4560.1    0.16       0  4630.1    0.12       0  4820.9    0.16       0
  4855.8    0.05       0  4890.3   0.033       0  4896.3    0.05       0
  5110.6    0.07       0  5177.5    0.05       0  5304.6    0.16       0
Bank Sta=4890.3,4896.3
Exp/Cntr=0.3,0.1

Type RM Length L Ch R = 1,1744,169,169,169
BEGIN DESCRIPTION:
UNT 078 IN CACR 4.0
END DESCRIPTION:
XS GIS Cut Line= 3
      3703349.63     10735610.15      3703099.61     10736010.19
      3703299.63     10736410.23
#Sta/Elev= 30
  4513.1  356.21  4542.0  354.43  4557.4  352.24  4572.1  352.11  4578.6  350.58
  4593.9  349.38  4599.8  349.63  4607.5  347.29  4618.3  346.67  4630.5  346.18
  4642.9  344.17  4651.7  345.08  4657.6  343.40  4678.8  342.63  4688.3  341.72
  4694.2  339.75  4731.2  338.20  4734.2  337.08  4736.9  336.58  4740.2  337.08
  5246.2  337.08  5267.1  338.08  5283.9  341.20  5306.3  343.06  5342.6  350.67
  5356.6  352.74  5365.0  356.54  5378.9  359.33  5387.3  362.18  5432.1  366.02
#Mann=6,-1,0
  4513.1    0.12       0  4618.3    0.16       0  4731.2    0.05       0
  4734.2   0.033       0  4740.2    0.05       0  5246.2    0.16       0
Bank Sta=4734.2,4740.2
Exp/Cntr=0.3,0.1

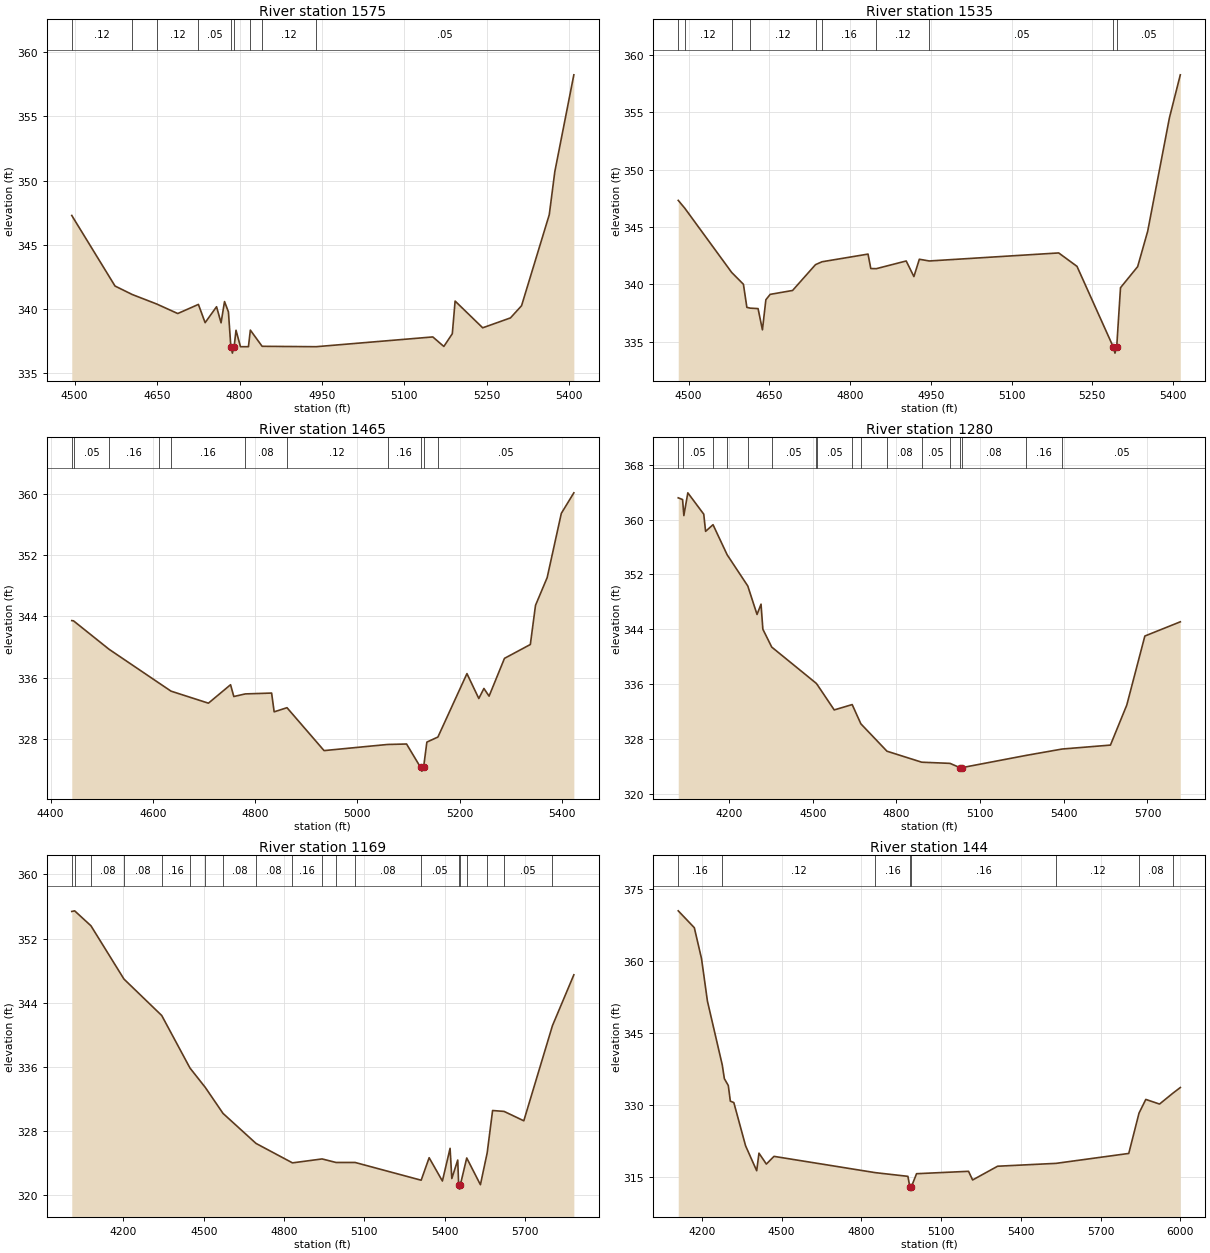
Type RM Length L Ch R = 1,1575,40,40,40
BEGIN DESCRIPTION:
Mapping XS 393b0a37
END DESCRIPTION:
XS GIS Cut Line= 3
      3703164.14     10735604.69      3702964.50     10735862.93
      3702884.51     10736444.44
#Sta/Elev= 30
  4494.8  347.29  4573.5  341.80  4604.8  341.14  4649.4  340.40  4687.6  339.66
  4725.2  340.37  4737.4  338.95  4758.2  340.19  4766.4  338.94  4772.7  340.59
  4779.8  339.79  4784.2  337.08  4787.0  336.58  4790.2  337.08  4793.6  338.36
  4801.7  337.08  4816.2  337.08  4819.7  338.37  4841.1  337.11  4939.5  337.08
  5151.6  337.84  5171.7  337.10  5187.1  338.09  5192.2  340.63  5242.4  338.55
  5292.9  339.32  5313.1  340.27  5363.5  347.35  5373.6  350.70  5408.2  358.23
#Mann=9,-1,0
  4494.8    0.12       0  4604.8    0.16       0  4649.4    0.12       0
  4725.2    0.05       0  4784.2    0.03       0  4790.2    0.05       0
  4819.7    0.16       0  4841.1    0.12       0  4939.5    0.05       0
Bank Sta=4784.2,4790.2
Exp/Cntr=0.3,0.1

Type RM Length L Ch R = 1,1535,70,70,70
BEGIN DESCRIPTION:
Mapping XS 86b2e56a
END DESCRIPTION:
XS GIS Cut Line= 3
      3703133.74     10735585.19      3702927.61     10735845.57
      3702842.97     10736440.18
#Sta/Elev= 30
  4480.8  347.32  4493.1  346.63  4580.1  341.04  4601.9  340.01  4608.3  338.00
  4614.4  337.93  4629.1  337.89  4637.2  336.04  4643.6  338.66  4651.6  339.13
  4693.2  339.47  4735.8  341.72  4747.8  341.97  4833.4  342.64  4838.5  341.38
  4848.8  341.37  4904.3  342.04  4918.6  340.68  4928.7  342.19  4947.2  342.04
  5187.6  342.74  5221.6  341.57  5289.3  334.51  5292.1  334.01  5295.3  334.51
  5302.4  339.71  5334.3  341.55  5352.9  344.63  5393.3  354.52  5413.5  358.26
#Mann=10,-1,0
  4480.8    0.16       0  4493.1    0.12       0  4580.1    0.16       0
  4614.4    0.12       0  4735.8    0.05       0  4747.8    0.16       0
  4848.8    0.12       0  4947.2    0.05       0  5289.3    0.03       0
  5295.3    0.05       0
Bank Sta=5289.3,5295.3
Exp/Cntr=0.3,0.1

Type RM Length L Ch R = 1,1465,185,185,185
BEGIN DESCRIPTION:
Mapping XS 7eac8f0a
END DESCRIPTION:
XS GIS Cut Line= 3
      3703079.09     10735533.93      3702859.90     10735811.72
      3702777.43     10736434.53
#Sta/Elev= 30
  4441.5  343.43  4444.9  343.40  4514.6  339.68  4613.0  335.24  4635.7  334.22
  4708.8  332.65  4752.1  335.06  4758.5  333.52  4781.0  333.86  4832.4  333.97
  4837.4  331.52  4862.5  332.06  4935.0  326.46  5059.3  327.26  5096.4  327.32
  5123.7  324.28  5126.4  323.78  5129.7  324.28  5136.1  327.57  5157.7  328.23
  5214.5  336.51  5237.7  333.26  5247.7  334.57  5257.8  333.57  5287.9  338.50
  5338.5  340.31  5348.6  345.42  5371.4  349.04  5399.1  357.43  5423.6  360.11
#Mann=11,-1,0
  4441.5    0.16       0  4444.9    0.05       0  4514.6    0.16       0
  4613.0    0.05       0  4635.7    0.16       0  4781.0    0.08       0
  4862.5    0.12       0  5059.3    0.16       0  5123.7    0.07       0
  5129.7    0.16       0  5157.7    0.05       0
Bank Sta=5123.7,5129.7
Exp/Cntr=0.3,0.1

Type RM Length L Ch R = 1,1280,111,111,111
BEGIN DESCRIPTION:
UNT 078 IN CACR 3.0
END DESCRIPTION:
XS GIS Cut Line= 3
      3703297.23     10735209.38      3702316.35     10736359.53
      3702485.14     10736593.24
#Sta/Elev= 30
  4017.9  363.16  4033.5  362.91  4038.0  360.58  4052.3  363.89  4109.4  360.78
  4116.0  358.28  4142.6  359.25  4193.3  354.87  4267.3  350.32  4300.4  346.18
  4314.7  347.68  4321.3  344.03  4353.1  341.43  4512.8  336.15  4516.8  335.93
  4577.1  332.28  4641.5  333.06  4672.6  330.26  4766.2  326.27  4890.9  324.67
  4992.2  324.50  5028.0  323.87  5030.7  323.37  5034.0  323.87  5265.1  325.66
  5394.8  326.59  5567.3  327.16  5625.9  332.99  5690.7  343.04  5817.8  345.11
#Mann=17,-1,0
  4017.9    0.16       0  4033.5    0.05       0  4142.6    0.16       0
  4193.3    0.05       0  4267.3    0.16       0  4353.1    0.05       0
  4512.8    0.08       0  4516.8    0.05       0  4641.5    0.16       0
  4672.6    0.05       0  4766.2    0.08       0  4890.9    0.05       0
  4992.2    0.08       0  5028.0    0.07       0  5034.0    0.08       0
  5265.1    0.16       0  5394.8    0.05       0
Bank Sta=5028,5034
Exp/Cntr=0.3,0.1

Type RM Length L Ch R = 1,1169,1025,1025,1025
BEGIN DESCRIPTION:
UNT 078 IN CACR 2.0
END DESCRIPTION:
XS GIS Cut Line= 3
      3703197.42     10735148.60      3702212.18     10736337.83
      3702398.82     10736611.28
#Sta/Elev= 30
  4007.2  355.37  4017.9  355.45  4078.8  353.59  4202.2  346.95  4343.3  342.41
  4448.8  335.87  4506.1  333.45  4572.2  330.22  4695.5  326.48  4831.6  324.06
  4942.2  324.55  4994.3  324.11  5065.6  324.11  5312.3  321.90  5342.1  324.70
  5391.6  321.80  5420.3  325.87  5426.8  322.11  5448.9  324.41  5452.4  321.29
  5455.2  320.79  5458.4  321.29  5482.5  324.67  5533.6  321.34  5558.9  325.31
  5579.1  330.58  5622.0  330.47  5695.7  329.30  5802.7  341.15  5882.6  347.48
#Mann=20,-1,0
  4007.2    0.08       0  4017.9    0.16       0  4078.8    0.08       0
  4202.2    0.08       0  4343.3    0.16       0  4448.8    0.08       0
  4506.1    0.16       0  4572.2    0.08       0  4695.5    0.08       0
  4831.6    0.16       0  4942.2    0.08       0  4994.3    0.16       0
  5065.6    0.08       0  5312.3    0.05       0  5452.4    0.07       0
  5458.4    0.05       0  5482.5    0.16       0  5558.9    0.08       0
  5622.0    0.05       0  5802.7    0.08       0
Bank Sta=5452.4,5458.4
Exp/Cntr=0.3,0.1

Type RM Length L Ch R = 1,144,0,0,0
BEGIN DESCRIPTION:
UNT 078 IN CACR 1.0
END DESCRIPTION:
XS GIS Cut Line= 4
      3702183.56     10734981.03      3701704.37     10735647.73
      3701720.00     10735757.10      3702235.12     10736563.60
#Sta/Elev= 30
  4111.0  370.47  4171.5  366.95  4198.6  360.49  4220.8  351.63  4276.7  338.27
  4284.5  335.43  4299.3  334.00  4307.0  330.74  4320.1  330.44  4364.3  321.42
  4406.1  316.21  4414.7  319.88  4442.5  317.60  4471.1  319.21  4852.3  315.81
  4974.9  315.04  4982.0  312.87  4984.8  312.37  4988.0  312.87  5007.4  315.59
  5203.0  316.09  5218.3  314.28  5312.2  317.15  5532.2  317.75  5805.6  319.82
  5844.2  328.24  5869.7  331.10  5921.3  330.13  5971.6  332.40  5999.5  333.58
#Mann=8,-1,0
  4111.0    0.16       0  4276.7    0.12       0  4852.3    0.16       0
  4982.0    0.07       0  4988.0    0.16       0  5532.2    0.12       0
  5844.2    0.08       0  5971.6    0.05       0
Bank Sta=4982,4988
Exp/Cntr=0.3,0.1

Chan Stop Cuts=-1