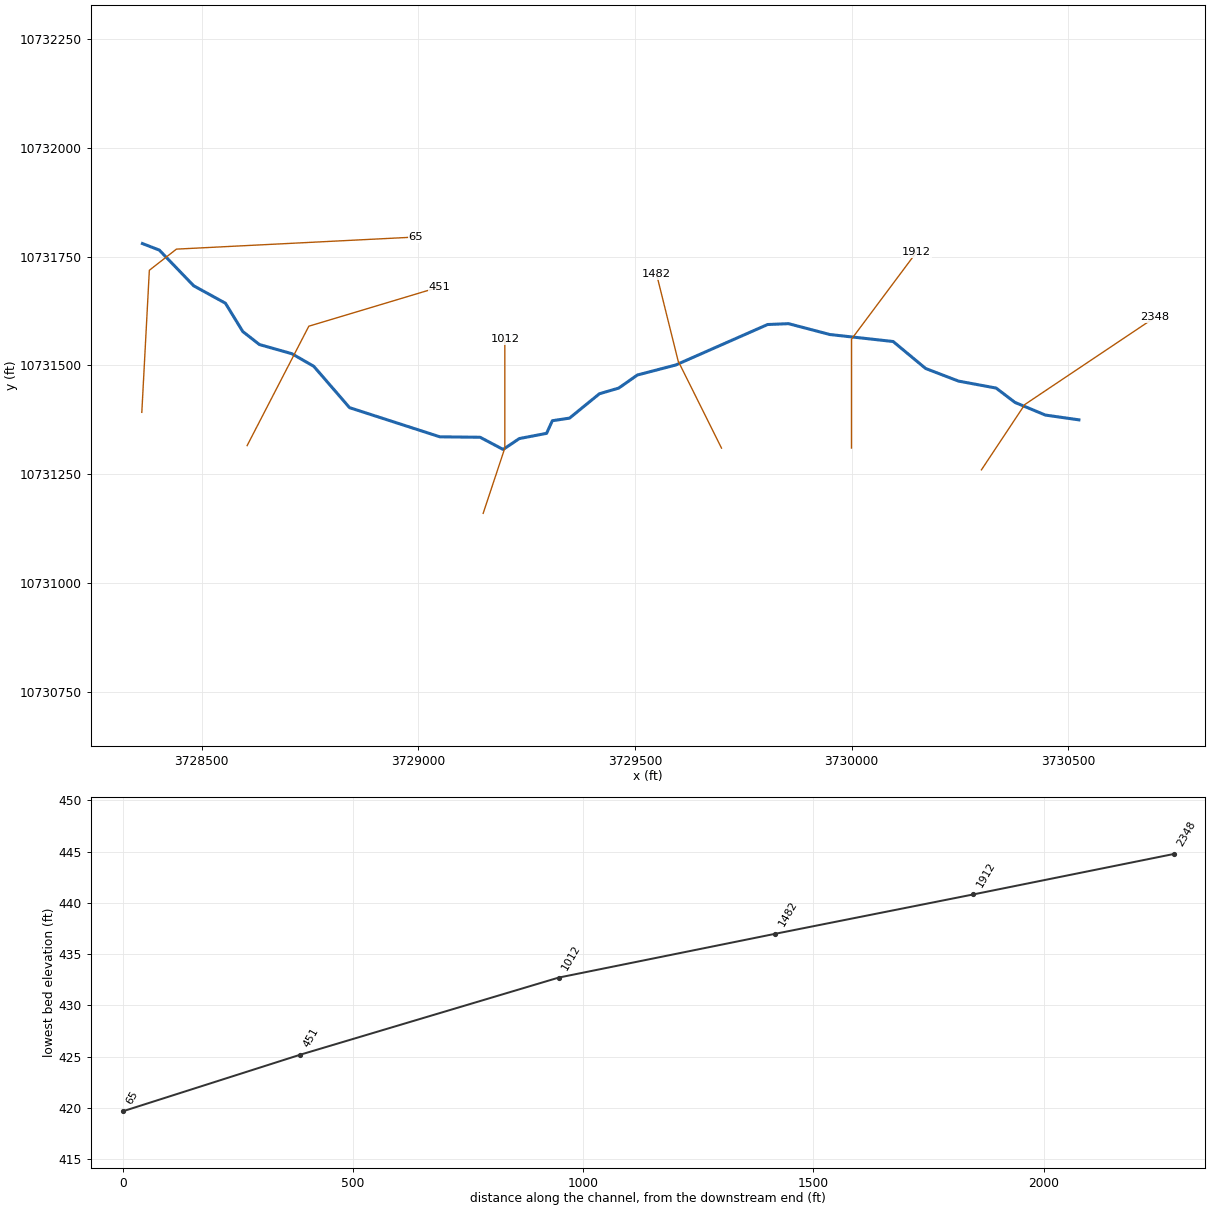
--- UNT 080 IN CACR.prj (project) ---

Proj Title=UNT 080 IN CACR Base Level Engineering
Current Plan=p01
Default Exp/Contr=0.3,0.1
English Units
Geom File=g01
Flow File=f01
Plan File=p01
BEGIN DESCRIPTION:
UNT 080 IN CACR
END DESCRIPTION:

--- UNT 080 IN CACR.p01 (plan) ---

Plan Title=Multiple Run
Short Identifier=Multiple
Geom File=g01
Flow File=f01
Subcritical Flow
K Sum by GR= 0
Std Step Tol= 0.01
Critical Tol= 0.01
Num of Std Step Trials= 20
Max Error Tol= 0.3
Flow Tol Ratio= 0.001
Split Flow NTrial= 30
Split Flow Tol= 0.02
Split Flow Ratio= 0.02
Log Output Level= 0
Friction Slope Method= 1
Unsteady Friction Slope Method= 2
Unsteady Bridges Friction Slope Method= 1
Parabolic Critical Depth
Global Vel Dist=  1 , 1 , 1
Global Log Level= 0
CheckData=True
Encroach Param= -1, 0, 0, 0
BEGIN DESCRIPTION:
Multiple Run
END DESCRIPTION:

--- UNT 080 IN CACR.f01 (steady flow) ---

Flow Title=Multiple
Number of Profiles=7
Profile Names=10-year,25-year,50-year,1pct_min,100-year,1pct_plu,500-year
River Rch & RM= UNT 080 IN CACR,Reach-1,2348
     334     440     525     462     625     845     884
River Rch & RM= UNT 080 IN CACR,Reach-1,65
     852    1176    1448    1306    1767    2389    2637
Boundary for River Rch & Prof#=UNT 080 IN CACR,Reach-1,1
Up Type=0
Dn Type=3
Dn Slope=0.005
Boundary for River Rch & Prof#=UNT 080 IN CACR,Reach-1,2
Up Type=0
Dn Type=3
Dn Slope=0.005
Boundary for River Rch & Prof#=UNT 080 IN CACR,Reach-1,3
Up Type=0
Dn Type=3
Dn Slope=0.005
Boundary for River Rch & Prof#=UNT 080 IN CACR,Reach-1,4
Up Type=0
Dn Type=3
Dn Slope=0.005
Boundary for River Rch & Prof#=UNT 080 IN CACR,Reach-1,5
Up Type=0
Dn Type=3
Dn Slope=0.005
Boundary for River Rch & Prof#=UNT 080 IN CACR,Reach-1,6
Up Type=0
Dn Type=3
Dn Slope=0.005
Boundary for River Rch & Prof#=UNT 080 IN CACR,Reach-1,7
Up Type=0
Dn Type=3
Dn Slope=0.005

--- UNT 080 IN CACR.g01 (geometry) ---

Geom Title=Existing Conditions

River Reach=UNT 080 IN CACR,Reach-1
Reach XY= 30
      3730524.50     10731375.00      3730447.00     10731386.00
      3730377.00     10731415.00      3730333.50     10731448.00
      3730246.75     10731464.00      3730170.75     10731493.00
      3730095.75     10731555.00      3729950.00     10731571.00
      3729854.25     10731596.00      3729806.00     10731594.00
      3729594.00     10731501.00      3729505.50     10731478.00
      3729462.50     10731448.00      3729418.00     10731435.00
      3729349.00     10731379.00      3729309.25     10731373.00
      3729296.00     10731344.00      3729233.00     10731332.00
      3729195.75     10731307.00      3729142.50     10731335.00
      3729049.75     10731336.00      3728841.25     10731403.00
      3728758.75     10731498.00      3728708.00     10731527.00
      3728633.25     10731548.00      3728594.75     10731578.00
      3728554.75     10731643.00      3728481.50     10731683.00
      3728402.25     10731765.00      3728363.25     10731780.00

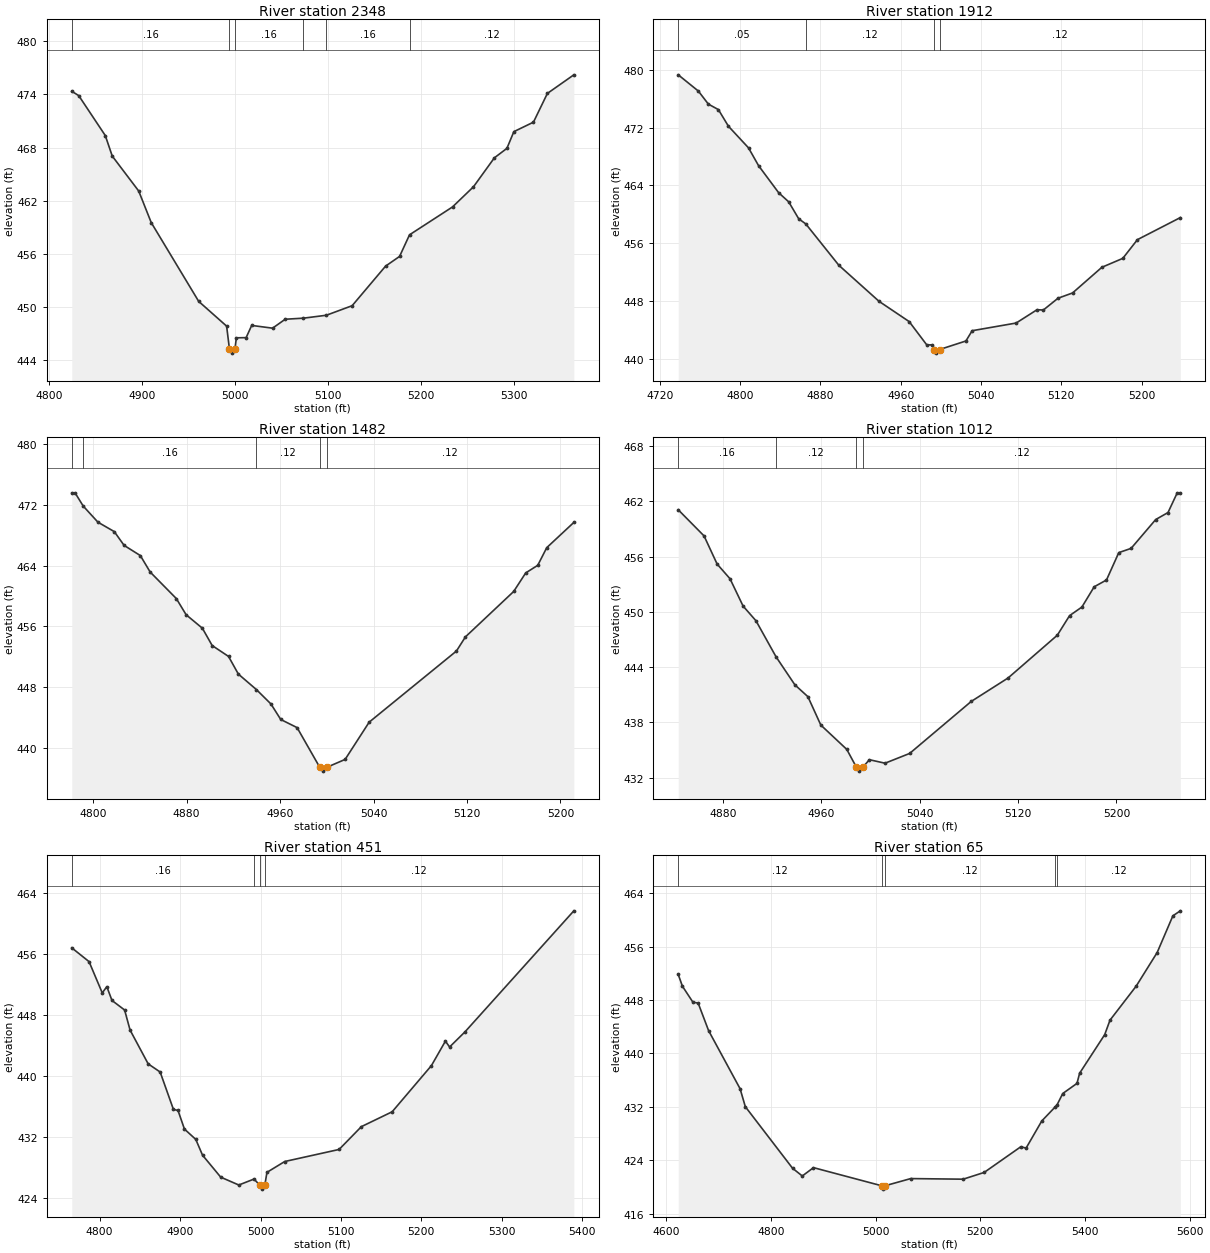
Type RM Length L Ch R = 1,2348,436,436,436
BEGIN DESCRIPTION:
UNT 080 IN CACR 5.0
END DESCRIPTION:
XS GIS Cut Line= 3
      3730299.60     10731260.18      3730399.61     10731410.19
      3730699.57     10731610.16
#Sta/Elev= 30
  4824.0  474.36  4831.5  473.87  4860.1  469.36  4867.6  467.04  4896.1  463.09
  4909.6  459.52  4960.7  450.62  4990.8  447.82  4993.8  445.27  4996.5  444.77
  4999.8  445.27  5001.3  446.50  5011.8  446.52  5017.8  447.90  5040.3  447.59
  5053.9  448.60  5073.5  448.72  5098.2  449.05  5126.0  450.13  5162.0  454.60
  5177.1  455.70  5187.8  458.14  5234.1  461.29  5256.7  463.57  5279.2  466.84
  5292.7  467.91  5300.2  469.80  5321.3  470.87  5336.3  474.12  5364.8  476.22
#Mann=6,-1,0
  4824.0    0.16       0  4993.8    0.07       0  4999.8    0.16       0
  5073.5    0.12       0  5098.2    0.16       0  5187.8    0.12       0
Bank Sta=4993.8,4999.8
Exp/Cntr=0.3,0.1

Type RM Length L Ch R = 1,1912,430,430,430
BEGIN DESCRIPTION:
UNT 080 IN CACR 4.0
END DESCRIPTION:
XS GIS Cut Line= 3
      3729999.61     10731310.16      3729999.61     10731560.19
      3730149.59     10731760.17
#Sta/Elev= 30
  4738.5  479.30  4758.5  477.06  4768.5  475.25  4778.5  474.49  4788.5  472.19
  4808.5  469.20  4818.5  466.74  4838.5  463.00  4848.5  461.74  4858.5  459.39
  4865.5  458.69  4898.5  452.96  4938.5  447.98  4968.5  445.18  4986.0  441.96
  4991.7  441.96  4992.8  441.32  4995.6  440.82  4998.8  441.32  5025.0  442.50
  5031.2  443.92  5075.0  444.98  5095.8  446.82  5102.1  446.78  5116.7  448.41
  5131.2  449.14  5160.4  452.69  5181.2  453.92  5195.8  456.51  5238.5  459.56
#Mann=4,-1,0
  4738.5    0.05       0  4865.5    0.12       0  4992.8    0.07       0
  4998.8    0.12       0
Bank Sta=4992.8,4998.8
Exp/Cntr=0.3,0.1

Type RM Length L Ch R = 1,1482,470,470,470
BEGIN DESCRIPTION:
UNT 080 IN CACR 3.0
END DESCRIPTION:
XS GIS Cut Line= 3
      3729699.63     10731310.15      3729599.61     10731510.19
      3729549.61     10731710.18
#Sta/Elev= 30
  4781.7  473.57  4784.5  473.57  4791.5  471.83  4804.1  469.71  4818.1  468.47
  4826.5  466.66  4840.4  465.32  4848.8  463.16  4871.2  459.67  4879.6  457.54
  4893.5  455.77  4901.9  453.49  4915.9  452.06  4924.3  449.74  4939.7  447.71
  4952.2  445.81  4960.6  443.77  4974.6  442.70  4994.0  437.48  4996.7  436.98
  5000.0  437.48  5015.7  438.52  5036.3  443.42  5111.0  452.77  5118.7  454.63
  5160.0  460.60  5170.3  463.04  5180.6  464.04  5188.3  466.36  5211.5  469.68
#Mann=5,-1,0
  4781.7    0.05       0  4791.5    0.16       0  4939.7    0.12       0
  4994.0    0.07       0  5000.0    0.12       0
Bank Sta=4994,5000
Exp/Cntr=0.3,0.1

Type RM Length L Ch R = 1,1012,561,561,561
BEGIN DESCRIPTION:
UNT 080 IN CACR 2.0
END DESCRIPTION:
XS GIS Cut Line= 3
      3729149.62     10731160.22      3729199.61     10731310.19
      3729199.61     10731560.21
#Sta/Elev= 30
  4843.8  461.08  4864.8  458.24  4875.4  455.19  4885.9  453.59  4896.5  450.63
  4907.0  449.03  4923.3  445.12  4938.6  442.08  4949.2  440.79  4959.7  437.71
  4980.8  435.07  4988.3  433.21  4991.1  432.71  4994.3  433.21  4999.2  433.95
  5011.9  433.57  5031.9  434.63  5081.9  440.27  5111.9  442.82  5151.9  447.46
  5161.9  449.59  5171.9  450.52  5181.9  452.72  5191.9  453.46  5201.9  456.43
  5211.9  456.89  5231.9  460.02  5241.9  460.78  5249.4  462.92  5251.9  462.92
#Mann=4,-1,0
  4843.8    0.16       0  4923.3    0.12       0  4988.3    0.07       0
  4994.3    0.12       0
Bank Sta=4988.3,4994.3
Exp/Cntr=0.3,0.1

Type RM Length L Ch R = 1,451,386,386,386
BEGIN DESCRIPTION:
Mapping XS ba8ebaf2
END DESCRIPTION:
XS GIS Cut Line= 3
      3728604.89     10731315.83      3728747.25     10731590.13
      3729049.30     10731680.40
#Sta/Elev= 30
  4765.3  456.82  4786.8  455.01  4803.2  450.91  4808.9  451.73  4815.3  449.92
  4831.0  448.67  4837.8  446.04  4860.3  441.61  4875.2  440.54  4891.7  435.64
  4897.4  435.50  4905.4  433.06  4919.5  431.71  4927.9  429.64  4950.5  426.76
  4973.0  425.73  4991.9  426.51  4999.3  425.69  5002.1  425.19  5005.3  425.69
  5008.0  427.39  5030.1  428.81  5097.7  430.39  5125.4  433.38  5163.7  435.33
  5212.5  441.38  5229.9  444.59  5235.1  443.82  5254.2  445.80  5389.6  461.67
#Mann=4,-1,0
  4765.3    0.16       0  4991.9    0.12       0  4999.3    0.07       0
  5005.3    0.12       0
Bank Sta=4999.3,5005.3
Exp/Cntr=0.3,0.1

Type RM Length L Ch R = 1,65,0,0,0
BEGIN DESCRIPTION:
UNT 080 IN CACR 1.0
END DESCRIPTION:
XS GIS Cut Line= 4
      3728361.83     10731392.23      3728379.20     10731718.61
      3728441.70     10731767.22      3728993.78     10731794.99
#Sta/Elev= 30
  4623.1  451.83  4631.1  450.07  4651.1  447.68  4661.1  447.55  4681.1  443.41
  4741.2  434.71  4751.2  432.02  4841.4  422.79  4860.0  421.63  4881.4  422.88
  5011.8  420.16  5014.6  419.66  5017.8  420.16  5067.1  421.24  5167.2  421.15
  5207.3  422.16  5277.3  426.01  5287.4  425.81  5317.4  429.88  5343.1  431.99
  5346.7  432.32  5357.4  433.99  5384.6  435.51  5389.6  437.03  5437.5  442.81
  5447.6  444.98  5497.6  450.08  5537.7  455.12  5567.7  460.62  5581.9  461.37
#Mann=5,-1,0
  4623.1    0.12       0  5011.8    0.07       0  5017.8    0.12       0
  5343.1    0.16       0  5346.7    0.12       0
Bank Sta=5011.8,5017.8
Exp/Cntr=0.3,0.1

Chan Stop Cuts=-1