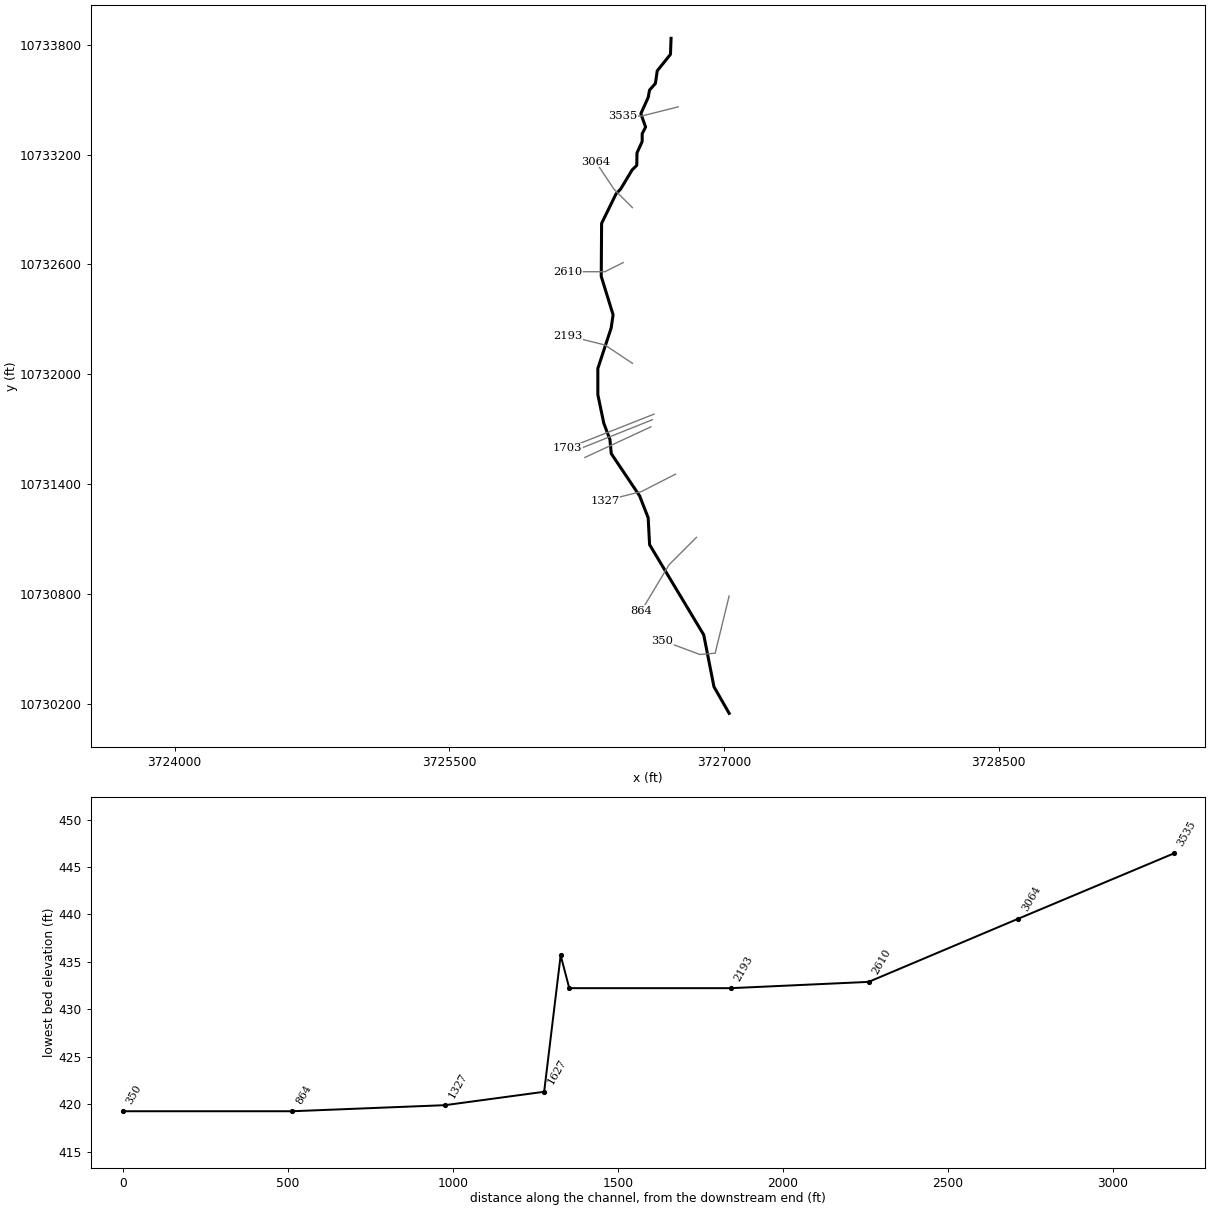
--- UNT 081 IN CACR.prj (project) ---

Proj Title=UNT 081 IN CACR Base Level Engineering
Current Plan=p01
Default Exp/Contr=0.3,0.1
English Units
Geom File=g01
Flow File=f01
Plan File=p01
BEGIN DESCRIPTION:
UNT 081 IN CACR
END DESCRIPTION:

--- UNT 081 IN CACR.p01 (plan) ---

Plan Title=Multiple Run
Short Identifier=Multiple
Geom File=g01
Flow File=f01
Subcritical Flow
K Sum by GR= 0
Std Step Tol= 0.01
Critical Tol= 0.01
Num of Std Step Trials= 20
Max Error Tol= 0.3
Flow Tol Ratio= 0.001
Split Flow NTrial= 30
Split Flow Tol= 0.02
Split Flow Ratio= 0.02
Log Output Level= 0
Friction Slope Method= 1
Unsteady Friction Slope Method= 2
Unsteady Bridges Friction Slope Method= 1
Parabolic Critical Depth
Global Vel Dist=  1 , 1 , 1
Global Log Level= 0
CheckData=True
Encroach Param= -1, 0, 0, 0
BEGIN DESCRIPTION:
Multiple Run
END DESCRIPTION:

--- UNT 081 IN CACR.f01 (steady flow) ---

Flow Title=Multiple
Number of Profiles=7
Profile Names=10-year,25-year,50-year,1pct_min,100-year,1pct_plu,500-year
River Rch & RM= UNT 081 IN CACR,Reach-1,3535
     432     574     688     608     822    1111    1171
Boundary for River Rch & Prof#=UNT 081 IN CACR,Reach-1,1
Up Type=0
Dn Type=3
Dn Slope=0.005
Boundary for River Rch & Prof#=UNT 081 IN CACR,Reach-1,2
Up Type=0
Dn Type=3
Dn Slope=0.005
Boundary for River Rch & Prof#=UNT 081 IN CACR,Reach-1,3
Up Type=0
Dn Type=3
Dn Slope=0.005
Boundary for River Rch & Prof#=UNT 081 IN CACR,Reach-1,4
Up Type=0
Dn Type=3
Dn Slope=0.005
Boundary for River Rch & Prof#=UNT 081 IN CACR,Reach-1,5
Up Type=0
Dn Type=3
Dn Slope=0.005
Boundary for River Rch & Prof#=UNT 081 IN CACR,Reach-1,6
Up Type=0
Dn Type=3
Dn Slope=0.005
Boundary for River Rch & Prof#=UNT 081 IN CACR,Reach-1,7
Up Type=0
Dn Type=3
Dn Slope=0.005

--- UNT 081 IN CACR.g01 (geometry) ---

Geom Title=Existing Conditions

River Reach=UNT 081 IN CACR,Reach-1
Reach XY= 30
      3726710.68     10733834.37      3726707.50     10733747.00
      3726635.25     10733657.00      3726625.25     10733588.00
      3726593.25     10733552.00      3726586.00     10733512.00
      3726545.75     10733423.00      3726571.75     10733350.00
      3726553.25     10733314.00      3726553.00     10733271.00
      3726524.75     10733209.00      3726523.50     10733141.00
      3726498.25     10733116.00      3726435.75     10733012.00
      3726410.25     10732985.00      3726331.50     10732824.00
      3726329.50     10732535.00      3726394.25     10732325.00
      3726383.75     10732253.00      3726311.00     10732032.00
      3726311.00     10731889.00      3726343.50     10731733.00
      3726377.00     10731644.00      3726384.25     10731567.00
      3726538.75     10731337.00      3726585.75     10731217.00
      3726593.50     10731070.00      3726889.00     10730578.00
      3726945.00     10730294.00      3727028.00     10730149.00

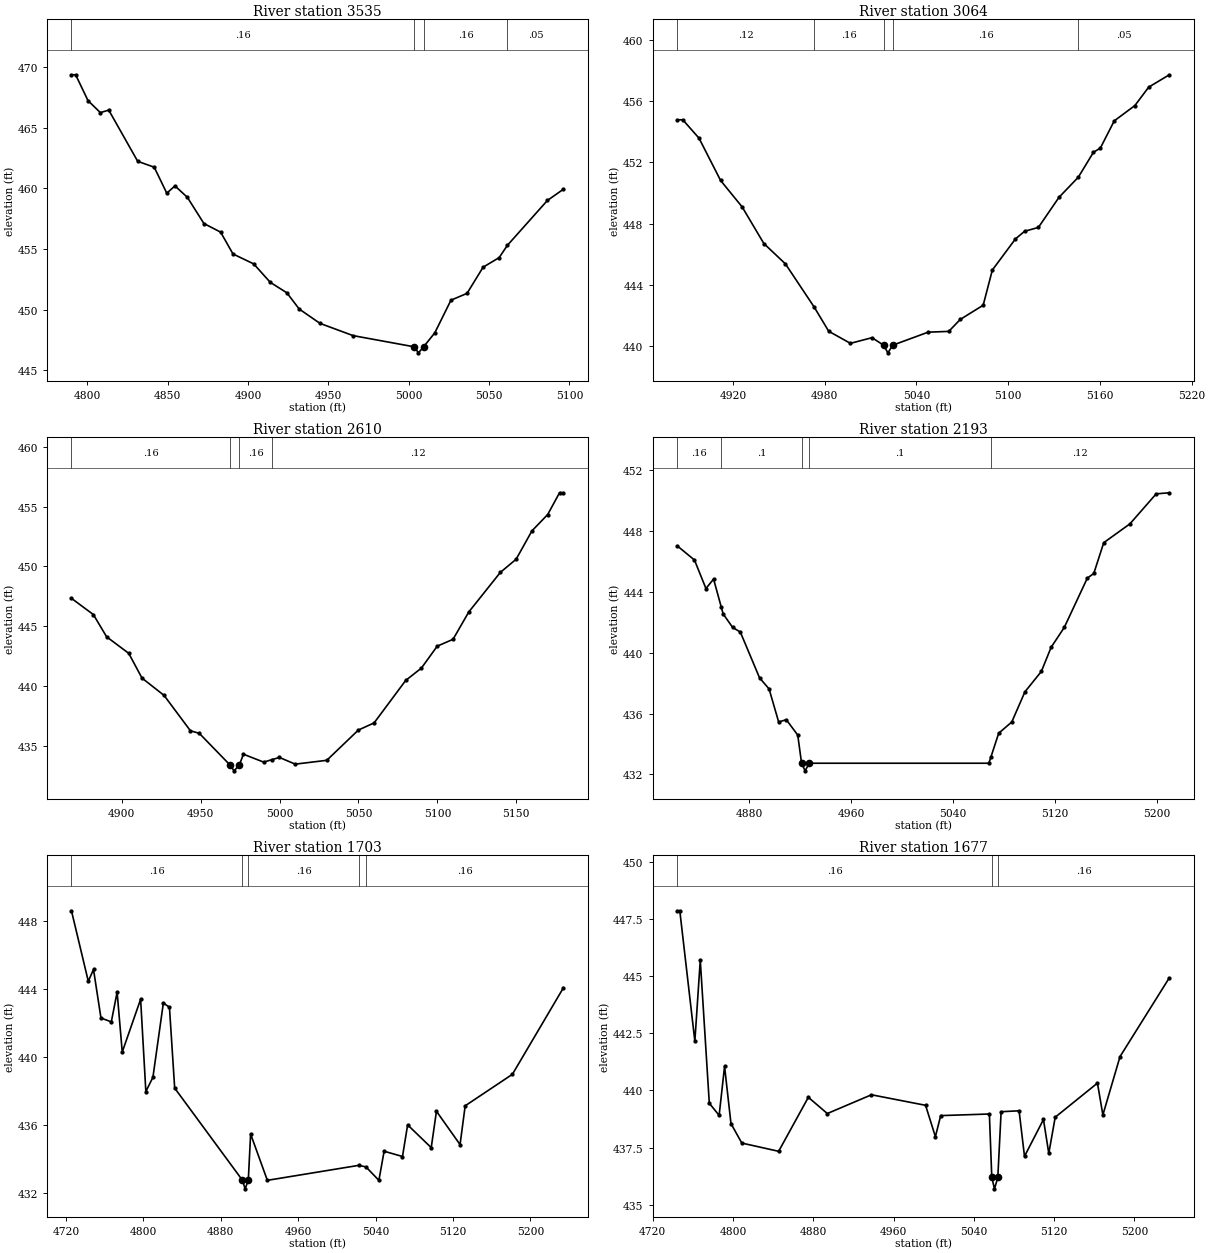
Type RM Length L Ch R = 1,3535,471,471,471
BEGIN DESCRIPTION:
UNT 081 IN CACR 8.0
END DESCRIPTION:
XS GIS Cut Line= 3
      3726749.60     10733460.19      3726549.61     10733410.19
      3726449.65     10733410.19
#Sta/Elev= 30
  4790.2  469.35  4792.8  469.35  4800.5  467.22  4808.2  466.23  4813.4  466.44
  4831.4  462.22  4841.7  461.73  4849.5  459.59  4854.6  460.19  4862.3  459.25
  4872.6  457.09  4883.0  456.38  4890.7  454.58  4903.6  453.76  4913.9  452.24
  4924.2  451.38  4931.9  450.04  4944.8  448.86  4965.4  447.85  5003.3  446.93
  5006.1  446.43  5009.3  446.93  5016.3  448.09  5026.3  450.77  5036.3  451.33
  5046.3  453.49  5056.3  454.28  5061.4  455.29  5086.3  458.99  5096.3  459.92
#Mann=4,-1,0
  4790.2    0.16       0  5003.3    0.07       0  5009.3    0.16       0
  5061.4    0.05       0
Bank Sta=5003.3,5009.3
Exp/Cntr=0.3,0.1

Type RM Length L Ch R = 1,3064,454,454,454
BEGIN DESCRIPTION:
UNT 081 IN CACR 7.0
END DESCRIPTION:
XS GIS Cut Line= 3
      3726499.62     10732910.17      3726399.61     10733010.19
      3726299.62     10733160.17
#Sta/Elev= 30
  4883.6  454.78  4887.2  454.78  4897.8  453.58  4911.9  450.82  4926.0  449.09
  4940.2  446.70  4954.3  445.37  4973.1  442.55  4982.6  440.97  4996.8  440.18
  5010.9  440.55  5018.5  440.06  5021.3  439.56  5024.5  440.06  5047.6  440.91
  5061.1  440.96  5068.6  441.74  5083.6  442.67  5089.6  444.97  5104.7  447.00
  5110.7  447.50  5119.7  447.75  5133.2  449.72  5145.8  451.03  5155.7  452.66
  5160.2  452.93  5169.3  454.71  5182.8  455.71  5191.8  456.91  5205.3  457.72
#Mann=5,-1,0
  4883.6    0.12       0  4973.1    0.16       0  5018.5    0.07       0
  5024.5    0.16       0  5145.8    0.05       0
Bank Sta=5018.5,5024.5
Exp/Cntr=0.3,0.1

Type RM Length L Ch R = 1,2610,417,417,417
BEGIN DESCRIPTION:
UNT 081 IN CACR 6.0
END DESCRIPTION:
XS GIS Cut Line= 3
      3726449.58     10732610.17      3726349.61     10732560.19
      3726149.58     10732560.19
#Sta/Elev= 30
  4868.1  447.33  4882.0  445.97  4890.4  444.11  4904.4  442.73  4912.8  440.66
  4926.8  439.21  4943.5  436.25  4949.1  436.04  4968.5  433.40  4971.2  432.90
  4974.5  433.40  4977.1  434.29  4989.9  433.63  4995.0  433.83  4999.9  434.02
  5009.9  433.46  5029.9  433.78  5049.9  436.31  5059.9  436.91  5079.9  440.46
  5089.9  441.50  5099.9  443.33  5109.9  443.90  5119.9  446.19  5139.9  449.50
  5149.9  450.60  5159.9  452.97  5169.9  454.34  5177.4  456.16  5179.9  456.16
#Mann=4,-1,0
  4868.1    0.16       0  4968.5    0.07       0  4974.5    0.16       0
  4995.0    0.12       0
Bank Sta=4968.5,4974.5
Exp/Cntr=0.3,0.1

Type RM Length L Ch R = 1,2193,490,490,490
BEGIN DESCRIPTION:
UNT 081 IN CACR 5.0
END DESCRIPTION:
XS GIS Cut Line= 3
      3726499.58     10732060.21      3726349.61     10732160.19
      3726149.60     10732210.19
#Sta/Elev= 30
  4823.3  447.02  4836.8  446.09  4845.8  444.22  4851.8  444.84  4857.9  442.98
  4859.3  442.55  4866.8  441.66  4872.8  441.36  4887.9  438.35  4895.4  437.62
  4902.9  435.45  4908.9  435.60  4917.9  434.59  4920.9  432.74  4923.7  432.24
  4926.9  432.74  5068.0  432.74  5069.5  433.12  5075.7  434.71  5086.0  435.45
  5096.3  437.43  5109.2  438.77  5116.9  440.36  5127.2  441.66  5145.3  444.90
  5150.4  445.21  5158.2  447.23  5178.8  448.47  5199.4  450.44  5209.7  450.51
#Mann=5,-1,0
  4823.3    0.16       0  4857.9     0.1       0  4920.9    0.07       0
  4926.9     0.1       0  5069.5    0.12       0
Bank Sta=4920.9,4926.9
Exp/Cntr=0.3,0.1

Type RM Length L Ch R = 1,1703,26,26,26
BEGIN DESCRIPTION:
UNT 081 IN CACR 4.0
END DESCRIPTION:
XS GIS Cut Line= 2
      3726617.95     10731782.71      3726144.83     10731596.07
#Sta/Elev= 30
  4725.6  448.58  4743.0  444.44  4748.4  445.13  4756.1  442.28  4766.8  442.05
  4772.8  443.80  4778.1  440.28  4797.1  443.38  4802.5  437.96  4809.8  438.79
  4820.6  443.16  4826.9  442.91  4832.3  438.16  4902.4  432.74  4905.1  432.24
  4908.4  432.74  4910.8  435.46  4928.1  432.74  5022.6  433.62  5030.0  433.53
  5043.4  432.74  5048.8  434.45  5067.8  434.14  5073.1  436.00  5097.5  434.66
  5102.9  436.80  5127.3  434.84  5132.6  437.12  5181.4  438.97  5234.2  444.06
#Mann=5,-1,0
  4725.6    0.16       0  4902.4    0.07       0  4908.4    0.16       0
  5022.6    0.05       0  5030.0    0.16       0
Bank Sta=4902.4,4908.4
Exp/Cntr=0.3,0.1

Type RM Length L Ch R = 1,1677,50,50,50
BEGIN DESCRIPTION:
Mapping XS 4cb5597f
END DESCRIPTION:
XS GIS Cut Line= 2
      3726609.27     10731752.33      3726154.04     10731570.24
#Sta/Elev= 30
  4744.4  447.85  4746.9  447.85  4761.9  442.15  4767.3  445.69  4776.3  439.44
  4786.1  438.91  4791.5  441.05  4797.9  438.55  4808.7  437.70  4845.4  437.34
  4875.0  439.70  4893.9  438.99  4937.9  439.81  4991.8  439.35  5001.6  437.98
  5006.9  438.90  5055.4  438.97  5057.8  436.20  5060.5  435.70  5063.8  436.20
  5067.1  439.07  5085.0  439.11  5090.4  437.12  5109.3  438.73  5114.6  437.25
  5121.0  438.83  5163.1  440.32  5168.5  438.93  5185.6  441.48  5234.7  444.92
#Mann=3,-1,0
  4744.4    0.16       0  5057.8    0.07       0  5063.8    0.16       0
Bank Sta=5057.8,5063.8
Exp/Cntr=0.3,0.1

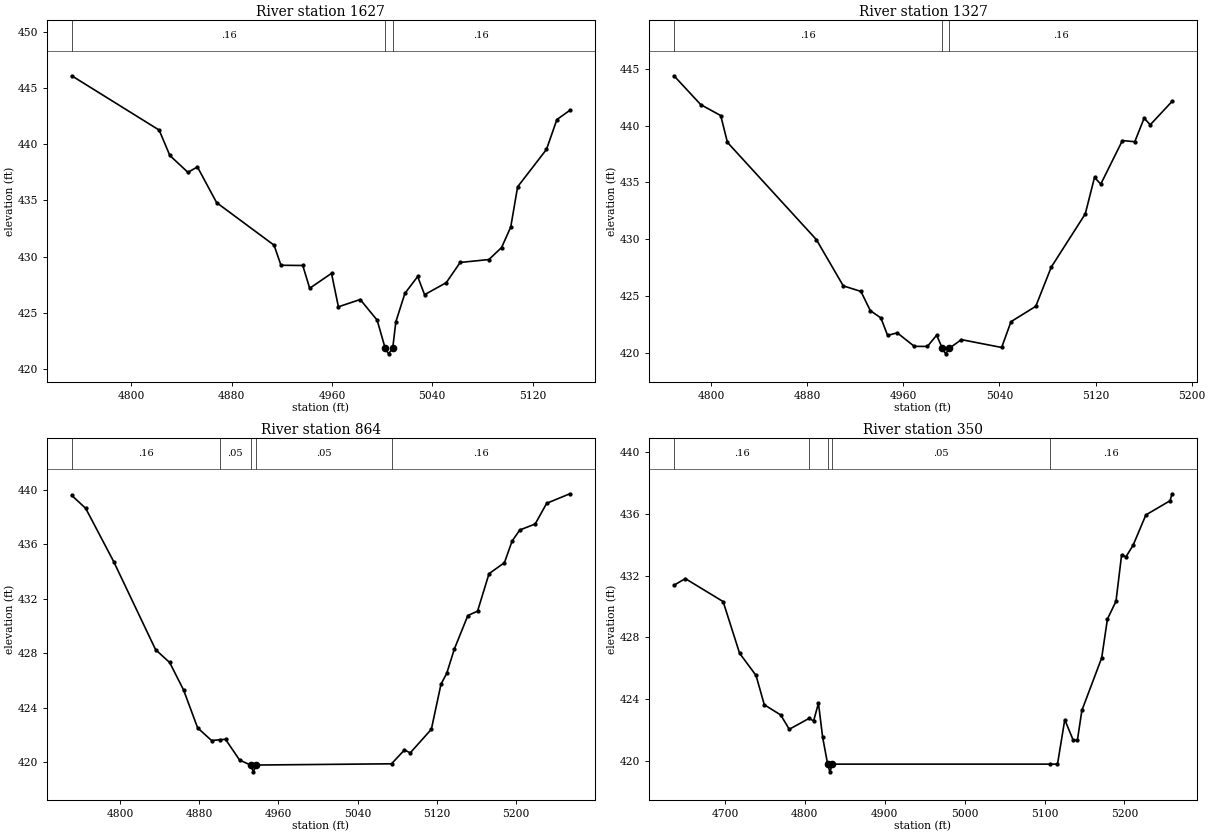
Type RM Length L Ch R = 1,1627,300,300,300
BEGIN DESCRIPTION:
Mapping XS 6cde66f3
END DESCRIPTION:
XS GIS Cut Line= 2
      3726600.51     10731713.24      3726240.28     10731546.14
#Sta/Elev= 30
  4752.6  446.10  4822.3  441.26  4830.8  439.00  4845.2  437.50  4852.8  437.98
  4868.1  434.80  4913.9  431.01  4919.4  429.22  4936.8  429.20  4942.3  427.17
  4959.7  428.50  4965.2  425.52  4982.6  426.17  4996.1  424.33  5002.5  421.83
  5005.2  421.33  5008.5  421.83  5011.0  424.18  5018.2  426.71  5028.4  428.22
  5033.9  426.60  5051.2  427.67  5062.3  429.47  5085.2  429.73  5095.3  430.80
  5102.6  432.62  5108.1  436.21  5131.1  439.54  5139.4  442.20  5149.7  443.02
#Mann=3,-1,0
  4752.6    0.16       0  5002.5    0.07       0  5008.5    0.16       0
Bank Sta=5002.5,5008.5
Exp/Cntr=0.3,0.1

Type RM Length L Ch R = 1,1327,463,463,463
BEGIN DESCRIPTION:
UNT 081 IN CACR 3.0
END DESCRIPTION:
XS GIS Cut Line= 3
      3726735.08     10731455.00      3726549.61     10731360.19
      3726349.57     10731310.18
#Sta/Elev= 30
  4769.1  444.38  4791.4  441.84  4808.0  440.88  4813.6  438.52  4887.6  429.97
  4910.0  425.90  4924.7  425.41  4932.5  423.72  4941.3  423.08  4946.9  421.54
  4954.9  421.77  4969.1  420.58  4980.0  420.57  4987.7  421.56  4992.4  420.42
  4995.2  419.92  4998.4  420.42  5008.3  421.17  5041.8  420.48  5049.6  422.75
  5070.2  424.10  5083.1  427.55  5111.4  432.23  5119.1  435.44  5124.3  434.85
  5142.3  438.68  5152.6  438.58  5160.4  440.65  5165.5  440.07  5183.6  442.12
#Mann=3,-1,0
  4769.1    0.16       0  4992.4    0.07       0  4998.4    0.16       0
Bank Sta=4992.4,4998.4
Exp/Cntr=0.3,0.1

Type RM Length L Ch R = 1,864,514,514,514
BEGIN DESCRIPTION:
UNT 081 IN CACR 2.0
END DESCRIPTION:
XS GIS Cut Line= 3
      3726849.59     10731110.17      3726699.61     10730960.19
      3726549.58     10730710.15
#Sta/Elev= 30
  4751.0  439.58  4765.1  438.63  4793.4  434.72  4835.8  428.25  4850.0  427.31
  4864.1  425.29  4878.3  422.51  4892.4  421.58  4901.1  421.64  4906.5  421.67
  4920.7  420.15  4931.8  419.78  4934.6  419.28  4937.8  419.78  5074.4  419.87
  5087.5  420.89  5093.3  420.67  5114.7  422.41  5124.4  425.71  5130.3  426.53
  5138.0  428.31  5151.6  430.76  5161.4  431.08  5173.0  433.83  5188.6  434.64
  5196.3  436.22  5204.1  437.04  5219.7  437.48  5231.3  439.00  5254.7  439.70
#Mann=5,-1,0
  4751.0    0.16       0  4901.1    0.05       0  4931.8   0.033       0
  4937.8    0.05       0  5074.4    0.16       0
Bank Sta=4931.8,4937.8
Exp/Cntr=0.3,0.1

Type RM Length L Ch R = 1,350,0,0,0
BEGIN DESCRIPTION:
UNT 081 IN CACR 1.0
END DESCRIPTION:
XS GIS Cut Line= 4
      3727027.77     10730789.92      3726951.39     10730477.43
      3726868.06     10730470.49      3726663.89     10730546.61
#Sta/Elev= 30
  4636.3  431.38  4650.5  431.81  4697.8  430.32  4718.4  426.97  4739.0  425.53
  4749.3  423.63  4769.8  422.97  4780.6  422.04  4805.5  422.75  4811.0  422.58
  4817.1  423.73  4822.3  421.53  4828.6  419.78  4831.4  419.28  4834.6  419.78
  5106.5  419.78  5116.2  419.78  5125.3  422.66  5135.8  421.34  5141.1  421.33
  5146.7  423.26  5171.5  426.67  5178.7  429.19  5189.4  430.34  5196.4  433.34
  5201.8  433.22  5210.7  433.96  5226.8  435.94  5257.1  436.86  5259.5  437.31
#Mann=5,-1,0
  4636.3    0.16       0  4805.5    0.05       0  4828.6   0.033       0
  4834.6    0.05       0  5106.5    0.16       0
Bank Sta=4828.6,4834.6
Exp/Cntr=0.3,0.1

Chan Stop Cuts=-1