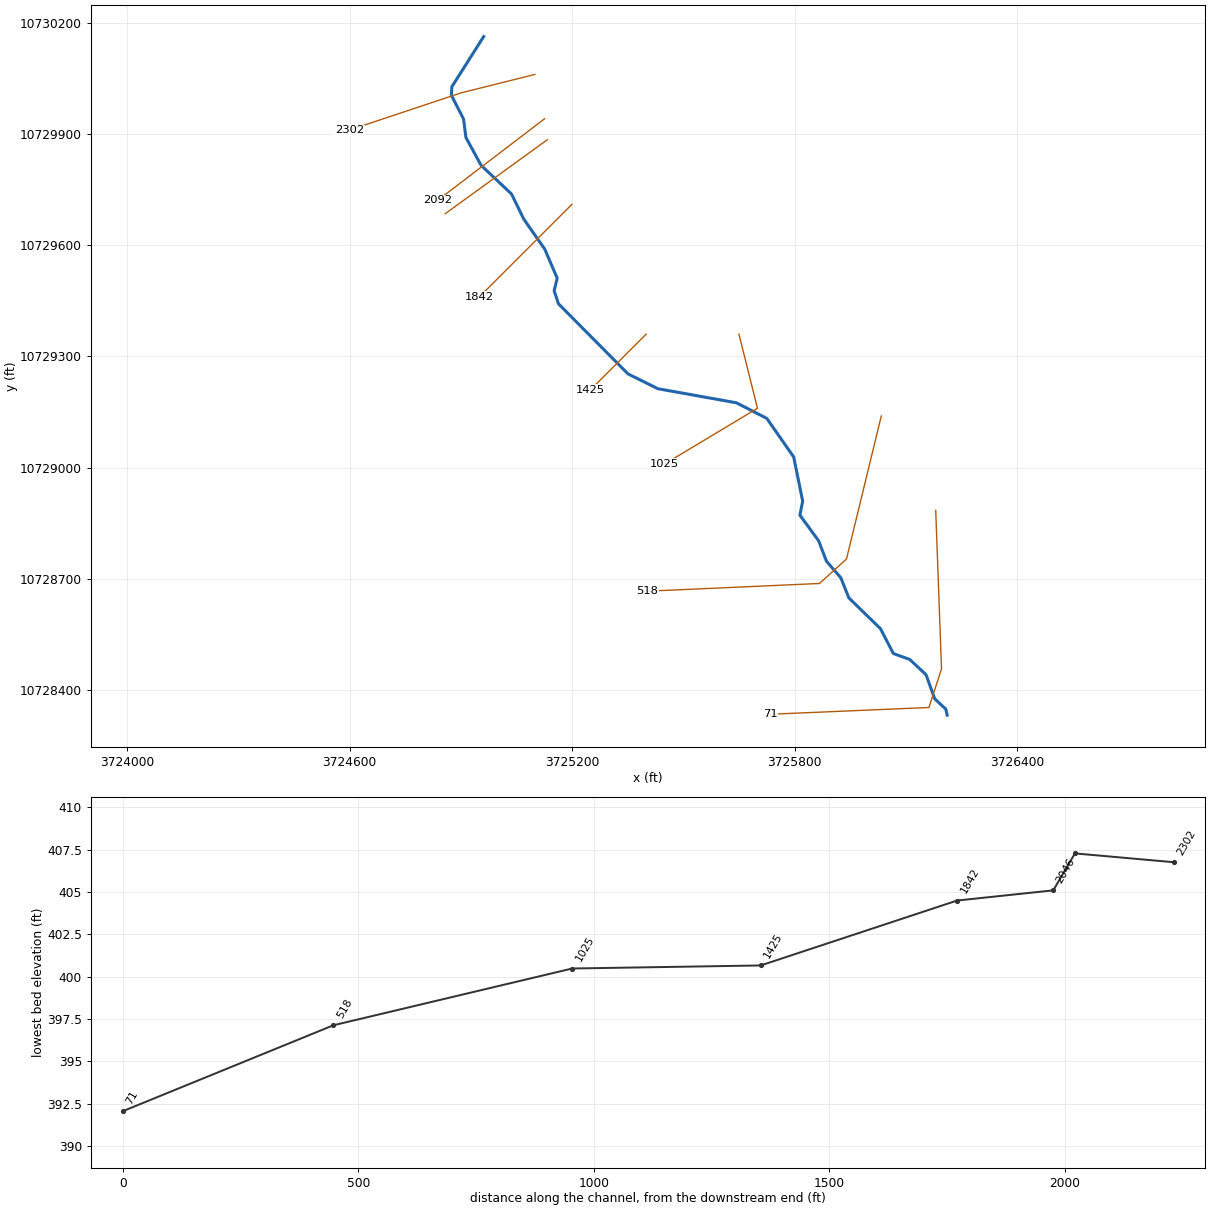
--- UNT 082 IN CACR.prj (project) ---

Proj Title=UNT 082 IN CACR Base Level Engineering
Current Plan=p01
Default Exp/Contr=0.3,0.1
English Units
Geom File=g01
Flow File=f01
Plan File=p01
BEGIN DESCRIPTION:
UNT 082 IN CACR
END DESCRIPTION:

--- UNT 082 IN CACR.p01 (plan) ---

Plan Title=Multiple Run
Short Identifier=Multiple
Geom File=g01
Flow File=f01
Subcritical Flow
K Sum by GR= 0
Std Step Tol= 0.01
Critical Tol= 0.01
Num of Std Step Trials= 20
Max Error Tol= 0.3
Flow Tol Ratio= 0.001
Split Flow NTrial= 30
Split Flow Tol= 0.02
Split Flow Ratio= 0.02
Log Output Level= 0
Friction Slope Method= 1
Unsteady Friction Slope Method= 2
Unsteady Bridges Friction Slope Method= 1
Parabolic Critical Depth
Global Vel Dist=  1 , 1 , 1
Global Log Level= 0
CheckData=True
Encroach Param= -1, 0, 0, 0
BEGIN DESCRIPTION:
Multiple Run
END DESCRIPTION:

--- UNT 082 IN CACR.f01 (steady flow) ---

Flow Title=Multiple
Number of Profiles=7
Profile Names=10-year,25-year,50-year,1pct_min,100-year,1pct_plu,500-year
River Rch & RM= UNT 082 IN CACR,Reach-1,2302
     478     641     774     688     930    1258    1342
Boundary for River Rch & Prof#=UNT 082 IN CACR,Reach-1,1
Up Type=0
Dn Type=3
Dn Slope=0.005
Boundary for River Rch & Prof#=UNT 082 IN CACR,Reach-1,2
Up Type=0
Dn Type=3
Dn Slope=0.005
Boundary for River Rch & Prof#=UNT 082 IN CACR,Reach-1,3
Up Type=0
Dn Type=3
Dn Slope=0.005
Boundary for River Rch & Prof#=UNT 082 IN CACR,Reach-1,4
Up Type=0
Dn Type=3
Dn Slope=0.005
Boundary for River Rch & Prof#=UNT 082 IN CACR,Reach-1,5
Up Type=0
Dn Type=3
Dn Slope=0.005
Boundary for River Rch & Prof#=UNT 082 IN CACR,Reach-1,6
Up Type=0
Dn Type=3
Dn Slope=0.005
Boundary for River Rch & Prof#=UNT 082 IN CACR,Reach-1,7
Up Type=0
Dn Type=3
Dn Slope=0.005

--- UNT 082 IN CACR.g01 (geometry) ---

Geom Title=Existing Conditions

River Reach=UNT 082 IN CACR,Reach-1
Reach XY= 30
      3724961.52     10730162.25      3724875.75     10730027.00
      3724874.50     10730004.00      3724907.25     10729940.00
      3724913.75     10729890.00      3724954.75     10729815.00
      3725036.50     10729738.00      3725069.75     10729670.00
      3725126.25     10729589.00      3725159.75     10729511.00
      3725151.50     10729477.00      3725163.00     10729442.00
      3725350.50     10729253.00      3725431.00     10729213.00
      3725642.75     10729175.00      3725724.75     10729133.00
      3725797.25     10729029.00      3725821.50     10728910.00
      3725814.00     10728872.00      3725864.50     10728803.00
      3725885.50     10728748.00      3725924.50     10728703.00
      3725946.00     10728649.00      3726031.25     10728566.00
      3726066.00     10728499.00      3726110.25     10728483.00
      3726154.00     10728442.00      3726177.50     10728377.00
      3726207.50     10728349.00      3726211.00     10728333.00

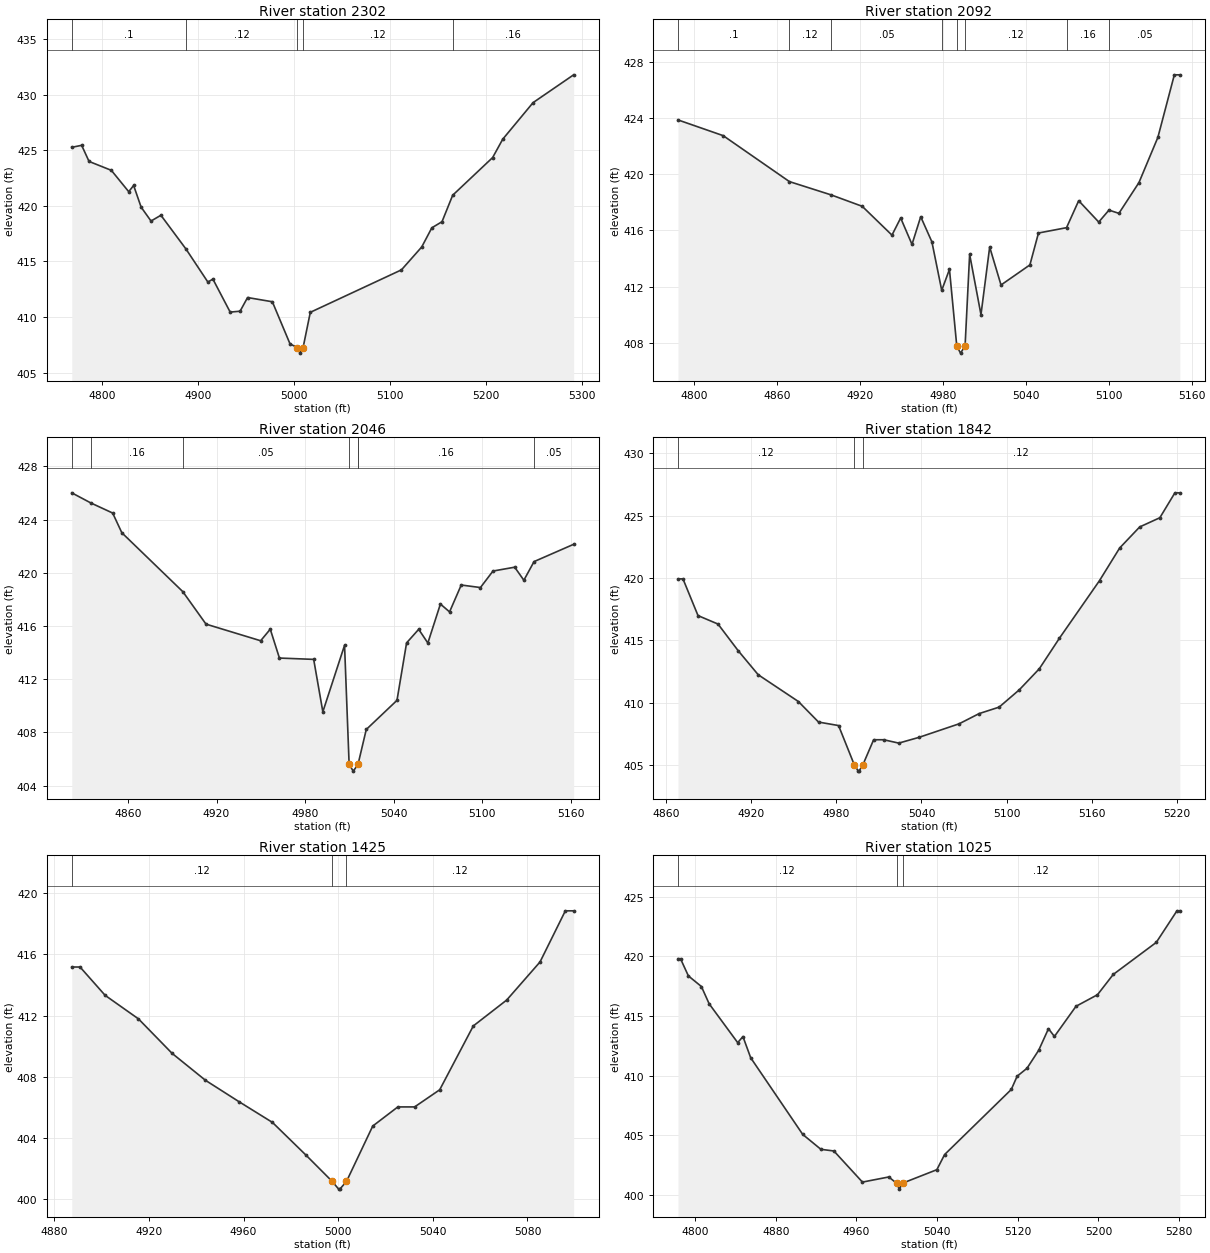
Type RM Length L Ch R = 1,2302,210,210,210
BEGIN DESCRIPTION:
UNT 082 IN CACR 5.0
END DESCRIPTION:
XS GIS Cut Line= 3
      3725099.61     10730060.19      3724899.61     10730010.19
      3724599.60     10729910.18
#Sta/Elev= 30
  4768.6  425.26  4778.9  425.44  4786.6  423.99  4809.8  423.19  4827.9  421.27
  4833.0  421.83  4840.8  419.88  4851.1  418.63  4861.4  419.15  4887.6  416.10
  4910.3  413.14  4915.5  413.41  4933.5  410.44  4943.8  410.52  4951.6  411.75
  4977.4  411.37  4995.8  407.58  5003.4  407.25  5006.1  406.75  5009.4  407.25
  5016.9  410.42  5111.8  414.24  5132.9  416.30  5143.4  418.02  5154.0  418.57
  5165.1  420.95  5206.7  424.34  5217.2  425.99  5248.8  429.28  5291.0  431.78
#Mann=5,-1,0
  4768.6     0.1       0  4887.6    0.12       0  5003.4    0.07       0
  5009.4    0.12       0  5165.1    0.16       0
Bank Sta=5003.4,5009.4
Exp/Cntr=0.3,0.1

Type RM Length L Ch R = 1,2092,46,46,46
BEGIN DESCRIPTION:
Mapping XS 8fd7c782
END DESCRIPTION:
XS GIS Cut Line= 2
      3725125.60     10729940.66      3724836.96     10729720.38
#Sta/Elev= 30
  4788.4  423.87  4821.1  422.75  4869.0  419.48  4899.3  418.53  4921.7  417.72
  4943.2  415.67  4949.5  416.89  4957.7  415.01  4964.0  416.98  4972.1  415.19
  4979.2  411.74  4984.8  413.23  4990.1  407.77  4992.8  407.27  4996.1  407.77
  4999.4  414.30  5007.6  410.01  5013.9  414.82  5022.1  412.12  5043.0  413.55
  5049.2  415.82  5069.5  416.20  5078.3  418.12  5092.8  416.60  5100.2  417.45
  5107.4  417.22  5121.9  419.41  5135.6  422.63  5147.5  427.08  5151.5  427.08
#Mann=8,-1,0
  4788.4     0.1       0  4869.0    0.12       0  4899.3    0.05       0
  4979.2    0.12       0  4990.1    0.07       0  4996.1    0.12       0
  5069.5    0.16       0  5100.2    0.05       0
Bank Sta=4990.1,4996.1
Exp/Cntr=0.3,0.1

Type RM Length L Ch R = 1,2046,204,204,204
BEGIN DESCRIPTION:
Mapping XS 386b5334
END DESCRIPTION:
XS GIS Cut Line= 2
      3725133.19     10729884.23      3724858.01     10729684.88
#Sta/Elev= 30
  4822.0  426.01  4834.9  425.25  4849.7  424.49  4855.9  423.01  4897.2  418.58
  4912.9  416.14  4949.9  414.89  4956.4  415.76  4962.6  413.59  4985.8  413.49
  4992.0  409.55  5006.7  414.55  5009.8  405.59  5012.6  405.09  5015.8  405.59
  5016.1  405.73  5021.4  408.22  5042.2  410.41  5048.7  414.73  5056.9  415.75
  5063.1  414.72  5071.6  417.65  5077.8  417.06  5085.7  419.08  5098.7  418.89
  5107.2  420.13  5121.9  420.42  5128.1  419.44  5135.0  420.84  5161.8  422.14
#Mann=7,-1,0
  4822.0     0.1       0  4834.9    0.16       0  4897.2    0.05       0
  5009.8    0.03       0  5015.8    0.05       0  5016.1    0.16       0
  5135.0    0.05       0
Bank Sta=5009.8,5015.8
Exp/Cntr=0.3,0.1

Type RM Length L Ch R = 1,1842,417,417,417
BEGIN DESCRIPTION:
UNT 082 IN CACR 4.0
END DESCRIPTION:
XS GIS Cut Line= 3
      3725199.58     10729710.16      3725099.61     10729610.19
      3724949.62     10729460.20
#Sta/Elev= 29
  4868.5  419.93  4872.0  419.93  4882.6  416.98  4896.7  416.30  4910.9  414.16
  4925.0  412.23  4953.3  410.08  4967.5  408.43  4981.6  408.15  4992.7  404.99
  4995.5  404.49  4996.0  404.49  4998.7  404.99  5006.3  407.01  5013.4  407.01
  5024.0  406.74  5038.2  407.20  5066.5  408.29  5080.6  409.11  5094.7  409.63
  5108.9  411.02  5123.0  412.71  5137.2  415.17  5165.4  419.79  5179.6  422.41
  5193.7  424.10  5207.9  424.84  5218.5  426.84  5222.0  426.84
#Mann=3,-1,0
  4868.5    0.12       0  4992.7    0.07       0  4998.7    0.12       0
Bank Sta=4992.7,4998.7
Exp/Cntr=0.3,0.1

Type RM Length L Ch R = 1,1425,400,400,400
BEGIN DESCRIPTION:
UNT 082 IN CACR 3.0
END DESCRIPTION:
XS GIS Cut Line= 3
      3725399.58     10729360.16      3725299.61     10729260.19
      3725249.60     10729210.18
#Sta/Elev= 22
  4887.4  415.17  4890.9  415.17  4901.5  413.32  4915.6  411.78  4929.8  409.53
  4943.9  407.77  4958.1  406.37  4972.2  405.02  4986.4  402.88  4997.5  401.16
  5000.2  400.66  5000.7  400.66  5003.5  401.16  5014.6  404.78  5025.2  406.03
  5032.3  406.03  5042.9  407.15  5057.1  411.32  5071.2  413.01  5085.3  415.50
  5096.0  418.84  5099.5  418.84
#Mann=3,-1,0
  4887.4    0.12       0  4997.5    0.07       0  5003.5    0.12       0
Bank Sta=4997.5,5003.5
Exp/Cntr=0.3,0.1

Type RM Length L Ch R = 1,1025,507,507,507
BEGIN DESCRIPTION:
UNT 082 IN CACR 2.0
END DESCRIPTION:
XS GIS Cut Line= 3
      3725649.62     10729360.16      3725699.61     10729160.19
      3725449.58     10729010.17
#Sta/Elev= 30
  4783.1  419.81  4785.6  419.81  4793.4  418.37  4806.3  417.48  4814.0  416.03
  4842.3  412.77  4847.5  413.28  4855.2  411.50  4906.8  405.07  4924.8  403.82
  4937.7  403.68  4966.0  401.07  4992.1  401.50  4999.8  400.98  5002.6  400.48
  5005.8  400.98  5039.8  402.11  5047.5  403.38  5113.6  408.84  5119.4  409.95
  5129.2  410.62  5140.8  412.13  5150.5  413.94  5156.4  413.29  5177.8  415.82
  5199.1  416.79  5214.7  418.49  5257.4  421.18  5277.9  423.83  5280.8  423.83
#Mann=3,-1,0
  4783.1    0.12       0  4999.8    0.07       0  5005.8    0.12       0
Bank Sta=4999.8,5005.8
Exp/Cntr=0.3,0.1

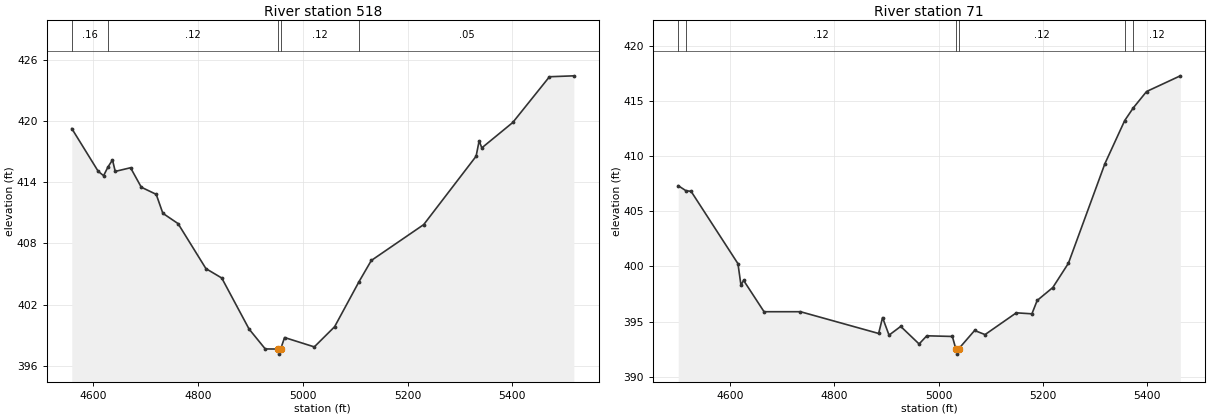
Type RM Length L Ch R = 1,518,447,447,447
BEGIN DESCRIPTION:
Mapping XS 6eea8f76
END DESCRIPTION:
XS GIS Cut Line= 4
      3726033.38     10729139.27      3725939.63     10728753.87
      3725866.72     10728687.90      3725403.05     10728667.14
#Sta/Elev= 30
  4558.6  419.27  4609.1  415.07  4619.4  414.64  4627.7  415.49  4636.4  416.19
  4641.6  415.06  4670.9  415.42  4691.4  413.51  4719.9  412.81  4732.6  410.95
  4761.6  409.94  4814.9  405.52  4845.1  404.60  4897.3  399.59  4928.2  397.64
  4951.6  397.63  4954.3  397.13  4957.6  397.63  4965.1  398.76  5021.9  397.84
  5060.7  399.82  5107.1  404.22  5130.8  406.32  5230.9  409.84  5331.0  416.55
  5336.8  418.06  5341.9  417.37  5401.0  419.86  5471.1  424.35  5517.7  424.44
#Mann=5,-1,0
  4558.6    0.16       0  4627.7    0.12       0  4951.6    0.07       0
  4957.6    0.12       0  5107.1    0.05       0
Bank Sta=4951.6,4957.6
Exp/Cntr=0.3,0.1

Type RM Length L Ch R = 1,71,0,0,0
BEGIN DESCRIPTION:
UNT 082 IN CACR 1.0
END DESCRIPTION:
XS GIS Cut Line= 4
      3726180.17     10728884.84      3726195.80     10728457.78
      3726161.94     10728353.61      3725734.91     10728335.38
#Sta/Elev= 30
  4499.9  407.31  4514.6  406.86  4524.6  406.80  4614.6  400.25  4620.4  398.30
  4625.4  398.74  4664.7  395.90  4734.7  395.90  4884.8  393.93  4892.3  395.37
  4904.8  393.78  4927.2  394.57  4962.5  392.98  4977.3  393.72  5026.4  393.66
  5032.9  392.56  5035.7  392.06  5038.9  392.56  5069.1  394.20  5089.2  393.83
  5149.2  395.80  5179.2  395.71  5189.3  396.92  5219.3  398.09  5249.3  400.29
  5319.4  409.31  5357.4  413.21  5373.9  414.36  5399.4  415.84  5464.2  417.26
#Mann=6,-1,0
  4499.9    0.16       0  4514.6    0.12       0  5032.9    0.07       0
  5038.9    0.12       0  5357.4    0.16       0  5373.9    0.12       0
Bank Sta=5032.9,5038.9
Exp/Cntr=0.3,0.1

Chan Stop Cuts=-1