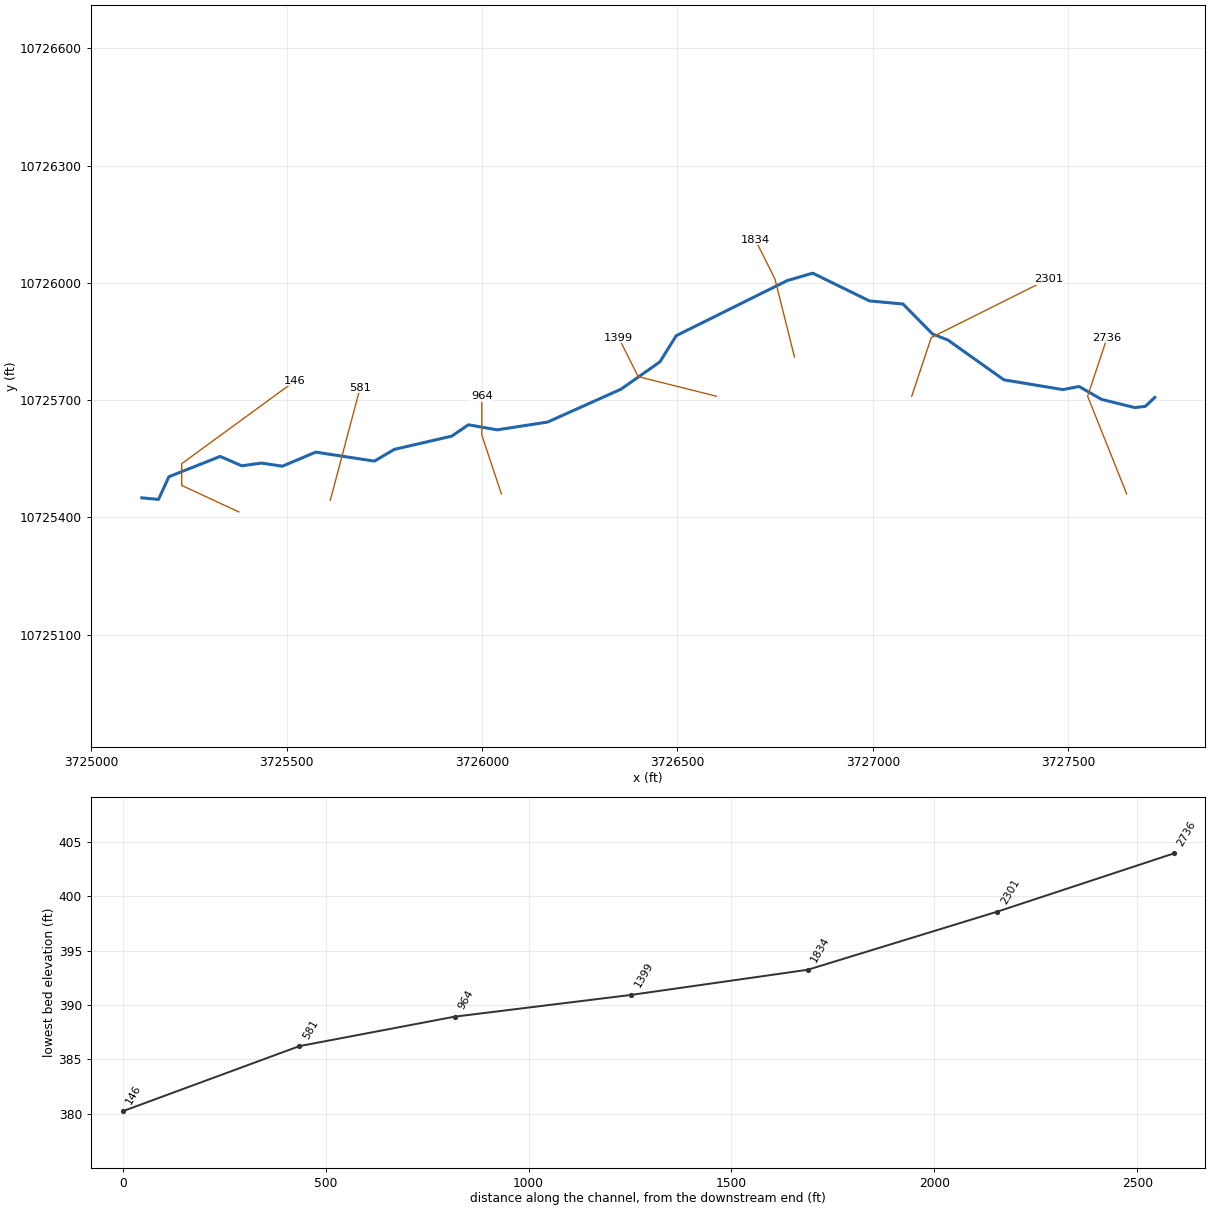
--- UNT 084 IN CACR.prj (project) ---

Proj Title=UNT 084 IN CACR Base Level Engineering
Current Plan=p01
Default Exp/Contr=0.3,0.1
English Units
Geom File=g01
Flow File=f01
Plan File=p01
Y Axis Title=Elevation
X Axis Title(PF)=Main Channel Distance
X Axis Title(XS)=Station
BEGIN DESCRIPTION:
UNT 084 IN CACR
END DESCRIPTION:
DSS Export Rating Curves= 0
DSS Export Rating Curve Sorted= 0
DSS Export Volume Flow Curves= 0
DXF OffsetX= 0
DXF OffsetY= 0
DXF ScaleX= 1
DXF ScaleY= 10

--- UNT 084 IN CACR.p01 (plan) ---

Plan Title=Multiple Run
Short Identifier=Multiple
Geom File=g01
Flow File=f01
Subcritical Flow
K Sum by GR= 0
Std Step Tol= 0.01
Critical Tol= 0.01
Num of Std Step Trials= 20
Max Error Tol= 0.3
Flow Tol Ratio= 0.001
Split Flow NTrial= 30
Split Flow Tol= 0.02
Split Flow Ratio= 0.02
Log Output Level= 0
Friction Slope Method= 1
Unsteady Friction Slope Method= 2
Unsteady Bridges Friction Slope Method= 1
Parabolic Critical Depth
Global Vel Dist=  1 , 1 , 1
Global Log Level= 0
CheckData=True
Encroach Param= -1, 0, 0, 0
BEGIN DESCRIPTION:
Multiple Run
END DESCRIPTION:

--- UNT 084 IN CACR.f01 (steady flow) ---

Flow Title=Multiple
Program Version=4.10
Number of Profiles= 7
Profile Names=10-year,25-year,50-year,1pct_min,100-year,1pct_plu,500-year
River Rch & RM=UNT 084 IN CACR,Reach-1         ,2736
     566     760     918     813    1100    1487    1582
River Rch & RM=UNT 084 IN CACR,Reach-1         ,146
    1814    2602    3284    3032    4101    5546    6412
Boundary for River Rch & Prof#=UNT 084 IN CACR,Reach-1         , 1
Up Type= 0
Dn Type= 3
Dn Slope=0.01373
Boundary for River Rch & Prof#=UNT 084 IN CACR,Reach-1         , 2
Up Type= 0
Dn Type= 3
Dn Slope=0.01373
Boundary for River Rch & Prof#=UNT 084 IN CACR,Reach-1         , 3
Up Type= 0
Dn Type= 3
Dn Slope=0.01373
Boundary for River Rch & Prof#=UNT 084 IN CACR,Reach-1         , 4
Up Type= 0
Dn Type= 3
Dn Slope=0.01373
Boundary for River Rch & Prof#=UNT 084 IN CACR,Reach-1         , 5
Up Type= 0
Dn Type= 3
Dn Slope=0.01373
Boundary for River Rch & Prof#=UNT 084 IN CACR,Reach-1         , 6
Up Type= 0
Dn Type= 3
Dn Slope=0.01373
Boundary for River Rch & Prof#=UNT 084 IN CACR,Reach-1         , 7
Up Type= 0
Dn Type= 3
Dn Slope=0.01373
DSS Import GetInterval= 0
DSS Import GetPeak= 0
DSS Import FillOption= 0

--- UNT 084 IN CACR.g01 (geometry) ---

Geom Title=Existing Conditions
Program Version=4.10

River Reach=UNT 084 IN CACR ,Reach-1
Reach XY= 30
       3727721.5       10725707.      3727697.25       10725684.
      3727670.25       10725681.      3727585.25       10725702.
      3727527.75       10725735.      3727486.25       10725727.
       3727335.5       10725752.        3727192.       10725854.
      3727153.25       10725869.      3727077.25       10725946.
      3726991.25       10725954.      3726846.25       10726025.
        3726781.       10726006.        3726497.       10725865.
      3726455.25       10725798.       3726355.5       10725728.
        3726168.       10725644.      3726038.75       10725624.
      3725965.25       10725637.      3725922.75       10725608.
      3725775.75       10725574.       3725724.5       10725544.
       3725574.5       10725567.      3725489.25       10725531.
      3725435.75       10725539.      3725385.25       10725532.
        3725330.       10725556.      3725198.75       10725504.
      3725172.25       10725446.       3725129.5       10725450.

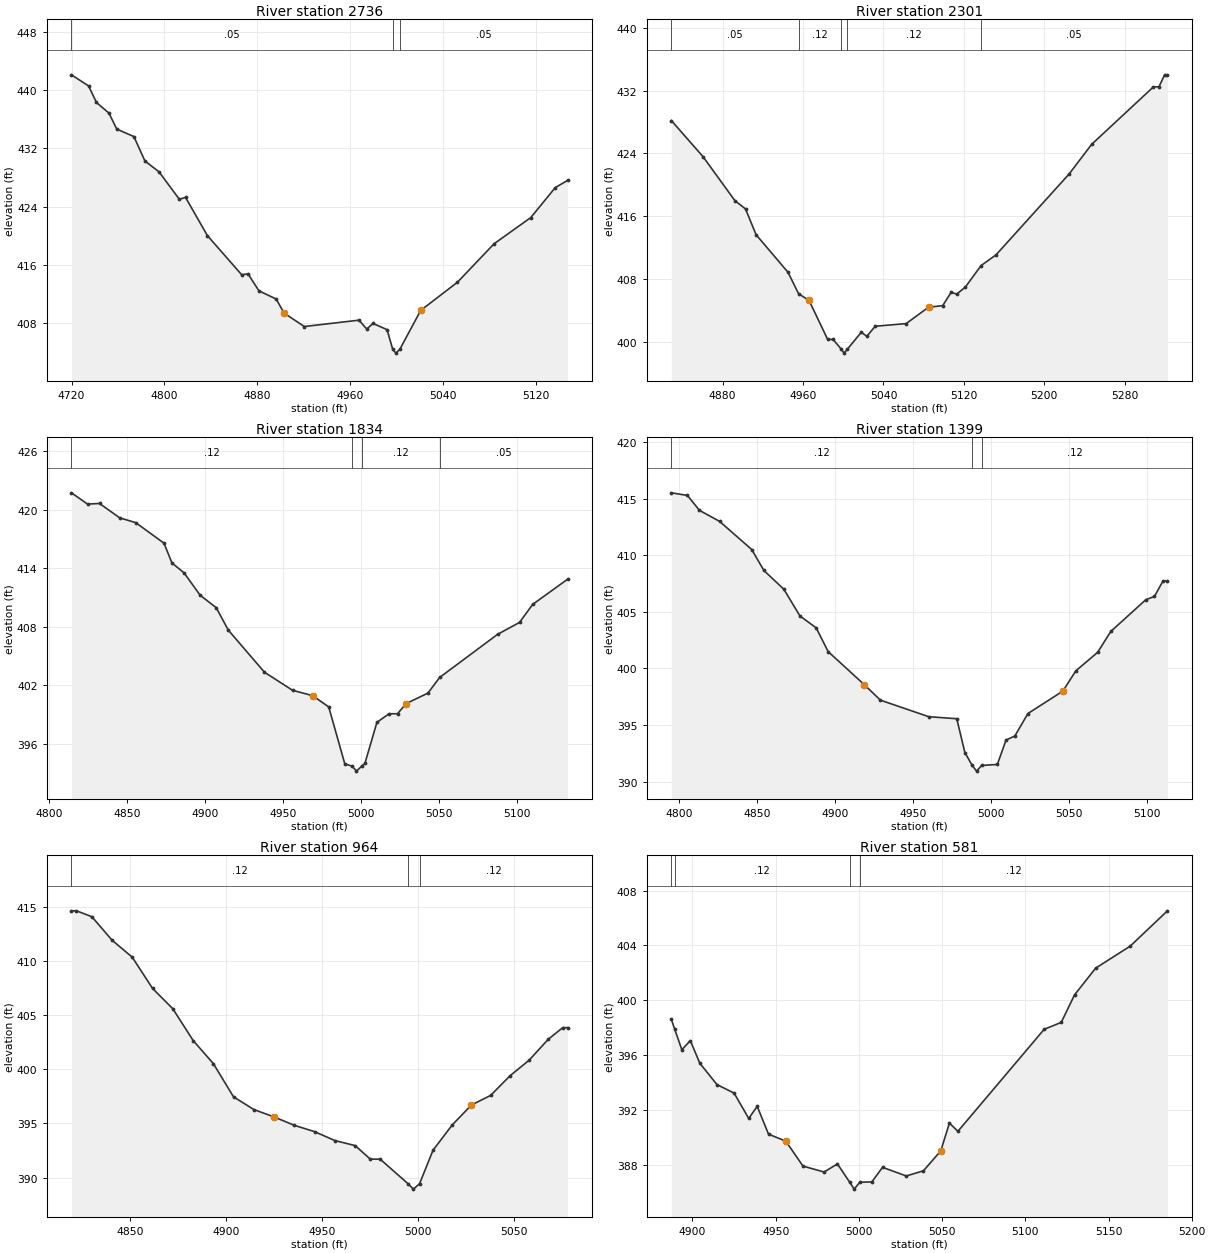
Type RM Length L Ch R = 1 ,2736    ,435,435,435
BEGIN DESCRIPTION:
UNT 084 IN CACR 6.0
END DESCRIPTION:
XS GIS Cut Line= 3
       3727649.6      10725460.2      3727549.61     10725710.19
      3727599.62     10725860.23
#Sta/Elev= 30
  4719.9   442.1  4734.7  440.57  4741.4  438.31  4752.2  436.85  4758.9  434.66
  4773.7  433.63  4783.2  430.28  4795.3   428.8  4812.8  425.04  4818.2  425.28
    4837  420.05  4866.6  414.67    4872  414.81  4881.4  412.47  4896.3  411.35
    4903  409.43  4920.5  407.58  4967.6  408.45  4974.3  407.24  4979.7     408
  4991.8  407.15  4996.7  404.43  4999.4  403.93  5002.7  404.43  5020.8  409.79
  5052.4  413.65    5084  418.93  5115.6  422.52  5136.7  426.63  5147.3  427.62
#Mann= 3 ,-1 , 0
  4719.9     .05       0  4996.7     .03       0  5002.7     .05       0
Bank Sta=4903,5020.8
XS Rating Curve= 0 ,0
Exp/Cntr=0.3,0.1

Type RM Length L Ch R = 1 ,2301    ,467,467,467
BEGIN DESCRIPTION:
UNT 084 IN CACR 5.0
END DESCRIPTION:
XS GIS Cut Line= 3
      3727099.61     10725710.18      3727149.61     10725860.19
      3727449.58     10726010.18
#Sta/Elev= 30
    4829  428.18  4860.6  423.57  4892.2  417.99  4902.8  416.93  4913.3  413.65
    4945  408.88  4955.6  406.13    4966  405.29  4984.5  400.32  4989.9  400.32
  4998.1  399.08  5000.8  398.58  5004.1  399.08  5017.9  401.23  5023.5  400.73
  5031.8     402  5062.6  402.34  5084.9  404.43  5098.9  404.62  5107.3  406.31
  5112.9   406.1  5121.3  406.96  5137.1  409.72    5152  411.09  5224.7  421.38
  5247.1  425.15  5308.6  432.47  5314.1  432.48  5319.7     434  5322.5     434
#Mann= 5 ,-1 , 0
    4829     .05       0  4955.6     .12       0  4998.1     .07       0
  5004.1     .12       0  5137.1     .05       0
Bank Sta=4966,5084.9
XS Rating Curve= 0 ,0
Exp/Cntr=0.3,0.1

Type RM Length L Ch R = 1 ,1834    ,435,435,435
BEGIN DESCRIPTION:
UNT 084 IN CACR 4.0
END DESCRIPTION:
XS GIS Cut Line= 3
      3726799.61     10725810.19      3726749.61     10726010.19
      3726699.59     10726110.22
#Sta/Elev= 30
  4814.2  421.71  4824.5  420.56  4832.2  420.62  4845.1  419.15  4855.4  418.66
  4873.5  416.56  4878.6  414.54  4886.4  413.52  4896.7  411.23    4907  409.96
  4914.7  407.67  4937.9  403.36  4955.9  401.51  4968.8  400.96  4979.1  399.81
  4989.4  393.99  4994.2  393.74  4996.9  393.24  5000.2  393.74  5002.3  394.03
    5010  398.23  5017.8  399.11  5023.2  399.11  5028.7  400.15  5042.7  401.22
  5050.2  402.82  5087.4  407.24  5101.4  408.45  5109.8  410.29  5132.2  412.87
#Mann= 4 ,-1 , 0
  4814.2     .12       0  4994.2     .07       0  5000.2     .12       0
  5050.2     .05       0
Bank Sta=4968.8,5028.7
XS Rating Curve= 0 ,0
Exp/Cntr=0.3,0.1

Type RM Length L Ch R = 1 ,1399    ,435,435,435
BEGIN DESCRIPTION:
UNT 084 IN CACR 3.0
END DESCRIPTION:
XS GIS Cut Line= 3
      3726599.59     10725710.19      3726399.61     10725760.19
      3726349.63     10725860.15
#Sta/Elev= 30
  4795.2  415.52  4805.5  415.29  4813.2  413.97  4826.1     413  4846.7  410.51
  4854.5  408.66  4867.3     407  4877.6  404.64    4888  403.59  4895.7  401.49
  4918.9  398.56  4929.2   397.2  4960.1  395.74  4978.1  395.56  4983.3  392.57
    4988  391.43  4990.8  390.93    4994  391.43  5004.1  391.52  5009.7  393.68
  5015.3  394.03  5023.7  396.02  5046.1     398  5054.4  399.79  5068.4  401.43
  5076.8  403.27  5099.2  406.07  5104.8  406.37  5110.3  407.74  5113.1  407.74
#Mann= 3 ,-1 , 0
  4795.2     .12       0    4988     .07       0    4994     .12       0
Bank Sta=4918.9,5046.1
XS Rating Curve= 0 ,0
Exp/Cntr=0.3,0.1

Type RM Length L Ch R = 1 ,964     ,383,383,383
BEGIN DESCRIPTION:
UNT 084 IN CACR 2.0
END DESCRIPTION:
XS GIS Cut Line= 3
      3726049.61     10725460.18      3725999.61     10725610.19
      3725999.61     10725710.16
#Sta/Elev= 30
  4819.6  414.64  4822.2  414.64  4830.2   414.1  4840.7  411.93  4851.2  410.36
  4861.8  407.47  4872.3   405.6  4882.9  402.66  4893.4  400.53  4903.9  397.46
  4914.5  396.28    4925   395.6  4935.6  394.82  4946.1  394.24  4956.6  393.42
  4967.2  392.95  4975.1   391.7  4980.2   391.7  4994.7  389.43  4997.5  388.93
  5000.7  389.43  5007.7  392.52  5017.7  394.86  5027.7   396.7  5037.7  397.59
  5047.7  399.39  5057.7  400.84  5067.7  402.78  5075.2  403.85  5077.7  403.85
#Mann= 3 ,-1 , 0
  4819.6     .12       0  4994.7     .07       0  5000.7     .12       0
Bank Sta=4925,5027.7
XS Rating Curve= 0 ,0
Exp/Cntr=0.3,0.1

Type RM Length L Ch R = 1 ,581     ,435,435,435
BEGIN DESCRIPTION:
Mapping XS d4176e6a
END DESCRIPTION:
XS GIS Cut Line= 2
       3725611.8      10725443.7      3725688.18     10725731.85
#Sta/Elev= 30
  4887.3  398.61  4889.4  397.87  4893.6  396.39  4898.7  397.06  4904.4  395.41
  4914.7  393.85    4925  393.23  4933.8  391.38  4938.9  392.26  4945.7  390.23
  4956.1  389.72  4966.4   387.9  4979.1  387.47  4987.1  388.06  4994.5  386.72
  4997.2  386.22  5000.5  386.72  5007.8  386.75  5014.2  387.81  5028.5  387.18
  5038.8  387.56  5049.2  389.01  5054.4  391.04  5059.5  390.44  5111.3  397.88
  5121.6  398.39  5129.6   400.4  5142.3  402.35    5163  403.95  5185.4  406.53
#Mann= 4 ,-1 , 0
  4887.3     .16       0  4889.4     .12       0  4994.5     .07       0
  5000.5     .12       0
Bank Sta=4956.1,5049.2
XS Rating Curve= 0 ,0
Exp/Cntr=0.3,0.1

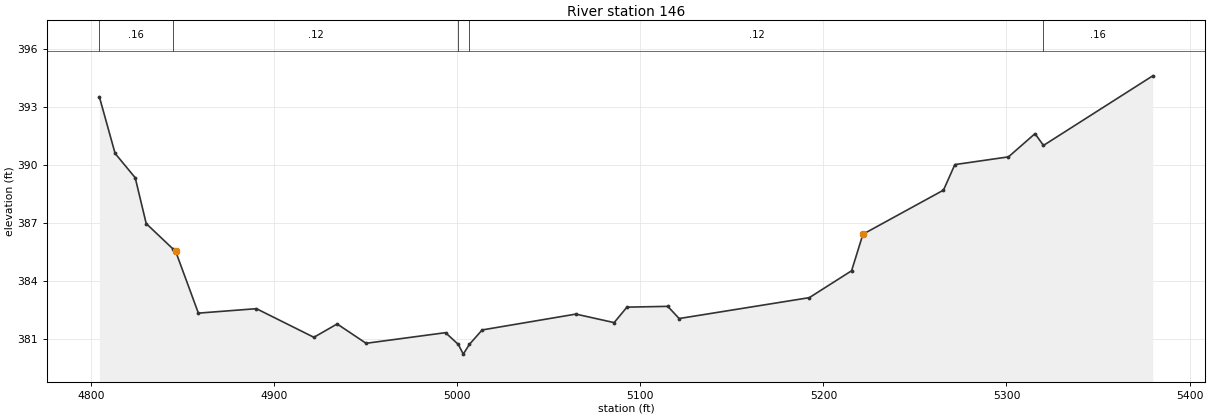
Type RM Length L Ch R = 1 ,146     ,0,0,0
BEGIN DESCRIPTION:
UNT 084 IN CACR 1.0
END DESCRIPTION:
XS GIS Cut Line= 4
      3725377.39     10725414.16      3725231.58     10725481.86
      3725231.58     10725537.41      3725521.54     10725749.24
#Sta/Elev= 30
  4804.5  393.55  4813.1  390.62  4824.1  389.36  4830.1  386.99  4844.5   385.7
  4846.2  385.55  4858.6  382.36  4890.3  382.59  4921.7  381.11  4934.4   381.8
  4950.2   380.8  4993.6  381.35  5000.6  380.74  5003.3  380.24  5006.6  380.74
  5013.6  381.49  5064.8  382.31  5085.7  381.87  5092.7  382.67    5115  382.71
  5121.2  382.08  5192.3  383.16  5215.4  384.55  5221.6  386.44  5265.6  388.72
  5271.8  390.04  5301.1  390.44  5315.6  391.64  5320.2  391.03  5379.9  394.63
#Mann= 5 ,-1 , 0
  4804.5     .16       0  4844.5     .12       0  5000.6     .07       0
  5006.6     .12       0  5320.2     .16       0
Bank Sta=4846.2,5221.6
XS Rating Curve= 0 ,0
Exp/Cntr=0.3,0.1

Chan Stop Cuts=-1
Use User Specified Reach Order=0
Composite Channel Slope=5