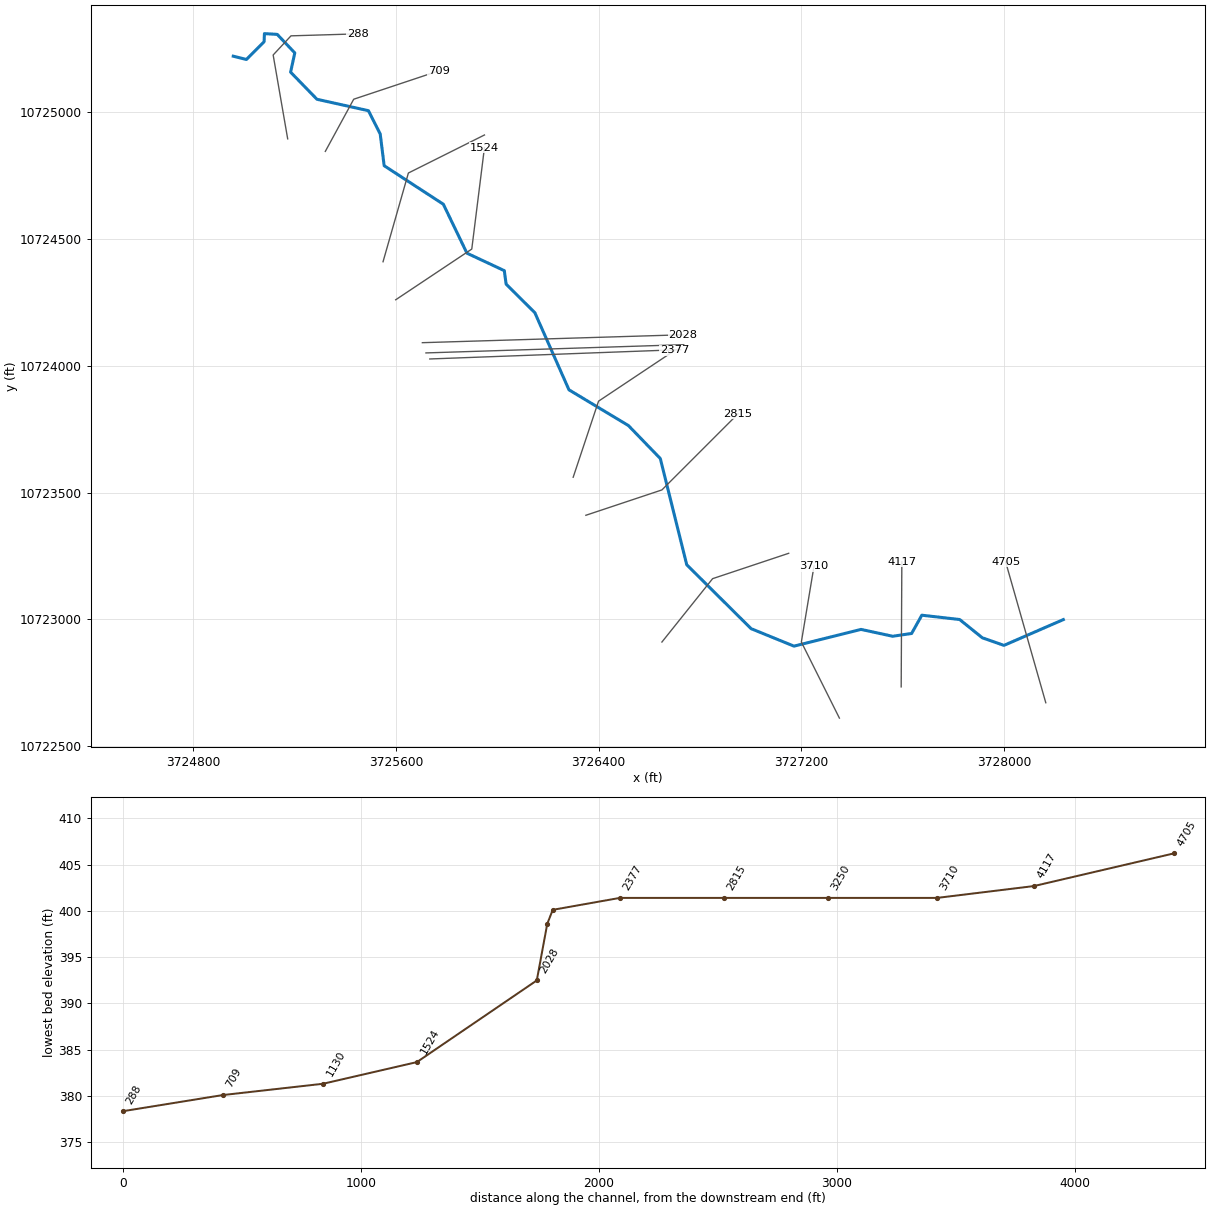
--- UNT 085 IN CACR.prj (project) ---

Proj Title=UNT 085 IN CACR Base Level Engineering
Current Plan=p01
Default Exp/Contr=0.3,0.1
English Units
Geom File=g01
Flow File=f01
Plan File=p01
BEGIN DESCRIPTION:
UNT 085 IN CACR
END DESCRIPTION:

--- UNT 085 IN CACR.p01 (plan) ---

Plan Title=Multiple Run
Short Identifier=Multiple
Geom File=g01
Flow File=f01
Subcritical Flow
K Sum by GR= 0
Std Step Tol= 0.01
Critical Tol= 0.01
Num of Std Step Trials= 20
Max Error Tol= 0.3
Flow Tol Ratio= 0.001
Split Flow NTrial= 30
Split Flow Tol= 0.02
Split Flow Ratio= 0.02
Log Output Level= 0
Friction Slope Method= 1
Unsteady Friction Slope Method= 2
Unsteady Bridges Friction Slope Method= 1
Parabolic Critical Depth
Global Vel Dist=  1 , 1 , 1
Global Log Level= 0
CheckData=True
Encroach Param= -1, 0, 0, 0
BEGIN DESCRIPTION:
Multiple Run
END DESCRIPTION:

--- UNT 085 IN CACR.f01 (steady flow) ---

Flow Title=Multiple
Number of Profiles=7
Profile Names=10-year,25-year,50-year,1pct_min,100-year,1pct_plu,500-year
River Rch & RM= UNT 085 IN CACR,Reach-1,4705
     578     776     937     831    1123    1519    1616
Boundary for River Rch & Prof#=UNT 085 IN CACR,Reach-1,1
Up Type=0
Dn Type=3
Dn Slope=0.005
Boundary for River Rch & Prof#=UNT 085 IN CACR,Reach-1,2
Up Type=0
Dn Type=3
Dn Slope=0.005
Boundary for River Rch & Prof#=UNT 085 IN CACR,Reach-1,3
Up Type=0
Dn Type=3
Dn Slope=0.005
Boundary for River Rch & Prof#=UNT 085 IN CACR,Reach-1,4
Up Type=0
Dn Type=3
Dn Slope=0.005
Boundary for River Rch & Prof#=UNT 085 IN CACR,Reach-1,5
Up Type=0
Dn Type=3
Dn Slope=0.005
Boundary for River Rch & Prof#=UNT 085 IN CACR,Reach-1,6
Up Type=0
Dn Type=3
Dn Slope=0.005
Boundary for River Rch & Prof#=UNT 085 IN CACR,Reach-1,7
Up Type=0
Dn Type=3
Dn Slope=0.005

--- UNT 085 IN CACR.g01 (geometry) ---

Geom Title=Existing Conditions

River Reach=UNT 085 IN CACR,Reach-1
Reach XY= 30
      3728232.96     10722998.73      3727998.75     10722897.00
      3727913.25     10722927.00      3727824.00     10722999.00
      3727674.75     10723016.00      3727634.50     10722944.00
      3727559.75     10722933.00      3727435.00     10722960.00
      3727170.50     10722894.00      3727001.25     10722963.00
      3726747.50     10723215.00      3726643.25     10723634.00
      3726517.50     10723764.00      3726283.00     10723905.00
      3726148.50     10724209.00      3726035.00     10724322.00
      3726028.00     10724375.00      3725880.50     10724444.00
      3725787.50     10724637.00      3725554.00     10724789.00
      3725538.50     10724914.00      3725492.00     10725006.00
      3725289.00     10725051.00      3725185.00     10725158.00
      3725201.50     10725234.00      3725132.25     10725307.00
      3725081.75     10725310.00      3725080.50     10725278.00
      3725010.75     10725208.00      3724958.75     10725221.00

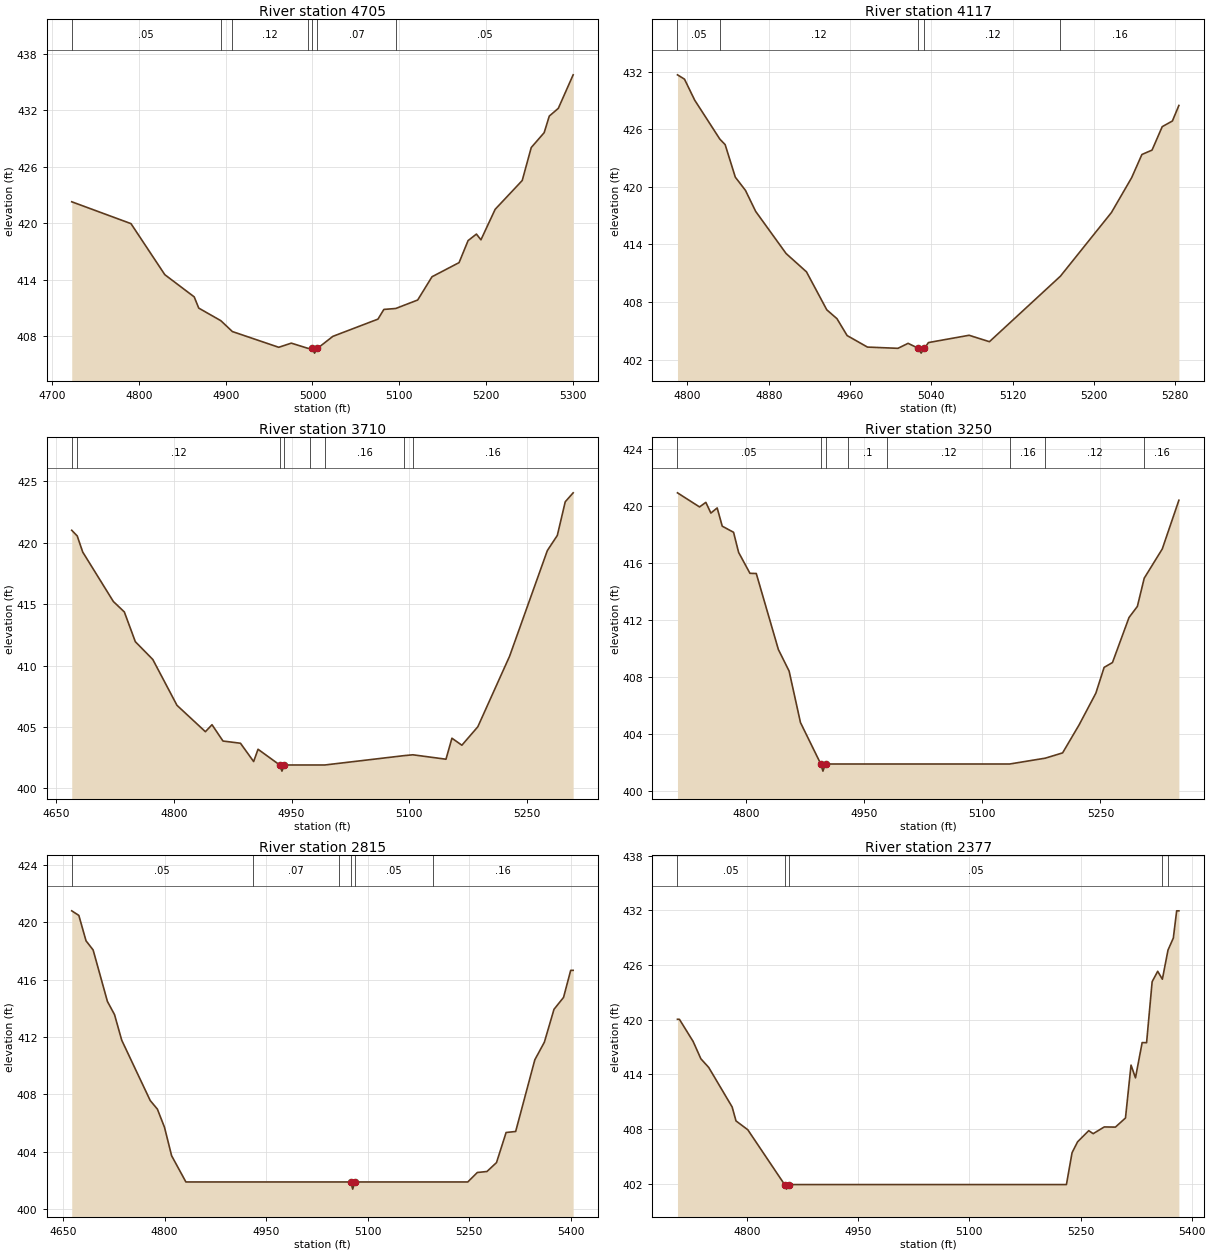
Type RM Length L Ch R = 1,4705,588,588,588
BEGIN DESCRIPTION:
UNT 085 IN CACR 10.0
END DESCRIPTION:
XS GIS Cut Line= 2
      3728163.68     10722670.75      3728005.23     10723226.61
#Sta/Elev= 30
  4722.5  422.28  4790.8  419.96  4829.8  414.54  4863.7  412.18  4868.9  410.99
  4894.3  409.66  4907.7  408.50  4961.1  406.83  4975.6  407.27  4995.1  406.71
  4999.7  406.71  5002.4  406.21  5005.7  406.71  5023.5  407.99  5075.5  409.82
  5082.3  410.85  5096.0  410.95  5121.3  411.85  5137.8  414.32  5169.0  415.82
  5179.4  418.16  5189.0  418.85  5194.2  418.24  5210.6  421.48  5241.8  424.54
  5252.2  428.04  5267.1  429.62  5273.0  431.38  5283.4  432.20  5300.5  435.76
#Mann=7,-1,0
  4722.5    0.05       0  4894.3    0.07       0  4907.7    0.12       0
  4995.1    0.07       0  4999.7    0.07       0  5005.7    0.07       0
  5096.0    0.05       0
Bank Sta=4999.7,5005.7
Exp/Cntr=0.3,0.1

Type RM Length L Ch R = 1,4117,407,407,407
BEGIN DESCRIPTION:
UNT 085 IN CACR 9.0
END DESCRIPTION:
XS GIS Cut Line= 2
      3727593.36     10722733.30      3727595.95     10723226.60
#Sta/Elev= 30
  4790.2  431.67  4797.1  431.22  4807.1  429.04  4831.9  424.97  4837.1  424.40
  4847.1  421.01  4857.1  419.63  4867.1  417.45  4897.1  413.05  4917.1  411.15
  4937.1  407.19  4947.1  406.27  4957.1  404.51  4977.1  403.31  5007.1  403.18
  5017.1  403.70  5027.2  403.18  5029.9  402.68  5033.2  403.18  5037.1  403.78
  5077.1  404.54  5097.1  403.87  5166.9  410.69  5217.1  417.32  5237.1  420.97
  5247.1  423.37  5257.1  423.83  5267.1  426.27  5277.1  426.86  5283.5  428.48
#Mann=5,-1,0
  4790.2    0.05       0  4831.9    0.12       0  5027.2    0.07       0
  5033.2    0.12       0  5166.9    0.16       0
Bank Sta=5027.2,5033.2
Exp/Cntr=0.3,0.1

Type RM Length L Ch R = 1,3710,460,460,460
BEGIN DESCRIPTION:
UNT 085 IN CACR 8.0
END DESCRIPTION:
XS GIS Cut Line= 3
      3727349.61     10722610.19      3727199.61     10722910.19
      3727249.60     10723210.15
#Sta/Elev= 30
  4669.7  421.01  4676.7  420.55  4683.7  419.24  4722.8  415.21  4736.8  414.36
  4750.8  411.94  4773.1  410.49  4803.9  406.76  4840.2  404.61  4848.6  405.18
  4862.6  403.85  4884.9  403.67  4901.7  402.18  4907.3  403.18  4935.0  401.90
  4937.8  401.40  4941.0  401.90  4973.1  401.90  4992.5  401.90  5093.4  402.66
  5104.8  402.73  5147.0  402.37  5154.6  404.08  5167.3  403.51  5187.6  405.01
  5228.1  410.75  5276.3  419.36  5289.0  420.59  5299.1  423.33  5309.2  424.06
#Mann=8,-1,0
  4669.7    0.05       0  4676.7    0.12       0  4935.0    0.07       0
  4941.0    0.12       0  4973.1    0.07       0  4992.5    0.16       0
  5093.4    0.12       0  5104.8    0.16       0
Bank Sta=4935,4941
Exp/Cntr=0.3,0.1

Type RM Length L Ch R = 1,3250,435,435,435
BEGIN DESCRIPTION:
UNT 085 IN CACR 7.0
END DESCRIPTION:
XS GIS Cut Line= 3
      3726649.61     10722910.19      3726849.61     10723160.19
      3727149.63     10723260.20
#Sta/Elev= 30
  4713.1  420.93  4741.1  419.94  4749.1  420.26  4755.5  419.51  4763.5  419.87
  4769.9  418.59  4784.3  418.16  4790.7  416.75  4805.1  415.28  4813.1  415.27
  4841.2  409.93  4854.8  408.42  4869.2  404.81  4895.0  401.90  4897.7  401.40
  4901.0  401.90  4928.9  401.90  4979.3  401.90  5134.8  401.90  5180.0  402.31
  5201.9  402.68  5223.0  404.66  5244.1  406.87  5254.6  408.68  5265.2  409.02
  5286.2  412.18  5296.8  412.96  5305.5  414.94  5328.4  416.99  5349.5  420.41
#Mann=8,-1,0
  4713.1    0.05       0  4895.0    0.07       0  4901.0    0.05       0
  4928.9     0.1       0  4979.3    0.12       0  5134.8    0.16       0
  5180.0    0.12       0  5305.5    0.16       0
Bank Sta=4895,4901
Exp/Cntr=0.3,0.1

Type RM Length L Ch R = 1,2815,438,438,438
BEGIN DESCRIPTION:
UNT 085 IN CACR 6.0
END DESCRIPTION:
XS GIS Cut Line= 3
      3726349.63     10723410.20      3726649.61     10723510.19
      3726949.63     10723810.21
#Sta/Elev= 30
  4662.8  420.81  4673.3  420.49  4683.9  418.72  4694.4  418.08  4715.5  414.49
  4726.0  413.57  4736.6  411.79  4778.7  407.58  4789.3  406.98  4799.8  405.71
  4810.3  403.73  4831.4  401.90  4930.3  401.90  5057.7  401.90  5075.0  401.90
  5077.7  401.40  5081.0  401.90  5195.9  401.90  5247.7  401.90  5261.8  402.56
  5276.0  402.63  5290.1  403.25  5304.3  405.35  5318.4  405.42  5346.7  410.42
  5360.8  411.65  5375.0  413.94  5389.1  414.77  5399.7  416.66  5403.3  416.66
#Mann=6,-1,0
  4662.8    0.05       0  4930.3    0.07       0  5057.7    0.05       0
  5075.0    0.07       0  5081.0    0.05       0  5195.9    0.16       0
Bank Sta=5075,5081
Exp/Cntr=0.3,0.1

Type RM Length L Ch R = 1,2377,282,282,282
BEGIN DESCRIPTION:
UNT 085 IN CACR 5.0
END DESCRIPTION:
XS GIS Cut Line= 3
      3726299.61     10723560.20      3726399.61     10723860.19
      3726699.63     10724060.20
#Sta/Elev= 30
  4706.0  420.05  4708.6  420.05  4727.1  417.62  4737.6  415.71  4748.2  414.76
  4779.8  410.42  4785.0  408.89  4800.9  407.92  4850.6  401.90  4853.3  401.40
  4856.6  401.90  5231.0  401.90  5238.6  405.40  5246.1  406.60  5261.1  407.82
  5267.1  407.49  5282.1  408.23  5297.1  408.21  5310.7  409.21  5318.2  415.02
  5324.2  413.62  5333.2  417.49  5339.2  417.48  5346.7  424.18  5354.2  425.32
  5360.5  424.45  5368.1  427.65  5375.3  428.97  5379.8  431.96  5382.8  431.96
#Mann=5,-1,0
  4706.0    0.05       0  4850.6   0.033       0  4856.6    0.05       0
  5360.5    0.16       0  5368.1    0.12       0
Bank Sta=4850.6,4856.6
Exp/Cntr=0.3,0.1

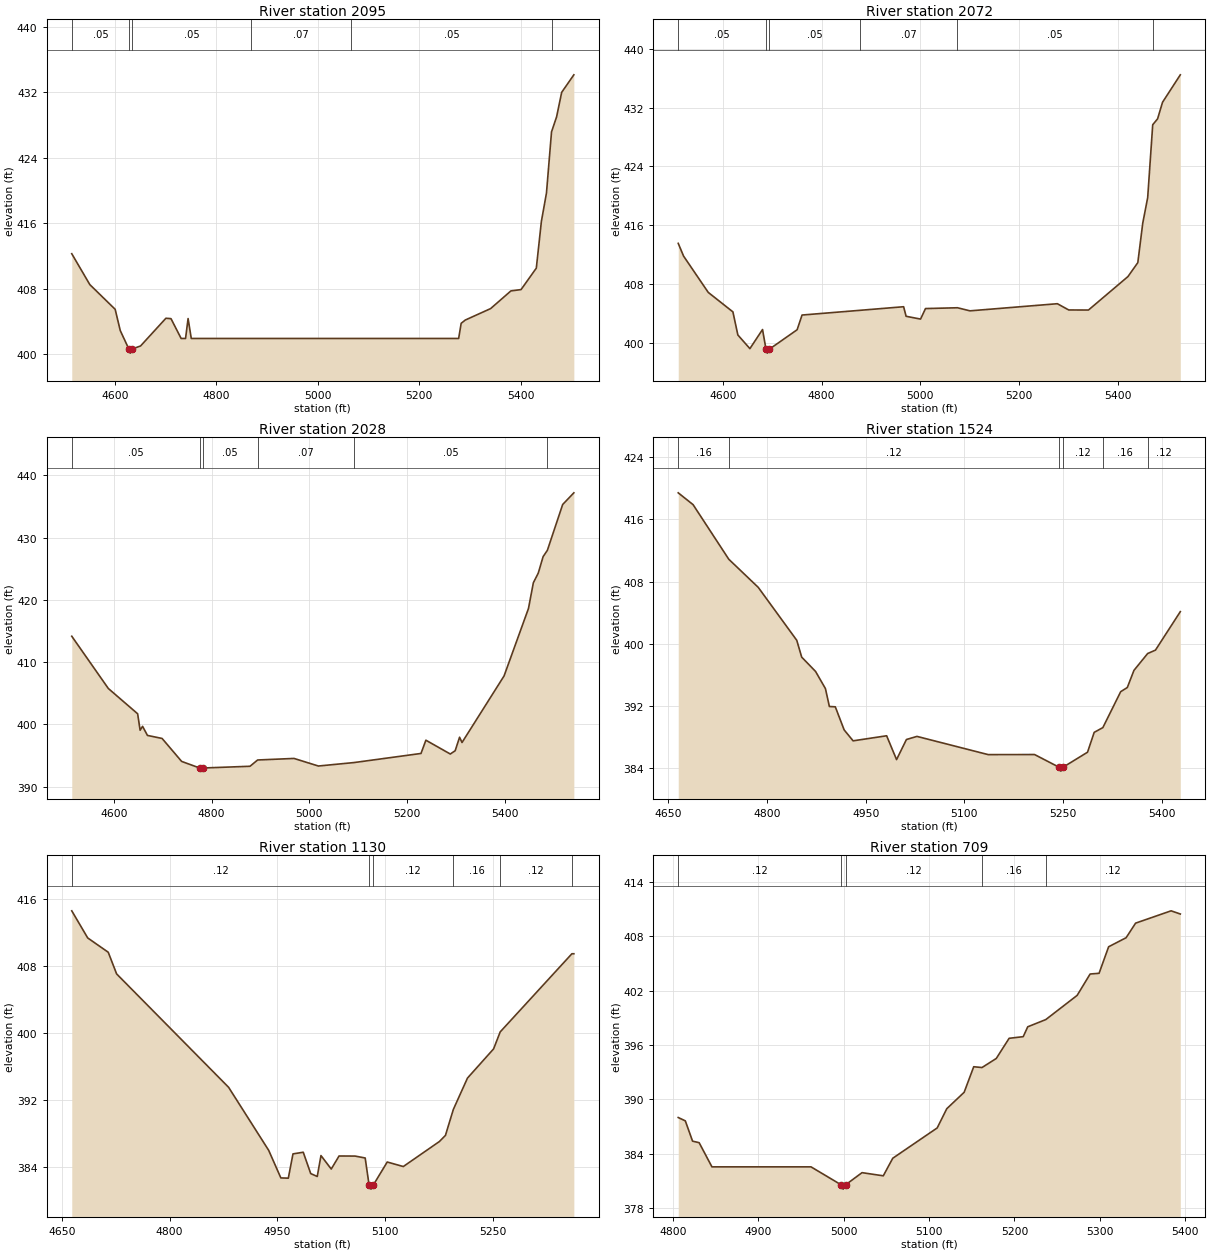
Type RM Length L Ch R = 1,2095,23,23,23
BEGIN DESCRIPTION:
Mapping XS 4f5bb655
END DESCRIPTION:
XS GIS Cut Line= 2
      3725734.08     10724026.69      3726723.59     10724063.58
#Sta/Elev= 30
  4514.8  412.25  4550.4  408.48  4600.4  405.46  4610.4  402.87  4627.4  400.61
  4630.2  400.11  4633.4  400.61  4650.4  400.98  4700.5  404.37  4710.5  404.32
  4730.5  401.90  4739.2  401.90  4744.2  404.33  4750.5  401.90  4868.5  401.90
  5066.3  401.90  5277.8  401.90  5282.8  403.75  5290.9  404.15  5340.9  405.55
  5380.9  407.71  5400.9  407.87  5431.0  410.49  5441.0  416.20  5451.0  419.66
  5461.0  427.14  5461.9  427.30  5471.0  428.97  5481.0  431.96  5505.0  434.10
#Mann=6,-1,0
  4514.8    0.05       0  4627.4    0.07       0  4633.4    0.05       0
  4868.5    0.07       0  5066.3    0.05       0  5461.9    0.12       0
Bank Sta=4627.4,4633.4
Exp/Cntr=0.3,0.1

Type RM Length L Ch R = 1,2072,44,44,44
BEGIN DESCRIPTION:
Mapping XS 5b18d1d9
END DESCRIPTION:
XS GIS Cut Line= 2
      3725718.85     10724050.56      3726735.63     10724083.08
#Sta/Elev= 30
  4509.5  413.53  4520.3  411.80  4570.3  406.86  4620.3  404.21  4630.3  401.07
  4654.7  399.21  4680.3  401.81  4687.4  399.10  4690.1  398.60  4693.4  399.10
  4750.4  401.78  4760.4  403.78  4877.5  404.42  4966.2  404.91  4971.2  403.61
  5000.5  403.23  5010.5  404.66  5075.3  404.77  5100.6  404.35  5277.7  405.32
  5300.7  404.47  5340.7  404.46  5420.7  409.01  5440.7  410.91  5450.7  416.28
  5460.7  419.75  5470.9  429.66  5480.8  430.47  5490.8  432.72  5526.8  436.45
#Mann=6,-1,0
  4509.5    0.05       0  4687.4    0.07       0  4693.4    0.05       0
  4877.5    0.07       0  5075.3    0.05       0  5470.9    0.12       0
Bank Sta=4687.4,4693.4
Exp/Cntr=0.3,0.1

Type RM Length L Ch R = 1,2028,504,504,504
BEGIN DESCRIPTION:
UNT 085 IN CACR 4.0
END DESCRIPTION:
XS GIS Cut Line= 2
      3725704.73     10724090.93      3726732.46     10724122.18
#Sta/Elev= 30
  4513.5  414.16  4588.4  405.76  4648.4  401.70  4653.5  399.05  4658.5  399.68
  4668.5  398.22  4698.5  397.73  4738.5  394.04  4775.5  392.98  4778.3  392.48
  4781.5  392.98  4878.5  393.26  4894.1  394.27  4968.6  394.52  5018.6  393.30
  5091.9  393.86  5228.7  395.32  5238.7  397.45  5288.7  395.23  5298.7  395.76
  5307.7  397.93  5312.7  397.08  5398.8  407.78  5448.8  418.62  5458.8  422.76
  5468.8  424.30  5478.8  426.96  5487.5  427.97  5518.8  435.33  5541.7  437.21
#Mann=6,-1,0
  4513.5    0.05       0  4775.5    0.07       0  4781.5    0.05       0
  4894.1    0.07       0  5091.9    0.05       0  5487.5    0.12       0
Bank Sta=4775.5,4781.5
Exp/Cntr=0.3,0.1

Type RM Length L Ch R = 1,1524,394,394,394
BEGIN DESCRIPTION:
UNT 085 IN CACR 3.0
END DESCRIPTION:
XS GIS Cut Line= 3
      3725599.57     10724260.17      3725899.61     10724460.19
      3725949.61     10724860.18
#Sta/Elev= 30
  4664.9  419.39  4687.5  417.87  4741.8  410.86  4786.6  407.25  4845.2  400.45
  4852.7  398.29  4873.8  396.45  4888.8  394.25  4894.8  391.95  4903.8  391.91
  4917.3  388.94  4930.9  387.54  4981.9  388.19  4997.0  385.13  5012.0  387.71
  5028.0  388.11  5136.4  385.77  5206.9  385.78  5244.2  384.15  5247.0  383.65
  5250.2  384.15  5287.5  386.08  5297.6  388.63  5310.8  389.24  5337.9  393.85
  5348.0  394.39  5358.1  396.59  5378.9  398.75  5390.8  399.19  5428.6  404.13
#Mann=6,-1,0
  4664.9    0.16       0  4741.8    0.12       0  5244.2    0.07       0
  5250.2    0.12       0  5310.8    0.16       0  5378.9    0.12       0
Bank Sta=5244.2,5250.2
Exp/Cntr=0.3,0.1

Type RM Length L Ch R = 1,1130,421,421,421
BEGIN DESCRIPTION:
UNT 085 IN CACR 2.0
END DESCRIPTION:
XS GIS Cut Line= 3
      3725549.60     10724410.14      3725649.61     10724760.19
      3725949.64     10724910.20
#Sta/Elev= 30
  4663.8  414.57  4686.0  411.33  4714.6  409.62  4726.3  407.03  4882.3  393.48
  4938.2  385.94  4955.1  382.65  4965.5  382.62  4972.0  385.52  4986.3  385.72
  4996.7  383.17  5005.8  382.82  5011.0  385.32  5025.3  383.71  5036.2  385.27
  5058.6  385.26  5072.6  385.03  5078.0  381.81  5080.7  381.31  5084.0  381.81
  5103.3  384.55  5125.7  384.01  5176.0  387.00  5184.4  387.73  5195.4  390.83
  5215.1  394.58  5251.5  398.07  5260.7  400.10  5360.6  409.44  5363.3  409.44
#Mann=6,-1,0
  4663.8    0.12       0  5078.0    0.07       0  5084.0    0.12       0
  5195.4    0.16       0  5260.7    0.12       0  5360.6    0.16       0
Bank Sta=5078,5084
Exp/Cntr=0.3,0.1

Type RM Length L Ch R = 1,709,421,421,421
BEGIN DESCRIPTION:
Mapping XS 37eb78fb
END DESCRIPTION:
XS GIS Cut Line= 3
      3725321.93     10724845.46      3725433.92     10725051.22
      3725769.89     10725163.20
#Sta/Elev= 30
  4806.0  388.00  4814.3  387.63  4822.8  385.39  4830.5  385.22  4845.5  382.55
  4961.6  382.55  4996.5  380.59  4999.3  380.09  5002.5  380.59  5021.4  381.91
  5046.3  381.56  5057.4  383.50  5109.5  386.85  5120.7  388.97  5141.1  390.79
  5152.3  393.61  5162.0  393.52  5178.7  394.52  5193.8  396.75  5210.3  396.93
  5215.6  398.02  5236.8  398.82  5273.5  401.49  5288.7  403.85  5299.2  403.93
  5310.4  406.86  5330.9  407.86  5342.0  409.47  5383.6  410.83  5394.4  410.48
#Mann=5,-1,0
  4806.0    0.12       0  4996.5    0.07       0  5002.5    0.12       0
  5162.0    0.16       0  5236.8    0.12       0
Bank Sta=4996.5,5002.5
Exp/Cntr=0.3,0.1

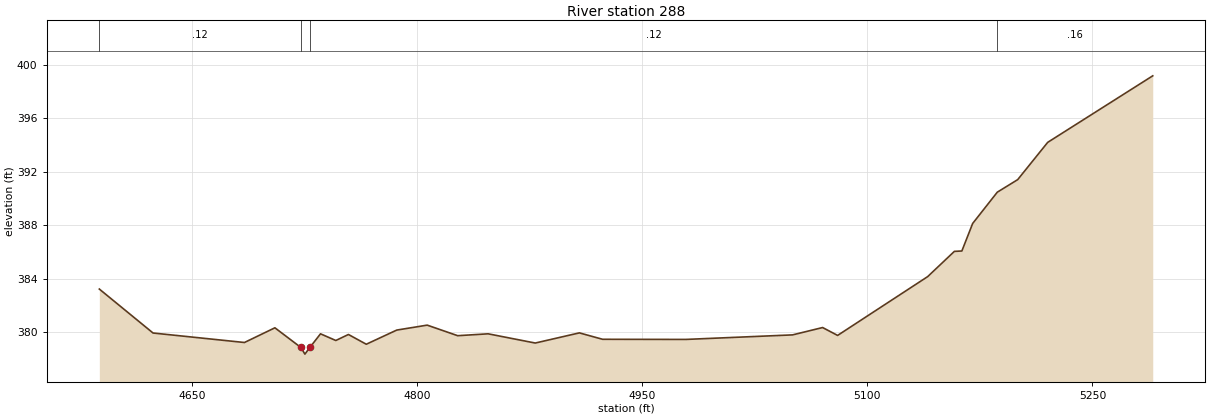
Type RM Length L Ch R = 1,288,0,0,0
BEGIN DESCRIPTION:
UNT 085 IN CACR 1.0
END DESCRIPTION:
XS GIS Cut Line= 4
      3725173.51     10724894.94      3725116.21     10725225.69
      3725186.53     10725301.22      3725449.54     10725309.03
#Sta/Elev= 30
  4588.2  383.21  4624.0  379.92  4684.9  379.21  4705.2  380.31  4722.5  378.84
  4725.2  378.34  4728.5  378.84  4735.6  379.86  4745.8  379.36  4754.2  379.81
  4766.1  379.08  4786.4  380.14  4806.7  380.51  4827.0  379.72  4847.3  379.86
  4878.7  379.17  4908.1  379.93  4923.6  379.45  4979.0  379.44  5050.2  379.78
  5070.2  380.33  5080.2  379.74  5140.2  384.14  5158.0  386.03  5163.0  386.06
  5170.2  388.12  5186.6  390.46  5200.2  391.40  5220.2  394.19  5290.2  399.17
#Mann=4,-1,0
  4588.2    0.12       0  4722.5    0.07       0  4728.5    0.12       0
  5186.6    0.16       0
Bank Sta=4722.5,4728.5
Exp/Cntr=0.3,0.1

Chan Stop Cuts=-1