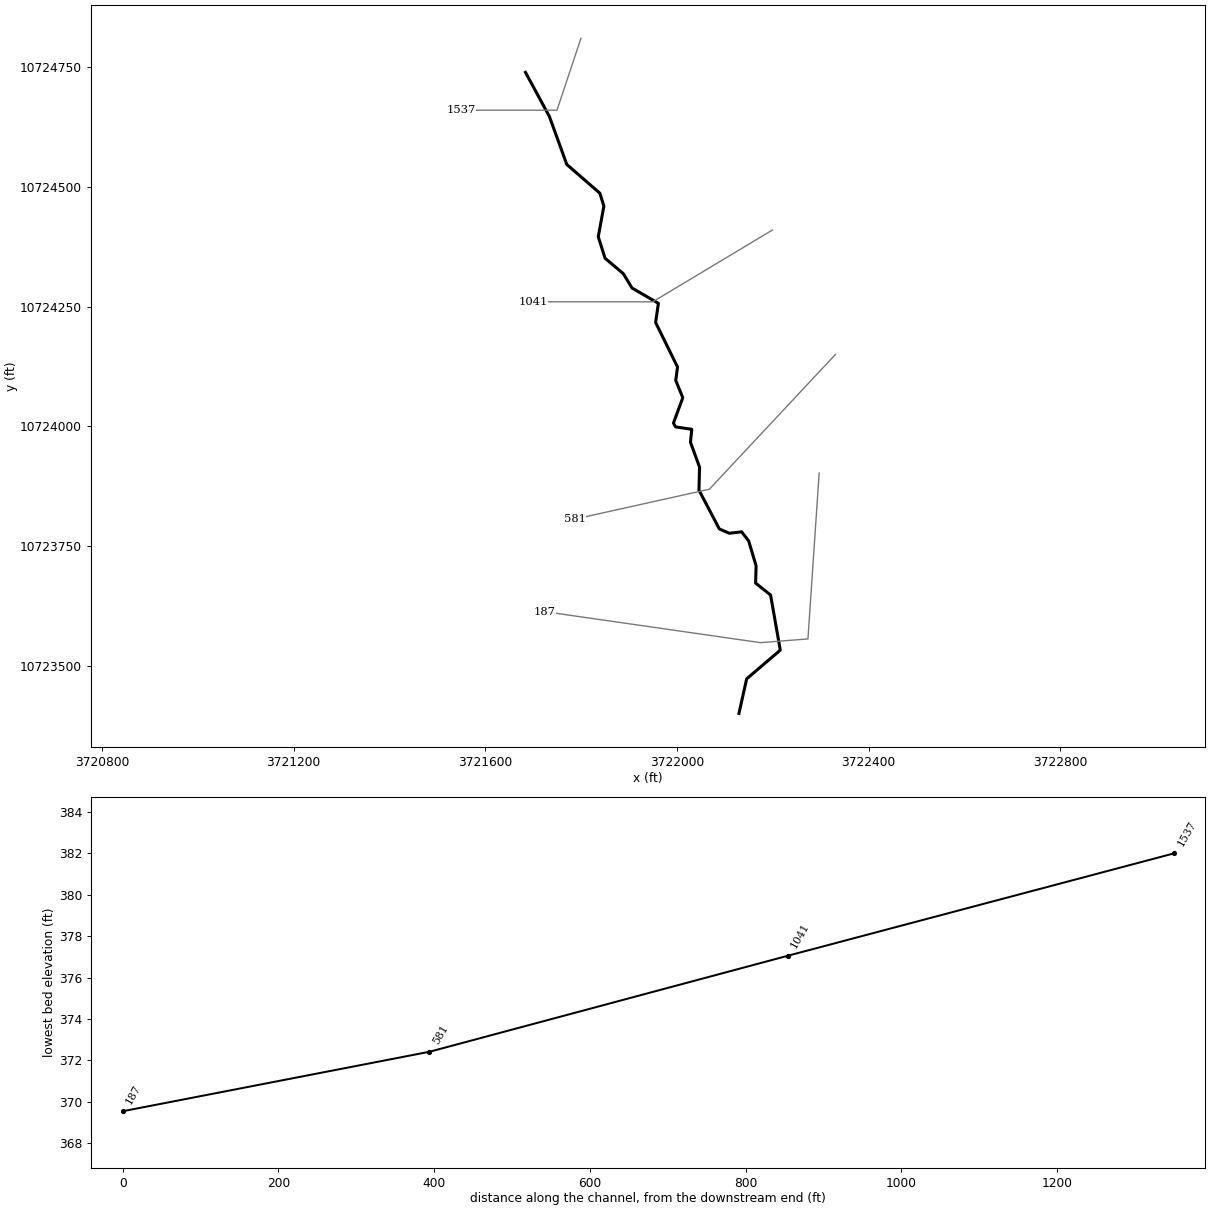
--- UNT 086 IN CACR.prj (project) ---

Proj Title=UNT 086 IN CACR Base Level Engineering
Current Plan=p01
Default Exp/Contr=0.3,0.1
English Units
Geom File=g01
Flow File=f01
Plan File=p01
BEGIN DESCRIPTION:
UNT 086 IN CACR
END DESCRIPTION:

--- UNT 086 IN CACR.p01 (plan) ---

Plan Title=Multiple Run
Short Identifier=Multiple
Geom File=g01
Flow File=f01
Subcritical Flow
K Sum by GR= 0
Std Step Tol= 0.01
Critical Tol= 0.01
Num of Std Step Trials= 20
Max Error Tol= 0.3
Flow Tol Ratio= 0.001
Split Flow NTrial= 30
Split Flow Tol= 0.02
Split Flow Ratio= 0.02
Log Output Level= 0
Friction Slope Method= 1
Unsteady Friction Slope Method= 2
Unsteady Bridges Friction Slope Method= 1
Parabolic Critical Depth
Global Vel Dist=  1 , 1 , 1
Global Log Level= 0
CheckData=True
Encroach Param= -1, 0, 0, 0
BEGIN DESCRIPTION:
Multiple Run
END DESCRIPTION:

--- UNT 086 IN CACR.f01 (steady flow) ---

Flow Title=Multiple
Number of Profiles=7
Profile Names=10-year,25-year,50-year,1pct_min,100-year,1pct_plu,500-year
River Rch & RM= UNT 086 IN CACR,Reach-1,1537
     714     979    1199    1079    1459    1973    2162
Boundary for River Rch & Prof#=UNT 086 IN CACR,Reach-1,1
Up Type=0
Dn Type=3
Dn Slope=0.005
Boundary for River Rch & Prof#=UNT 086 IN CACR,Reach-1,2
Up Type=0
Dn Type=3
Dn Slope=0.005
Boundary for River Rch & Prof#=UNT 086 IN CACR,Reach-1,3
Up Type=0
Dn Type=3
Dn Slope=0.005
Boundary for River Rch & Prof#=UNT 086 IN CACR,Reach-1,4
Up Type=0
Dn Type=3
Dn Slope=0.005
Boundary for River Rch & Prof#=UNT 086 IN CACR,Reach-1,5
Up Type=0
Dn Type=3
Dn Slope=0.005
Boundary for River Rch & Prof#=UNT 086 IN CACR,Reach-1,6
Up Type=0
Dn Type=3
Dn Slope=0.005
Boundary for River Rch & Prof#=UNT 086 IN CACR,Reach-1,7
Up Type=0
Dn Type=3
Dn Slope=0.005

--- UNT 086 IN CACR.g01 (geometry) ---

Geom Title=Existing Conditions

River Reach=UNT 086 IN CACR,Reach-1
Reach XY= 30
      3721683.80     10724739.28      3721733.75     10724647.00
      3721770.00     10724547.00      3721839.00     10724487.00
      3721847.50     10724460.00      3721835.75     10724396.00
      3721850.00     10724351.00      3721888.00     10724319.00
      3721906.25     10724289.00      3721961.25     10724257.00
      3721955.50     10724217.00      3722001.25     10724124.00
      3721997.50     10724096.00      3722012.25     10724060.00
      3721992.75     10724007.00      3721997.25     10723999.00
      3722031.00     10723994.00      3722028.25     10723967.00
      3722047.25     10723915.00      3722046.00     10723867.00
      3722088.50     10723786.00      3722109.25     10723777.00
      3722135.00     10723780.00      3722149.75     10723761.00
      3722165.25     10723709.00      3722164.25     10723673.00
      3722195.50     10723648.00      3722215.75     10723533.00
      3722145.50     10723473.00      3722129.50     10723401.00

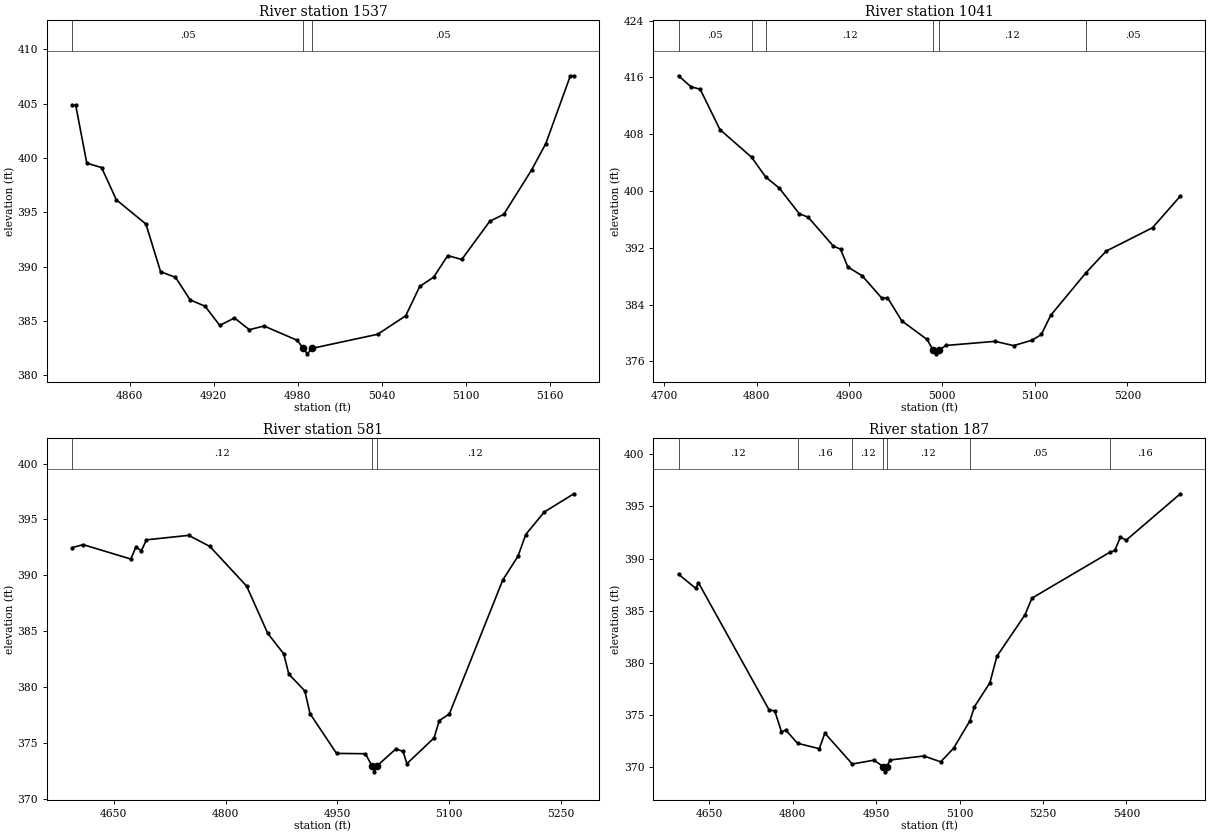
Type RM Length L Ch R = 1,1537,496,496,496
BEGIN DESCRIPTION:
UNT 086 IN CACR 3.0
END DESCRIPTION:
XS GIS Cut Line= 3
      3721799.61     10724810.18      3721749.61     10724660.19
      3721549.61     10724660.19
#Sta/Elev= 30
  4818.9  404.86  4821.5  404.86  4829.4  399.54  4840.0  399.12  4850.5  396.16
  4871.6  393.93  4882.1  389.54  4892.7  389.03  4903.2  386.95  4913.8  386.37
  4924.3  384.61  4934.8  385.29  4945.4  384.21  4955.9  384.55  4979.5  383.24
  4984.0  382.49  4986.8  381.99  4990.0  382.49  5037.0  383.79  5057.0  385.49
  5067.0  388.19  5077.0  389.05  5087.0  391.03  5097.0  390.67  5117.0  394.19
  5127.0  394.82  5147.0  398.94  5157.0  401.34  5174.5  407.57  5177.0  407.57
#Mann=3,-1,0
  4818.9    0.05       0  4984.0    0.03       0  4990.0    0.05       0
Bank Sta=4984,4990
Exp/Cntr=0.3,0.1

Type RM Length L Ch R = 1,1041,460,460,460
BEGIN DESCRIPTION:
UNT 086 IN CACR 2.0
END DESCRIPTION:
XS GIS Cut Line= 3
      3722199.62     10724410.20      3721949.61     10724260.19
      3721699.57     10724260.19
#Sta/Elev= 30
  4715.5  416.23  4729.1  414.66  4738.8  414.35  4760.2  408.65  4794.3  404.76
  4809.5  401.98  4824.4  400.38  4845.7  396.81  4855.5  396.29  4882.7  392.22
  4890.4  391.80  4898.2  389.29  4913.8  388.04  4935.2  384.85  4941.0  384.97
  4956.5  381.69  4983.7  379.08  4990.5  377.55  4993.2  377.05  4996.5  377.55
  5004.1  378.23  5057.1  378.81  5077.1  378.21  5097.1  378.97  5107.1  379.78
  5117.1  382.46  5154.8  388.41  5177.1  391.53  5227.1  394.82  5257.1  399.28
#Mann=6,-1,0
  4715.5    0.05       0  4794.3    0.16       0  4809.5    0.12       0
  4990.5    0.07       0  4996.5    0.12       0  5154.8    0.05       0
Bank Sta=4990.5,4996.5
Exp/Cntr=0.3,0.1

Type RM Length L Ch R = 1,581,394,394,394
BEGIN DESCRIPTION:
Mapping XS 303edb3d
END DESCRIPTION:
XS GIS Cut Line= 3
      3722330.80     10724150.22      3722067.75     10723868.94
      3721786.52     10723806.45
#Sta/Elev= 30
  4594.0  392.48  4608.8  392.75  4672.8  391.46  4679.6  392.53  4687.0  392.21
  4693.8  393.18  4750.5  393.58  4778.8  392.59  4828.2  389.04  4856.5  384.81
  4878.0  382.98  4884.8  381.16  4906.3  379.66  4913.2  377.63  4948.8  374.07
  4987.5  374.04  4996.6  372.92  4999.4  372.42  5002.6  372.92  5028.4  374.47
  5038.0  374.25  5043.2  373.15  5079.6  375.45  5086.7  377.01  5100.1  377.59
  5171.8  389.58  5192.3  391.72  5202.6  393.65  5227.5  395.67  5267.2  397.30
#Mann=3,-1,0
  4594.0    0.12       0  4996.6    0.07       0  5002.6    0.12       0
Bank Sta=4996.6,5002.6
Exp/Cntr=0.3,0.1

Type RM Length L Ch R = 1,187,0,0,0
BEGIN DESCRIPTION:
UNT 086 IN CACR 1.0
END DESCRIPTION:
XS GIS Cut Line= 4
      3722296.92     10723902.80      3722273.48     10723556.44
      3722174.52     10723548.63      3721722.97     10723613.51
#Sta/Elev= 30
  4594.4  388.50  4625.3  387.15  4630.3  387.68  4757.4  375.48  4767.4  375.40
  4779.6  373.39  4787.4  373.55  4808.4  372.29  4847.6  371.77  4857.6  373.26
  4906.9  370.30  4946.0  370.67  4962.5  370.05  4965.2  369.55  4968.5  370.05
  4975.5  370.69  5035.7  371.07  5066.0  370.51  5089.1  371.81  5118.4  374.43
  5126.6  375.79  5154.5  378.10  5167.0  380.63  5217.5  384.60  5230.1  386.21
  5369.9  390.60  5379.2  390.78  5389.3  392.08  5399.4  391.76  5497.0  396.22
#Mann=7,-1,0
  4594.4    0.12       0  4808.4    0.16       0  4906.9    0.12       0
  4962.5    0.07       0  4968.5    0.12       0  5118.4    0.05       0
  5369.9    0.16       0
Bank Sta=4962.5,4968.5
Exp/Cntr=0.3,0.1

Chan Stop Cuts=-1