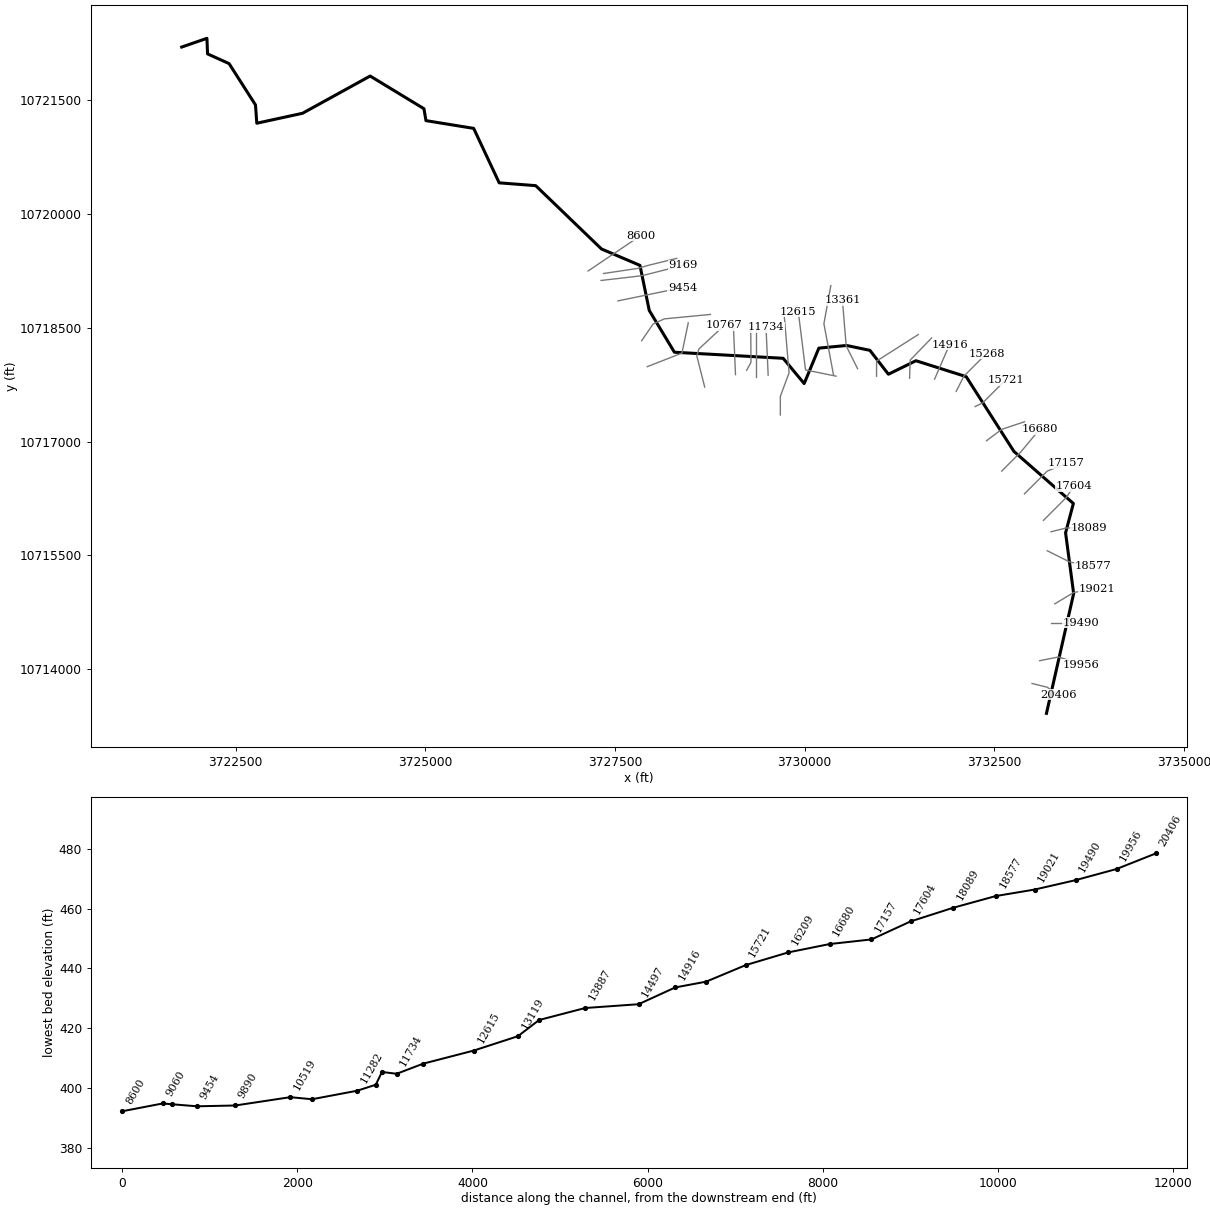
--- UNT 087 IN CACR.prj (project) ---

Proj Title=UNT 087 IN CACR Base Level Engineering
Current Plan=p01
Default Exp/Contr=0.3,0.1
English Units
Geom File=g01
Flow File=f01
Plan File=p01
BEGIN DESCRIPTION:
UNT 087 IN CACR
END DESCRIPTION:

--- UNT 087 IN CACR.p01 (plan) ---

Plan Title=Multiple Run
Short Identifier=Multiple
Geom File=g01
Flow File=f01
Subcritical Flow
K Sum by GR= 0
Std Step Tol= 0.01
Critical Tol= 0.01
Num of Std Step Trials= 20
Max Error Tol= 0.3
Flow Tol Ratio= 0.001
Split Flow NTrial= 30
Split Flow Tol= 0.02
Split Flow Ratio= 0.02
Log Output Level= 0
Friction Slope Method= 1
Unsteady Friction Slope Method= 2
Unsteady Bridges Friction Slope Method= 1
Parabolic Critical Depth
Global Vel Dist=  1 , 1 , 1
Global Log Level= 0
CheckData=True
Encroach Param= -1, 0, 0, 0
BEGIN DESCRIPTION:
Multiple Run
END DESCRIPTION:

--- UNT 087 IN CACR.f01 (steady flow) ---

Flow Title=Multiple
Number of Profiles=7
Profile Names=10-year,25-year,50-year,1pct_min,100-year,1pct_plu,500-year
River Rch & RM= UNT 087 IN CACR,Reach-1,20406
     445     599     725     648     876    1184    1280
River Rch & RM= UNT 087 IN CACR,Reach-1,13361
     563     769     942     848    1147    1551    1708
River Rch & RM= UNT 087 IN CACR,Reach-1,12037
    1020    1441    1803    1656    2240    3029    3473
River Rch & RM= UNT 087 IN CACR,Reach-1,9890
    1509    2157    2718    2510    3394    4591    5321
Boundary for River Rch & Prof#=UNT 087 IN CACR,Reach-1,1
Up Type=0
Dn Type=3
Dn Slope=0.005
Boundary for River Rch & Prof#=UNT 087 IN CACR,Reach-1,2
Up Type=0
Dn Type=3
Dn Slope=0.005
Boundary for River Rch & Prof#=UNT 087 IN CACR,Reach-1,3
Up Type=0
Dn Type=3
Dn Slope=0.005
Boundary for River Rch & Prof#=UNT 087 IN CACR,Reach-1,4
Up Type=0
Dn Type=3
Dn Slope=0.005
Boundary for River Rch & Prof#=UNT 087 IN CACR,Reach-1,5
Up Type=0
Dn Type=3
Dn Slope=0.005
Boundary for River Rch & Prof#=UNT 087 IN CACR,Reach-1,6
Up Type=0
Dn Type=3
Dn Slope=0.005
Boundary for River Rch & Prof#=UNT 087 IN CACR,Reach-1,7
Up Type=0
Dn Type=3
Dn Slope=0.005

--- UNT 087 IN CACR.g01 (geometry) ---

Geom Title=Existing Conditions

River Reach=UNT 087 IN CACR,Reach-1
Reach XY= 30
      3733189.50     10713416.00      3733548.00     10714996.00
      3733441.50     10715796.00      3733544.25     10716183.00
      3732760.00     10716870.00      3732131.25     10717855.00
      3731468.75     10718065.00      3731106.00     10717887.00
      3730861.75     10718202.00      3730554.00     10718266.00
      3730189.00     10718231.00      3729995.50     10717764.00
      3729718.25     10718097.00      3728285.00     10718177.00
      3727953.00     10718728.00      3727830.75     10719322.00
      3727323.50     10719538.00      3726456.25     10720373.00
      3725975.00     10720410.00      3725638.50     10721128.00
      3725009.50     10721230.00      3724983.00     10721387.00
      3724273.75     10721818.00      3723382.25     10721327.00
      3722779.50     10721196.00      3722762.25     10721437.00
      3722414.00     10721982.00      3722130.25     10722110.00
      3722122.00     10722315.00      3721789.00     10722200.00

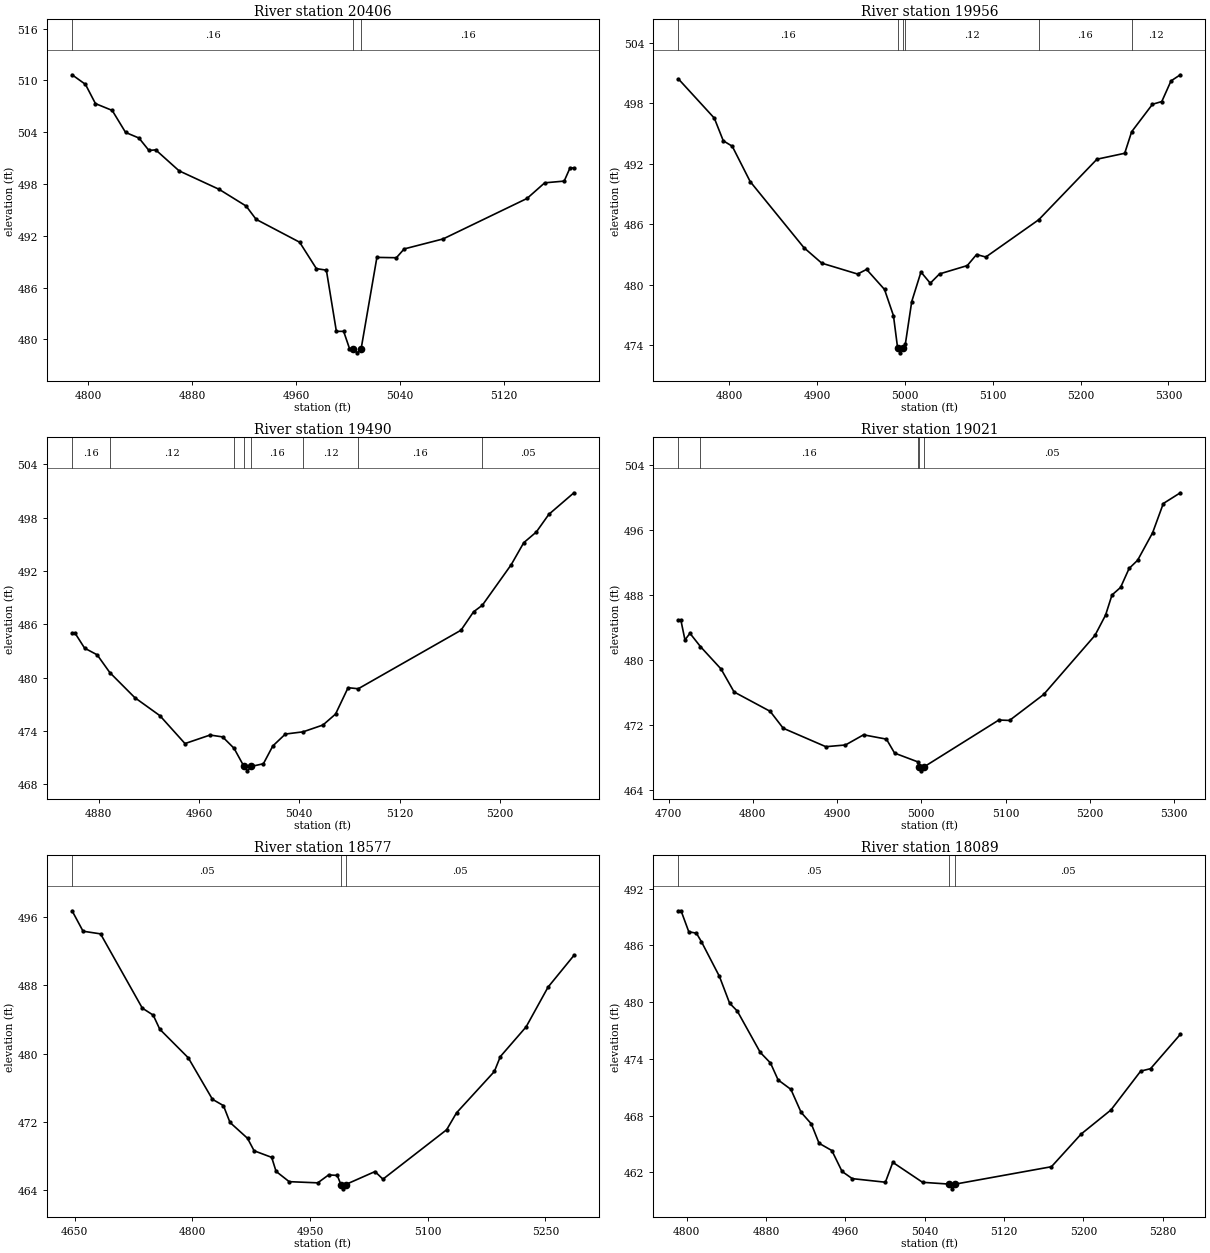
Type RM Length L Ch R = 1,20406,450,450,450
BEGIN DESCRIPTION:
UNT 087 IN CACR 41.0
END DESCRIPTION:
XS GIS Cut Line= 3
      3732999.66     10713810.18      3733199.61     10713760.19
      3733349.62     10713660.18
#Sta/Elev= 30
  4787.6  510.65  4797.9  509.54  4805.6  507.31  4818.5  506.52  4828.8  503.97
  4839.1  503.32  4846.8  501.88  4852.0  501.95  4870.0  499.52  4900.9  497.37
  4921.6  495.44  4929.3  493.90  4962.8  491.25  4975.7  488.19  4983.4  488.01
  4991.1  480.92  4996.7  480.92  5001.2  478.93  5004.2  478.93  5007.0  478.43
  5010.2  478.93  5022.3  489.49  5037.3  489.45  5043.3  490.47  5073.3  491.63
  5137.9  496.32  5151.5  498.13  5166.5  498.33  5171.0  499.86  5174.0  499.86
#Mann=3,-1,0
  4787.6    0.16       0  5004.2    0.07       0  5010.2    0.16       0
Bank Sta=5004.2,5010.2
Exp/Cntr=0.3,0.1

Type RM Length L Ch R = 1,19956,466,466,466
BEGIN DESCRIPTION:
UNT 087 IN CACR 40.0
END DESCRIPTION:
XS GIS Cut Line= 3
      3733099.63     10714110.19      3733349.61     10714160.19
      3733649.65     10714060.17
#Sta/Elev= 30
  4742.4  500.42  4783.2  496.53  4793.4  494.28  4803.6  493.74  4824.0  490.23
  4885.2  483.66  4905.5  482.12  4946.3  481.04  4956.5  481.50  4976.9  479.51
  4987.1  476.90  4991.8  473.71  4994.5  473.21  4997.8  473.71  5000.7  474.12
  5007.9  478.31  5018.4  481.24  5029.0  480.13  5039.5  481.05  5071.1  481.88
  5081.7  482.98  5092.2  482.73  5152.5  486.44  5218.7  492.45  5250.3  493.04
  5258.2  495.18  5281.9  497.91  5292.5  498.18  5303.0  500.23  5313.6  500.84
#Mann=6,-1,0
  4742.4    0.16       0  4991.8    0.07       0  4997.8    0.16       0
  5000.7    0.12       0  5152.5    0.16       0  5258.2    0.12       0
Bank Sta=4991.8,4997.8
Exp/Cntr=0.3,0.1

Type RM Length L Ch R = 1,19490,469,469,469
BEGIN DESCRIPTION:
UNT 087 IN CACR 39.0
END DESCRIPTION:
XS GIS Cut Line= 3
      3733249.56     10714610.19      3733399.61     10714610.19
      3733649.56     10714610.19
#Sta/Elev= 30
  4858.9  484.97  4861.4  484.97  4868.9  483.31  4878.9  482.56  4889.0  480.56
  4908.9  477.74  4928.9  475.71  4948.9  472.57  4968.9  473.53  4978.9  473.32
  4988.0  472.04  4995.9  470.00  4998.7  469.50  5001.9  470.00  5011.4  470.30
  5018.9  472.30  5028.9  473.64  5043.0  473.89  5058.9  474.66  5068.9  475.89
  5078.9  478.86  5087.0  478.74  5168.9  485.33  5178.9  487.40  5185.9  488.14
  5208.9  492.70  5218.9  495.18  5228.9  496.38  5238.9  498.37  5258.9  500.80
#Mann=8,-1,0
  4858.9    0.16       0  4889.0    0.12       0  4988.0    0.16       0
  4995.9    0.07       0  5001.9    0.16       0  5043.0    0.12       0
  5087.0    0.16       0  5185.9    0.05       0
Bank Sta=4995.9,5001.9
Exp/Cntr=0.3,0.1

Type RM Length L Ch R = 1,19021,444,444,444
BEGIN DESCRIPTION:
UNT 087 IN CACR 38.0
END DESCRIPTION:
XS GIS Cut Line= 3
      3733299.65     10714860.21      3733549.61     10715010.19
      3733849.57     10715060.18
#Sta/Elev= 30
  4711.8  484.86  4714.7  484.86  4719.5  482.45  4725.4  483.27  4737.9  481.63
  4762.3  478.88  4777.8  476.05  4820.6  473.67  4836.1  471.59  4886.7  469.32
  4910.0  469.53  4931.4  470.78  4958.6  470.25  4968.3  468.53  4996.2  467.44
  4997.4  466.85  5000.1  466.35  5003.4  466.85  5092.0  472.60  5104.7  472.55
  5145.2  475.74  5206.1  483.01  5218.7  485.51  5226.3  487.98  5236.5  488.91
  5246.6  491.24  5256.7  492.25  5274.5  495.63  5287.2  499.23  5307.4  500.55
#Mann=5,-1,0
  4711.8    0.12       0  4737.9    0.16       0  4996.2    0.05       0
  4997.4    0.03       0  5003.4    0.05       0
Bank Sta=4997.4,5003.4
Exp/Cntr=0.3,0.1

Type RM Length L Ch R = 1,18577,488,488,488
BEGIN DESCRIPTION:
UNT 087 IN CACR 37.0
END DESCRIPTION:
XS GIS Cut Line= 3
      3733199.60     10715560.19      3733499.61     10715410.19
      3733799.65     10715360.18
#Sta/Elev= 30
  4646.7  496.69  4660.7  494.30  4683.0  493.99  4736.2  485.31  4750.1  484.49
  4758.5  482.84  4794.8  479.50  4825.6  474.65  4839.6  473.91  4848.0  471.94
  4870.3  470.09  4878.7  468.63  4901.1  467.86  4906.7  466.22  4923.4  465.02
  4959.8  464.88  4973.7  465.81  4984.7  465.75  4989.3  464.68  4992.0  464.18
  4995.3  464.68  5032.8  466.20  5042.9  465.31  5124.1  471.09  5136.7  473.07
  5184.9  477.90  5192.5  479.64  5225.4  483.12  5253.3  487.76  5286.3  491.47
#Mann=3,-1,0
  4646.7    0.05       0  4989.3    0.03       0  4995.3    0.05       0
Bank Sta=4989.3,4995.3
Exp/Cntr=0.3,0.1

Type RM Length L Ch R = 1,18089,485,485,485
BEGIN DESCRIPTION:
UNT 087 IN CACR 36.0
END DESCRIPTION:
XS GIS Cut Line= 3
      3733249.56     10715810.18      3733449.61     10715860.19
      3733749.61     10715860.19
#Sta/Elev= 30
  4791.6  489.66  4794.2  489.66  4802.0  487.44  4809.7  487.29  4814.8  486.38
  4832.9  482.72  4843.2  479.88  4850.9  479.06  4874.1  474.68  4884.4  473.56
  4892.1  471.77  4905.0  470.77  4915.3  468.34  4925.6  467.12  4933.4  465.07
  4946.3  464.30  4956.6  462.09  4966.9  461.33  5000.3  460.95  5007.8  463.05
  5037.8  460.94  5064.8  460.75  5067.6  460.25  5070.8  460.75  5167.8  462.59
  5197.8  466.05  5227.8  468.59  5257.8  472.70  5267.8  472.96  5297.8  476.59
#Mann=3,-1,0
  4791.6    0.05       0  5064.8    0.03       0  5070.8    0.05       0
Bank Sta=5064.8,5070.8
Exp/Cntr=0.3,0.1

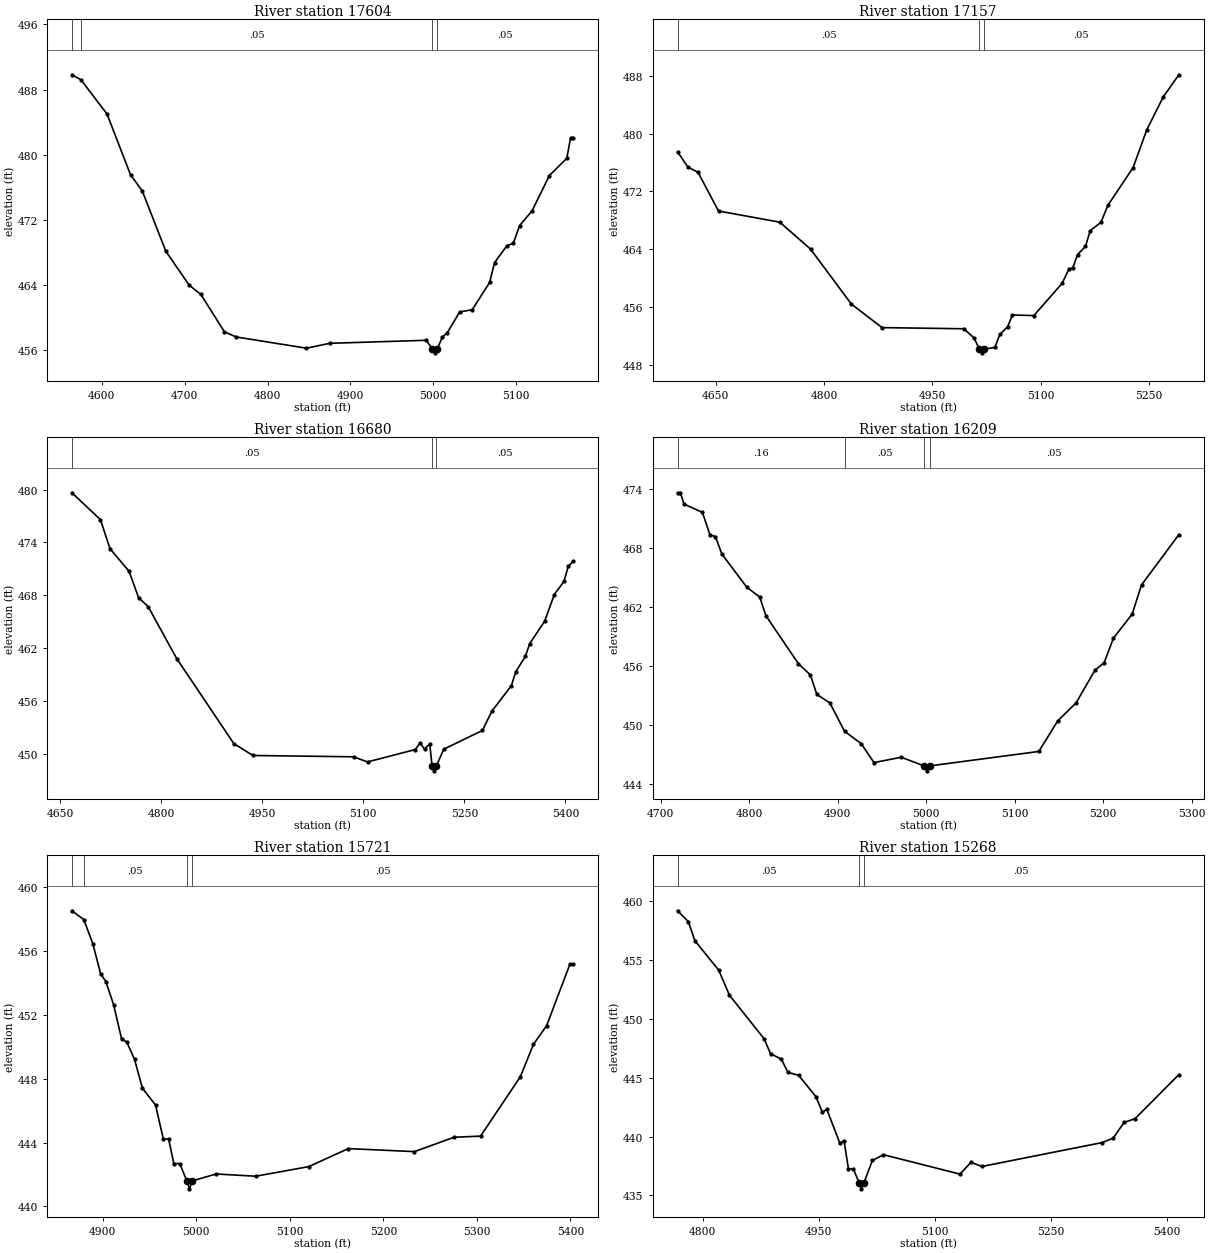
Type RM Length L Ch R = 1,17604,447,447,447
BEGIN DESCRIPTION:
UNT 087 IN CACR 35.0
END DESCRIPTION:
XS GIS Cut Line= 3
      3733149.60     10715960.18      3733449.61     10716260.19
      3733549.63     10716410.22
#Sta/Elev= 30
  4564.0  489.82  4574.8  489.22  4606.4  484.99  4634.7  477.55  4648.9  475.56
  4677.2  468.18  4705.4  464.01  4719.6  462.86  4747.9  458.29  4762.0  457.65
  4846.9  456.27  4875.1  456.87  4991.3  457.24  4998.8  456.20  5001.6  455.70
  5004.8  456.20  5010.8  457.62  5016.8  458.17  5031.8  460.72  5046.9  460.99
  5067.9  464.34  5073.9  466.78  5088.9  468.87  5096.4  469.12  5104.0  471.31
  5119.0  473.11  5140.0  477.46  5161.0  479.57  5165.6  482.11  5168.6  482.11
#Mann=4,-1,0
  4564.0    0.16       0  4574.8    0.05       0  4998.8    0.03       0
  5004.8    0.05       0
Bank Sta=4998.8,5004.8
Exp/Cntr=0.3,0.1

Type RM Length L Ch R = 1,17157,477,477,477
BEGIN DESCRIPTION:
UNT 087 IN CACR 34.0
END DESCRIPTION:
XS GIS Cut Line= 3
      3732899.60     10716310.18      3733199.61     10716610.19
      3733449.58     10716710.18
#Sta/Elev= 30
  4597.4  477.46  4611.6  475.39  4625.7  474.64  4654.0  469.30  4738.8  467.75
  4781.3  464.03  4837.8  456.43  4880.3  453.17  4993.4  453.01  5007.5  451.75
  5015.1  450.18  5017.9  449.68  5021.1  450.18  5036.5  450.44  5043.2  452.22
  5054.0  453.29  5060.7  454.92  5090.3  454.83  5129.4  459.29  5138.8  461.24
  5144.2  461.44  5150.9  463.28  5161.7  464.39  5168.4  466.59  5183.2  467.73
  5192.7  470.07  5227.7  475.31  5246.5  480.51  5269.4  485.08  5290.9  488.14
#Mann=3,-1,0
  4597.4    0.05       0  5015.1    0.03       0  5021.1    0.05       0
Bank Sta=5015.1,5021.1
Exp/Cntr=0.3,0.1

Type RM Length L Ch R = 1,16680,471,471,471
BEGIN DESCRIPTION:
UNT 087 IN CACR 33.0
END DESCRIPTION:
XS GIS Cut Line= 3
      3732599.63     10716610.21      3732849.61     10716860.19
      3733099.58     10717160.16
#Sta/Elev= 30
  4667.4  479.63  4709.8  476.58  4723.9  473.30  4752.2  470.74  4766.4  467.75
  4780.5  466.75  4822.9  460.86  4907.8  451.22  4936.1  449.88  5085.4  449.73
  5106.2  449.15  5177.1  450.55  5184.3  451.31  5190.8  450.59  5198.6  451.19
  5202.1  448.64  5204.9  448.14  5208.1  448.64  5219.4  450.59  5276.7  452.71
  5291.0  454.92  5319.7  457.78  5326.2  459.34  5340.5  461.11  5347.0  462.55
  5369.1  465.08  5383.5  468.11  5397.8  469.59  5404.3  471.33  5411.4  471.85
#Mann=3,-1,0
  4667.4    0.05       0  5202.1    0.03       0  5208.1    0.05       0
Bank Sta=5202.1,5208.1
Exp/Cntr=0.3,0.1

Type RM Length L Ch R = 1,16209,488,488,488
BEGIN DESCRIPTION:
UNT 087 IN CACR 32.0
END DESCRIPTION:
XS GIS Cut Line= 3
      3732399.61     10717010.19      3732599.61     10717160.19
      3732899.58     10717260.18
#Sta/Elev= 30
  4719.3  473.61  4722.4  473.61  4726.6  472.46  4747.4  471.61  4755.8  469.34
  4762.0  469.16  4769.3  467.39  4797.4  464.02  4812.0  463.02  4819.3  461.09
  4855.8  456.24  4869.3  455.11  4876.6  453.12  4891.2  452.27  4907.9  449.38
  4926.6  448.13  4941.2  446.20  4971.9  446.74  4997.9  445.86  5000.7  445.36
  5003.9  445.86  5127.4  447.33  5148.5  450.41  5169.6  452.28  5190.7  455.57
  5201.2  456.36  5211.7  458.85  5232.8  461.28  5243.4  464.25  5285.5  469.35
#Mann=4,-1,0
  4719.3    0.16       0  4907.9    0.05       0  4997.9    0.03       0
  5003.9    0.05       0
Bank Sta=4997.9,5003.9
Exp/Cntr=0.3,0.1

Type RM Length L Ch R = 1,15721,453,453,453
BEGIN DESCRIPTION:
UNT 087 IN CACR 31.0
END DESCRIPTION:
XS GIS Cut Line= 3
      3732249.64     10717460.21      3732349.61     10717510.19
      3732649.59     10717810.17
#Sta/Elev= 30
  4866.9  458.51  4879.6  457.96  4889.2  456.46  4897.6  454.57  4903.2  454.08
  4911.6  452.61  4920.0  450.49  4925.6  450.29  4933.9  449.20  4942.3  447.40
  4956.3  446.35  4964.7  444.21  4970.3  444.23  4975.9  442.68  4982.2  442.68
  4989.8  441.60  4992.6  441.10  4995.8  441.60  5021.1  442.03  5063.5  441.89
  5120.1  442.49  5162.5  443.62  5233.2  443.43  5275.6  444.33  5303.9  444.40
  5346.4  448.11  5360.5  450.15  5374.6  451.32  5399.4  455.15  5402.9  455.15
#Mann=4,-1,0
  4866.9    0.16       0  4879.6    0.05       0  4989.8    0.03       0
  4995.8    0.05       0
Bank Sta=4989.8,4995.8
Exp/Cntr=0.3,0.1

Type RM Length L Ch R = 1,15268,352,352,352
BEGIN DESCRIPTION:
UNT 087 IN CACR 30.0
END DESCRIPTION:
XS GIS Cut Line= 3
      3731999.63     10717660.23      3732099.61     10717860.19
      3732399.59     10718160.17
#Sta/Elev= 30
  4767.5  459.18  4781.4  458.26  4789.8  456.64  4820.6  454.14  4834.5  452.01
  4879.3  448.31  4887.6  447.04  4901.6  446.58  4910.0  445.46  4924.0  445.20
  4946.3  443.39  4954.7  442.05  4960.3  442.33  4977.1  439.45  4982.7  439.63
  4988.3  437.26  4994.6  437.26  5002.2  436.06  5005.0  435.56  5008.2  436.06
  5019.3  437.97  5033.5  438.46  5132.5  436.81  5146.6  437.81  5160.8  437.46
  5316.3  439.49  5330.5  439.87  5344.6  441.20  5358.8  441.52  5415.3  445.26
#Mann=3,-1,0
  4767.5    0.05       0  5002.2    0.03       0  5008.2    0.05       0
Bank Sta=5002.2,5008.2
Exp/Cntr=0.3,0.1

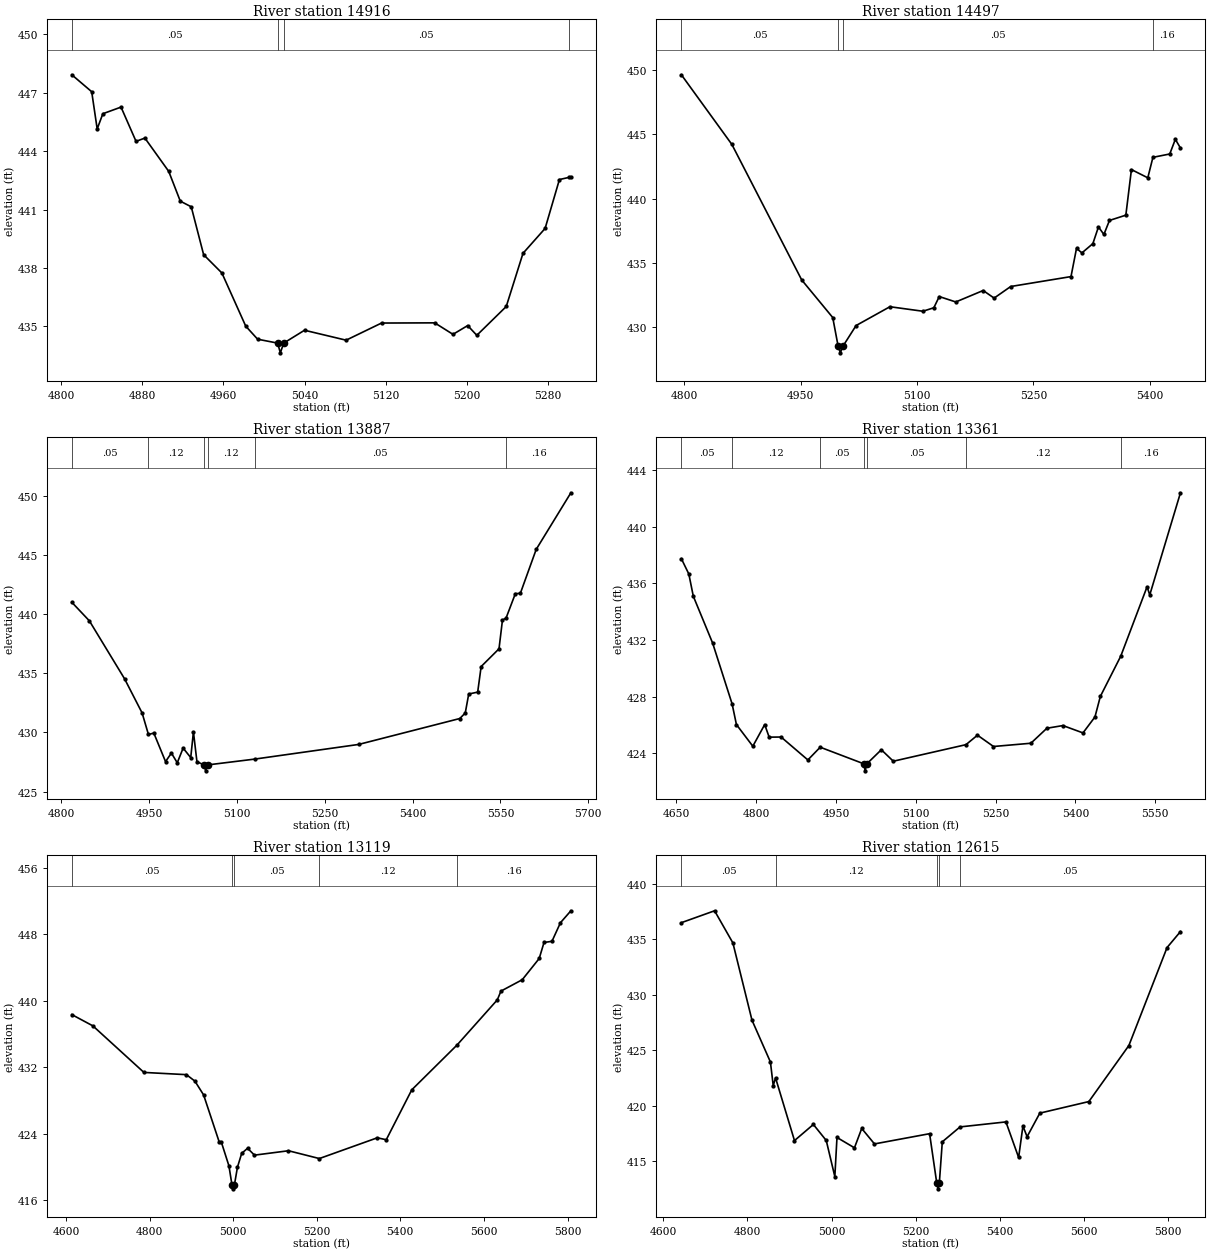
Type RM Length L Ch R = 1,14916,419,419,419
BEGIN DESCRIPTION:
UNT 087 IN CACR 29.0
END DESCRIPTION:
XS GIS Cut Line= 2
      3731714.71     10717822.12      3731910.01     10718273.48
#Sta/Elev= 30
  4810.7  447.92  4830.3  447.05  4835.7  445.14  4841.3  445.92  4859.2  446.26
  4874.0  444.50  4882.7  444.67  4906.2  442.96  4917.6  441.43  4928.4  441.14
  4940.6  438.68  4958.6  437.74  4982.1  435.01  4993.8  434.34  5013.5  434.14
  5016.2  433.64  5019.5  434.14  5040.0  434.80  5081.0  434.29  5115.9  435.17
  5168.3  435.18  5186.3  434.59  5200.8  435.04  5209.8  434.54  5238.8  436.02
  5255.3  438.75  5277.1  440.03  5291.2  442.54  5300.6  442.65  5302.5  442.65
#Mann=4,-1,0
  4810.7    0.05       0  5013.5    0.03       0  5019.5    0.05       0
  5300.6    0.16       0
Bank Sta=5013.5,5019.5
Exp/Cntr=0.3,0.1

Type RM Length L Ch R = 1,14497,610,610,610
BEGIN DESCRIPTION:
UNT 087 IN CACR 28.0
END DESCRIPTION:
XS GIS Cut Line= 3
      3731384.85     10717835.18      3731393.53     10718073.86
      3731675.16     10718364.16
#Sta/Elev= 30
  4796.3  449.62  4861.4  444.21  4951.4  433.69  4991.4  430.77  4998.4  428.53
  5001.2  428.03  5004.4  428.53  5021.5  430.15  5065.1  431.61  5107.6  431.26
  5121.7  431.53  5128.7  432.40  5150.0  431.98  5185.3  432.87  5199.4  432.28
  5220.8  433.18  5298.5  433.95  5305.6  436.14  5312.6  435.79  5326.7  436.51
  5333.9  437.81  5340.9  437.22  5348.1  438.31  5369.2  438.72  5376.4  442.26
  5397.5  441.62  5404.1  443.21  5425.8  443.47  5433.0  444.61  5439.6  443.93
#Mann=4,-1,0
  4796.3    0.05       0  4998.4    0.03       0  5004.4    0.05       0
  5404.1    0.16       0
Bank Sta=4998.4,5004.4
Exp/Cntr=0.3,0.1

Type RM Length L Ch R = 1,13887,526,526,526
BEGIN DESCRIPTION:
UNT 087 IN CACR 27.0
END DESCRIPTION:
XS GIS Cut Line= 3
      3730949.61     10717860.18      3730949.61     10718060.19
      3731499.58     10718410.17
#Sta/Elev= 30
  4818.4  441.00  4848.4  439.43  4908.4  434.54  4938.4  431.65  4949.2  429.83
  4958.4  429.95  4978.4  427.54  4988.4  428.26  4998.4  427.44  5008.4  428.68
  5021.4  427.88  5026.0  430.05  5032.0  427.53  5044.2  427.26  5046.9  426.76
  5050.2  427.26  5130.3  427.75  5308.0  428.99  5480.7  431.18  5490.0  431.65
  5495.9  433.25  5511.2  433.41  5517.1  435.57  5547.6  437.07  5553.5  439.50
  5559.6  439.66  5575.5  441.73  5584.0  441.75  5611.1  445.47  5670.3  450.25
#Mann=6,-1,0
  4818.4    0.05       0  4949.2    0.12       0  5044.2    0.07       0
  5050.2    0.12       0  5130.3    0.05       0  5559.6    0.16       0
Bank Sta=5044.2,5050.2
Exp/Cntr=0.3,0.1

Type RM Length L Ch R = 1,13361,242,242,242
BEGIN DESCRIPTION:
UNT 087 IN CACR 26.0
END DESCRIPTION:
XS GIS Cut Line= 3
      3730699.61     10717960.18      3730549.61     10718260.19
      3730499.61     10718860.19
#Sta/Elev= 30
  4659.7  437.74  4673.7  436.66  4682.1  435.09  4718.4  431.78  4755.0  427.48
  4763.1  426.02  4793.9  424.49  4816.2  426.02  4824.6  425.13  4847.0  425.14
  4897.3  423.52  4920.5  424.42  5002.2  423.25  5004.9  422.75  5008.2  423.25
  5035.3  424.24  5057.8  423.43  5194.3  424.60  5215.9  425.27  5246.0  424.47
  5316.2  424.70  5346.3  425.76  5376.4  425.95  5414.1  425.43  5436.6  426.56
  5446.7  428.01  5485.0  430.85  5534.5  435.76  5539.5  435.18  5597.2  442.40
#Mann=7,-1,0
  4659.7    0.05       0  4755.0    0.12       0  4920.5    0.05       0
  5002.2    0.03       0  5008.2    0.05       0  5194.3    0.12       0
  5485.0    0.16       0
Bank Sta=5002.2,5008.2
Exp/Cntr=0.3,0.1

Type RM Length L Ch R = 1,13119,504,504,504
BEGIN DESCRIPTION:
Mapping XS fab32648
END DESCRIPTION:
XS GIS Cut Line= 4
      3730381.50     10717880.64      3730316.40     10718230.05
      3730255.63     10718553.40      3730346.79     10719054.75
#Sta/Elev= 30
  4614.1  438.34  4664.5  436.98  4786.6  431.37  4888.3  431.10  4908.6  430.32
  4929.4  428.66  4967.1  422.93  4972.1  422.93  4990.0  420.11  4997.2  417.84
  4999.9  417.34  5003.2  417.84  5010.4  419.95  5020.5  421.61  5034.6  422.23
  5051.1  421.40  5132.5  421.93  5206.3  420.99  5344.9  423.49  5366.4  423.26
  5427.4  429.27  5535.7  434.67  5632.0  440.11  5640.8  441.17  5691.7  442.54
  5732.3  445.10  5743.8  447.03  5762.8  447.17  5783.1  449.41  5808.1  450.85
#Mann=5,-1,0
  4614.1    0.05       0  4997.2    0.03       0  5003.2    0.05       0
  5206.3    0.12       0  5535.7    0.16       0
Bank Sta=4997.2,5003.2
Exp/Cntr=0.3,0.1

Type RM Length L Ch R = 1,12615,578,578,578
BEGIN DESCRIPTION:
UNT 087 IN CACR 25.0
END DESCRIPTION:
XS GIS Cut Line= 3
      3730416.95     10717861.19      3730013.32     10717943.65
      3729917.83     10718711.87
#Sta/Elev= 30
  4643.0  436.48  4721.9  437.55  4765.4  434.66  4810.8  427.71  4854.6  423.95
  4861.3  421.82  4866.8  422.52  4911.8  416.88  4956.7  418.33  4987.3  416.89
  5007.7  413.64  5012.8  417.16  5054.3  416.23  5071.6  417.97  5101.9  416.58
  5232.9  417.50  5250.0  413.04  5252.8  412.54  5256.0  413.04  5263.1  416.77
  5305.3  418.11  5414.3  418.56  5444.5  415.36  5454.7  418.19  5464.6  417.23
  5494.9  419.35  5611.4  420.39  5706.5  425.43  5797.2  434.24  5829.1  435.68
#Mann=5,-1,0
  4643.0    0.05       0  4866.8    0.12       0  5250.0    0.07       0
  5256.0    0.12       0  5305.3    0.05       0
Bank Sta=5250,5256
Exp/Cntr=0.3,0.1

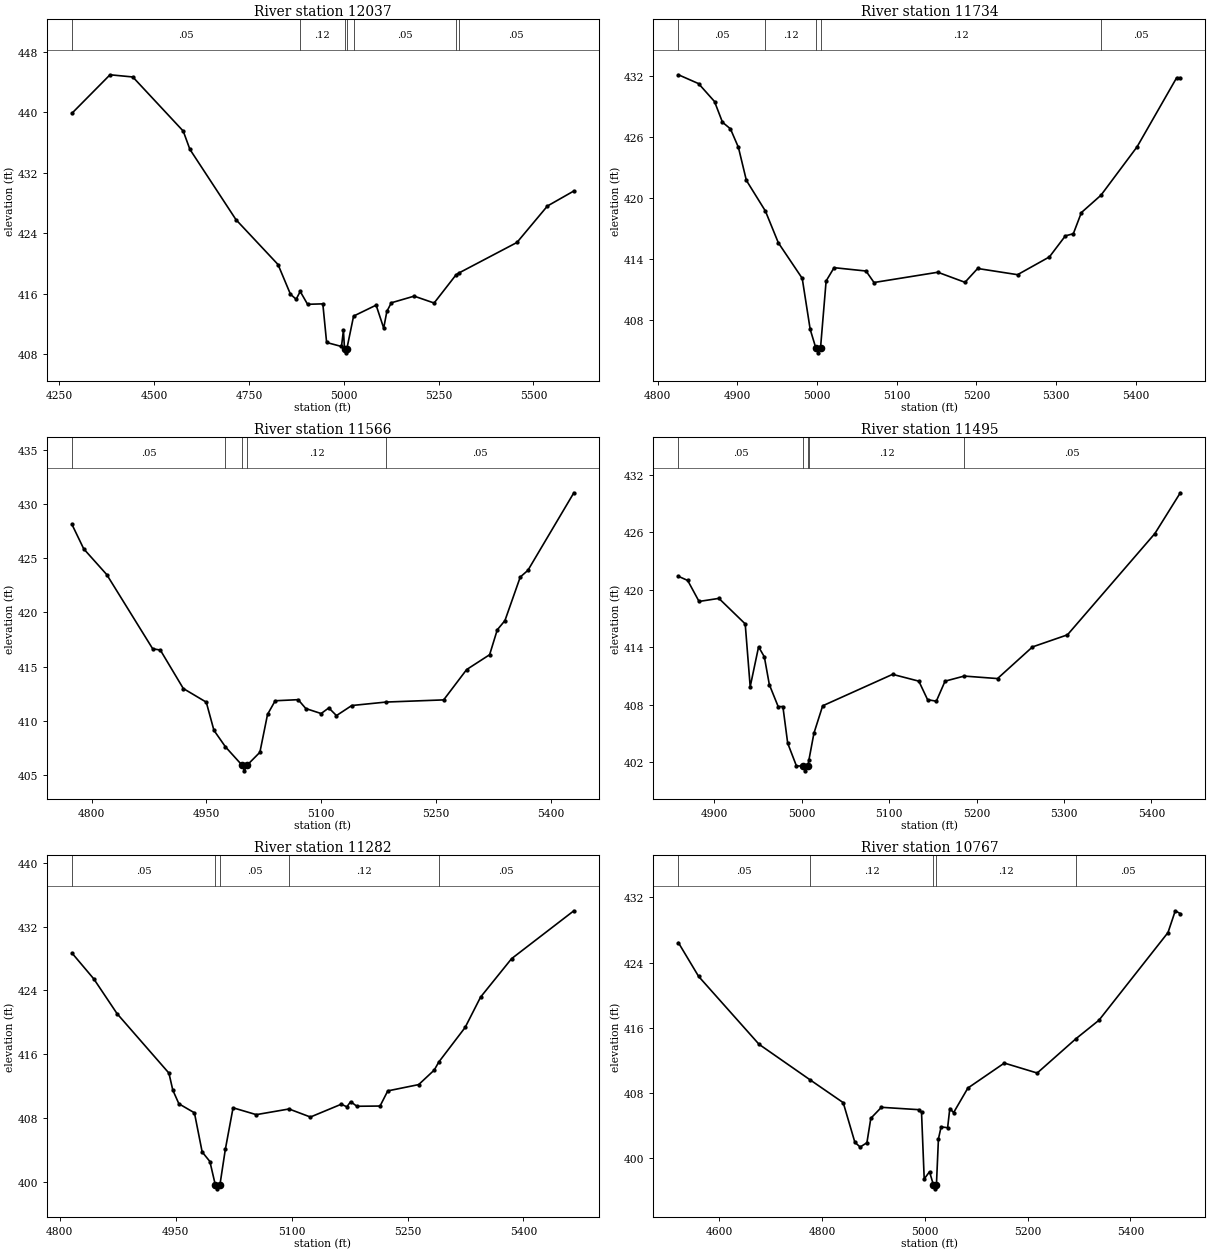
Type RM Length L Ch R = 1,12037,303,303,303
BEGIN DESCRIPTION:
UNT 087 IN CACR 24.0
END DESCRIPTION:
XS GIS Cut Line= 4
      3729681.26     10717349.75      3729681.26     10717595.00
      3729796.28     10717905.33      3729733.35     10718649.67
#Sta/Elev= 30
  4283.4  439.85  4383.8  444.94  4443.8  444.65  4576.8  437.49  4594.3  435.08
  4715.9  425.77  4826.7  419.84  4859.5  415.91  4874.5  415.25  4885.2  416.28
  4904.6  414.58  4944.8  414.64  4954.8  409.53  4994.0  409.00  4999.1  411.14
  5002.0  408.66  5004.7  408.16  5008.0  408.66  5025.9  413.02  5085.3  414.47
  5105.3  411.43  5113.6  413.64  5125.4  414.78  5185.6  415.66  5238.2  414.75
  5295.7  418.46  5302.7  418.70  5456.6  422.76  5536.9  427.58  5606.6  429.57
#Mann=7,-1,0
  4283.4    0.05       0  4885.2    0.12       0  5002.0    0.07       0
  5008.0    0.12       0  5025.9    0.05       0  5295.7    0.12       0
  5302.7    0.05       0
Bank Sta=5002,5008
Exp/Cntr=0.3,0.1

Type RM Length L Ch R = 1,11734,168,168,168
BEGIN DESCRIPTION:
UNT 087 IN CACR 23.0
END DESCRIPTION:
XS GIS Cut Line= 2
      3729520.67     10717874.94      3729492.46     10718504.31
#Sta/Elev= 30
  4826.0  432.14  4851.3  431.27  4871.3  429.51  4881.3  427.47  4891.3  426.82
  4901.3  425.00  4911.3  421.75  4935.2  418.73  4951.4  415.61  4981.4  412.11
  4991.4  407.09  4998.4  405.28  5001.2  404.78  5004.4  405.28  5011.4  411.85
  5021.4  413.16  5061.5  412.83  5071.5  411.70  5151.6  412.71  5185.7  411.72
  5201.6  413.08  5251.7  412.47  5291.7  414.22  5311.7  416.29  5321.7  416.50
  5331.8  418.58  5356.4  420.29  5401.8  425.06  5451.4  431.85  5456.0  431.85
#Mann=5,-1,0
  4826.0    0.05       0  4935.2    0.12       0  4998.4    0.07       0
  5004.4    0.12       0  5356.4    0.05       0
Bank Sta=4998.4,5004.4
Exp/Cntr=0.3,0.1

Type RM Length L Ch R = 1,11566,71,71,71
BEGIN DESCRIPTION:
Mapping XS fcc34030
END DESCRIPTION:
XS GIS Cut Line= 2
      3729365.48     10717844.76      3729365.48     10718500.16
#Sta/Elev= 30
  4774.4  428.13  4789.8  425.87  4819.8  423.50  4879.8  416.65  4889.8  416.53
  4919.8  412.98  4949.8  411.72  4959.8  409.12  4974.9  407.59  4996.8  405.88
  4999.6  405.38  5002.8  405.88  5019.8  407.09  5029.8  410.59  5039.8  411.85
  5069.8  411.95  5079.8  411.13  5099.8  410.67  5109.8  411.19  5119.8  410.48
  5139.8  411.41  5184.6  411.73  5259.8  411.93  5289.8  414.73  5319.8  416.10
  5329.8  418.40  5339.8  419.25  5359.8  423.27  5369.8  423.89  5429.8  431.05
#Mann=5,-1,0
  4774.4    0.05       0  4974.9    0.12       0  4996.8    0.07       0
  5002.8    0.12       0  5184.6    0.05       0
Bank Sta=4996.8,5002.8
Exp/Cntr=0.3,0.1

Type RM Length L Ch R = 1,11495,213,213,213
BEGIN DESCRIPTION:
UNT 087 IN CACR 22.0
END DESCRIPTION:
XS GIS Cut Line= 3
      3729237.70     10717939.37      3729294.14     10718044.65
      3729290.88     10718499.28
#Sta/Elev= 30
  4859.0  421.39  4869.6  420.96  4882.6  418.77  4905.3  419.09  4935.4  416.43
  4941.1  409.88  4950.7  414.04  4957.3  412.99  4963.0  410.10  4973.1  407.81
  4978.5  407.81  4984.0  403.99  4994.0  401.62  5001.0  401.61  5003.7  401.11
  5007.0  401.61  5008.3  402.25  5014.0  405.03  5024.0  407.89  5104.0  411.17
  5134.0  410.46  5144.0  408.53  5154.0  408.37  5164.0  410.46  5185.9  410.99
  5224.0  410.73  5264.0  414.03  5304.0  415.29  5404.0  425.85  5433.1  430.10
#Mann=5,-1,0
  4859.0    0.05       0  5001.0    0.03       0  5007.0    0.05       0
  5008.3    0.12       0  5185.9    0.05       0
Bank Sta=5001,5007
Exp/Cntr=0.3,0.1

Type RM Length L Ch R = 1,11282,515,515,515
BEGIN DESCRIPTION:
Mapping XS b25376f6
END DESCRIPTION:
XS GIS Cut Line= 2
      3729090.15     10717881.87      3729061.93     10718530.76
#Sta/Elev= 30
  4815.7  428.70  4844.0  425.45  4874.1  421.09  4941.2  413.63  4946.2  411.50
  4954.1  409.78  4974.2  408.65  4984.2  403.74  4994.2  402.54  5001.2  399.61
  5003.9  399.11  5007.2  399.61  5014.2  404.07  5024.2  409.28  5054.2  408.42
  5096.6  409.13  5124.3  408.12  5164.3  409.73  5171.4  409.40  5176.4  410.05
  5184.4  409.47  5214.4  409.50  5224.4  411.40  5264.4  412.19  5284.5  414.01
  5290.4  415.02  5324.5  419.36  5344.5  423.17  5384.6  427.99  5465.2  434.00
#Mann=5,-1,0
  4815.7    0.05       0  5001.2    0.03       0  5007.2    0.05       0
  5096.6    0.12       0  5290.4    0.05       0
Bank Sta=5001.2,5007.2
Exp/Cntr=0.3,0.1

Type RM Length L Ch R = 1,10767,248,248,248
BEGIN DESCRIPTION:
UNT 087 IN CACR 21.0
END DESCRIPTION:
XS GIS Cut Line= 4
      3728684.32     10717717.34      3728580.16     10718127.50
      3728608.37     10718220.81      3728942.55     10718531.12
#Sta/Elev= 30
  4520.3  426.43  4559.6  422.30  4677.2  413.98  4776.2  409.64  4841.0  406.83
  4863.7  401.97  4874.0  401.39  4887.1  401.92  4894.7  404.91  4915.3  406.26
  4988.1  405.97  4993.4  405.63  4998.6  397.48  5009.0  398.37  5016.4  396.77
  5019.2  396.27  5022.4  396.77  5026.3  402.39  5031.5  403.86  5044.2  403.76
  5048.4  406.11  5055.8  405.61  5083.6  408.62  5154.5  411.68  5218.5  410.46
  5294.0  414.67  5338.7  416.93  5473.0  427.67  5487.2  430.34  5497.0  429.99
#Mann=5,-1,0
  4520.3    0.05       0  4776.2    0.12       0  5016.4    0.07       0
  5022.4    0.12       0  5294.0    0.05       0
Bank Sta=5016.4,5022.4
Exp/Cntr=0.3,0.1

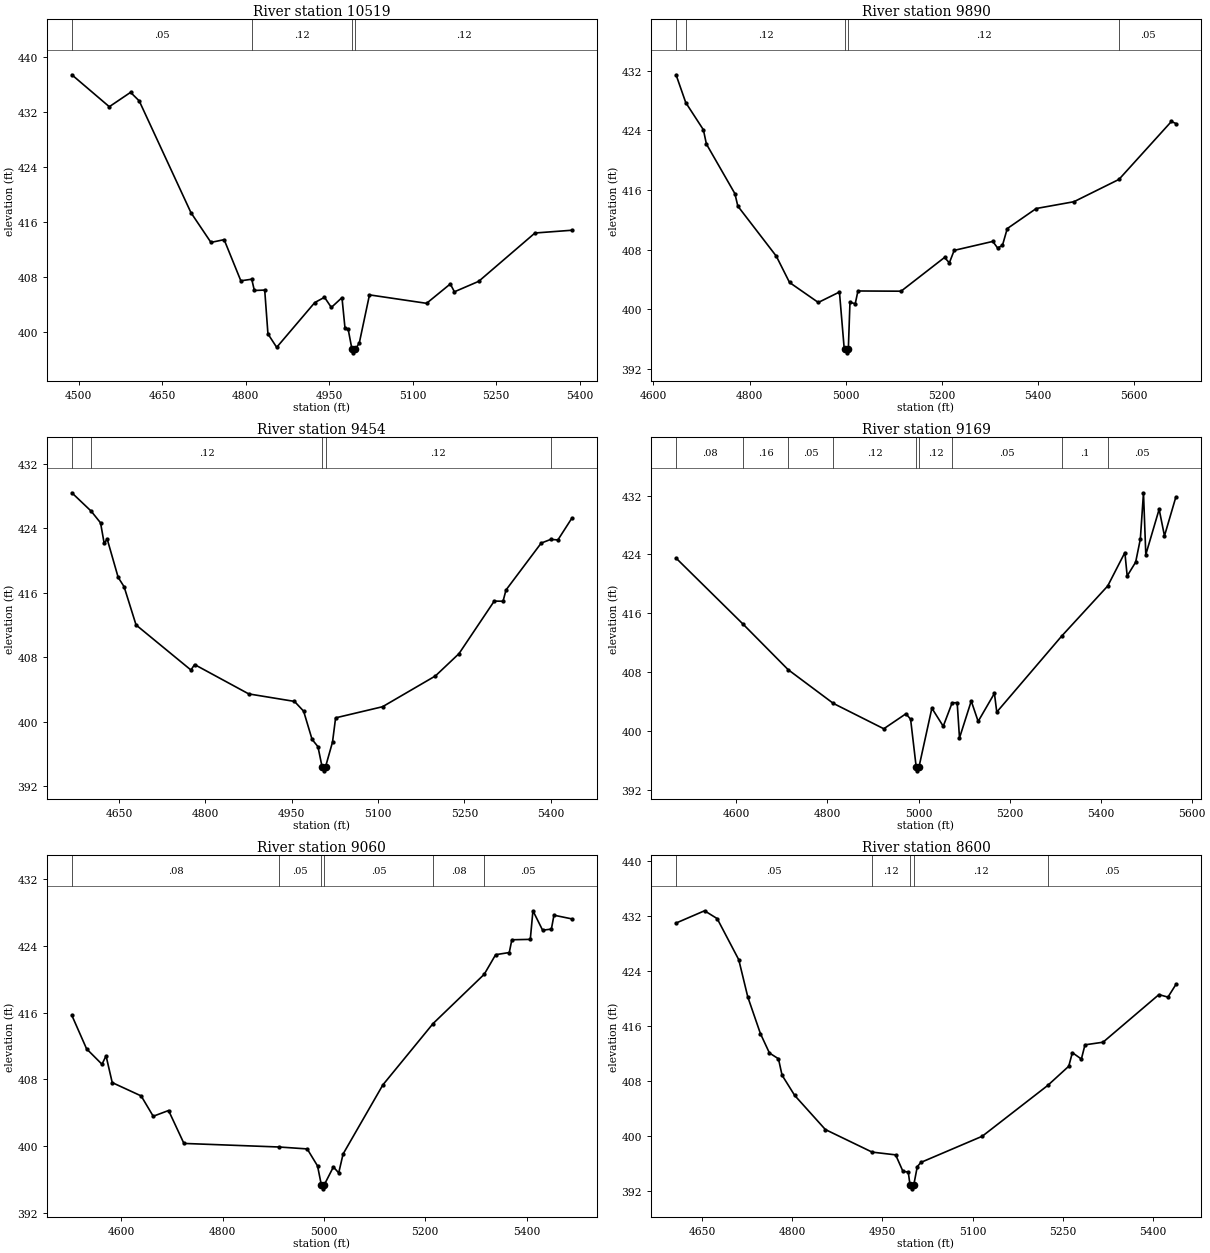
Type RM Length L Ch R = 1,10519,629,629,629
BEGIN DESCRIPTION:
UNT 087 IN CACR 20.0
END DESCRIPTION:
XS GIS Cut Line= 4
      3727926.98     10717986.45      3728384.80     10718165.90
      3728393.48     10718211.04      3728467.31     10718563.70
#Sta/Elev= 30
  4487.8  437.45  4555.1  432.80  4593.3  434.89  4608.8  433.65  4701.8  417.37
  4737.7  413.04  4761.4  413.44  4791.4  407.45  4811.0  407.68  4815.7  406.04
  4834.3  406.10  4840.1  399.72  4855.8  397.76  4924.2  404.28  4941.7  405.05
  4954.0  403.57  4973.1  405.00  4978.5  400.59  4984.3  400.37  4991.1  397.46
  4993.8  396.96  4997.1  397.46  5004.3  398.43  5022.5  405.40  5125.1  404.17
  5167.7  406.99  5175.1  405.85  5218.7  407.37  5319.8  414.41  5385.8  414.81
#Mann=4,-1,0
  4487.8    0.05       0  4811.0    0.12       0  4991.1    0.07       0
  4997.1    0.12       0
Bank Sta=4991.1,4997.1
Exp/Cntr=0.3,0.1

Type RM Length L Ch R = 1,9890,436,436,436
BEGIN DESCRIPTION:
UNT 087 IN CACR 19.0
END DESCRIPTION:
XS GIS Cut Line= 4
      3727852.56     10718328.11      3728004.46     10718549.46
      3728152.03     10718616.73      3728758.97     10718675.26
#Sta/Elev= 30
  4647.0  431.44  4667.2  427.71  4703.9  424.07  4710.2  422.16  4769.5  415.51
  4775.6  413.84  4855.7  407.13  4883.2  403.61  4943.1  400.93  4987.1  402.33
  4997.1  394.68  4999.6  394.68  5002.3  394.18  5005.6  394.68  5009.0  400.94
  5020.0  400.77  5025.6  402.47  5115.4  402.44  5205.8  406.96  5215.9  406.24
  5225.9  407.91  5306.3  409.11  5316.3  408.23  5326.4  408.58  5336.4  410.83
  5396.7  413.52  5475.2  414.43  5568.9  417.42  5678.0  425.18  5687.4  424.91
#Mann=5,-1,0
  4647.0    0.05       0  4667.2    0.12       0  4999.6    0.07       0
  5005.6    0.12       0  5568.9    0.05       0
Bank Sta=4999.6,5005.6
Exp/Cntr=0.3,0.1

Type RM Length L Ch R = 1,9454,285,285,285
BEGIN DESCRIPTION:
UNT 087 IN CACR 18.0
END DESCRIPTION:
XS GIS Cut Line= 2
      3727540.74     10718853.56      3728391.46     10719029.35
#Sta/Elev= 30
  4567.8  428.39  4601.4  426.11  4617.7  424.66  4624.0  422.11  4629.2  422.66
  4648.3  417.90  4658.6  416.74  4679.4  412.00  4774.8  406.41  4781.1  407.09
  4875.2  403.45  4954.7  402.52  4970.6  401.31  4985.3  397.81  4995.5  396.91
  5002.7  394.41  5005.5  393.91  5008.7  394.41  5020.8  397.47  5026.2  400.48
  5107.8  401.86  5199.7  405.68  5240.6  408.44  5301.9  414.96  5317.2  414.94
  5322.3  416.33  5383.5  422.15  5400.1  422.61  5412.5  422.54  5436.5  425.21
#Mann=5,-1,0
  4567.8    0.16       0  4601.4    0.12       0  5002.7    0.07       0
  5008.7    0.12       0  5400.1    0.05       0
Bank Sta=5002.7,5008.7
Exp/Cntr=0.3,0.1

Type RM Length L Ch R = 1,9169,109,109,109
BEGIN DESCRIPTION:
Mapping XS ffb1860d
END DESCRIPTION:
XS GIS Cut Line= 4
      3727317.85     10719122.81      3727824.78     10719181.84
      3727876.86     10719190.52      3728395.32     10719322.30
#Sta/Elev= 30
  4467.3  423.51  4614.4  414.54  4713.6  408.34  4812.8  403.76  4923.7  400.31
  4972.4  402.35  4982.6  401.60  4994.9  395.09  4997.7  394.59  5000.9  395.09
  5029.3  403.11  5054.3  400.65  5073.8  403.83  5084.9  403.86  5090.0  399.06
  5115.8  404.08  5131.0  401.31  5166.7  405.12  5171.9  402.58  5314.5  412.91
  5415.6  419.72  5453.3  424.26  5458.4  421.08  5477.0  422.96  5487.3  426.10
  5494.2  432.39  5499.3  423.99  5528.6  430.15  5540.3  426.53  5565.4  431.83
#Mann=9,-1,0
  4467.3    0.08       0  4614.4    0.16       0  4713.6    0.05       0
  4812.8    0.12       0  4994.9    0.07       0  5000.9    0.12       0
  5073.8    0.05       0  5314.5     0.1       0  5415.6    0.05       0
Bank Sta=4994.9,5000.9
Exp/Cntr=0.3,0.1

Type RM Length L Ch R = 1,9060,460,460,460
BEGIN DESCRIPTION:
UNT 087 IN CACR 17.0
END DESCRIPTION:
XS GIS Cut Line= 4
      3727350.78     10719214.82      3727805.68     10719282.53
      3727927.21     10719318.99      3728315.39     10719414.30
#Sta/Elev= 30
  4502.6  415.67  4531.7  411.65  4562.1  409.80  4570.1  410.81  4582.3  407.60
  4639.4  406.00  4663.2  403.56  4693.5  404.25  4723.8  400.30  4911.9  399.87
  4967.1  399.64  4987.5  397.60  4994.9  395.35  4997.7  394.85  5000.9  395.35
  5018.8  397.48  5029.3  396.76  5037.9  399.03  5116.5  407.33  5215.6  414.69
  5316.5  420.60  5339.0  422.95  5365.9  423.21  5371.0  424.74  5407.4  424.79
  5412.6  428.22  5431.7  425.89  5449.0  426.02  5454.1  427.69  5489.1  427.25
#Mann=6,-1,0
  4502.6    0.08       0  4911.9    0.05       0  4994.9    0.04       0
  5000.9    0.05       0  5215.6    0.08       0  5316.5    0.05       0
Bank Sta=4994.9,5000.9
Exp/Cntr=0.3,0.1

Type RM Length L Ch R = 1,8600,432,432,432
BEGIN DESCRIPTION:
UNT 087 IN CACR 16.0
END DESCRIPTION:
XS GIS Cut Line= 2
      3727146.58     10719247.90      3727836.13     10719712.22
#Sta/Elev= 30
  4606.9  430.98  4654.3  432.77  4675.3  431.63  4711.2  425.64  4726.2  420.22
  4747.2  414.88  4762.2  412.05  4777.2  411.21  4783.2  408.82  4804.2  405.87
  4855.2  400.90  4933.0  397.61  4972.1  397.21  4984.3  394.80  4993.1  394.71
  4996.1  392.76  4998.9  392.26  5002.1  392.76  5008.1  395.49  5014.1  396.11
  5116.1  399.92  5225.0  407.32  5260.0  410.12  5266.0  412.10  5281.0  411.17
  5287.0  413.24  5317.0  413.62  5410.0  420.56  5425.0  420.19  5438.2  422.03
#Mann=5,-1,0
  4606.9    0.05       0  4933.0    0.12       0  4996.1    0.07       0
  5002.1    0.12       0  5225.0    0.05       0
Bank Sta=4996.1,5002.1
Exp/Cntr=0.3,0.1