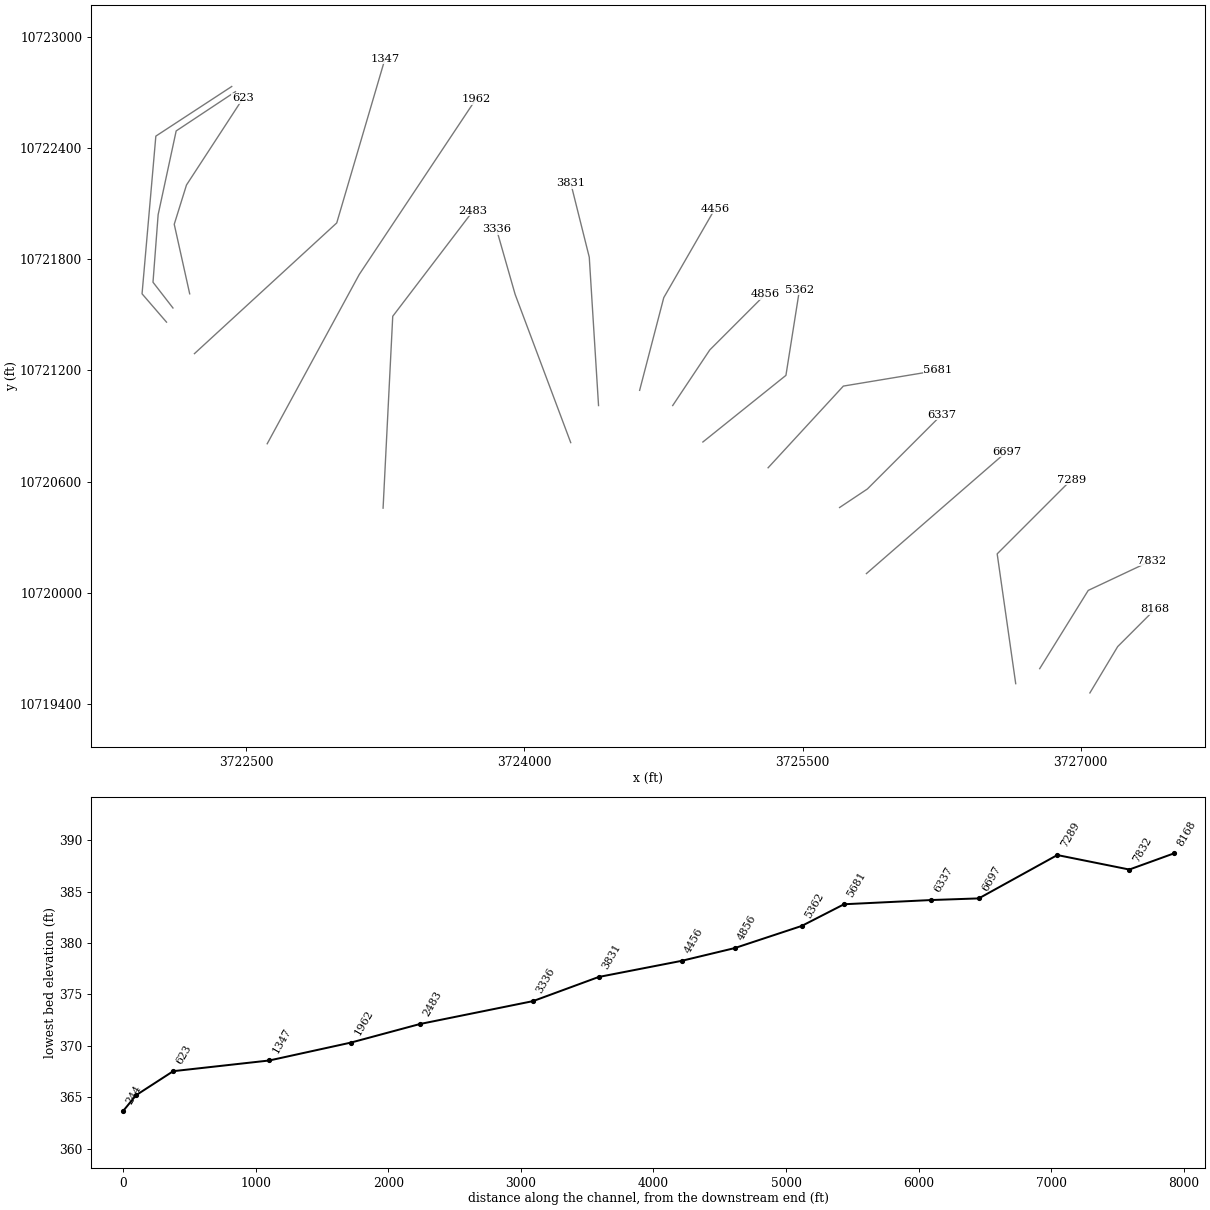
HEC-RAS study UNT 087 IN CACR.prj: UNT 087 IN CACR Base Level Engineering

--- UNT 087 IN CACR.g01 (geometry) --- (continued)

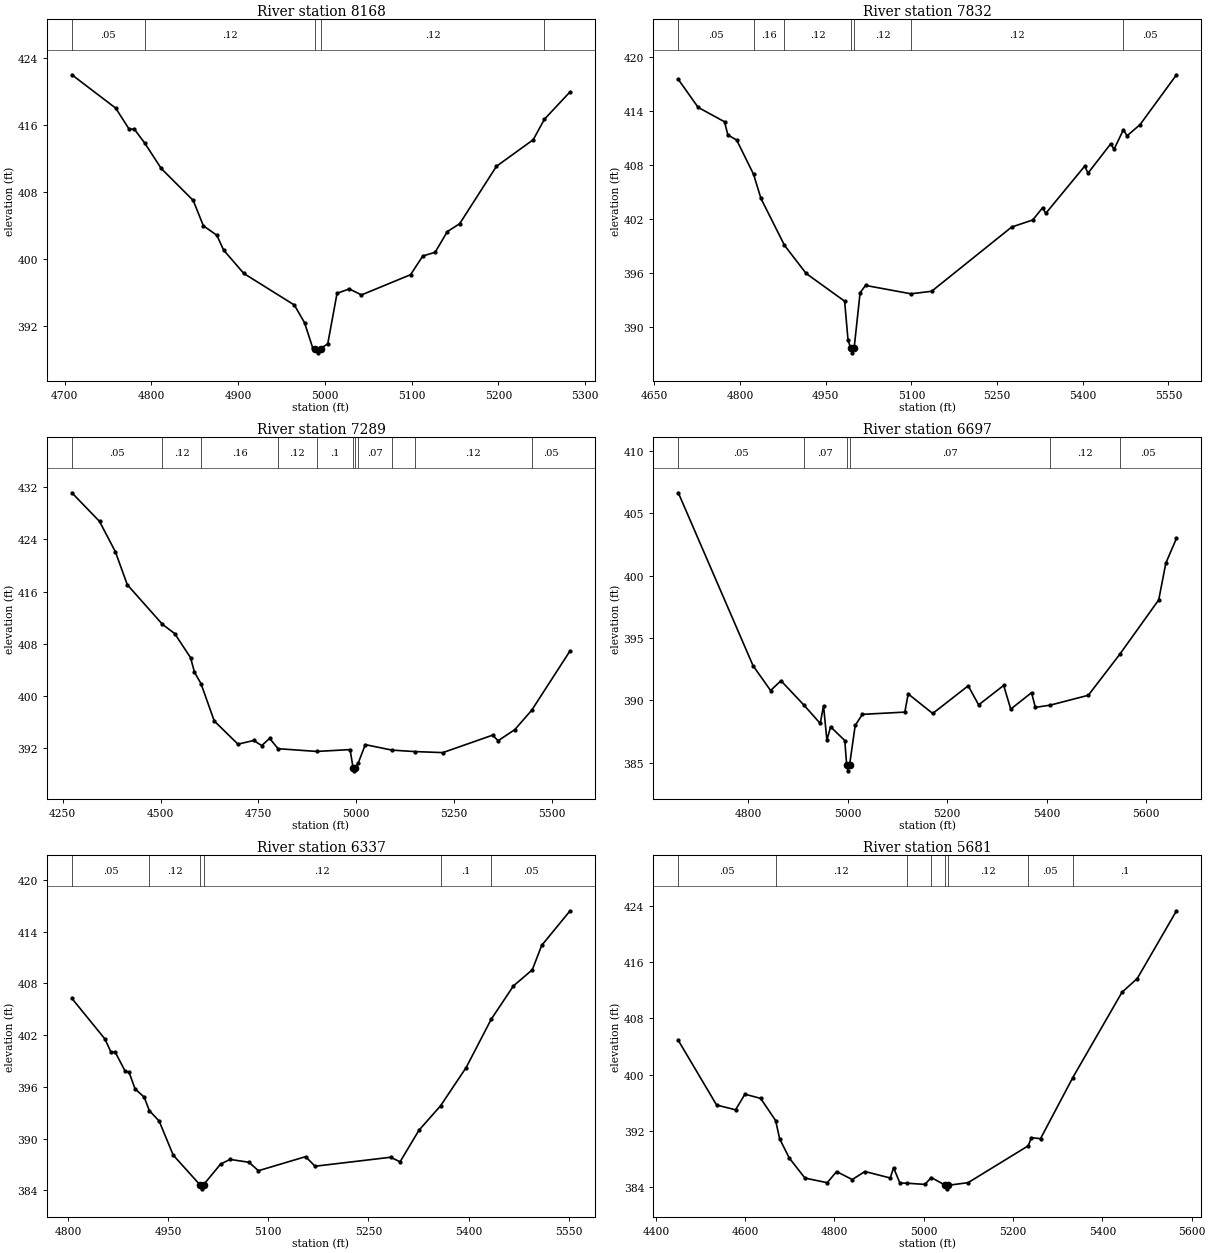
Type RM Length L Ch R = 1,8168,336,336,336
BEGIN DESCRIPTION:
UNT 087 IN CACR 15.0
END DESCRIPTION:
XS GIS Cut Line= 3
      3727049.63     10719460.22      3727199.61     10719710.19
      3727399.64     10719910.22
#Sta/Elev= 30
  4708.3  422.00  4758.8  418.01  4774.3  415.49  4780.2  415.51  4792.2  413.84
  4811.3  410.79  4848.2  406.96  4859.9  403.93  4875.4  402.80  4883.2  401.03
  4906.5  398.23  4964.8  394.45  4976.5  392.34  4986.2  389.25  4989.0  389.23
  4991.8  388.73  4995.0  389.23  5003.3  389.81  5014.0  395.85  5028.1  396.38
  5042.2  395.66  5098.8  398.08  5112.9  400.32  5127.1  400.76  5141.2  403.24
  5155.4  404.18  5197.8  411.05  5240.2  414.23  5253.1  416.68  5282.7  419.96
#Mann=5,-1,0
  4708.3    0.05       0  4792.2    0.12       0  4989.0    0.07       0
  4995.0    0.12       0  5253.1    0.05       0
Bank Sta=4989,4995
Exp/Cntr=0.3,0.1

Type RM Length L Ch R = 1,7832,543,543,543
BEGIN DESCRIPTION:
UNT 087 IN CACR 14.0
END DESCRIPTION:
XS GIS Cut Line= 3
      3726778.97     10719591.20      3727040.71     10720013.11
      3727380.56     10720173.27
#Sta/Elev= 30
  4691.8  417.50  4726.6  414.39  4772.7  412.80  4778.6  411.33  4794.0  410.77
  4823.5  406.98  4836.5  404.29  4877.7  399.09  4915.6  395.97  4983.0  392.89
  4988.9  388.62  4993.6  387.66  4996.3  387.16  4999.6  387.66  5010.1  393.83
  5019.6  394.64  5099.1  393.71  5135.3  393.99  5275.5  401.12  5312.3  401.90
  5329.6  403.26  5335.1  402.63  5403.5  407.89  5409.0  407.09  5449.0  410.36
  5454.6  409.74  5471.1  411.91  5477.4  411.24  5500.1  412.47  5564.0  418.01
#Mann=7,-1,0
  4691.8    0.05       0  4823.5    0.16       0  4877.7    0.12       0
  4993.6    0.07       0  4999.6    0.12       0  5099.1    0.12       0
  5471.1    0.05       0
Bank Sta=4993.6,4999.6
Exp/Cntr=0.3,0.1

Type RM Length L Ch R = 1,7289,592,592,592
BEGIN DESCRIPTION:
UNT 087 IN CACR 13.0
END DESCRIPTION:
XS GIS Cut Line= 3
      3726649.61     10719510.15      3726549.61     10720210.19
      3726949.59     10720610.17
#Sta/Elev= 30
  4273.3  431.13  4344.0  426.74  4384.5  422.09  4414.8  417.06  4504.6  411.00
  4536.0  409.57  4576.4  405.90  4586.5  403.67  4603.1  401.92  4637.0  396.20
  4697.6  392.65  4738.0  393.22  4758.2  392.43  4778.4  393.54  4800.1  391.96
  4898.6  391.54  4984.0  391.82  4991.6  389.07  4994.3  388.57  4997.6  389.07
  5004.8  389.76  5022.9  392.58  5091.2  391.74  5149.0  391.52  5220.9  391.36
  5348.1  394.03  5362.3  393.18  5404.7  394.87  5447.7  397.82  5546.1  406.94
#Mann=11,-1,0
  4273.3    0.05       0  4504.6    0.12       0  4603.1    0.16       0
  4800.1    0.12       0  4898.6     0.1       0  4991.6    0.07       0
  4997.6     0.1       0  5004.8    0.07       0  5091.2     0.1       0
  5149.0    0.12       0  5447.7    0.05       0
Bank Sta=4991.6,4997.6
Exp/Cntr=0.3,0.1

Type RM Length L Ch R = 1,6697,360,360,360
BEGIN DESCRIPTION:
UNT 087 IN CACR 12.0
END DESCRIPTION:
XS GIS Cut Line= 3
      3725844.41     10720103.83      3726154.92     10720374.02
      3726599.63     10720760.21
#Sta/Elev= 30
  4660.0  406.65  4810.2  392.78  4845.4  390.79  4866.2  391.58  4912.4  389.62
  4945.1  388.15  4951.7  389.57  4958.5  386.81  4965.9  387.88  4994.4  386.78
  4998.1  384.85  5000.8  384.35  5004.1  384.85  5015.3  387.99  5029.6  388.88
  5115.0  389.06  5121.7  390.52  5171.0  388.95  5242.3  391.17  5263.2  389.64
  5313.5  391.20  5327.7  389.30  5369.5  390.62  5377.1  389.44  5407.1  389.62
  5483.5  390.41  5546.7  393.70  5624.9  398.06  5639.2  401.01  5660.6  403.00
#Mann=6,-1,0
  4660.0    0.05       0  4912.4    0.07       0  4998.1    0.07       0
  5004.1    0.07       0  5407.1    0.12       0  5546.7    0.05       0
Bank Sta=4998.1,5004.1
Exp/Cntr=0.3,0.1

Type RM Length L Ch R = 1,6337,656,656,656
BEGIN DESCRIPTION:
UNT 087 IN CACR 11.0
END DESCRIPTION:
XS GIS Cut Line= 3
      3725699.62     10720460.19      3725849.61     10720560.19
      3726249.64     10720960.22
#Sta/Elev= 30
  4805.9  406.26  4855.5  401.54  4864.5  400.01  4870.5  400.07  4885.5  397.85
  4891.5  397.70  4900.5  395.77  4914.1  394.82  4921.9  393.25  4936.6  392.04
  4957.6  388.10  4997.3  384.69  5000.1  384.19  5003.3  384.69  5028.6  387.06
  5042.7  387.60  5071.0  387.27  5085.2  386.29  5155.9  387.92  5170.0  386.81
  5283.2  387.85  5297.3  387.32  5325.6  390.98  5357.9  393.81  5396.3  398.25
  5433.7  403.83  5467.0  407.70  5495.3  409.57  5509.4  412.40  5551.9  416.41
#Mann=6,-1,0
  4805.9    0.05       0  4921.9    0.12       0  4997.3    0.07       0
  5003.3    0.12       0  5357.9     0.1       0  5433.7    0.05       0
Bank Sta=4997.3,5003.3
Exp/Cntr=0.3,0.1

Type RM Length L Ch R = 1,5681,319,319,319
BEGIN DESCRIPTION:
UNT 087 IN CACR 10.0
END DESCRIPTION:
XS GIS Cut Line= 3
      3725314.19     10720674.58      3725720.03     10721115.14
      3726230.06     10721199.78
#Sta/Elev= 30
  4450.1  404.86  4535.9  395.68  4578.4  395.00  4599.4  397.22  4634.6  396.62
  4668.2  393.47  4677.1  390.89  4698.6  388.16  4733.8  385.31  4783.7  384.65
  4804.7  386.23  4839.8  385.10  4868.2  386.24  4924.9  385.32  4932.3  386.78
  4946.5  384.61  4961.7  384.58  5002.6  384.41  5016.7  385.39  5048.6  384.28
  5051.3  383.78  5054.6  384.28  5099.4  384.66  5233.7  389.88  5241.3  391.05
  5261.5  390.90  5333.4  399.53  5444.0  411.69  5478.2  413.64  5566.1  423.26
#Mann=8,-1,0
  4450.1    0.05       0  4668.2    0.12       0  4961.7    0.07       0
  5016.7    0.12       0  5048.6    0.07       0  5054.6    0.12       0
  5233.7    0.05       0  5333.4     0.1       0
Bank Sta=5048.6,5054.6
Exp/Cntr=0.3,0.1

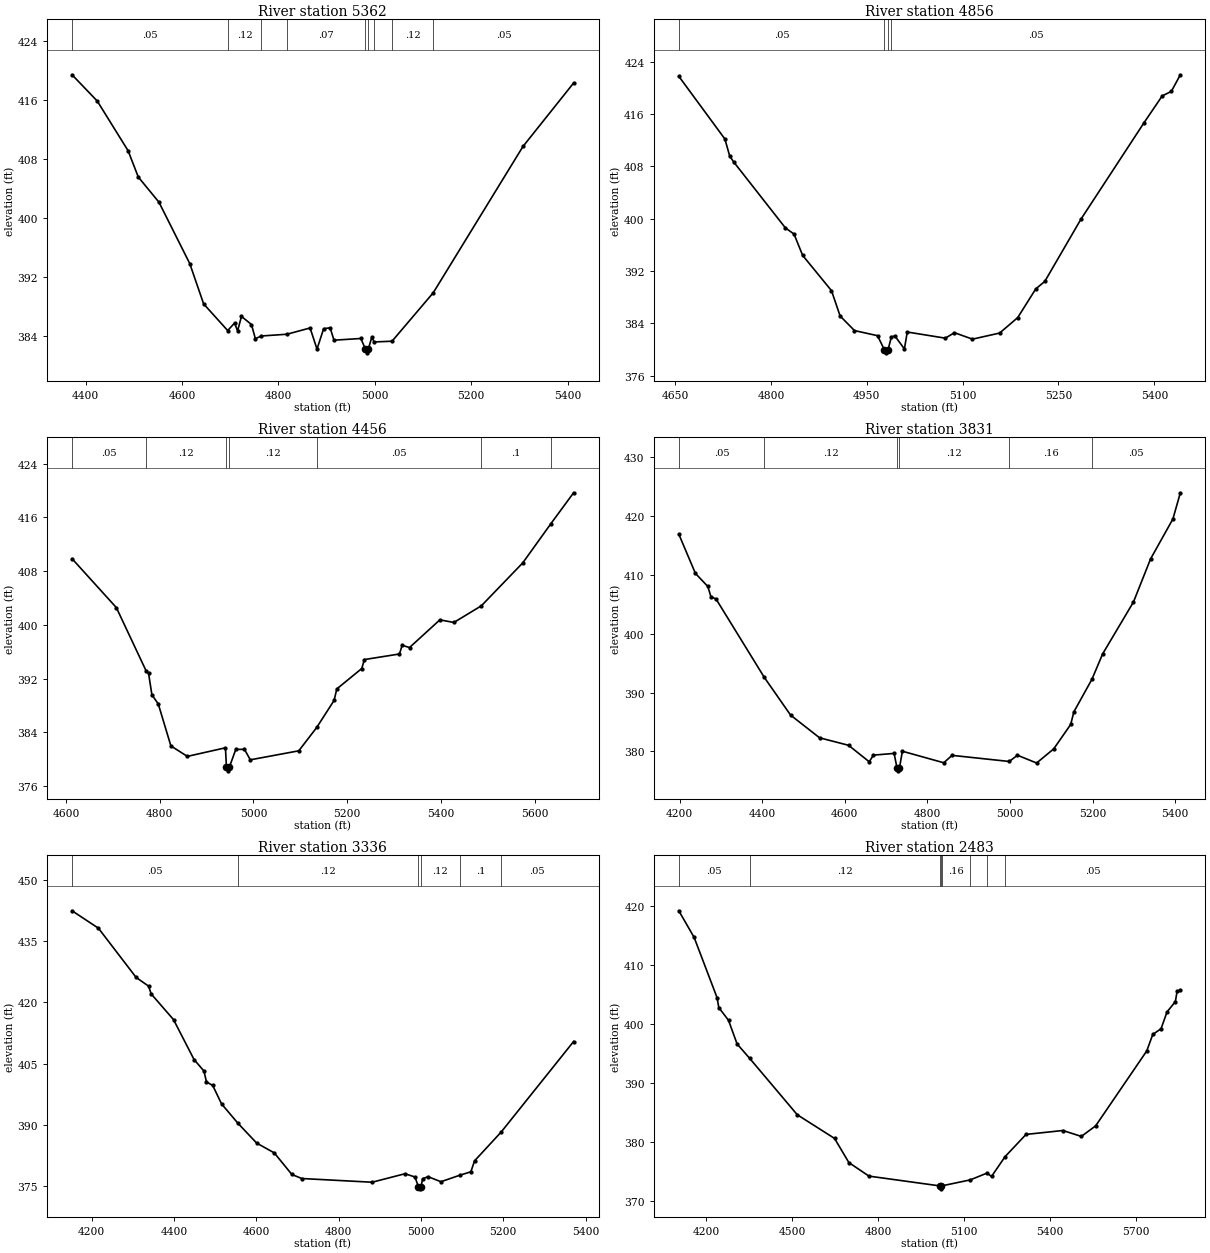
Type RM Length L Ch R = 1,5362,506,506,506
BEGIN DESCRIPTION:
UNT 087 IN CACR 9.0
END DESCRIPTION:
XS GIS Cut Line= 3
      3724962.36     10720813.61      3725410.28     10721172.98
      3725483.19     10721633.89
#Sta/Elev= 30
  4371.6  419.46  4423.9  415.89  4487.9  409.14  4509.1  405.56  4551.9  402.15
  4615.9  393.80  4644.7  388.32  4694.6  384.70  4708.8  385.71  4715.2  384.66
  4723.2  386.62  4744.0  385.52  4752.0  383.60  4764.7  383.96  4817.7  384.20
  4865.6  385.05  4880.0  382.18  4893.7  384.94  4907.2  385.08  4915.2  383.39
  4971.0  383.62  4980.5  382.17  4983.3  381.67  4986.5  382.17  4993.7  383.80
  4998.6  383.15  5035.7  383.25  5121.3  389.84  5307.5  409.72  5412.5  418.34
#Mann=9,-1,0
  4371.6    0.05       0  4694.6    0.12       0  4764.7    0.05       0
  4817.7    0.07       0  4980.5    0.03       0  4986.5    0.07       0
  4998.6    0.05       0  5035.7    0.12       0  5121.3    0.05       0
Bank Sta=4980.5,4986.5
Exp/Cntr=0.3,0.1

Type RM Length L Ch R = 1,4856,400,400,400
BEGIN DESCRIPTION:
UNT 087 IN CACR 8.0
END DESCRIPTION:
XS GIS Cut Line= 3
      3724799.61     10721010.19      3724999.61     10721310.19
      3725299.60     10721610.18
#Sta/Elev= 30
  4655.9  421.75  4728.0  412.17  4735.5  409.58  4741.5  408.70  4822.7  398.59
  4836.2  397.65  4849.7  394.39  4894.8  389.01  4908.3  385.14  4930.8  382.91
  4966.9  382.13  4977.4  380.01  4980.1  379.51  4983.4  380.01  4988.5  381.93
  4993.9  382.10  5008.9  380.11  5013.4  382.69  5073.0  381.75  5087.2  382.59
  5115.4  381.60  5157.9  382.53  5186.2  384.89  5214.4  389.27  5228.6  390.42
  5285.2  399.93  5384.1  414.69  5412.4  418.76  5426.6  419.44  5440.7  421.98
#Mann=4,-1,0
  4655.9    0.05       0  4977.4    0.03       0  4983.4    0.05       0
  4988.5    0.05       0
Bank Sta=4977.4,4983.4
Exp/Cntr=0.3,0.1

Type RM Length L Ch R = 1,4456,625,625,625
BEGIN DESCRIPTION:
UNT 087 IN CACR 7.0
END DESCRIPTION:
XS GIS Cut Line= 3
      3724621.21     10721092.23      3724751.42     10721592.25
      3725027.47     10722071.43
#Sta/Elev= 30
  4613.0  409.84  4707.5  402.56  4770.8  393.17  4776.2  392.77  4783.3  389.59
  4796.9  388.22  4823.8  381.98  4858.9  380.42  4940.2  381.70  4942.3  378.77
  4945.1  378.27  4948.3  378.77  4962.2  381.46  4980.7  381.47  4993.2  379.91
  5096.6  381.25  5134.9  384.73  5171.9  388.75  5177.7  390.46  5230.8  393.49
  5236.6  394.83  5311.3  395.66  5317.1  396.95  5332.8  396.62  5397.5  400.74
  5427.4  400.35  5486.0  402.83  5574.2  409.21  5634.5  415.07  5682.7  419.65
#Mann=7,-1,0
  4613.0    0.05       0  4770.8    0.12       0  4942.3    0.07       0
  4948.3    0.12       0  5134.9    0.05       0  5486.0     0.1       0
  5634.5    0.05       0
Bank Sta=4942.3,4948.3
Exp/Cntr=0.3,0.1

Type RM Length L Ch R = 1,3831,495,495,495
BEGIN DESCRIPTION:
UNT 087 IN CACR 6.0
END DESCRIPTION:
XS GIS Cut Line= 3
      3724399.61     10721010.14      3724349.61     10721810.19
      3724249.61     10722210.17
#Sta/Elev= 30
  4198.3  416.89  4238.4  410.24  4268.5  408.01  4276.0  406.28  4288.5  405.87
  4405.2  392.57  4468.9  386.16  4539.0  382.31  4609.1  381.04  4659.2  378.24
  4669.3  379.37  4719.4  379.66  4726.4  377.20  4729.1  376.70  4732.4  377.20
  4739.4  380.03  4839.6  378.07  4859.6  379.33  4998.1  378.29  5017.9  379.35
  5064.3  378.03  5105.6  380.42  5146.8  384.57  5154.5  386.72  5198.3  392.26
  5224.1  396.55  5298.8  405.38  5340.1  412.68  5394.2  419.47  5412.2  423.92
#Mann=6,-1,0
  4198.3    0.05       0  4405.2    0.12       0  4726.4    0.07       0
  4732.4    0.12       0  4998.1    0.16       0  5198.3    0.05       0
Bank Sta=4726.4,4732.4
Exp/Cntr=0.3,0.1

Type RM Length L Ch R = 1,3336,853,853,853
BEGIN DESCRIPTION:
UNT 087 IN CACR 5.0
END DESCRIPTION:
XS GIS Cut Line= 3
      3724249.60     10720810.21      3723949.61     10721610.19
      3723849.60     10721960.21
#Sta/Elev= 30
  4152.6  442.44  4216.7  438.17  4308.3  426.11  4338.6  423.98  4344.8  422.08
  4399.1  415.79  4448.9  406.02  4473.0  403.20  4479.2  400.53  4494.3  399.67
  4515.7  395.17  4555.9  390.37  4601.1  385.56  4643.9  383.15  4686.6  377.87
  4710.6  376.88  4881.5  375.97  4961.6  378.05  4985.6  377.25  4994.2  374.85
  4996.9  374.35  5000.2  374.85  5004.3  376.81  5017.4  377.34  5048.6  376.09
  5094.2  377.67  5121.4  378.52  5130.5  381.21  5195.0  388.25  5371.0  410.42
#Mann=6,-1,0
  4152.6    0.05       0  4555.9    0.12       0  4994.2    0.07       0
  5000.2    0.12       0  5094.2     0.1       0  5195.0    0.05       0
Bank Sta=4994.2,5000.2
Exp/Cntr=0.3,0.1

Type RM Length L Ch R = 1,2483,521,521,521
BEGIN DESCRIPTION:
UNT 087 IN CACR 4.0
END DESCRIPTION:
XS GIS Cut Line= 3
      3723237.53     10720456.80      3723289.62     10721491.56
      3723723.67     10722061.03
#Sta/Elev= 30
  4103.6  419.12  4157.1  414.62  4237.2  404.44  4243.3  402.76  4277.2  400.61
  4307.2  396.61  4351.2  394.17  4517.5  384.64  4647.7  380.64  4697.7  376.56
  4767.8  374.27  5015.1  372.62  5017.9  372.12  5021.1  372.62  5023.1  372.63
  5121.5  373.63  5180.3  374.78  5196.0  374.21  5243.2  377.55  5316.6  381.32
  5445.4  381.98  5509.8  380.98  5559.7  382.76  5738.5  395.44  5759.3  398.21
  5788.4  399.19  5809.2  402.03  5838.3  403.76  5844.6  405.57  5855.7  405.65
#Mann=8,-1,0
  4103.6    0.05       0  4351.2    0.12       0  5015.1    0.07       0
  5021.1    0.12       0  5023.1    0.16       0  5121.5    0.05       0
  5180.3    0.12       0  5243.2    0.05       0
Bank Sta=5015.1,5021.1
Exp/Cntr=0.3,0.1

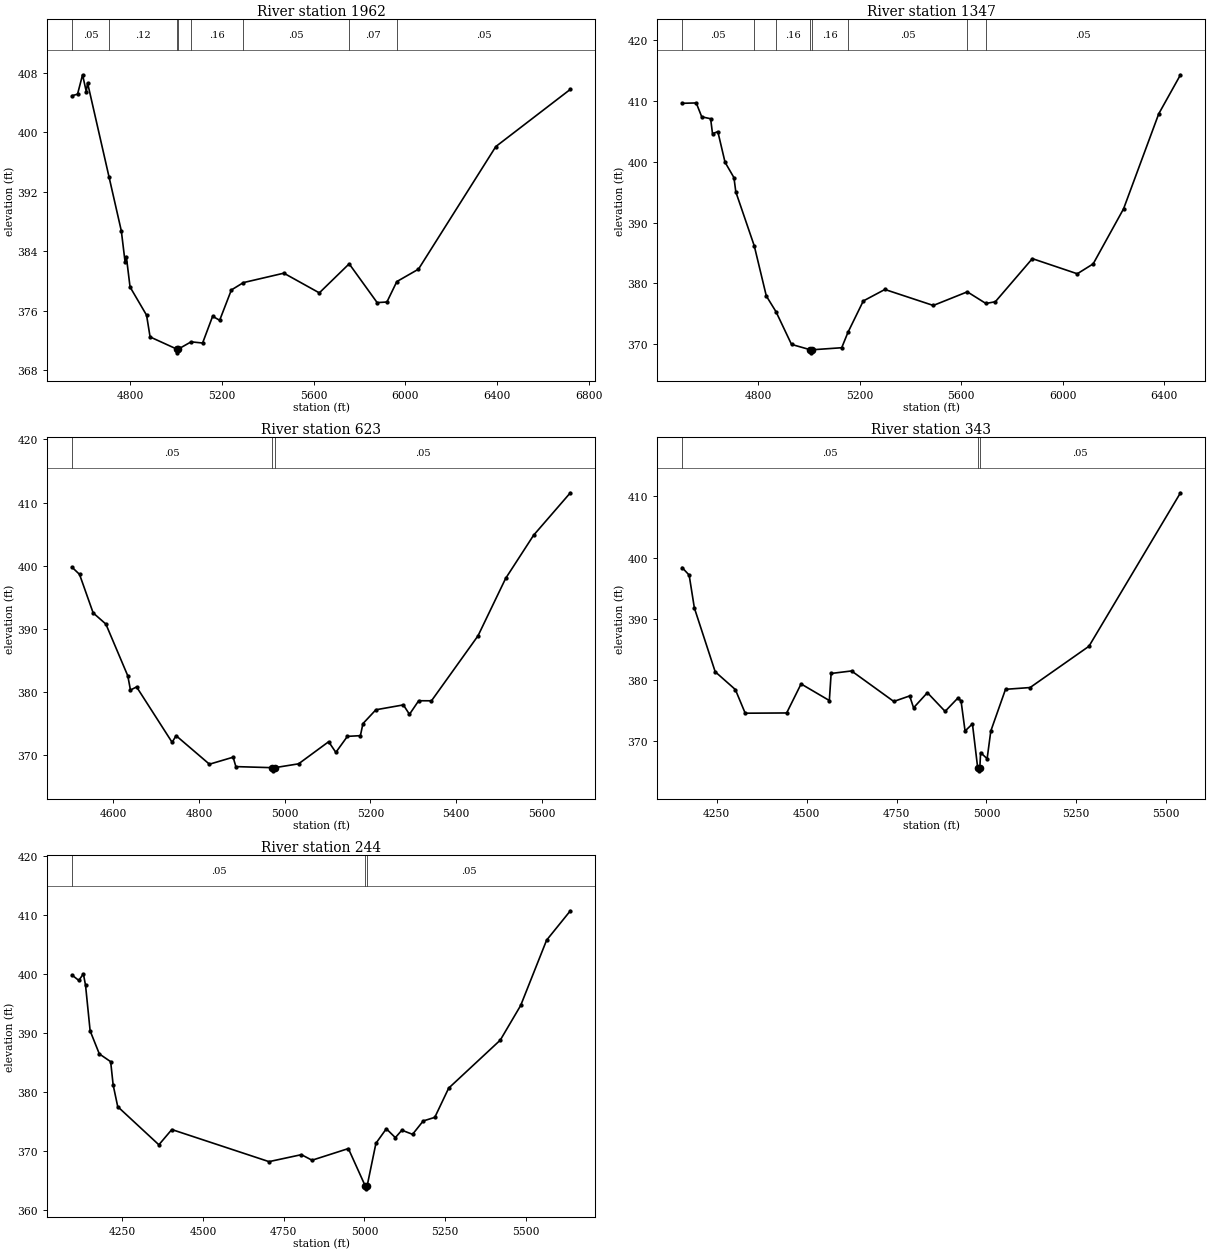
Type RM Length L Ch R = 1,1962,615,615,615
BEGIN DESCRIPTION:
UNT 087 IN CACR 3.0
END DESCRIPTION:
XS GIS Cut Line= 3
      3722612.56     10720804.10      3723109.06     10721717.25
      3723737.51     10722661.66
#Sta/Elev= 30
  4545.5  404.91  4570.1  405.12  4592.0  407.73  4608.1  405.47  4613.8  406.64
  4707.0  394.04  4761.1  386.71  4777.2  382.59  4782.9  383.26  4799.1  379.17
  4871.1  375.38  4886.5  372.45  5003.2  370.81  5006.0  370.31  5009.2  370.81
  5065.4  371.79  5115.5  371.63  5159.2  375.23  5189.9  374.69  5240.9  378.77
  5293.2  379.76  5469.8  381.03  5624.5  378.38  5754.7  382.29  5876.7  377.07
  5919.3  377.15  5962.5  379.90  6056.9  381.57  6394.2  398.07  6719.3  405.77
#Mann=8,-1,0
  4545.5    0.05       0  4707.0    0.12       0  5003.2    0.07       0
  5009.2    0.12       0  5065.4    0.16       0  5293.2    0.05       0
  5754.7    0.07       0  5962.5    0.05       0
Bank Sta=5003.2,5009.2
Exp/Cntr=0.3,0.1

Type RM Length L Ch R = 1,1347,724,724,724
BEGIN DESCRIPTION:
UNT 087 IN CACR 2.0
END DESCRIPTION:
XS GIS Cut Line= 3
      3722220.19     10721290.19      3722987.53     10721995.03
      3723247.94     10722880.40
#Sta/Elev= 30
  4500.0  409.60  4556.0  409.66  4577.6  407.38  4612.7  407.06  4620.1  404.61
  4641.1  404.94  4669.5  399.91  4704.6  397.38  4712.0  395.03  4784.7  386.16
  4832.2  377.92  4870.3  375.34  4931.5  369.96  5006.2  369.07  5008.9  368.57
  5012.2  369.07  5129.4  369.41  5153.8  371.92  5214.5  377.10  5299.6  378.99
  5490.4  376.36  5624.5  378.60  5697.6  376.69  5734.9  376.97  5880.8  384.06
  6058.0  381.57  6120.6  383.20  6240.4  392.25  6379.1  407.88  6464.8  414.29
#Mann=8,-1,0
  4500.0    0.05       0  4784.7    0.12       0  4870.3    0.16       0
  5006.2    0.07       0  5012.2    0.16       0  5153.8    0.05       0
  5624.5    0.07       0  5697.6    0.05       0
Bank Sta=5006.2,5012.2
Exp/Cntr=0.3,0.1

Type RM Length L Ch R = 1,623,280,280,280
BEGIN DESCRIPTION:
Mapping XS 62d3a2ee
END DESCRIPTION:
XS GIS Cut Line= 4
      3722194.50     10721612.78      3722111.17     10721987.80
      3722177.14     10722199.60      3722481.68     10722666.80
#Sta/Elev= 30
  4503.0  399.79  4520.8  398.64  4552.6  392.54  4582.3  390.77  4633.5  382.57
  4639.7  380.32  4654.0  380.82  4737.0  372.04  4746.2  373.10  4824.1  368.58
  4879.4  369.69  4885.8  368.20  4970.5  368.03  4973.2  367.53  4976.5  368.03
  5032.2  368.64  5102.4  372.14  5119.2  370.45  5146.2  372.99  5176.5  373.10
  5182.5  375.01  5212.7  377.20  5276.8  377.97  5291.1  376.48  5312.6  378.63
  5342.5  378.62  5451.1  388.91  5515.6  398.00  5580.9  404.84  5666.7  411.56
#Mann=3,-1,0
  4503.0    0.05       0  4970.5    0.03       0  4976.5    0.05       0
Bank Sta=4970.5,4976.5
Exp/Cntr=0.3,0.1

Type RM Length L Ch R = 1,343,99,99,99
BEGIN DESCRIPTION:
Mapping XS 77543d9b
END DESCRIPTION:
XS GIS Cut Line= 5
      3722104.25     10721536.38      3721996.58     10721675.30
      3722024.36     10722039.88      3722121.58     10722491.27
      3722441.01     10722703.07
#Sta/Elev= 30
  4153.4  398.39  4173.2  397.15  4187.7  391.78  4245.6  381.37  4301.7  378.46
  4329.1  374.60  4444.4  374.64  4484.5  379.38  4563.1  376.67  4568.1  381.09
  4624.9  381.50  4742.3  376.52  4786.5  377.42  4797.4  375.48  4835.8  377.95
  4885.1  374.90  4920.2  377.05  4929.4  376.63  4940.6  371.69  4961.1  372.86
  4975.7  365.69  4978.4  365.19  4981.7  365.69  4983.8  368.17  5002.0  367.17
  5012.2  371.69  5053.1  378.50  5121.5  378.79  5285.2  385.53  5539.8  410.59
#Mann=3,-1,0
  4153.4    0.05       0  4975.7    0.03       0  4981.7    0.05       0
Bank Sta=4975.7,4981.7
Exp/Cntr=0.3,0.1

Type RM Length L Ch R = 1,244,0,0,0
BEGIN DESCRIPTION:
UNT 087 IN CACR 1.0
END DESCRIPTION:
XS GIS Cut Line= 4
      3722069.49     10721460.04      3721937.56     10721612.80
      3722011.94     10722463.29      3722421.18     10722730.98
#Sta/Elev= 30
  4093.5  399.80  4114.9  398.88  4129.1  399.99  4135.8  398.04  4150.0  390.35
  4178.5  386.45  4213.6  385.14  4221.3  381.21  4235.5  377.53  4363.0  371.08
  4403.1  373.66  4704.3  368.23  4804.7  369.41  4837.6  368.47  4950.2  370.44
  5002.4  364.13  5005.2  363.63  5008.4  364.13  5035.6  371.33  5067.8  373.79
  5095.8  372.29  5115.9  373.55  5149.1  372.85  5182.1  375.11  5218.0  375.72
  5261.0  380.66  5420.9  388.78  5484.1  394.64  5564.5  405.69  5638.1  410.66
#Mann=3,-1,0
  4093.5    0.05       0  5002.4    0.03       0  5008.4    0.05       0
Bank Sta=5002.4,5008.4
Exp/Cntr=0.3,0.1

Chan Stop Cuts=-1