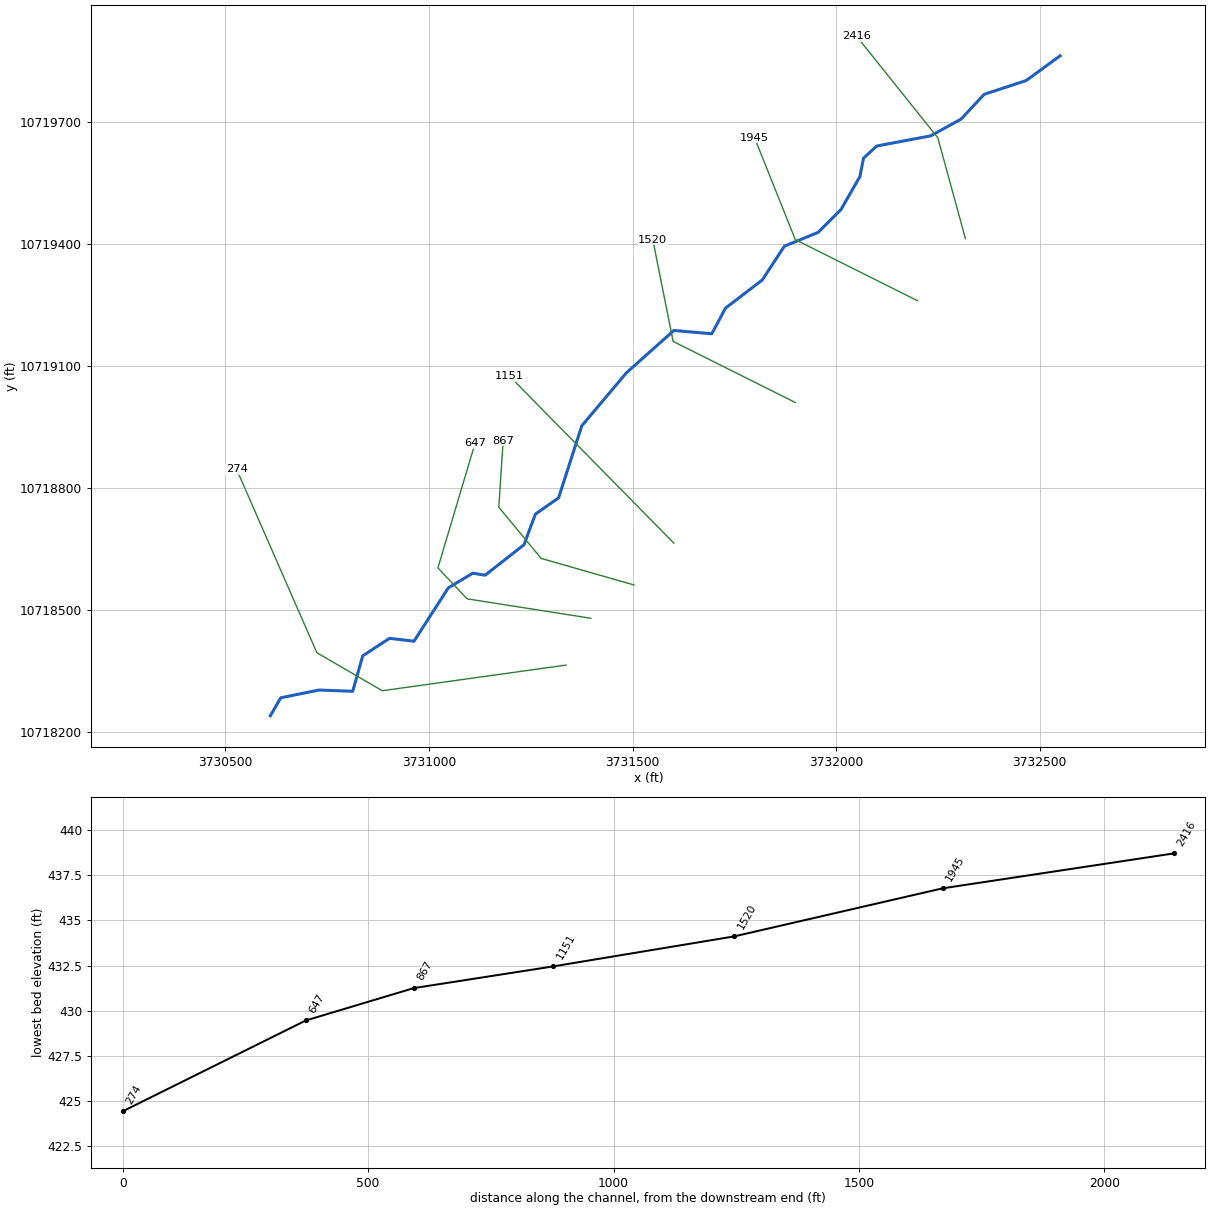
--- UNT 088 IN CACR.prj (project) ---

Proj Title=UNT 088 IN CACR Base Level Engineering
Current Plan=p01
Default Exp/Contr=0.3,0.1
English Units
Geom File=g01
Flow File=f01
Plan File=p01
Y Axis Title=Elevation
X Axis Title(PF)=Main Channel Distance
X Axis Title(XS)=Station
BEGIN DESCRIPTION:
UNT 088 IN CACR
END DESCRIPTION:
DSS Export Rating Curves= 0
DSS Export Rating Curve Sorted= 0
DSS Export Volume Flow Curves= 0
DXF OffsetX= 0
DXF OffsetY= 0
DXF ScaleX= 1
DXF ScaleY= 10

--- UNT 088 IN CACR.p01 (plan) ---

Plan Title=Multiple Run
Short Identifier=Multiple
Geom File=g01
Flow File=f01
Subcritical Flow
K Sum by GR= 0
Std Step Tol= 0.01
Critical Tol= 0.01
Num of Std Step Trials= 20
Max Error Tol= 0.3
Flow Tol Ratio= 0.001
Split Flow NTrial= 30
Split Flow Tol= 0.02
Split Flow Ratio= 0.02
Log Output Level= 0
Friction Slope Method= 1
Unsteady Friction Slope Method= 2
Unsteady Bridges Friction Slope Method= 1
Parabolic Critical Depth
Global Vel Dist=  1 , 1 , 1
Global Log Level= 0
CheckData=True
Encroach Param= -1, 0, 0, 0
BEGIN DESCRIPTION:
Multiple Run
END DESCRIPTION:

--- UNT 088 IN CACR.f01 (steady flow) ---

Flow Title=Multiple
Number of Profiles=7
Profile Names=10-year,25-year,50-year,1pct_min,100-year,1pct_plu,500-year
River Rch & RM= UNT 088 IN CACR,Reach-1,2416
     181     229     267     229     310     419     418
Boundary for River Rch & Prof#=UNT 088 IN CACR,Reach-1,1
Up Type=0
Dn Type=3
Dn Slope=0.005
Boundary for River Rch & Prof#=UNT 088 IN CACR,Reach-1,2
Up Type=0
Dn Type=3
Dn Slope=0.005
Boundary for River Rch & Prof#=UNT 088 IN CACR,Reach-1,3
Up Type=0
Dn Type=3
Dn Slope=0.005
Boundary for River Rch & Prof#=UNT 088 IN CACR,Reach-1,4
Up Type=0
Dn Type=3
Dn Slope=0.005
Boundary for River Rch & Prof#=UNT 088 IN CACR,Reach-1,5
Up Type=0
Dn Type=3
Dn Slope=0.005
Boundary for River Rch & Prof#=UNT 088 IN CACR,Reach-1,6
Up Type=0
Dn Type=3
Dn Slope=0.005
Boundary for River Rch & Prof#=UNT 088 IN CACR,Reach-1,7
Up Type=0
Dn Type=3
Dn Slope=0.005

--- UNT 088 IN CACR.g01 (geometry) ---

Geom Title=Existing Conditions
Program Version=4.10

River Reach=UNT 088 IN CACR ,Reach-1
Reach XY= 30
      3732549.87     10719861.55      3732466.54     10719800.79
       3732363.5       10719767.       3732306.5       10719706.
        3732232.       10719665.       3732099.5       10719640.
        3732067.       10719610.      3732058.25       10719565.
      3732011.75       10719484.      3731955.75       10719428.
      3731872.75       10719394.       3731818.5       10719311.
      3731728.25       10719242.       3731694.5       10719179.
      3731601.25       10719187.      3731484.75       10719083.
      3731375.25       10718953.      3731318.25       10718776.
      3731261.25       10718736.       3731233.5       10718661.
      3731137.75       10718586.       3731107.5       10718591.
       3731047.5       10718555.      3730963.25       10718424.
        3730903.       10718431.      3730837.25       10718388.
      3730812.75       10718301.      3730729.75       10718304.
        3730636.       10718285.       3730610.5       10718241.

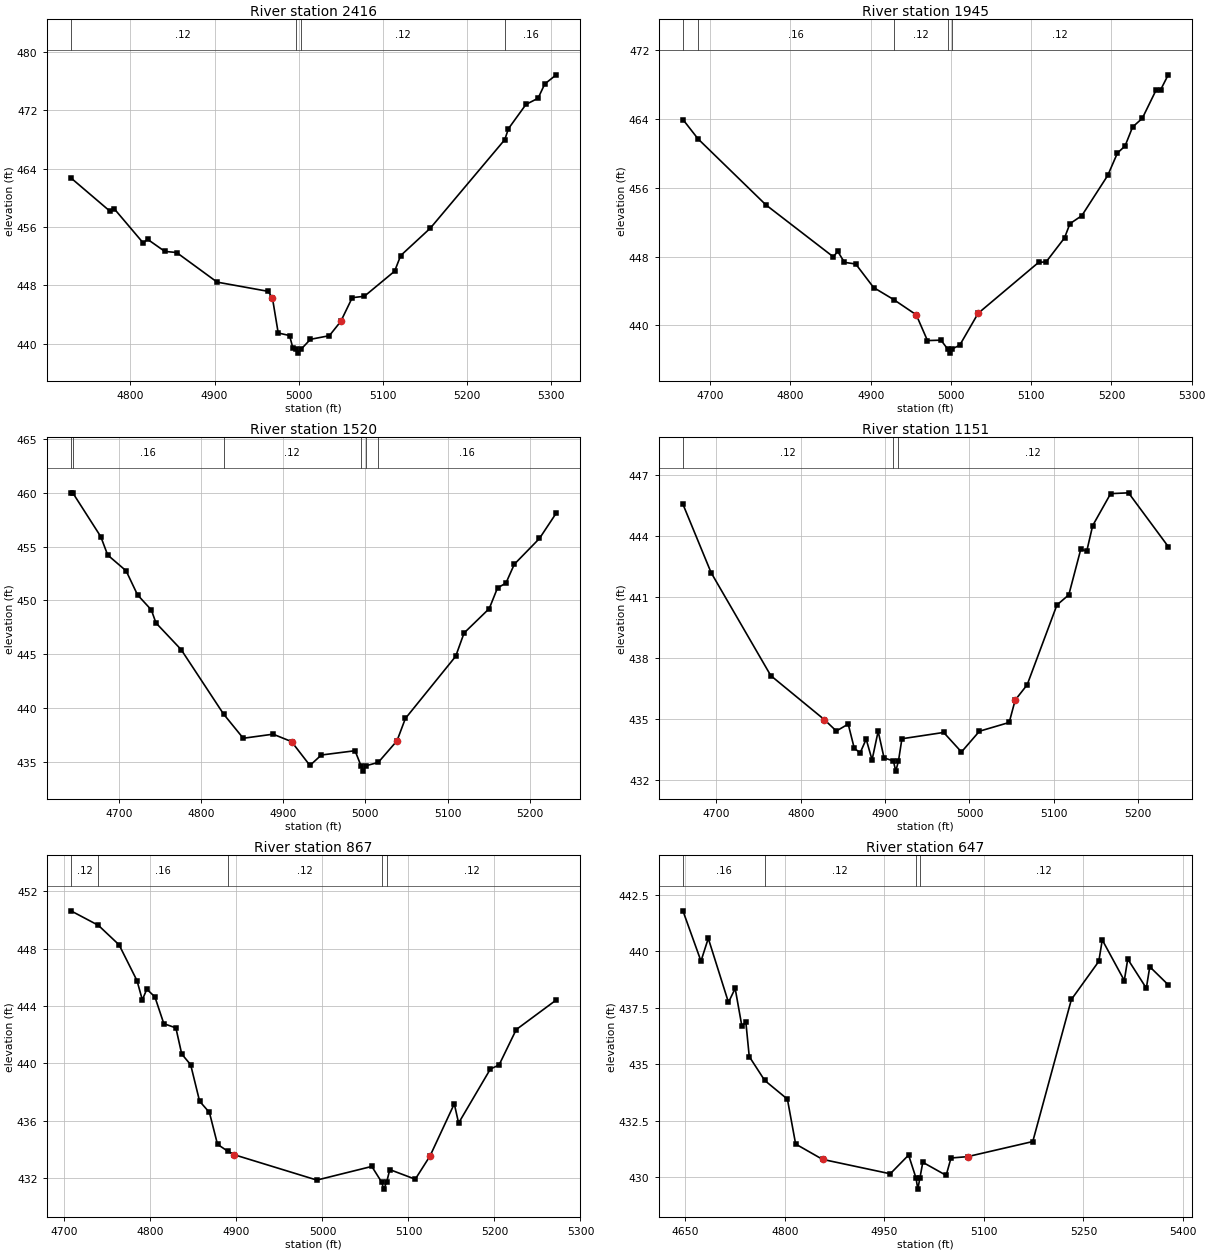
Type RM Length L Ch R = 1 ,2416    ,471,471,471
BEGIN DESCRIPTION:
UNT 088 IN CACR 5.0
END DESCRIPTION:
XS GIS Cut Line= 3
      3732317.37     10719412.56      3732249.61     10719660.19
       3732049.6      10719910.2
#Sta/Elev= 30
  4729.2  462.71  4775.5  458.16  4780.7  458.48  4815.1   453.8  4820.3   454.3
  4840.8  452.64  4854.8  452.49    4903  448.43  4963.5  447.17  4968.7  446.28
  4975.6  441.46  4989.1  441.11  4993.1  439.37  4996.5   439.2  4999.3   438.7
  5002.5   439.2  5013.9  440.59  5036.4  441.09    5050  443.05  5063.6   446.3
    5078  446.49    5114  449.93  5121.2  452.07  5156.4  455.82  5244.9  467.95
  5249.3  469.46  5270.1  472.78  5284.5  473.63  5292.5  475.59  5306.1  476.84
#Mann= 4 ,-1 , 0
  4729.2     .12       0  4996.5     .07       0  5002.5     .12       0
  5244.9     .16       0
Bank Sta=4968.7,5050
XS Rating Curve= 0 ,0
Exp/Cntr=0.3,0.1

Type RM Length L Ch R = 1 ,1945    ,425,425,425
BEGIN DESCRIPTION:
UNT 088 IN CACR 4.0
END DESCRIPTION:
XS GIS Cut Line= 3
      3732199.65     10719260.17      3731899.61     10719410.19
      3731799.61     10719660.17
#Sta/Elev= 30
  4666.1  463.95    4685  461.69  4769.6  454.01  4853.4  447.98    4859   448.6
  4867.4  447.33  4881.4  447.14  4903.7   444.4  4928.9  442.99  4956.8  441.23
  4970.8  438.23  4987.6  438.28  4995.8  437.27  4998.5  436.77  5001.8  437.27
    5011  437.69  5033.9   441.4  5109.3  447.33  5118.7  447.39  5141.6  450.18
  5148.3  451.83  5163.1  452.76  5195.4  457.44  5207.5  460.05    5217  460.87
  5226.4  463.08  5238.5  464.09    5256  467.44  5261.4  467.42  5270.8  469.15
#Mann= 5 ,-1 , 0
  4666.1     .12       0    4685     .16       0  4928.9     .12       0
  4995.8     .07       0  5001.8     .12       0
Bank Sta=4956.8,5033.9
XS Rating Curve= 0 ,0
Exp/Cntr=0.3,0.1

Type RM Length L Ch R = 1 ,1520    ,369,369,369
BEGIN DESCRIPTION:
UNT 088 IN CACR 3.0
END DESCRIPTION:
XS GIS Cut Line= 3
      3731899.59      10719010.2      3731599.61     10719160.19
      3731549.62     10719410.15
#Sta/Elev= 30
  4641.9  460.02  4644.1  460.02  4678.2  455.94  4686.6  454.23    4709  452.76
  4722.9  450.52  4739.7  449.12  4745.3  447.91    4776  445.42  4827.5  439.43
  4851.5  437.17  4887.8  437.55  4910.2  436.86  4932.6  434.64  4946.5  435.61
  4987.5  436.01  4994.7  434.61  4997.4  434.11  5000.7  434.61  5015.7  434.92
  5038.5  436.93  5048.7  439.01  5109.9   444.8  5120.1  446.97  5150.7  449.24
  5160.8  451.17    5171  451.61  5181.2  453.37  5211.8  455.77  5232.2  458.13
#Mann= 6 ,-1 , 0
  4641.9     .12       0  4644.1     .16       0  4827.5     .12       0
  4994.7     .07       0  5000.7     .12       0  5015.7     .16       0
Bank Sta=4910.2,5038.5
XS Rating Curve= 0 ,0
Exp/Cntr=0.3,0.1

Type RM Length L Ch R = 1 ,1151    ,284,284,284
BEGIN DESCRIPTION:
UNT 088 IN CACR 2.0
END DESCRIPTION:
XS GIS Cut Line= 2
       3731601.4     10718664.74      3731197.73     10719074.92
#Sta/Elev= 30
  4660.2  445.56  4693.6   442.2  4764.4  437.14  4827.9  434.98  4842.1  434.42
  4856.2  434.76  4863.4  433.57  4870.4  433.35  4877.5  434.02  4884.5     433
  4891.7  434.41  4898.7   433.1  4909.8  432.95  4912.6  432.45  4915.8  432.95
  4919.9  434.04  4969.4  434.35  4990.5  433.39  5011.8  434.41  5047.1  434.84
  5054.2  435.94  5068.4  436.69  5103.7  440.61  5117.8  441.11    5132  443.35
  5139.1  443.26  5146.1  444.51  5167.4  446.08  5188.6  446.12  5235.7  443.48
#Mann= 3 ,-1 , 0
  4660.2     .12       0  4909.8     .07       0  4915.8     .12       0
Bank Sta=4827.9,5054.2
XS Rating Curve= 0 ,0
Exp/Cntr=0.3,0.1

Type RM Length L Ch R = 1 ,867     ,220,220,220
BEGIN DESCRIPTION:
Mapping XS fe38a8fc
END DESCRIPTION:
XS GIS Cut Line= 4
      3731503.44     10718562.08       3731275.6     10718627.18
      3731171.43     10718753.05      3731182.19     10718916.55
#Sta/Elev= 30
  4707.6  450.63  4739.5  449.62  4763.6  448.26  4784.4  445.77  4790.6  444.43
  4795.8  445.17  4805.2  444.64  4815.6  442.77  4829.6  442.48  4836.4  440.66
  4846.8  439.91  4857.2  437.37  4868.6  436.59    4878  434.37  4890.2  433.88
  4897.2  433.65  4993.5  431.88  5057.4  432.83  5068.7  431.75  5071.4  431.25
  5074.7  431.75  5078.3  432.61  5107.9  431.94  5125.1  433.56  5153.3  437.19
  5158.3  435.85  5195.3  439.62  5205.3  439.89  5225.3  442.36  5271.8  444.42
#Mann= 5 ,-1 , 0
  4707.6     .12       0  4739.5     .16       0  4890.2     .12       0
  5068.7     .07       0  5074.7     .12       0
Bank Sta=4897.2,5125.1
XS Rating Curve= 0 ,0
Exp/Cntr=0.3,0.1

Type RM Length L Ch R = 1 ,647     ,373,373,373
BEGIN DESCRIPTION:
Mapping XS ec5c43dd
END DESCRIPTION:
XS GIS Cut Line= 4
      3731397.35     10718480.31      3731093.56     10718528.05
      3731021.94     10718604.01      3731113.09     10718910.01
#Sta/Elev= 30
  4646.6   441.8  4673.8  439.57  4684.8  440.58  4715.2  437.74  4725.3  438.36
  4735.4  436.69  4741.4  436.87  4746.5  435.34  4769.8  434.28    4804  433.45
  4816.4  431.46  4856.9  430.78    4959  430.14  4986.6  430.97  4997.7  429.96
  5000.5  429.46  5003.7  429.96    5008  430.65  5043.2  430.07  5050.5  430.84
  5075.4   430.9  5173.7  431.57  5231.9  437.87  5273.2  439.56  5278.4  440.51
  5311.6  438.71  5316.8  439.66  5344.8  438.37    5350  439.32  5377.8  438.52
#Mann= 4 ,-1 , 0
  4646.6     .16       0  4769.8     .12       0  4997.7     .07       0
  5003.7     .12       0
Bank Sta=4856.9,5075.4
XS Rating Curve= 0 ,0
Exp/Cntr=0.3,0.1

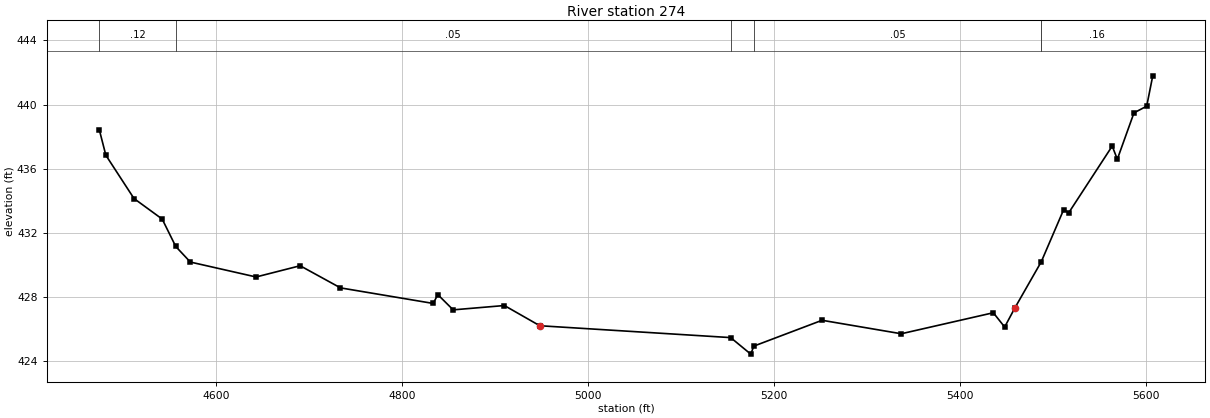
Type RM Length L Ch R = 1 ,274     ,0,0,0
BEGIN DESCRIPTION:
UNT 088 IN CACR 1.0
END DESCRIPTION:
XS GIS Cut Line= 4
      3731336.57     10718365.29      3730885.22     10718302.36
      3730724.63     10718395.67      3730527.57     10718846.11
#Sta/Elev= 30
  4474.6  438.42  4481.6  436.84  4511.9  434.14  4542.2  432.86  4556.8  431.15
  4572.5  430.18  4643.2  429.25  4690.6  429.95    4734  428.57  4833.7   427.6
  4838.7  428.15  4855.2   427.2  4910.3  427.47  4948.4  426.21  5153.7  425.47
  5175.3  424.44  5178.6  424.94    5252  426.55  5337.2  425.71  5436.2  427.02
  5448.4  426.13  5459.3  427.31  5487.8   430.2  5511.9  433.45  5517.3  433.25
  5564.1  437.41  5569.6  436.59  5587.5  439.48  5601.2   439.9  5607.7  441.79
#Mann= 6 ,-1 , 0
  4474.6     .12       0  4556.8     .05       0  5153.7     .03       0
  5178.6     .05       0  5487.8     .09       0  5487.8     .16       0
Bank Sta=4948.4,5459.3
XS Rating Curve= 0 ,0
Exp/Cntr=0.3,0.1

Chan Stop Cuts=-1
Use User Specified Reach Order=0
Composite Channel Slope=5