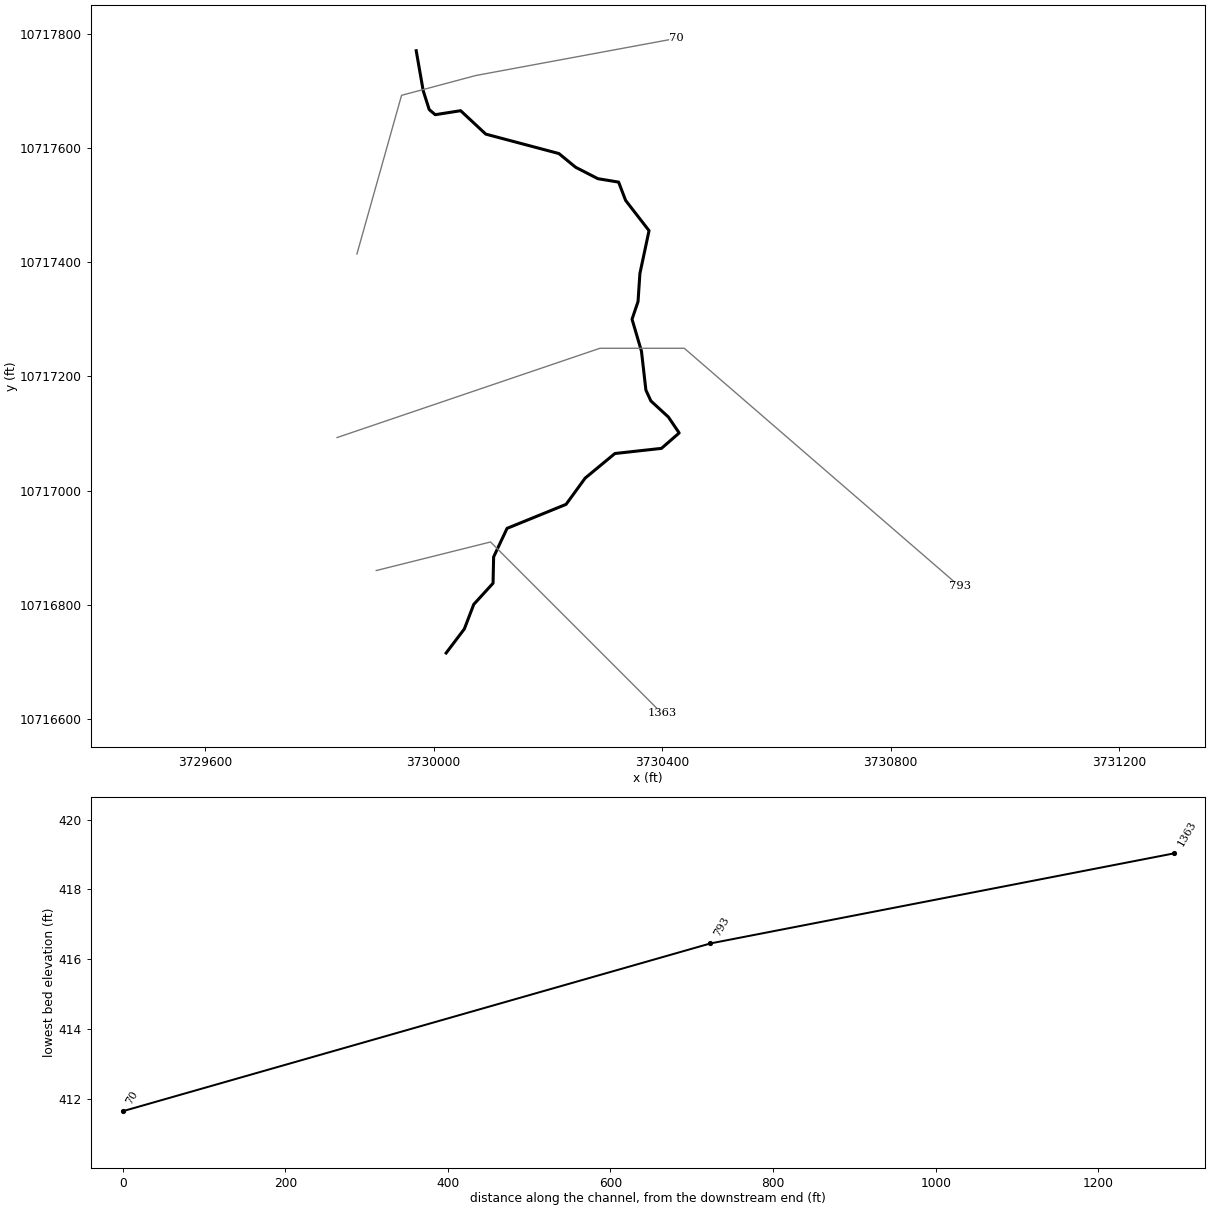
--- UNT 089 IN CACR.prj (project) ---

Proj Title=UNT 089 IN CACR Base Level Engineering
Current Plan=p01
Default Exp/Contr=0.3,0.1
English Units
Geom File=g01
Flow File=f01
Plan File=p01
Y Axis Title=Elevation
X Axis Title(PF)=Main Channel Distance
X Axis Title(XS)=Station
BEGIN DESCRIPTION:
UNT 089 IN CACR
END DESCRIPTION:
DSS Export Rating Curves= 0
DSS Export Rating Curve Sorted= 0
DSS Export Volume Flow Curves= 0
DXF OffsetX= 0
DXF OffsetY= 0
DXF ScaleX= 1
DXF ScaleY= 10

--- UNT 089 IN CACR.p01 (plan) ---

Plan Title=Multiple Run
Short Identifier=Multiple
Geom File=g01
Flow File=f01
Subcritical Flow
K Sum by GR= 0
Std Step Tol= 0.01
Critical Tol= 0.01
Num of Std Step Trials= 20
Max Error Tol= 0.3
Flow Tol Ratio= 0.001
Split Flow NTrial= 30
Split Flow Tol= 0.02
Split Flow Ratio= 0.02
Log Output Level= 0
Friction Slope Method= 1
Unsteady Friction Slope Method= 2
Unsteady Bridges Friction Slope Method= 1
Parabolic Critical Depth
Global Vel Dist=  1 , 1 , 1
Global Log Level= 0
CheckData=True
Encroach Param= -1, 0, 0, 0
BEGIN DESCRIPTION:
Multiple Run
END DESCRIPTION:

--- UNT 089 IN CACR.f01 (steady flow) ---

Flow Title=Multiple
Number of Profiles=7
Profile Names=10-year,25-year,50-year,1pct_min,100-year,1pct_plu,500-year
River Rch & RM= UNT 089 IN CACR,Reach-1,1363
     612     844    1040     943    1276    1725    1928
Boundary for River Rch & Prof#=UNT 089 IN CACR,Reach-1,1
Up Type=0
Dn Type=3
Dn Slope=0.005
Boundary for River Rch & Prof#=UNT 089 IN CACR,Reach-1,2
Up Type=0
Dn Type=3
Dn Slope=0.005
Boundary for River Rch & Prof#=UNT 089 IN CACR,Reach-1,3
Up Type=0
Dn Type=3
Dn Slope=0.005
Boundary for River Rch & Prof#=UNT 089 IN CACR,Reach-1,4
Up Type=0
Dn Type=3
Dn Slope=0.005
Boundary for River Rch & Prof#=UNT 089 IN CACR,Reach-1,5
Up Type=0
Dn Type=3
Dn Slope=0.005
Boundary for River Rch & Prof#=UNT 089 IN CACR,Reach-1,6
Up Type=0
Dn Type=3
Dn Slope=0.005
Boundary for River Rch & Prof#=UNT 089 IN CACR,Reach-1,7
Up Type=0
Dn Type=3
Dn Slope=0.005

--- UNT 089 IN CACR.g01 (geometry) ---

Geom Title=Existing Conditions
Program Version=4.10

River Reach=UNT 089 IN CACR ,Reach-1
Reach XY= 30
      3730021.92      10716715.9      3730053.75       10716758.
      3730070.25       10716801.        3730104.       10716838.
        3730105.       10716884.       3730128.5       10716934.
      3730231.75       10716976.      3730265.25       10717022.
      3730317.25       10717065.      3730398.75       10717074.
      3730429.75       10717101.      3730410.75       10717129.
      3730380.25       10717157.       3730371.5       10717176.
      3730363.75       10717244.      3730347.25       10717300.
      3730357.75       10717331.        3730361.       10717380.
        3730377.       10717455.        3730336.       10717508.
      3730323.75       10717540.       3730287.5       10717546.
       3730248.5       10717566.      3730219.25       10717590.
      3730091.25       10717624.      3730047.25       10717665.
      3730002.75       10717658.      3729992.25       10717667.
      3729981.75       10717700.       3729969.5       10717770.

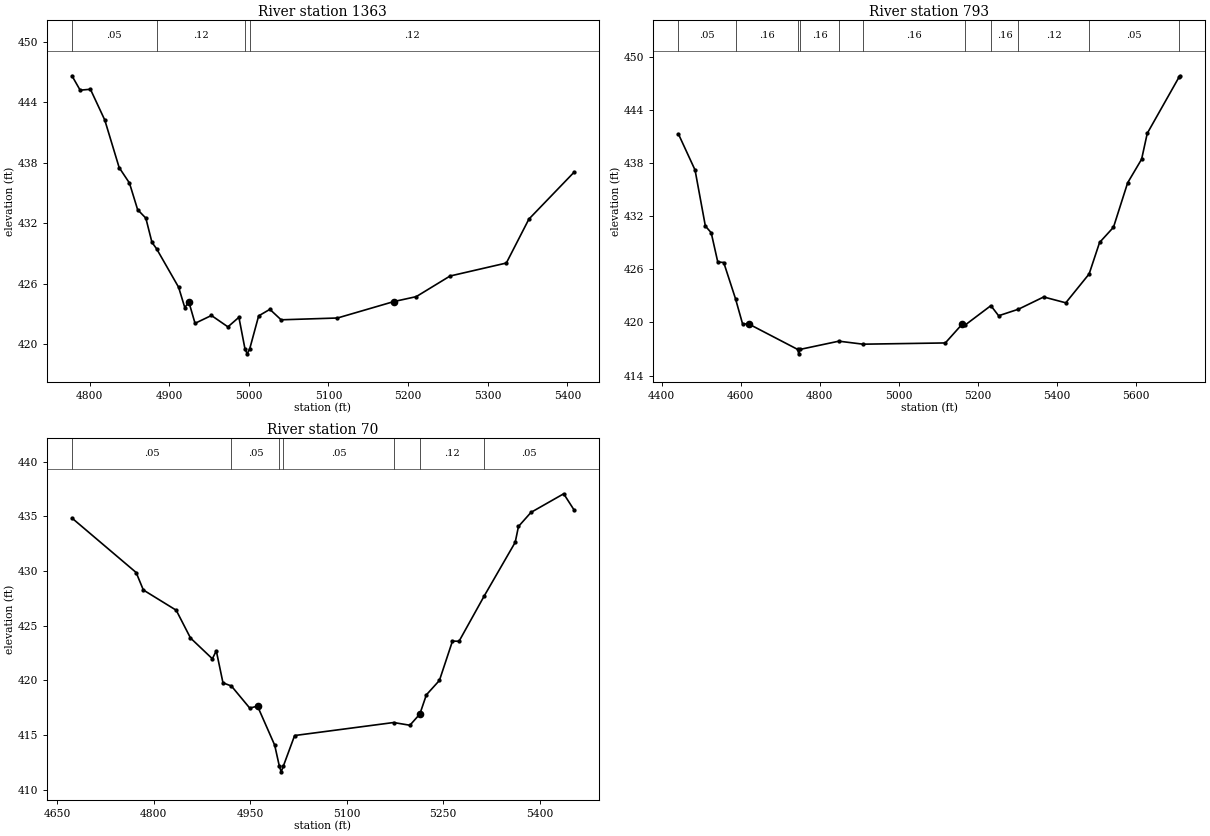
Type RM Length L Ch R = 1 ,1363    ,570,570,570
BEGIN DESCRIPTION:
UNT 089 IN CACR 3.0
END DESCRIPTION:
XS GIS Cut Line= 3
      3729899.59     10716860.18      3730099.61     10716910.19
      3730399.58     10716610.21
#Sta/Elev= 30
  4777.8  446.65  4788.1  445.22    4801  445.31    4819  442.26  4837.1  437.53
    4850     436  4860.3  433.35  4870.6  432.51  4878.3   430.1    4884  429.48
  4911.8  425.64  4919.5  423.63  4924.7  424.17  4932.4  422.06    4953  422.84
  4973.7  421.71  4987.5  422.66  4995.1  419.53  4997.9  419.03  5001.1  419.53
  5012.3   422.8  5026.4  423.45  5040.5  422.41  5111.3  422.59    5182  424.22
  5210.2  424.71  5252.7  426.76  5323.4  428.05  5351.7  432.41  5408.2  437.05
#Mann= 4 ,-1 , 0
  4777.8     .05       0    4884     .12       0  4995.1     .07       0
  5001.1     .12       0
Bank Sta=4924.7,5182
XS Rating Curve= 0 ,0
Exp/Cntr=0.3,0.1

Type RM Length L Ch R = 1 ,793     ,723,723,723
BEGIN DESCRIPTION:
UNT 089 IN CACR 2.0
END DESCRIPTION:
XS GIS Cut Line= 4
      3729830.99     10717092.94       3730291.1      10717249.2
      3730438.67      10717249.2       3730920.4     10716832.57
#Sta/Elev= 30
  4442.6  441.27  4484.7   437.2  4510.8  430.88  4525.6  430.12  4542.2  426.82
  4557.3  426.76  4587.1  422.67    4605  419.83  4620.7  419.82  4744.4  416.95
  4747.2  416.45  4750.4  416.95  4848.7  417.88  4909.7  417.54  5118.2  417.68
    5161  419.81    5168  419.69  5233.5  421.89  5253.1  420.75  5303.4  421.49
  5367.1  422.87  5423.1  422.21  5482.2  425.47  5508.6  429.02  5543.8  430.74
  5579.7  435.76    5615  438.42  5629.3  441.34  5709.5  447.67    5713  447.84
#Mann= 11 ,-1 , 0
  4442.6     .05       0  4587.1     .16       0  4744.4     .07       0
  4750.4     .16       0  4848.7     .05       0  4909.7     .16       0
    5168     .12       0  5233.5     .16       0  5303.4     .12       0
  5482.2     .05       0  5709.5     .16       0
Bank Sta=4620.7,5161
XS Rating Curve= 0 ,0
Exp/Cntr=0.3,0.1

Type RM Length L Ch R = 1 ,70      ,0,0,0
BEGIN DESCRIPTION:
UNT 089 IN CACR 1.0
END DESCRIPTION:
XS GIS Cut Line= 4
      3729865.75     10717414.15      3729943.87     10717691.91
      3730074.08     10717726.63      3730425.12     10717791.64
#Sta/Elev= 30
  4672.8  434.85  4772.6  429.87  4783.8  428.27  4834.9  426.42  4857.1  423.88
  4891.1  421.98  4897.2  422.71  4907.6  419.78  4920.7  419.49  4949.2  417.47
  4961.3  417.65    4988  414.08  4995.3  412.14  4998.1  411.64  5001.3  412.14
    5019  414.96  5172.9  416.15  5198.2   415.9  5213.6  416.92  5213.8  416.95
  5223.8  418.68  5244.1     420  5264.4   423.6  5274.6  423.58  5313.7  427.72
  5361.9  432.63    5367  434.08  5386.5  435.37  5437.3  437.07  5453.1  435.62
#Mann= 7 ,-1 , 0
  4672.8     .05       0  4920.7     .05       0  4995.3     .03       0
  5001.3     .05       0  5172.9     .16       0  5213.8     .12       0
  5313.7     .05       0
Bank Sta=4961.3,5213.6
XS Rating Curve= 0 ,0
Exp/Cntr=0.3,0.1

Chan Stop Cuts=-1
Use User Specified Reach Order=0
Composite Channel Slope=5