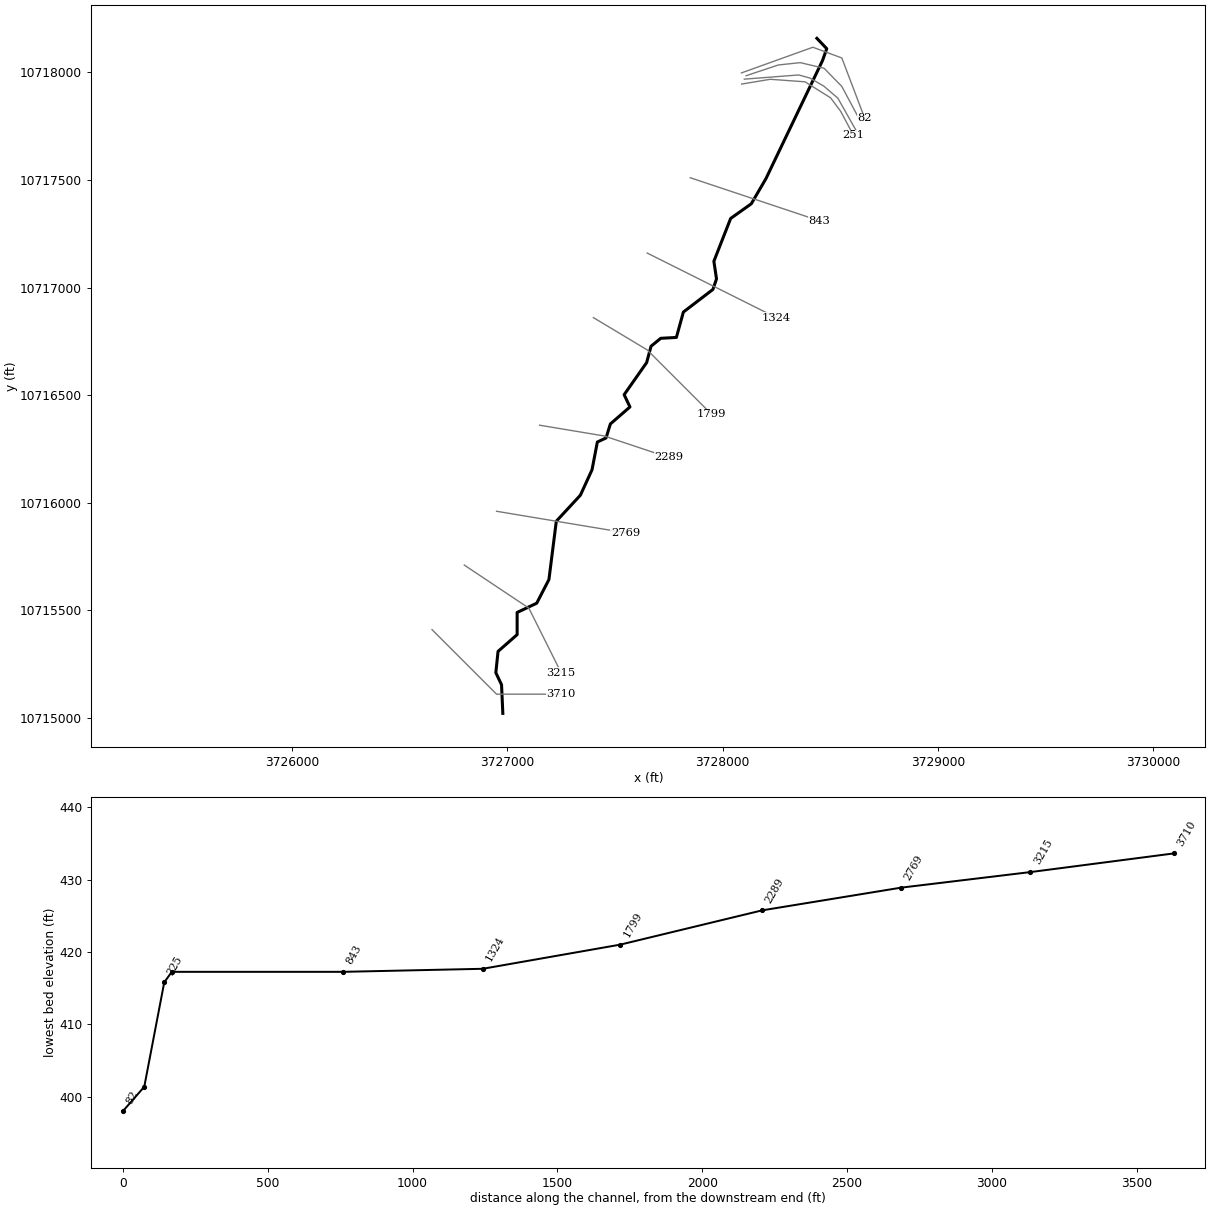
--- UNT 090 IN CACR.prj (project) ---

Proj Title=UNT 090 IN CACR Base Level Engineering
Current Plan=p01
Default Exp/Contr=0.3,0.1
English Units
Geom File=g01
Flow File=f01
Plan File=p01
BEGIN DESCRIPTION:
UNT 090 IN CACR
END DESCRIPTION:

--- UNT 090 IN CACR.p01 (plan) ---

Plan Title=Multiple Run
Short Identifier=Multiple
Geom File=g01
Flow File=f01
Subcritical Flow
K Sum by GR= 0
Std Step Tol= 0.01
Critical Tol= 0.01
Num of Std Step Trials= 20
Max Error Tol= 0.3
Flow Tol Ratio= 0.001
Split Flow NTrial= 30
Split Flow Tol= 0.02
Split Flow Ratio= 0.02
Log Output Level= 0
Friction Slope Method= 1
Unsteady Friction Slope Method= 2
Unsteady Bridges Friction Slope Method= 1
Parabolic Critical Depth
Global Vel Dist=  1 , 1 , 1
Global Log Level= 0
CheckData=True
Encroach Param= -1, 0, 0, 0
BEGIN DESCRIPTION:
Multiple Run
END DESCRIPTION:

--- UNT 090 IN CACR.f01 (steady flow) ---

Flow Title=Multiple
Number of Profiles=7
Profile Names=10-year,25-year,50-year,1pct_min,100-year,1pct_plu,500-year
River Rch & RM= UNT 090 IN CACR,Reach-1,3710
     665     924    1144    1043    1411    1908    2153
Boundary for River Rch & Prof#=UNT 090 IN CACR,Reach-1,1
Up Type=0
Dn Type=3
Dn Slope=0.005
Boundary for River Rch & Prof#=UNT 090 IN CACR,Reach-1,2
Up Type=0
Dn Type=3
Dn Slope=0.005
Boundary for River Rch & Prof#=UNT 090 IN CACR,Reach-1,3
Up Type=0
Dn Type=3
Dn Slope=0.005
Boundary for River Rch & Prof#=UNT 090 IN CACR,Reach-1,4
Up Type=0
Dn Type=3
Dn Slope=0.005
Boundary for River Rch & Prof#=UNT 090 IN CACR,Reach-1,5
Up Type=0
Dn Type=3
Dn Slope=0.005
Boundary for River Rch & Prof#=UNT 090 IN CACR,Reach-1,6
Up Type=0
Dn Type=3
Dn Slope=0.005
Boundary for River Rch & Prof#=UNT 090 IN CACR,Reach-1,7
Up Type=0
Dn Type=3
Dn Slope=0.005

--- UNT 090 IN CACR.g01 (geometry) ---

Geom Title=Existing Conditions

River Reach=UNT 090 IN CACR,Reach-1
Reach XY= 30
      3726978.75     10715021.00      3726972.75     10715154.00
      3726946.25     10715210.00      3726956.50     10715309.00
      3727045.25     10715387.00      3727045.25     10715490.00
      3727136.25     10715533.00      3727193.00     10715643.00
      3727227.25     10715914.00      3727339.25     10716035.00
      3727393.25     10716153.00      3727418.00     10716282.00
      3727458.50     10716301.00      3727478.50     10716366.00
      3727569.50     10716445.00      3727542.50     10716502.00
      3727647.00     10716651.00      3727667.50     10716727.00
      3727712.50     10716764.00      3727785.25     10716768.00
      3727817.75     10716886.00      3727955.00     10716991.00
      3727971.75     10717040.00      3727959.50     10717122.00
      3728037.50     10717321.00      3728133.25     10717389.00
      3728201.50     10717506.00      3728464.50     10718055.00
      3728484.00     10718110.00      3728438.25     10718158.00

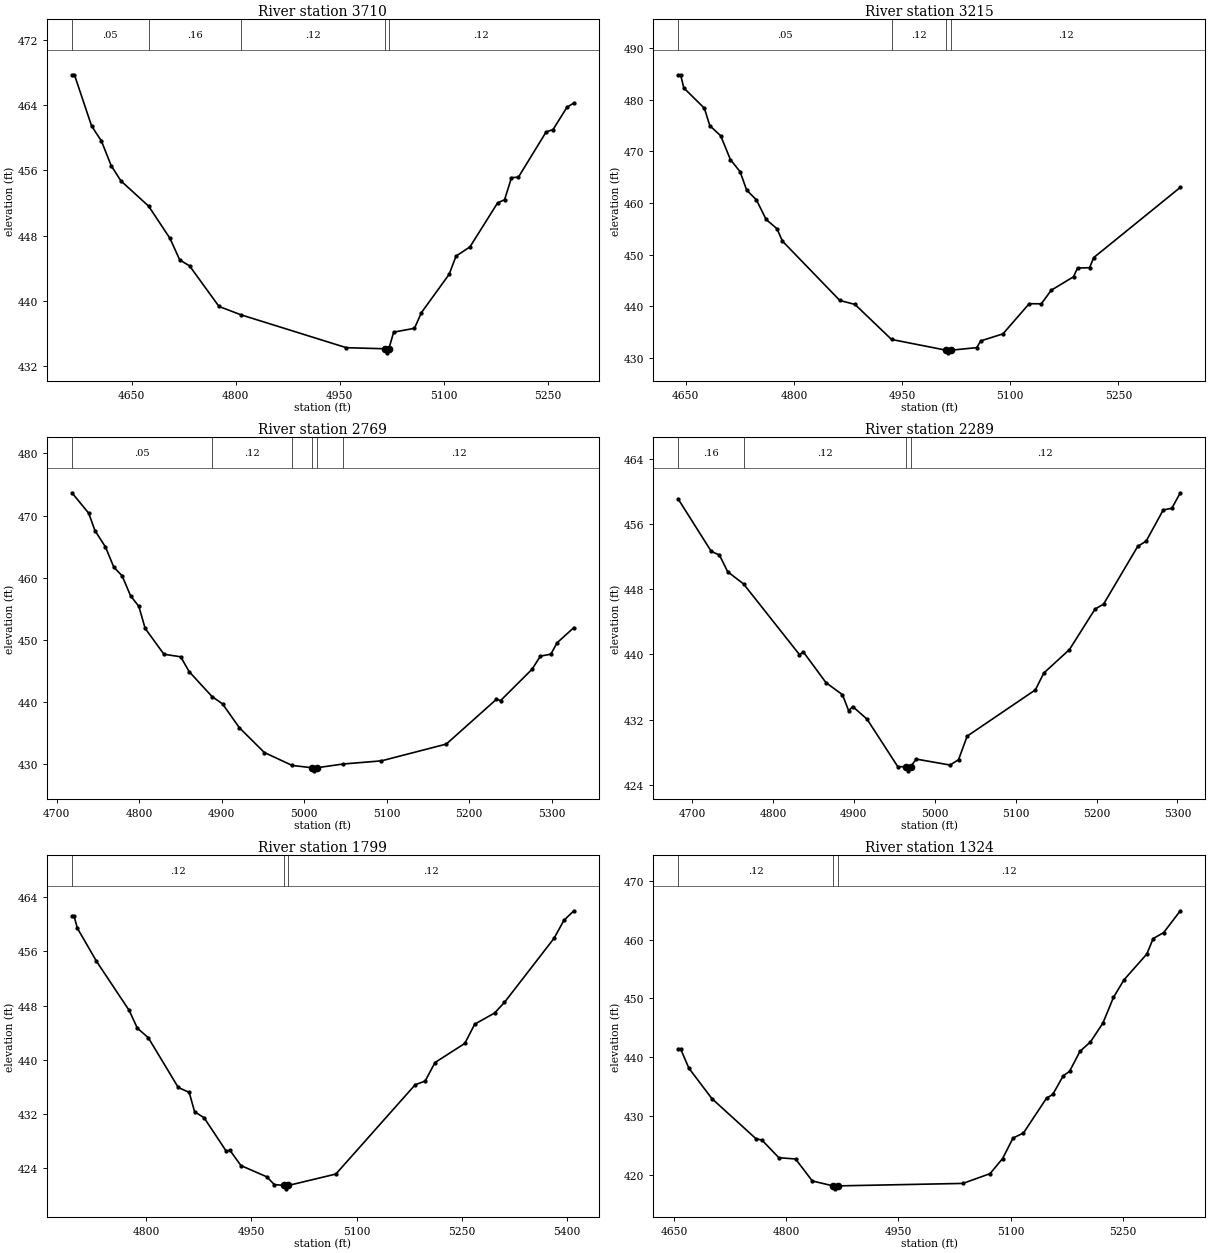
Type RM Length L Ch R = 1,3710,495,495,495
BEGIN DESCRIPTION:
UNT 090 IN CACR 8.0
END DESCRIPTION:
XS GIS Cut Line= 3
      3726649.59     10715410.21      3726949.61     10715110.19
      3727249.62     10715110.19
#Sta/Elev= 30
  4563.7  467.72  4567.3  467.72  4592.0  461.45  4606.2  459.60  4620.3  456.58
  4634.4  454.70  4674.3  451.61  4705.1  447.66  4719.3  445.00  4733.4  444.28
  4775.9  439.30  4807.8  438.27  4959.7  434.24  5015.0  434.11  5017.7  433.61
  5021.0  434.11  5028.0  436.15  5058.0  436.62  5068.0  438.54  5108.0  443.24
  5118.0  445.48  5138.0  446.60  5178.0  452.01  5188.0  452.39  5198.0  455.10
  5208.0  455.16  5248.0  460.71  5258.0  461.00  5278.0  463.73  5288.0  464.26
#Mann=5,-1,0
  4563.7    0.05       0  4674.3    0.16       0  4807.8    0.12       0
  5015.0    0.07       0  5021.0    0.12       0
Bank Sta=5015,5021
Exp/Cntr=0.3,0.1

Type RM Length L Ch R = 1,3215,446,446,446
BEGIN DESCRIPTION:
UNT 090 IN CACR 7.0
END DESCRIPTION:
XS GIS Cut Line= 3
      3726799.64     10715710.17      3727099.61     10715510.19
      3727249.60     10715210.21
#Sta/Elev= 30
  4639.9  484.82  4642.9  484.82  4647.4  482.27  4675.9  478.35  4683.4  474.98
  4698.5  473.02  4712.0  468.42  4725.5  466.05  4734.5  462.51  4748.0  460.63
  4761.5  456.83  4776.6  455.04  4784.1  452.65  4863.7  441.16  4884.7  440.40
  4935.4  433.62  5011.4  431.53  5014.1  431.03  5017.4  431.53  5053.5  432.04
  5059.1  433.34  5089.9  434.70  5126.2  440.53  5143.0  440.51  5156.9  443.15
  5187.7  445.74  5193.3  447.44  5210.0  447.49  5215.6  449.44  5335.8  463.04
#Mann=4,-1,0
  4639.9    0.05       0  4935.4    0.12       0  5011.4    0.07       0
  5017.4    0.12       0
Bank Sta=5011.4,5017.4
Exp/Cntr=0.3,0.1

Type RM Length L Ch R = 1,2769,480,480,480
BEGIN DESCRIPTION:
UNT 090 IN CACR 6.0
END DESCRIPTION:
XS GIS Cut Line= 3
      3726949.58     10715960.19      3727249.61     10715910.19
      3727549.60     10715860.19
#Sta/Elev= 30
  4718.5  473.67  4738.8  470.38  4746.4  467.57  4759.1  464.95  4769.2  461.70
  4779.4  460.27  4789.5  457.09  4799.6  455.36  4807.2  451.83  4830.0  447.66
  4850.3  447.25  4860.5  444.87  4888.4  440.83  4901.0  439.67  4921.3  435.84
  4951.7  431.83  4985.4  429.75  5009.5  429.38  5012.3  428.88  5015.5  429.38
  5047.1  429.98  5093.6  430.49  5172.2  433.19  5233.0  440.41  5238.1  440.21
  5276.1  445.24  5286.3  447.36  5298.9  447.67  5306.5  449.51  5326.8  451.95
#Mann=6,-1,0
  4718.5    0.05       0  4888.4    0.12       0  4985.4    0.16       0
  5009.5    0.07       0  5015.5    0.16       0  5047.1    0.12       0
Bank Sta=5009.5,5015.5
Exp/Cntr=0.3,0.1

Type RM Length L Ch R = 1,2289,490,490,490
BEGIN DESCRIPTION:
UNT 090 IN CACR 5.0
END DESCRIPTION:
XS GIS Cut Line= 3
      3727149.58     10716360.19      3727449.61     10716310.19
      3727749.62     10716210.19
#Sta/Elev= 30
  4683.2  459.01  4723.8  452.64  4733.9  452.19  4744.1  450.14  4763.7  448.65
  4832.8  439.99  4837.8  440.29  4865.7  436.54  4886.0  435.07  4893.6  433.11
  4898.7  433.62  4916.4  432.07  4954.4  426.25  4964.1  426.24  4966.8  425.74
  4970.1  426.24  4977.2  427.18  5019.0  426.45  5029.5  427.11  5040.1  429.99
  5124.4  435.66  5134.9  437.73  5166.6  440.61  5198.2  445.57  5208.7  446.17
  5250.9  453.24  5261.4  453.90  5282.5  457.72  5293.1  457.92  5303.6  459.82
#Mann=4,-1,0
  4683.2    0.16       0  4763.7    0.12       0  4964.1    0.07       0
  4970.1    0.12       0
Bank Sta=4964.1,4970.1
Exp/Cntr=0.3,0.1

Type RM Length L Ch R = 1,1799,475,475,475
BEGIN DESCRIPTION:
UNT 090 IN CACR 4.0
END DESCRIPTION:
XS GIS Cut Line= 3
      3727399.61     10716860.19      3727649.61     10716710.19
      3727949.60     10716410.20
#Sta/Elev= 30
  4694.1  461.22  4697.0  461.22  4701.9  459.39  4729.1  454.53  4775.7  447.29
  4787.4  444.67  4802.9  443.28  4845.7  435.94  4861.3  435.21  4869.0  432.37
  4882.6  431.47  4913.7  426.62  4919.6  426.65  4935.1  424.43  4972.0  422.77
  4982.7  421.63  4996.8  421.50  4999.5  421.00  5002.8  421.50  5070.5  423.18
  5183.6  436.34  5197.8  436.88  5211.9  439.61  5254.4  442.43  5268.5  445.26
  5296.8  446.90  5310.9  448.47  5381.6  457.91  5395.8  460.57  5409.9  461.97
#Mann=3,-1,0
  4694.1    0.12       0  4996.8    0.07       0  5002.8    0.12       0
Bank Sta=4996.8,5002.8
Exp/Cntr=0.3,0.1

Type RM Length L Ch R = 1,1324,481,481,481
BEGIN DESCRIPTION:
UNT 090 IN CACR 3.0
END DESCRIPTION:
XS GIS Cut Line= 3
      3727649.59     10717160.20      3727949.61     10717010.19
      3728249.57     10716860.21
#Sta/Elev= 30
  4656.0  441.45  4658.8  441.45  4670.0  438.15  4700.7  432.99  4759.4  426.20
  4767.8  425.92  4790.2  422.95  4812.6  422.73  4834.9  419.00  4862.7  418.16
  4865.4  417.66  4868.7  418.16  5036.2  418.58  5072.5  420.24  5089.3  422.81
  5103.2  426.28  5117.2  427.15  5148.0  433.06  5156.3  433.69  5170.3  436.85
  5178.7  437.60  5192.7  441.01  5206.7  442.61  5223.4  445.82  5237.4  450.16
  5251.4  453.13  5282.1  457.55  5290.5  460.16  5304.5  461.17  5326.8  464.88
#Mann=3,-1,0
  4656.0    0.12       0  4862.7    0.07       0  4868.7    0.12       0
Bank Sta=4862.7,4868.7
Exp/Cntr=0.3,0.1

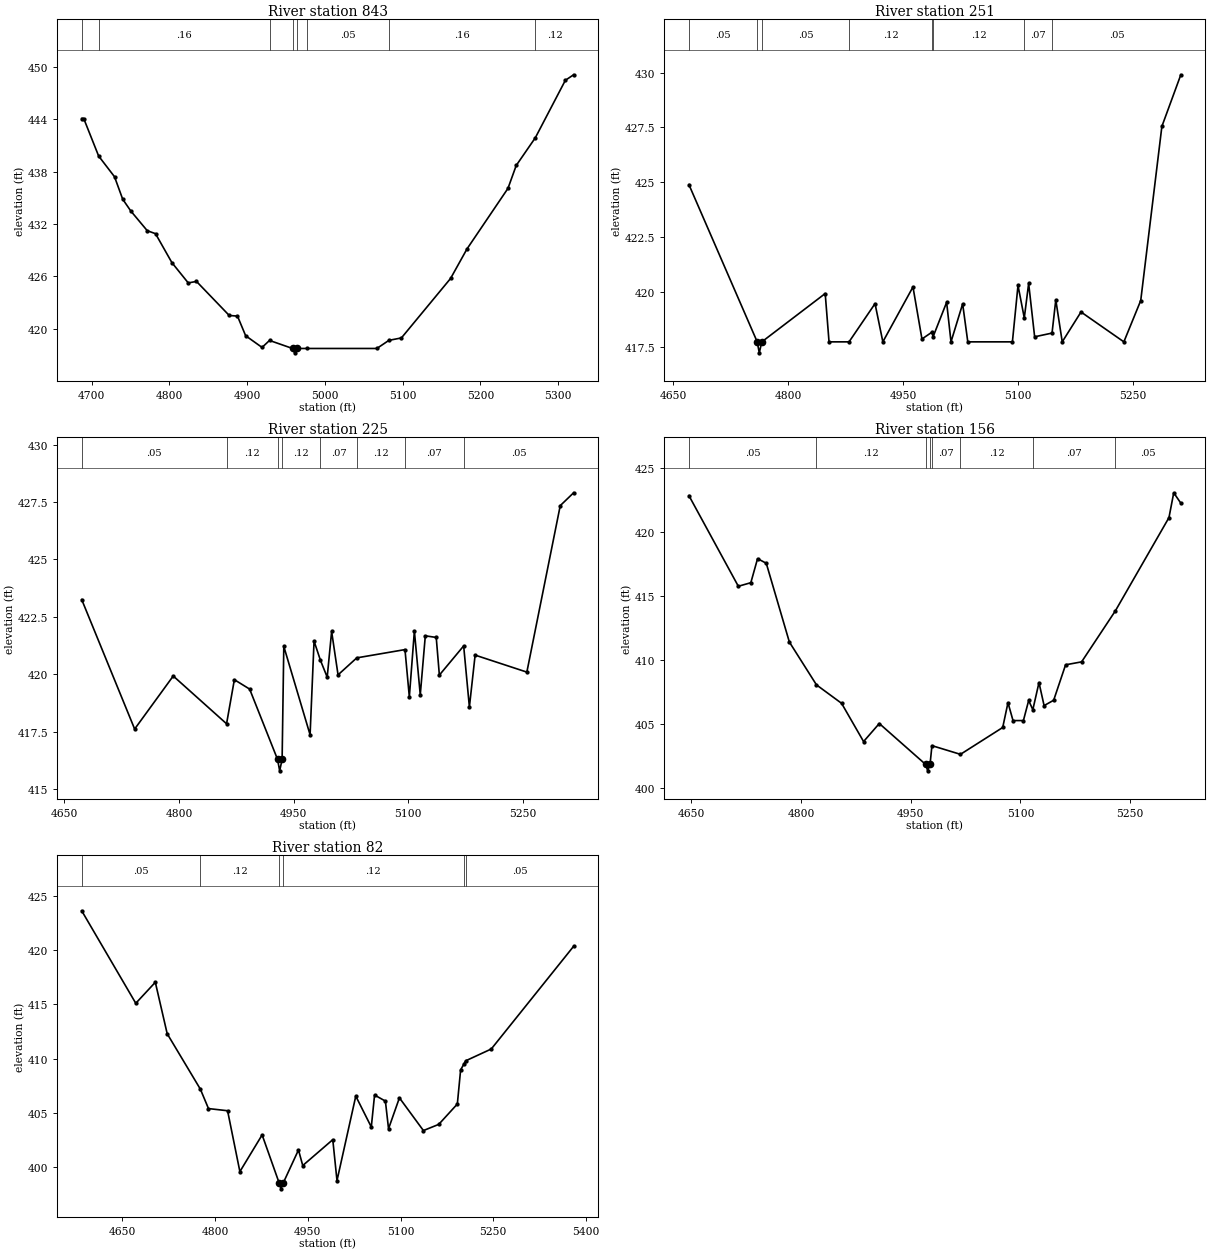
Type RM Length L Ch R = 1,843,592,592,592
BEGIN DESCRIPTION:
UNT 090 IN CACR 2.0
END DESCRIPTION:
XS GIS Cut Line= 3
      3727849.61     10717510.19      3728149.61     10717410.19
      3728449.65     10717310.17
#Sta/Elev= 30
  4687.3  444.08  4689.9  444.08  4709.1  439.78  4729.5  437.41  4740.0  434.84
  4750.5  433.48  4771.6  431.23  4782.2  430.89  4803.3  427.57  4824.3  425.25
  4834.9  425.42  4877.0  421.52  4887.6  421.45  4898.1  419.20  4919.2  417.86
  4928.8  418.66  4958.4  417.74  4961.1  417.24  4964.4  417.74  4976.6  417.74
  5066.8  417.74  5082.3  418.67  5098.4  418.95  5161.6  425.76  5182.7  429.14
  5235.4  436.08  5246.0  438.70  5270.6  441.88  5309.2  448.46  5319.8  449.09
#Mann=8,-1,0
  4687.3    0.05       0  4709.1    0.16       0  4928.8    0.12       0
  4958.4   0.033       0  4964.4    0.12       0  4976.6    0.05       0
  5082.3    0.16       0  5270.6    0.12       0
Bank Sta=4958.4,4964.4
Exp/Cntr=0.3,0.1

Type RM Length L Ch R = 1,251,26,26,26
BEGIN DESCRIPTION:
Mapping XS a03a4c3c
END DESCRIPTION:
XS GIS Cut Line= 6
      3728088.81     10717945.52      3728221.65     10717967.66
      3728383.11     10717955.95      3728501.60     10717881.73
      3728548.47     10717819.23      3728608.36     10717707.27
#Sta/Elev= 30
  4670.8  424.90  4759.9  417.74  4762.6  417.24  4765.9  417.74  4848.6  419.94
  4853.6  417.74  4879.7  417.74  4913.6  419.48  4923.8  417.74  4963.1  420.24
  4974.8  417.87  4987.8  418.18  4989.3  417.97  5007.0  419.54  5012.7  417.74
  5027.9  419.47  5034.6  417.74  5092.8  417.74  5100.1  420.31  5108.3  418.83
  5114.0  420.40  5121.8  417.97  5144.5  418.14  5149.4  419.65  5157.8  417.74
  5182.3  419.10  5238.2  417.74  5260.2  419.62  5287.8  427.55  5312.5  429.90
#Mann=8,-1,0
  4670.8    0.05       0  4759.9    0.07       0  4765.9    0.05       0
  4879.7    0.12       0  4987.8    0.07       0  4989.3    0.12       0
  5108.3    0.07       0  5144.5    0.05       0
Bank Sta=4759.9,4765.9
Exp/Cntr=0.3,0.1

Type RM Length L Ch R = 1,225,69,69,69
BEGIN DESCRIPTION:
Mapping XS d30dbf4a
END DESCRIPTION:
XS GIS Cut Line= 6
      3728100.91     10717968.32      3728353.49     10717987.85
      3728405.57     10717973.52      3728470.68     10717935.76
      3728535.78     10717879.77      3728621.71     10717727.45
#Sta/Elev= 30
  4672.7  423.25  4742.0  417.61  4792.5  419.92  4862.3  417.84  4872.5  419.76
  4892.5  419.35  4929.0  416.29  4931.8  415.79  4935.0  416.29  4937.2  421.21
  4971.6  417.36  4976.8  421.44  4985.2  420.60  4994.0  419.87  4999.8  421.86
  5008.2  419.97  5032.7  420.71  5095.8  421.07  5101.5  419.01  5108.1  421.88
  5115.8  419.10  5122.4  421.67  5136.7  421.60  5140.8  419.96  5172.6  421.23
  5180.1  418.57  5187.6  420.83  5255.3  420.09  5299.0  427.34  5316.5  427.90
#Mann=8,-1,0
  4672.7    0.05       0  4862.3    0.12       0  4929.0    0.07       0
  4935.0    0.12       0  4985.2    0.07       0  5032.7    0.12       0
  5095.8    0.07       0  5172.6    0.05       0
Bank Sta=4929,4935
Exp/Cntr=0.3,0.1

Type RM Length L Ch R = 1,156,74,74,74
BEGIN DESCRIPTION:
Mapping XS 8cb6956b
END DESCRIPTION:
XS GIS Cut Line= 6
      3728109.22     10717984.26      3728258.98     10718034.18
      3728360.97     10718045.03      3728471.65     10718018.99
      3728554.12     10717934.35      3728638.76     10717775.92
#Sta/Elev= 30
  4646.6  422.87  4714.2  415.78  4731.3  416.06  4740.5  417.94  4752.4  417.58
  4784.0  411.42  4821.1  408.07  4855.4  406.63  4885.5  403.64  4907.0  405.05
  4970.4  401.85  4973.2  401.35  4976.4  401.85  4979.0  403.32  5018.0  402.64
  5075.8  404.74  5083.0  406.68  5089.9  405.28  5104.1  405.28  5111.3  406.85
  5117.0  406.13  5125.4  408.25  5132.4  406.45  5145.5  406.87  5161.8  409.64
  5183.7  409.87  5229.9  413.86  5303.2  421.15  5309.7  423.09  5319.4  422.28
#Mann=8,-1,0
  4646.6    0.05       0  4821.1    0.12       0  4970.4    0.07       0
  4976.4    0.12       0  4979.0    0.07       0  5018.0    0.12       0
  5117.0    0.07       0  5229.9    0.05       0
Bank Sta=4970.4,4976.4
Exp/Cntr=0.3,0.1

Type RM Length L Ch R = 1,82,0,0,0
BEGIN DESCRIPTION:
UNT 090 IN CACR 1.0
END DESCRIPTION:
XS GIS Cut Line= 4
      3728087.53     10717997.28      3728419.57     10718116.64
      3728554.12     10718066.73      3728660.45     10717786.80
#Sta/Elev= 30
  4584.2  423.64  4671.7  415.10  4703.3  417.04  4722.5  412.29  4776.2  407.17
  4789.3  405.38  4820.2  405.18  4840.1  399.56  4876.1  402.95  4903.9  398.47
  4906.6  397.97  4909.9  398.47  4934.9  401.56  4941.8  400.12  4990.4  402.51
  4997.2  398.73  5027.6  406.53  5052.7  403.68  5058.0  406.63  5075.5  406.07
  5080.6  403.52  5098.2  406.37  5137.0  403.35  5161.8  403.92  5191.9  405.80
  5197.2  408.95  5202.3  409.47  5205.4  409.79  5246.8  410.88  5380.0  420.36
#Mann=6,-1,0
  4584.2    0.05       0  4776.2    0.12       0  4903.9    0.07       0
  4909.9    0.12       0  5202.3    0.07       0  5205.4    0.05       0
Bank Sta=4903.9,4909.9
Exp/Cntr=0.3,0.1

Chan Stop Cuts=-1