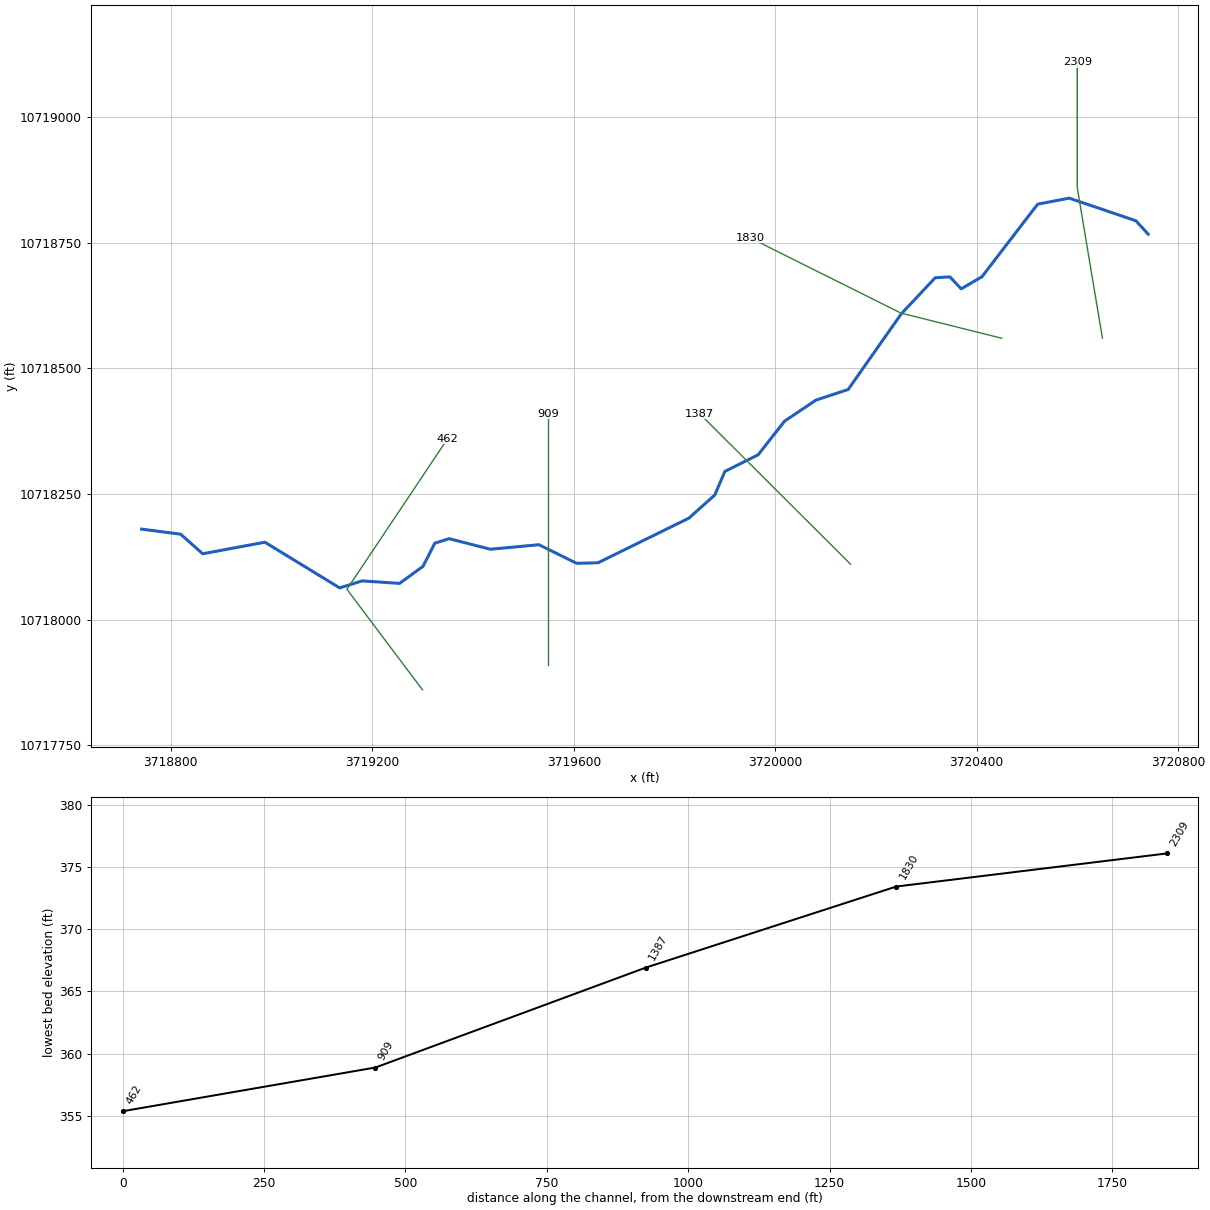
--- UNT 091 IN CACR.prj (project) ---

Proj Title=UNT 091 IN CACR Base Level Engineering
Current Plan=p01
Default Exp/Contr=0.3,0.1
English Units
Geom File=g01
Flow File=f01
Plan File=p01
BEGIN DESCRIPTION:
UNT 091 IN CACR
END DESCRIPTION:

--- UNT 091 IN CACR.p01 (plan) ---

Plan Title=Multiple Run
Short Identifier=Multiple
Geom File=g01
Flow File=f01
Subcritical Flow
K Sum by GR= 0
Std Step Tol= 0.01
Critical Tol= 0.01
Num of Std Step Trials= 20
Max Error Tol= 0.3
Flow Tol Ratio= 0.001
Split Flow NTrial= 30
Split Flow Tol= 0.02
Split Flow Ratio= 0.02
Log Output Level= 0
Friction Slope Method= 1
Unsteady Friction Slope Method= 2
Unsteady Bridges Friction Slope Method= 1
Parabolic Critical Depth
Global Vel Dist=  1 , 1 , 1
Global Log Level= 0
CheckData=True
Encroach Param= -1, 0, 0, 0
BEGIN DESCRIPTION:
Multiple Run
END DESCRIPTION:

--- UNT 091 IN CACR.f01 (steady flow) ---

Flow Title=Multiple
Number of Profiles=7
Profile Names=10-year,25-year,50-year,1pct_min,100-year,1pct_plu,500-year
River Rch & RM= UNT 091 IN CACR,Reach-1,2309
     478     646     785     702     949    1283    1391
Boundary for River Rch & Prof#=UNT 091 IN CACR,Reach-1,1
Up Type=0
Dn Type=3
Dn Slope=0.005
Boundary for River Rch & Prof#=UNT 091 IN CACR,Reach-1,2
Up Type=0
Dn Type=3
Dn Slope=0.005
Boundary for River Rch & Prof#=UNT 091 IN CACR,Reach-1,3
Up Type=0
Dn Type=3
Dn Slope=0.005
Boundary for River Rch & Prof#=UNT 091 IN CACR,Reach-1,4
Up Type=0
Dn Type=3
Dn Slope=0.005
Boundary for River Rch & Prof#=UNT 091 IN CACR,Reach-1,5
Up Type=0
Dn Type=3
Dn Slope=0.005
Boundary for River Rch & Prof#=UNT 091 IN CACR,Reach-1,6
Up Type=0
Dn Type=3
Dn Slope=0.005
Boundary for River Rch & Prof#=UNT 091 IN CACR,Reach-1,7
Up Type=0
Dn Type=3
Dn Slope=0.005

--- UNT 091 IN CACR.g01 (geometry) ---

Geom Title=Existing Conditions

River Reach=UNT 091 IN CACR,Reach-1
Reach XY= 30
      3720740.41     10718767.34      3720716.00     10718794.00
      3720583.75     10718839.00      3720521.00     10718827.00
      3720410.54     10718682.69      3720369.31     10718658.38
      3720346.74     10718682.25      3720317.66     10718680.52
      3720250.50     10718609.00      3720144.75     10718458.00
      3720081.00     10718437.00      3720018.50     10718395.00
      3719966.00     10718328.00      3719900.00     10718295.00
      3719880.00     10718248.00      3719828.75     10718202.00
      3719648.00     10718113.00      3719605.75     10718112.00
      3719530.75     10718149.00      3719434.75     10718140.00
      3719352.50     10718161.00      3719324.00     10718152.00
      3719300.75     10718106.00      3719254.25     10718072.00
      3719179.75     10718077.00      3719135.25     10718063.00
      3718986.75     10718154.00      3718863.25     10718131.00
      3718819.50     10718170.00      3718742.00     10718180.00

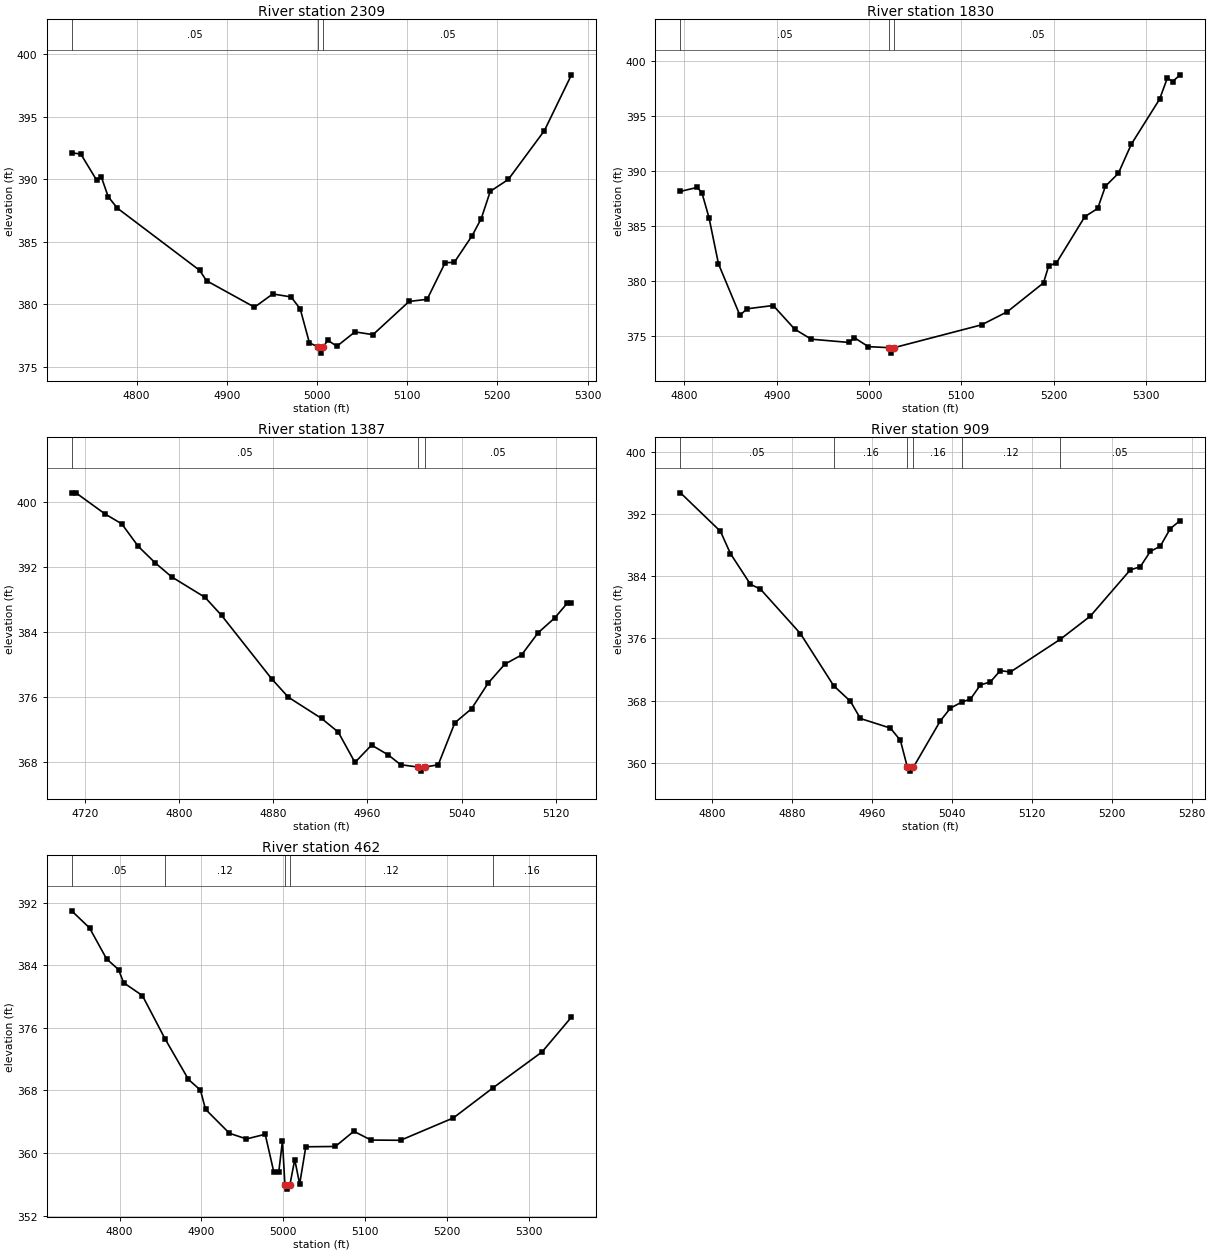
Type RM Length L Ch R = 1,2309,479,479,479
BEGIN DESCRIPTION:
UNT 091 IN CACR 5.0
END DESCRIPTION:
XS GIS Cut Line= 3
      3720649.60     10718560.22      3720599.61     10718860.19
      3720599.61     10719110.19
#Sta/Elev= 30
  4728.1  392.12  4738.2  392.03  4755.9  389.92  4761.0  390.19  4768.6  388.61
  4778.8  387.69  4870.0  382.71  4877.6  381.88  4930.8  379.76  4951.1  380.82
  4971.4  380.58  4981.5  379.62  4991.7  376.90  5001.3  376.58  5004.1  376.08
  5007.3  376.58  5011.9  377.12  5022.1  376.63  5042.2  377.78  5062.2  377.56
  5102.2  380.22  5122.2  380.39  5142.2  383.33  5152.2  383.34  5172.2  385.50
  5182.2  386.86  5192.2  389.04  5212.2  389.99  5252.2  393.90  5282.2  398.37
#Mann=3,-1,0
  4728.1    0.05       0  5001.3    0.03       0  5007.3    0.05       0
Bank Sta=5001.3,5007.3
Exp/Cntr=0.3,0.1

Type RM Length L Ch R = 1,1830,443,443,443
BEGIN DESCRIPTION:
UNT 091 IN CACR 4.0
END DESCRIPTION:
XS GIS Cut Line= 3
      3720449.62     10718560.18      3720249.61     10718610.19
      3719949.59     10718760.20
#Sta/Elev= 30
  4795.7  388.16  4813.8  388.52  4818.9  388.04  4826.6  385.77  4836.9  381.55
  4860.1  376.87  4867.9  377.46  4896.2  377.76  4919.4  375.61  4937.4  374.69
  4978.7  374.39  4983.8  374.84  4999.3  374.01  5021.2  373.92  5024.0  373.42
  5027.2  373.92  5122.1  376.00  5150.0  377.20  5189.1  379.82  5194.7  381.37
  5203.1  381.64  5233.9  385.86  5247.8  386.60  5256.2  388.63  5270.2  389.80
  5284.2  392.45  5314.9  396.56  5323.3  398.49  5328.9  398.17  5337.3  398.78
#Mann=3,-1,0
  4795.7    0.05       0  5021.2    0.03       0  5027.2    0.05       0
Bank Sta=5021.2,5027.2
Exp/Cntr=0.3,0.1

Type RM Length L Ch R = 1,1387,478,478,478
BEGIN DESCRIPTION:
UNT 091 IN CACR 3.0
END DESCRIPTION:
XS GIS Cut Line= 3
      3720149.64     10718110.16      3719949.61     10718310.19
      3719849.61     10718410.19
#Sta/Elev= 30
  4708.9  401.11  4712.5  401.11  4737.2  398.52  4751.4  397.30  4765.5  394.52
  4779.7  392.52  4793.8  390.78  4822.1  388.27  4836.2  386.04  4878.6  378.27
  4892.8  376.00  4921.1  373.38  4935.2  371.71  4949.4  367.98  4963.5  370.11
  4977.6  368.91  4988.2  367.70  5002.9  367.41  5005.7  366.91  5008.9  367.41
  5020.1  367.69  5034.2  372.85  5048.4  374.58  5062.5  377.73  5076.6  380.05
  5090.8  381.18  5104.9  383.91  5119.1  385.75  5129.7  387.56  5133.2  387.56
#Mann=3,-1,0
  4708.9    0.05       0  5002.9    0.03       0  5008.9    0.05       0
Bank Sta=5002.9,5008.9
Exp/Cntr=0.3,0.1

Type RM Length L Ch R = 1,909,447,447,447
BEGIN DESCRIPTION:
UNT 091 IN CACR 2.0
END DESCRIPTION:
XS GIS Cut Line= 3
      3719549.61     10717910.19      3719549.61     10718110.19
      3719549.61     10718410.19
#Sta/Elev= 30
  4768.6  394.79  4808.6  389.82  4818.6  386.95  4838.6  382.99  4848.6  382.37
  4888.6  376.63  4921.9  369.90  4938.6  367.90  4948.6  365.68  4978.6  364.44
  4988.6  362.86  4995.6  359.39  4998.3  358.89  5001.6  359.39  5028.6  365.38
  5038.6  367.01  5050.4  367.83  5058.6  368.16  5068.6  370.00  5078.6  370.40
  5088.6  371.86  5098.6  371.67  5148.5  375.89  5178.6  378.88  5218.6  384.85
  5228.6  385.25  5238.6  387.23  5248.6  387.90  5258.6  390.17  5268.6  391.22
#Mann=6,-1,0
  4768.6    0.05       0  4921.9    0.16       0  4995.6    0.07       0
  5001.6    0.16       0  5050.4    0.12       0  5148.5    0.05       0
Bank Sta=4995.6,5001.6
Exp/Cntr=0.3,0.1

Type RM Length L Ch R = 1,462,0,0,0
BEGIN DESCRIPTION:
UNT 091 IN CACR 1.0
END DESCRIPTION:
XS GIS Cut Line= 3
      3719299.59     10717860.21      3719149.61     10718060.19
      3719349.59     10718360.16
#Sta/Elev= 30
  4741.4  390.94  4763.2  388.76  4784.1  384.79  4798.7  383.43  4804.9  381.75
  4827.8  380.11  4855.6  374.56  4884.1  369.39  4898.7  368.03  4904.9  365.58
  4934.1  362.52  4954.9  361.79  4977.8  362.39  4988.3  357.58  4994.4  357.58
  4998.9  361.54  5001.9  355.88  5004.6  355.38  5007.9  355.88  5013.9  359.16
  5019.9  356.02  5027.4  360.79  5063.5  360.83  5086.0  362.77  5107.1  361.65
  5143.1  361.62  5207.7  364.48  5255.9  368.31  5315.9  372.90  5351.9  377.36
#Mann=5,-1,0
  4741.4    0.05       0  4855.6    0.12       0  5001.9    0.07       0
  5007.9    0.12       0  5255.9    0.16       0
Bank Sta=5001.9,5007.9
Exp/Cntr=0.3,0.1

Chan Stop Cuts=-1