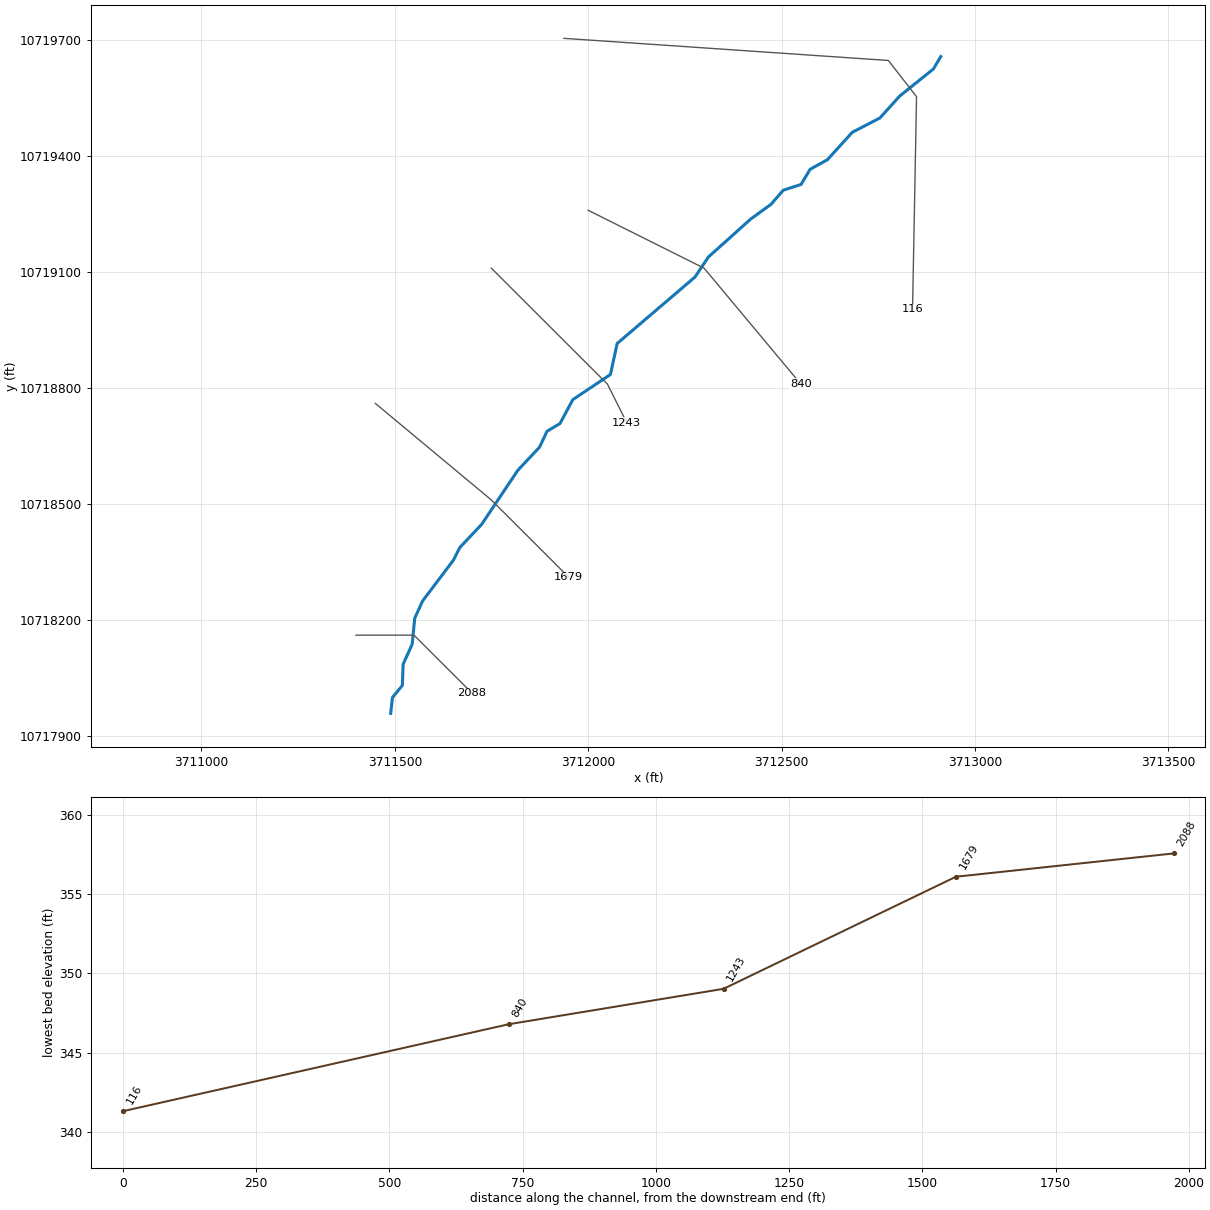
--- UNT 093 IN CACR.prj (project) ---

Proj Title=UNT 093 IN CACR Base Level Engineering
Current Plan=p01
Default Exp/Contr=0.3,0.1
English Units
Geom File=g01
Flow File=f01
Plan File=p01
BEGIN DESCRIPTION:
UNT 093 IN CACR
END DESCRIPTION:

--- UNT 093 IN CACR.p01 (plan) ---

Plan Title=Multiple Run
Short Identifier=Multiple
Geom File=g01
Flow File=f01
Subcritical Flow
K Sum by GR= 0
Std Step Tol= 0.01
Critical Tol= 0.01
Num of Std Step Trials= 20
Max Error Tol= 0.3
Flow Tol Ratio= 0.001
Split Flow NTrial= 30
Split Flow Tol= 0.02
Split Flow Ratio= 0.02
Log Output Level= 0
Friction Slope Method= 1
Unsteady Friction Slope Method= 2
Unsteady Bridges Friction Slope Method= 1
Parabolic Critical Depth
Global Vel Dist=  1 , 1 , 1
Global Log Level= 0
CheckData=True
Encroach Param= -1, 0, 0, 0
BEGIN DESCRIPTION:
Multiple Run
END DESCRIPTION:

--- UNT 093 IN CACR.f01 (steady flow) ---

Flow Title=Multiple
Number of Profiles=7
Profile Names=10-year,25-year,50-year,1pct_min,100-year,1pct_plu,500-year
River Rch & RM= UNT 093 IN CACR,Reach-1,2088
     333     442     530     470     636     859     914
Boundary for River Rch & Prof#=UNT 093 IN CACR,Reach-1,1
Up Type=0
Dn Type=3
Dn Slope=0.005
Boundary for River Rch & Prof#=UNT 093 IN CACR,Reach-1,2
Up Type=0
Dn Type=3
Dn Slope=0.005
Boundary for River Rch & Prof#=UNT 093 IN CACR,Reach-1,3
Up Type=0
Dn Type=3
Dn Slope=0.005
Boundary for River Rch & Prof#=UNT 093 IN CACR,Reach-1,4
Up Type=0
Dn Type=3
Dn Slope=0.005
Boundary for River Rch & Prof#=UNT 093 IN CACR,Reach-1,5
Up Type=0
Dn Type=3
Dn Slope=0.005
Boundary for River Rch & Prof#=UNT 093 IN CACR,Reach-1,6
Up Type=0
Dn Type=3
Dn Slope=0.005
Boundary for River Rch & Prof#=UNT 093 IN CACR,Reach-1,7
Up Type=0
Dn Type=3
Dn Slope=0.005

--- UNT 093 IN CACR.g01 (geometry) ---

Geom Title=Existing Conditions

River Reach=UNT 093 IN CACR,Reach-1
Reach XY= 30
      3711489.39     10717957.75      3711494.00     10717999.00
      3711519.50     10718030.00      3711521.50     10718085.00
      3711545.00     10718137.00      3711551.50     10718204.00
      3711572.00     10718249.00      3711651.25     10718354.00
      3711668.00     10718387.00      3711724.50     10718447.00
      3711818.00     10718587.00      3711874.25     10718647.00
      3711893.50     10718688.00      3711926.91     10718707.92
      3711960.25     10718770.00      3712057.39     10718834.91
      3712074.87     10718915.29      3712275.75     10719087.00
      3712310.50     10719139.00      3712420.75     10719238.00
      3712472.00     10719275.00      3712504.25     10719312.00
      3712550.25     10719327.00      3712573.50     10719366.00
      3712618.25     10719391.00      3712682.75     10719462.00
      3712754.00     10719499.00      3712805.50     10719556.00
      3712892.50     10719626.00      3712911.25     10719658.00

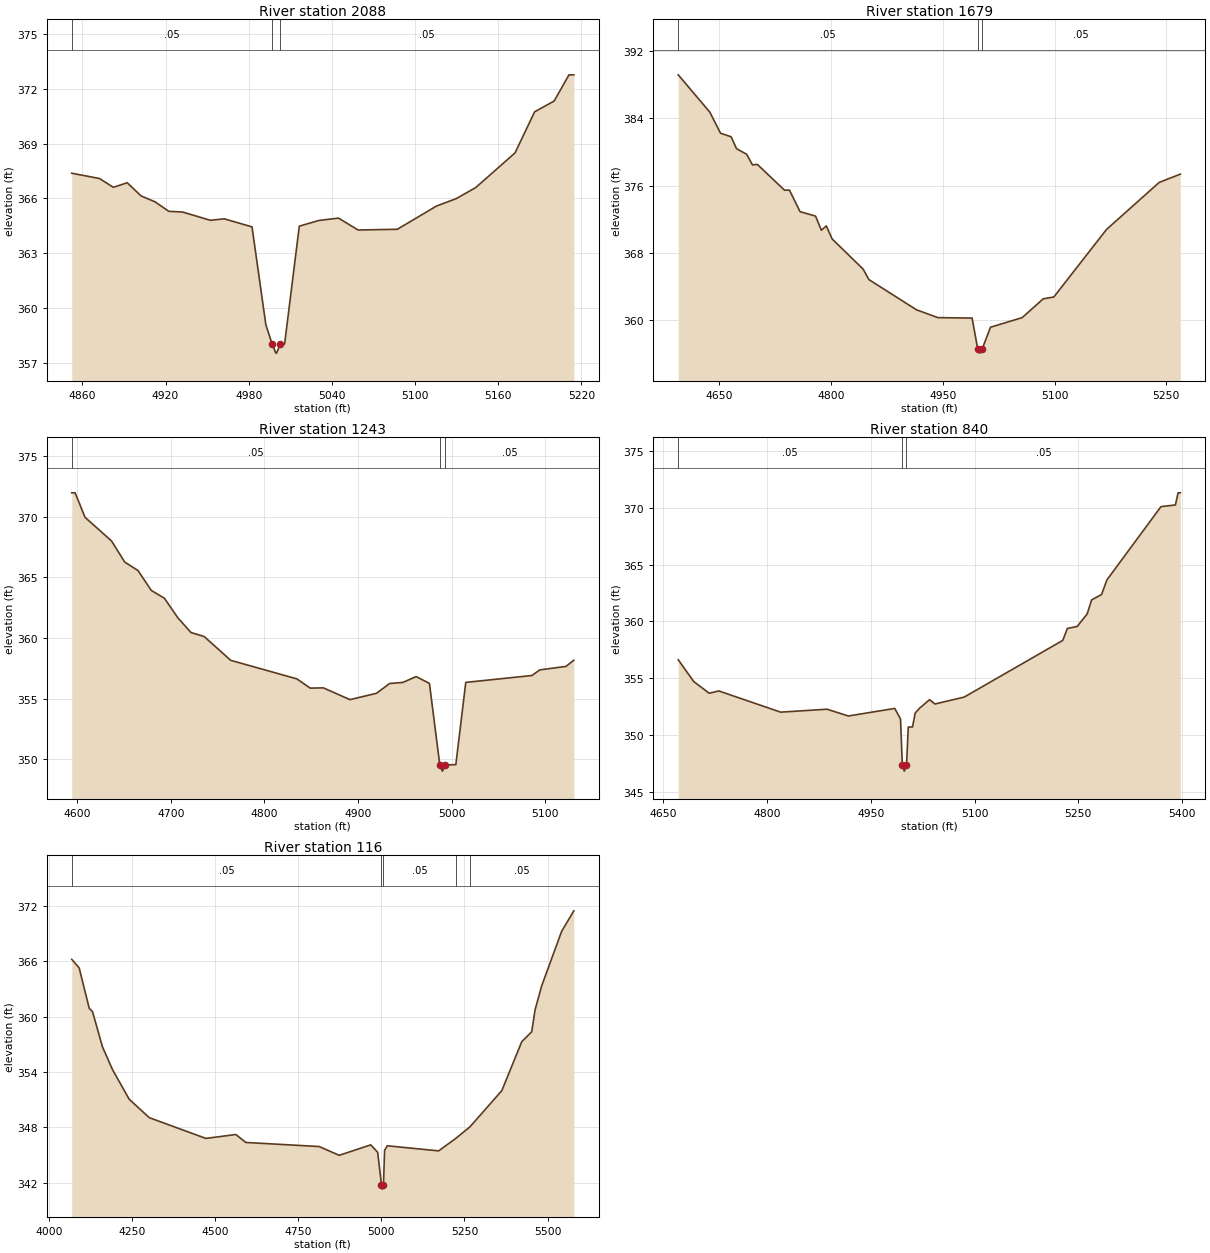
Type RM Length L Ch R = 1,2088,409,409,409
BEGIN DESCRIPTION:
UNT 093 IN CACR 5.0
END DESCRIPTION:
XS GIS Cut Line= 3
      3711399.65     10718160.19      3711549.61     10718160.19
      3711699.62     10718010.18
#Sta/Elev= 30
  4852.4  367.38  4872.4  367.09  4882.4  366.61  4892.4  366.86  4902.4  366.14
  4912.4  365.82  4922.4  365.30  4932.4  365.26  4952.4  364.81  4962.4  364.89
  4982.4  364.45  4992.4  359.10  4996.9  358.06  4999.6  357.56  5000.1  357.56
  5002.9  358.06  5005.9  358.06  5016.5  364.49  5030.6  364.80  5044.8  364.93
  5058.9  364.28  5087.2  364.32  5115.5  365.59  5129.6  365.99  5143.8  366.60
  5172.1  368.49  5186.2  370.73  5200.3  371.32  5211.0  372.75  5214.5  372.75
#Mann=3,-1,0
  4852.4    0.05       0  4996.9    0.03       0  5002.9    0.05       0
Bank Sta=4996.9,5002.9
Exp/Cntr=0.3,0.1

Type RM Length L Ch R = 1,1679,436,436,436
BEGIN DESCRIPTION:
UNT 093 IN CACR 4.0
END DESCRIPTION:
XS GIS Cut Line= 3
      3711449.57     10718760.22      3711749.61     10718510.19
      3711949.61     10718310.19
#Sta/Elev= 30
  4595.3  389.18  4637.7  384.74  4652.0  382.24  4666.3  381.81  4673.5  380.40
  4687.1  379.73  4694.9  378.47  4701.4  378.53  4737.9  375.46  4744.4  375.48
  4758.7  372.91  4779.5  372.38  4787.3  370.70  4793.9  371.22  4801.7  369.67
  4843.3  366.08  4851.1  364.83  4914.9  361.24  4943.6  360.31  4989.4  360.26
  4997.0  356.59  4999.8  356.09  5003.0  356.59  5014.1  359.17  5056.6  360.31
  5084.9  362.55  5099.0  362.76  5169.7  370.79  5240.4  376.39  5268.7  377.37
#Mann=3,-1,0
  4595.3    0.05       0  4997.0    0.03       0  5003.0    0.05       0
Bank Sta=4997,5003
Exp/Cntr=0.3,0.1

Type RM Length L Ch R = 1,1243,403,403,403
BEGIN DESCRIPTION:
UNT 093 IN CACR 3.0
END DESCRIPTION:
XS GIS Cut Line= 3
      3711749.60     10719110.20      3712049.61     10718810.19
      3712099.62     10718710.17
#Sta/Elev= 30
  4594.3  371.96  4597.9  371.96  4608.5  369.94  4636.7  368.00  4650.9  366.25
  4665.0  365.56  4679.2  363.92  4693.3  363.27  4707.5  361.67  4721.6  360.45
  4735.7  360.12  4764.0  358.16  4834.7  356.63  4848.9  355.87  4863.0  355.89
  4891.3  354.92  4919.6  355.44  4933.7  356.25  4947.9  356.34  4962.0  356.82
  4976.2  356.26  4987.3  349.53  4990.0  349.03  4993.3  349.53  5004.4  349.57
  5015.0  356.34  5085.7  356.91  5094.0  357.37  5122.0  357.66  5130.4  358.17
#Mann=3,-1,0
  4594.3    0.05       0  4987.3    0.03       0  4993.3    0.05       0
Bank Sta=4987.3,4993.3
Exp/Cntr=0.3,0.1

Type RM Length L Ch R = 1,840,724,724,724
BEGIN DESCRIPTION:
UNT 093 IN CACR 2.0
END DESCRIPTION:
XS GIS Cut Line= 3
      3711999.61     10719260.19      3712299.61     10719110.19
      3712549.60     10718810.20
#Sta/Elev= 30
  4671.6  356.62  4694.0  354.70  4716.3  353.67  4730.3  353.87  4819.7  352.00
  4886.8  352.26  4917.6  351.66  4984.6  352.33  4993.0  351.40  4995.6  347.30
  4998.4  346.80  5001.6  347.30  5004.2  350.69  5010.3  350.69  5014.2  351.92
  5020.7  352.36  5035.0  353.10  5042.8  352.72  5085.1  353.33  5227.6  358.33
  5234.2  359.38  5248.5  359.56  5262.8  360.66  5269.3  361.90  5283.6  362.37
  5291.4  363.66  5369.5  370.12  5390.4  370.27  5394.3  371.34  5397.5  371.34
#Mann=3,-1,0
  4671.6    0.05       0  4995.6    0.03       0  5001.6    0.05       0
Bank Sta=4995.6,5001.6
Exp/Cntr=0.3,0.1

Type RM Length L Ch R = 1,116,0,0,0
BEGIN DESCRIPTION:
UNT 093 IN CACR 1.0
END DESCRIPTION:
XS GIS Cut Line= 4
      3711937.31     10719705.19      3712775.87     10719647.90
      3712848.78     10719554.15      3712838.40     10719003.63
#Sta/Elev= 30
  4069.3  366.19  4091.7  365.25  4121.7  360.90  4131.7  360.53  4161.8  356.70
  4191.9  354.25  4242.0  351.05  4302.1  349.06  4472.5  346.81  4562.7  347.23
  4592.8  346.37  4813.3  345.93  4873.5  344.98  4968.4  346.11  4989.2  345.31
  5000.7  341.82  5003.5  341.32  5006.7  341.82  5010.0  345.51  5018.2  346.01
  5172.6  345.46  5223.5  346.79  5267.0  348.07  5362.6  351.98  5422.6  357.28
  5452.6  358.36  5462.6  360.73  5482.6  363.33  5542.6  369.23  5579.2  371.44
#Mann=5,-1,0
  4069.3    0.05       0  5000.7    0.03       0  5006.7    0.05       0
  5223.5    0.16       0  5267.0    0.05       0
Bank Sta=5000.7,5006.7
Exp/Cntr=0.3,0.1

Chan Stop Cuts=-1