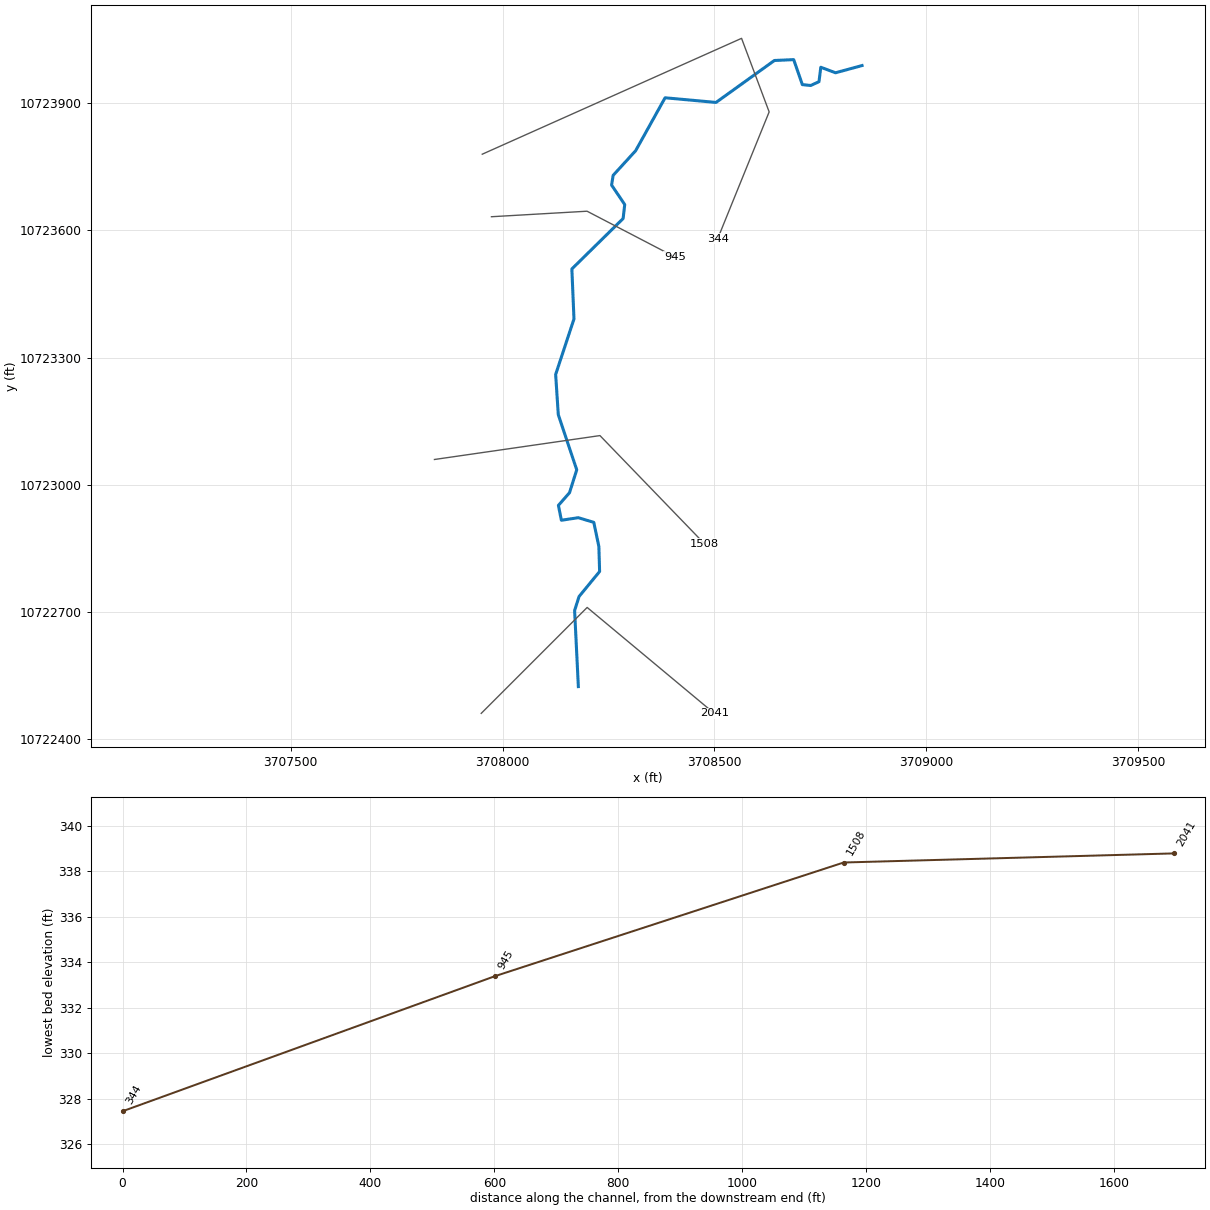
--- UNT 094 IN CACR.prj (project) ---

Proj Title=UNT 094 IN CACR Base Level Engineering
Current Plan=p01
Default Exp/Contr=0.3,0.1
English Units
Geom File=g01
Flow File=f01
Plan File=p01
BEGIN DESCRIPTION:
UNT 094 IN CACR
END DESCRIPTION:

--- UNT 094 IN CACR.p01 (plan) ---

Plan Title=Multiple Run
Short Identifier=Multiple
Geom File=g01
Flow File=f01
Subcritical Flow
K Sum by GR= 0
Std Step Tol= 0.01
Critical Tol= 0.01
Num of Std Step Trials= 20
Max Error Tol= 0.3
Flow Tol Ratio= 0.001
Split Flow NTrial= 30
Split Flow Tol= 0.02
Split Flow Ratio= 0.02
Log Output Level= 0
Friction Slope Method= 1
Unsteady Friction Slope Method= 2
Unsteady Bridges Friction Slope Method= 1
Parabolic Critical Depth
Global Vel Dist=  1 , 1 , 1
Global Log Level= 0
CheckData=True
Encroach Param= -1, 0, 0, 0
BEGIN DESCRIPTION:
Multiple Run
END DESCRIPTION:

--- UNT 094 IN CACR.f01 (steady flow) ---

Flow Title=Multiple
Number of Profiles=7
Profile Names=10-year,25-year,50-year,1pct_min,100-year,1pct_plu,500-year
River Rch & RM= UNT 094 IN CACR,Reach-1,2041
     526     715     872     783    1059    1432    1565
Boundary for River Rch & Prof#=UNT 094 IN CACR,Reach-1,1
Up Type=0
Dn Type=3
Dn Slope=0.005
Boundary for River Rch & Prof#=UNT 094 IN CACR,Reach-1,2
Up Type=0
Dn Type=3
Dn Slope=0.005
Boundary for River Rch & Prof#=UNT 094 IN CACR,Reach-1,3
Up Type=0
Dn Type=3
Dn Slope=0.005
Boundary for River Rch & Prof#=UNT 094 IN CACR,Reach-1,4
Up Type=0
Dn Type=3
Dn Slope=0.005
Boundary for River Rch & Prof#=UNT 094 IN CACR,Reach-1,5
Up Type=0
Dn Type=3
Dn Slope=0.005
Boundary for River Rch & Prof#=UNT 094 IN CACR,Reach-1,6
Up Type=0
Dn Type=3
Dn Slope=0.005
Boundary for River Rch & Prof#=UNT 094 IN CACR,Reach-1,7
Up Type=0
Dn Type=3
Dn Slope=0.005

--- UNT 094 IN CACR.g01 (geometry) ---

Geom Title=Existing Conditions

River Reach=UNT 094 IN CACR,Reach-1
Reach XY= 30
      3708178.83     10722523.41      3708170.00     10722703.00
      3708180.50     10722736.00      3708229.00     10722795.00
      3708227.25     10722854.00      3708215.25     10722911.00
      3708178.75     10722922.00      3708138.75     10722916.00
      3708131.75     10722951.00      3708158.00     10722981.00
      3708175.00     10723035.00      3708131.50     10723165.00
      3708125.25     10723260.00      3708168.50     10723391.00
      3708163.50     10723509.00      3708284.50     10723628.00
      3708288.25     10723661.00      3708257.25     10723707.00
      3708261.00     10723730.00      3708314.00     10723788.00
      3708383.50     10723913.00      3708503.75     10723902.00
      3708641.50     10724001.00      3708687.00     10724003.00
      3708707.50     10723944.00      3708727.25     10723942.00
      3708746.75     10723951.00      3708751.00     10723985.00
      3708785.75     10723972.00      3708848.25     10723989.00

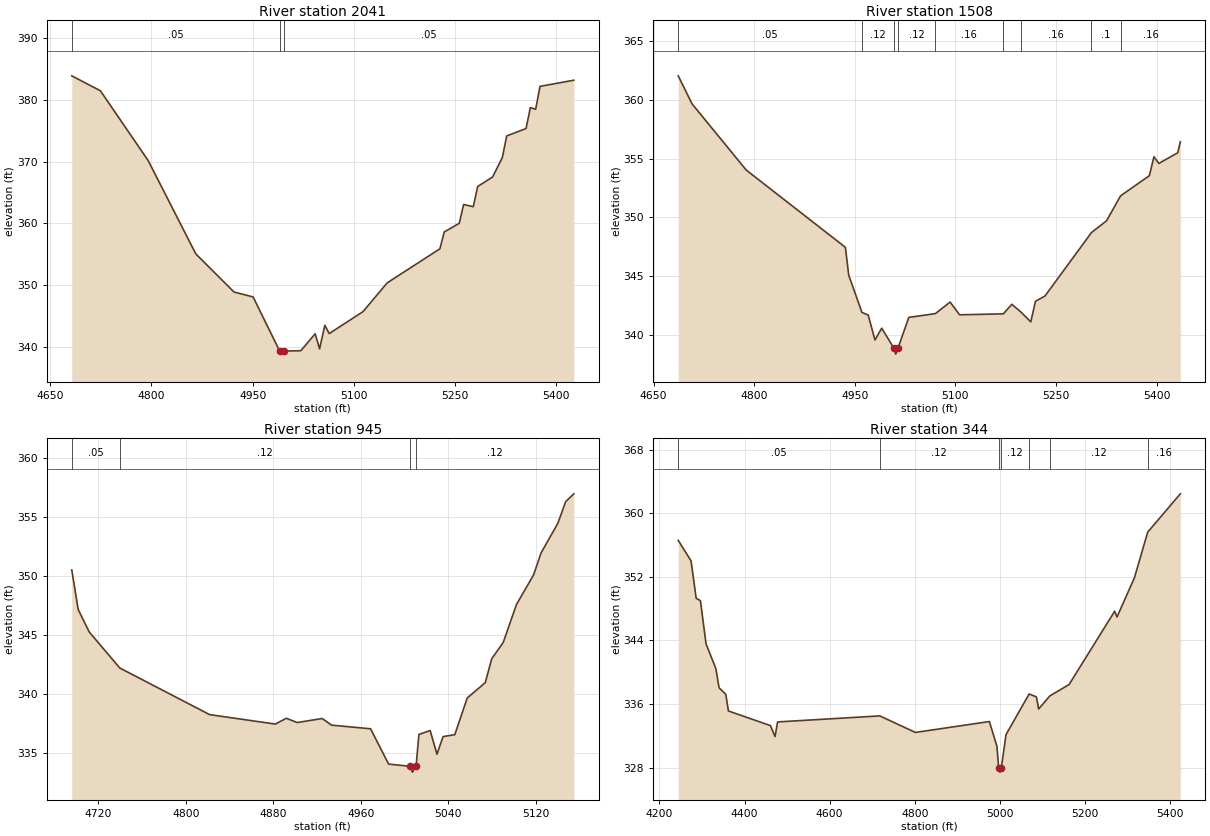
Type RM Length L Ch R = 1,2041,533,533,533
BEGIN DESCRIPTION:
UNT 094 IN CACR 3.0
END DESCRIPTION:
XS GIS Cut Line= 3
      3707949.62     10722460.20      3708199.61     10722710.19
      3708499.57     10722460.22
#Sta/Elev= 30
  4682.0  383.90  4724.4  381.48  4795.1  370.19  4865.8  355.04  4922.4  348.86
  4950.7  348.06  4990.1  339.29  4992.9  338.79  4996.1  339.29  5021.4  339.34
  5042.7  342.09  5049.2  339.65  5057.0  343.46  5063.5  342.12  5113.6  345.68
  5149.4  350.34  5227.5  355.86  5234.0  358.60  5256.2  359.99  5262.7  363.05
  5277.0  362.69  5283.5  365.96  5305.6  367.50  5320.0  370.64  5326.5  374.16
  5355.1  375.35  5361.6  378.75  5369.4  378.48  5375.9  382.19  5426.0  383.19
#Mann=3,-1,0
  4682.0    0.05       0  4990.1   0.035       0  4996.1    0.05       0
Bank Sta=4990.1,4996.1
Exp/Cntr=0.3,0.1

Type RM Length L Ch R = 1,1508,563,563,563
BEGIN DESCRIPTION:
UNT 094 IN CACR 2.0
END DESCRIPTION:
XS GIS Cut Line= 3
      3707839.22     10723059.36      3708229.80     10723115.78
      3708475.88     10722861.06
#Sta/Elev= 30
  4686.7  362.02  4707.3  359.64  4788.1  354.02  4936.0  347.46  4941.0  345.09
  4960.7  341.93  4970.0  341.71  4980.1  339.59  4990.2  340.59  5008.4  338.89
  5011.1  338.39  5014.4  338.89  5030.6  341.51  5070.2  341.83  5092.2  342.81
  5106.3  341.73  5171.6  341.81  5184.2  342.62  5198.1  341.95  5212.5  341.13
  5219.5  342.88  5233.6  343.32  5303.0  348.71  5325.5  349.71  5346.4  351.83
  5389.3  353.54  5396.2  355.15  5403.4  354.58  5431.7  355.49  5435.5  356.42
#Mann=9,-1,0
  4686.7    0.05       0  4960.7    0.12       0  5008.4    0.07       0
  5014.4    0.12       0  5070.2    0.16       0  5171.6     0.1       0
  5198.1    0.16       0  5303.0     0.1       0  5346.4    0.16       0
Bank Sta=5008.4,5014.4
Exp/Cntr=0.3,0.1

Type RM Length L Ch R = 1,945,601,601,601
BEGIN DESCRIPTION:
Mapping XS e99a98c3
END DESCRIPTION:
XS GIS Cut Line= 3
      3707973.73     10723632.27      3708199.42     10723645.29
      3708406.19     10723537.60
#Sta/Elev= 30
  4695.6  350.51  4701.5  347.16  4711.5  345.27  4739.5  342.21  4821.7  338.26
  4881.8  337.46  4891.8  337.95  4901.8  337.59  4924.7  337.93  4933.2  337.37
  4968.9  337.06  4985.4  334.07  5004.5  333.89  5007.2  333.39  5010.5  333.89
  5013.1  336.58  5023.4  336.91  5029.6  334.91  5035.2  336.40  5045.9  336.56
  5057.3  339.67  5073.8  340.97  5079.7  342.99  5090.2  344.37  5102.3  347.58
  5118.0  350.10  5124.8  351.95  5140.1  354.45  5147.4  356.31  5154.8  356.96
#Mann=4,-1,0
  4695.6    0.05       0  4739.5    0.12       0  5004.5    0.07       0
  5010.5    0.12       0
Bank Sta=5004.5,5010.5
Exp/Cntr=0.3,0.1

Type RM Length L Ch R = 1,344,0,0,0
BEGIN DESCRIPTION:
UNT 094 IN CACR 1.0
END DESCRIPTION:
XS GIS Cut Line= 4
      3707952.05     10723779.85      3708564.00     10724053.28
      3708629.11     10723879.67      3708507.57     10723580.17
#Sta/Elev= 30
  4244.4  356.59  4274.6  354.00  4286.5  349.31  4296.5  349.01  4309.7  343.58
  4332.9  340.45  4340.3  338.05  4356.1  337.23  4362.2  335.14  4460.8  333.30
  4471.7  331.92  4477.7  333.76  4717.7  334.52  4801.3  332.44  4975.0  333.81
  4992.7  330.70  4996.9  327.95  4999.7  327.45  5002.9  327.95  5014.1  332.17
  5068.4  337.28  5085.4  336.91  5090.7  335.39  5116.9  337.03  5162.1  338.46
  5269.2  347.68  5274.6  346.95  5315.4  351.86  5346.8  357.63  5423.3  362.44
#Mann=7,-1,0
  4244.4    0.05       0  4717.7    0.12       0  4996.9    0.07       0
  5002.9    0.12       0  5068.4    0.16       0  5116.9    0.12       0
  5346.8    0.16       0
Bank Sta=4996.9,5002.9
Exp/Cntr=0.3,0.1

Chan Stop Cuts=-1