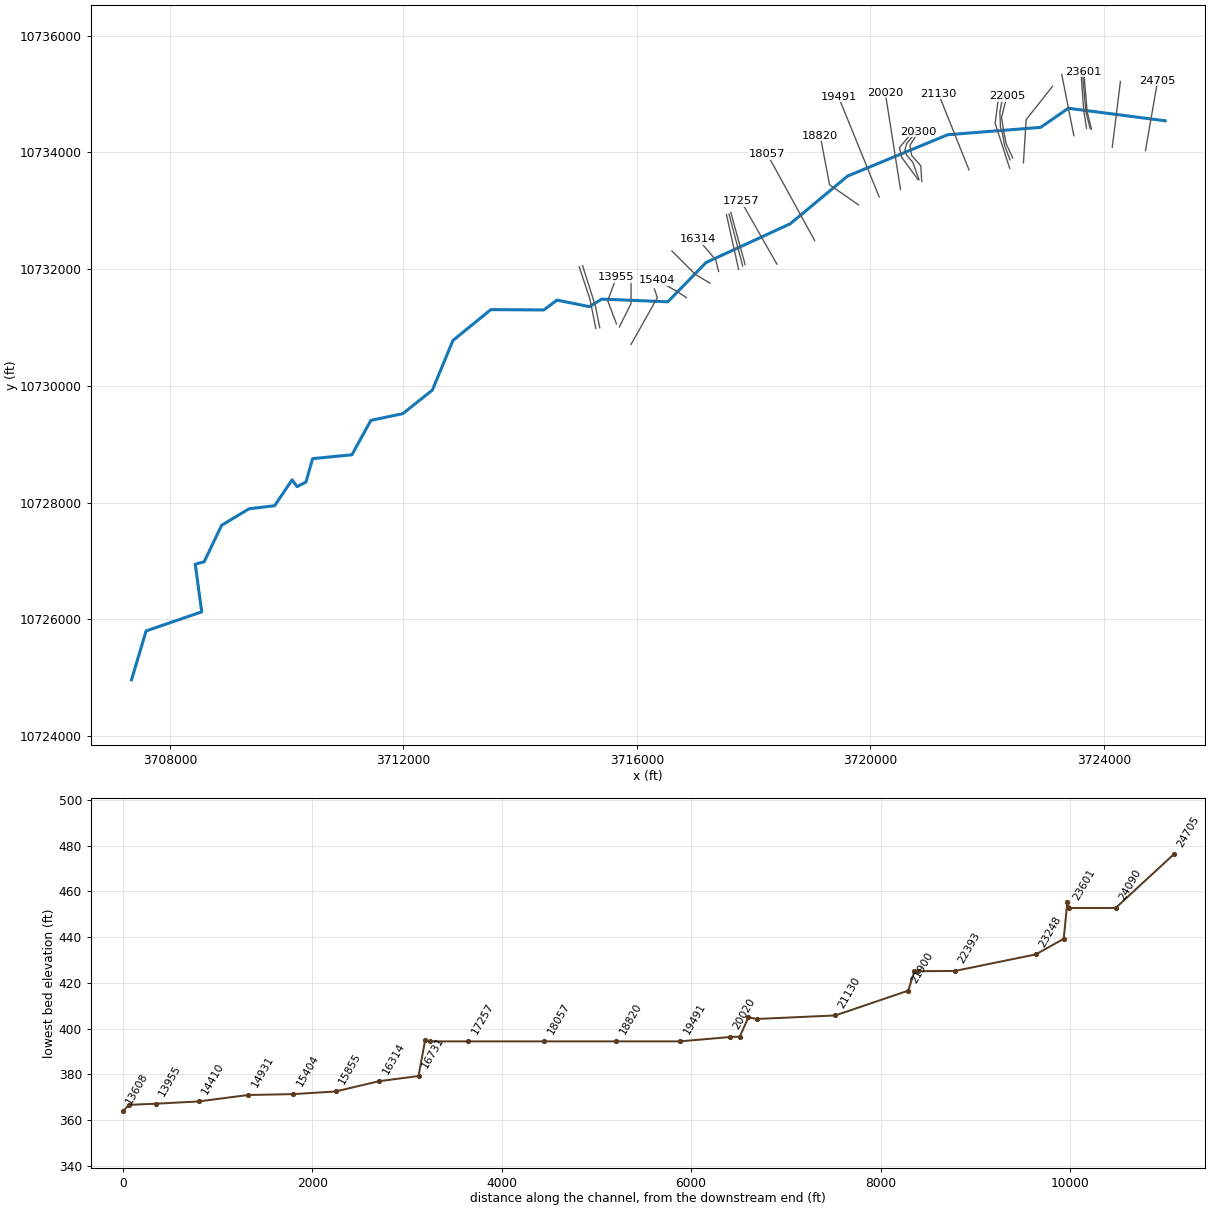
--- UNT 096 IN CACR.prj (project) ---

Proj Title=UNT 096 IN CACR Base Level Engineering
Current Plan=p01
Default Exp/Contr=0.3,0.1
English Units
Geom File=g01
Flow File=f01
Plan File=p01
BEGIN DESCRIPTION:
UNT 096 IN CACR
END DESCRIPTION:

--- UNT 096 IN CACR.p01 (plan) ---

Plan Title=Multiple Run
Short Identifier=Multiple
Geom File=g01
Flow File=f01
Subcritical Flow
K Sum by GR= 0
Std Step Tol= 0.01
Critical Tol= 0.01
Num of Std Step Trials= 20
Max Error Tol= 0.3
Flow Tol Ratio= 0.001
Split Flow NTrial= 30
Split Flow Tol= 0.02
Split Flow Ratio= 0.02
Log Output Level= 0
Friction Slope Method= 1
Unsteady Friction Slope Method= 2
Unsteady Bridges Friction Slope Method= 1
Parabolic Critical Depth
Global Vel Dist=  1 , 1 , 1
Global Log Level= 0
CheckData=True
Encroach Param= -1, 0, 0, 0
BEGIN DESCRIPTION:
Multiple Run
END DESCRIPTION:

--- UNT 096 IN CACR.f01 (steady flow) ---

Flow Title=Multiple
Number of Profiles=7
Profile Names=10-year,25-year,50-year,1pct_min,100-year,1pct_plu,500-year
River Rch & RM= UNT 096 IN CACR,Reach-1,24705
     829    1151    1424    1292    1747    2363    2637
River Rch & RM= UNT 096 IN CACR,Reach-1,17257
    1230    1742    2182    2002    2708    3662    4180
River Rch & RM= UNT 096 IN CACR,Reach-1,13955
    1290    1829    2293    2106    2848    3852    4404
River Rch & RM= UNT 096 IN CACR,Reach-1,13608
    1340    1902    2386    2192    2964    4009    4588
River Rch & RM= UNT 096 IN CACR,Reach-1,11060
    1956    2822    3577    3317    4485    6066    7073
River Rch & RM= UNT 096 IN CACR,Reach-1,6868
    1940    2782    3511    3240    4381    5925    6842
Boundary for River Rch & Prof#=UNT 096 IN CACR,Reach-1,1
Up Type=0
Dn Type=3
Dn Slope=0.005
Boundary for River Rch & Prof#=UNT 096 IN CACR,Reach-1,2
Up Type=0
Dn Type=3
Dn Slope=0.005
Boundary for River Rch & Prof#=UNT 096 IN CACR,Reach-1,3
Up Type=0
Dn Type=3
Dn Slope=0.005
Boundary for River Rch & Prof#=UNT 096 IN CACR,Reach-1,4
Up Type=0
Dn Type=3
Dn Slope=0.005
Boundary for River Rch & Prof#=UNT 096 IN CACR,Reach-1,5
Up Type=0
Dn Type=3
Dn Slope=0.005
Boundary for River Rch & Prof#=UNT 096 IN CACR,Reach-1,6
Up Type=0
Dn Type=3
Dn Slope=0.005
Boundary for River Rch & Prof#=UNT 096 IN CACR,Reach-1,7
Up Type=0
Dn Type=3
Dn Slope=0.005

--- UNT 096 IN CACR.g01 (geometry) ---

Geom Title=Existing Conditions

River Reach=UNT 096 IN CACR,Reach-1
Reach XY= 30
      3725049.94     10734542.76      3723392.71     10734757.30
      3722917.45     10734429.61      3721325.44     10734303.31
      3719610.16     10733594.97      3718626.75     10732777.00
      3717184.75     10732113.00      3716529.50     10731440.00
      3715397.50     10731486.00      3715185.50     10731357.00
      3714630.00     10731469.00      3714404.50     10731300.00
      3713496.75     10731306.00      3712847.25     10730777.00
      3712495.00     10729927.00      3711988.75     10729523.00
      3711441.25     10729408.00      3711116.25     10728818.00
      3710443.25     10728752.00      3710329.00     10728350.00
      3710177.75     10728272.00      3710091.50     10728389.00
      3709792.00     10727945.00      3709354.50     10727893.00
      3708884.50     10727610.00      3708585.00     10726985.00
      3708432.00     10726942.00      3708542.50     10726126.00
      3707590.00     10725799.00      3707339.75     10724961.00

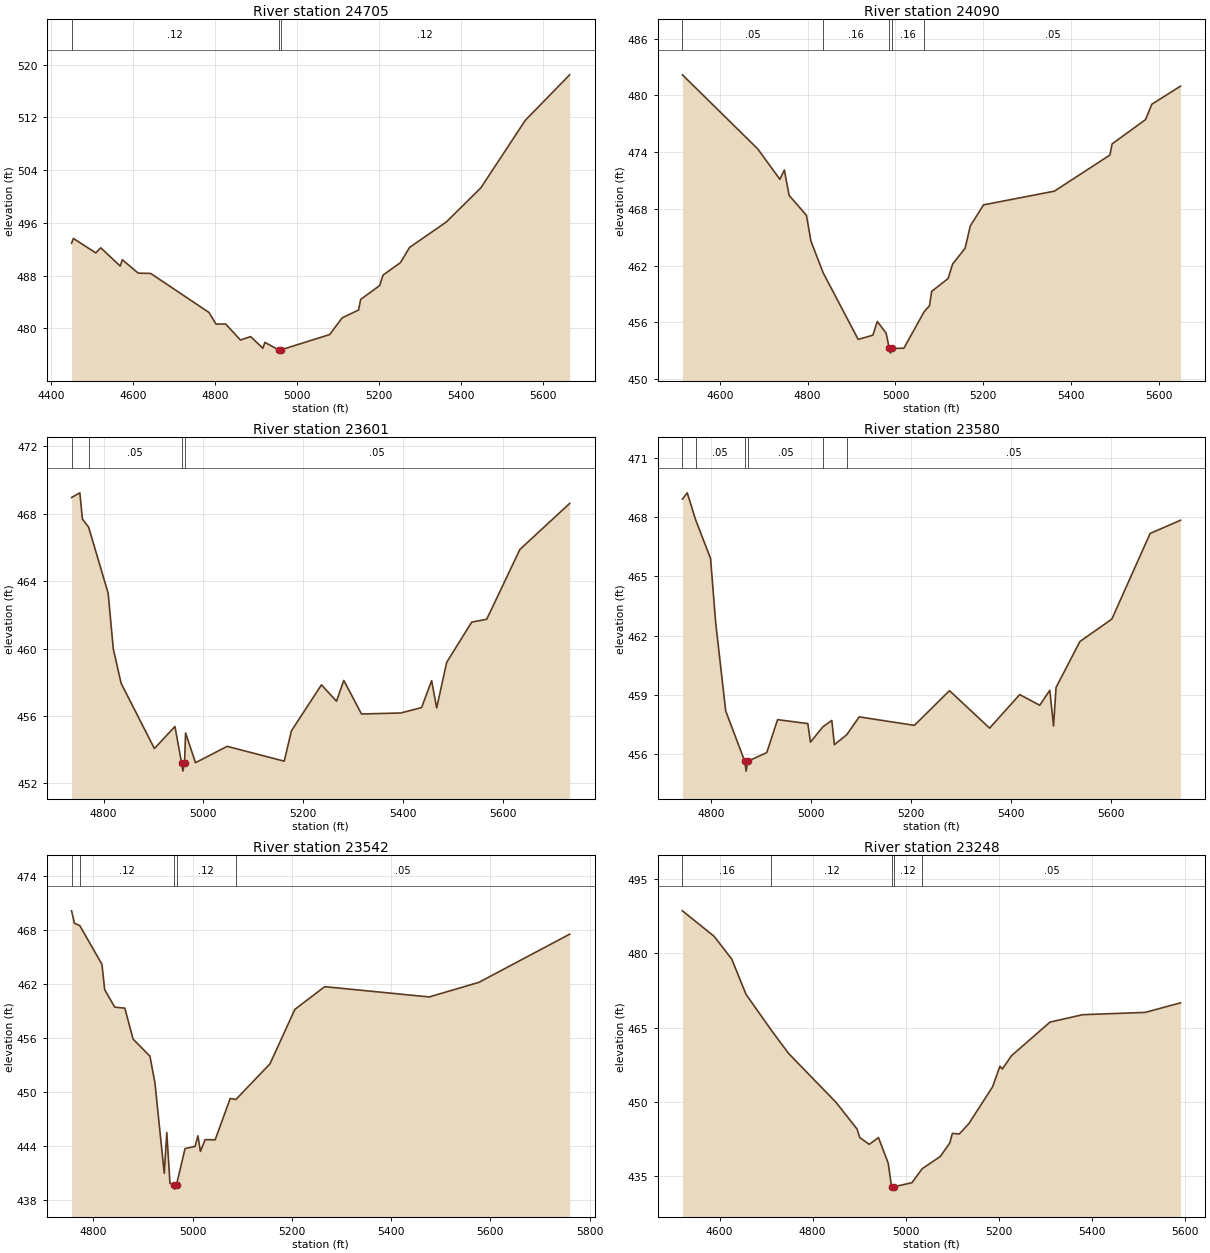
Type RM Length L Ch R = 1,24705,615,615,615
BEGIN DESCRIPTION:
UNT 096 IN CACR 36.0
END DESCRIPTION:
XS GIS Cut Line= 2
      3724713.94     10734030.08      3724922.03     10735226.62
#Sta/Elev= 30
  4449.5  492.90  4454.0  493.63  4508.6  491.44  4520.7  492.21  4568.2  489.44
  4573.3  490.40  4612.0  488.37  4642.5  488.32  4784.6  482.40  4801.7  480.64
  4825.2  480.65  4861.3  478.22  4886.1  478.74  4915.9  476.97  4920.9  477.86
  4954.1  476.73  4956.9  476.23  4960.1  476.73  5078.9  479.05  5109.4  481.59
  5149.3  482.77  5154.4  484.38  5200.7  486.48  5209.0  488.07  5251.5  489.97
  5273.7  492.27  5363.1  496.12  5447.5  501.31  5556.0  511.57  5664.0  518.46
#Mann=3,-1,0
  4449.5    0.12       0  4954.1    0.07       0  4960.1    0.12       0
Bank Sta=4954.1,4960.1
Exp/Cntr=0.3,0.1

Type RM Length L Ch R = 1,24090,489,489,489
BEGIN DESCRIPTION:
Mapping XS 79ae8fd6
END DESCRIPTION:
XS GIS Cut Line= 2
      3724145.37     10734090.05      3724284.26     10735215.00
#Sta/Elev= 30
  4515.2  482.18  4686.6  474.34  4737.0  471.12  4747.1  472.11  4758.0  469.42
  4797.5  467.31  4807.5  464.60  4835.5  461.23  4915.2  454.18  4948.6  454.63
  4958.7  456.08  4978.8  454.84  4985.9  453.23  4988.7  452.73  4991.9  453.23
  5019.1  453.25  5065.2  457.10  5077.4  457.75  5082.4  459.26  5119.9  460.63
  5130.0  462.15  5158.5  463.83  5170.3  466.19  5200.5  468.42  5361.7  469.87
  5488.0  473.69  5493.0  474.87  5569.1  477.44  5583.4  479.07  5648.7  480.98
#Mann=5,-1,0
  4515.2    0.05       0  4835.5    0.16       0  4985.9    0.07       0
  4991.9    0.16       0  5065.2    0.05       0
Bank Sta=4985.9,4991.9
Exp/Cntr=0.3,0.1

Type RM Length L Ch R = 1,23601,21,21,21
BEGIN DESCRIPTION:
Mapping XS 33e48ee5
END DESCRIPTION:
XS GIS Cut Line= 3
      3723788.59     10734399.08      3723714.82     10734696.35
      3723656.28     10735385.78
#Sta/Elev= 30
  4736.0  468.96  4752.6  469.24  4757.8  467.68  4770.1  467.21  4809.3  463.29
  4819.6  459.99  4835.3  457.94  4902.0  454.07  4943.2  455.38  4956.4  453.23
  4959.1  452.73  4962.4  453.23  4964.5  454.99  4984.4  453.23  5047.9  454.20
  5162.2  453.32  5176.6  455.12  5236.8  457.85  5266.9  456.88  5281.6  458.11
  5317.1  456.12  5395.9  456.18  5437.5  456.50  5457.6  458.10  5467.7  456.48
  5487.7  459.18  5537.9  461.57  5568.0  461.74  5634.5  465.88  5734.2  468.61
#Mann=4,-1,0
  4736.0    0.16       0  4770.1    0.05       0  4956.4   0.033       0
  4962.4    0.05       0
Bank Sta=4956.4,4962.4
Exp/Cntr=0.3,0.1

Type RM Length L Ch R = 1,23580,38,38,38
BEGIN DESCRIPTION:
Mapping XS c8223177
END DESCRIPTION:
XS GIS Cut Line= 4
      3723766.89     10734405.60      3723695.28     10734689.84
      3723690.94     10734731.08      3723632.35     10735390.80
#Sta/Elev= 30
  4742.5  468.92  4752.1  469.24  4769.1  467.86  4798.8  465.91  4809.1  462.65
  4829.1  458.18  4867.2  455.63  4870.0  455.13  4873.2  455.63  4911.3  456.07
  4932.9  457.74  4993.5  457.54  4998.7  456.60  5023.8  457.38  5041.5  457.70
  5046.6  456.47  5071.2  456.97  5096.3  457.88  5206.7  457.45  5277.0  459.21
  5357.3  457.31  5417.5  459.01  5457.7  458.47  5477.8  459.23  5485.3  457.42
  5490.3  459.37  5538.0  461.70  5602.0  462.84  5678.6  467.18  5739.4  467.85
#Mann=6,-1,0
  4742.5    0.16       0  4769.1    0.05       0  4867.2   0.033       0
  4873.2    0.05       0  5023.8    0.12       0  5071.2    0.05       0
Bank Sta=4867.2,4873.2
Exp/Cntr=0.3,0.1

Type RM Length L Ch R = 1,23542,294,294,294
BEGIN DESCRIPTION:
Mapping XS 1592664e
END DESCRIPTION:
XS GIS Cut Line= 3
      3723703.97     10734414.22      3723656.22     10734720.23
      3723606.31     10735412.52
#Sta/Elev= 30
  4756.0  470.12  4762.0  468.73  4772.5  468.49  4817.2  464.19  4822.8  461.37
  4843.0  459.44  4863.3  459.33  4880.0  455.90  4913.9  454.00  4924.0  451.06
  4942.8  441.01  4947.9  445.54  4954.3  439.91  4961.5  439.76  4964.2  439.26
  4967.5  439.76  4984.7  443.76  5004.9  444.00  5010.7  445.17  5015.7  443.44
  5025.2  444.75  5045.4  444.73  5075.7  449.31  5087.2  449.20  5155.9  453.16
  5206.0  459.19  5266.2  461.71  5476.7  460.57  5577.0  462.19  5759.8  467.53
#Mann=5,-1,0
  4756.0    0.16       0  4772.5    0.12       0  4961.5    0.07       0
  4967.5    0.12       0  5087.2    0.05       0
Bank Sta=4961.5,4967.5
Exp/Cntr=0.3,0.1

Type RM Length L Ch R = 1,23248,855,855,855
BEGIN DESCRIPTION:
Mapping XS f003a82c
END DESCRIPTION:
XS GIS Cut Line= 2
      3723487.38     10734286.24      3723279.36     10735336.74
#Sta/Elev= 30
  4520.1  488.51  4588.1  483.39  4626.1  478.79  4656.7  471.71  4711.1  464.47
  4748.4  459.77  4850.3  449.93  4895.5  444.56  4901.3  442.84  4921.7  441.46
  4941.6  442.83  4962.5  437.68  4969.7  432.94  4972.4  432.44  4975.7  432.94
  5013.5  433.73  5035.7  436.56  5074.6  439.02  5095.0  441.75  5100.4  443.67
  5115.4  443.55  5135.8  445.62  5186.8  453.03  5202.8  457.21  5207.9  456.64
  5227.5  459.31  5310.4  466.09  5380.4  467.58  5515.3  468.05  5591.0  469.97
#Mann=5,-1,0
  4520.1    0.16       0  4711.1    0.12       0  4969.7    0.07       0
  4975.7    0.12       0  5035.7    0.05       0
Bank Sta=4969.7,4975.7
Exp/Cntr=0.3,0.1

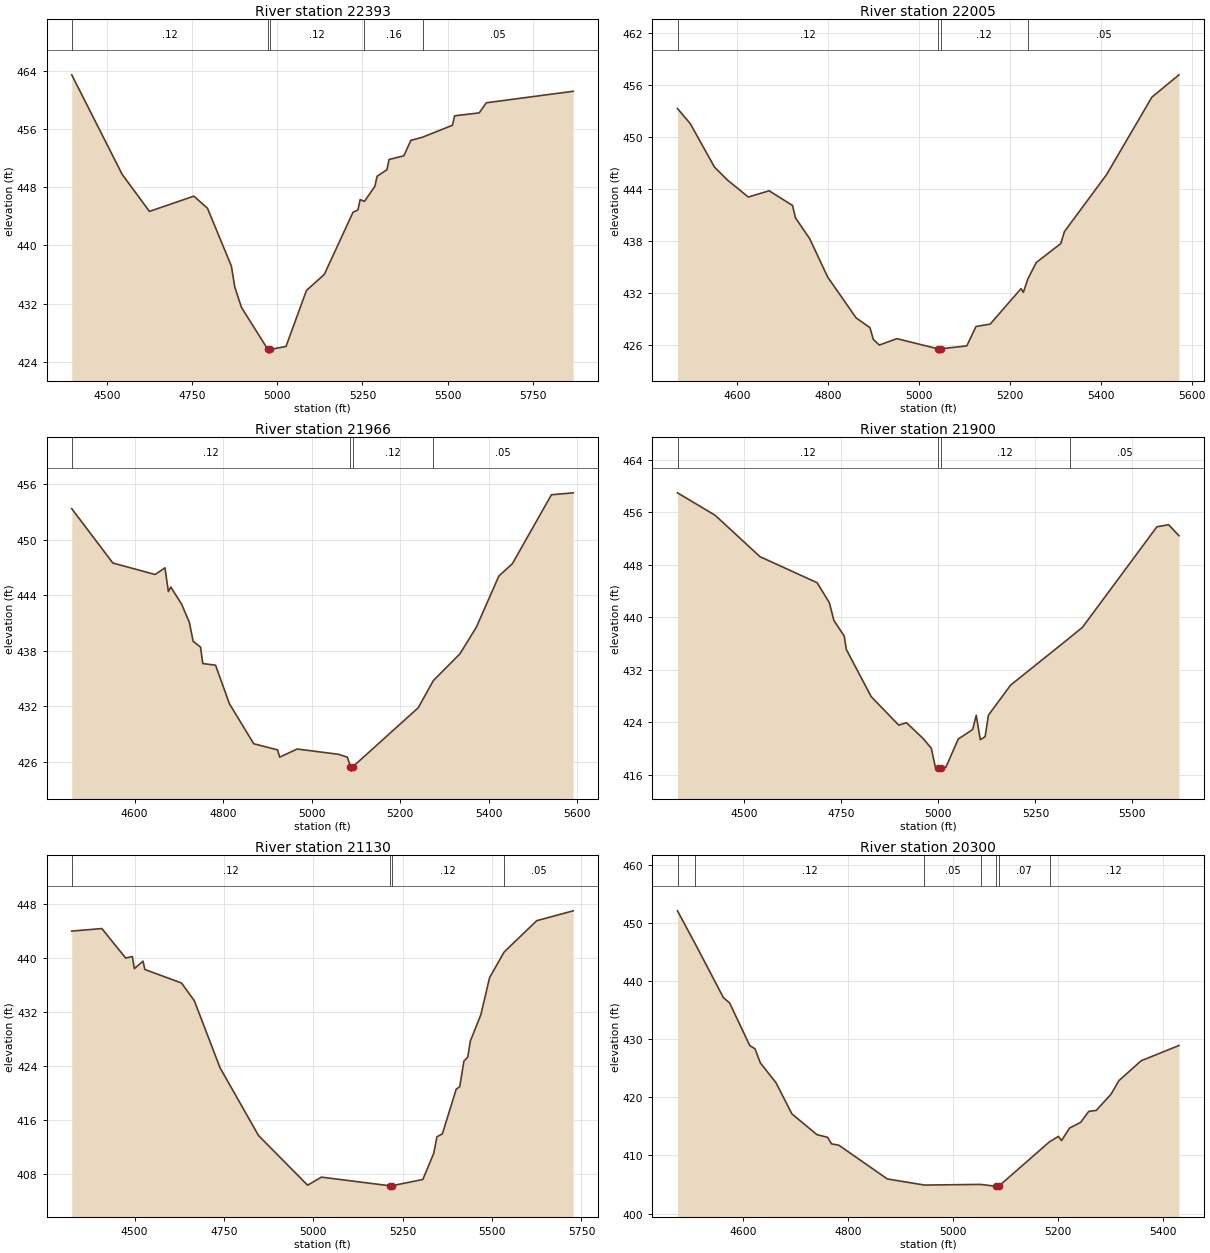
Type RM Length L Ch R = 1,22393,388,388,388
BEGIN DESCRIPTION:
Mapping XS 0ea648a9
END DESCRIPTION:
XS GIS Cut Line= 3
      3722622.80     10733822.64      3722669.68     10734562.24
      3723122.78     10735135.13
#Sta/Elev= 30
  4396.9  463.44  4544.7  449.78  4624.9  444.67  4755.2  446.77  4795.2  445.11
  4865.4  437.16  4875.4  434.27  4895.1  431.47  4972.6  425.70  4975.4  425.20
  4978.6  425.70  5025.7  426.12  5085.8  433.82  5138.0  436.01  5222.4  444.56
  5236.8  444.88  5243.2  446.29  5255.9  446.05  5286.5  448.12  5292.9  449.50
  5321.8  450.40  5328.1  451.81  5371.4  452.31  5392.2  454.44  5426.3  454.87
  5514.1  456.51  5520.5  457.81  5592.6  458.21  5613.5  459.60  5868.4  461.18
#Mann=5,-1,0
  4396.9    0.12       0  4972.6    0.07       0  4978.6    0.12       0
  5255.9    0.16       0  5426.3    0.05       0
Bank Sta=4972.6,4978.6
Exp/Cntr=0.3,0.1

Type RM Length L Ch R = 1,22005,39,39,39
BEGIN DESCRIPTION:
Mapping XS 63e7f357
END DESCRIPTION:
XS GIS Cut Line= 5
      3722440.36     10733904.65      3722328.40     10734146.80
      3722286.73     10734347.32      3722247.67     10734602.53
      3722338.80     10734964.47
#Sta/Elev= 30
  4469.1  453.27  4497.2  451.53  4550.5  446.52  4579.0  445.03  4624.8  443.07
  4670.7  443.79  4722.1  442.10  4728.6  440.67  4759.8  438.27  4799.6  433.83
  4861.9  429.14  4892.5  428.00  4899.8  426.65  4913.0  426.00  4951.7  426.74
  5041.7  425.57  5044.5  425.07  5047.7  425.57  5105.4  425.90  5125.7  428.14
  5157.0  428.42  5224.8  432.51  5229.9  432.08  5239.8  433.63  5258.3  435.52
  5312.1  437.70  5320.2  439.08  5413.0  445.66  5512.5  454.58  5572.1  457.16
#Mann=4,-1,0
  4469.1    0.12       0  5041.7    0.07       0  5047.7    0.12       0
  5239.8    0.05       0
Bank Sta=5041.7,5047.7
Exp/Cntr=0.3,0.1

Type RM Length L Ch R = 1,21966,66,66,66
BEGIN DESCRIPTION:
Mapping XS bb7b533f
END DESCRIPTION:
XS GIS Cut Line= 6
      3722393.48     10733873.40      3722299.75     10734118.15
      3722265.90     10734316.07      3722229.44     10734430.65
      3722219.02     10734693.67      3722273.72     10734974.96
#Sta/Elev= 30
  4457.8  453.34  4550.7  447.46  4646.1  446.22  4668.5  446.94  4676.1  444.37
  4681.5  444.87  4706.2  443.00  4723.5  441.05  4732.1  439.00  4748.8  438.37
  4753.9  436.59  4782.8  436.41  4814.0  432.25  4869.0  427.92  4922.8  427.26
  4927.6  426.47  4967.0  427.35  5060.5  426.78  5080.5  426.47  5087.5  425.46
  5090.2  424.96  5093.5  425.46  5240.6  431.81  5274.8  434.75  5334.8  437.64
  5371.9  440.52  5422.8  446.05  5453.4  447.39  5541.5  454.84  5590.7  455.05
#Mann=4,-1,0
  4457.8    0.12       0  5087.5    0.07       0  5093.5    0.12       0
  5274.8    0.05       0
Bank Sta=5087.5,5093.5
Exp/Cntr=0.3,0.1

Type RM Length L Ch R = 1,21900,770,770,770
BEGIN DESCRIPTION:
Mapping XS 60dbef06
END DESCRIPTION:
XS GIS Cut Line= 3
      3722387.17     10733727.92      3722138.29     10734498.36
      3722199.49     10734976.52
#Sta/Elev= 30
  4328.1  458.93  4425.1  455.51  4540.7  449.21  4687.8  445.25  4719.3  442.21
  4730.9  439.51  4757.7  437.12  4763.0  435.10  4827.0  427.92  4898.0  423.58
  4917.9  423.95  4961.0  421.53  4981.9  420.06  4992.5  417.16  5000.0  417.08
  5002.8  416.58  5006.0  417.08  5019.2  417.14  5051.2  421.45  5088.5  422.92
  5097.6  425.09  5108.1  421.36  5120.5  421.82  5129.1  425.10  5186.2  429.67
  5338.7  436.89  5371.5  438.48  5563.0  453.76  5593.2  454.08  5619.8  452.40
#Mann=4,-1,0
  4328.1    0.12       0  5000.0    0.07       0  5006.0    0.12       0
  5338.7    0.05       0
Bank Sta=5000,5006
Exp/Cntr=0.3,0.1

Type RM Length L Ch R = 1,21130,830,830,830
BEGIN DESCRIPTION:
Mapping XS 223b904c
END DESCRIPTION:
XS GIS Cut Line= 2
      3721689.27     10733701.84      3721168.43     10735003.93
#Sta/Elev= 30
  4324.4  444.01  4408.8  444.38  4475.2  440.01  4494.0  440.23  4499.4  438.44
  4523.7  439.55  4529.0  438.31  4631.4  436.31  4667.3  433.68  4739.1  423.75
  4846.8  413.70  4984.1  406.33  5022.7  407.53  5213.6  406.25  5216.3  405.75
  5219.6  406.25  5306.3  407.18  5336.8  411.05  5345.8  413.52  5361.0  413.94
  5399.7  420.57  5409.5  420.93  5421.2  424.72  5432.0  425.33  5439.1  427.69
  5468.7  431.63  5493.0  437.10  5533.5  440.89  5624.9  445.55  5726.8  447.01
#Mann=4,-1,0
  4324.4    0.12       0  5213.6    0.07       0  5219.6    0.12       0
  5533.5    0.05       0
Bank Sta=5213.6,5219.6
Exp/Cntr=0.3,0.1

Type RM Length L Ch R = 1,20300,86,86,86
BEGIN DESCRIPTION:
Mapping XS 4e0c1039
END DESCRIPTION:
XS GIS Cut Line= 5
      3720880.15     10733502.70      3720864.53     10733771.80
      3720706.54     10733950.62      3720678.77     10734122.49
      3720824.61     10734353.42
#Sta/Elev= 30
  4474.6  452.11  4507.9  446.51  4562.2  437.15  4573.8  436.27  4612.3  428.92
  4622.3  428.36  4632.4  425.94  4662.4  422.51  4692.5  417.17  4740.2  413.59
  4760.6  413.13  4768.1  412.00  4782.0  411.77  4874.4  405.96  4945.2  404.91
  5052.1  405.02  5080.6  404.71  5083.4  404.21  5086.6  404.71  5183.4  412.36
  5200.4  413.28  5206.3  412.57  5221.6  414.72  5242.8  415.71  5258.1  417.58
  5272.4  417.76  5300.4  420.52  5315.7  422.89  5358.1  426.31  5430.0  428.93
#Mann=7,-1,0
  4474.6    0.16       0  4507.9    0.12       0  4945.2    0.05       0
  5052.1    0.07       0  5080.6   0.033       0  5086.6    0.07       0
  5183.4    0.12       0
Bank Sta=5080.6,5086.6
Exp/Cntr=0.3,0.1

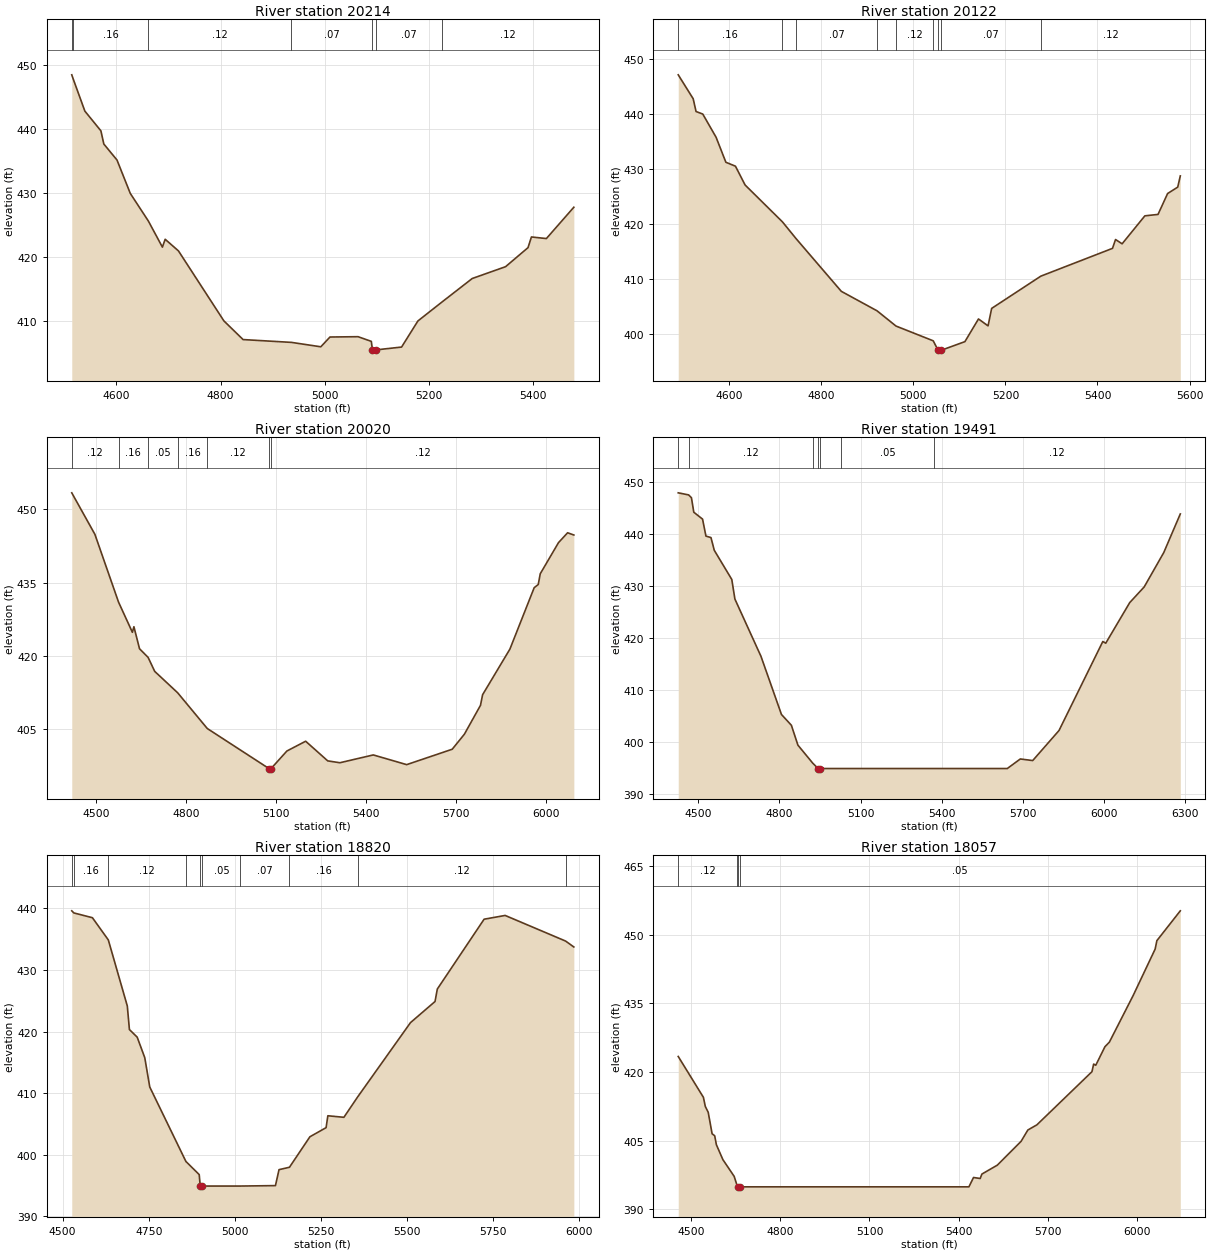
Type RM Length L Ch R = 1,20214,92,92,92
BEGIN DESCRIPTION:
Mapping XS 66f07254
END DESCRIPTION:
XS GIS Cut Line= 6
      3720833.28     10733532.21      3720725.64     10733834.30
      3720619.74     10733955.82      3720591.96     10734044.37
      3720623.21     10734152.01      3720796.80     10734367.26
#Sta/Elev= 30
  4514.3  448.48  4516.4  447.98  4539.4  442.81  4570.2  439.72  4575.8  437.66
  4601.1  435.15  4626.6  429.93  4661.2  425.62  4688.2  421.53  4693.5  422.76
  4719.0  420.94  4806.2  409.99  4843.0  407.07  4935.8  406.63  4992.1  405.94
  5009.7  407.47  5063.6  407.52  5089.0  406.79  5091.2  405.45  5093.9  404.95
  5097.2  405.45  5147.1  405.90  5178.4  409.98  5223.9  412.90  5282.6  416.62
  5346.6  418.47  5389.7  421.45  5396.2  423.12  5424.9  422.87  5477.6  427.77
#Mann=7,-1,0
  4514.3    0.05       0  4516.4    0.16       0  4661.2    0.12       0
  4935.8    0.07       0  5091.2    0.07       0  5097.2    0.07       0
  5223.9    0.12       0
Bank Sta=5091.2,5097.2
Exp/Cntr=0.3,0.1

Type RM Length L Ch R = 1,20122,102,102,102
BEGIN DESCRIPTION:
Mapping XS a1b1d9a8
END DESCRIPTION:
XS GIS Cut Line= 4
      3720817.50     10733533.97      3720533.22     10733920.23
      3720498.50     10734082.99      3720785.87     10734422.22
#Sta/Elev= 30
  4489.3  447.15  4521.8  442.79  4528.0  440.47  4542.6  440.01  4571.5  435.79
  4592.8  431.23  4613.6  430.52  4634.5  427.10  4715.7  420.38  4745.0  417.36
  4843.5  407.74  4921.2  404.19  4962.3  401.42  5043.2  398.73  5053.9  396.99
  5056.7  396.49  5059.9  396.99  5112.0  398.58  5141.5  402.71  5162.3  401.45
  5170.1  404.63  5276.9  410.50  5432.6  415.56  5439.2  417.17  5453.5  416.39
  5502.9  421.48  5531.5  421.74  5552.3  425.54  5574.3  426.71  5579.9  428.75
#Mann=9,-1,0
  4489.3    0.16       0  4715.7    0.12       0  4745.0    0.07       0
  4921.2    0.16       0  4962.3    0.12       0  5043.2    0.07       0
  5053.9    0.07       0  5059.9    0.07       0  5276.9    0.12       0
Bank Sta=5053.9,5059.9
Exp/Cntr=0.3,0.1

Type RM Length L Ch R = 1,20020,529,529,529
BEGIN DESCRIPTION:
Mapping XS e3972ead
END DESCRIPTION:
XS GIS Cut Line= 2
      3720516.30     10733367.06      3720255.87     10735020.78
#Sta/Elev= 30
  4419.0  453.40  4496.1  444.89  4574.9  431.00  4621.1  424.80  4626.2  425.94
  4644.9  421.43  4673.6  419.65  4695.5  416.79  4772.2  412.39  4870.8  405.07
  5077.2  396.83  5079.9  396.33  5083.2  396.83  5136.4  400.46  5198.9  402.46
  5272.5  398.43  5313.0  398.05  5424.4  399.65  5535.7  397.66  5687.6  400.82
  5728.1  403.90  5781.8  409.82  5788.8  411.99  5879.9  421.35  5960.9  433.95
  5974.4  434.60  5981.1  436.80  6041.9  443.18  6072.3  445.21  6093.1  444.75
#Mann=7,-1,0
  4419.0    0.12       0  4574.9    0.16       0  4673.6    0.05       0
  4772.2    0.16       0  4870.8    0.12       0  5077.2    0.07       0
  5083.2    0.12       0
Bank Sta=5077.2,5083.2
Exp/Cntr=0.3,0.1

Type RM Length L Ch R = 1,19491,671,671,671
BEGIN DESCRIPTION:
Mapping XS 7fd0bd8b
END DESCRIPTION:
XS GIS Cut Line= 2
      3720151.71     10733236.90      3719453.02     10734955.40
#Sta/Elev= 30
  4425.9  447.96  4464.2  447.56  4474.7  447.02  4483.4  444.23  4515.8  442.90
  4528.2  439.64  4546.9  439.35  4559.0  436.91  4623.8  431.29  4635.3  427.52
  4731.6  416.51  4807.3  405.32  4844.0  403.24  4868.1  399.42  4922.3  395.99
  4942.7  394.92  4945.5  394.42  4948.7  394.92  5026.5  394.92  5372.4  394.92
  5641.7  394.92  5689.9  396.76  5735.6  396.45  5832.8  402.23  5994.7  419.36
  6005.5  419.03  6094.1  426.84  6147.6  429.86  6219.8  436.46  6281.0  443.90
#Mann=7,-1,0
  4425.9    0.05       0  4464.2    0.12       0  4922.3    0.07       0
  4942.7    0.07       0  4948.7    0.07       0  5026.5    0.05       0
  5372.4    0.12       0
Bank Sta=4942.7,4948.7
Exp/Cntr=0.3,0.1

Type RM Length L Ch R = 1,18820,763,763,763
BEGIN DESCRIPTION:
Mapping XS ab55a54d
END DESCRIPTION:
XS GIS Cut Line= 3
      3719795.80     10733102.35      3719301.01     10733445.23
      3719140.62     10734286.19
#Sta/Elev= 30
  4526.5  439.60  4532.5  439.26  4586.5  438.48  4632.6  434.88  4687.8  424.15
  4693.9  420.33  4716.5  419.09  4738.5  415.76  4753.0  411.00  4858.0  398.91
  4896.6  396.78  4899.6  394.92  4902.4  394.42  4905.6  394.92  5016.5  394.92
  5118.0  394.99  5128.4  397.58  5158.7  397.97  5218.1  402.92  5265.1  404.40
  5270.2  406.33  5316.8  406.08  5356.8  409.39  5510.2  421.45  5581.5  424.88
  5588.1  426.90  5724.0  438.24  5785.1  438.85  5960.7  434.69  5984.6  433.73
#Mann=10,-1,0
  4526.5    0.12       0  4532.5    0.16       0  4632.6    0.12       0
  4858.0    0.05       0  4899.6   0.033       0  4905.6    0.05       0
  5016.5    0.07       0  5158.7    0.16       0  5356.8    0.12       0
  5960.7    0.16       0
Bank Sta=4899.6,4905.6
Exp/Cntr=0.3,0.1

Type RM Length L Ch R = 1,18057,800,800,800
BEGIN DESCRIPTION:
Mapping XS cae77b51
END DESCRIPTION:
XS GIS Cut Line= 2
      3719044.92     10732490.39      3718233.95     10733969.22
#Sta/Elev= 30
  4457.7  423.38  4542.3  414.46  4548.7  412.46  4558.4  411.20  4571.5  406.50
  4580.2  406.07  4585.9  404.11  4607.7  400.86  4645.6  397.21  4654.4  395.41
  4658.7  394.92  4661.4  394.42  4664.7  394.92  5434.2  394.92  5449.7  396.96
  5472.1  396.74  5477.8  397.71  5529.5  399.65  5609.4  404.85  5632.2  407.33
  5662.6  408.46  5847.5  420.06  5853.2  421.72  5860.3  421.47  5891.1  425.51
  5905.9  426.50  5985.7  436.66  6059.8  446.83  6065.6  448.67  6144.3  455.18
#Mann=4,-1,0
  4457.7    0.12       0  4654.4    0.05       0  4658.7   0.033       0
  4664.7    0.05       0
Bank Sta=4658.7,4664.7
Exp/Cntr=0.3,0.1

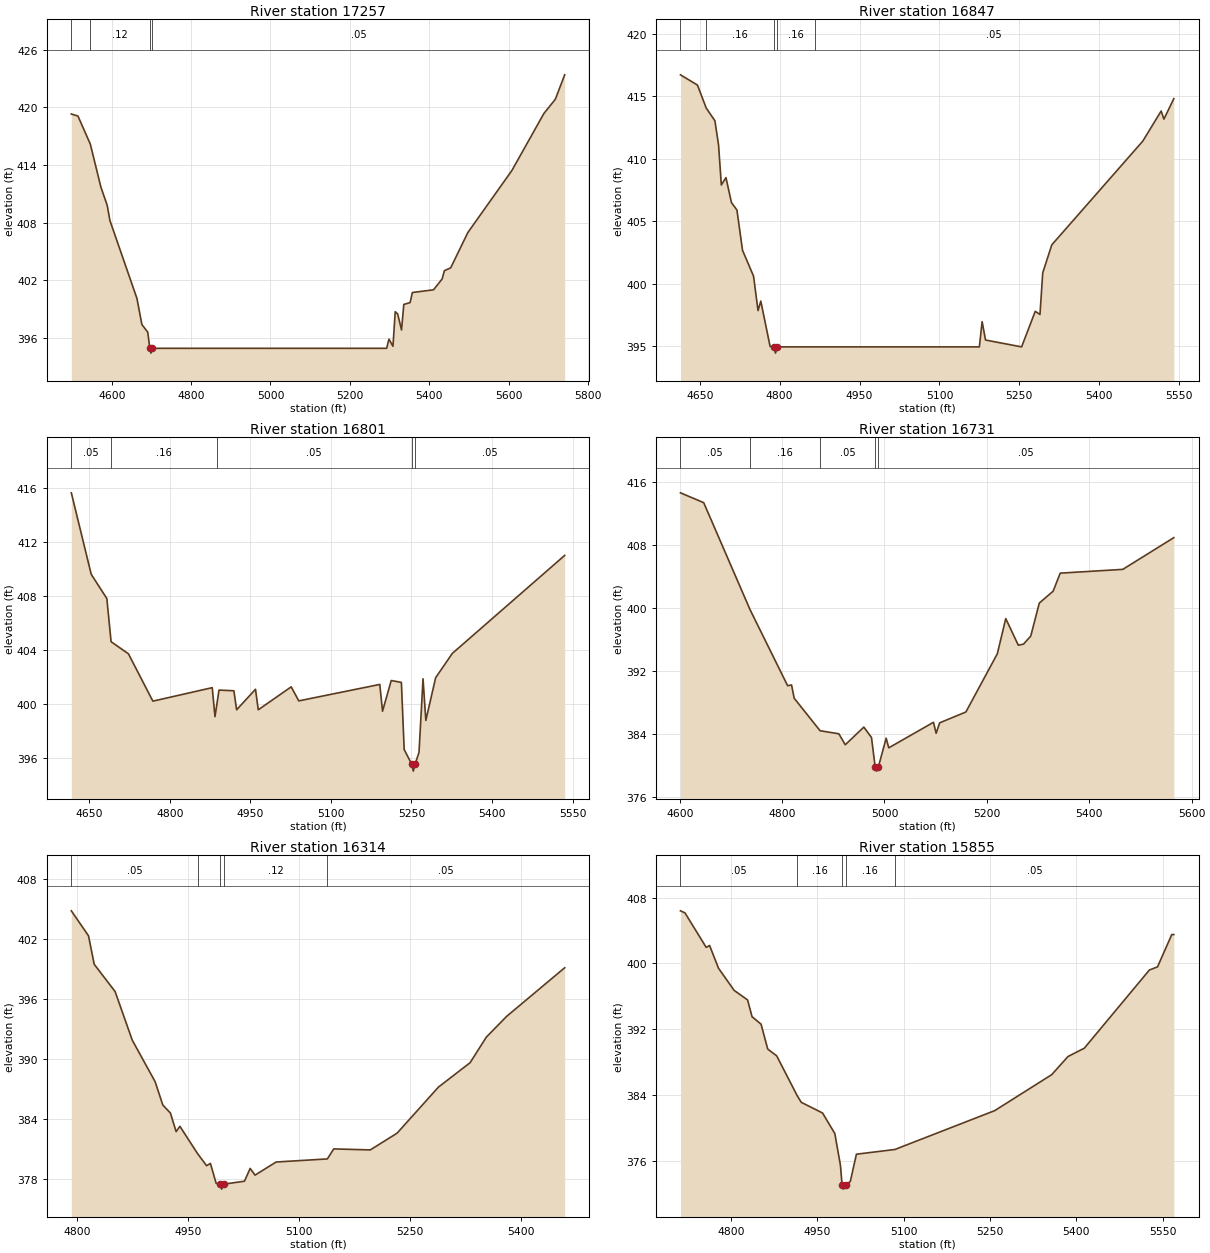
Type RM Length L Ch R = 1,17257,410,410,410
BEGIN DESCRIPTION:
UNT 096 IN CACR 35.0
END DESCRIPTION:
XS GIS Cut Line= 2
      3718398.82     10732085.72      3717782.85     10733165.83
#Sta/Elev= 30
  4498.2  419.31  4514.9  419.10  4546.1  416.17  4572.7  411.70  4588.6  409.81
  4595.4  408.23  4663.5  400.12  4676.0  397.40  4690.8  396.60  4696.0  394.92
  4698.8  394.42  4702.0  394.92  5292.9  394.92  5298.7  395.88  5308.8  395.13
  5314.5  398.73  5320.7  398.49  5330.4  396.83  5336.1  399.49  5352.0  399.68
  5357.7  400.73  5411.0  401.01  5432.7  402.14  5438.4  403.00  5454.3  403.30
  5497.5  406.97  5608.5  413.43  5689.1  419.36  5717.9  420.84  5741.6  423.39
#Mann=4,-1,0
  4498.2    0.05       0  4546.1    0.12       0  4696.0   0.033       0
  4702.0    0.05       0
Bank Sta=4696,4702
Exp/Cntr=0.3,0.1

Type RM Length L Ch R = 1,16847,46,46,46
BEGIN DESCRIPTION:
Mapping XS 3d279420
END DESCRIPTION:
XS GIS Cut Line= 2
      3717853.96     10732077.85      3717609.16     10732971.12
#Sta/Elev= 30
  4613.8  416.73  4645.7  415.91  4662.1  414.07  4678.4  413.05  4685.3  411.11
  4690.5  407.90  4699.2  408.49  4709.5  406.49  4719.8  405.89  4730.3  402.66
  4751.0  400.59  4759.4  397.83  4764.6  398.59  4782.1  394.95  4789.5  394.92
  4792.2  394.42  4795.5  394.92  4865.5  394.92  5174.9  394.92  5180.1  396.94
  5186.5  395.47  5254.2  394.92  5279.8  397.77  5288.7  397.52  5293.9  400.86
  5310.9  403.10  5481.8  411.42  5516.2  413.83  5521.4  413.18  5540.0  414.82
#Mann=5,-1,0
  4613.8    0.05       0  4662.1    0.16       0  4789.5    0.03       0
  4795.5    0.16       0  4865.5    0.05       0
Bank Sta=4789.5,4795.5
Exp/Cntr=0.3,0.1

Type RM Length L Ch R = 1,16801,70,70,70
BEGIN DESCRIPTION:
Mapping XS b0b5a7a6
END DESCRIPTION:
XS GIS Cut Line= 2
      3717812.29     10732054.44      3717577.92     10732942.43
#Sta/Elev= 30
  4616.9  415.65  4653.9  409.61  4683.0  407.81  4690.9  404.61  4723.2  403.71
  4768.7  400.20  4879.2  401.20  4884.3  399.05  4887.4  399.86  4891.8  401.02
  4919.5  400.97  4924.6  399.56  4959.7  401.08  4964.9  399.56  5026.2  401.26
  5040.3  400.22  5191.1  401.44  5196.2  399.45  5212.4  401.73  5231.3  401.59
  5236.5  396.61  5250.7  395.51  5253.5  395.01  5256.7  395.51  5264.1  396.40
  5271.6  401.86  5276.8  398.77  5295.1  401.94  5326.1  403.74  5535.3  411.01
#Mann=5,-1,0
  4616.9    0.05       0  4690.9    0.16       0  4887.4    0.05       0
  5250.7    0.03       0  5256.7    0.05       0
Bank Sta=5250.7,5256.7
Exp/Cntr=0.3,0.1

Type RM Length L Ch R = 1,16731,417,417,417
BEGIN DESCRIPTION:
UNT 096 IN CACR 34.0
END DESCRIPTION:
XS GIS Cut Line= 2
      3717741.98     10731995.83      3717534.02     10732936.83
#Sta/Elev= 30
  4601.5  414.61  4646.9  413.36  4737.5  399.76  4810.8  390.12  4818.5  390.21
  4823.6  388.53  4874.2  384.40  4910.9  384.01  4923.4  382.62  4959.7  384.86
  4974.6  383.54  4981.9  379.77  4984.6  379.27  4987.9  379.77  5003.3  383.45
  5008.4  382.23  5095.7  385.47  5100.9  384.08  5107.8  385.40  5159.0  386.78
  5220.4  394.17  5236.9  398.64  5261.4  395.26  5271.6  395.40  5285.7  396.42
  5302.4  400.61  5329.4  402.12  5343.3  404.41  5465.5  404.89  5565.2  408.92
#Mann=5,-1,0
  4601.5    0.05       0  4737.5    0.16       0  4874.2    0.05       0
  4981.9    0.03       0  4987.9    0.05       0
Bank Sta=4981.9,4987.9
Exp/Cntr=0.3,0.1

Type RM Length L Ch R = 1,16314,459,459,459
BEGIN DESCRIPTION:
UNT 096 IN CACR 33.0
END DESCRIPTION:
XS GIS Cut Line= 3
      3717399.60     10731960.23      3717349.61     10732160.19
      3717049.60     10732510.19
#Sta/Elev= 30
  4792.3  404.83  4815.5  402.34  4823.2  399.49  4851.5  396.76  4874.7  391.90
  4905.6  387.75  4916.0  385.42  4926.3  384.61  4934.0  382.76  4939.1  383.29
  4962.9  380.57  4975.2  379.35  4980.4  379.58  4988.1  377.59  4992.8  377.51
  4995.6  377.01  4998.8  377.51  5026.4  377.80  5034.1  379.08  5040.7  378.41
  5069.2  379.72  5138.5  380.03  5147.1  381.03  5196.5  380.93  5232.7  382.60
  5288.7  387.21  5331.5  389.65  5353.5  392.21  5380.9  394.28  5459.4  399.14
#Mann=5,-1,0
  4792.3    0.05       0  4962.9    0.12       0  4992.8    0.07       0
  4998.8    0.12       0  5138.5    0.05       0
Bank Sta=4992.8,4998.8
Exp/Cntr=0.3,0.1

Type RM Length L Ch R = 1,15855,451,451,451
BEGIN DESCRIPTION:
UNT 096 IN CACR 32.0
END DESCRIPTION:
XS GIS Cut Line= 3
      3717249.63     10731760.18      3716999.61     10731910.19
      3716599.58     10732310.22
#Sta/Elev= 30
  4712.0  406.41  4719.8  406.16  4756.7  401.96  4762.6  402.19  4778.1  399.42
  4805.3  396.72  4828.6  395.56  4836.4  393.52  4852.0  392.61  4863.6  389.58
  4879.2  388.75  4914.5  383.94  4921.9  383.09  4958.9  381.79  4980.2  379.29
  4990.0  375.41  4992.8  373.02  4995.5  372.52  4998.8  373.02  5007.1  373.45
  5017.7  376.77  5084.7  377.35  5258.1  382.08  5357.1  386.46  5385.4  388.67
  5413.7  389.68  5526.8  399.20  5541.0  399.59  5565.7  403.52  5569.3  403.52
#Mann=5,-1,0
  4712.0    0.05       0  4914.5    0.16       0  4992.8    0.07       0
  4998.8    0.16       0  5084.7    0.05       0
Bank Sta=4992.8,4998.8
Exp/Cntr=0.3,0.1

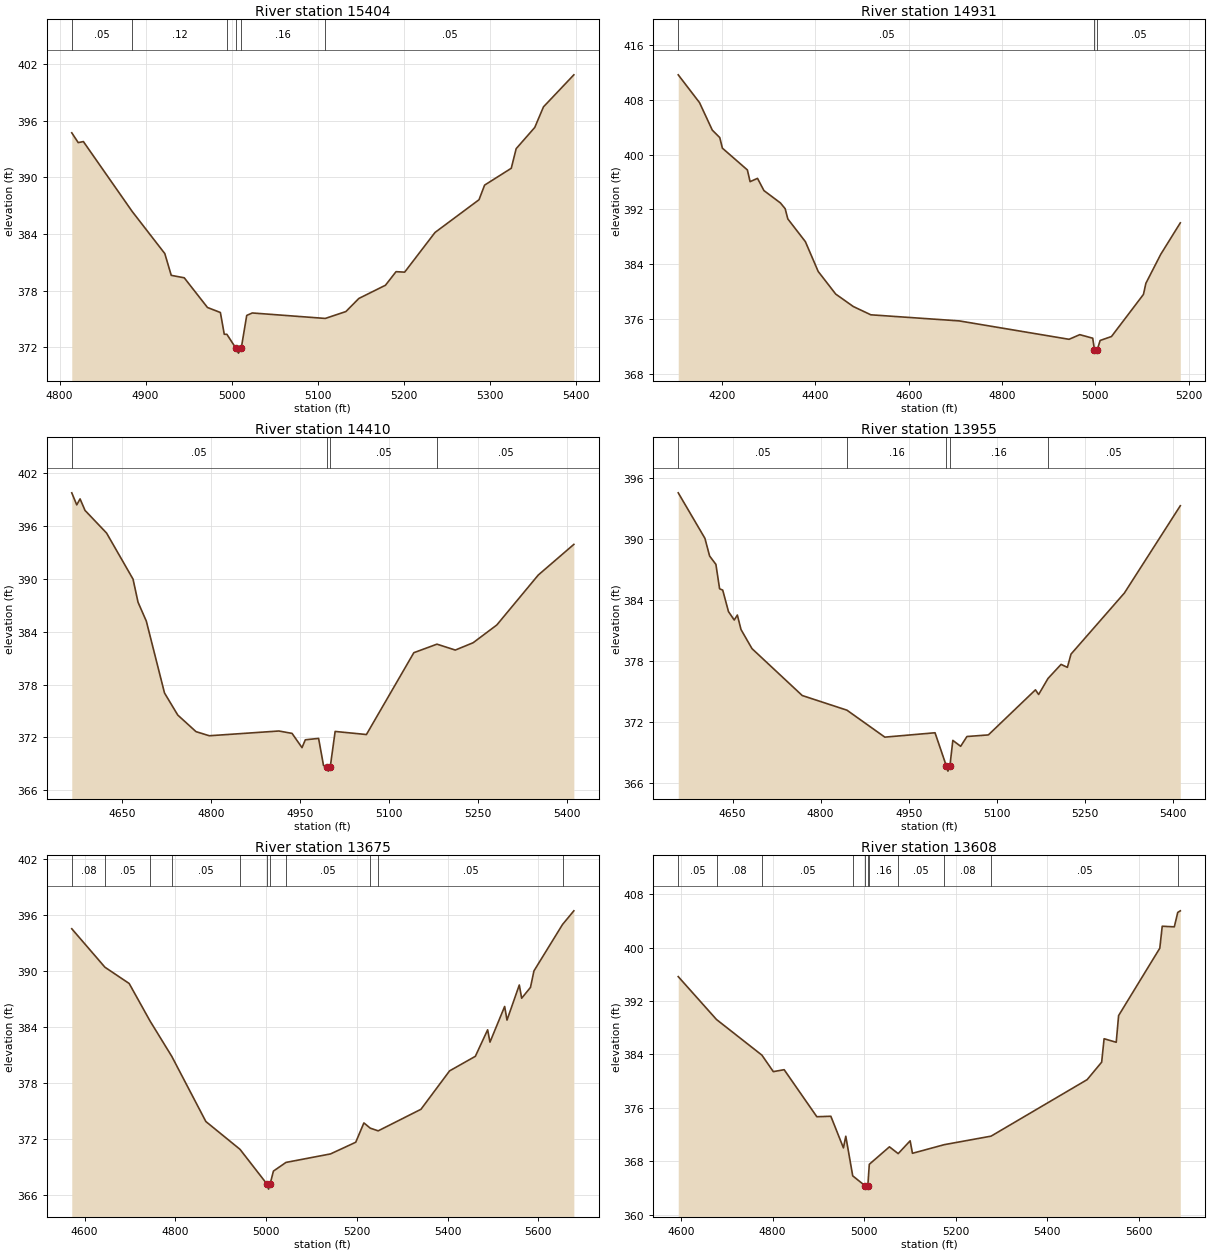
Type RM Length L Ch R = 1,15404,473,473,473
BEGIN DESCRIPTION:
UNT 096 IN CACR 31.0
END DESCRIPTION:
XS GIS Cut Line= 3
      3716849.58     10731510.21      3716699.61     10731610.19
      3716349.57     10731810.21
#Sta/Elev= 30
  4814.2  394.73  4821.7  393.69  4827.7  393.80  4884.3  386.40  4922.3  381.92
  4929.8  379.61  4944.9  379.35  4971.9  376.20  4986.9  375.67  4991.4  373.36
  4994.4  373.36  5005.1  371.86  5007.9  371.36  5011.1  371.86  5017.5  375.36
  5024.0  375.62  5108.8  375.04  5132.7  375.77  5147.8  377.16  5178.7  378.56
  5191.0  380.00  5201.0  379.95  5236.3  384.16  5287.4  387.63  5293.9  389.18
  5324.9  390.97  5330.6  393.05  5352.2  395.30  5362.3  397.48  5397.6  400.88
#Mann=6,-1,0
  4814.2    0.05       0  4884.3    0.12       0  4994.4    0.16       0
  5005.1    0.07       0  5011.1    0.16       0  5108.8    0.05       0
Bank Sta=5005.1,5011.1
Exp/Cntr=0.3,0.1

Type RM Length L Ch R = 1,14931,521,521,521
BEGIN DESCRIPTION:
UNT 096 IN CACR 30.0
END DESCRIPTION:
XS GIS Cut Line= 3
      3715899.59     10730710.16      3716349.61     10731510.19
      3716299.62     10731660.16
#Sta/Elev= 30
  4106.1  411.65  4151.7  407.59  4179.1  403.57  4195.1  402.48  4200.8  400.93
  4254.3  397.75  4260.1  396.04  4276.0  396.52  4289.7  394.74  4325.1  392.93
  4335.3  392.08  4341.0  390.59  4378.6  387.27  4406.0  382.92  4443.6  379.61
  4481.3  377.79  4518.9  376.58  4708.2  375.69  4943.7  373.00  4966.6  373.68
  4994.4  373.16  4998.1  371.48  5000.8  370.98  5004.1  371.48  5010.3  372.83
  5034.6  373.41  5103.1  379.56  5108.3  381.18  5140.0  385.40  5182.1  390.02
#Mann=3,-1,0
  4106.1    0.05       0  4998.1    0.03       0  5004.1    0.05       0
Bank Sta=4998.1,5004.1
Exp/Cntr=0.3,0.1

Type RM Length L Ch R = 1,14410,455,455,455
BEGIN DESCRIPTION:
UNT 096 IN CACR 29.0
END DESCRIPTION:
XS GIS Cut Line= 3
      3715699.61     10731010.20      3715899.61     10731410.19
      3715899.61     10731810.18
#Sta/Elev= 30
  4564.6  399.80  4573.0  398.43  4578.6  399.11  4587.0  397.80  4623.3  395.23
  4668.0  389.99  4676.4  387.37  4690.4  385.22  4721.1  377.05  4743.5  374.54
  4774.2  372.66  4796.6  372.19  4914.0  372.73  4936.3  372.46  4953.1  370.84
  4958.7  371.73  4981.1  371.89  4989.4  368.81  4994.8  368.67  4997.6  368.17
  5000.8  368.67  5009.0  372.68  5061.8  372.33  5141.8  381.63  5180.8  382.60
  5211.8  381.93  5241.8  382.76  5281.8  384.78  5351.8  390.46  5411.8  393.94
#Mann=4,-1,0
  4564.6    0.05       0  4994.8    0.07       0  5000.8    0.05       0
  5180.8    0.05       0
Bank Sta=4994.8,5000.8
Exp/Cntr=0.3,0.1

Type RM Length L Ch R = 1,13955,280,280,280
BEGIN DESCRIPTION:
UNT 096 IN CACR 28.0
END DESCRIPTION:
XS GIS Cut Line= 3
      3715649.62     10731060.15      3715499.61     10731460.19
      3715649.59     10731860.15
#Sta/Elev= 30
  4557.6  394.52  4603.0  390.05  4611.0  388.31  4621.7  387.49  4628.0  385.09
  4633.3  384.96  4643.1  382.85  4652.9  382.02  4658.2  382.51  4664.4  381.09
  4683.1  379.21  4768.6  374.60  4844.7  373.16  4909.2  370.51  4994.6  370.94
  5013.9  367.67  5016.6  367.17  5019.9  367.67  5024.9  370.19  5038.2  369.61
  5048.9  370.57  5085.4  370.73  5165.5  375.16  5170.9  374.70  5186.9  376.28
  5209.1  377.66  5219.8  377.37  5226.0  378.67  5316.8  384.67  5412.0  393.25
#Mann=5,-1,0
  4557.6    0.05       0  4844.7    0.16       0  5013.9    0.07       0
  5019.9    0.16       0  5186.9    0.05       0
Bank Sta=5013.9,5019.9
Exp/Cntr=0.3,0.1

Type RM Length L Ch R = 1,13675,67,67,67
BEGIN DESCRIPTION:
Mapping XS 031efff4
END DESCRIPTION:
XS GIS Cut Line= 4
      3715363.07     10730996.21      3715287.55     10731371.24
      3715251.09     10731485.82      3715068.80     10732061.34
#Sta/Elev= 30
  4571.6  394.55  4644.7  390.43  4698.1  388.69  4743.9  384.69  4792.2  380.87
  4867.1  373.91  4942.4  370.93  5002.5  367.17  5005.3  366.67  5008.5  367.17
  5016.0  368.60  5043.7  369.53  5141.9  370.44  5197.4  371.69  5215.4  373.76
  5229.4  373.20  5246.9  372.91  5341.2  375.22  5404.2  379.33  5461.0  380.89
  5488.1  383.73  5493.3  382.41  5525.6  386.23  5530.8  384.77  5557.9  388.53
  5563.1  387.11  5582.5  388.27  5590.2  390.04  5653.2  395.01  5678.1  396.47
#Mann=11,-1,0
  4571.6    0.08       0  4644.7    0.05       0  4743.9    0.16       0
  4792.2    0.05       0  4942.4    0.08       0  5002.5    0.07       0
  5008.5    0.08       0  5043.7    0.05       0  5229.4    0.08       0
  5246.9    0.05       0  5653.2    0.08       0
Bank Sta=5002.5,5008.5
Exp/Cntr=0.3,0.1

Type RM Length L Ch R = 1,13608,356,356,356
BEGIN DESCRIPTION:
UNT 096 IN CACR 27.0
END DESCRIPTION:
XS GIS Cut Line= 4
      3715295.37     10730983.17      3715227.65     10731324.37
      3715193.80     10731488.43      3715011.49     10732040.54
#Sta/Elev= 30
  4594.0  395.67  4677.6  389.24  4776.8  383.90  4801.7  381.43  4825.4  381.72
  4896.8  374.67  4927.4  374.74  4954.9  370.00  4960.0  371.75  4975.2  365.81
  5002.2  364.32  5004.9  363.82  5008.2  364.32  5011.4  367.54  5055.4  370.16
  5074.5  369.14  5100.6  371.06  5105.7  369.19  5175.5  370.49  5277.4  371.76
  5487.3  380.23  5519.0  382.85  5524.3  386.36  5550.8  385.83  5556.0  389.83
  5646.0  399.93  5651.3  403.22  5677.7  403.13  5685.2  405.29  5690.8  405.53
#Mann=11,-1,0
  4594.0    0.05       0  4677.6    0.08       0  4776.8    0.05       0
  4975.2    0.08       0  5002.2    0.07       0  5008.2    0.08       0
  5011.4    0.16       0  5074.5    0.05       0  5175.5    0.08       0
  5277.4    0.05       0  5685.2    0.08       0
Bank Sta=5002.2,5008.2
Exp/Cntr=0.3,0.1