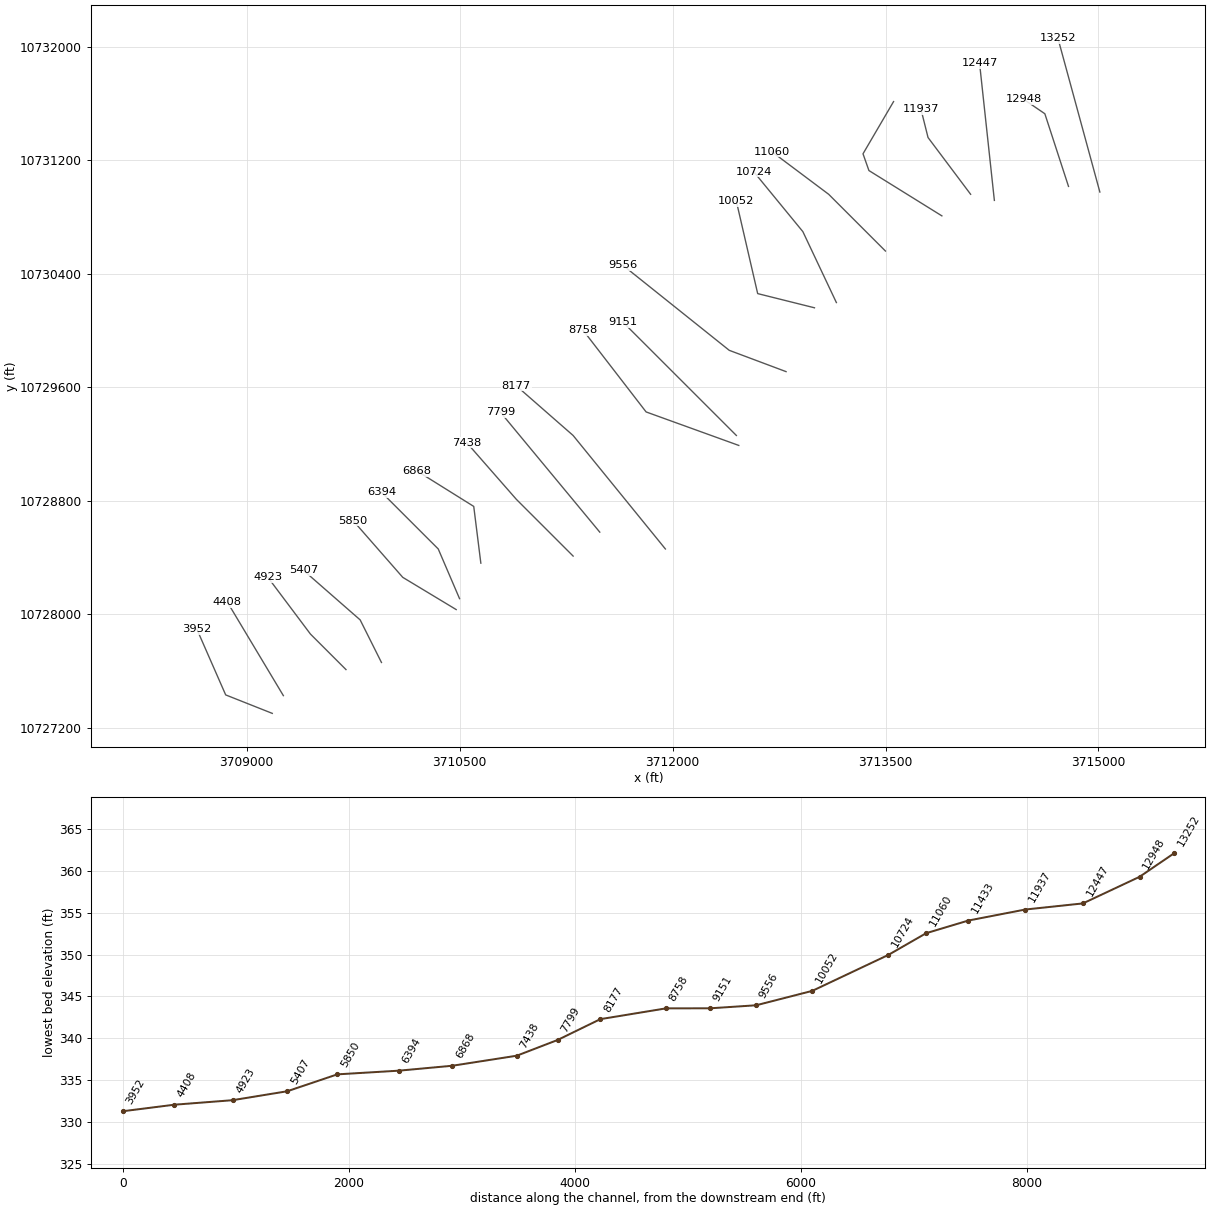
HEC-RAS study UNT 096 IN CACR.prj: UNT 096 IN CACR Base Level Engineering

--- UNT 096 IN CACR.g01 (geometry) --- (continued)

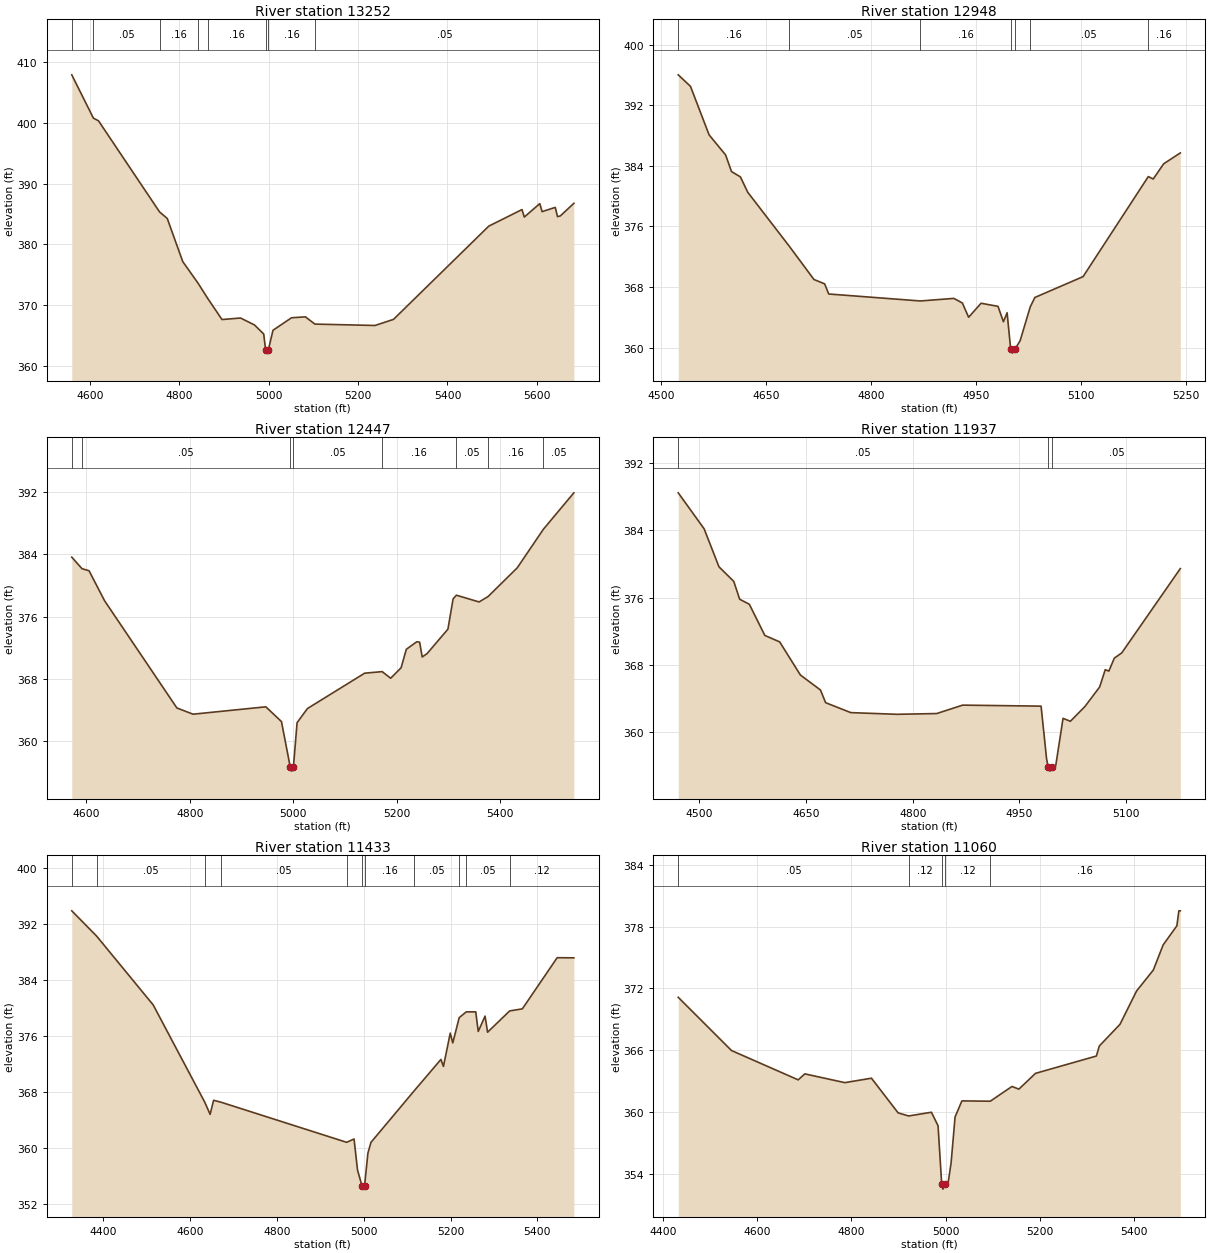
Type RM Length L Ch R = 1,13252,304,304,304
BEGIN DESCRIPTION:
Mapping XS 74bce452
END DESCRIPTION:
XS GIS Cut Line= 2
      3715009.92     10730975.97      3714714.76     10732059.38
#Sta/Elev= 30
  4559.8  407.90  4608.2  400.77  4619.6  400.33  4756.1  385.34  4773.4  384.25
  4808.0  377.16  4841.7  373.66  4864.0  371.08  4895.8  367.62  4937.3  367.87
  4968.4  366.73  4989.1  365.24  4993.4  362.59  4996.1  362.09  4999.4  362.59
  5009.8  365.85  5051.3  367.91  5082.4  368.06  5103.5  366.87  5237.9  366.64
  5279.3  367.64  5492.4  382.99  5566.7  385.72  5571.9  384.49  5606.5  386.70
  5611.7  385.38  5641.1  386.08  5646.2  384.56  5652.4  384.67  5682.7  386.75
#Mann=8,-1,0
  4559.8    0.16       0  4608.2    0.05       0  4756.1    0.16       0
  4841.7    0.05       0  4864.0    0.16       0  4993.4    0.07       0
  4999.4    0.16       0  5103.5    0.05       0
Bank Sta=4993.4,4999.4
Exp/Cntr=0.3,0.1

Type RM Length L Ch R = 1,12948,501,501,501
BEGIN DESCRIPTION:
UNT 096 IN CACR 26.0
END DESCRIPTION:
XS GIS Cut Line= 3
      3714789.10     10731015.77      3714622.44     10731527.88
      3714474.87     10731628.58
#Sta/Elev= 30
  4524.8  396.00  4542.3  394.48  4568.9  388.08  4592.5  385.43  4600.9  383.24
  4613.6  382.54  4624.1  380.51  4683.7  373.36  4718.7  369.00  4733.9  368.43
  4739.8  367.09  4870.7  366.17  4918.5  366.51  4930.7  365.90  4939.6  364.02
  4957.4  365.87  4981.6  365.46  4989.3  363.43  4994.6  364.61  4999.7  359.79
  5002.4  359.29  5005.7  359.79  5013.2  360.93  5027.6  365.38  5034.2  366.63
  5103.1  369.38  5196.3  382.58  5203.3  382.26  5218.2  384.26  5242.0  385.70
#Mann=7,-1,0
  4524.8    0.16       0  4683.7    0.05       0  4870.7    0.16       0
  4999.7    0.07       0  5005.7    0.16       0  5027.6    0.05       0
  5196.3    0.16       0
Bank Sta=4999.7,5005.7
Exp/Cntr=0.3,0.1

Type RM Length L Ch R = 1,12447,510,510,510
BEGIN DESCRIPTION:
UNT 096 IN CACR 25.0
END DESCRIPTION:
XS GIS Cut Line= 2
      3714266.85     10730917.01      3714162.68     10731882.31
#Sta/Elev= 30
  4571.7  383.66  4591.5  382.17  4605.1  381.91  4635.2  378.04  4775.0  364.24
  4806.2  363.44  4947.0  364.39  4977.2  362.49  4994.3  356.61  4997.1  356.11
  5000.3  356.61  5007.4  362.35  5027.5  364.17  5138.1  368.72  5171.9  368.92
  5188.4  368.07  5208.6  369.42  5218.6  371.79  5238.7  372.76  5244.4  372.71
  5249.4  370.81  5258.8  371.24  5299.1  374.39  5309.1  378.28  5315.5  378.76
  5359.4  377.89  5376.8  378.59  5433.2  382.29  5483.7  387.25  5542.6  391.94
#Mann=8,-1,0
  4571.7    0.16       0  4591.5    0.05       0  4994.3    0.03       0
  5000.3    0.05       0  5171.9    0.16       0  5315.5    0.05       0
  5376.8    0.16       0  5483.7    0.05       0
Bank Sta=4994.3,5000.3
Exp/Cntr=0.3,0.1

Type RM Length L Ch R = 1,11937,504,504,504
BEGIN DESCRIPTION:
UNT 096 IN CACR 24.0
END DESCRIPTION:
XS GIS Cut Line= 3
      3714099.59     10730960.22      3713799.61     10731360.19
      3713749.61     10731560.17
#Sta/Elev= 30
  4470.1  388.44  4506.5  384.17  4527.4  379.65  4548.2  377.92  4556.5  375.80
  4570.1  375.20  4591.9  371.50  4612.8  370.73  4641.9  366.80  4670.1  365.02
  4677.4  363.51  4712.8  362.33  4777.4  362.13  4833.6  362.22  4870.1  363.22
  4980.4  363.10  4988.1  356.86  4990.3  355.88  4993.0  355.38  4996.3  355.88
  5001.0  356.03  5011.3  361.65  5021.6  361.30  5042.2  363.07  5062.8  365.38
  5070.6  367.43  5075.7  367.26  5083.4  368.80  5093.8  369.42  5176.2  379.44
#Mann=3,-1,0
  4470.1    0.05       0  4990.3    0.03       0  4996.3    0.05       0
Bank Sta=4990.3,4996.3
Exp/Cntr=0.3,0.1

Type RM Length L Ch R = 1,11433,373,373,373
BEGIN DESCRIPTION:
UNT 096 IN CACR 23.0
END DESCRIPTION:
XS GIS Cut Line= 4
      3713897.07     10730808.06      3713383.21     10731127.49
      3713341.54     10731245.55      3713556.80     10731613.56
#Sta/Elev= 30
  4327.3  393.84  4384.4  390.24  4514.9  380.39  4633.4  366.52  4646.0  364.75
  4654.0  366.76  4670.8  366.49  4960.6  360.75  4977.6  361.23  4985.6  356.78
  4995.8  354.56  4998.6  354.06  5001.8  354.56  5009.5  359.20  5016.5  360.74
  5116.2  368.12  5177.7  372.60  5183.5  371.60  5199.2  376.36  5205.0  374.96
  5219.8  378.57  5236.1  379.40  5257.9  379.40  5263.7  376.60  5279.4  378.79
  5285.2  376.49  5336.0  379.53  5365.3  379.83  5445.5  387.14  5483.9  387.12
#Mann=11,-1,0
  4327.3    0.16       0  4384.4    0.05       0  4633.4    0.16       0
  4670.8    0.05       0  4960.6    0.16       0  4995.8    0.07       0
  5001.8    0.16       0  5116.2    0.05       0  5219.8    0.12       0
  5236.1    0.05       0  5336.0    0.12       0
Bank Sta=4995.8,5001.8
Exp/Cntr=0.3,0.1

Type RM Length L Ch R = 1,11060,336,336,336
BEGIN DESCRIPTION:
UNT 096 IN CACR 22.0
END DESCRIPTION:
XS GIS Cut Line= 3
      3713499.61     10730560.19      3713099.61     10730960.19
      3712699.60     10731260.20
#Sta/Elev= 30
  4432.4  371.14  4545.5  365.98  4687.0  363.14  4701.1  363.72  4786.0  362.87
  4842.5  363.30  4899.1  359.94  4921.5  359.64  4969.8  360.00  4983.9  358.69
  4991.6  353.05  4994.3  352.55  4997.6  353.05  5005.4  353.20  5011.6  355.10
  5020.0  359.54  5034.5  361.10  5094.7  361.07  5140.8  362.50  5155.4  362.24
  5190.8  363.77  5320.0  365.45  5326.2  366.42  5370.0  368.52  5405.4  371.76
  5440.8  373.78  5461.6  376.21  5490.8  378.07  5495.0  379.52  5498.1  379.52
#Mann=5,-1,0
  4432.4    0.05       0  4921.5    0.12       0  4991.6    0.07       0
  4997.6    0.12       0  5094.7    0.16       0
Bank Sta=4991.6,4997.6
Exp/Cntr=0.3,0.1

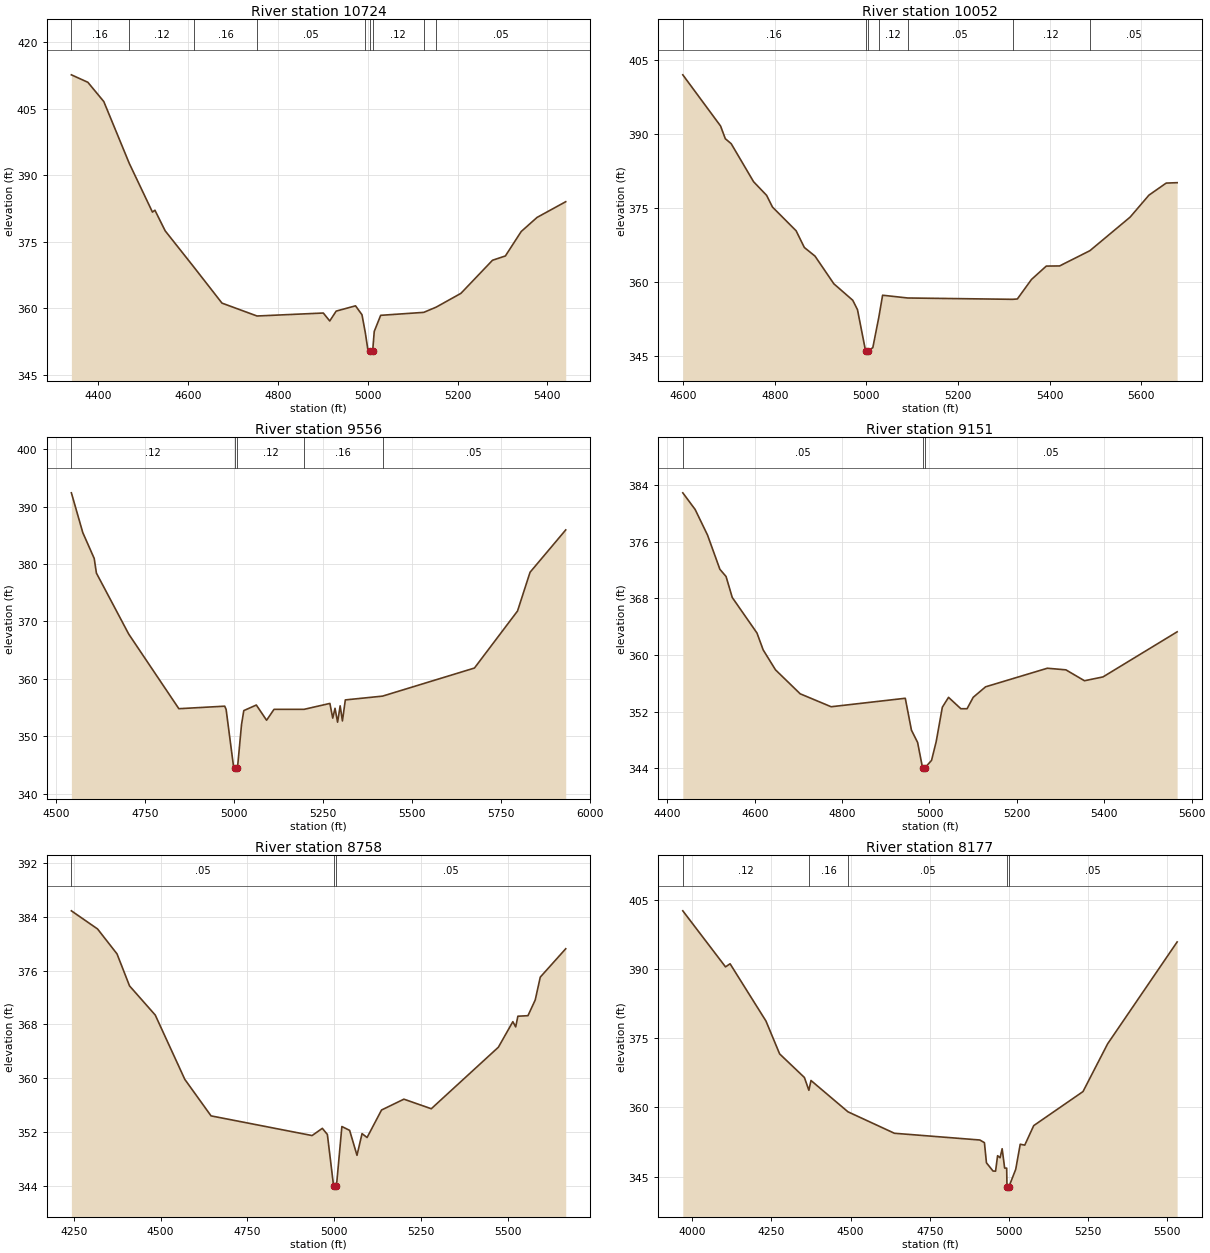
Type RM Length L Ch R = 1,10724,672,672,672
BEGIN DESCRIPTION:
UNT 096 IN CACR 21.0
END DESCRIPTION:
XS GIS Cut Line= 3
      3713154.02     10730196.98      3712917.93     10730696.93
      3712570.73     10731120.52
#Sta/Elev= 30
  4340.3  412.60  4377.0  410.92  4412.5  406.58  4469.3  392.64  4520.8  381.69
  4526.3  382.12  4549.1  377.48  4613.0  369.32  4675.6  361.20  4753.6  358.30
  4901.2  358.97  4915.5  357.18  4929.9  359.40  4972.9  360.59  4987.3  358.59
  4994.7  354.55  5000.8  350.49  5005.1  350.44  5007.8  349.94  5011.1  350.44
  5014.6  354.82  5028.9  358.45  5124.9  359.12  5152.4  360.29  5207.6  363.40
  5277.9  370.85  5306.6  371.82  5341.8  377.32  5377.0  380.49  5440.9  384.03
#Mann=9,-1,0
  4340.3    0.16       0  4469.3    0.12       0  4613.0    0.16       0
  4753.6    0.05       0  4994.7    0.12       0  5005.1    0.07       0
  5011.1    0.12       0  5124.9    0.16       0  5152.4    0.05       0
Bank Sta=5005.1,5011.1
Exp/Cntr=0.3,0.1

Type RM Length L Ch R = 1,10052,496,496,496
BEGIN DESCRIPTION:
UNT 096 IN CACR 20.0
END DESCRIPTION:
XS GIS Cut Line= 3
      3712999.61     10730160.19      3712599.61     10730260.19
      3712449.61     10730910.19
#Sta/Elev= 30
  4599.3  402.08  4681.8  391.70  4692.1  389.13  4705.0  388.11  4753.9  380.40
  4782.3  377.64  4795.2  375.26  4846.7  370.46  4864.7  367.07  4887.9  365.33
  4929.2  359.70  4970.4  356.37  4980.7  354.47  4998.3  346.15  5001.1  345.65
  5004.3  346.15  5014.2  346.76  5027.2  352.87  5035.6  357.39  5090.5  356.83
  5319.3  356.56  5329.8  356.63  5360.6  360.58  5393.0  363.30  5422.1  363.33
  5488.2  366.42  5576.1  373.23  5617.1  377.68  5654.8  380.13  5678.7  380.21
#Mann=7,-1,0
  4599.3    0.16       0  4998.3    0.07       0  5004.3    0.16       0
  5027.2    0.12       0  5090.5    0.05       0  5319.3    0.12       0
  5488.2    0.05       0
Bank Sta=4998.3,5004.3
Exp/Cntr=0.3,0.1

Type RM Length L Ch R = 1,9556,405,405,405
BEGIN DESCRIPTION:
UNT 096 IN CACR 19.0
END DESCRIPTION:
XS GIS Cut Line= 3
      3712799.59     10729710.19      3712399.61     10729860.19
      3711649.57     10730460.22
#Sta/Elev= 30
  4543.7  392.39  4575.7  385.47  4607.8  380.96  4614.0  378.41  4704.8  367.78
  4845.4  354.80  4974.1  355.24  4978.1  354.67  4998.9  344.74  5003.9  344.43
  5006.7  343.93  5009.9  344.43  5021.3  352.03  5027.7  354.47  5062.9  355.44
  5091.7  352.79  5112.6  354.69  5197.0  354.69  5269.4  355.72  5277.4  353.16
  5283.8  354.87  5291.0  352.45  5298.2  355.30  5304.6  352.67  5312.7  356.33
  5417.2  356.99  5675.2  361.88  5796.1  371.81  5831.3  378.56  5931.4  385.93
#Mann=5,-1,0
  4543.7    0.12       0  5003.9    0.07       0  5009.9    0.12       0
  5197.0    0.16       0  5417.2    0.05       0
Bank Sta=5003.9,5009.9
Exp/Cntr=0.3,0.1

Type RM Length L Ch R = 1,9151,393,393,393
BEGIN DESCRIPTION:
UNT 096 IN CACR 18.0
END DESCRIPTION:
XS GIS Cut Line= 3
      3712449.64     10729260.15      3712049.61     10729660.19
      3711649.62     10730060.17
#Sta/Elev= 30
  4435.4  382.95  4463.7  380.59  4492.0  376.97  4520.3  372.13  4534.4  371.11
  4548.6  368.14  4605.2  363.11  4619.3  360.73  4647.6  357.90  4704.1  354.51
  4774.9  352.68  4944.6  353.88  4958.7  349.37  4972.8  347.63  4984.0  344.07
  4986.7  343.57  4990.0  344.07  5004.7  345.09  5015.3  347.73  5029.4  352.61
  5043.6  354.01  5071.8  352.40  5086.0  352.40  5100.1  354.02  5128.4  355.50
  5269.8  358.13  5312.3  357.90  5354.7  356.36  5397.1  356.90  5566.8  363.28
#Mann=3,-1,0
  4435.4    0.05       0  4984.0    0.03       0  4990.0    0.05       0
Bank Sta=4984,4990
Exp/Cntr=0.3,0.1

Type RM Length L Ch R = 1,8758,581,581,581
BEGIN DESCRIPTION:
UNT 096 IN CACR 17.0
END DESCRIPTION:
XS GIS Cut Line= 3
      3712466.56     10729189.98      3711813.76     10729426.10
      3711369.34     10730002.47
#Sta/Elev= 30
  4243.5  384.86  4318.8  382.17  4374.8  378.47  4410.8  373.72  4484.8  369.39
  4569.9  359.84  4645.3  354.43  4935.9  351.51  4965.4  352.58  4979.9  351.67
  4997.7  344.06  5000.5  343.56  5003.7  344.06  5007.1  344.64  5021.6  352.85
  5043.9  352.28  5065.1  348.58  5079.6  351.80  5094.1  351.22  5135.7  355.30
  5200.0  356.91  5278.8  355.49  5471.8  364.62  5513.4  368.41  5521.6  367.63
  5527.9  369.22  5556.9  369.30  5577.8  371.63  5592.3  375.02  5665.5  379.23
#Mann=3,-1,0
  4243.5    0.05       0  4997.7    0.03       0  5003.7    0.05       0
Bank Sta=4997.7,5003.7
Exp/Cntr=0.3,0.1

Type RM Length L Ch R = 1,8177,378,378,378
BEGIN DESCRIPTION:
UNT 096 IN CACR 16.0
END DESCRIPTION:
XS GIS Cut Line= 3
      3711949.58     10728460.23      3711299.61     10729260.19
      3710899.64     10729610.17
#Sta/Elev= 30
  3969.8  402.55  4104.8  390.41  4119.2  391.08  4232.6  378.68  4275.8  371.56
  4354.1  366.45  4368.2  363.68  4374.9  365.80  4491.7  359.02  4638.5  354.37
  4908.6  352.91  4923.0  352.33  4929.4  347.97  4950.2  346.19  4958.2  346.16
  4964.6  349.51  4972.5  349.06  4979.0  351.02  4986.9  346.83  4993.3  346.82
  4994.3  342.77  4997.1  342.27  5000.3  342.77  5021.9  346.56  5036.1  351.99
  5050.4  351.80  5078.8  356.03  5234.5  363.40  5312.3  373.74  5532.0  395.81
#Mann=5,-1,0
  3969.8    0.12       0  4368.2    0.16       0  4491.7    0.05       0
  4994.3    0.03       0  5000.3    0.05       0
Bank Sta=4994.3,5000.3
Exp/Cntr=0.3,0.1

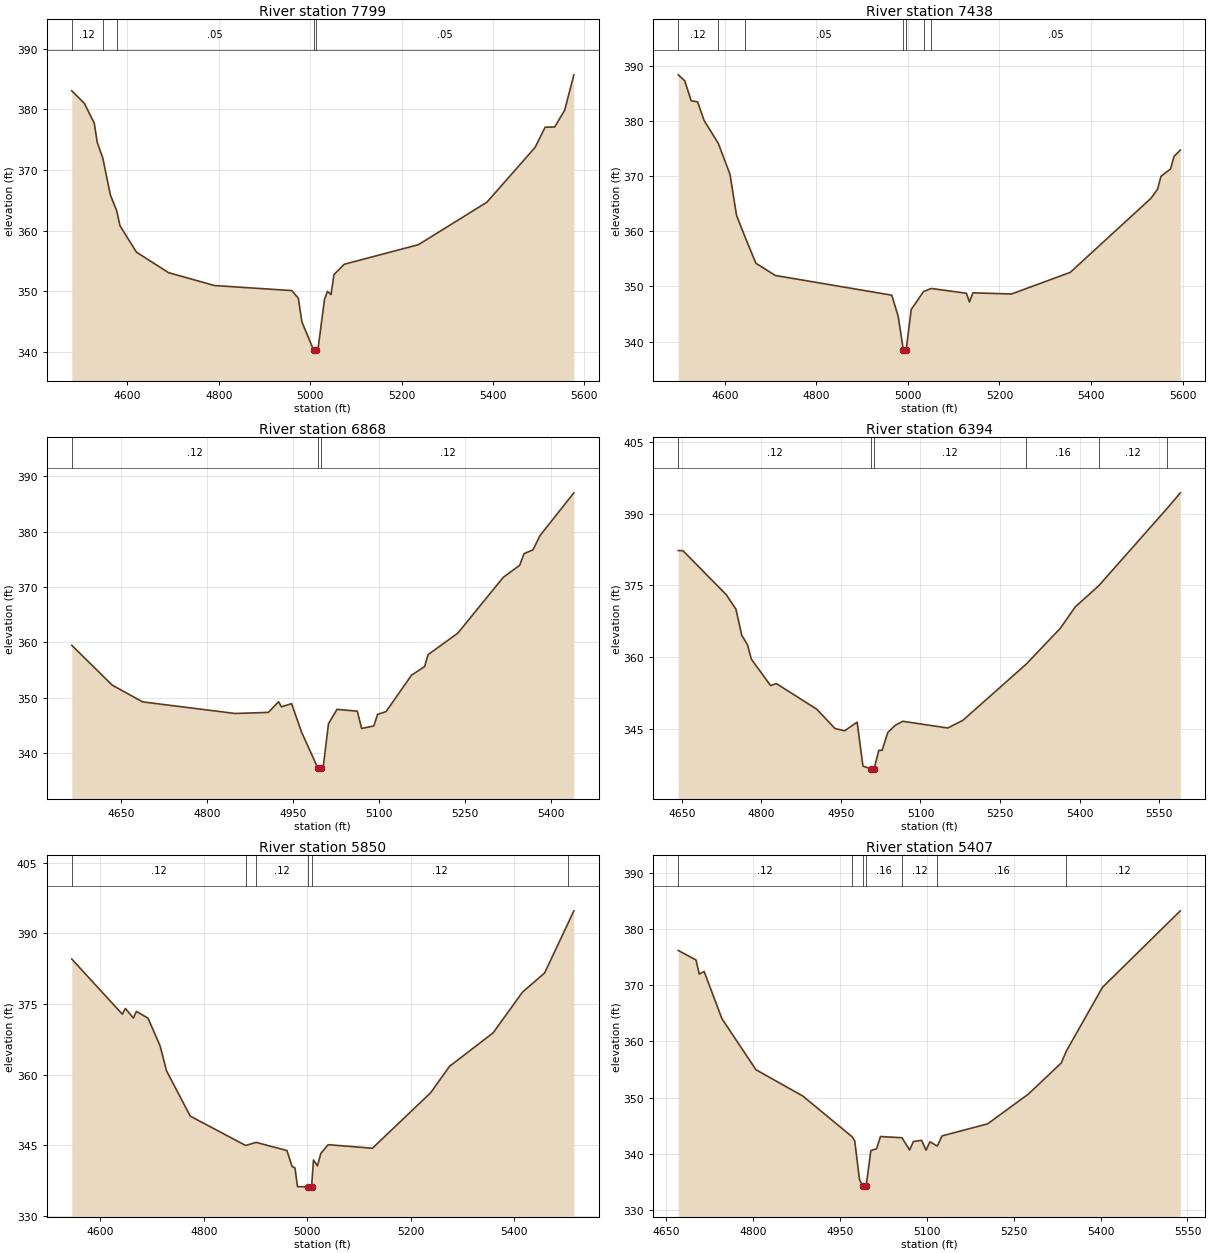
Type RM Length L Ch R = 1,7799,361,361,361
BEGIN DESCRIPTION:
UNT 096 IN CACR 15.0
END DESCRIPTION:
XS GIS Cut Line= 2
      3711487.37     10728578.88      3710786.35     10729425.66
#Sta/Elev= 30
  4478.0  383.05  4505.7  380.96  4527.3  377.70  4533.7  374.55  4545.9  371.96
  4562.4  365.91  4576.5  363.23  4583.6  360.78  4619.7  356.43  4690.0  353.05
  4790.4  350.93  4960.0  350.09  4974.0  348.84  4981.8  344.96  5007.5  340.28
  5010.2  339.78  5013.5  340.28  5017.0  340.37  5031.3  348.62  5037.9  349.96
  5045.6  349.43  5052.1  352.73  5074.3  354.43  5237.1  357.67  5386.9  364.67
  5492.4  373.70  5514.5  377.04  5535.4  377.08  5557.2  379.84  5577.3  385.68
#Mann=5,-1,0
  4478.0    0.12       0  4545.9    0.16       0  4576.5    0.05       0
  5007.5    0.03       0  5013.5    0.05       0
Bank Sta=5007.5,5013.5
Exp/Cntr=0.3,0.1

Type RM Length L Ch R = 1,7438,570,570,570
BEGIN DESCRIPTION:
UNT 096 IN CACR 14.0
END DESCRIPTION:
XS GIS Cut Line= 3
      3711299.61     10728410.19      3710899.61     10728810.19
      3710549.60     10729210.20
#Sta/Elev= 30
  4498.0  388.43  4512.1  387.37  4526.3  383.72  4540.4  383.52  4554.6  380.13
  4585.5  375.99  4611.1  370.37  4625.3  362.96  4643.8  359.03  4667.7  354.22
  4710.1  352.00  4964.7  348.42  4978.8  344.54  4990.0  338.40  4992.7  337.90
  4996.0  338.40  5007.1  345.81  5034.0  349.07  5051.0  349.64  5127.7  348.77
  5134.4  347.18  5142.0  348.85  5226.5  348.64  5354.6  352.56  5531.1  366.01
  5545.4  367.65  5553.0  370.01  5573.8  371.33  5581.4  373.61  5595.2  374.77
#Mann=7,-1,0
  4498.0    0.12       0  4585.5    0.16       0  4643.8    0.05       0
  4990.0    0.03       0  4996.0    0.05       0  5034.0    0.12       0
  5051.0    0.05       0
Bank Sta=4990,4996
Exp/Cntr=0.3,0.1

Type RM Length L Ch R = 1,6868,474,474,474
BEGIN DESCRIPTION:
UNT 096 IN CACR 13.0
END DESCRIPTION:
XS GIS Cut Line= 3
      3710649.61     10728360.19      3710599.61     10728760.19
      3710199.62     10729010.18
#Sta/Elev= 30
  4564.4  359.45  4634.9  352.25  4687.9  349.22  4849.1  347.12  4907.0  347.32
  4924.7  349.25  4929.7  348.33  4947.4  348.90  4965.0  343.70  4993.4  337.20
  4996.2  336.70  4999.4  337.20  5002.9  337.77  5011.7  345.27  5026.5  347.87
  5061.9  347.54  5069.5  344.41  5090.7  344.87  5097.2  346.96  5112.0  347.47
  5156.2  354.03  5179.2  355.61  5185.1  357.75  5237.0  361.64  5316.0  371.72
  5344.9  373.93  5352.5  376.03  5367.9  376.70  5380.3  379.30  5439.2  387.02
#Mann=3,-1,0
  4564.4    0.12       0  4993.4    0.07       0  4999.4    0.12       0
Bank Sta=4993.4,4999.4
Exp/Cntr=0.3,0.1

Type RM Length L Ch R = 1,6394,544,544,544
BEGIN DESCRIPTION:
UNT 096 IN CACR 12.0
END DESCRIPTION:
XS GIS Cut Line= 3
      3710499.62     10728110.16      3710349.61     10728460.19
      3709949.61     10728860.18
#Sta/Elev= 30
  4643.4  382.27  4652.5  382.22  4734.1  373.02  4752.2  369.98  4763.1  364.56
  4774.0  362.55  4781.2  359.55  4817.5  354.02  4828.4  354.43  4904.5  349.08
  4939.0  345.02  4957.1  344.55  4980.7  346.36  4991.6  337.16  5006.7  336.61
  5009.5  336.11  5012.7  336.61  5021.5  340.46  5027.8  340.46  5038.4  344.19
  5052.5  345.70  5066.6  346.54  5151.5  345.14  5179.8  346.72  5299.3  358.49
  5363.6  365.99  5391.9  370.49  5435.9  374.88  5565.1  391.10  5589.9  394.35
#Mann=6,-1,0
  4643.4    0.12       0  5006.7    0.07       0  5012.7    0.12       0
  5299.3    0.16       0  5435.9    0.12       0  5565.1    0.16       0
Bank Sta=5006.7,5012.7
Exp/Cntr=0.3,0.1

Type RM Length L Ch R = 1,5850,443,443,443
BEGIN DESCRIPTION:
UNT 096 IN CACR 11.0
END DESCRIPTION:
XS GIS Cut Line= 3
      3710475.87     10728033.14      3710099.61     10728260.19
      3709749.59     10728660.21
#Sta/Elev= 30
  4544.7  384.53  4642.5  372.82  4648.4  374.04  4663.9  372.01  4669.7  373.41
  4692.2  371.97  4715.5  366.10  4728.0  360.78  4773.9  351.17  4881.0  344.94
  4901.2  345.60  4960.9  343.86  4970.6  340.53  4976.4  340.16  4981.2  336.19
  5002.5  336.17  5005.3  335.67  5008.5  336.17  5012.2  341.86  5019.8  340.60
  5026.4  343.26  5040.6  345.11  5126.1  344.35  5239.0  356.16  5275.1  361.73
  5359.5  368.85  5416.5  377.52  5459.2  381.58  5503.7  391.95  5515.7  394.77
#Mann=6,-1,0
  4544.7    0.12       0  4881.0    0.16       0  4901.2    0.12       0
  5002.5    0.07       0  5008.5    0.12       0  5503.7    0.16       0
Bank Sta=5002.5,5008.5
Exp/Cntr=0.3,0.1

Type RM Length L Ch R = 1,5407,484,484,484
BEGIN DESCRIPTION:
UNT 096 IN CACR 10.0
END DESCRIPTION:
XS GIS Cut Line= 3
      3709949.61     10727660.20      3709799.61     10727960.19
      3709399.62     10728310.18
#Sta/Elev= 30
  4670.7  376.25  4701.4  374.55  4707.0  372.03  4715.4  372.50  4746.2  364.06
  4804.9  354.96  4885.9  350.26  4971.0  342.99  4975.4  342.26  4983.7  335.36
  4989.1  334.15  4991.9  333.65  4995.1  334.15  5003.3  340.52  5013.2  340.86
  5019.9  343.04  5057.0  342.82  5070.2  340.62  5076.8  342.15  5091.0  342.35
  5098.6  340.61  5105.3  342.09  5118.1  341.34  5126.2  343.15  5204.9  345.30
  5275.2  350.61  5332.1  356.17  5340.9  358.31  5403.3  369.68  5537.6  383.32
#Mann=7,-1,0
  4670.7    0.12       0  4971.0    0.16       0  4989.1    0.07       0
  4995.1    0.16       0  5057.0    0.12       0  5118.1    0.16       0
  5340.9    0.12       0
Bank Sta=4989.1,4995.1
Exp/Cntr=0.3,0.1

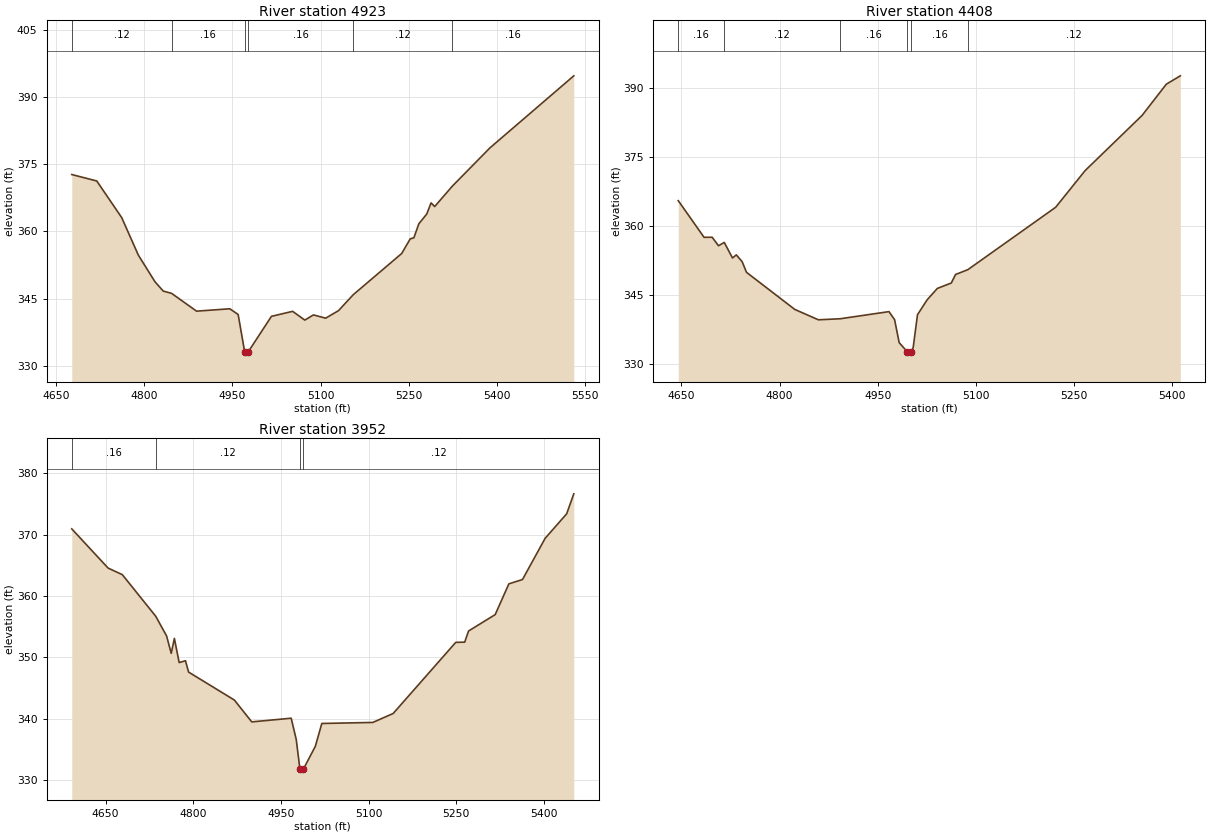
Type RM Length L Ch R = 1,4923,515,515,515
BEGIN DESCRIPTION:
UNT 096 IN CACR 9.0
END DESCRIPTION:
XS GIS Cut Line= 3
      3709699.64     10727610.16      3709449.61     10727860.19
      3709149.61     10728260.19
#Sta/Elev= 30
  4677.0  372.70  4719.5  371.26  4761.9  363.08  4790.2  354.70  4818.5  348.74
  4832.6  346.66  4846.7  346.16  4889.2  342.18  4945.7  342.71  4959.9  341.44
  4971.0  333.08  4973.8  332.58  4977.0  333.08  5016.5  341.02  5052.5  342.14
  5073.3  340.18  5087.9  341.34  5108.7  340.61  5130.6  342.30  5155.4  345.83
  5237.9  355.05  5252.5  358.33  5258.7  358.57  5267.1  361.69  5280.6  363.88
  5287.9  366.37  5294.1  365.55  5324.1  370.11  5387.9  378.64  5530.6  394.75
#Mann=6,-1,0
  4677.0    0.12       0  4846.7    0.16       0  4971.0    0.07       0
  4977.0    0.16       0  5155.4    0.12       0  5324.1    0.16       0
Bank Sta=4971,4977
Exp/Cntr=0.3,0.1

Type RM Length L Ch R = 1,4408,456,456,456
BEGIN DESCRIPTION:
UNT 096 IN CACR 8.0
END DESCRIPTION:
XS GIS Cut Line= 2
      3709258.58     10727426.42      3708864.47     10728085.01
#Sta/Elev= 30
  4645.2  365.43  4684.6  357.46  4697.0  357.47  4706.7  355.62  4715.5  356.35
  4728.1  352.96  4733.9  353.64  4742.8  352.17  4749.5  349.84  4823.4  341.76
  4859.4  339.51  4893.0  339.74  4967.3  341.29  4975.9  339.54  4982.9  334.54
  4995.4  332.54  4998.2  332.04  5001.4  332.54  5004.3  333.47  5010.9  340.61
  5025.6  343.85  5041.2  346.33  5062.6  347.52  5069.1  349.37  5087.9  350.42
  5222.1  363.99  5267.2  371.98  5354.3  383.99  5391.3  390.78  5412.7  392.60
#Mann=6,-1,0
  4645.2    0.16       0  4715.5    0.12       0  4893.0    0.16       0
  4995.4    0.07       0  5001.4    0.16       0  5087.9    0.12       0
Bank Sta=4995.4,5001.4
Exp/Cntr=0.3,0.1

Type RM Length L Ch R = 1,3952,546,546,546
BEGIN DESCRIPTION:
UNT 096 IN CACR 7.0
END DESCRIPTION:
XS GIS Cut Line= 3
      3709180.46     10727301.44      3708852.32     10727431.66
      3708649.20     10727895.18
#Sta/Elev= 30
  4592.1  370.96  4654.3  364.56  4678.6  363.49  4735.8  356.70  4754.4  353.48
  4762.3  350.65  4767.7  353.08  4775.9  349.14  4786.7  349.44  4792.0  347.59
  4870.4  343.02  4900.1  339.46  4967.6  340.06  4976.3  336.56  4982.5  331.76
  4985.2  331.26  4988.5  331.76  5008.9  335.47  5020.0  339.20  5107.3  339.37
  5142.1  340.83  5249.2  352.44  5264.5  352.47  5271.1  354.29  5316.7  356.97
  5340.1  361.99  5363.4  362.69  5402.1  369.41  5439.0  373.42  5451.2  376.68
#Mann=4,-1,0
  4592.1    0.16       0  4735.8    0.12       0  4982.5    0.07       0
  4988.5    0.12       0
Bank Sta=4982.5,4988.5
Exp/Cntr=0.3,0.1