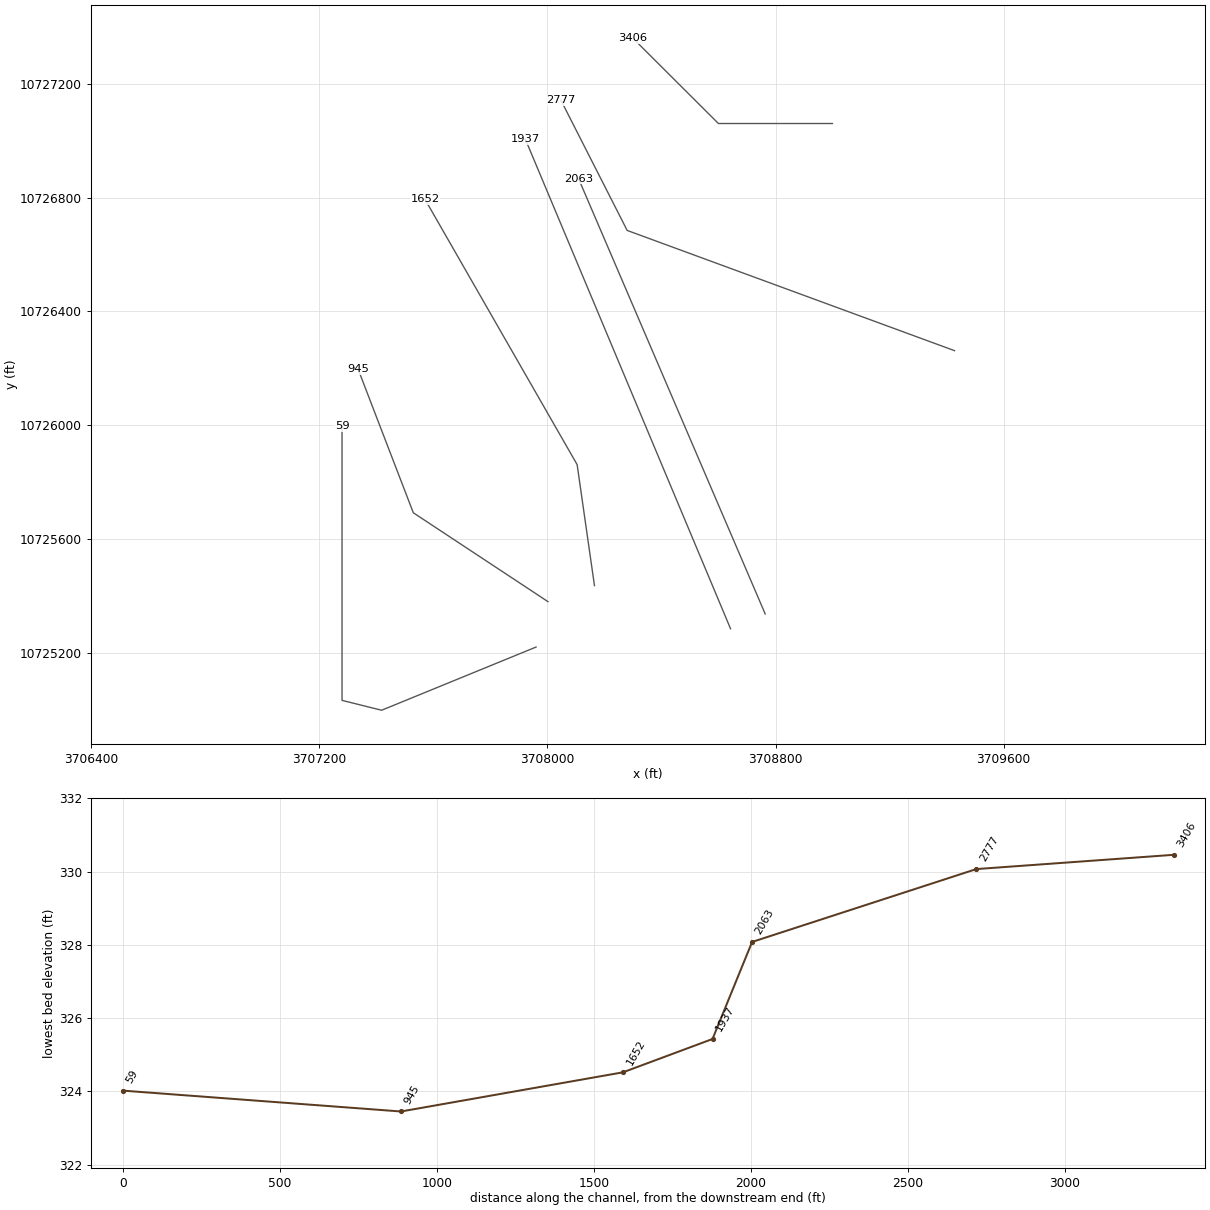
HEC-RAS study UNT 096 IN CACR.prj: UNT 096 IN CACR Base Level Engineering

--- UNT 096 IN CACR.g01 (geometry) --- (continued)

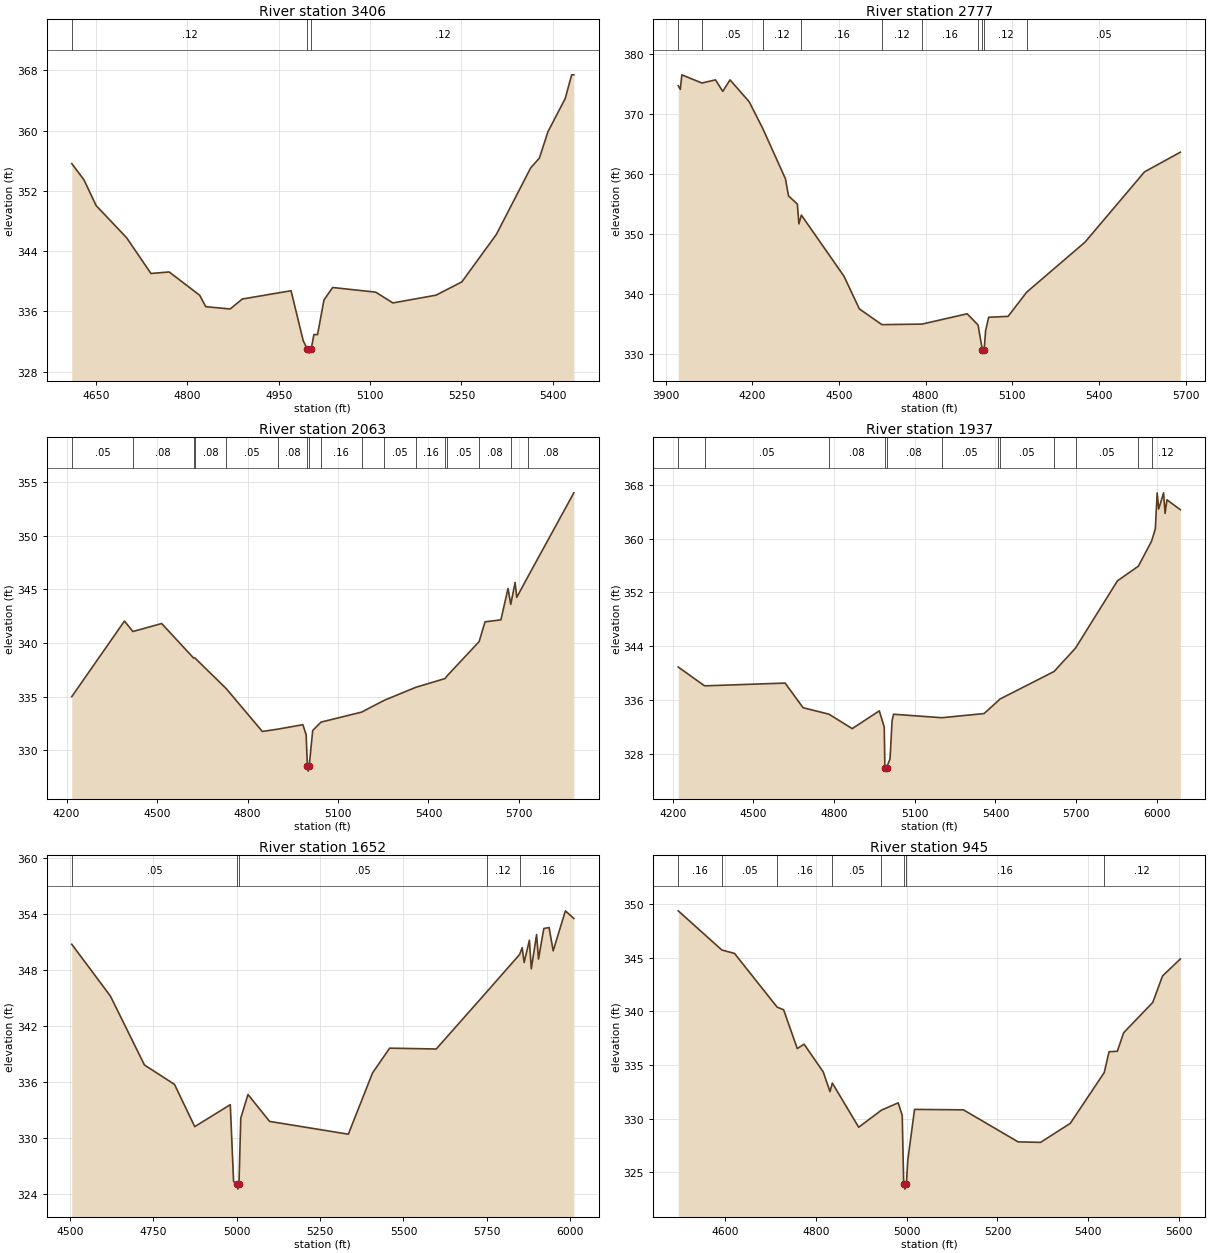
Type RM Length L Ch R = 1,3406,629,629,629
BEGIN DESCRIPTION:
UNT 096 IN CACR 6.0
END DESCRIPTION:
XS GIS Cut Line= 3
      3708999.60     10727060.19      3708599.61     10727060.19
      3708299.58     10727360.22
#Sta/Elev= 30
  4610.3  355.61  4630.3  353.46  4650.3  350.04  4700.3  345.78  4740.3  341.03
  4770.3  341.23  4820.3  338.14  4830.3  336.62  4870.3  336.32  4890.3  337.64
  4970.3  338.74  4990.3  332.10  4997.3  330.96  5000.0  330.46  5003.3  330.96
  5007.8  332.92  5013.8  332.92  5024.4  337.52  5038.6  339.17  5109.3  338.55
  5137.6  337.12  5208.3  338.15  5250.7  339.91  5307.3  346.20  5363.8  355.05
  5378.0  356.34  5392.1  359.84  5420.4  364.24  5431.0  367.39  5434.6  367.39
#Mann=3,-1,0
  4610.3    0.12       0  4997.3    0.07       0  5003.3    0.12       0
Bank Sta=4997.3,5003.3
Exp/Cntr=0.3,0.1

Type RM Length L Ch R = 1,2777,714,714,714
BEGIN DESCRIPTION:
Mapping XS 97178715
END DESCRIPTION:
XS GIS Cut Line= 3
      3709427.91     10726261.43      3708279.58     10726684.22
      3708046.93     10727142.57
#Sta/Elev= 30
  3943.7  374.66  3950.9  374.04  3956.2  376.47  4025.8  375.10  4072.7  375.63
  4097.8  373.71  4123.0  375.63  4189.2  371.99  4236.7  367.48  4314.9  359.12
  4325.5  356.27  4356.0  354.92  4361.3  351.63  4369.9  353.08  4517.3  342.90
  4570.6  337.44  4648.6  334.82  4787.5  334.91  4943.8  336.63  4981.5  334.75
  4996.4  330.57  4999.1  330.07  5002.4  330.57  5007.5  333.81  5018.2  336.05
  5085.4  336.20  5149.8  340.24  5351.5  348.57  5557.5  360.29  5681.4  363.57
#Mann=10,-1,0
  3943.7    0.12       0  4025.8    0.05       0  4236.7    0.12       0
  4369.9    0.16       0  4648.6    0.12       0  4787.5    0.16       0
  4981.5    0.12       0  4996.4    0.07       0  5002.4    0.12       0
  5149.8    0.05       0
Bank Sta=4996.4,5002.4
Exp/Cntr=0.3,0.1

Type RM Length L Ch R = 1,2063,126,126,126
BEGIN DESCRIPTION:
UNT 096 IN CACR 5.0
END DESCRIPTION:
XS GIS Cut Line= 2
      3708763.77     10725335.60      3708108.95     10726866.42
#Sta/Elev= 30
  4217.2  335.01  4391.9  342.04  4420.0  341.07  4515.3  341.81  4621.3  338.60
  4625.0  338.62  4729.0  335.77  4849.2  331.77  4901.6  331.99  4983.5  332.40
  4994.4  331.48  4998.6  328.58  5001.3  328.08  5004.6  328.58  5016.2  331.86
  5043.7  332.64  5178.3  333.57  5253.5  334.67  5358.4  335.88  5454.9  336.69
  5463.2  336.98  5568.1  340.13  5587.7  341.97  5640.3  342.15  5663.9  345.07
  5673.0  343.59  5687.4  345.63  5692.9  344.25  5731.5  346.25  5882.2  353.97
#Mann=17,-1,0
  4217.2    0.05       0  4420.0    0.08       0  4621.3    0.05       0
  4625.0    0.08       0  4729.0    0.05       0  4901.6    0.08       0
  4998.6    0.07       0  5004.6    0.08       0  5043.7    0.16       0
  5178.3    0.08       0  5253.5    0.05       0  5358.4    0.16       0
  5454.9    0.08       0  5463.2    0.05       0  5568.1    0.08       0
  5673.0    0.05       0  5731.5    0.08       0
Bank Sta=4998.6,5004.6
Exp/Cntr=0.3,0.1

Type RM Length L Ch R = 1,1937,285,285,285
BEGIN DESCRIPTION:
UNT 096 IN CACR 4.0
END DESCRIPTION:
XS GIS Cut Line= 2
      3708642.24     10725283.53      3707922.05     10727005.92
#Sta/Elev= 30
  4220.5  340.91  4318.6  338.11  4617.9  338.52  4684.7  334.86  4781.3  333.89
  4867.5  331.75  4968.1  334.39  4986.5  331.98  4988.9  325.93  4991.7  325.43
  4994.9  325.93  5008.1  327.27  5015.7  332.94  5021.2  333.89  5200.9  333.37
  5357.7  333.99  5408.7  335.83  5415.1  336.11  5617.8  340.24  5697.7  343.72
  5853.6  353.72  5931.5  355.91  5980.4  359.61  5994.5  361.45  6001.4  366.80
  6006.9  364.40  6025.2  366.81  6030.7  363.76  6037.8  365.77  6087.4  364.30
#Mann=12,-1,0
  4220.5    0.08       0  4318.6    0.05       0  4781.3    0.08       0
  4988.9    0.07       0  4994.9    0.08       0  5200.9    0.05       0
  5408.7    0.08       0  5415.1    0.05       0  5617.8    0.08       0
  5697.7    0.05       0  5931.5    0.08       0  5980.4    0.12       0
Bank Sta=4988.9,4994.9
Exp/Cntr=0.3,0.1

Type RM Length L Ch R = 1,1652,707,707,707
BEGIN DESCRIPTION:
UNT 096 IN CACR 3.0
END DESCRIPTION:
XS GIS Cut Line= 3
      3708164.82     10725435.42      3708104.05     10725860.77
      3707570.22     10726793.89
#Sta/Elev= 30
  4506.0  350.73  4621.9  345.18  4723.8  337.81  4813.9  335.73  4874.5  331.21
  4981.1  333.56  4990.9  325.35  5001.1  325.02  5003.9  324.52  5007.1  325.02
  5012.5  332.12  5034.1  334.65  5098.8  331.77  5334.9  330.40  5407.4  336.96
  5458.7  339.61  5598.3  339.52  5749.6  345.63  5848.2  349.64  5855.9  350.37
  5861.7  348.78  5877.5  351.16  5883.2  348.11  5899.1  351.77  5904.8  349.15
  5920.7  352.42  5936.5  352.52  5948.8  350.03  5985.4  354.31  6010.7  353.49
#Mann=5,-1,0
  4506.0    0.05       0  5001.1    0.03       0  5007.1    0.05       0
  5749.6    0.12       0  5848.2    0.16       0
Bank Sta=5001.1,5007.1
Exp/Cntr=0.3,0.1

Type RM Length L Ch R = 1,945,886,886,886
BEGIN DESCRIPTION:
UNT 096 IN CACR 2.0
END DESCRIPTION:
XS GIS Cut Line= 3
      3708001.63     10725378.99      3707529.40     10725691.49
      3707335.58     10726196.83
#Sta/Elev= 30
  4496.0  349.35  4592.3  345.70  4620.1  345.39  4714.1  340.39  4728.5  340.14
  4758.6  336.53  4773.6  336.94  4815.7  334.37  4830.8  332.52  4835.9  333.32
  4894.1  329.21  4944.2  330.80  4981.2  331.48  4990.1  330.31  4993.3  323.95
  4996.0  323.45  4999.3  323.95  5002.3  326.12  5017.3  330.87  5125.1  330.83
  5245.7  327.85  5295.1  327.80  5360.8  329.57  5435.7  334.30  5446.4  336.24
  5464.5  336.28  5478.6  338.01  5542.8  340.83  5564.3  343.29  5603.5  344.87
#Mann=8,-1,0
  4496.0    0.16       0  4592.3    0.05       0  4714.1    0.16       0
  4835.9    0.05       0  4944.2    0.16       0  4993.3    0.07       0
  4999.3    0.16       0  5435.7    0.12       0
Bank Sta=4993.3,4999.3
Exp/Cntr=0.3,0.1

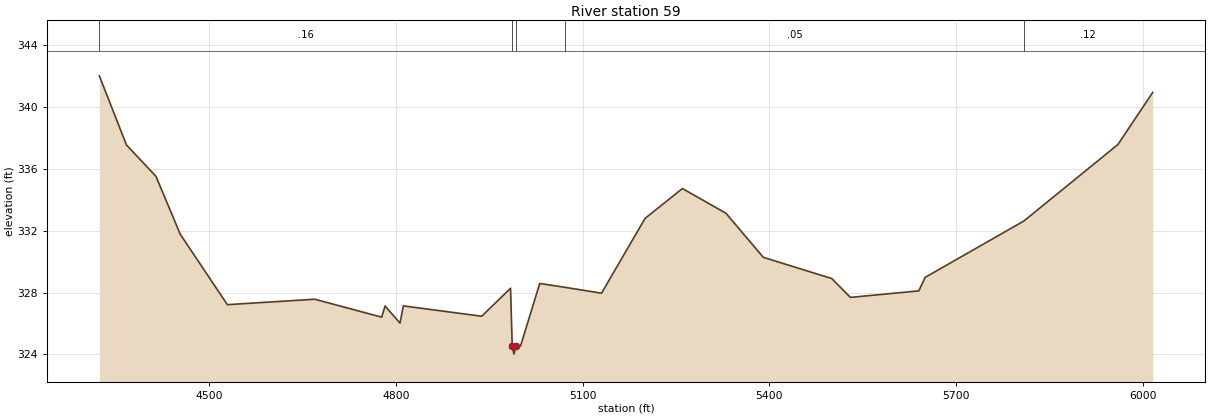
Type RM Length L Ch R = 1,59,0,0,0
BEGIN DESCRIPTION:
UNT 096 IN CACR 1.0
END DESCRIPTION:
XS GIS Cut Line= 4
      3707959.96     10725219.27      3707418.29     10724997.05
      3707279.40     10725031.77      3707279.40     10725996.12
#Sta/Elev= 30
  4323.3  342.02  4366.9  337.55  4414.3  335.52  4453.4  331.77  4529.1  327.22
  4669.6  327.57  4777.1  326.41  4782.5  327.13  4806.5  326.03  4811.9  327.14
  4937.8  326.47  4984.2  328.28  4986.9  324.52  4989.6  324.02  4992.9  324.52
  5000.2  324.54  5031.1  328.59  5071.9  328.34  5130.4  327.96  5200.4  332.80
  5260.4  334.73  5330.4  333.13  5390.4  330.28  5500.4  328.91  5530.4  327.69
  5640.4  328.11  5650.4  328.98  5809.2  332.63  5960.4  337.58  6016.3  340.95
#Mann=5,-1,0
  4323.3    0.16       0  4986.9    0.07       0  4992.9    0.16       0
  5071.9    0.05       0  5809.2    0.12       0
Bank Sta=4986.9,4992.9
Exp/Cntr=0.3,0.1

Chan Stop Cuts=-1