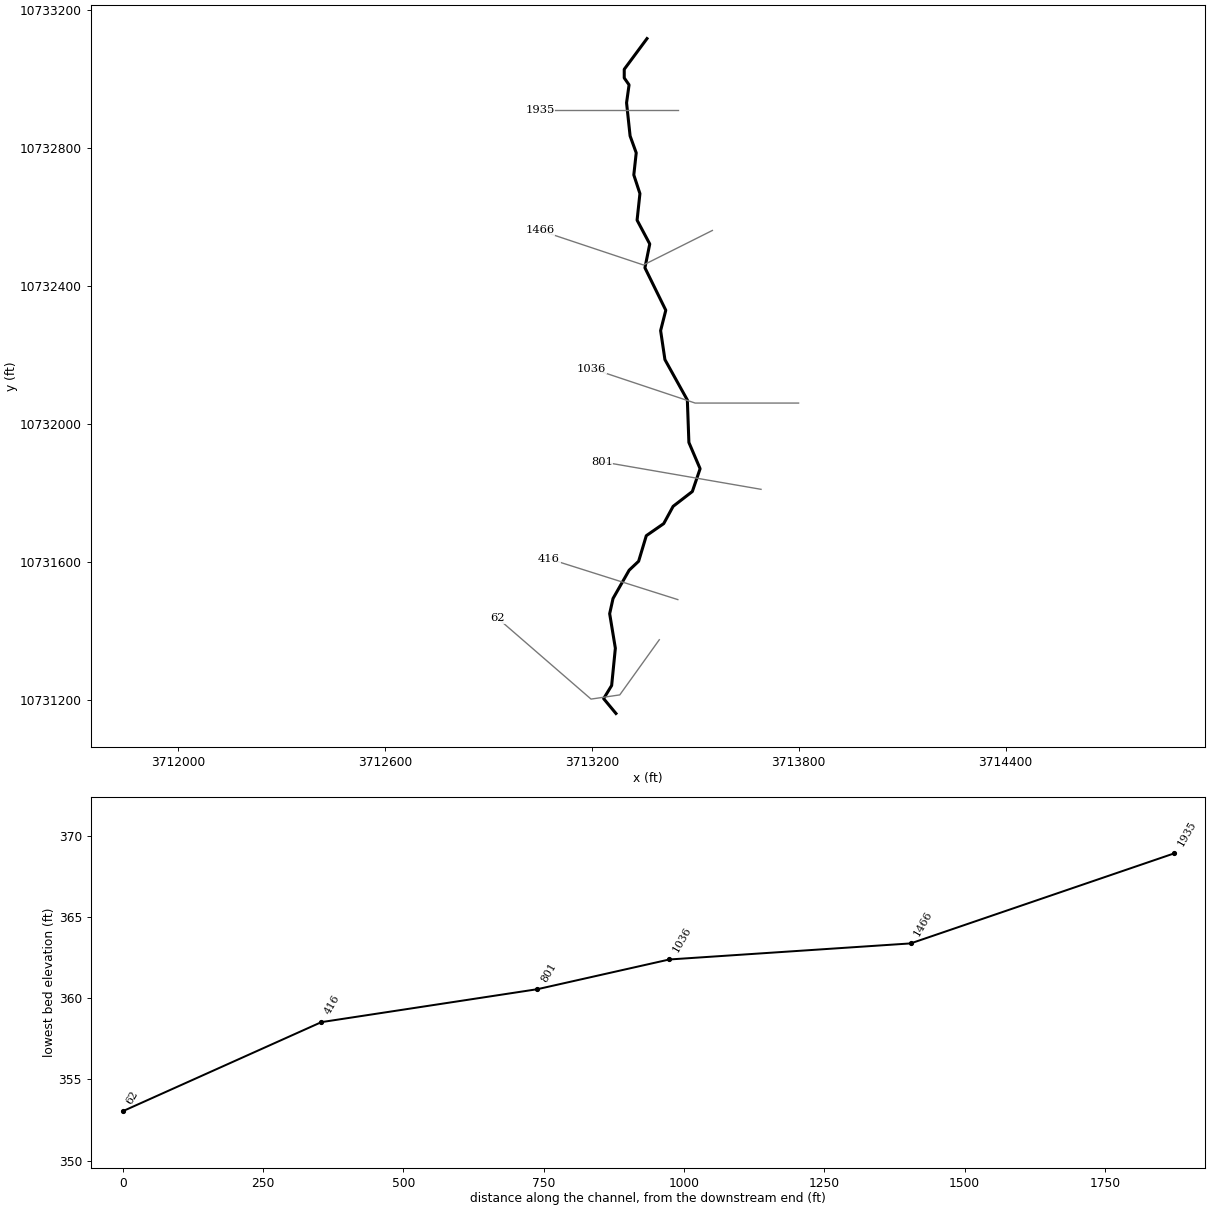
--- UNT 097 IN CACR.prj (project) ---

Proj Title=UNT 097 IN CACR Base Level Engineering
Current Plan=p01
Default Exp/Contr=0.3,0.1
English Units
Geom File=g01
Flow File=f01
Plan File=p01
Y Axis Title=Elevation
X Axis Title(PF)=Main Channel Distance
X Axis Title(XS)=Station
BEGIN DESCRIPTION:
UNT 097 IN CACR
END DESCRIPTION:
DSS Export Rating Curves= 0
DSS Export Rating Curve Sorted= 0
DSS Export Volume Flow Curves= 0
DXF OffsetX= 0
DXF OffsetY= 0
DXF ScaleX= 1
DXF ScaleY= 10

--- UNT 097 IN CACR.p01 (plan) ---

Plan Title=Multiple Run
Short Identifier=Multiple
Geom File=g01
Flow File=f01
Subcritical Flow
K Sum by GR= 0
Std Step Tol= 0.01
Critical Tol= 0.01
Num of Std Step Trials= 20
Max Error Tol= 0.3
Flow Tol Ratio= 0.001
Split Flow NTrial= 30
Split Flow Tol= 0.02
Split Flow Ratio= 0.02
Log Output Level= 0
Friction Slope Method= 1
Unsteady Friction Slope Method= 2
Unsteady Bridges Friction Slope Method= 1
Parabolic Critical Depth
Global Vel Dist=  1 , 1 , 1
Global Log Level= 0
CheckData=True
Encroach Param= -1, 0, 0, 0
BEGIN DESCRIPTION:
Multiple Run
END DESCRIPTION:

--- UNT 097 IN CACR.f01 (steady flow) ---

Flow Title=Multiple
Program Version=4.10
Number of Profiles= 7
Profile Names=10-year,25-year,50-year,1pct_min,100-year,1pct_plu,500-year
River Rch & RM=UNT 097 IN CACR,Reach-1         ,1935
     605     823    1002     897    1213    1640    1778
Boundary for River Rch & Prof#=UNT 097 IN CACR,Reach-1         , 1
Up Type= 0
Dn Type= 3
Dn Slope=0.01557
Boundary for River Rch & Prof#=UNT 097 IN CACR,Reach-1         , 2
Up Type= 0
Dn Type= 3
Dn Slope=0.01557
Boundary for River Rch & Prof#=UNT 097 IN CACR,Reach-1         , 3
Up Type= 0
Dn Type= 3
Dn Slope=0.01557
Boundary for River Rch & Prof#=UNT 097 IN CACR,Reach-1         , 4
Up Type= 0
Dn Type= 3
Dn Slope=0.01557
Boundary for River Rch & Prof#=UNT 097 IN CACR,Reach-1         , 5
Up Type= 0
Dn Type= 3
Dn Slope=0.01557
Boundary for River Rch & Prof#=UNT 097 IN CACR,Reach-1         , 6
Up Type= 0
Dn Type= 3
Dn Slope=0.01557
Boundary for River Rch & Prof#=UNT 097 IN CACR,Reach-1         , 7
Up Type= 0
Dn Type= 3
Dn Slope=0.01557
DSS Import GetInterval= 0
DSS Import GetPeak= 0
DSS Import FillOption= 0

--- UNT 097 IN CACR.g01 (geometry) ---

Geom Title=Existing Conditions
Program Version=4.10

River Reach=UNT 097 IN CACR ,Reach-1
Reach XY= 30
        3713360.       10733116.        3713294.       10733027.
        3713294.       10733002.        3713308.       10732982.
      3713300.75       10732930.        3713311.       10732834.
      3713328.75       10732785.      3713321.75       10732721.
       3713339.5       10732667.      3713331.25       10732590.
        3713368.       10732521.        3713354.       10732452.
       3713414.5       10732329.       3713399.5       10732270.
        3713412.       10732186.        3713477.       10732069.
       3713481.5       10731946.        3713514.       10731870.
       3713491.5       10731804.      3713435.75       10731761.
       3713408.5       10731711.        3713358.       10731676.
      3713335.75       10731602.      3713308.25       10731576.
       3713261.5       10731494.      3713251.75       10731450.
      3713268.25       10731350.       3713257.5       10731242.
      3713234.25       10731204.        3713270.       10731161.

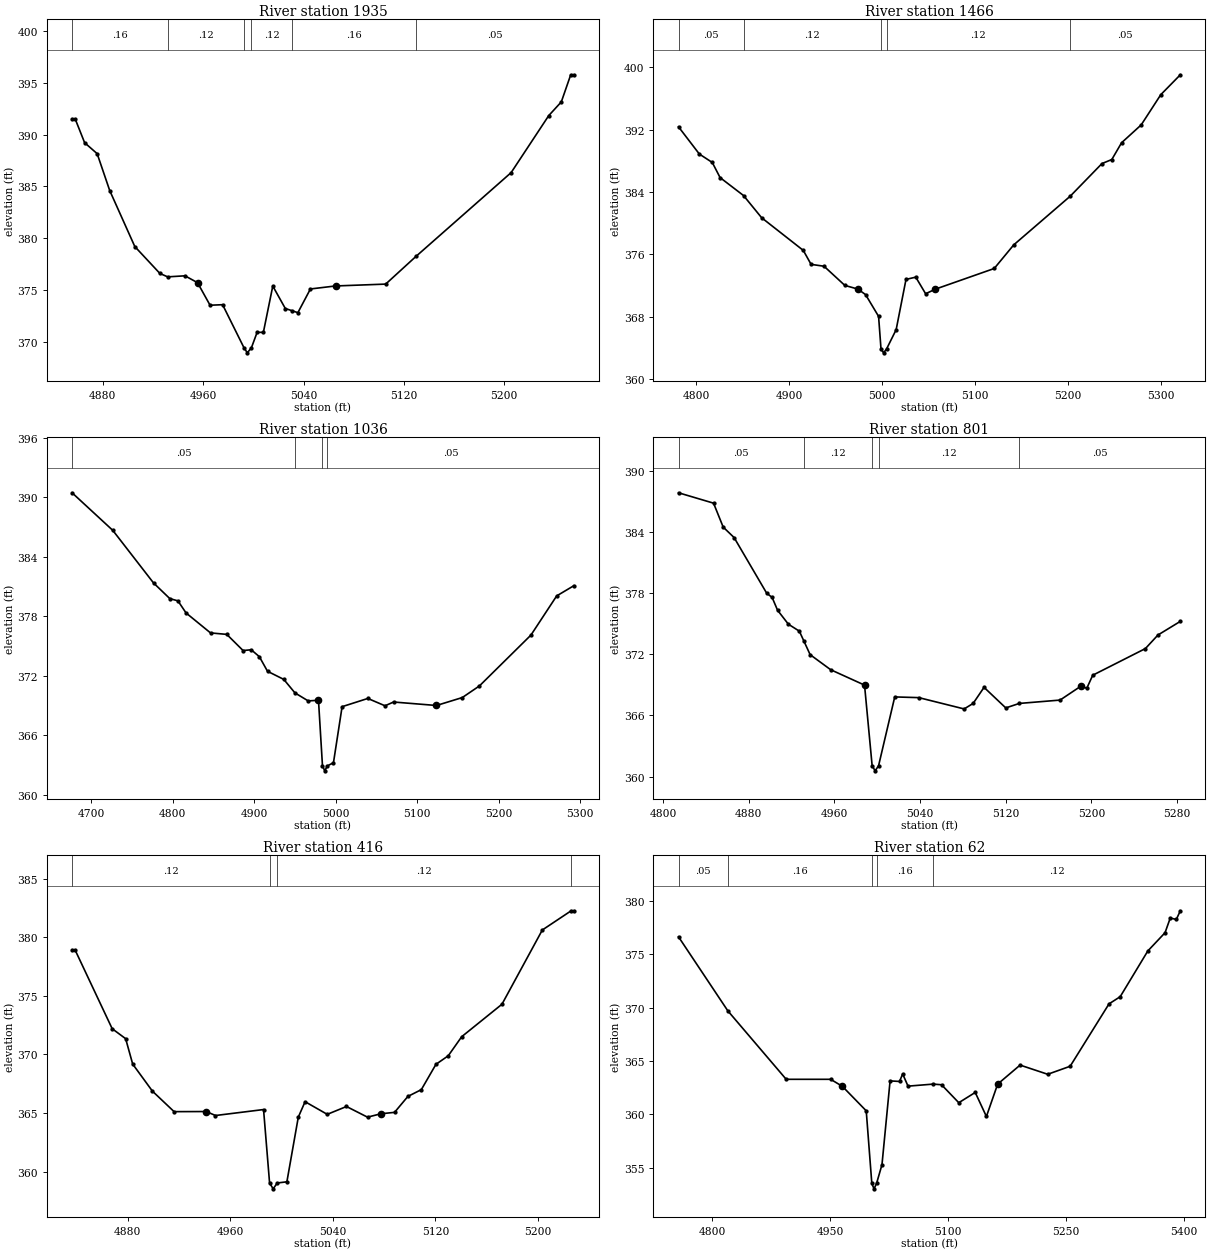
Type RM Length L Ch R = 1 ,1935    ,469,469,469
BEGIN DESCRIPTION:
UNT 097 IN CACR 4.0
END DESCRIPTION:
XS GIS Cut Line= 3
      3713449.56     10732910.19      3713299.61     10732910.19
      3713049.56     10732910.19
#Sta/Elev= 30
  4855.5  391.51    4858  391.51  4865.5  389.22  4875.5  388.16  4885.5   384.6
  4905.5  379.19  4925.5  376.59  4931.7  376.26  4945.5  376.36  4955.5   375.7
  4965.5  373.52  4975.5  373.57  4992.5  369.42  4995.2  368.92  4998.5  369.42
    5003   370.9    5008   370.9  5015.5  375.37  5025.5   373.2  5030.6     373
  5035.5   372.8  5045.5  375.09  5065.5  375.38  5105.5  375.56  5129.6  378.23
  5205.5  386.33  5235.5  391.84  5245.5  393.16    5253  395.78  5255.5  395.78
#Mann= 6 ,-1 , 0
  4855.5     .16       0  4931.7     .12       0  4992.5     .07       0
  4998.5     .12       0  5030.6     .16       0  5129.6     .05       0
Bank Sta=4955.5,5065.5
XS Rating Curve= 0 ,0
Exp/Cntr=0.3,0.1

Type RM Length L Ch R = 1 ,1466    ,430,430,430
BEGIN DESCRIPTION:
UNT 097 IN CACR 3.0
END DESCRIPTION:
XS GIS Cut Line= 3
      3713549.61     10732560.19      3713349.61     10732460.19
      3713049.64     10732560.18
#Sta/Elev= 30
  4781.3  392.37  4803.7  388.88  4817.6   387.8    4826  385.86  4851.2  383.56
  4870.7  380.71  4915.5  376.52  4923.9  374.73  4937.8  374.49  4960.2  372.03
  4974.2  371.56  4982.5  370.85  4996.5  368.06  4999.1  363.88  5001.9  363.38
  5005.1  363.88  5015.4  366.35    5026   372.8  5036.5  373.09  5047.1  370.96
  5057.6  371.55  5120.9   374.2  5141.9  377.23  5202.7  383.48  5236.8  387.66
  5247.4  388.18  5257.9  390.33    5279  392.62  5300.1   396.5  5321.1  399.05
#Mann= 5 ,-1 , 0
  4781.3     .05       0  4851.2     .12       0  4999.1     .07       0
  5005.1     .12       0  5202.7     .05       0
Bank Sta=4974.2,5057.6
XS Rating Curve= 0 ,0
Exp/Cntr=0.3,0.1

Type RM Length L Ch R = 1 ,1036    ,235,235,235
BEGIN DESCRIPTION:
UNT 097 IN CACR 2.0
END DESCRIPTION:
XS GIS Cut Line= 3
      3713799.57     10732060.19      3713499.61     10732060.19
       3713199.6     10732160.19
#Sta/Elev= 30
  4676.3  390.43  4726.3  386.64  4776.3  381.34  4796.3  379.76  4806.3  379.53
  4816.3  378.31  4846.3   376.3  4866.3  376.15  4886.3  374.52  4896.3   374.6
  4906.3   373.9  4916.3  372.43  4936.3  371.61    4950  370.25  4966.3  369.44
  4978.9  369.51  4983.8  362.89  4986.6  362.39  4989.8  362.89  4997.3  363.21
  5007.9  368.86  5039.5  369.69  5060.6  368.95  5071.1  369.33  5123.8  368.98
  5155.5  369.78  5176.5  370.95  5239.8  376.08  5271.4  380.03  5292.5  381.06
#Mann= 4 ,-1 , 0
  4676.3     .05       0    4950     .16       0  4983.8     .03       0
  4989.8     .05       0
Bank Sta=4978.9,5123.8
XS Rating Curve= 0 ,0
Exp/Cntr=0.3,0.1

Type RM Length L Ch R = 1 ,801     ,385,385,385
BEGIN DESCRIPTION:
Mapping XS 99d81181
END DESCRIPTION:
XS GIS Cut Line= 2
      3713690.73      10731810.3      3713228.99     10731890.15
#Sta/Elev= 30
  4814.5  387.87  4847.2  386.85  4856.2   384.5  4866.4  383.47  4896.8  378.01
  4901.9  377.59    4907  376.33  4917.1  374.96  4927.3  374.28  4931.6   373.3
  4937.4  371.97  4956.6  370.49  4988.2  368.98  4995.3  361.06  4998.1  360.56
  5001.3  361.06  5016.4  367.82  5038.9  367.75  5081.2  366.64  5089.6  367.18
  5099.8  368.76  5120.1  366.74  5132.7  367.18  5170.8  367.51  5190.7  368.91
  5195.7  368.66  5201.3  369.95  5250.5  372.57  5262.2   373.9  5283.1  375.24
#Mann= 5 ,-1 , 0
  4814.5     .05       0  4931.6     .12       0  4995.3     .07       0
  5001.3     .12       0  5132.7     .05       0
Bank Sta=4988.2,5190.7
XS Rating Curve= 0 ,0
Exp/Cntr=0.3,0.1

Type RM Length L Ch R = 1 ,416     ,354,354,354
BEGIN DESCRIPTION:
Mapping XS 65779065
END DESCRIPTION:
XS GIS Cut Line= 2
      3713449.42     10731490.86      3713076.15     10731608.92
#Sta/Elev= 30
  4836.5  378.89    4839  378.89  4867.8   372.2  4878.3  371.35  4883.8  369.18
  4899.2  366.87  4916.1  365.12  4941.2  365.13  4948.4  364.79  4985.9   365.3
  4990.6  359.03  4993.4  358.53  4996.6  359.03  5004.1  359.13    5013  364.65
  5018.3  365.97  5035.6  364.89  5050.6  365.56    5067  364.65  5077.5  364.94
  5088.1  365.06  5098.5  366.42    5109     367  5120.4  369.16    5130  369.89
  5140.5  371.52  5171.9  374.29  5203.4  380.63  5225.9  382.27    5228  382.27
#Mann= 4 ,-1 , 0
  4836.5     .12       0  4990.6     .07       0  4996.6     .12       0
  5225.9     .05       0
Bank Sta=4941.2,5077.5
XS Rating Curve= 0 ,0
Exp/Cntr=0.3,0.1

Type RM Length L Ch R = 1 ,62      ,0,0,0
BEGIN DESCRIPTION:
UNT 097 IN CACR 1.0
END DESCRIPTION:
XS GIS Cut Line= 4
      3713395.66     10731374.56      3713281.05     10731214.81
      3713197.72     10731202.66      3712927.94     10731436.12
#Sta/Elev= 30
  4757.5  376.62  4820.2  369.69  4894.3  363.29  4950.8  363.29  4965.7  362.63
    4996  360.34  5003.1  353.54  5005.9  353.04  5009.1  353.54    5016   355.3
  5026.3  363.14  5038.3  363.09  5042.3  363.79  5049.1  362.65    5081  362.84
  5091.7  362.78  5113.6   361.1  5134.5  362.06  5148.7  359.81    5163  362.84
  5191.5  364.62  5226.6  363.76  5255.1  364.51  5304.5  370.35  5318.7  371.02
  5353.8   375.3  5375.7  377.01  5382.3  378.38    5390  378.25  5395.1  379.06
#Mann= 5 ,-1 , 0
  4757.5     .05       0  4820.2     .16       0  5003.1     .07       0
  5009.1     .16       0    5081     .12       0
Bank Sta=4965.7,5163
XS Rating Curve= 0 ,0
Exp/Cntr=0.3,0.1

Chan Stop Cuts=-1
Use User Specified Reach Order=0
Composite Channel Slope=5