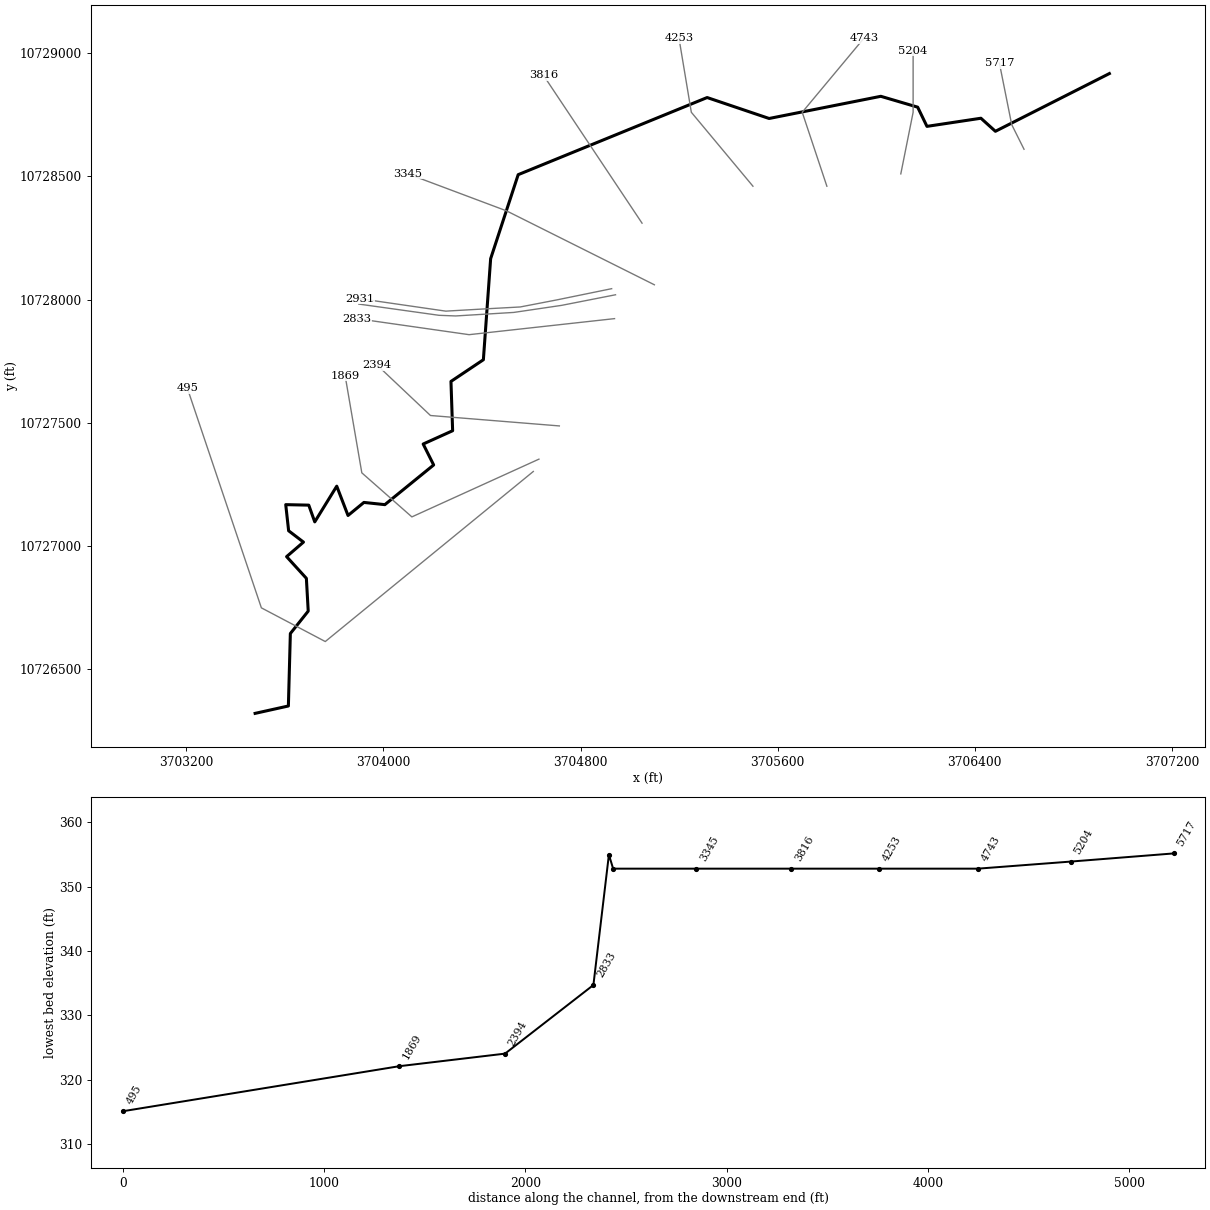
--- UNT 100 IN CACR.prj (project) ---

Proj Title=UNT 100 IN CACR Base Level Engineering
Current Plan=p01
Default Exp/Contr=0.3,0.1
English Units
Geom File=g01
Flow File=f01
Plan File=p01
Y Axis Title=Elevation
X Axis Title(PF)=Main Channel Distance
X Axis Title(XS)=Station
BEGIN DESCRIPTION:
UNT 100 IN CACR
END DESCRIPTION:
DSS Export Rating Curves= 0
DSS Export Rating Curve Sorted= 0
DSS Export Volume Flow Curves= 0
DXF OffsetX= 0
DXF OffsetY= 0
DXF ScaleX= 1
DXF ScaleY= 10

--- UNT 100 IN CACR.p01 (plan) ---

Plan Title=Multiple Run
Short Identifier=Multiple
Geom File=g01
Flow File=f01
Subcritical Flow
K Sum by GR= 0
Std Step Tol= 0.01
Critical Tol= 0.01
Num of Std Step Trials= 20
Max Error Tol= 0.3
Flow Tol Ratio= 0.001
Split Flow NTrial= 30
Split Flow Tol= 0.02
Split Flow Ratio= 0.02
Log Output Level= 0
Friction Slope Method= 1
Unsteady Friction Slope Method= 2
Unsteady Bridges Friction Slope Method= 1
Parabolic Critical Depth
Global Vel Dist=  1 , 1 , 1
Global Log Level= 0
CheckData=True
Encroach Param= -1, 0, 0, 0
BEGIN DESCRIPTION:
Multiple Run
END DESCRIPTION:

--- UNT 100 IN CACR.f01 (steady flow) ---

Flow Title=Multiple
Program Version=4.10
Number of Profiles= 7
Profile Names=10-year,25-year,50-year,1pct_min,100-year,1pct_plu,500-year
River Rch & RM=UNT 100 IN CACR,Reach-1         ,5717
     442     586     702     619     837    1132    1188
Boundary for River Rch & Prof#=UNT 100 IN CACR,Reach-1         , 1
Up Type= 0
Dn Type= 3
Dn Slope=0.0051
Boundary for River Rch & Prof#=UNT 100 IN CACR,Reach-1         , 2
Up Type= 0
Dn Type= 3
Dn Slope=0.0051
Boundary for River Rch & Prof#=UNT 100 IN CACR,Reach-1         , 3
Up Type= 0
Dn Type= 3
Dn Slope=0.0051
Boundary for River Rch & Prof#=UNT 100 IN CACR,Reach-1         , 4
Up Type= 0
Dn Type= 3
Dn Slope=0.0051
Boundary for River Rch & Prof#=UNT 100 IN CACR,Reach-1         , 5
Up Type= 0
Dn Type= 3
Dn Slope=0.0051
Boundary for River Rch & Prof#=UNT 100 IN CACR,Reach-1         , 6
Up Type= 0
Dn Type= 3
Dn Slope=0.0051
Boundary for River Rch & Prof#=UNT 100 IN CACR,Reach-1         , 7
Up Type= 0
Dn Type= 3
Dn Slope=0.0051
DSS Import GetInterval= 0
DSS Import GetPeak= 0
DSS Import FillOption= 0

--- UNT 100 IN CACR.g01 (geometry) ---

Geom Title=Existing Conditions
Program Version=4.10

River Reach=UNT 100 IN CACR ,Reach-1
Reach XY= 30
      3706945.97     10728917.31       3706483.5       10728683.
      3706424.75       10728736.      3706205.75       10728703.
        3706168.       10728781.       3706018.5       10728825.
      3705565.25       10728735.      3705313.75       10728820.
        3704547.       10728507.      3704435.25       10728166.
      3704405.75       10727756.      3704274.25       10727668.
        3704281.       10727468.       3704161.5       10727414.
        3704204.       10727329.        3704006.       10727168.
        3703921.       10727177.       3703856.5       10727124.
      3703810.75       10727243.       3703721.5       10727098.
      3703697.25       10727166.      3703603.75       10727168.
       3703615.5       10727062.      3703675.75       10727016.
      3703607.25       10726957.       3703687.5       10726869.
        3703695.       10726736.       3703622.5       10726645.
       3703614.5       10726351.       3703479.5       10726321.

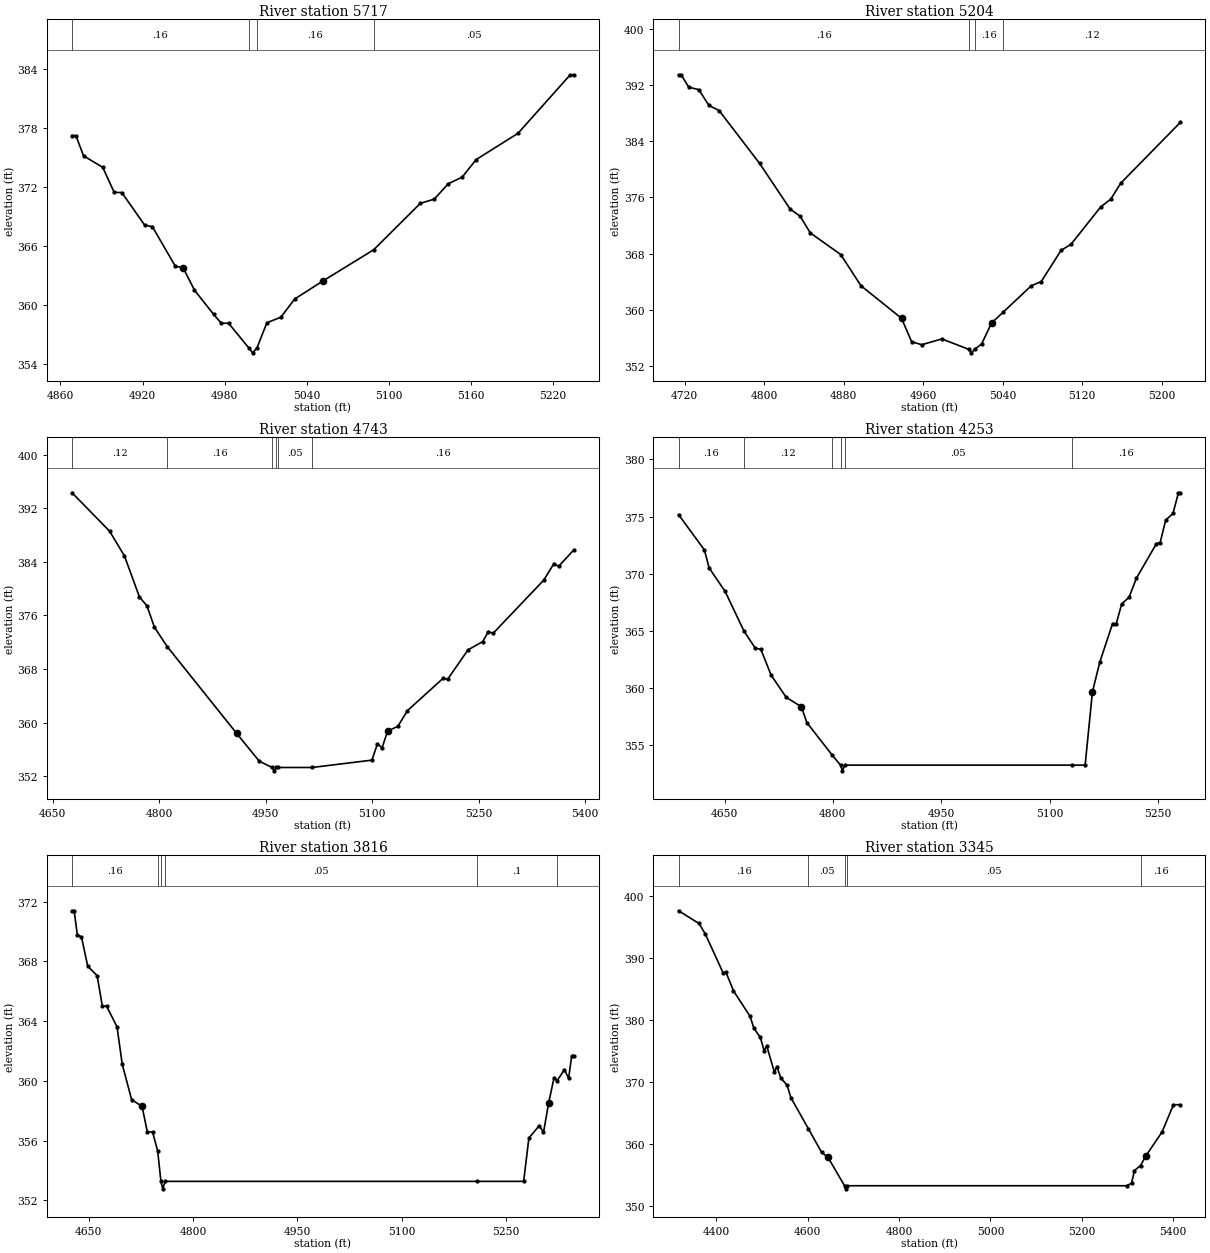
Type RM Length L Ch R = 1 ,5717    ,513,513,513
BEGIN DESCRIPTION:
UNT 100 IN CACR 9.0
END DESCRIPTION:
XS GIS Cut Line= 3
      3706599.63     10728610.15      3706549.61     10728710.19
      3706499.61     10728960.19
#Sta/Elev= 30
  4868.5  377.24  4871.3  377.24  4876.9  375.18  4890.9  374.01  4899.3  371.47
  4904.9  371.44  4921.6  368.13  4927.2  367.98    4944  363.95  4949.6  363.82
    4958  361.52    4972  359.06  4977.6  358.16  4982.9  358.16  4997.7  355.65
  5000.5  355.15  5003.7  355.65  5010.9  358.21  5021.1  358.77  5031.3  360.63
  5051.7  362.44    5089  365.63  5123.1  370.35  5133.3  370.78  5143.5  372.34
  5153.7  373.02  5163.9   374.8  5194.5  377.47  5232.7  383.42  5235.3  383.42
#Mann= 4 ,-1 , 0
  4868.5     .16       0  4997.7     .07       0  5003.7     .16       0
    5089     .05       0
Bank Sta=4949.6,5051.7
XS Rating Curve= 0 ,0
Exp/Cntr=0.3,0.1

Type RM Length L Ch R = 1 ,5204    ,461,461,461
BEGIN DESCRIPTION:
UNT 100 IN CACR 8.0
END DESCRIPTION:
XS GIS Cut Line= 3
       3706099.6     10728510.15      3706149.61     10728760.19
      3706149.61      10729010.2
#Sta/Elev= 30
  4713.9  393.47  4716.5  393.47  4724.1  391.71  4734.3  391.35  4744.5   389.1
  4754.7  388.38  4795.5  380.84  4826.1  374.37  4836.3  373.32  4846.5  370.95
  4877.1  367.88  4897.5  363.43  4938.3   358.8  4948.5  355.45  4958.7  355.04
  4978.9  355.86  5005.9  354.38  5008.6  353.88  5011.9  354.38  5018.9  355.14
  5028.9  358.13  5040.7  359.68  5068.9  363.43  5078.9  364.03  5098.9  368.47
  5108.9  369.34  5138.9  374.68  5148.9  375.76  5158.9  378.03  5218.9  386.69
#Mann= 4 ,-1 , 0
  4713.9     .16       0  5005.9     .07       0  5011.9     .16       0
  5040.7     .12       0
Bank Sta=4938.3,5028.9
XS Rating Curve= 0 ,0
Exp/Cntr=0.3,0.1

Type RM Length L Ch R = 1 ,4743    ,490,490,490
BEGIN DESCRIPTION:
UNT 100 IN CACR 7.0
END DESCRIPTION:
XS GIS Cut Line= 3
      3705799.62     10728460.14      3705699.61     10728760.19
      3705949.62      10729060.2
#Sta/Elev= 30
  4677.1  394.33  4729.9   388.6  4750.9  384.89    4772  378.76  4782.6  377.44
  4793.1  374.24  4811.4  371.31    4909  358.37  4940.7  354.23  4958.8  353.28
  4961.5  352.78  4964.8  353.28  4966.6  353.28  5015.2  353.28  5099.5  354.38
  5107.3  356.84  5113.8  356.21  5121.6  358.73  5135.9  359.42  5149.6  361.78
  5199.7   366.6  5206.2  366.47  5234.8  370.85  5255.7   372.1  5263.5   373.6
    5270  373.31  5341.6  381.28  5355.9  383.76  5362.4  383.32  5383.9   385.8
#Mann= 6 ,-1 , 0
  4677.1     .12       0  4811.4     .16       0  4958.8    .033       0
  4964.8     .16       0  4966.6     .05       0  5015.2     .16       0
Bank Sta=4909,5121.6
XS Rating Curve= 0 ,0
Exp/Cntr=0.3,0.1

Type RM Length L Ch R = 1 ,4253    ,437,437,437
BEGIN DESCRIPTION:
UNT 100 IN CACR 6.0
END DESCRIPTION:
XS GIS Cut Line= 3
      3705499.61     10728460.18      3705249.61     10728760.19
       3705199.6     10729060.23
#Sta/Elev= 30
  4586.4  375.18  4622.2  372.09  4628.7  370.52  4650.8  368.47    4677     365
  4692.5  363.51  4700.3   363.4  4714.6  361.14  4735.5   359.2  4756.3  358.39
  4764.1  356.99  4798.8  354.18  4810.6  353.28  4813.3  352.78  4816.6  353.28
  5130.9  353.28  5149.3  353.28  5159.4  359.68  5169.5  362.26  5187.3  365.66
  5192.3  365.63    5200  367.38  5210.1  367.95  5220.2  369.61  5248.1  372.65
  5253.2  372.74  5260.8   374.7  5270.9  375.28  5278.5  377.09  5281.1  377.09
#Mann= 6 ,-1 , 0
  4586.4     .16       0    4677     .12       0  4798.8     .05       0
  4810.6    .033       0  4816.6     .05       0  5130.9     .16       0
Bank Sta=4756.3,5159.4
XS Rating Curve= 0 ,0
Exp/Cntr=0.3,0.1

Type RM Length L Ch R = 1 ,3816    ,471,471,471
BEGIN DESCRIPTION:
UNT 100 IN CACR 5.0
END DESCRIPTION:
XS GIS Cut Line= 3
       3705049.6     10728310.21      3704849.61     10728610.19
       3704649.6      10728910.2
#Sta/Elev= 30
  4626.2  371.39  4629.2  371.39  4633.7   369.8  4639.7  369.64  4648.7  367.68
  4662.2  367.05  4669.7  365.02  4675.8  365.01  4690.8  363.62  4698.3  361.12
  4711.8  358.75  4726.8   358.3  4734.3   356.6  4741.9  356.58  4749.2  355.32
  4753.9  353.28  4756.6  352.78  4759.9  353.28  5208.6  353.28  5275.2  353.28
  5282.7  356.18  5297.7  357.01  5303.7  356.56  5311.2  358.54  5318.7  360.19
  5323.5  360.03  5333.8  360.76  5339.8  360.17  5344.3  361.69  5347.3  361.69
#Mann= 6 ,-1 , 0
  4626.2     .16       0  4749.2     .05       0  4753.9    .033       0
  4759.9     .05       0  5208.6      .1       0  5323.5     .16       0
Bank Sta=4726.8,5311.2
XS Rating Curve= 0 ,0
Exp/Cntr=0.3,0.1

Type RM Length L Ch R = 1 ,3345    ,414,414,414
BEGIN DESCRIPTION:
UNT 100 IN CACR 4.0
END DESCRIPTION:
XS GIS Cut Line= 3
      3705099.61     10728060.19      3704499.61     10728360.19
      3704099.63     10728510.18
#Sta/Elev= 30
  4317.5  397.68  4362.2  395.63  4376.2  393.91  4415.3   387.6  4420.9  387.81
  4437.7  384.75    4474  380.63  4482.4   378.7  4496.4  377.23  4504.8  375.09
  4510.4  375.87  4527.1  371.64  4532.7  372.53  4541.1   370.7  4555.1  369.49
  4563.5  367.47  4601.5   362.5  4630.5  358.68  4644.5  357.87  4680.7  353.28
  4683.4  352.78  4686.7  353.28    5298  353.28  5308.7  353.68  5314.9  355.72
  5328.5  356.54  5339.9  358.09  5375.5  361.95  5400.4  366.36  5415.5  366.37
#Mann= 5 ,-1 , 0
  4317.5     .16       0  4601.5     .05       0  4680.7    .033       0
  4686.7     .05       0  5328.5     .16       0
Bank Sta=4644.5,5339.9
XS Rating Curve= 0 ,0
Exp/Cntr=0.3,0.1

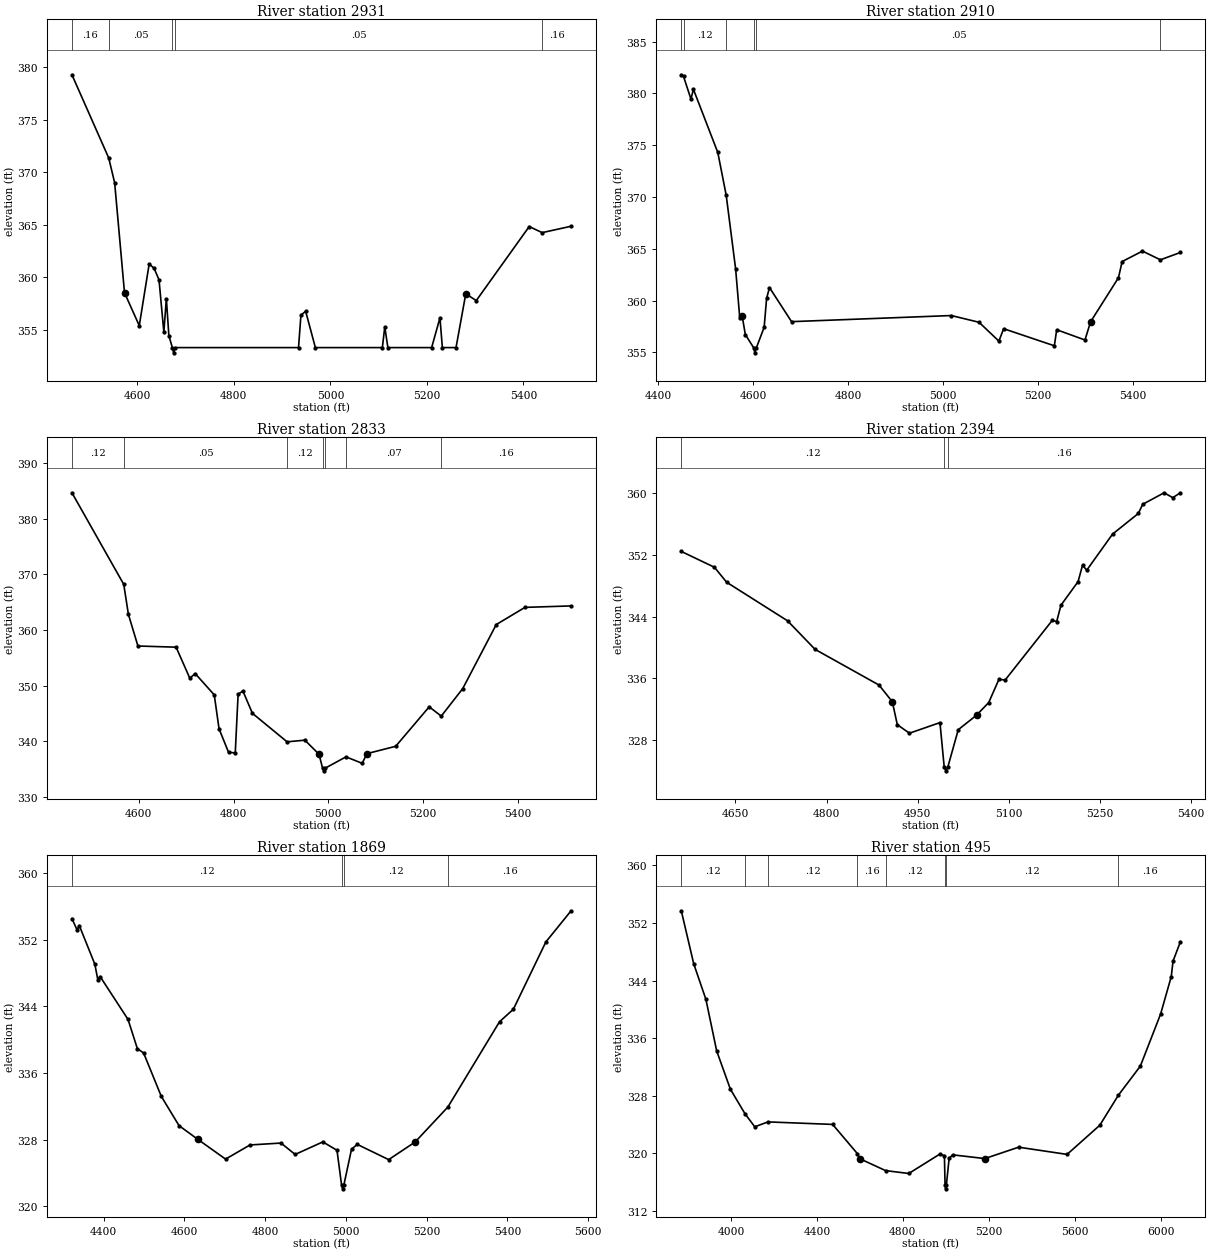
Type RM Length L Ch R = 1 ,2931    ,21,21,21
BEGIN DESCRIPTION:
Mapping XS 54237c7b
END DESCRIPTION:
XS GIS Cut Line= 6
      3704926.32     10728044.37      3704703.66      10727998.8
      3704555.23     10727970.16        3704412.     10727962.34
      3704253.14     10727953.23       3703903.7     10728003.89
#Sta/Elev= 30
  4464.6  379.29  4540.8  371.36  4553.1  368.99  4573.5  358.51  4604.1  355.37
  4624.6  361.25  4634.8  360.84    4645  359.74    4655  354.75  4660.2  357.95
  4665.4  354.42  4672.6  353.28  4675.3  352.78  4678.6  353.28    4934  353.28
    4939  356.38  4948.8  356.74  4968.9  353.28  5107.7  353.28  5112.7  355.26
  5119.1  353.28  5209.8  353.28    5227  356.12    5232  353.28  5260.3  353.28
  5280.5  358.41  5302.2  357.76  5411.9  364.82  5438.8  364.24  5498.7  364.85
#Mann= 5 ,-1 , 0
  4464.6     .16       0  4540.8     .05       0  4672.6     .03       0
  4678.6     .05       0  5438.8     .16       0
Bank Sta=4573.5,5280.5
XS Rating Curve= 0 ,0
Exp/Cntr=0.3,0.1

Type RM Length L Ch R = 1 ,2910    ,77,77,77
BEGIN DESCRIPTION:
Mapping XS 1ba12ea5
END DESCRIPTION:
XS GIS Cut Line= 6
      3704941.97     10728019.64       3704723.2     10727976.67
      3704529.19     10727948.02      3704293.51      10727933.7
       3704225.8      10727936.3      3703900.31     10727981.87
#Sta/Elev= 30
  4448.2  381.79  4452.9  381.63  4468.6  379.44  4473.7  380.39  4525.1  374.29
  4542.8  370.17  4562.7  363.04  4571.4  358.32  4576.5  358.49  4583.1  356.72
  4600.5  355.45  4603.2  354.95  4606.5  355.45  4622.8  357.42  4627.9   360.2
    4634  361.25  4680.5  357.96  5017.1  358.55  5075.5   357.9  5117.3  356.08
  5127.3  357.28  5234.1  355.63  5239.1  357.18  5298.6  356.19  5310.5  357.95
  5369.2   362.2  5376.9  363.76  5419.7  364.77  5457.6  363.93  5499.8  364.64
#Mann= 6 ,-1 , 0
  4448.2     .16       0  4452.9     .12       0  4542.8     .05       0
  4600.5     .03       0  4606.5     .05       0  5457.6     .16       0
Bank Sta=4576.5,5310.5
XS Rating Curve= 0 ,0
Exp/Cntr=0.3,0.1

Type RM Length L Ch R = 1 ,2833    ,439,439,439
BEGIN DESCRIPTION:
UNT 100 IN CACR 3.0
END DESCRIPTION:
XS GIS Cut Line= 3
        3704938.     10727922.84      3704347.76     10727857.74
      3703893.29     10727922.67
#Sta/Elev= 30
  4459.2  384.64  4568.5  368.19  4578.3   362.8  4598.4  357.12  4678.9  356.91
  4707.8  351.34  4719.2  352.17  4759.4  348.34  4769.5  342.25  4789.6  338.01
  4803.7  337.93  4809.7  348.45  4819.8  349.04  4839.9  345.03    4913  339.91
  4950.5  340.21  4980.4  337.68  4987.8   335.2  4990.5   334.7  4993.8   335.2
  5037.3  337.21  5071.4  336.05  5081.5  337.79  5142.1  339.11  5212.8   346.2
  5238.2  344.53  5283.5  349.47  5354.2  360.97  5414.8  364.06  5512.1  364.32
#Mann= 7 ,-1 , 0
  4459.2     .12       0  4568.5     .05       0    4913     .12       0
  4987.8     .07       0  4993.8     .12       0  5037.3     .07       0
  5238.2     .16       0
Bank Sta=4980.4,5081.5
XS Rating Curve= 0 ,0
Exp/Cntr=0.3,0.1

Type RM Length L Ch R = 1 ,2394    ,525,525,525
BEGIN DESCRIPTION:
UNT 100 IN CACR 2.0
END DESCRIPTION:
XS GIS Cut Line= 3
      3704714.02     10727487.43      3704191.06     10727529.74
      3703975.14     10727733.72
#Sta/Elev= 30
  4560.8  352.43  4615.4  350.38  4635.5  348.44  4735.8  343.45    4781  339.76
  4886.3  335.14  4908.2  332.98  4916.4  330.01  4936.4  328.91  4986.6  330.28
  4993.6  324.54  4996.4  324.04  4999.6  324.54  5016.7  329.36  5046.8  331.24
  5066.9  332.88  5083.7  335.88  5093.9  335.79  5171.5  343.51  5178.8  343.36
  5185.7  345.46    5214  348.53  5221.3  350.65  5228.2     350  5270.7  354.67
  5313.1  357.34  5320.4  358.53  5355.6  360.02  5369.8  359.39  5382.5  360.02
#Mann= 3 ,-1 , 0
  4560.8     .12       0  4993.6     .07       0  4999.6     .16       0
Bank Sta=4908.2,5046.8
XS Rating Curve= 0 ,0
Exp/Cntr=0.3,0.1

Type RM Length L Ch R = 1 ,1869    ,1374,1374,1374
BEGIN DESCRIPTION:
Mapping XS f1dfb3c3
END DESCRIPTION:
XS GIS Cut Line= 4
      3704631.26     10727352.67      3704115.61     10727118.28
      3703912.49      10727297.1      3703844.78     10727691.19
#Sta/Elev= 30
  4321.1  354.55  4333.8  353.19  4339.3  353.72  4377.8  349.08  4385.4  347.17
  4390.9  347.59  4460.1  342.44  4483.2  338.93  4498.7  338.41  4542.6  333.19
  4586.5  329.68  4632.6  328.05  4701.8  325.66  4762.3  327.36  4839.2  327.59
  4874.2  326.22  4942.8  327.73  4977.9  326.72  4989.1  322.59  4991.9  322.09
  4995.1  322.59  5013.9  326.85  5028.1  327.43  5105.9   325.6  5171.4  327.71
  5252.7  331.92  5380.6  342.16  5414.9  343.66  5495.5  351.75    5558  355.49
#Mann= 4 ,-1 , 0
  4321.1     .12       0  4989.1     .07       0  4995.1     .12       0
  5252.7     .16       0
Bank Sta=4632.6,5171.4
XS Rating Curve= 0 ,0
Exp/Cntr=0.3,0.1

Type RM Length L Ch R = 1 ,495     ,0,0,0
BEGIN DESCRIPTION:
UNT 100 IN CACR 1.0
END DESCRIPTION:
XS GIS Cut Line= 4
      3704608.42     10727302.62      3703764.22     10726612.51
      3703504.89     10726749.23      3703204.47     10727640.73
#Sta/Elev= 30
  3768.3  353.68  3826.2  346.32    3883  341.38  3933.1  334.23    3997  328.91
    4065  325.51  4110.4   323.7  4172.1  324.38    4473  324.03  4587.8  319.99
  4600.8  319.25  4719.6  317.62  4827.6  317.22  4971.5   319.9  4993.5   319.7
  4996.5  315.59  4999.3  315.09  5002.5  315.59  5015.5  319.32  5031.9  319.81
  5181.6  319.29  5339.1  320.87  5564.7  319.87  5716.9  323.91  5803.9   328.1
  5905.8  332.12  6000.3  339.36  6049.8  344.55    6058  346.69  6092.6   349.4
#Mann= 8 ,-1 , 0
  3768.3     .12       0    4065     .16       0  4172.1     .12       0
  4587.8     .16       0  4719.6     .12       0  4996.5     .07       0
  5002.5     .12       0  5803.9     .16       0
Bank Sta=4600.8,5181.6
XS Rating Curve= 0 ,0
Exp/Cntr=0.3,0.1

Chan Stop Cuts=-1
Use User Specified Reach Order=0
Composite Channel Slope=5