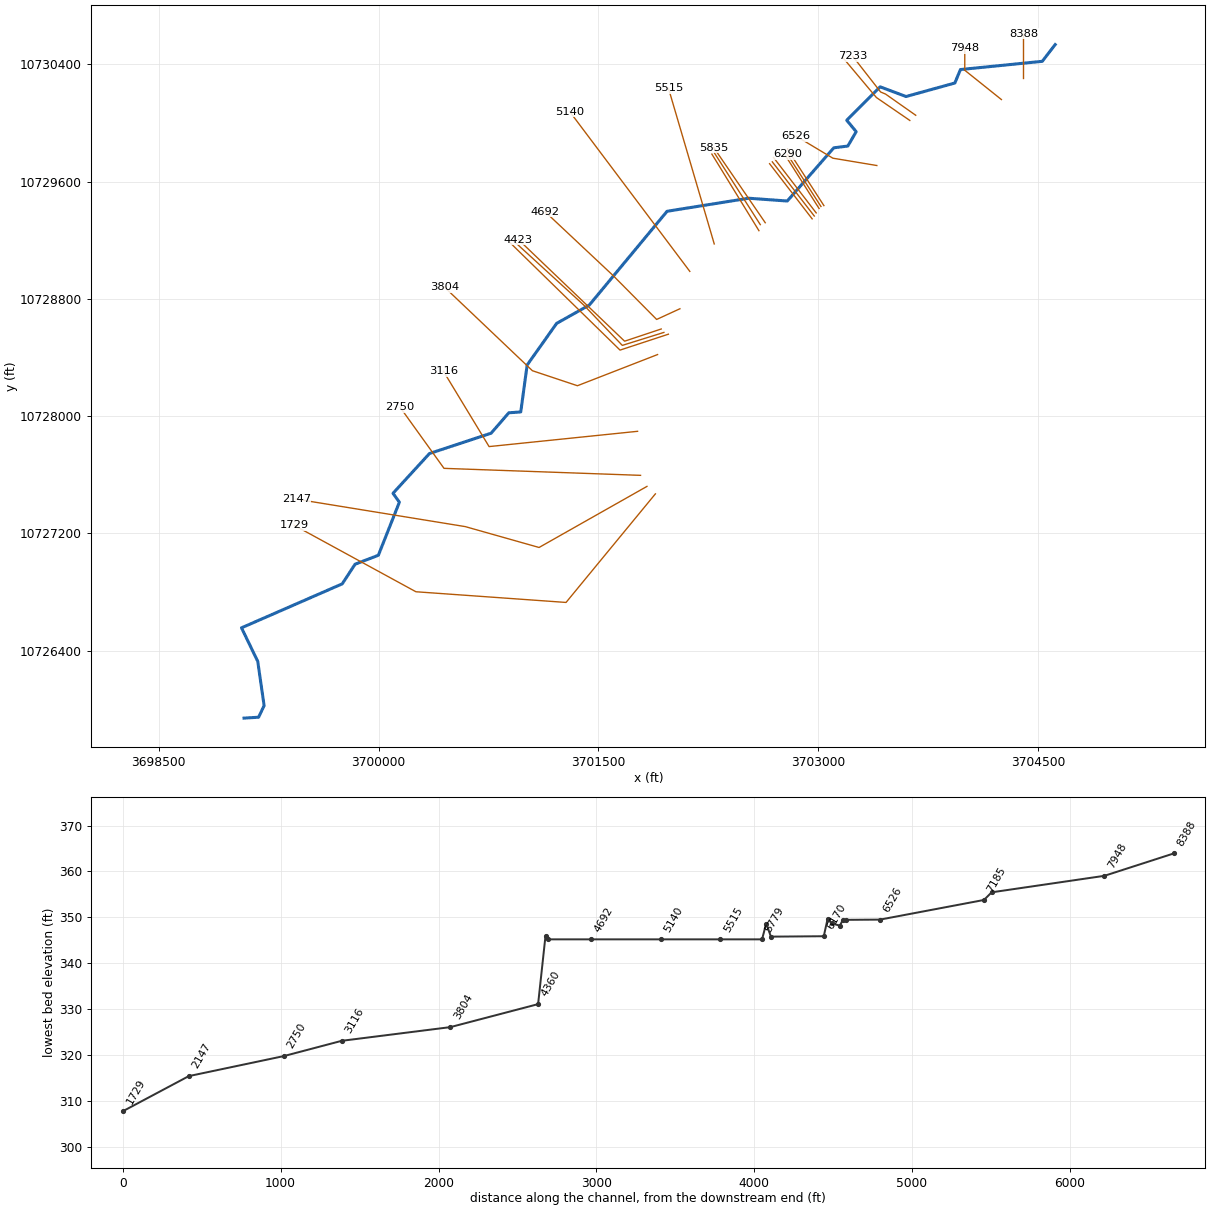
--- UNT 101 IN CACR.prj (project) ---

Proj Title=UNT 101 IN CACR Base Level Engineering
Current Plan=p01
Default Exp/Contr=0.3,0.1
English Units
Geom File=g01
Flow File=f01
Plan File=p01
BEGIN DESCRIPTION:
UNT 101 IN CACR
END DESCRIPTION:

--- UNT 101 IN CACR.p01 (plan) ---

Plan Title=Multiple Run
Short Identifier=Multiple
Geom File=g01
Flow File=f01
Subcritical Flow
K Sum by GR= 0
Std Step Tol= 0.01
Critical Tol= 0.01
Num of Std Step Trials= 20
Max Error Tol= 0.3
Flow Tol Ratio= 0.001
Split Flow NTrial= 30
Split Flow Tol= 0.02
Split Flow Ratio= 0.02
Log Output Level= 0
Friction Slope Method= 1
Unsteady Friction Slope Method= 2
Unsteady Bridges Friction Slope Method= 1
Parabolic Critical Depth
Global Vel Dist=  1 , 1 , 1
Global Log Level= 0
CheckData=True
Encroach Param= -1, 0, 0, 0
BEGIN DESCRIPTION:
Multiple Run
END DESCRIPTION:

--- UNT 101 IN CACR.f01 (steady flow) ---

Flow Title=Multiple
Number of Profiles=7
Profile Names=10-year,25-year,50-year,1pct_min,100-year,1pct_plu,500-year
River Rch & RM= UNT 101 IN CACR,Reach-1,8388
     286     368     432     374     506     684     692
River Rch & RM= UNT 101 IN CACR,Reach-1,7233
     489     651     782     689     932    1261    1328
Boundary for River Rch & Prof#=UNT 101 IN CACR,Reach-1,1
Up Type=0
Dn Type=3
Dn Slope=0.005
Boundary for River Rch & Prof#=UNT 101 IN CACR,Reach-1,2
Up Type=0
Dn Type=3
Dn Slope=0.005
Boundary for River Rch & Prof#=UNT 101 IN CACR,Reach-1,3
Up Type=0
Dn Type=3
Dn Slope=0.005
Boundary for River Rch & Prof#=UNT 101 IN CACR,Reach-1,4
Up Type=0
Dn Type=3
Dn Slope=0.005
Boundary for River Rch & Prof#=UNT 101 IN CACR,Reach-1,5
Up Type=0
Dn Type=3
Dn Slope=0.005
Boundary for River Rch & Prof#=UNT 101 IN CACR,Reach-1,6
Up Type=0
Dn Type=3
Dn Slope=0.005
Boundary for River Rch & Prof#=UNT 101 IN CACR,Reach-1,7
Up Type=0
Dn Type=3
Dn Slope=0.005

--- UNT 101 IN CACR.g01 (geometry) ---

Geom Title=Existing Conditions

River Reach=UNT 101 IN CACR,Reach-1
Reach XY= 30
      3704616.56     10730535.44      3704528.25     10730421.00
      3703970.25     10730365.00      3703931.75     10730273.00
      3703599.00     10730181.00      3703422.00     10730247.00
      3703194.25     10730019.00      3703258.75     10729941.00
      3703201.75     10729843.00      3703106.00     10729831.00
      3702788.75     10729468.00      3702525.75     10729487.00
      3701968.50     10729398.00      3701437.75     10728758.00
      3701215.00     10728633.00      3701013.75     10728349.00
      3700970.25     10728029.00      3700888.75     10728023.00
      3700768.25     10727884.00      3700347.25     10727745.00
      3700098.75     10727474.00      3700142.00     10727413.00
      3699998.75     10727051.00      3699839.75     10726990.00
      3699752.25     10726856.00      3699065.00     10726556.00
      3699175.75     10726327.00      3699219.25     10726025.00
      3699181.50     10725946.00      3699082.00     10725940.00

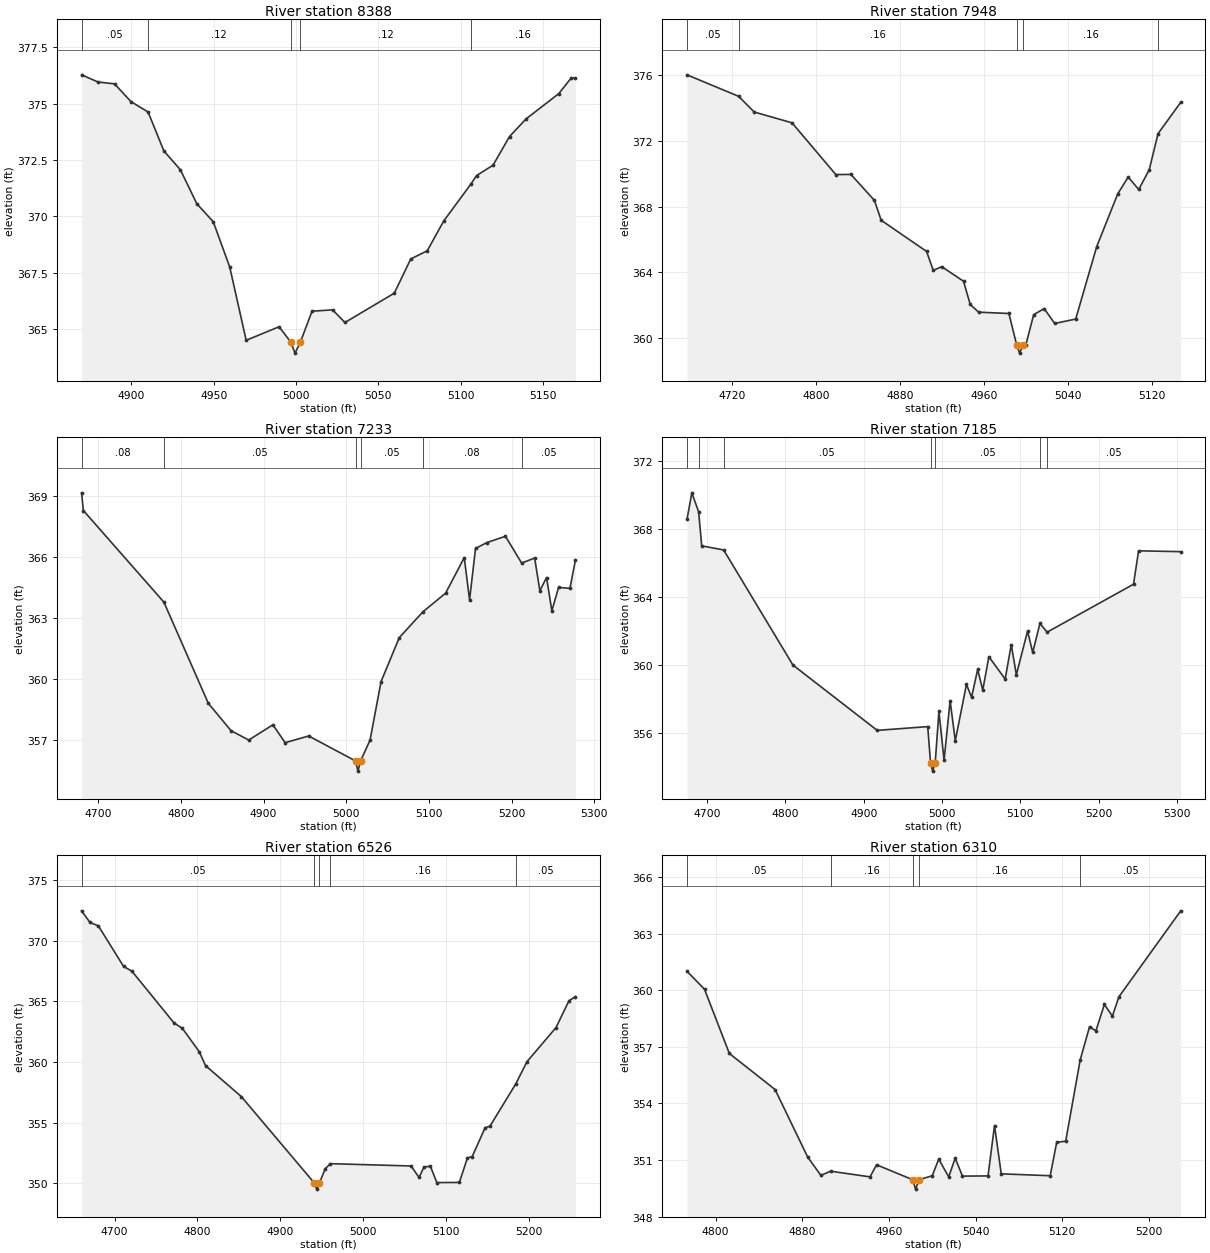
Type RM Length L Ch R = 1,8388,440,440,440
BEGIN DESCRIPTION:
UNT 101 IN CACR 13.0
END DESCRIPTION:
XS GIS Cut Line= 3
      3704399.61     10730310.23      3704399.61     10730460.19
      3704399.61     10730610.23
#Sta/Elev= 30
  4869.7  376.28  4879.7  375.96  4889.7  375.88  4899.7  375.09  4910.1  374.63
  4919.7  372.90  4929.7  372.07  4939.7  370.56  4949.7  369.76  4959.7  367.75
  4969.7  364.50  4989.7  365.10  4996.7  364.43  4999.4  363.93  5002.7  364.43
  5009.7  365.79  5022.2  365.85  5029.7  365.29  5059.7  366.59  5069.7  368.11
  5079.7  368.47  5089.7  369.79  5106.2  371.43  5109.7  371.81  5119.7  372.27
  5129.7  373.54  5139.7  374.32  5159.7  375.45  5167.2  376.14  5169.7  376.14
#Mann=5,-1,0
  4869.7    0.05       0  4910.1    0.12       0  4996.7    0.07       0
  5002.7    0.12       0  5106.2    0.16       0
Bank Sta=4996.7,5002.7
Exp/Cntr=0.3,0.1

Type RM Length L Ch R = 1,7948,715,715,715
BEGIN DESCRIPTION:
UNT 101 IN CACR 12.0
END DESCRIPTION:
XS GIS Cut Line= 3
      3704249.60     10730160.20      3703999.61     10730360.19
      3703999.61     10730510.14
#Sta/Elev= 30
  4677.2  376.04  4726.3  374.73  4741.2  373.77  4777.2  373.11  4818.9  369.95
  4833.3  369.96  4855.7  368.37  4862.1  367.16  4905.3  365.26  4911.7  364.10
  4919.7  364.33  4940.5  363.44  4946.9  362.02  4954.9  361.55  4983.7  361.47
  4991.1  359.55  4993.9  359.05  4997.1  359.55  4999.8  359.55  5007.3  361.40
  5017.3  361.77  5027.3  360.86  5047.3  361.13  5067.3  365.55  5087.3  368.77
  5097.3  369.80  5107.3  369.04  5117.3  370.24  5125.7  372.45  5147.3  374.36
#Mann=5,-1,0
  4677.2    0.05       0  4726.3    0.16       0  4991.1    0.07       0
  4997.1    0.16       0  5125.7    0.05       0
Bank Sta=4991.1,4997.1
Exp/Cntr=0.3,0.1

Type RM Length L Ch R = 1,7233,48,48,48
BEGIN DESCRIPTION:
UNT 101 IN CACR 11.0
END DESCRIPTION:
XS GIS Cut Line= 4
      3703664.97     10730053.05      3703459.23     10730197.59
      3703425.38     10730211.92      3703235.34     10730455.32
#Sta/Elev= 30
  4680.0  369.15  4682.1  368.28  4779.5  363.77  4833.2  358.79  4860.7  357.44
  4882.1  356.98  4911.3  357.73  4926.1  356.85  4954.6  357.18  5011.3  355.95
  5014.1  355.45  5017.3  355.95  5028.8  356.98  5042.1  359.86  5064.1  362.02
  5092.6  363.29  5120.1  364.21  5142.7  365.96  5149.1  363.88  5156.3  366.41
  5169.9  366.70  5192.5  367.01  5212.1  365.69  5227.8  365.94  5234.1  364.33
  5242.2  364.98  5248.6  363.34  5256.7  364.49  5270.5  364.45  5277.0  365.82
#Mann=6,-1,0
  4680.0    0.08       0  4779.5    0.05       0  5011.3    0.04       0
  5017.3    0.05       0  5092.6    0.08       0  5212.1    0.05       0
Bank Sta=5011.3,5017.3
Exp/Cntr=0.3,0.1

Type RM Length L Ch R = 1,7185,659,659,659
BEGIN DESCRIPTION:
UNT 101 IN CACR 10.0
END DESCRIPTION:
XS GIS Cut Line= 3
      3703624.70     10730017.69      3703396.84     10730173.94
      3703169.01     10730445.16
#Sta/Elev= 30
  4674.3  368.55  4680.5  370.11  4689.2  368.99  4693.1  367.00  4721.1  366.76
  4809.6  360.01  4917.2  356.18  4981.7  356.40  4985.3  354.29  4988.0  353.79
  4991.3  354.29  4996.0  357.29  5002.6  354.43  5010.3  357.92  5016.9  355.57
  5031.2  358.88  5037.7  358.12  5045.5  359.76  5052.0  358.54  5059.8  360.50
  5080.6  359.19  5088.4  361.20  5094.9  359.44  5109.2  362.00  5115.8  360.75
  5125.0  362.45  5134.2  361.94  5244.5  364.75  5251.0  366.71  5304.8  366.66
#Mann=7,-1,0
  4674.3    0.05       0  4689.2    0.08       0  4721.1    0.05       0
  4985.3    0.04       0  4991.3    0.05       0  5125.0    0.08       0
  5134.2    0.05       0
Bank Sta=4985.3,4991.3
Exp/Cntr=0.3,0.1

Type RM Length L Ch R = 1,6526,216,216,216
BEGIN DESCRIPTION:
UNT 101 IN CACR 9.0
END DESCRIPTION:
XS GIS Cut Line= 3
      3703399.56     10729710.20      3703099.61     10729760.19
      3702849.64     10729910.17
#Sta/Elev= 30
  4660.3  372.47  4670.4  371.51  4680.5  371.23  4710.9  367.89  4721.1  367.48
  4771.8  363.22  4781.9  362.77  4802.2  360.85  4809.8  359.70  4852.9  357.15
  4941.1  350.01  4943.9  349.51  4947.1  350.01  4954.3  351.20  4960.4  351.61
  5057.7  351.42  5067.4  350.47  5073.2  351.32  5081.0  351.41  5088.8  350.05
  5116.0  350.06  5125.7  352.08  5131.5  352.20  5147.1  354.58  5152.9  354.70
  5184.1  358.20  5197.6  360.03  5232.6  362.84  5248.2  365.05  5255.9  365.38
#Mann=5,-1,0
  4660.3    0.05       0  4941.1    0.07       0  4947.1    0.05       0
  4960.4    0.16       0  5184.1    0.05       0
Bank Sta=4941.1,4947.1
Exp/Cntr=0.3,0.1

Type RM Length L Ch R = 1,6310,20,20,20
BEGIN DESCRIPTION:
Mapping XS a25840ee
END DESCRIPTION:
XS GIS Cut Line= 2
      3703038.54     10729436.58      3702791.14     10729819.39
#Sta/Elev= 30
  4773.6  361.01  4789.8  360.05  4812.7  356.65  4854.9  354.74  4885.1  351.15
  4897.2  350.19  4906.2  350.41  4942.6  350.11  4948.6  350.75  4981.9  349.96
  4984.6  349.46  4987.9  349.96  5000.0  350.17  5006.0  351.05  5015.2  350.11
  5021.2  351.10  5027.9  350.15  5051.5  350.16  5057.5  352.83  5063.7  350.27
  5108.9  350.17  5114.9  351.94  5123.2  352.00  5136.6  356.31  5145.2  358.06
  5151.1  357.85  5158.9  359.25  5166.3  358.63  5172.3  359.65  5229.4  364.21
#Mann=5,-1,0
  4773.6    0.05       0  4906.2    0.16       0  4981.9    0.07       0
  4987.9    0.16       0  5136.6    0.05       0
Bank Sta=4981.9,4987.9
Exp/Cntr=0.3,0.1

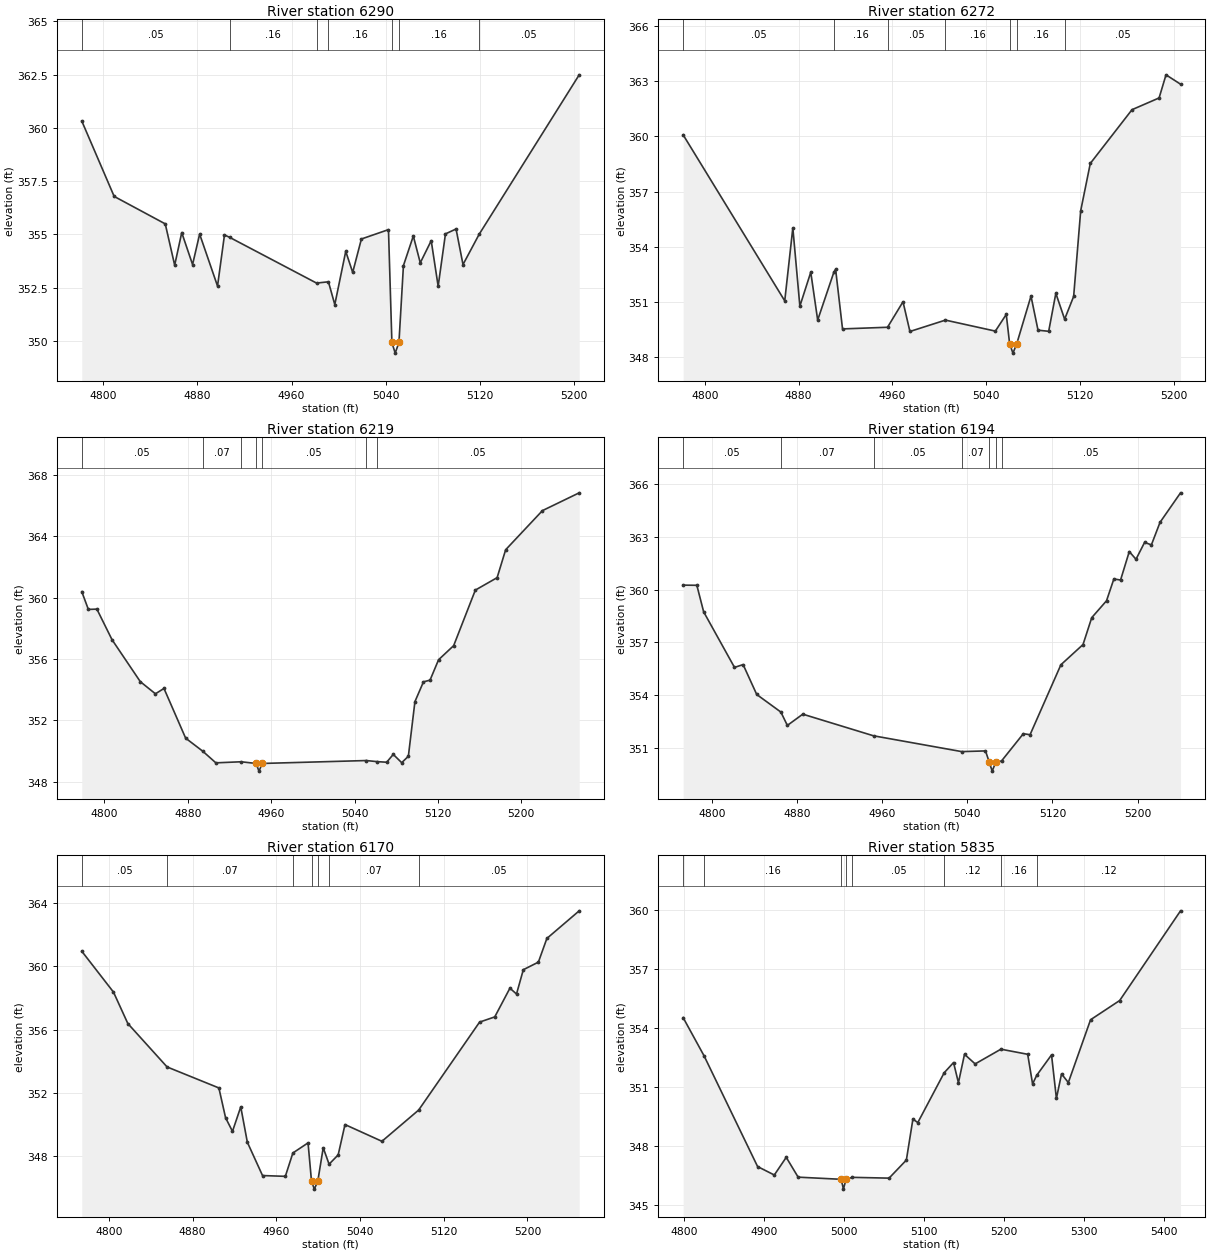
Type RM Length L Ch R = 1,6290,18,18,18
BEGIN DESCRIPTION:
Mapping XS 61af7a93
END DESCRIPTION:
XS GIS Cut Line= 2
      3703018.50     10729430.56      3702789.57     10729785.66
#Sta/Elev= 30
  4781.8  360.32  4809.3  356.78  4852.7  355.49  4860.7  353.55  4866.7  355.08
  4875.9  353.58  4881.9  355.01  4897.1  352.57  4903.0  354.97  4907.3  354.86
  4981.2  352.71  4991.3  352.77  4996.7  351.70  5006.0  354.20  5011.9  353.21
  5019.3  354.78  5042.3  355.22  5045.2  349.92  5048.0  349.42  5051.2  349.92
  5055.0  353.53  5063.4  354.92  5069.3  353.66  5078.6  354.70  5084.5  352.56
  5090.7  355.02  5099.7  355.25  5105.6  353.58  5119.3  355.00  5204.3  362.49
#Mann=7,-1,0
  4781.8    0.05       0  4907.3    0.16       0  4981.2    0.05       0
  4991.3    0.16       0  5045.2    0.07       0  5051.2    0.16       0
  5119.3    0.05       0
Bank Sta=5045.2,5051.2
Exp/Cntr=0.3,0.1

Type RM Length L Ch R = 1,6272,53,53,53
BEGIN DESCRIPTION:
Mapping XS 0ffbca1d
END DESCRIPTION:
XS GIS Cut Line= 2
      3703005.45     10729417.07      3702777.60     10729775.12
#Sta/Elev= 30
  4781.5  360.09  4868.2  351.04  4875.1  355.02  4881.1  350.75  4890.4  352.60
  4896.3  349.99  4910.1  352.60  4911.6  352.76  4917.5  349.51  4955.9  349.60
  4969.1  350.99  4975.0  349.37  5005.3  349.99  5047.9  349.39  5057.2  350.30
  5060.1  348.69  5062.9  348.19  5066.1  348.69  5078.3  351.30  5084.3  349.44
  5093.4  349.38  5099.5  351.45  5107.0  350.04  5114.7  351.28  5120.7  355.95
  5128.9  358.53  5164.5  361.46  5187.6  362.10  5193.5  363.36  5205.9  362.85
#Mann=7,-1,0
  4781.5    0.05       0  4910.1    0.16       0  4955.9    0.05       0
  5005.3    0.16       0  5060.1    0.03       0  5066.1    0.16       0
  5107.0    0.05       0
Bank Sta=5060.1,5066.1
Exp/Cntr=0.3,0.1

Type RM Length L Ch R = 1,6219,25,25,25
BEGIN DESCRIPTION:
Mapping XS fd56ffdd
END DESCRIPTION:
XS GIS Cut Line= 2
      3702985.92     10729386.86      3702694.66     10729765.24
#Sta/Elev= 30
  4778.2  360.40  4784.5  359.24  4792.7  359.26  4807.2  357.27  4834.4  354.53
  4848.9  353.74  4857.1  354.09  4877.9  350.85  4894.3  350.00  4906.9  349.24
  4931.2  349.31  4945.5  349.20  4948.3  348.70  4951.5  349.20  5051.3  349.39
  5061.5  349.32  5070.9  349.28  5077.2  349.79  5085.3  349.25  5091.7  349.67
  5098.0  353.23  5106.2  354.52  5112.5  354.63  5120.7  355.96  5135.2  356.88
  5156.0  360.50  5176.9  361.31  5185.1  363.13  5220.4  365.68  5255.7  366.84
#Mann=7,-1,0
  4778.2    0.05       0  4894.3    0.07       0  4931.2    0.05       0
  4945.5    0.03       0  4951.5    0.05       0  5051.3    0.16       0
  5061.5    0.05       0
Bank Sta=4945.5,4951.5
Exp/Cntr=0.3,0.1

Type RM Length L Ch R = 1,6194,24,24,24
BEGIN DESCRIPTION:
Mapping XS ef8ef421
END DESCRIPTION:
XS GIS Cut Line= 2
      3702972.93     10729365.46      3702686.51     10729735.20
#Sta/Elev= 30
  4772.7  360.26  4785.6  360.25  4792.0  358.74  4821.0  355.58  4829.1  355.74
  4841.9  354.04  4864.6  353.04  4870.7  352.28  4885.2  352.92  4951.7  351.69
  5034.7  350.79  5057.0  350.83  5060.6  350.18  5063.3  349.68  5066.6  350.18
  5072.1  350.26  5092.6  351.81  5098.9  351.75  5127.9  355.73  5148.7  356.88
  5156.9  358.41  5170.8  359.37  5177.7  360.61  5184.0  360.55  5192.2  362.17
  5198.5  361.73  5206.6  362.69  5213.0  362.55  5221.1  363.83  5240.4  365.51
#Mann=7,-1,0
  4772.7    0.05       0  4864.6    0.07       0  4951.7    0.05       0
  5034.7    0.07       0  5060.6    0.03       0  5066.6    0.07       0
  5072.1    0.05       0
Bank Sta=5060.6,5066.6
Exp/Cntr=0.3,0.1

Type RM Length L Ch R = 1,6170,335,335,335
BEGIN DESCRIPTION:
UNT 101 IN CACR 8.0
END DESCRIPTION:
XS GIS Cut Line= 2
      3702958.34     10729346.20      3702667.98     10729722.50
#Sta/Elev= 30
  4774.2  360.96  4804.5  358.37  4818.2  356.38  4855.7  353.63  4905.2  352.30
  4911.6  350.41  4918.2  349.55  4926.1  351.10  4932.4  348.86  4946.9  346.75
  4968.7  346.70  4975.9  348.18  4990.4  348.82  4993.7  346.39  4996.4  345.89
  4999.7  346.39  5004.9  348.51  5010.5  347.47  5019.2  348.06  5025.7  349.98
  5061.0  348.92  5096.1  350.90  5154.3  356.47  5168.8  356.80  5183.3  358.62
  5189.6  358.25  5196.1  359.79  5210.5  360.27  5218.6  361.77  5249.5  363.52
#Mann=7,-1,0
  4774.2    0.05       0  4855.7    0.07       0  4975.9    0.05       0
  4993.7    0.03       0  4999.7    0.05       0  5010.5    0.07       0
  5096.1    0.05       0
Bank Sta=4993.7,4999.7
Exp/Cntr=0.3,0.1

Type RM Length L Ch R = 1,5835,30,30,30
BEGIN DESCRIPTION:
Mapping XS 1d1bc45d
END DESCRIPTION:
XS GIS Cut Line= 2
      3702638.25     10729319.95      3702286.70     10729832.96
#Sta/Elev= 30
  4798.4  354.54  4824.6  352.59  4891.5  346.95  4912.4  346.52  4927.3  347.42
  4942.2  346.41  4996.1  346.30  4998.8  345.80  5002.1  346.30  5010.1  346.40
  5055.9  346.36  5077.5  347.28  5085.7  349.37  5091.8  349.19  5124.8  351.73
  5136.5  352.25  5142.6  351.22  5150.2  352.67  5163.5  352.18  5195.7  352.93
  5229.2  352.67  5235.3  351.16  5240.5  351.60  5259.0  352.64  5265.1  350.42
  5271.5  351.67  5280.0  351.23  5307.8  354.43  5344.2  355.41  5420.3  359.98
#Mann=8,-1,0
  4798.4    0.07       0  4824.6    0.16       0  4996.1    0.07       0
  5002.1    0.16       0  5010.1    0.05       0  5124.8    0.12       0
  5195.7    0.16       0  5240.5    0.12       0
Bank Sta=4996.1,5002.1
Exp/Cntr=0.3,0.1

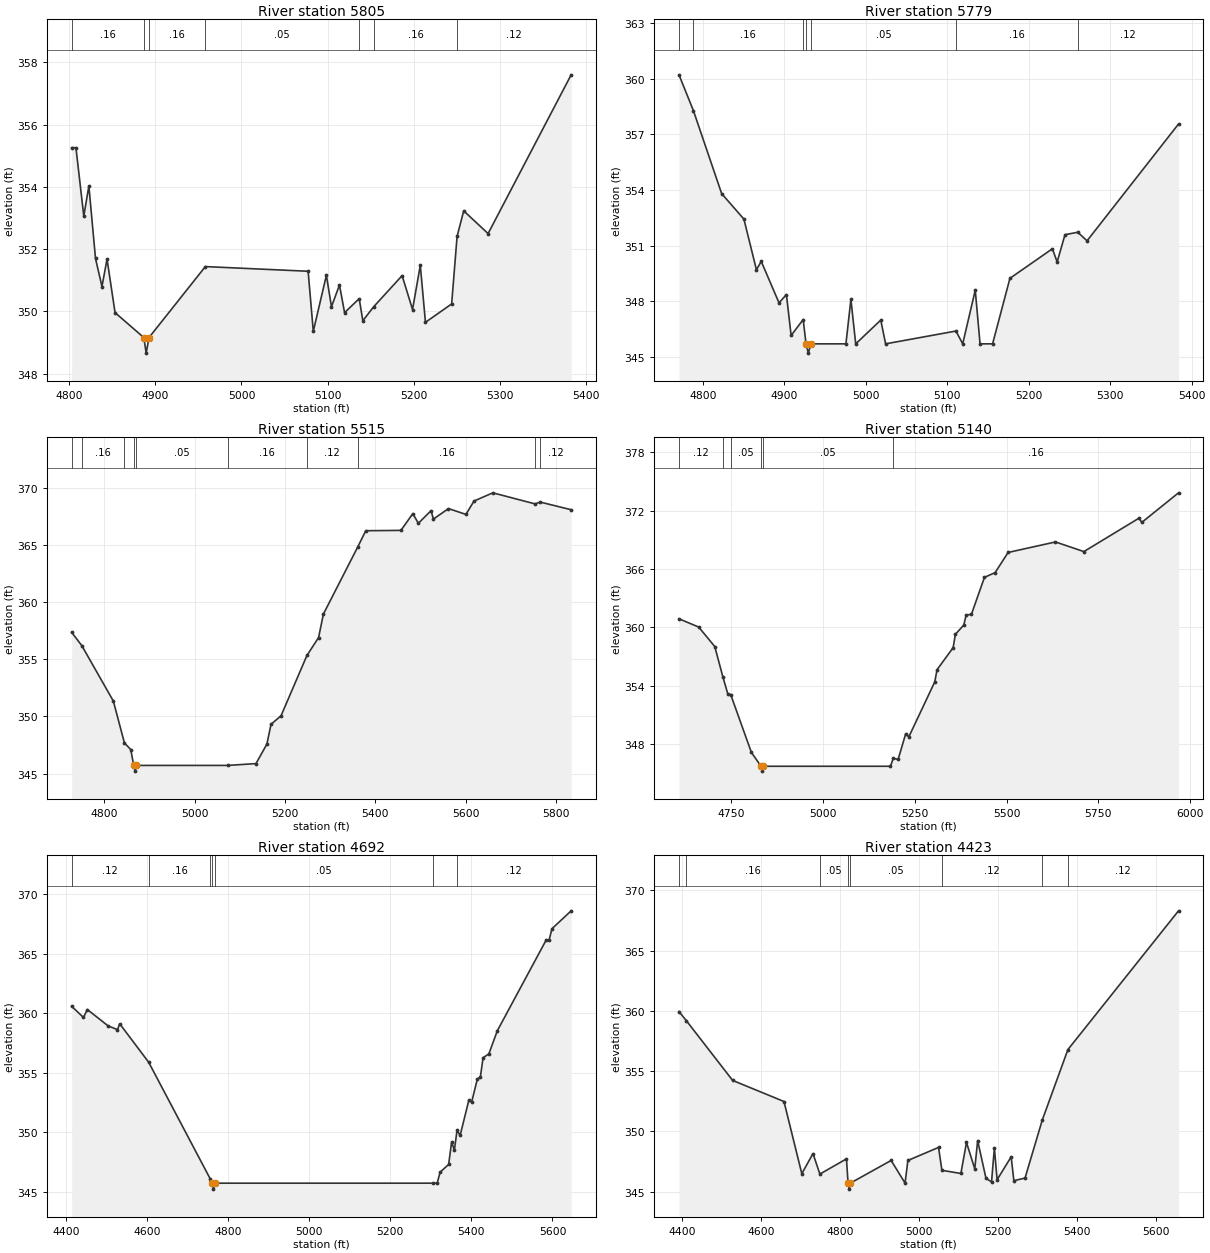
Type RM Length L Ch R = 1,5805,26,26,26
BEGIN DESCRIPTION:
Mapping XS ca7db236
END DESCRIPTION:
XS GIS Cut Line= 2
      3702604.44     10729306.87      3702291.90     10729795.22
#Sta/Elev= 30
  4802.9  355.26  4807.9  355.26  4817.0  353.06  4822.9  354.03  4830.6  351.70
  4838.1  350.80  4844.0  351.68  4853.3  349.96  4886.7  349.16  4889.4  348.66
  4892.7  349.16  4958.1  351.44  5077.4  351.29  5083.4  349.36  5098.6  351.16
  5104.5  350.15  5113.8  350.85  5119.7  349.96  5136.7  350.41  5140.9  349.70
  5153.5  350.15  5186.5  351.15  5198.6  350.06  5207.6  351.48  5213.6  349.65
  5244.0  350.24  5250.3  352.41  5258.0  353.23  5286.3  352.50  5382.7  357.60
#Mann=7,-1,0
  4802.9    0.16       0  4886.7   0.035       0  4892.7    0.16       0
  4958.1    0.05       0  5136.7    0.12       0  5153.5    0.16       0
  5250.3    0.12       0
Bank Sta=4886.7,4892.7
Exp/Cntr=0.3,0.1

Type RM Length L Ch R = 1,5779,264,264,264
BEGIN DESCRIPTION:
UNT 101 IN CACR 7.0
END DESCRIPTION:
XS GIS Cut Line= 2
      3702595.28     10729265.53      3702274.17     10729788.16
#Sta/Elev= 30
  4770.5  360.20  4788.2  358.27  4822.9  353.80  4850.2  352.43  4865.6  349.70
  4871.5  350.15  4893.3  347.92  4902.4  348.36  4908.2  346.16  4923.0  347.02
  4926.5  345.71  4929.3  345.21  4932.5  345.71  4975.5  345.71  4981.6  348.11
  4987.5  345.71  5018.3  346.99  5024.2  345.71  5110.6  346.40  5118.9  345.71
  5134.3  348.60  5140.2  345.71  5155.6  345.71  5176.9  349.24  5229.0  350.83
  5234.9  350.12  5244.5  351.59  5260.2  351.72  5271.6  351.26  5383.9  357.55
#Mann=7,-1,0
  4770.5    0.12       0  4788.2    0.16       0  4923.0    0.05       0
  4926.5   0.035       0  4932.5    0.05       0  5110.6    0.16       0
  5260.2    0.12       0
Bank Sta=4926.5,4932.5
Exp/Cntr=0.3,0.1

Type RM Length L Ch R = 1,5515,375,375,375
BEGIN DESCRIPTION:
Mapping XS 22d20059
END DESCRIPTION:
XS GIS Cut Line= 2
      3702290.30     10729175.36      3701978.19     10730236.51
#Sta/Elev= 30
  4727.4  357.37  4749.8  356.21  4819.7  351.35  4844.3  347.68  4858.3  347.10
  4864.9  345.71  4867.7  345.21  4870.9  345.71  5073.1  345.71  5135.6  345.87
  5159.8  347.58  5168.9  349.31  5191.1  350.06  5248.4  355.34  5274.2  356.91
  5284.9  358.97  5361.1  364.86  5378.7  366.27  5456.6  366.30  5482.9  367.77
  5495.2  366.92  5523.3  368.03  5528.5  367.29  5561.9  368.21  5600.5  367.70
  5618.4  368.87  5660.1  369.59  5753.6  368.62  5764.9  368.78  5833.5  368.11
#Mann=10,-1,0
  4727.4    0.12       0  4749.8    0.16       0  4844.3    0.05       0
  4864.9   0.033       0  4870.9    0.05       0  5073.1    0.16       0
  5248.4    0.12       0  5361.1    0.16       0  5753.6    0.05       0
  5764.9    0.12       0
Bank Sta=4864.9,4870.9
Exp/Cntr=0.3,0.1

Type RM Length L Ch R = 1,5140,448,448,448
BEGIN DESCRIPTION:
UNT 101 IN CACR 6.0
END DESCRIPTION:
XS GIS Cut Line= 2
      3702123.62     10728987.89      3701305.49     10730076.42
#Sta/Elev= 30
  4607.1  360.87  4660.8  360.02  4704.6  358.02  4726.7  354.90  4740.0  353.17
  4748.1  353.07  4804.5  347.13  4830.7  345.71  4833.4  345.21  4836.7  345.71
  5183.6  345.71  5191.2  346.53  5204.4  346.41  5225.2  349.06  5233.6  348.73
  5304.4  354.39  5310.6  355.64  5354.4  357.90  5360.6  359.28  5383.5  360.23
  5389.8  361.24  5404.4  361.34  5439.8  365.13  5468.9  365.62  5504.3  367.69
  5633.4  368.77  5710.8  367.78  5860.9  371.21  5868.8  370.78  5968.8  373.82
#Mann=6,-1,0
  4607.1    0.12       0  4726.7    0.16       0  4748.1    0.05       0
  4830.7   0.033       0  4836.7    0.05       0  5191.2    0.16       0
Bank Sta=4830.7,4836.7
Exp/Cntr=0.3,0.1

Type RM Length L Ch R = 1,4692,269,269,269
BEGIN DESCRIPTION:
UNT 101 IN CACR 5.0
END DESCRIPTION:
XS GIS Cut Line= 4
      3702056.19     10728732.92      3701897.35     10728660.01
      3701599.61     10728960.19      3701136.91     10729394.41
#Sta/Elev= 30
  4414.0  360.57  4443.2  359.63  4452.6  360.30  4504.1  358.92  4527.1  358.61
  4532.6  359.10  4604.0  355.87  4756.2  346.05  4761.1  345.71  4763.8  345.21
  4767.1  345.71  5305.0  345.71  5315.6  345.71  5322.9  346.63  5344.0  347.29
  5351.3  349.18  5358.1  348.48  5364.7  350.17  5372.3  349.72  5393.8  352.69
  5400.6  352.51  5414.8  354.47  5422.1  354.61  5428.9  356.25  5443.1  356.57
  5464.1  358.52  5584.7  366.15  5591.6  366.12  5598.9  367.09  5646.1  368.59
#Mann=7,-1,0
  4414.0    0.12       0  4604.0    0.16       0  4756.2    0.05       0
  4761.1   0.033       0  4767.1    0.05       0  5305.0    0.16       0
  5364.7    0.12       0
Bank Sta=4761.1,4767.1
Exp/Cntr=0.3,0.1

Type RM Length L Ch R = 1,4423,16,16,16
BEGIN DESCRIPTION:
Mapping XS c771e99a
END DESCRIPTION:
XS GIS Cut Line= 3
      3701928.56     10728594.90      3701678.60     10728511.58
      3700954.24     10729204.79
#Sta/Elev= 30
  4391.4  359.94  4409.7  359.20  4527.3  354.23  4657.5  352.48  4702.7  346.49
  4731.0  348.16  4748.5  346.46  4815.9  347.72  4819.9  345.71  4822.6  345.21
  4825.9  345.71  4929.1  347.59  4964.4  345.71  4971.6  347.59  5049.3  348.67
  5057.8  346.77  5105.9  346.51  5120.1  349.08  5141.1  346.89  5148.4  349.24
  5169.4  346.12  5183.6  345.80  5190.8  348.63  5197.7  345.99  5233.3  347.89
  5240.2  345.91  5268.5  346.13  5312.4  350.96  5377.2  356.79  5657.5  368.30
#Mann=8,-1,0
  4391.4    0.12       0  4409.7    0.16       0  4748.5    0.05       0
  4819.9   0.033       0  4825.9    0.05       0  5057.8    0.12       0
  5312.4    0.16       0  5377.2    0.12       0
Bank Sta=4819.9,4825.9
Exp/Cntr=0.3,0.1

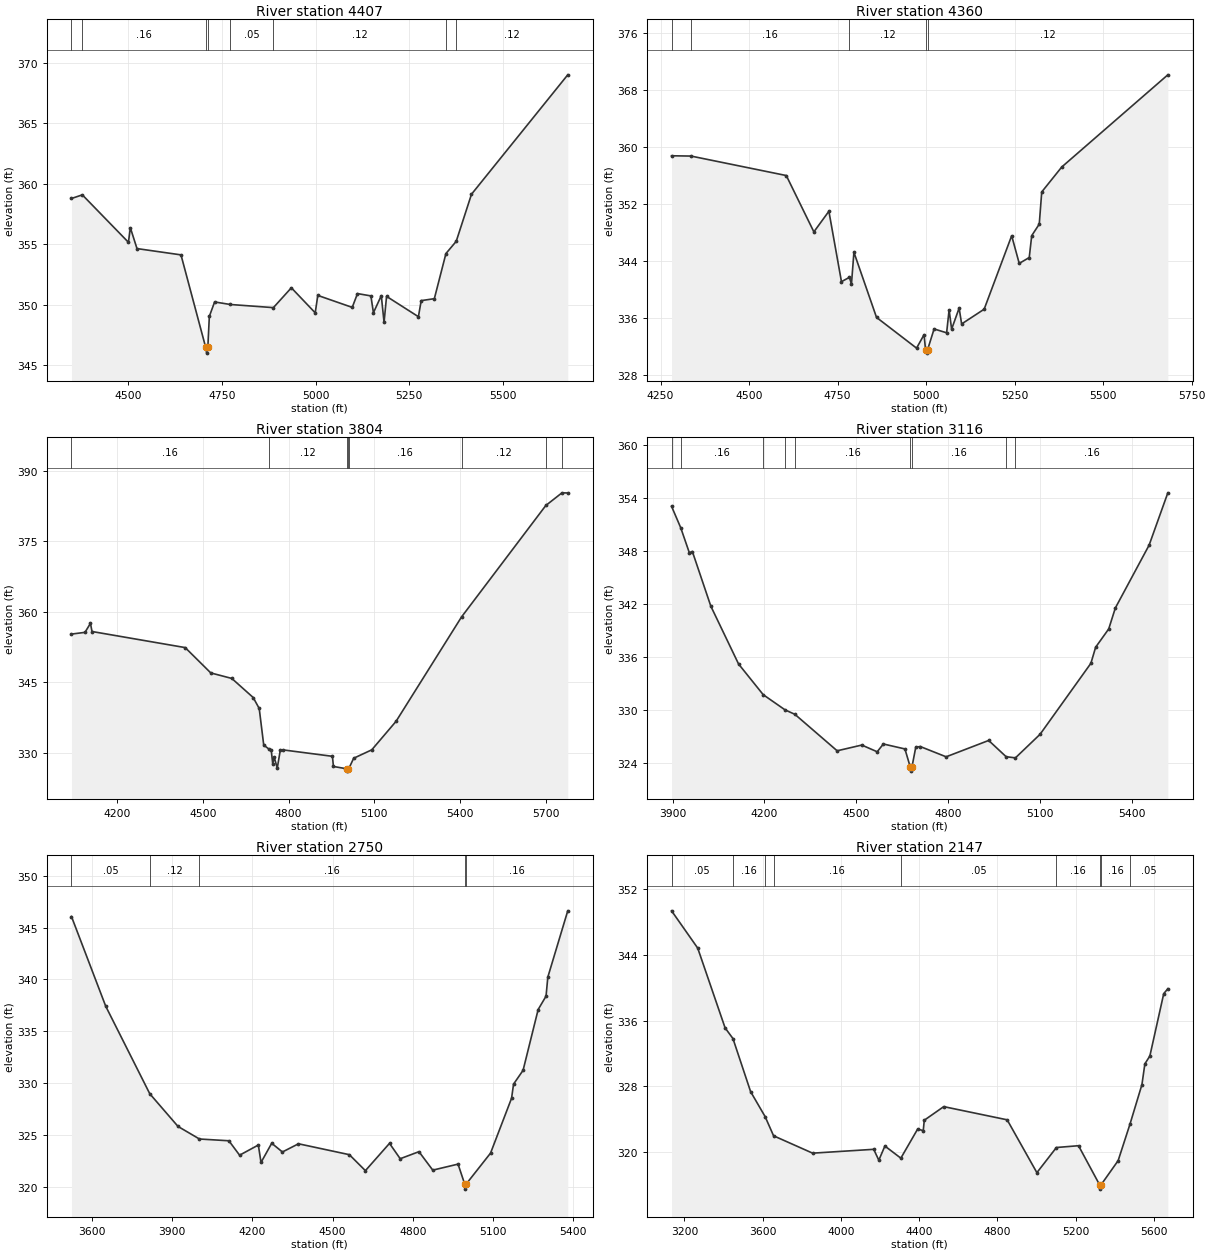
Type RM Length L Ch R = 1,4407,47,47,47
BEGIN DESCRIPTION:
Mapping XS 1ffaf240
END DESCRIPTION:
XS GIS Cut Line= 4
      3701946.80     10728571.46      3701662.98     10728482.93
      3701402.56     10728755.79      3700921.47     10729195.86
#Sta/Elev= 30
  4347.7  358.79  4376.7  359.09  4499.9  355.17  4505.1  356.37  4522.8  354.65
  4640.4  354.13  4706.2  346.51  4709.0  346.01  4712.2  346.51  4716.2  349.05
  4730.3  350.24  4772.1  350.03  4887.4  349.77  4935.4  351.41  4999.2  349.34
  5006.1  350.78  5098.1  349.79  5112.2  350.93  5148.0  350.74  5154.8  349.35
  5175.8  350.76  5183.2  348.56  5189.9  350.70  5275.0  349.02  5282.5  350.35
  5317.6  350.51  5348.6  354.24  5376.1  355.25  5416.9  359.14  5674.2  369.01
#Mann=8,-1,0
  4347.7    0.12       0  4376.7    0.16       0  4706.2    0.07       0
  4712.2    0.16       0  4772.1    0.05       0  4887.4    0.12       0
  5348.6    0.16       0  5376.1    0.12       0
Bank Sta=4706.2,4712.2
Exp/Cntr=0.3,0.1

Type RM Length L Ch R = 1,4360,556,556,556
BEGIN DESCRIPTION:
UNT 101 IN CACR 4.0
END DESCRIPTION:
XS GIS Cut Line= 3
      3701977.43     10728559.32      3701647.57     10728450.81
      3700893.48     10729187.56
#Sta/Elev= 30
  4281.2  358.77  4336.1  358.73  4605.2  356.00  4683.1  348.10  4725.5  350.99
  4761.0  341.12  4783.7  341.73  4789.2  340.76  4796.2  345.24  4860.0  336.11
  4973.1  331.80  4994.3  333.69  4998.4  331.60  5001.2  331.10  5004.4  331.60
  5022.6  334.49  5058.0  333.95  5065.0  337.17  5072.1  334.46  5093.3  337.41
  5100.4  335.19  5164.0  337.26  5241.7  347.56  5263.0  343.68  5291.3  344.50
  5298.3  347.57  5319.6  349.19  5326.6  353.70  5383.2  357.20  5682.7  370.12
#Mann=5,-1,0
  4281.2    0.12       0  4336.1    0.16       0  4783.7    0.12       0
  4998.4    0.07       0  5004.4    0.12       0
Bank Sta=4998.4,5004.4
Exp/Cntr=0.3,0.1

Type RM Length L Ch R = 1,3804,688,688,688
BEGIN DESCRIPTION:
UNT 101 IN CACR 3.0
END DESCRIPTION:
XS GIS Cut Line= 4
      3701903.64     10728420.43      3701356.77     10728207.76
      3701049.61     10728310.19      3700449.67     10728880.48
#Sta/Elev= 30
  4039.5  355.23  4086.8  355.60  4106.0  357.52  4111.4  355.78  4437.8  352.36
  4527.5  346.97  4601.1  345.80  4676.0  341.74  4697.1  339.41  4712.9  331.63
  4730.5  330.81  4739.2  330.52  4744.5  327.64  4749.8  329.01  4760.3  326.74
  4770.9  330.53  4781.4  330.60  4953.5  329.24  4957.1  327.08  5003.5  326.59
  5006.3  326.09  5009.5  326.59  5010.7  326.60  5027.9  328.83  5091.4  330.62
  5176.4  336.68  5405.8  358.88  5701.0  382.58  5757.6  385.27  5777.8  385.24
#Mann=8,-1,0
  4039.5    0.16       0  4730.5    0.12       0  5003.5    0.07       0
  5009.5    0.12       0  5010.7    0.16       0  5405.8    0.12       0
  5701.0    0.05       0  5757.6    0.08       0
Bank Sta=5003.5,5009.5
Exp/Cntr=0.3,0.1

Type RM Length L Ch R = 1,3116,366,366,366
BEGIN DESCRIPTION:
Mapping XS 773eee37
END DESCRIPTION:
XS GIS Cut Line= 3
      3701767.17     10727896.74      3700754.12     10727792.57
      3700442.51     10728306.72
#Sta/Elev= 30
  3896.8  353.07  3926.7  350.65  3954.7  347.83  3964.7  347.96  4025.0  341.77
  4115.5  335.23  4195.9  331.76  4267.2  330.04  4299.2  329.54  4437.2  325.41
  4517.6  326.06  4567.9  325.30  4588.0  326.18  4658.4  325.62  4675.5  323.61
  4678.2  323.11  4681.5  323.61  4693.8  325.82  4708.6  325.89  4792.9  324.73
  4931.7  326.58  4988.7  324.74  5019.0  324.61  5099.5  327.28  5265.3  335.31
  5280.8  337.13  5323.5  339.20  5345.1  341.57  5455.3  348.68  5516.4  354.60
#Mann=9,-1,0
  3896.8    0.05       0  3926.7    0.16       0  4195.9    0.05       0
  4267.2    0.12       0  4299.2    0.16       0  4675.5    0.07       0
  4681.5    0.16       0  4988.7    0.12       0  5019.0    0.16       0
Bank Sta=4675.5,4681.5
Exp/Cntr=0.3,0.1

Type RM Length L Ch R = 1,2750,603,603,603
BEGIN DESCRIPTION:
UNT 101 IN CACR 2.0
END DESCRIPTION:
XS GIS Cut Line= 3
      3701787.65     10727596.33      3700446.50     10727644.07
      3700147.03     10728060.71
#Sta/Elev= 30
  3524.1  346.06  3652.2  337.41  3816.8  328.98  3922.4  325.83  4002.5  324.62
  4112.5  324.45  4152.5  323.06  4222.6  324.04  4232.6  322.36  4272.6  324.21
  4312.6  323.37  4372.7  324.16  4562.8  323.11  4622.8  321.57  4712.9  324.20
  4752.9  322.72  4823.0  323.40  4874.6  321.62  4969.1  322.20  4993.8  320.29
  4996.5  319.79  4999.8  320.29  5090.6  323.26  5169.2  328.55  5176.6  329.91
  5212.2  331.24  5268.6  337.10  5298.1  338.39  5304.7  340.22  5379.2  346.61
#Mann=5,-1,0
  3524.1    0.05       0  3816.8    0.12       0  4002.5    0.16       0
  4993.8    0.07       0  4999.8    0.16       0
Bank Sta=4993.8,4999.8
Exp/Cntr=0.3,0.1

Type RM Length L Ch R = 1,2147,418,418,418
BEGIN DESCRIPTION:
Mapping XS 48a7dd26
END DESCRIPTION:
XS GIS Cut Line= 4
      3701831.25     10727520.88      3701095.11     10727104.20
      3700591.64     10727246.56      3699438.89     10727434.05
#Sta/Elev= 30
  3133.9  349.39  3267.6  344.84  3407.6  335.10  3447.7  333.80  3538.0  327.32
  3612.2  324.27  3655.4  321.93  3855.0  319.81  4167.3  320.28  4193.4  318.95
  4224.5  320.68  4306.0  319.20  4391.9  322.75  4420.6  322.56  4425.8  323.83
  4525.3  325.49  4849.5  323.88  5001.5  317.43  5101.3  320.50  5214.3  320.72
  5322.7  315.92  5325.5  315.42  5328.7  315.92  5416.9  318.90  5477.2  323.34
  5538.5  328.18  5553.5  330.71  5579.0  331.67  5649.9  339.28  5670.9  339.88
#Mann=9,-1,0
  3133.9    0.05       0  3447.7    0.16       0  3612.2    0.12       0
  3655.4    0.16       0  4306.0    0.05       0  5101.3    0.16       0
  5322.7    0.03       0  5328.7    0.16       0  5477.2    0.05       0
Bank Sta=5322.7,5328.7
Exp/Cntr=0.3,0.1

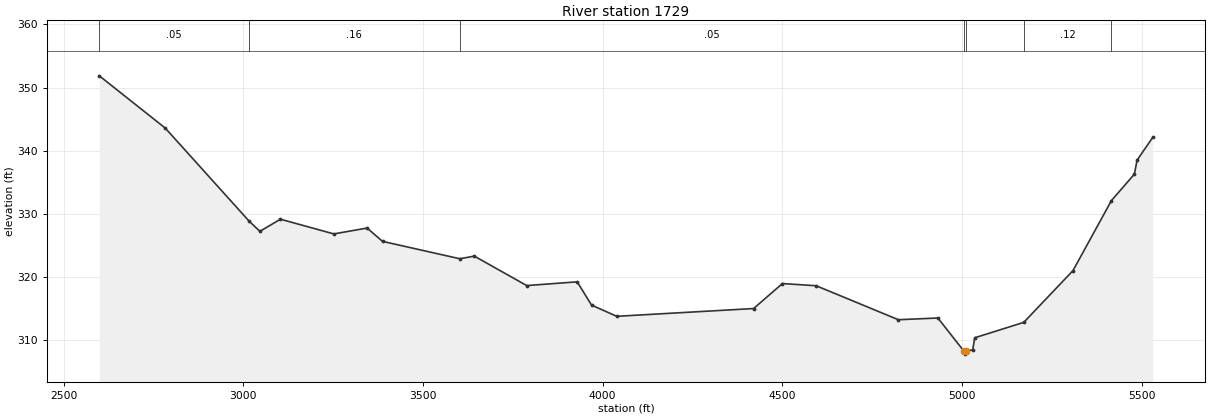
Type RM Length L Ch R = 1,1729,0,0,0
BEGIN DESCRIPTION:
UNT 101 IN CACR 1.0
END DESCRIPTION:
XS GIS Cut Line= 4
      3701888.69     10727469.93      3701279.14     10726729.20
      3700254.83     10726802.11      3699424.73     10727255.21
#Sta/Elev= 30
  2599.2  351.85  2782.7  343.57  3015.5  328.87  3046.0  327.22  3103.3  329.14
  3251.9  326.81  3344.4  327.74  3387.4  325.63  3602.1  322.88  3643.0  323.29
  3788.7  318.63  3929.2  319.22  3969.1  315.54  4039.2  313.76  4420.2  314.99
  4500.4  318.95  4594.4  318.60  4823.1  313.22  4933.1  313.49  5005.2  308.27
  5008.0  307.77  5011.2  308.27  5030.0  308.44  5035.7  310.36  5172.1  312.80
  5309.1  321.00  5416.0  332.08  5480.0  336.28  5487.5  338.49  5531.1  342.10
#Mann=7,-1,0
  2599.2    0.05       0  3015.5    0.16       0  3602.1    0.05       0
  5005.2    0.03       0  5011.2    0.05       0  5172.1    0.12       0
  5416.0    0.05       0
Bank Sta=5005.2,5011.2
Exp/Cntr=0.3,0.1

Chan Stop Cuts=-1