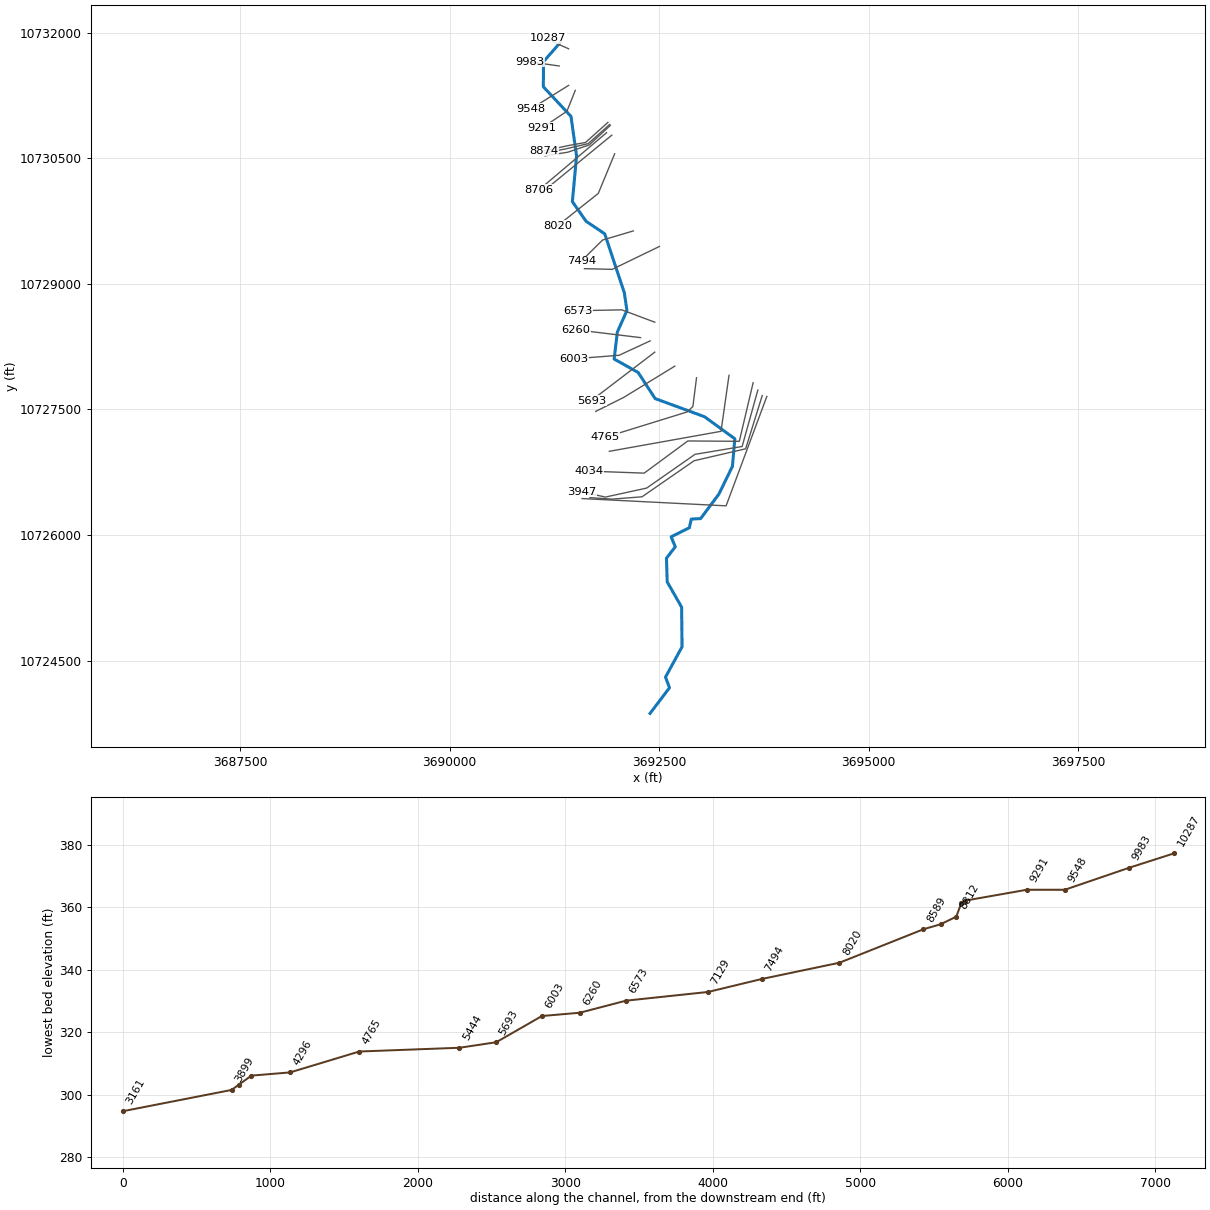
--- UNT 102 IN CACR.prj (project) ---

Proj Title=UNT 102 IN CACR Base Level Engineering
Current Plan=p01
Default Exp/Contr=0.3,0.1
English Units
Geom File=g01
Flow File=f01
Plan File=p01
Y Axis Title=Elevation
X Axis Title(PF)=Main Channel Distance
X Axis Title(XS)=Station
BEGIN DESCRIPTION:
UNT 102 IN CACR
END DESCRIPTION:
DSS Export Rating Curves= 0
DSS Export Rating Curve Sorted= 0
DSS Export Volume Flow Curves= 0
DXF OffsetX= 0
DXF OffsetY= 0
DXF ScaleX= 1
DXF ScaleY= 10

--- UNT 102 IN CACR.p01 (plan) ---

Plan Title=Multiple Run
Short Identifier=Multiple
Geom File=g01
Flow File=f01
Subcritical Flow
K Sum by GR= 0
Std Step Tol= 0.01
Critical Tol= 0.01
Num of Std Step Trials= 20
Max Error Tol= 0.3
Flow Tol Ratio= 0.001
Split Flow NTrial= 30
Split Flow Tol= 0.02
Split Flow Ratio= 0.02
Log Output Level= 0
Friction Slope Method= 1
Unsteady Friction Slope Method= 2
Unsteady Bridges Friction Slope Method= 1
Parabolic Critical Depth
Global Vel Dist=  1 , 1 , 1
Global Log Level= 0
CheckData=True
Encroach Param= -1, 0, 0, 0
BEGIN DESCRIPTION:
Multiple Run
END DESCRIPTION:

--- UNT 102 IN CACR.f01 (steady flow) ---

Flow Title=Multiple
Program Version=4.10
Number of Profiles= 7
Profile Names=10-year,25-year,50-year,1pct_min,100-year,1pct_plu,500-year
River Rch & RM=UNT 102 IN CACR,Reach-1         ,10287
     490     658     795     706     955    1292    1379
River Rch & RM=UNT 102 IN CACR,Reach-1         ,8020
     709     970    1187    1065    1440    1948    2125
Boundary for River Rch & Prof#=UNT 102 IN CACR,Reach-1         , 1
Up Type= 0
Dn Type= 3
Dn Slope=0.01311
Boundary for River Rch & Prof#=UNT 102 IN CACR,Reach-1         , 2
Up Type= 0
Dn Type= 3
Dn Slope=0.01311
Boundary for River Rch & Prof#=UNT 102 IN CACR,Reach-1         , 3
Up Type= 0
Dn Type= 3
Dn Slope=0.01311
Boundary for River Rch & Prof#=UNT 102 IN CACR,Reach-1         , 4
Up Type= 0
Dn Type= 3
Dn Slope=0.01311
Boundary for River Rch & Prof#=UNT 102 IN CACR,Reach-1         , 5
Up Type= 0
Dn Type= 3
Dn Slope=0.01311
Boundary for River Rch & Prof#=UNT 102 IN CACR,Reach-1         , 6
Up Type= 0
Dn Type= 3
Dn Slope=0.01311
Boundary for River Rch & Prof#=UNT 102 IN CACR,Reach-1         , 7
Up Type= 0
Dn Type= 3
Dn Slope=0.01311
DSS Import GetInterval= 0
DSS Import GetPeak= 0
DSS Import FillOption= 0

--- UNT 102 IN CACR.g01 (geometry) ---

Geom Title=Existing Conditions
Program Version=4.10

River Reach=UNT 102 IN CACR ,Reach-1
Reach XY= 30
       3691319.5       10731880.        3691121.       10731654.
      3691118.25       10731353.        3691448.       10731000.
        3691515.       10730527.      3691464.75       10729981.
      3691629.25       10729746.      3691851.25       10729597.
      3692084.75       10728893.        3692116.       10728681.
      3692001.75       10728425.        3691963.       10728102.
       3692249.5       10727942.       3692452.5       10727630.
        3693042.       10727413.      3693403.25       10727150.
      3693374.75       10726821.      3693213.25       10726489.
        3692995.       10726197.      3692883.25       10726191.
        3692861.       10726087.      3692643.25       10725979.
      3692692.75       10725860.      3692587.75       10725724.
      3692596.25       10725441.      3692768.25       10725140.
       3692773.5       10724666.        3692576.       10724304.
      3692623.75       10724177.        3692392.       10723871.

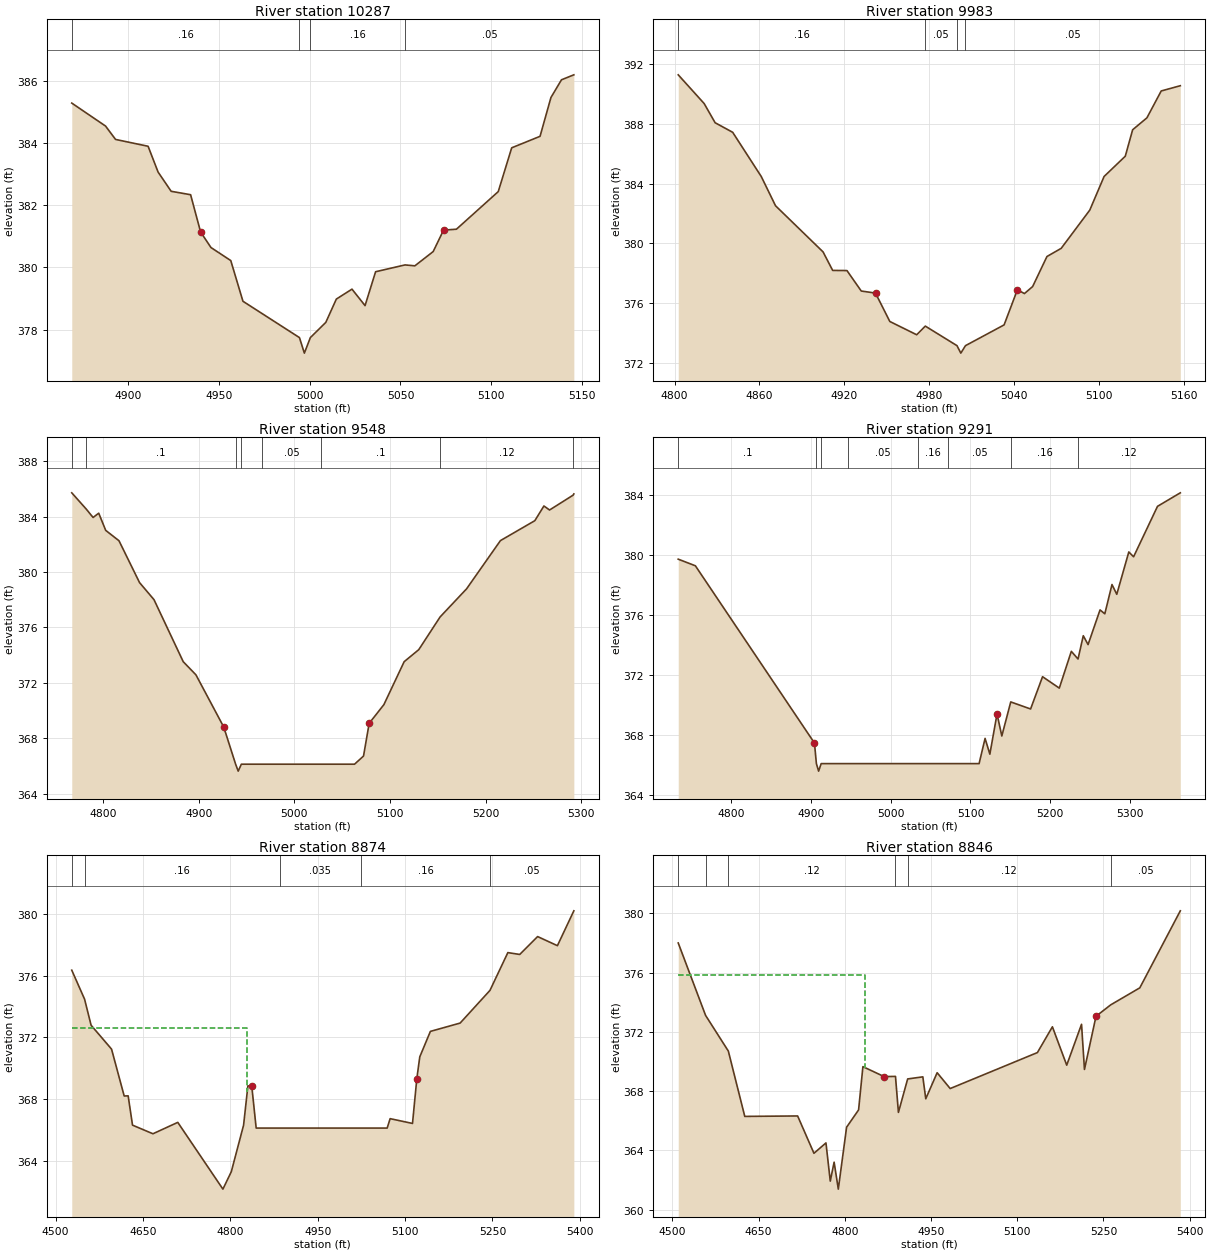
Type RM Length L Ch R = 1 ,10287   ,304,304,304
BEGIN DESCRIPTION:
UNT 102 IN CACR 15.0
END DESCRIPTION:
XS GIS Cut Line= 3
      3691419.76     10731806.89      3691299.83     10731859.35
      3691173.46     10731931.27
#Sta/Elev= 30
  4869.1  385.29  4887.7  384.55  4893.2  384.12  4911.1   383.9  4916.6  383.07
  4923.8  382.45  4934.5  382.34    4940  381.14  4945.7  380.64  4956.6  380.22
  4963.3  378.91  4994.4  377.74  4997.1  377.24  5000.4  377.74  5008.9  378.23
  5014.7  378.98  5023.3   379.3  5030.5  378.77  5036.3  379.86  5052.5  380.08
  5057.9  380.05    5068  380.51  5073.7   381.2  5080.8  381.23  5103.8  382.44
  5111.2  383.85  5126.8  384.22  5132.8  385.47  5138.6  386.04  5145.4   386.2
#Mann= 4 ,-1 , 0
  4869.1     .16       0  4994.4     .07       0  5000.4     .16       0
  5052.5     .05       0
Bank Sta=4940,5073.7
XS Rating Curve= 0 ,0
Exp/Cntr=0.3,0.1

Type RM Length L Ch R = 1 ,9983    ,435,435,435
BEGIN DESCRIPTION:
Mapping XS c0c9ccfa
END DESCRIPTION:
XS GIS Cut Line= 2
      3691307.74     10731601.16      3690956.21     10731650.64
#Sta/Elev= 30
  4802.6  391.28  4820.9  389.36  4828.7  388.07  4841.1  387.43  4861.3  384.47
  4871.4  382.51    4905  379.42  4911.8  378.18  4921.9  378.17    4932   376.8
  4942.1  376.66  4952.2  374.76  4971.2  373.87  4977.3  374.45  4999.7  373.14
  5002.4  372.64  5005.7  373.14    5033  374.53  5042.4  376.88  5047.4  376.63
  5053.2   377.1  5063.3  379.11  5073.4  379.66  5093.6  382.22  5103.7  384.47
  5118.7  385.83  5123.9   387.6    5134   388.4  5144.1   390.2  5157.6  390.55
#Mann= 4 ,-1 , 0
  4802.6     .16       0  4977.3     .05       0  4999.7     .03       0
  5005.7     .05       0
Bank Sta=4942.1,5042.4
XS Rating Curve= 0 ,0
Exp/Cntr=0.3,0.1

Type RM Length L Ch R = 1 ,9548    ,257,257,257
BEGIN DESCRIPTION:
Mapping XS 9507a77b
END DESCRIPTION:
XS GIS Cut Line= 2
      3691419.73     10731369.37      3690974.51     10731090.78
#Sta/Elev= 30
  4767.1  385.71  4782.2  384.54  4789.4  383.93  4795.3  384.24  4802.6     383
  4816.5  382.25    4838  379.23  4853.1     378  4883.7  373.52    4897  372.57
  4926.1   368.8  4938.5  366.12  4941.2  365.62  4944.5  366.12  4965.8  366.12
  5027.9  366.12  5062.9  366.12  5072.3  366.71  5078.2  369.07  5093.6  370.42
  5114.8  373.52  5130.1  374.39  5152.4  376.75  5180.1  378.78  5215.5  382.26
  5251.5   383.7    5261  384.76  5266.9  384.47  5291.5  385.54  5292.3  385.63
#Mann= 8 ,-1 , 0
  4767.1     .16       0  4782.2      .1       0  4938.5    .033       0
  4944.5      .1       0  4965.8     .05       0  5027.9      .1       0
  5152.4     .12       0  5291.5     .16       0
Bank Sta=4926.1,5078.2
XS Rating Curve= 0 ,0
Exp/Cntr=0.3,0.1

Type RM Length L Ch R = 1 ,9291    ,417,417,417
BEGIN DESCRIPTION:
UNT 102 IN CACR 14.0
END DESCRIPTION:
XS GIS Cut Line= 3
      3691499.59     10731310.14      3691399.61     10731060.19
      3691099.58     10730860.17
#Sta/Elev= 30
  4733.4  379.74  4754.9   379.3  4904.3  367.49  4906.7  366.12  4909.5  365.62
  4912.7  366.12  4946.1  366.12  5034.6  366.12  5072.2  366.12  5110.8  366.12
  5118.3   367.8  5124.3  366.75  5133.3  369.43  5139.3  367.96  5150.5  370.23
  5175.4  369.76  5190.4  371.91  5211.4  371.15  5226.5   373.6  5234.9  373.09
  5241.5  374.64  5247.5  374.05  5262.5  376.36  5268.5   376.1  5277.5  378.05
  5283.5   377.4  5298.6  380.22  5304.6   379.9  5334.6  383.26  5363.2  384.16
#Mann= 8 ,-1 , 0
  4733.4      .1       0  4906.7    .033       0  4912.7      .1       0
  4946.1     .05       0  5034.6     .16       0  5072.2     .05       0
  5150.5     .16       0  5234.9     .12       0
Bank Sta=4904.3,5133.3
XS Rating Curve= 0 ,0
Exp/Cntr=0.3,0.1

Type RM Length L Ch R = 1 ,8874    ,28,28,28
BEGIN DESCRIPTION:
Mapping XS 95b555fb
END DESCRIPTION:
XS GIS Cut Line= 4
      3691889.29     10730927.42      3691621.93     10730687.84
      3691418.81     10730651.38      3691128.83     10730588.87
#Sta/Elev= 30
  4527.8  376.36  4549.8  374.48    4561  372.79  4596.1  371.24  4617.8   368.2
  4624.6  368.21  4632.1  366.31  4667.2  365.75  4709.8  366.49  4787.3  362.16
  4801.7  363.29  4822.8  366.31  4830.2  368.86  4836.9  368.82  4844.4  366.12
    4885  366.12  5024.2  366.12  5069.3  366.12  5074.4  366.73  5112.8  366.42
  5120.2  369.32  5125.3  370.74  5143.5  372.39  5194.6  372.93  5245.8  375.05
  5276.5   377.5  5296.9  377.38  5327.6  378.54  5361.6  377.95  5389.8  380.21
#Mann= 5 ,-1 , 0
  4527.8     .05       0  4549.8     .16       0    4885    .035       0
  5024.2     .16       0  5245.8     .05       0
#XS Ineff= 2 , 0
         4828.98  372.58
Permanent Ineff=
       F       F
Bank Sta=4836.9,5120.2
XS Rating Curve= 0 ,0
Exp/Cntr=0.3,0.1

Type RM Length L Ch R = 1 ,8846    ,34,34,34
BEGIN DESCRIPTION:
Mapping XS aca50a37
END DESCRIPTION:
XS GIS Cut Line= 4
      3691910.09     10730903.08      3691653.18     10730673.95
      3691401.44     10730614.92      3691135.85     10730561.11
#Sta/Elev= 30
  4510.1  378.01  4557.7  373.12  4597.3  370.71  4625.9   366.3  4717.9  366.33
  4746.3  363.81  4767.2  364.51  4774.7  361.93  4781.4  363.21  4788.7  361.39
  4803.1  365.57    4824  366.74  4831.5  369.66  4868.3  368.99  4888.2     369
  4893.3  366.57  4909.4  368.83  4935.8  368.97  4940.9  367.49  4960.7  369.25
  4983.4  368.18  5135.2  370.61  5161.3  372.35  5186.2  369.76    5212  372.52
  5217.1  369.47  5237.2  373.06  5262.7  373.83  5313.4  374.98  5383.9  380.18
#Mann= 6 ,-1 , 0
  4510.1     .05       0  4557.7     .16       0  4597.3     .12       0
  4888.2     .07       0  4909.4     .12       0  5262.7     .05       0
#XS Ineff= 2 , 0
         4835.23  375.83
Permanent Ineff=
       F       F
Bank Sta=4868.3,5237.2
XS Rating Curve= 0 ,0
Exp/Cntr=0.3,0.1

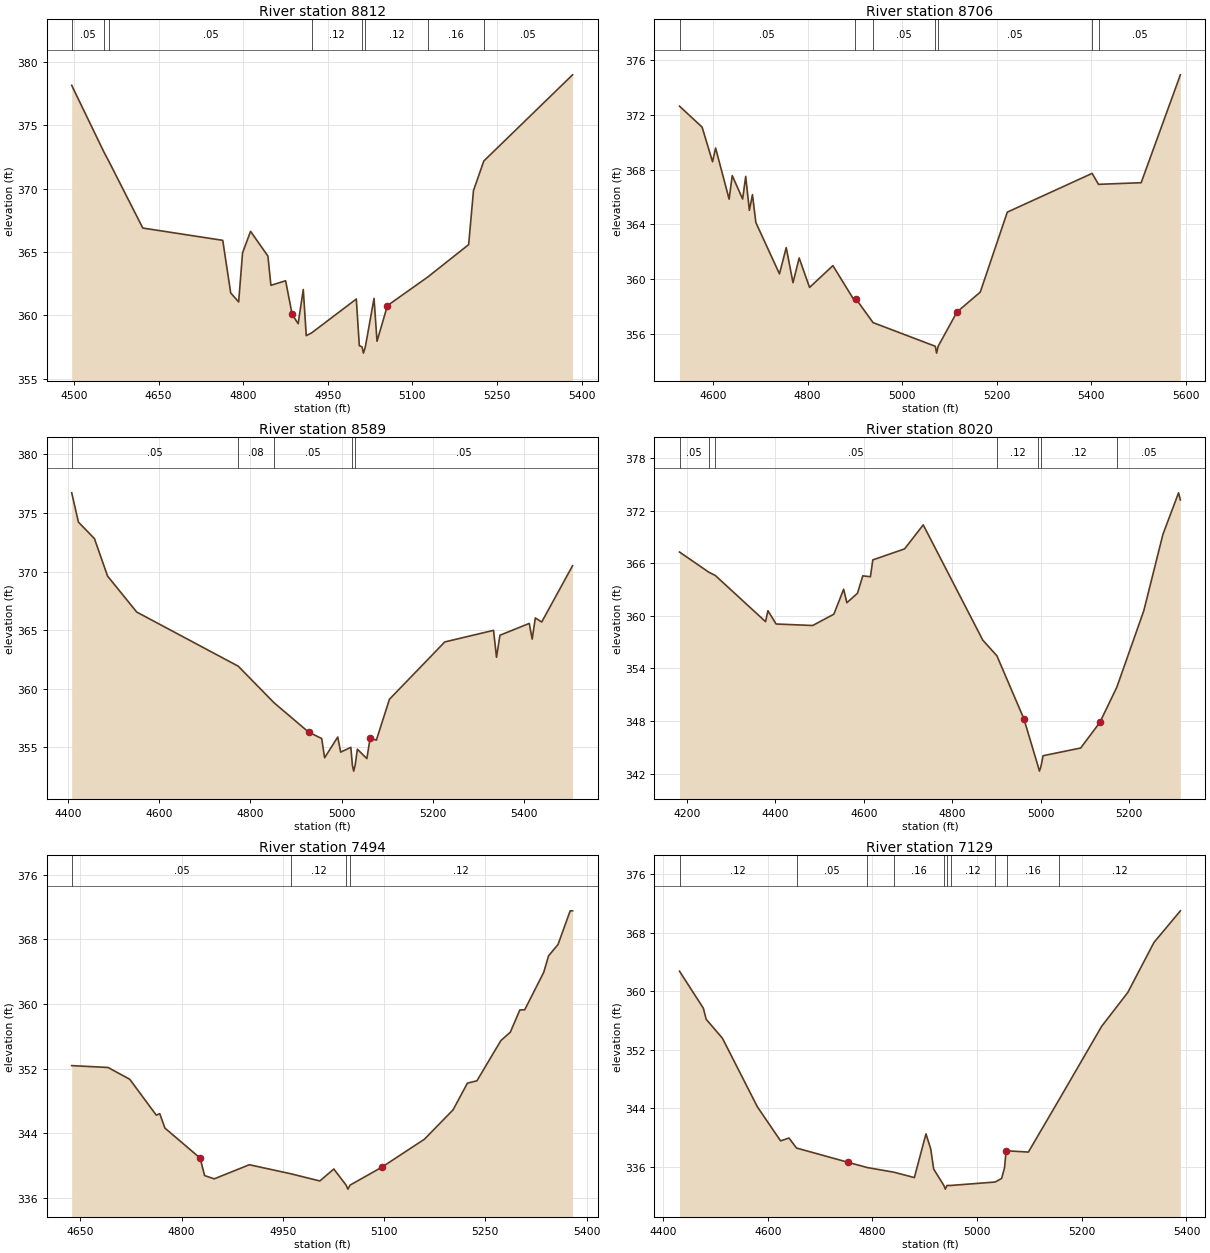
Type RM Length L Ch R = 1 ,8812    ,106,106,106
BEGIN DESCRIPTION:
Mapping XS 77e61900
END DESCRIPTION:
XS GIS Cut Line= 4
      3691917.04     10730890.94      3691665.33     10730658.33
      3691410.12     10730571.52      3691137.56     10730528.12
#Sta/Elev= 30
  4495.8  378.14  4552.7   372.9  4562.1  372.11  4621.9  366.88  4763.7  365.91
  4777.8  361.76  4791.9  361.05  4798.8  364.92    4813  366.62  4843.8  364.67
  4849.1  362.36  4875.2  362.72  4886.8  360.07  4897.4  359.33  4906.5  362.03
  4911.8  358.39  4921.4  358.61  5000.6  361.28  5005.9   357.6  5010.6  357.51
  5013.3  357.01  5016.6  357.51    5032  361.33  5037.3  357.95  5055.8  360.76
  5127.1  363.01  5199.8  365.57  5208.4  369.84  5226.7  372.17  5384.1  378.97
#Mann= 8 ,-1 , 0
  4495.8     .05       0  4552.7     .16       0  4562.1     .05       0
  4921.4     .12       0  5010.6     .07       0  5016.6     .12       0
  5127.1     .16       0  5226.7     .05       0
Bank Sta=4886.8,5055.8
XS Rating Curve= 0 ,0
Exp/Cntr=0.3,0.1

Type RM Length L Ch R = 1 ,8706    ,117,117,117
BEGIN DESCRIPTION:
UNT 102 IN CACR 13.0
END DESCRIPTION:
XS GIS Cut Line= 2
      3691872.99     10730804.52      3691063.44     10730119.79
#Sta/Elev= 30
  4528.7  372.63  4576.5   371.1  4598.6  368.57  4605.1  369.57  4633.7  365.84
  4640.3  367.56  4662.3  365.85  4668.8   367.5  4676.6  365.02  4683.1  366.17
  4690.3  364.13  4740.3  360.38  4754.6   362.3  4768.9  359.74    4782  361.54
    4804  359.39  4853.4  360.98    4900  358.37  4902.9  358.52  4938.4  356.82
  5070.2  355.09  5072.9  354.59  5076.2  355.09    5116  357.59  5165.4  359.05
  5222.6  364.89  5402.2  367.72  5415.7  366.92    5506  367.04    5589  374.92
#Mann= 7 ,-1 , 0
  4528.7     .05       0    4900     .12       0  4938.4     .05       0
  5070.2     .04       0  5076.2     .05       0  5402.2     .16       0
  5415.7     .05       0
Bank Sta=4902.9,5116
XS Rating Curve= 0 ,0
Exp/Cntr=0.3,0.1

Type RM Length L Ch R = 1 ,8589    ,569,569,569
BEGIN DESCRIPTION:
UNT 102 IN CACR 12.0
END DESCRIPTION:
XS GIS Cut Line= 2
      3691935.48       10730775.      3691086.53     10730078.83
#Sta/Elev= 30
  4408.4  376.72  4423.2  374.22  4458.3  372.81    4487  369.62  4550.9  366.55
  4773.5  361.93  4852.3   358.8  4927.7  356.31  4956.4  355.76  4962.8  354.12
  4991.6  355.89    4998   354.6  5020.3  355.01  5023.7  353.48  5026.5  352.98
  5029.7  353.48  5034.6  354.85  5055.4  354.05  5062.6  355.81  5076.2  355.62
  5104.9  359.11  5226.2     364  5333.1  364.99  5339.6  362.69  5347.1  364.57
  5411.4  365.58  5417.8  364.24  5424.7  366.05  5438.7   365.7  5506.3   370.5
#Mann= 5 ,-1 , 0
  4408.4     .05       0  4773.5     .08       0  4852.3     .05       0
  5023.7     .04       0  5029.7     .05       0
Bank Sta=4927.7,5062.6
XS Rating Curve= 0 ,0
Exp/Cntr=0.3,0.1

Type RM Length L Ch R = 1 ,8020    ,526,526,526
BEGIN DESCRIPTION:
UNT 102 IN CACR 11.0
END DESCRIPTION:
XS GIS Cut Line= 3
      3691969.55     10730552.81      3691774.25     10730079.74
      3691289.24     10729694.33
#Sta/Elev= 30
  4183.9   367.3  4249.9     365  4264.8  364.62  4378.2  359.35  4383.6   360.6
  4402.1  359.08  4484.7  358.91  4532.5   360.2  4554.6  363.05  4561.9  361.51
  4585.8  362.59  4597.9  364.58  4615.1  364.48  4620.5   366.4  4692.3  367.66
  4734.4   370.4  4868.9  357.24  4900.9  355.44  4961.8  348.25  4994.1  342.78
  4996.8  342.28  5000.1  342.78  5005.1  344.04    5090  344.92  5133.3  347.84
  5171.7  351.87  5232.6   360.6  5275.8  369.32  5311.1  374.06  5315.2  373.25
#Mann= 7 ,-1 , 0
  4183.9     .05       0  4249.9     .16       0  4264.8     .05       0
  4900.9     .12       0  4994.1     .07       0  5000.1     .12       0
  5171.7     .05       0
Bank Sta=4961.8,5133.3
XS Rating Curve= 0 ,0
Exp/Cntr=0.3,0.1

Type RM Length L Ch R = 1 ,7494    ,365,365,365
BEGIN DESCRIPTION:
UNT 102 IN CACR 10.0
END DESCRIPTION:
XS GIS Cut Line= 3
        3692192.     10729631.77      3691824.79     10729522.39
      3691569.61     10729269.81
#Sta/Elev= 30
  4637.1  352.38  4690.9  352.15  4723.1  350.69  4762.4  346.25  4767.6  346.43
  4775.2  344.65  4827.4  340.93    4834  338.77  4848.3  338.36  4900.3  340.11
  4962.4  338.98  5004.8   338.1  5025.5  339.58  5043.7  337.59  5046.4  337.09
  5049.7  337.59  5096.2  339.78  5159.8  343.27  5202.2   346.9  5223.5  350.21
  5237.6   350.5    5273  355.47  5287.1  356.52  5301.2  359.27  5308.4  359.29
  5336.6  363.93  5343.7  365.96  5357.8  367.38  5375.8  371.54  5379.3  371.54
#Mann= 4 ,-1 , 0
  4637.1     .05       0  4962.4     .12       0  5043.7     .07       0
  5049.7     .12       0
Bank Sta=4827.4,5096.2
XS Rating Curve= 0 ,0
Exp/Cntr=0.3,0.1

Type RM Length L Ch R = 1 ,7129    ,556,556,556
BEGIN DESCRIPTION:
UNT 102 IN CACR 9.0
END DESCRIPTION:
XS GIS Cut Line= 3
       3692503.4     10729446.05      3691939.18     10729172.62
      3691609.27     10729181.31
#Sta/Elev= 30
  4431.3  362.74  4476.8  357.68  4482.3  356.16  4513.3  353.57    4580   344.2
  4624.4  339.53  4640.4  339.92  4654.9  338.55  4753.3   336.6  4790.1  335.88
  4841.2  335.24    4880  334.51  4902.2  340.49  4911.3  338.43  4916.9  335.68
  4936.4  333.43  4939.2  332.93  4942.4  333.43  4949.1  333.43  5034.4   333.9
  5046.7  334.39  5052.3  335.84  5055.3  338.17  5057.1  338.17  5097.9     338
  5156.3  345.14  5237.9   355.2  5287.9  359.84  5337.9  366.68  5388.3     371
#Mann= 10 ,-1 , 0
  4431.3     .12       0  4654.9     .05       0  4790.1     .12       0
  4841.2     .16       0  4936.4     .07       0  4942.4     .16       0
  4949.1     .12       0  5034.4     .05       0  5057.1     .16       0
  5156.3     .12       0
Bank Sta=4753.3,5055.3
XS Rating Curve= 0 ,0
Exp/Cntr=0.3,0.1

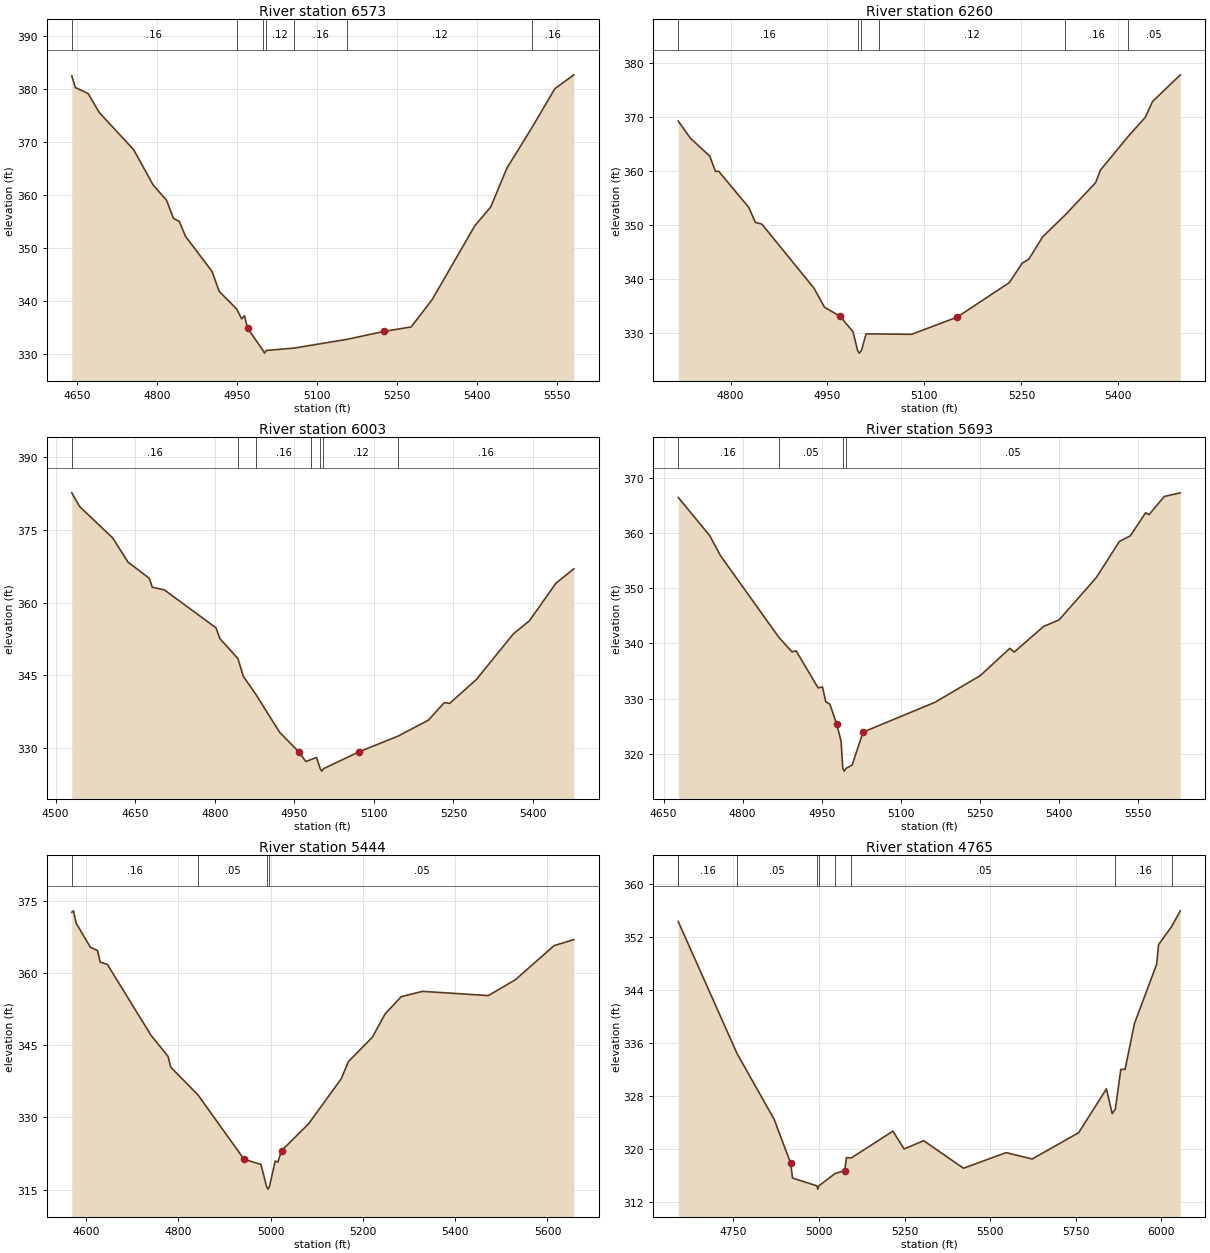
Type RM Length L Ch R = 1 ,6573    ,313,313,313
BEGIN DESCRIPTION:
UNT 102 IN CACR 8.0
END DESCRIPTION:
XS GIS Cut Line= 3
      3692448.19     10728541.84       3692054.1     10728689.41
      3691533.92     10728679.01
#Sta/Elev= 30
    4640  382.46  4646.7  380.26  4670.5  379.14  4691.9  375.51  4755.9  368.55
  4792.7  361.85  4817.7  358.99  4830.7  355.56  4841.4  355.03  4853.3  352.18
  4903.1  345.54  4916.1  341.83  4949.4  338.45  4958.4  336.61  4963.7   337.2
  4969.5  334.87  4998.5  330.65  5001.3  330.15  5004.5  330.65  5056.6   331.1
  5155.9  332.75  5225.3  334.25  5276.1  335.09  5315.4  340.23  5395.4  354.16
  5425.4  357.74  5455.4  365.01    5503  372.77  5545.4  380.04  5581.1  382.66
#Mann= 7 ,-1 , 0
    4640     .16       0  4949.4     .12       0  4998.5     .07       0
  5004.5     .12       0  5056.6     .16       0  5155.9     .12       0
    5503     .16       0
Bank Sta=4969.5,5225.3
XS Rating Curve= 0 ,0
Exp/Cntr=0.3,0.1

Type RM Length L Ch R = 1 ,6260    ,257,257,257
BEGIN DESCRIPTION:
UNT 102 IN CACR 7.0
END DESCRIPTION:
XS GIS Cut Line= 2
      3692278.06     10728357.81       3691506.9     10728451.25
#Sta/Elev= 30
  4719.1  369.22  4737.7  366.07  4767.9  362.72  4776.7  359.89  4781.7  359.92
  4828.3  353.24  4838.4  350.47  4848.5  350.15  4929.1  338.31  4945.4  334.78
  4969.4  333.11  4989.5  330.25  4996.6  326.79  4999.3  326.29  5002.6  326.79
  5009.7  329.85  5029.1  329.83  5080.2  329.77  5150.7  332.95  5231.3  339.33
  5251.4  342.94  5261.5  343.66    5283  347.81    5318  351.87  5364.8  357.81
  5372.3  360.14  5415.2  366.37  5441.7  369.89  5452.9  372.82  5495.9  377.76
#Mann= 6 ,-1 , 0
  4719.1     .16       0  4996.6     .07       0  5002.6     .16       0
  5029.1     .12       0    5318     .16       0  5415.2     .05       0
Bank Sta=4969.4,5150.7
XS Rating Curve= 0 ,0
Exp/Cntr=0.3,0.1

Type RM Length L Ch R = 1 ,6003    ,310,310,310
BEGIN DESCRIPTION:
Mapping XS 253009a9
END DESCRIPTION:
XS GIS Cut Line= 3
        3692393.     10728318.56      3692021.51      10728146.7
      3691486.04     10728105.11
#Sta/Elev= 30
  4530.5  382.69  4545.3  379.86  4607.9  373.35  4636.4   368.4  4676.7  365.04
  4682.2  363.21  4705.1  362.65  4802.4  354.82  4809.7   352.6  4843.7  348.48
  4853.8  344.82  4877.6  341.07  4922.5  333.23  4958.1  329.27  4971.8  327.23
  4981.4  327.63  4991.9  328.07  4998.9  325.74  5001.7  325.24  5004.9  325.74
  5072.1  329.23  5145.4  332.46  5202.5  335.74  5232.6  339.38  5242.6  339.22
  5292.8  344.11    5363  353.59  5393.1  356.27  5443.2  364.04  5476.9     367
#Mann= 7 ,-1 , 0
  4530.5     .16       0  4843.7     .05       0  4877.6     .16       0
  4981.4     .12       0  4998.9     .07       0  5004.9     .12       0
  5145.4     .16       0
Bank Sta=4958.1,5072.1
XS Rating Curve= 0 ,0
Exp/Cntr=0.3,0.1

Type RM Length L Ch R = 1 ,5693    ,249,249,249
BEGIN DESCRIPTION:
UNT 102 IN CACR 6.0
END DESCRIPTION:
XS GIS Cut Line= 2
      3692448.19     10728184.19      3691691.29     10727606.11
#Sta/Elev= 30
  4677.9  366.46  4737.4  359.56  4758.3  355.87  4868.1  341.19  4893.4  338.49
  4901.6  338.64  4943.3  331.93  4951.5  332.12  4957.8  329.41  4965.5     329
  4978.6  325.33  4986.8   322.3  4990.1  317.35  4992.9  316.85  4996.1  317.35
  5007.7  317.94  5028.5  323.92  5165.5  329.35  5250.8  334.16  5306.9  339.11
  5315.2  338.43  5371.3   343.1  5400.4  344.26  5471.1  351.95  5514.7  358.48
  5535.5   359.5  5564.6  363.69  5570.9  363.32  5599.9  366.63  5630.3  367.29
#Mann= 4 ,-1 , 0
  4677.9     .16       0  4868.1     .05       0  4990.1     .03       0
  4996.1     .05       0
Bank Sta=4978.6,5028.5
XS Rating Curve= 0 ,0
Exp/Cntr=0.3,0.1

Type RM Length L Ch R = 1 ,5444    ,679,679,679
BEGIN DESCRIPTION:
UNT 102 IN CACR 5.0
END DESCRIPTION:
XS GIS Cut Line= 3
      3692687.45     10728017.21      3692077.65     10727643.96
        3691744.     10727477.13
#Sta/Elev= 30
  4569.1  372.65  4572.7  372.95  4578.6  370.39  4609.4  365.38  4624.9  364.69
  4630.7  362.29  4646.2  361.82    4741  347.05  4777.6  342.71  4783.6  340.45
  4842.6  334.68  4942.3  321.32    4979  320.22  4991.4  315.59  4994.2  315.09
  4997.4  315.59  5009.9  320.93  5015.8  320.71  5023.8  323.11  5082.4  328.68
  5153.1  338.05  5168.6   341.6  5220.8  346.72  5247.9  351.49  5282.9   355.1
  5329.1  356.21  5471.9  355.33  5530.4  358.62  5614.2  365.71  5657.1  366.97
#Mann= 4 ,-1 , 0
  4569.1     .16       0  4842.6     .05       0  4991.4     .03       0
  4997.4     .05       0
Bank Sta=4942.3,5023.8
XS Rating Curve= 0 ,0
Exp/Cntr=0.3,0.1

Type RM Length L Ch R = 1 ,4765    ,469,469,469
BEGIN DESCRIPTION:
UNT 102 IN CACR 4.0
END DESCRIPTION:
XS GIS Cut Line= 4
       3692946.3     10727878.02      3692902.89     10727535.11
      3692833.45       10727470.      3691853.61     10727166.51
#Sta/Elev= 30
  4588.6  354.41  4588.8  354.36  4760.3  334.42  4868.7  324.46  4917.3  317.78
  4922.3  315.57  4993.5  314.39  4996.3  313.89  4999.5  314.39    5047  316.26
  5074.8  316.69    5080  318.65  5094.5  318.62  5215.7  322.66  5248.3  319.97
  5305.6  321.22  5421.8  317.05  5546.4  319.41  5622.6  318.45  5758.3  322.43
  5839.5  329.07  5856.1  325.33  5865.4  325.99  5881.4  332.01  5893.9  332.02
  5921.3  338.95  5986.1  347.92  5991.7  350.88  6030.5  353.68  6055.2     356
#Mann= 9 ,-1 , 0
  4588.6     .05       0  4588.8     .16       0  4760.3     .05       0
  4993.5     .03       0  4999.5     .05       0    5047     .16       0
  5094.5     .05       0  5865.4     .16       0  6030.5     .05       0
Bank Sta=4917.3,5074.8
XS Rating Curve= 0 ,0
Exp/Cntr=0.3,0.1

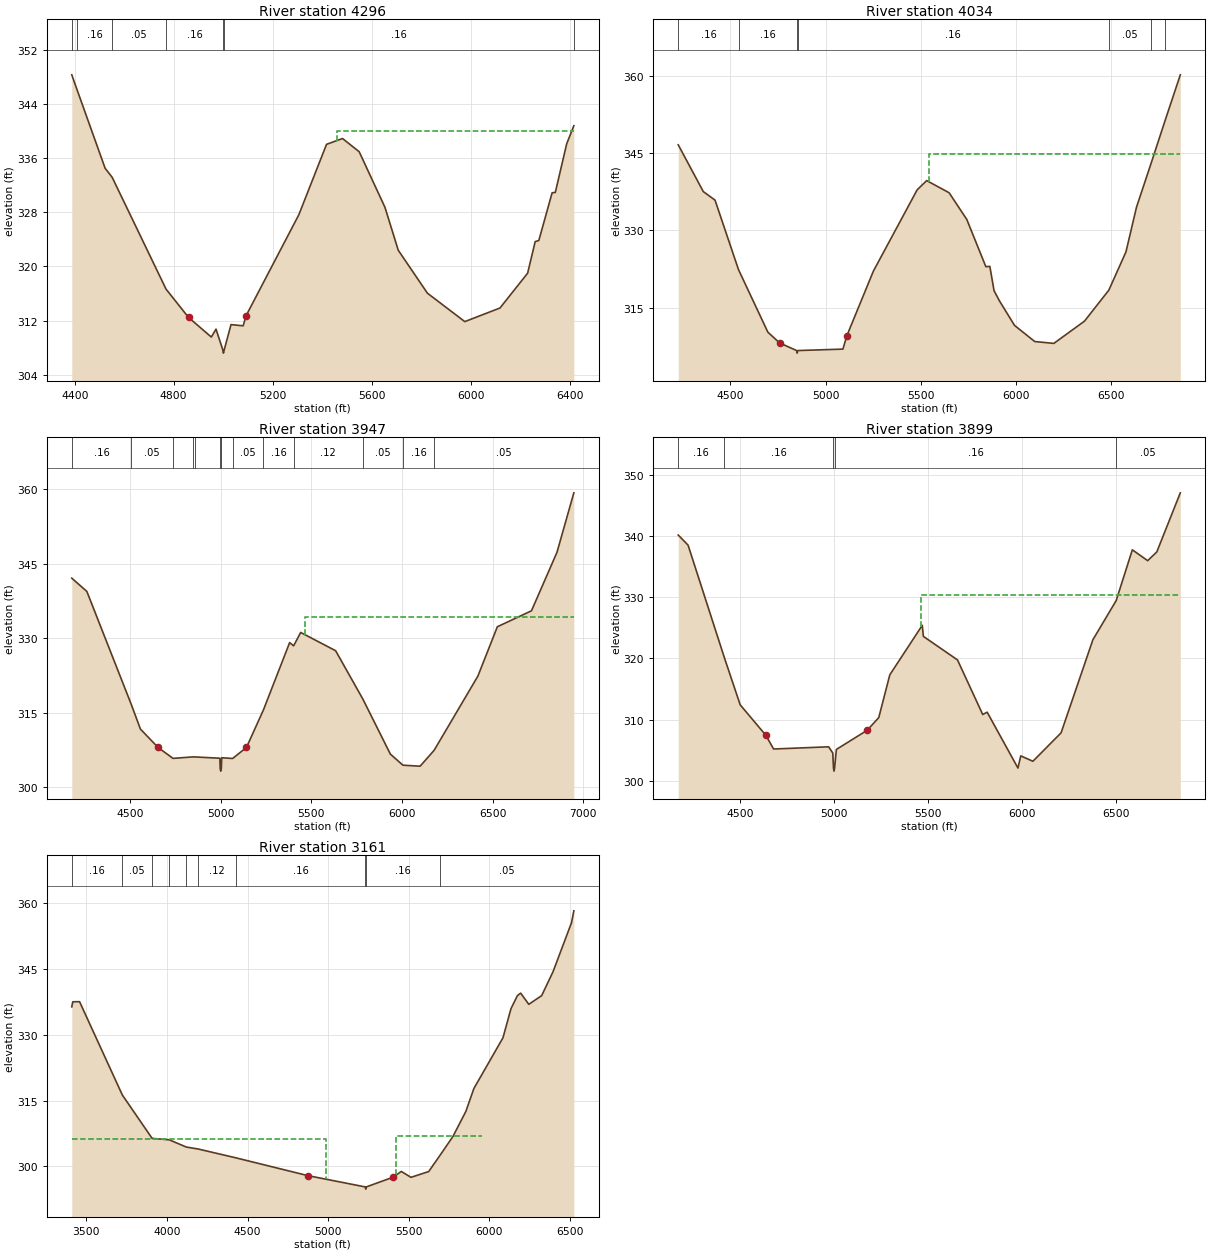
Type RM Length L Ch R = 1 ,4296    ,262,262,262
BEGIN DESCRIPTION:
Mapping XS d88d9c26
END DESCRIPTION:
XS GIS Cut Line= 3
      3693333.84     10727907.25      3693238.36     10727238.86
      3691905.85     10727000.14
#Sta/Elev= 30
  4388.2  348.28  4408.2  346.22  4522.9   334.5  4551.7  333.14  4769.1  316.66
    4860  312.48  4952.2  309.58  4971.1  310.75  4998.4  307.71  5001.2  307.21
  5004.4  307.71  5031.7  311.42  5080.8  311.24  5092.6  312.73  5305.9  327.64
  5417.7  338.02  5482.4  338.88  5549.7  336.93  5653.8  328.73  5707.6  322.39
  5825.3  316.06  5976.4  311.86  6118.7  313.87  6230.4  319.01  6260.9  323.67
  6275.6  323.83  6329.3  330.87  6342.2  330.92  6388.2   338.1  6417.1  340.77
#Mann= 7 ,-1 , 0
  4388.2     .05       0  4408.2     .16       0  4551.7     .05       0
  4769.1     .16       0  4998.4     .07       0  5004.4     .16       0
  6417.1     .16       0
#XS Ineff= 2 , 0
                         5458.81          339.99
Permanent Ineff=
       F       F
Bank Sta=4860,5092.6
XS Rating Curve= 0 ,0
Exp/Cntr=0.3,0.1

Type RM Length L Ch R = 1 ,4034    ,87,87,87
BEGIN DESCRIPTION:
Mapping XS 9dcad548
END DESCRIPTION:
XS GIS Cut Line= 5
      3693621.59     10727818.29      3693456.65     10727119.46
       3692842.5      10727123.8      3692321.67     10726739.69
      3691664.35     10726763.55
#Sta/Elev= 30
  4225.5  346.63  4357.1  337.55  4418.8  335.89  4542.1  322.39  4696.3  310.25
  4757.8  308.16  4847.3  306.68  4850.1  306.18  4853.3  306.68  5090.6  306.96
  5110.6  309.51  5250.6  322.11  5480.6   337.9  5530.6  339.68  5648.3  337.32
  5741.1  332.14  5841.3  322.96  5862.2  323.03  5884.3  318.31  5912.3  316.35
  5991.7  311.57  6098.1  308.43  6198.4  308.07  6359.3  312.39  6487.1   318.4
  6577.2  325.84  6632.2  334.48    6710  343.13    6784  351.49  6862.6  360.22
#Mann= 7 ,-1 , 0
  4225.5     .16       0  4542.1     .16       0  4847.3     .07       0
  4853.3     .16       0  6487.1     .05       0    6710     .16       0
    6784     .05       0
#XS Ineff= 2 , 0
                         5542.61          344.94
Permanent Ineff=
       F       F
Bank Sta=4757.8,5110.6
XS Rating Curve= 0 ,0
Exp/Cntr=0.3,0.1

Type RM Length L Ch R = 1 ,3947    ,48,48,48
BEGIN DESCRIPTION:
Mapping XS 930fba27
END DESCRIPTION:
XS GIS Cut Line= 6
      3693678.09     10727731.47      3693490.58     10727057.81
      3692928.08     10726964.06      3692351.69     10726561.29
      3691858.64     10726453.65      3691577.35     10726516.16
#Sta/Elev= 30
  4177.6  342.12  4260.9  339.44  4505.3  316.75  4556.6  311.71  4653.7  308.02
  4736.3  305.81  4848.3  306.11  4855.1   306.1  4995.1  305.84    4997  303.74
  4999.8  303.24    5003  303.74  5005.3  305.93  5065.7  305.79    5142  308.02
  5235.4  315.56  5380.3  329.14  5402.2  328.48  5441.1  331.18    5634   327.5
  5784.7  317.73  5936.3  306.66  6005.5  304.44  6100.3  304.23  6177.8  307.44
  6419.2  322.38  6526.7  332.33    6715  335.54  6855.9  347.33  6948.9  359.31
#Mann= 13 ,-1 , 0
  4177.6     .16       0  4505.3     .05       0  4736.3     .16       0
  4848.3     .12       0  4855.1     .16       0    4997     .07       0
    5003     .16       0  5065.7     .05       0  5235.4     .16       0
  5402.2     .12       0  5784.7     .05       0  6005.5     .16       0
  6177.8     .05       0
#XS Ineff= 2 , 0
                         5465.35          334.37
Permanent Ineff=
       F       F
Bank Sta=4653.7,5142
XS Rating Curve= 0 ,0
Exp/Cntr=0.3,0.1

Type RM Length L Ch R = 1 ,3899    ,738,738,738
BEGIN DESCRIPTION:
Mapping XS 0a06a8de
END DESCRIPTION:
XS GIS Cut Line= 6
      3693730.17     10727665.48      3693532.25     10727030.04
      3692917.67     10726887.67      3692296.14     10726457.12
      3691941.97     10726429.34      3691674.59      10726446.7
#Sta/Elev= 30
  4169.7  340.13  4222.2  338.48  4416.1  320.07  4499.9  312.42  4636.1  307.47
    4678  305.21  4971.4  305.57  4993.4  304.55    4997   302.1  4999.8   301.6
    5003   302.1  5012.5  305.14  5176.7  308.27  5238.3  310.33  5297.3  317.32
  5470.2   325.4  5476.2  323.59    5658  319.75  5792.4  310.84  5816.1  311.22
  5980.2   302.1  5995.1  304.09  6059.8  303.21    6210  307.85  6379.5  323.04
  6503.6  329.43  6589.8  337.72  6671.4  335.95  6720.1  337.37  6845.4  347.02
#Mann= 5 ,-1 , 0
  4169.7     .16       0  4416.1     .16       0    4997     .07       0
    5003     .16       0  6503.6     .05       0
#XS Ineff= 2 , 0
                         5463.27          330.37
Permanent Ineff=
       F       F
Bank Sta=4636.1,5176.7
XS Rating Curve= 0 ,0
Exp/Cntr=0.3,0.1

Type RM Length L Ch R = 1 ,3161    ,0,0,0
BEGIN DESCRIPTION:
UNT 102 IN CACR 3.0
END DESCRIPTION:
XS GIS Cut Line= 3
      3693785.23     10727655.52      3693299.12      10726349.1
      3691580.34     10726435.91
#Sta/Elev= 30
  3409.2  336.37  3415.6  337.53  3457.6  337.55    3723  316.26  3907.7  306.37
  4013.8  306.04  4119.9  304.39  4192.5  303.95  4428.5  301.92  4872.7  297.88
  5230.2  295.29  5232.9  294.79  5236.2  295.29  5403.4  297.52  5453.5  298.83
  5513.5  297.48  5623.7   298.8  5693.8   302.5  5773.9  306.79    5854  312.51
    5904  317.75  6084.3  329.31  6134.3  335.98  6174.4  338.96  6194.4   339.5
  6244.5  336.95  6324.6  338.94  6394.7  344.36  6509.8  355.59  6524.1  358.28
#Mann= 10 ,-1 , 0
  3409.2     .16       0    3723     .05       0  3907.7     .16       0
  4013.8     .12       0  4119.9     .16       0  4192.5     .12       0
  4428.5     .16       0  5230.2     .03       0  5236.2     .16       0
  5693.8     .05       0
#XS Ineff= 2 ,-1
  3409.2 4986.36   306.3 5420.45 5956.82     307
Permanent Ineff=
       F       F
Bank Sta=4872.7,5403.4
XS Rating Curve= 0 ,0
Exp/Cntr=0.3,0.1

Chan Stop Cuts=-1
Use User Specified Reach Order=0
Composite Channel Slope=5