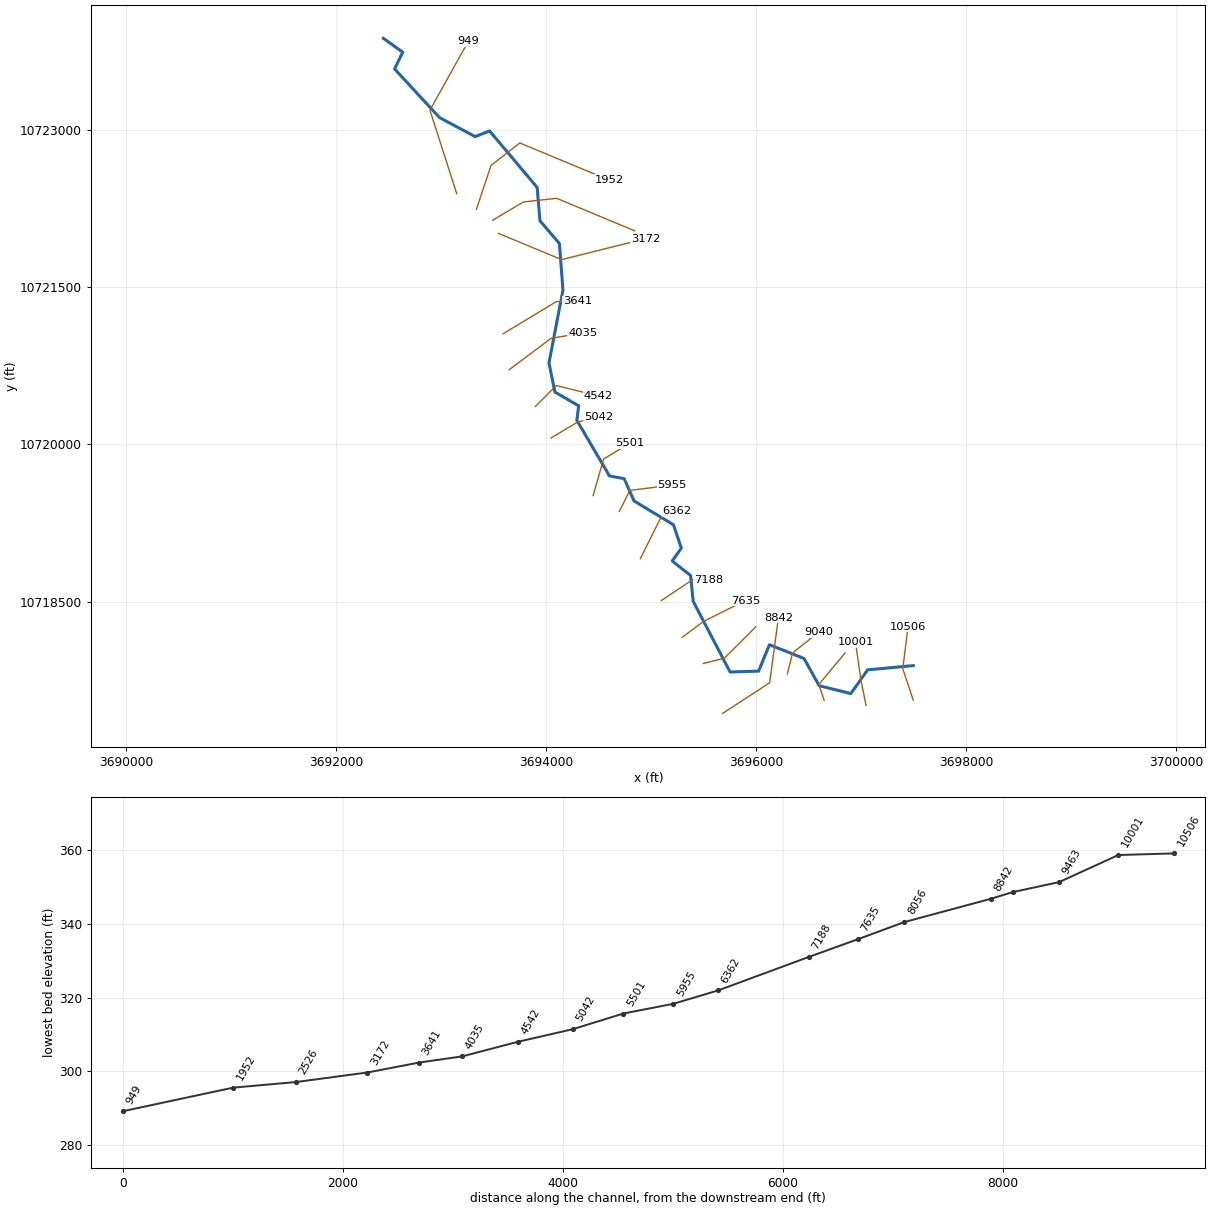
--- UNT 103 IN CACR.prj (project) ---

Proj Title=UNT 103 IN CACR Base Level Engineering
Current Plan=p01
Default Exp/Contr=0.3,0.1
English Units
Geom File=g01
Flow File=f01
Plan File=p01
Y Axis Title=Elevation
X Axis Title(PF)=Main Channel Distance
X Axis Title(XS)=Station
BEGIN DESCRIPTION:
UNT 103 IN CACR
END DESCRIPTION:
DSS Export Rating Curves= 0
DSS Export Rating Curve Sorted= 0
DSS Export Volume Flow Curves= 0
DXF OffsetX= 0
DXF OffsetY= 0
DXF ScaleX= 1
DXF ScaleY= 10

--- UNT 103 IN CACR.p01 (plan) ---

Plan Title=Multiple Run
Short Identifier=Multiple
Geom File=g01
Flow File=f01
Subcritical Flow
K Sum by GR= 0
Std Step Tol= 0.01
Critical Tol= 0.01
Num of Std Step Trials= 20
Max Error Tol= 0.3
Flow Tol Ratio= 0.001
Split Flow NTrial= 30
Split Flow Tol= 0.02
Split Flow Ratio= 0.02
Log Output Level= 0
Friction Slope Method= 1
Unsteady Friction Slope Method= 2
Unsteady Bridges Friction Slope Method= 1
Parabolic Critical Depth
Global Vel Dist=  1 , 1 , 1
Global Log Level= 0
CheckData=True
Encroach Param= -1, 0, 0, 0
BEGIN DESCRIPTION:
Multiple Run
END DESCRIPTION:

--- UNT 103 IN CACR.f01 (steady flow) ---

Flow Title=Multiple
Program Version=4.10
Number of Profiles= 7
Profile Names=10-year,25-year,50-year,1pct_min,100-year,1pct_plu,500-year
River Rch & RM=UNT 103 IN CACR,Reach-1         ,10506
     568     776     949     854    1154    1561    1715
River Rch & RM=UNT 103 IN CACR,Reach-1         ,9040
     819    1137    1406    1277    1727    2335    2615
River Rch & RM=UNT 103 IN CACR,Reach-1         ,1952
    1001    1402    1745    1592    2154    2912    3296
Boundary for River Rch & Prof#=UNT 103 IN CACR,Reach-1         , 1
Up Type= 0
Dn Type= 3
Dn Slope=0.00637
Boundary for River Rch & Prof#=UNT 103 IN CACR,Reach-1         , 2
Up Type= 0
Dn Type= 3
Dn Slope=0.00637
Boundary for River Rch & Prof#=UNT 103 IN CACR,Reach-1         , 3
Up Type= 0
Dn Type= 3
Dn Slope=0.00637
Boundary for River Rch & Prof#=UNT 103 IN CACR,Reach-1         , 4
Up Type= 0
Dn Type= 3
Dn Slope=0.00637
Boundary for River Rch & Prof#=UNT 103 IN CACR,Reach-1         , 5
Up Type= 0
Dn Type= 3
Dn Slope=0.00637
Boundary for River Rch & Prof#=UNT 103 IN CACR,Reach-1         , 6
Up Type= 0
Dn Type= 3
Dn Slope=0.00637
Boundary for River Rch & Prof#=UNT 103 IN CACR,Reach-1         , 7
Up Type= 0
Dn Type= 3
Dn Slope=0.00637
DSS Import GetInterval= 0
DSS Import GetPeak= 0
DSS Import FillOption= 0

--- UNT 103 IN CACR.g01 (geometry) ---

Geom Title=Existing Conditions
Program Version=4.10

River Reach=UNT 103 IN CACR ,Reach-1
Reach XY= 30
       3697499.5       10717890.       3697064.5       10717849.
        3696905.       10717623.        3696603.       10717698.
      3696458.75       10717958.       3696129.5       10718089.
      3696026.25       10717837.      3695754.25       10717829.
      3695403.25       10718502.        3695378.       10718749.
      3695203.25       10718887.        3695290.       10719010.
      3695214.75       10719233.      3694839.25       10719460.
      3694745.75       10719672.      3694605.25       10719698.
      3694294.75       10720228.        3694312.       10720367.
        3694086.       10720497.        3694029.       10720775.
      3694162.25       10721470.       3694128.5       10721914.
        3693943.       10722131.      3693916.25       10722449.
      3693463.25       10722987.        3693326.       10722933.
        3692987.       10723114.      3692558.25       10723578.
      3692636.25       10723738.        3692452.       10723870.

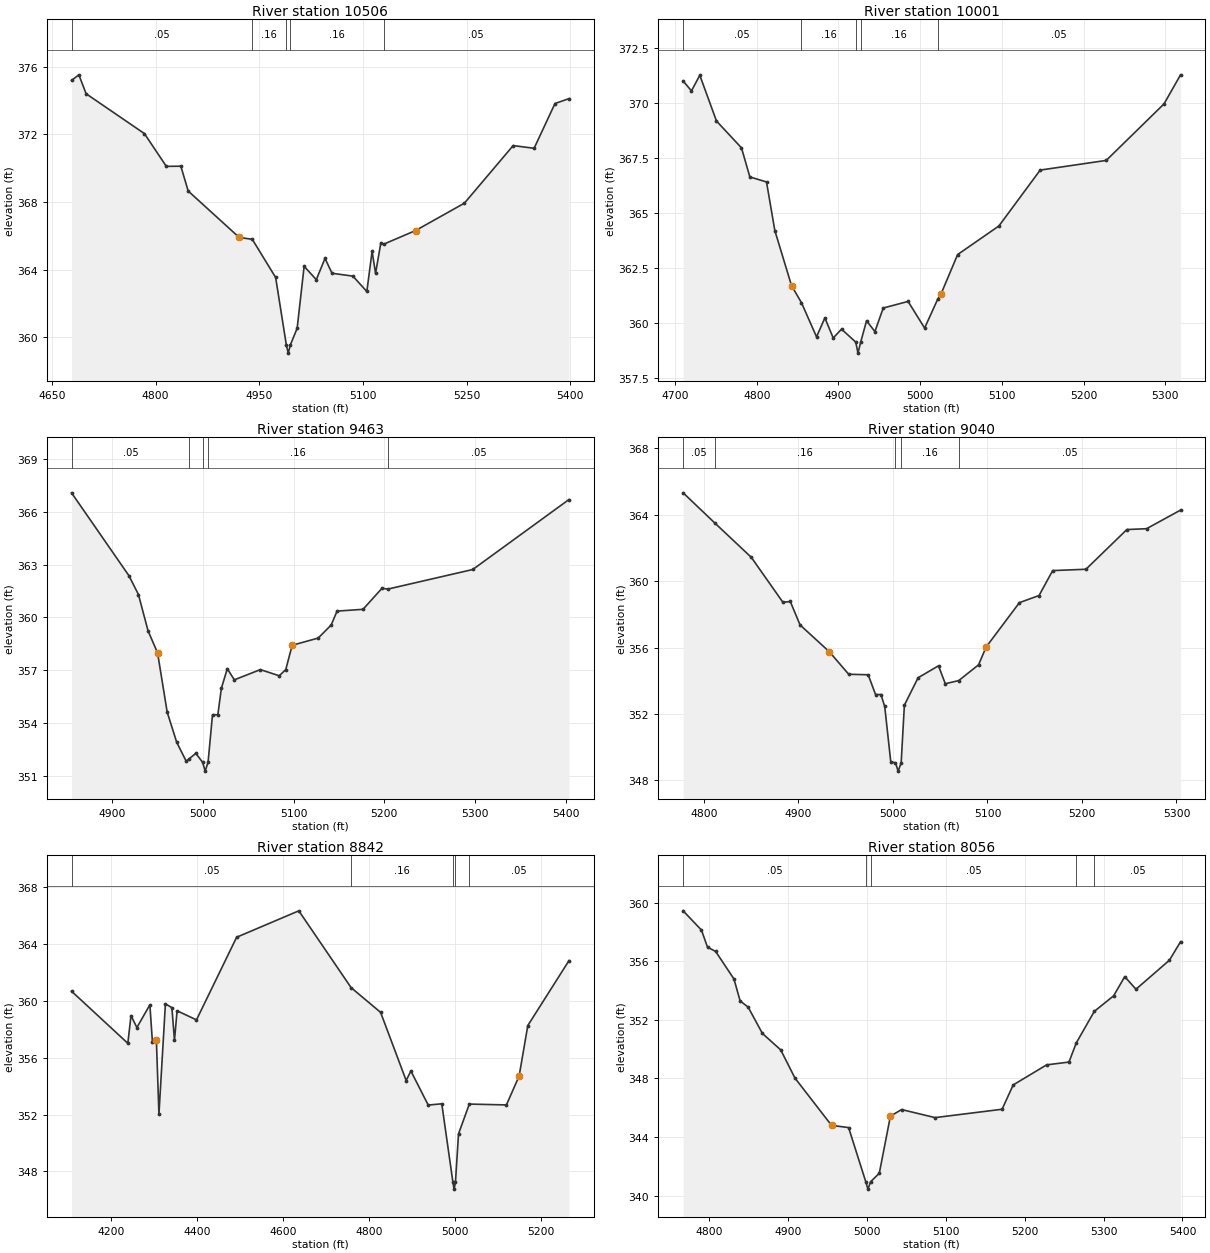
Type RM Length L Ch R = 1 ,10506   ,505,505,505
BEGIN DESCRIPTION:
UNT 103 IN CACR 18.0
END DESCRIPTION:
XS GIS Cut Line= 3
      3697499.62     10717560.17      3697399.61     10717860.19
      3697449.61     10718260.23
#Sta/Elev= 30
  4678.5   375.2  4689.1  375.53  4699.6  374.41  4783.9  372.05  4815.6  370.11
  4836.6  370.12  4847.2  368.65    4921   365.9  4939.9  365.79  4973.7  363.53
  4989.1  359.55  4991.9  359.05  4995.1  359.55  5004.8  360.52  5014.9  364.19
  5032.5   363.4  5045.1  364.66  5055.2  363.78  5085.4  363.61  5105.6   362.7
  5113.2  365.08  5118.2  363.77  5125.8  365.57  5129.9   365.5  5176.1  366.31
  5246.7  367.93  5317.2  371.34  5347.5  371.18  5377.7  373.83  5397.9  374.12
#Mann= 5 ,-1 , 0
  4678.5     .05       0  4939.9     .16       0  4989.1     .07       0
  4995.1     .16       0  5129.9     .05       0
Bank Sta=4921,5176.1
XS Rating Curve= 0 ,0
Exp/Cntr=0.3,0.1

Type RM Length L Ch R = 1 ,10001   ,538,538,538
BEGIN DESCRIPTION:
UNT 103 IN CACR 17.0
END DESCRIPTION:
XS GIS Cut Line= 3
      3697049.61     10717510.17      3696999.61     10717760.19
      3696949.61     10718110.16
#Sta/Elev= 30
    4710  370.98  4720.2  370.53  4730.4  371.24  4750.8  369.16  4781.4  367.94
  4791.6  366.62    4812  366.39  4822.2  364.18  4842.6  361.68  4854.8   360.9
  4873.2  359.35  4883.4  360.21  4893.6   359.3  4903.8   359.7  4921.2  359.11
  4923.9  358.61  4927.2  359.11  4934.4  360.08  4944.6  359.59  4954.8  360.66
  4985.2  360.96  5005.4  359.75  5021.3  361.05  5025.6  361.31  5045.8  363.09
  5096.3  364.39  5146.8  366.93  5227.6  367.37  5298.3  369.94  5318.5  371.26
#Mann= 5 ,-1 , 0
    4710     .05       0  4854.8     .16       0  4921.2     .07       0
  4927.2     .16       0  5021.3     .05       0
Bank Sta=4842.6,5025.6
XS Rating Curve= 0 ,0
Exp/Cntr=0.3,0.1

Type RM Length L Ch R = 1 ,9463    ,423,423,423
BEGIN DESCRIPTION:
UNT 103 IN CACR 16.0
END DESCRIPTION:
XS GIS Cut Line= 3
      3696649.62     10717560.14      3696599.61     10717710.19
      3696849.62     10718010.21
#Sta/Elev= 30
  4855.1  367.07  4918.4  362.37  4928.9   361.3  4939.5  359.24    4950  357.99
  4960.6  354.63  4971.1  352.92  4981.6  351.84  4985.1  351.99  4992.2  352.29
  4999.7  351.78  5002.5  351.28  5005.7  351.78  5010.6  354.48  5016.5  354.48
  5020.4  355.98  5026.9  357.09  5034.7  356.46  5063.4  357.04  5084.2  356.69
  5091.4  357.04  5098.5  358.42  5127.2  358.83  5141.5  359.57    5148  360.36
  5176.6  360.46  5197.5  361.65  5204.2  361.61  5297.7  362.72  5403.8  366.69
#Mann= 5 ,-1 , 0
  4855.1     .05       0  4985.1     .16       0  4999.7     .07       0
  5005.7     .16       0  5204.2     .05       0
Bank Sta=4950,5098.5
XS Rating Curve= 0 ,0
Exp/Cntr=0.3,0.1

Type RM Length L Ch R = 1 ,9040    ,198,198,198
BEGIN DESCRIPTION:
UNT 103 IN CACR 15.0
END DESCRIPTION:
XS GIS Cut Line= 3
      3696299.61     10717810.21      3696349.61     10718010.19
      3696599.62     10718210.19
#Sta/Elev= 30
    4778  365.31  4811.6  363.49  4850.1  361.43  4883.6  358.72  4891.4  358.77
  4901.7  357.36  4932.6  355.75  4953.2  354.39  4973.8  354.36  4981.6  353.17
  4987.3  353.17  4991.3  352.45  4997.7  349.12  5002.7  349.06  5005.5  348.56
  5008.7  349.06  5012.1  352.53  5026.6  354.18  5048.2   354.9  5055.4  353.82
  5069.6  354.01  5090.6  354.96  5098.6  356.03  5133.8   358.7  5154.6  359.13
    5169  360.63  5204.2  360.71  5247.5   363.1  5268.3  363.15  5304.3  364.27
#Mann= 5 ,-1 , 0
    4778     .05       0  4811.6     .16       0  5002.7     .07       0
  5008.7     .16       0  5069.6     .05       0
Bank Sta=4932.6,5098.6
XS Rating Curve= 0 ,0
Exp/Cntr=0.3,0.1

Type RM Length L Ch R = 1 ,8842    ,786,786,786
BEGIN DESCRIPTION:
Mapping XS d0121aa6
END DESCRIPTION:
XS GIS Cut Line= 3
      3695683.44     10717434.38      3696131.36     10717726.05
      3696214.61     10718345.27
#Sta/Elev= 30
  4106.9  360.69  4238.1  357.02  4245.5  358.97  4259.2  358.13  4289.5  359.73
  4295.4  357.11  4304.6  357.28  4310.6  352.03  4325.7   359.8  4340.8  359.53
  4346.8  357.23  4352.9  359.31  4398.1  358.67  4491.7  364.49  4636.6  366.35
  4758.5  360.94  4827.2   359.2  4886.8   354.4  4897.8  355.07  4938.2  352.67
  4969.8  352.76  4995.7  347.25  4998.5  346.75  5001.7  347.25  5008.8  350.64
    5034  352.74  5120.5  352.68  5150.1  354.72  5170.3  358.27  5266.2  362.84
#Mann= 5 ,-1 , 0
  4106.9     .05       0  4758.5     .16       0  4995.7     .07       0
  5001.7     .16       0    5034     .05       0
Bank Sta=4304.6,5150.1
XS Rating Curve= 0 ,0
Exp/Cntr=0.3,0.1

Type RM Length L Ch R = 1 ,8056    ,421,421,421
BEGIN DESCRIPTION:
UNT 103 IN CACR 14.0
END DESCRIPTION:
XS GIS Cut Line= 3
       3695499.6     10717910.19      3695699.61     10717960.19
      3695999.59     10718260.17
#Sta/Elev= 30
  4767.2  359.44  4790.4  358.13  4798.1  356.96  4808.4  356.67  4831.6  354.79
  4839.4   353.3  4849.7  352.86  4867.7  351.07  4890.9  349.95  4908.9  348.03
  4955.3   344.8  4976.9  344.65  4998.7  340.95  5001.4  340.45  5004.7  340.95
  5015.8  341.53  5029.9  345.43  5044.1  345.88  5086.5  345.33  5171.4   345.9
  5185.5  347.56  5227.9  348.93  5256.2  349.12  5265.4  350.42  5288.3  352.58
  5312.8  353.64  5326.9  354.95  5341.1  354.09  5383.5  356.07  5397.6  357.33
#Mann= 5 ,-1 , 0
  4767.2     .05       0  4998.7     .03       0  5004.7     .05       0
  5265.4     .16       0  5288.3     .05       0
Bank Sta=4955.3,5029.9
XS Rating Curve= 0 ,0
Exp/Cntr=0.3,0.1

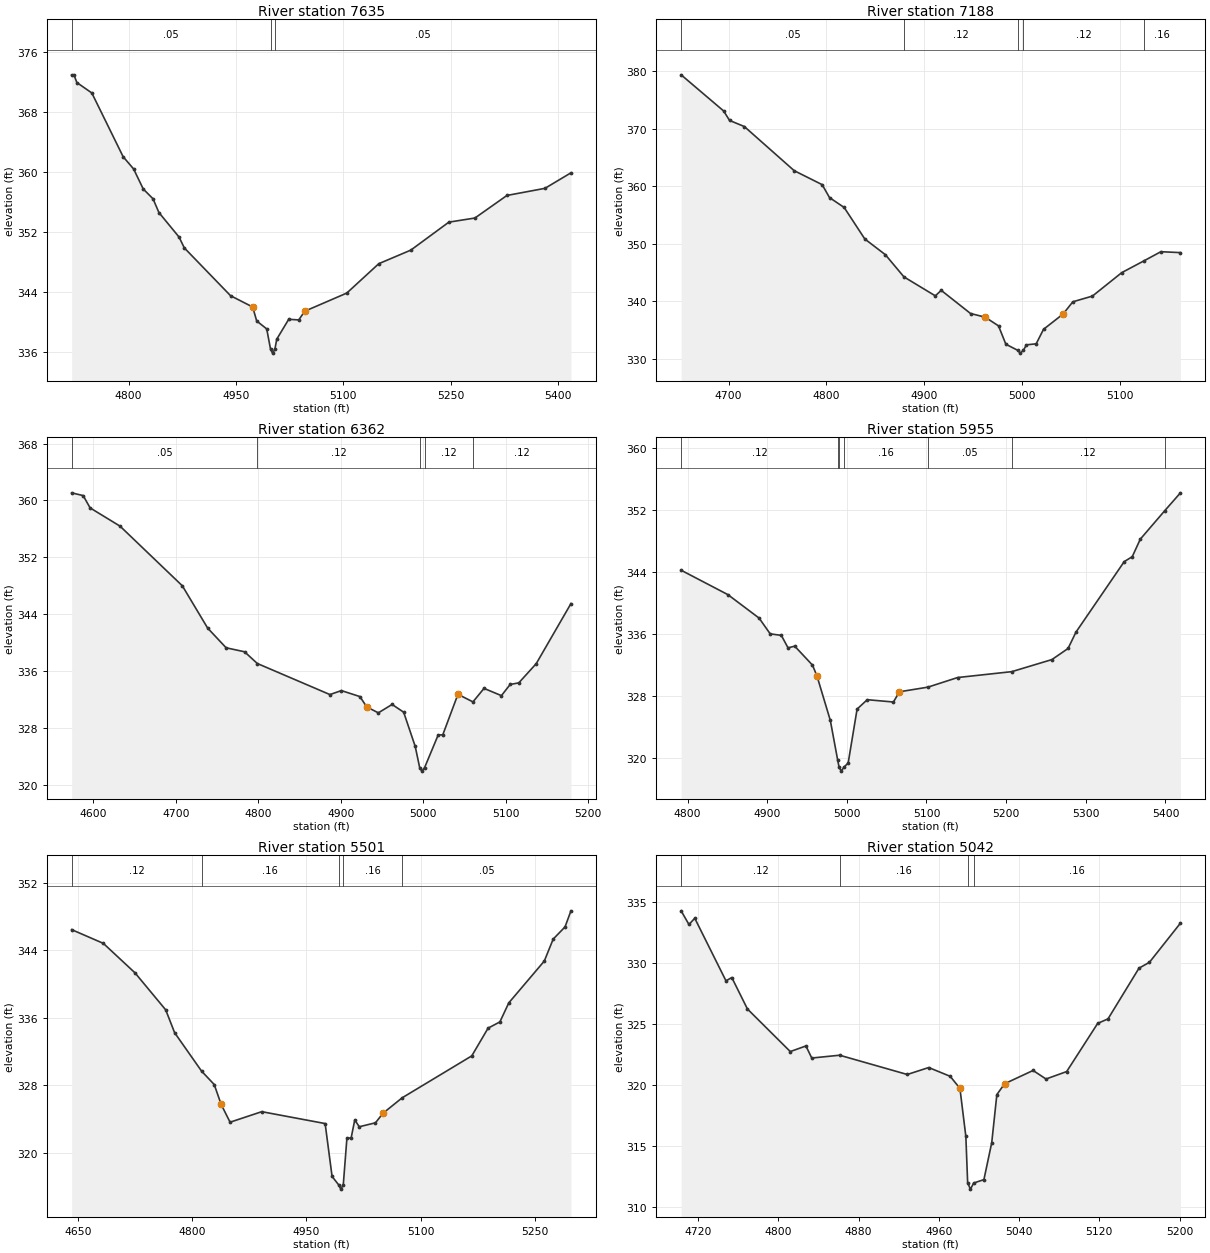
Type RM Length L Ch R = 1 ,7635    ,447,447,447
BEGIN DESCRIPTION:
UNT 103 IN CACR 13.0
END DESCRIPTION:
XS GIS Cut Line= 3
      3695299.59     10718160.17      3695499.61     10718310.19
      3695899.57     10718510.17
#Sta/Elev= 30
  4720.5  372.94  4723.7  372.94  4727.8  371.91  4748.7  370.52  4792.4  362.02
    4807  360.39  4820.5  357.71  4834.1  356.41  4842.4  354.57  4870.5   351.3
  4877.8  349.86  4942.4  343.48  4973.3  341.97  4978.9  340.11  4992.9  339.05
  4998.3  336.32    5001  335.82  5004.3  336.32  5006.9  337.68  5023.6  340.33
  5037.6  340.25    5046  341.41  5104.7  343.83  5149.4  347.75  5194.1  349.56
  5247.2  353.29  5283.6  353.84  5328.3  356.85  5381.4   357.8  5417.7  359.87
#Mann= 3 ,-1 , 0
  4720.5     .05       0  4998.3     .03       0  5004.3     .05       0
Bank Sta=4973.3,5046
XS Rating Curve= 0 ,0
Exp/Cntr=0.3,0.1

Type RM Length L Ch R = 1 ,7188    ,826,826,826
BEGIN DESCRIPTION:
UNT 103 IN CACR 12.0
END DESCRIPTION:
XS GIS Cut Line= 3
      3695099.64     10718510.21      3695399.61     10718710.19
      3695549.59     10718710.19
#Sta/Elev= 30
  4651.4  379.41  4694.9  373.12  4700.9  371.48    4716  370.42    4767  362.74
  4795.6  360.31  4803.1  358.06  4818.1  356.34  4839.2  350.86  4860.2  348.13
  4879.2  344.27  4911.3  340.97  4917.3  341.93  4947.3   337.9  4962.3  337.26
  4975.9  335.75  4983.4  332.56  4995.4  331.51  4998.2  331.01  5001.4  331.51
  5004.4  332.45  5014.4  332.63  5021.9  335.15  5041.9  337.81  5051.9  339.94
  5071.9  340.93  5101.9  345.01  5124.6  347.06  5141.9  348.65  5161.9  348.49
#Mann= 5 ,-1 , 0
  4651.4     .05       0  4879.2     .12       0  4995.4     .07       0
  5001.4     .12       0  5124.6     .16       0
Bank Sta=4962.3,5041.9
XS Rating Curve= 0 ,0
Exp/Cntr=0.3,0.1

Type RM Length L Ch R = 1 ,6362    ,407,407,407
BEGIN DESCRIPTION:
UNT 103 IN CACR 11.0
END DESCRIPTION:
XS GIS Cut Line= 3
       3694899.6     10718910.18      3695099.61     10719310.19
      3695249.57     10719360.18
#Sta/Elev= 30
  4573.7  361.07  4587.7  360.68  4596.1  358.95  4632.4  356.38  4707.9  347.99
  4738.6  342.04    4761  339.27  4783.3  338.71  4798.8  337.06  4886.8  332.69
  4900.7  333.25  4923.1  332.41  4931.5  330.95  4945.5  330.12  4962.2   331.3
  4976.2  330.21  4990.2   325.4  4995.6  322.42  4998.3  321.92  5001.6  322.42
  5018.1  327.02  5023.6  327.02    5042  332.73  5060.2  331.66  5073.6  333.56
  5094.7  332.54  5105.3  334.11  5115.8  334.34  5136.9  337.04    5179  345.49
#Mann= 5 ,-1 , 0
  4573.7     .05       0  4798.8     .12       0  4995.6     .07       0
  5001.6     .12       0  5060.2     .12       0
Bank Sta=4931.5,5042
XS Rating Curve= 0 ,0
Exp/Cntr=0.3,0.1

Type RM Length L Ch R = 1 ,5955    ,454,454,454
BEGIN DESCRIPTION:
UNT 103 IN CACR 10.0
END DESCRIPTION:
XS GIS Cut Line= 3
      3694699.59     10719360.15      3694799.61     10719560.19
      3695199.65     10719610.19
#Sta/Elev= 30
    4792  344.23  4850.7  341.08  4889.9  338.05  4903.8  336.02  4917.8  335.82
  4926.2  334.21  4934.6  334.43  4956.9  331.98  4962.5  330.59  4979.3  324.84
  4988.6  319.68  4990.3   318.8    4993   318.3  4996.3   318.8  5001.7  319.35
  5012.9  326.31  5025.7  327.52  5058.5  327.22    5066  328.54  5101.8  329.14
  5139.1  330.38  5207.1  331.14  5257.5   332.7  5277.7  334.13  5287.7  336.25
  5348.2  345.34  5358.3  345.98  5368.4  348.24  5398.9  351.89  5418.8  354.22
#Mann= 7 ,-1 , 0
    4792     .12       0  4988.6     .16       0  4990.3     .07       0
  4996.3     .16       0  5101.8     .05       0  5207.1     .12       0
  5398.9     .05       0
Bank Sta=4962.5,5066
XS Rating Curve= 0 ,0
Exp/Cntr=0.3,0.1

Type RM Length L Ch R = 1 ,5501    ,459,459,459
BEGIN DESCRIPTION:
UNT 103 IN CACR 9.0
END DESCRIPTION:
XS GIS Cut Line= 3
      3694449.62     10719510.23      3694549.61     10719860.19
       3694799.6     10720010.18
#Sta/Elev= 30
    4642  346.45  4683.6  344.82  4725.2  341.32  4765.5  336.93  4777.2  334.22
  4812.6  329.66  4829.2  328.07  4838.3  325.71    4850   323.6  4891.6  324.85
  4974.8  323.44  4983.9  317.17  4992.6  316.16  4995.3  315.66  4998.6  316.16
  5003.4  321.72  5008.9  321.72  5013.7  323.87  5019.6  323.06  5040.9  323.53
  5050.7  324.66    5076   326.5  5167.3  331.47  5188.7  334.76  5204.2   335.5
  5215.9  337.76  5262.5  342.72  5274.2  345.33  5289.7  346.77  5297.5  348.68
#Mann= 5 ,-1 , 0
    4642     .12       0  4812.6     .16       0  4992.6     .07       0
  4998.6     .16       0    5076     .05       0
Bank Sta=4838.3,5050.7
XS Rating Curve= 0 ,0
Exp/Cntr=0.3,0.1

Type RM Length L Ch R = 1 ,5042    ,500,500,500
BEGIN DESCRIPTION:
UNT 103 IN CACR 8.0
END DESCRIPTION:
XS GIS Cut Line= 3
      3694049.63      10720060.2      3694299.61     10720210.19
      3694499.63     10720260.19
#Sta/Elev= 30
  4703.2  334.25    4711  333.13  4716.8  333.64  4747.9  328.51  4753.7  328.78
  4769.3   326.2    4812  322.71  4827.6  323.17  4833.4  322.18  4861.2  322.41
  4928.6  320.83    4950   321.4  4971.4  320.68  4981.1  319.69    4987  315.75
  4988.8  311.93  4991.6  311.43  4994.8  311.93    5005  312.21  5012.8  315.24
  5017.9  319.18  5025.6  320.07    5054  321.16  5066.9  320.46  5087.5  321.07
  5118.4  325.02  5128.7  325.39  5159.6  329.55    5170  330.03  5200.9  333.24
#Mann= 4 ,-1 , 0
  4703.2     .12       0  4861.2     .16       0  4988.8     .07       0
  4994.8     .16       0
Bank Sta=4981.1,5025.6
XS Rating Curve= 0 ,0
Exp/Cntr=0.3,0.1

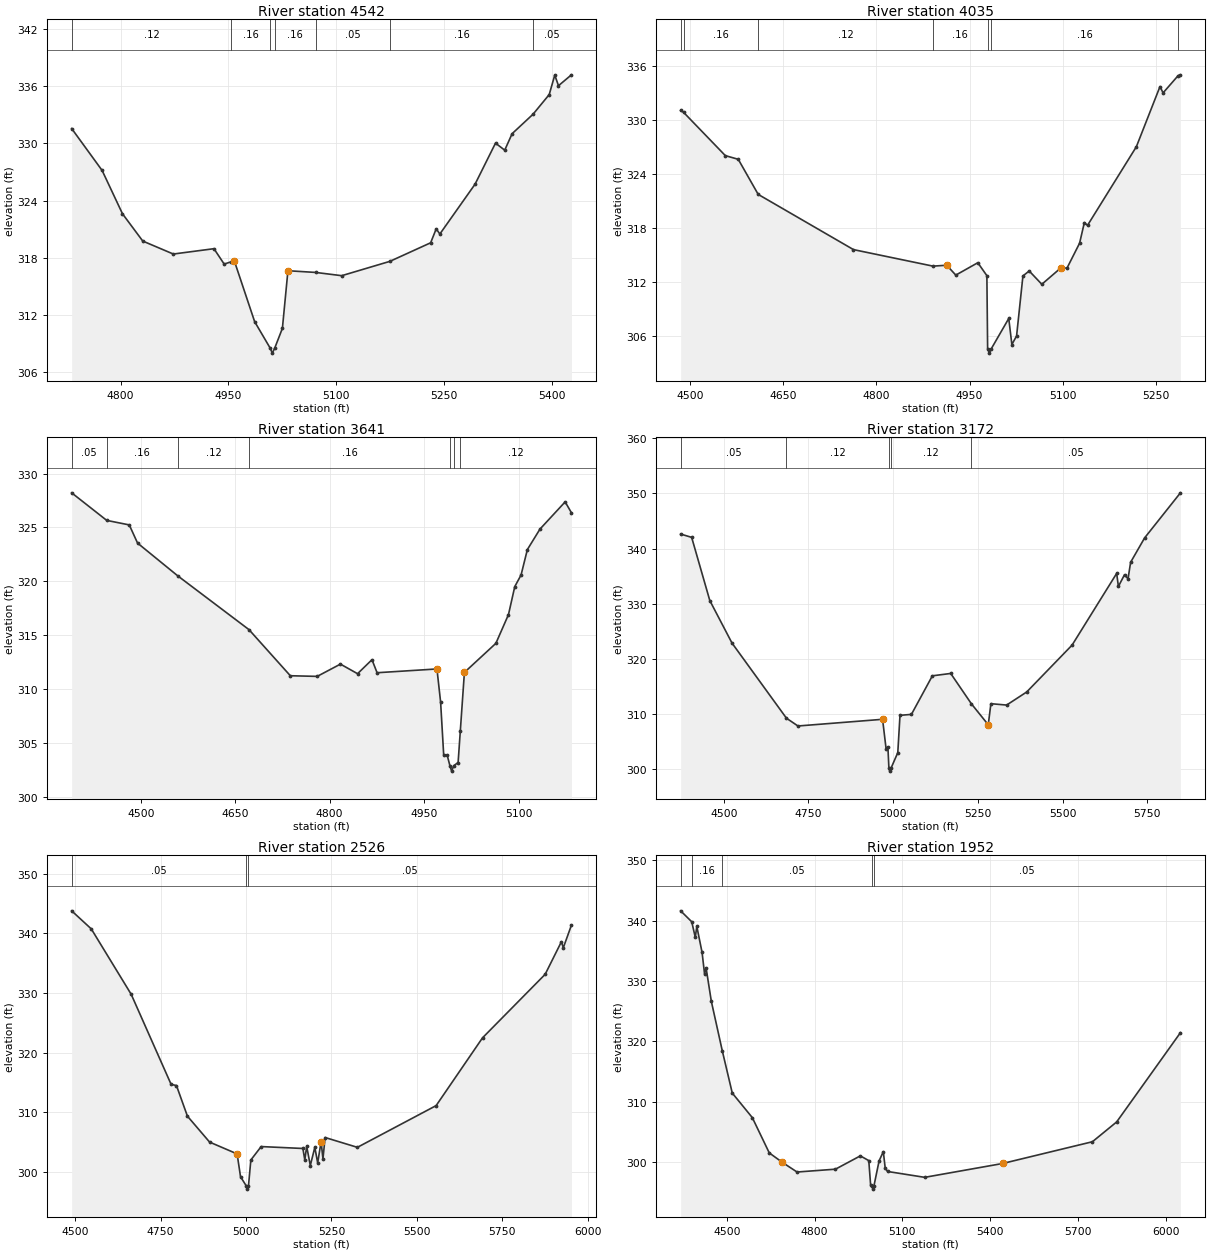
Type RM Length L Ch R = 1 ,4542    ,507,507,507
BEGIN DESCRIPTION:
UNT 103 IN CACR 7.0
END DESCRIPTION:
XS GIS Cut Line= 3
      3693899.64     10720360.22      3694099.61     10720560.19
       3694499.6     10720460.19
#Sta/Elev= 30
    4732  331.55  4774.4  327.15  4802.7  322.61  4830.9  319.75  4873.4  318.39
  4929.9  318.95  4944.1  317.34  4954.2  317.58  4958.2  317.68  4986.5   311.3
  5008.3   308.5    5011     308  5014.3   308.5  5025.1   310.6  5032.8  316.64
  5071.5  316.46  5107.6  316.12  5174.5  317.62  5231.3  319.57    5239  321.03
  5244.1  320.49  5293.1  325.72  5321.5  330.02  5334.3  329.28  5344.6  331.01
  5373.7  333.05  5396.2  335.11  5403.9  337.15  5409.1  336.04  5427.1  337.18
#Mann= 7 ,-1 , 0
    4732     .12       0  4954.2     .16       0  5008.3     .07       0
  5014.3     .16       0  5071.5     .05       0  5174.5     .16       0
  5373.7     .05       0
Bank Sta=4958.2,5032.8
XS Rating Curve= 0 ,0
Exp/Cntr=0.3,0.1

Type RM Length L Ch R = 1 ,4035    ,394,394,394
BEGIN DESCRIPTION:
UNT 103 IN CACR 6.0
END DESCRIPTION:
XS GIS Cut Line= 3
      3693649.62      10720710.2      3694049.61     10721010.19
      3694349.59     10721060.18
#Sta/Elev= 30
  4485.1  331.08  4489.7  330.88    4557  326.05  4577.8  325.64  4609.9  321.73
  4763.2  315.58  4891.1  313.74  4913.2  313.84  4927.8  312.74  4963.2  314.12
  4977.8  312.68    4979  304.55  4981.7  304.05    4985  304.55    5013  307.91
    5018  305.01  5025.6  305.96  5035.8  312.65  5045.9   313.2  5066.2  311.72
  5096.6  313.53  5106.7  313.52    5127   316.3  5134.6  318.59  5139.7  318.28
  5218.3  327.04  5256.3  333.74  5261.3  333.04  5285.4  334.95  5289.2  335.05
#Mann= 7 ,-1 , 0
  4485.1     .05       0  4489.7     .16       0  4609.9     .12       0
  4891.1     .16       0    4979     .07       0    4985     .16       0
  5285.4     .05       0
Bank Sta=4913.2,5096.6
XS Rating Curve= 0 ,0
Exp/Cntr=0.3,0.1

Type RM Length L Ch R = 1 ,3641    ,469,469,469
BEGIN DESCRIPTION:
UNT 103 IN CACR 5.0
END DESCRIPTION:
XS GIS Cut Line= 3
       3693591.3     10721053.25      3694099.61     10721360.19
      3694299.61     10721362.26
#Sta/Elev= 30
  4390.2  328.21  4445.9  325.65  4481.7  325.23  4494.9  323.54  4558.9  320.49
  4671.9   315.5  4737.5  311.22  4780.2  311.16  4817.1   312.3  4844.3  311.41
  4867.2  312.71  4875.3   311.5  4970.4  311.85  4976.2  308.78  4981.1  303.87
  4986.5  303.87    4991  302.86  4993.7  302.36    4997  302.86    5004  303.16
  5007.5  306.09    5014  311.53    5064  314.23    5084   316.9    5094   319.5
    5104  320.58    5114  322.94    5134  324.84    5174  327.37    5184  326.36
#Mann= 7 ,-1 , 0
  4390.2     .05       0  4445.9     .16       0  4558.9     .12       0
  4671.9     .16       0    4991     .07       0    4997     .16       0
  5007.5     .12       0
Bank Sta=4970.4,5014
XS Rating Curve= 0 ,0
Exp/Cntr=0.3,0.1

Type RM Length L Ch R = 1 ,3172    ,646,646,646
BEGIN DESCRIPTION:
UNT 103 IN CACR 4.0
END DESCRIPTION:
XS GIS Cut Line= 3
      3693549.65     10722010.17      3694149.61     10721760.19
      3694949.63     10721960.19
#Sta/Elev= 30
  4372.8  342.63  4405.3  342.03  4458.9  330.57  4524.4  322.87    4685  309.26
  4718.9  307.85  4968.6  309.06  4978.9  303.75  4984.3  304.06  4987.3  300.17
    4990  299.67  4993.3  300.17  5013.5  303.02    5020  309.78  5053.7  309.95
  5115.5  316.94  5169.6  317.37  5230.9  311.85  5280.4  308.07  5288.2  311.89
  5334.6  311.64  5393.8  314.01  5527.8  322.51  5659.3   335.5  5664.4  333.14
  5682.5  335.27  5692.8  334.52  5700.5  337.52  5741.7  341.93  5847.4   350.1
#Mann= 5 ,-1 , 0
  4372.8     .05       0    4685     .12       0  4987.3     .07       0
  4993.3     .12       0  5230.9     .05       0
Bank Sta=4968.6,5280.4
XS Rating Curve= 0 ,0
Exp/Cntr=0.3,0.1

Type RM Length L Ch R = 1 ,2526    ,574,574,574
BEGIN DESCRIPTION:
UNT 103 IN CACR 3.0
END DESCRIPTION:
XS GIS Cut Line= 4
      3693494.06     10722136.57      3693785.73     10722310.18
       3694101.7      10722344.9      3694845.15     10722035.41
#Sta/Elev= 30
  4489.8  343.79  4547.2  340.76    4664  329.79  4780.9  314.67  4796.5  314.48
  4828.6  309.34  4893.5  304.99    4974  303.01    4984  299.19  5001.2   297.6
  5003.9   297.1  5007.2   297.6  5014.2  301.99  5044.4  304.24  5166.5  303.92
  5172.1  301.99  5177.6  304.28  5188.2  301.06  5201.4  304.11  5209.8   301.5
  5219.8  305.05  5225.2  302.18  5231.5  305.76    5326  304.11  5556.4  311.11
  5692.3  322.49  5875.5  333.14  5923.1  338.61  5928.6  337.59  5952.4  341.39
#Mann= 3 ,-1 , 0
  4489.8     .05       0  5001.2     .03       0  5007.2     .05       0
Bank Sta=4974,5219.8
XS Rating Curve= 0 ,0
Exp/Cntr=0.3,0.1

Type RM Length L Ch R = 1 ,1952    ,1003,1003,1003
BEGIN DESCRIPTION:
Mapping XS c32c2d2b
END DESCRIPTION:
XS GIS Cut Line= 4
       3693337.8      10722240.7       3693476.7      10722657.4
        3693751.     10722872.68      3694600.79     10722518.96
#Sta/Elev= 30
    4342  341.61  4379.9   339.8    4392  337.24  4397.3  339.02  4415.3  334.72
  4423.7  331.19  4428.9  332.19  4446.9  326.64  4484.6   318.4  4518.5  311.46
    4587   307.4    4645  301.56  4689.3  300.01  4739.9   298.4  4871.2  298.87
  4956.2  301.07  4985.1  300.29  4991.5   296.2  4996.6  296.07  4999.3  295.57
  5002.6  296.07  5020.4  300.25  5034.8  301.77  5041.2  299.08  5049.3  298.49
  5176.3  297.52  5442.5  299.81  5749.6  303.41  5832.5  306.69  6050.4  321.45
#Mann= 5 ,-1 , 0
    4342     .05       0  4379.9     .16       0  4484.6     .05       0
  4996.6     .03       0  5002.6     .05       0
Bank Sta=4689.3,5442.5
XS Rating Curve= 0 ,0
Exp/Cntr=0.3,0.1

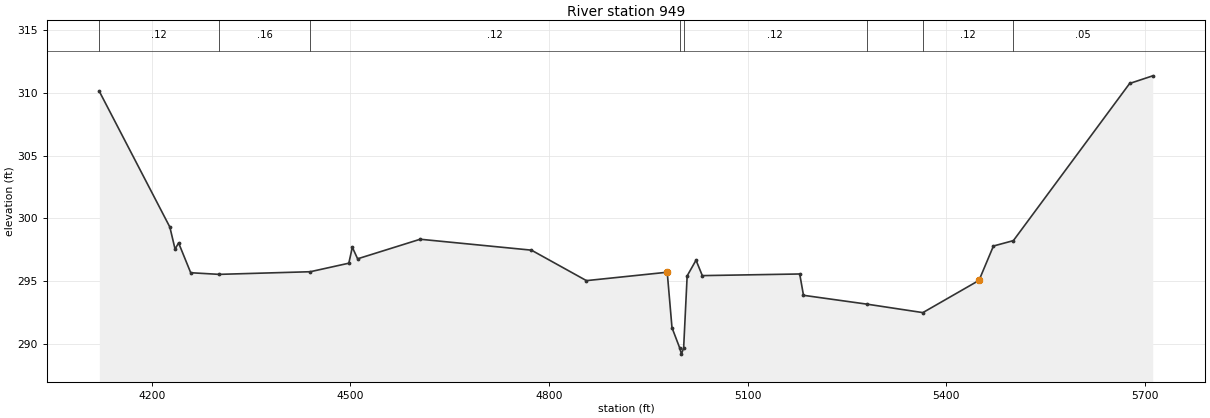
Type RM Length L Ch R = 1 ,949     ,0,0,0
BEGIN DESCRIPTION:
UNT 103 IN CACR 2.0
END DESCRIPTION:
XS GIS Cut Line= 3
      3693150.32     10722388.72       3692895.1     10723185.61
      3693262.28     10723844.44
#Sta/Elev= 30
  4120.8  310.13  4227.3  299.31  4235.2  297.55  4240.5  298.05  4258.8  295.67
  4301.6  295.54  4439.4  295.75  4497.6  296.43  4502.9   297.7  4510.9  296.78
  4605.4  298.34  4773.4  297.47  4856.5  295.04  4978.5  295.71  4985.7  291.29
  4997.3  289.68    5000  289.18  5003.3  289.68  5008.6  295.42    5022  296.67
  5031.5  295.44  5178.6  295.57  5184.3  293.87  5279.5  293.17  5364.6  292.49
  5449.4  295.06  5471.2   297.8  5501.3  298.23  5676.9  310.76  5711.8  311.37
#Mann= 8 ,-1 , 0
  4120.8     .12       0  4301.6     .16       0  4439.4     .12       0
  4997.3     .07       0  5003.3     .12       0  5279.5     .05       0
  5364.6     .12       0  5501.3     .05       0
Bank Sta=4978.5,5449.4
XS Rating Curve= 0 ,0
Exp/Cntr=0.3,0.1

Chan Stop Cuts=-1
Use User Specified Reach Order=0
Composite Channel Slope=5