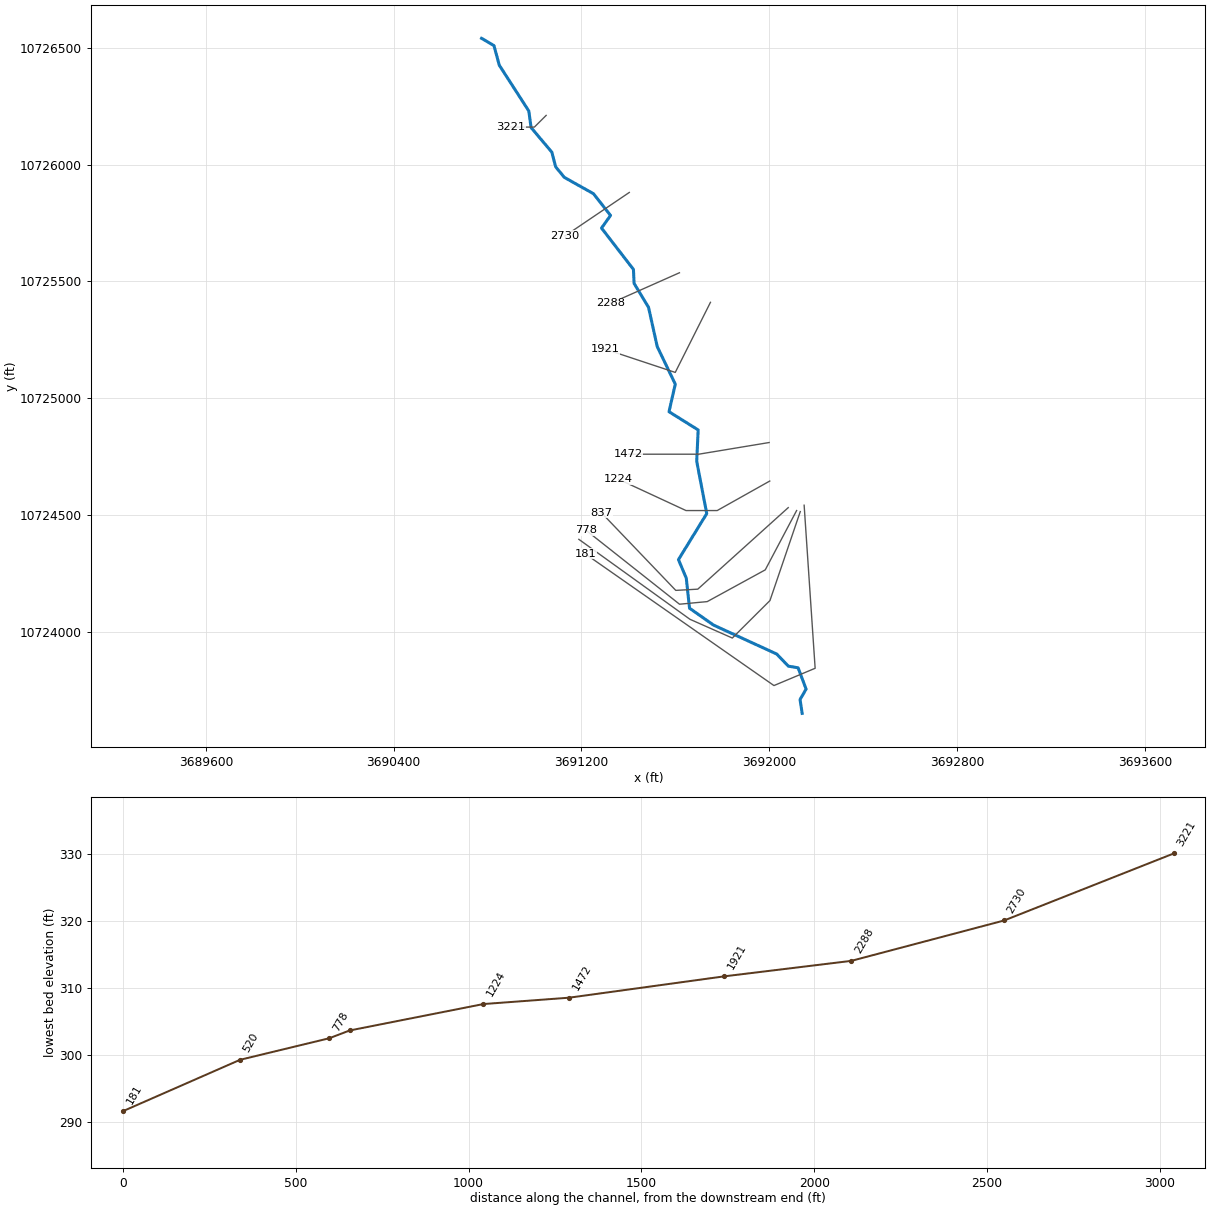
--- UNT 104 IN CACR.prj (project) ---

Proj Title=UNT 104 IN CACR Base Level Engineering
Current Plan=p01
Default Exp/Contr=0.3,0.1
English Units
Geom File=g01
Flow File=f01
Plan File=p01
Y Axis Title=Elevation
X Axis Title(PF)=Main Channel Distance
X Axis Title(XS)=Station
BEGIN DESCRIPTION:
UNT 104 IN CACR
END DESCRIPTION:
DSS Export Rating Curves= 0
DSS Export Rating Curve Sorted= 0
DSS Export Volume Flow Curves= 0
DXF OffsetX= 0
DXF OffsetY= 0
DXF ScaleX= 1
DXF ScaleY= 10

--- UNT 104 IN CACR.p01 (plan) ---

Plan Title=Multiple Run
Short Identifier=Multiple
Geom File=g01
Flow File=f01
Subcritical Flow
K Sum by GR= 0
Std Step Tol= 0.01
Critical Tol= 0.01
Num of Std Step Trials= 20
Max Error Tol= 0.3
Flow Tol Ratio= 0.001
Split Flow NTrial= 30
Split Flow Tol= 0.02
Split Flow Ratio= 0.02
Log Output Level= 0
Friction Slope Method= 1
Unsteady Friction Slope Method= 2
Unsteady Bridges Friction Slope Method= 1
Parabolic Critical Depth
Global Vel Dist=  1 , 1 , 1
Global Log Level= 0
CheckData=True
Encroach Param= -1, 0, 0, 0
BEGIN DESCRIPTION:
Multiple Run
END DESCRIPTION:

--- UNT 104 IN CACR.f01 (steady flow) ---

Flow Title=Multiple
Number of Profiles=7
Profile Names=10-year,25-year,50-year,1pct_min,100-year,1pct_plu,500-year
River Rch & RM= UNT 104 IN CACR,Reach-1,3221
     291     378     447     390     528     714     734
Boundary for River Rch & Prof#=UNT 104 IN CACR,Reach-1,1
Up Type=0
Dn Type=3
Dn Slope=0.005
Boundary for River Rch & Prof#=UNT 104 IN CACR,Reach-1,2
Up Type=0
Dn Type=3
Dn Slope=0.005
Boundary for River Rch & Prof#=UNT 104 IN CACR,Reach-1,3
Up Type=0
Dn Type=3
Dn Slope=0.005
Boundary for River Rch & Prof#=UNT 104 IN CACR,Reach-1,4
Up Type=0
Dn Type=3
Dn Slope=0.005
Boundary for River Rch & Prof#=UNT 104 IN CACR,Reach-1,5
Up Type=0
Dn Type=3
Dn Slope=0.005
Boundary for River Rch & Prof#=UNT 104 IN CACR,Reach-1,6
Up Type=0
Dn Type=3
Dn Slope=0.005
Boundary for River Rch & Prof#=UNT 104 IN CACR,Reach-1,7
Up Type=0
Dn Type=3
Dn Slope=0.005

--- UNT 104 IN CACR.g01 (geometry) ---

Geom Title=Existing Conditions
Program Version=4.10

River Reach=UNT 104 IN CACR ,Reach-1
Reach XY= 30
       3690774.5       10726540.      3690827.25       10726509.
        3690850.       10726425.      3690975.75       10726229.
       3690985.5       10726158.      3691073.75       10726053.
      3691090.25       10725990.        3691127.       10725945.
      3691251.25       10725875.        3691324.       10725782.
       3691285.5       10725728.       3691421.5       10725551.
      3691424.25       10725491.      3691485.75       10725389.
      3691522.75       10725221.      3691599.75       10725060.
        3691573.       10724942.      3691697.25       10724864.
        3691691.       10724730.      3691733.75       10724506.
      3691613.25       10724309.       3691646.5       10724230.
       3691660.5       10724101.       3691762.5       10724029.
      3692031.75       10723905.       3692081.5       10723853.
        3692123.       10723846.        3692157.       10723755.
      3692131.25       10723710.      3692140.25       10723651.

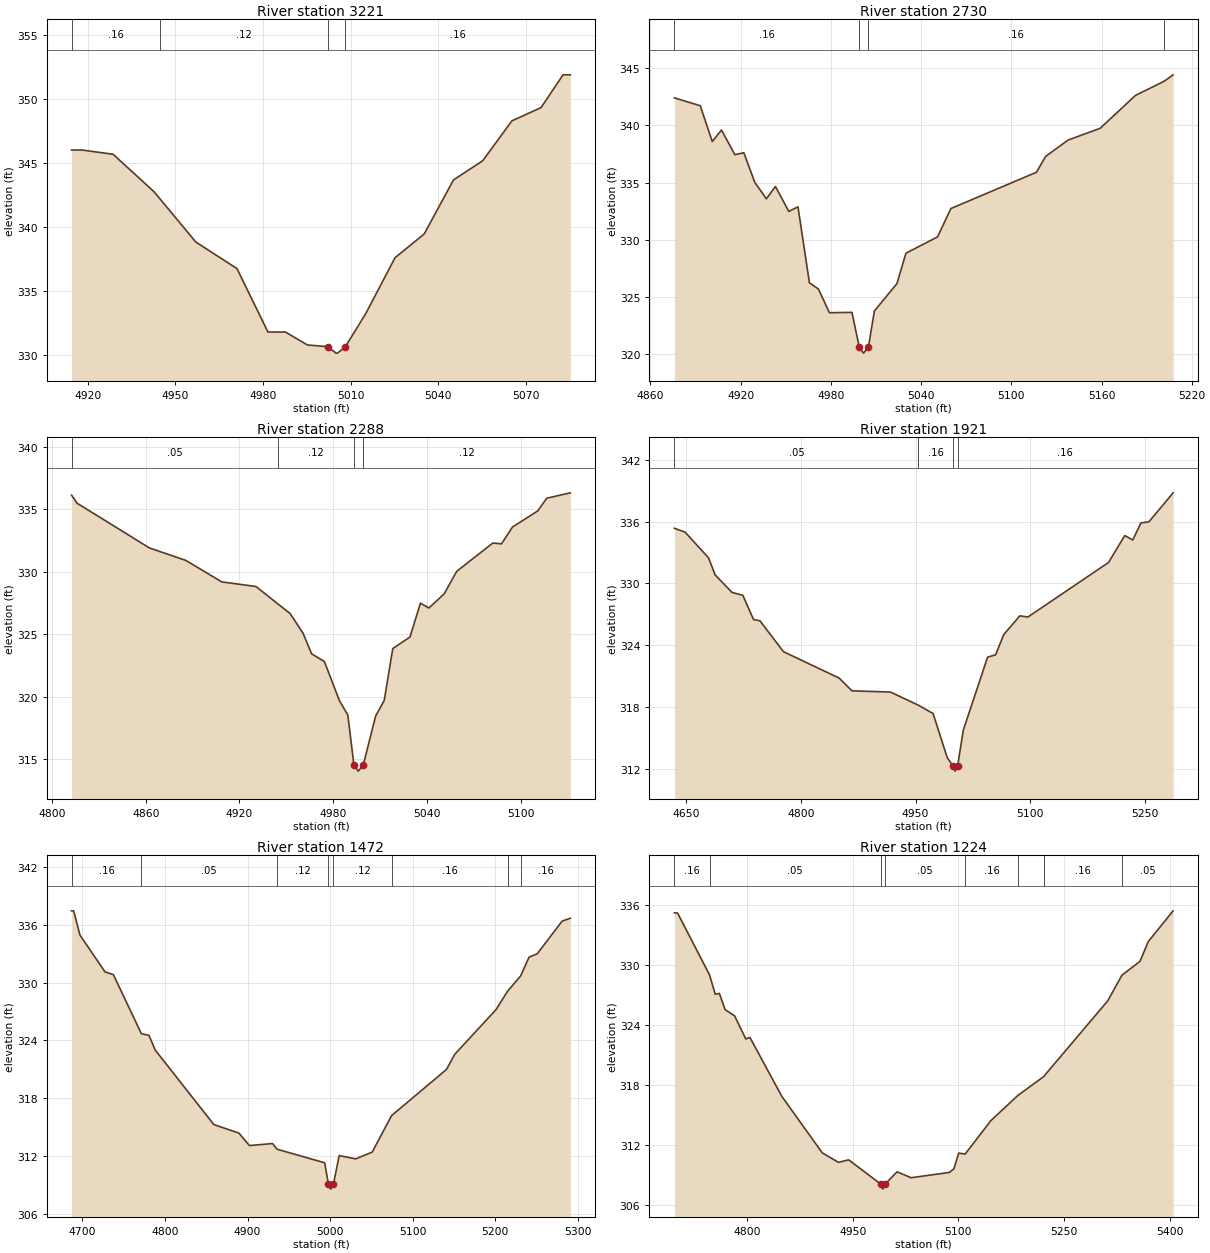
Type RM Length L Ch R = 1 ,3221    ,491,491,491
BEGIN DESCRIPTION:
UNT 104 IN CACR 7.0
END DESCRIPTION:
XS GIS Cut Line= 3
      3691049.63     10726210.21      3690999.61     10726160.19
      3690899.66     10726160.19
#Sta/Elev= 24
  4914.5     346  4918.1     346  4928.7  345.67  4942.8  342.72  4944.6  342.22
    4957  338.81  4971.1  336.73  4981.7  331.77  4985.2  331.77  4987.7  331.77
  4995.2  330.76  5002.2  330.62    5005  330.12  5005.5  330.12  5008.2  330.62
  5015.2  333.22  5025.2  337.58  5035.2  339.44  5045.2  343.66  5055.2  345.16
  5065.2  348.28  5075.2  349.32  5082.7  351.88  5085.2  351.88
#Mann= 4 ,-1 , 0
  4914.5     .16       0  4944.6     .12       0  5002.2     .07       0
  5008.2     .16       0
Bank Sta=5002.2,5008.2
XS Rating Curve= 0 ,0
Exp/Cntr=0.3,0.1

Type RM Length L Ch R = 1 ,2730    ,442,442,442
BEGIN DESCRIPTION:
UNT 104 IN CACR 6.0
END DESCRIPTION:
XS GIS Cut Line= 2
      3691403.87     10725880.47      3691129.48      10725694.1
#Sta/Elev= 30
  4875.9   342.4  4893.1  341.71  4901.1  338.58  4907.2  339.59  4916.1  337.44
  4922.1   337.6  4929.4  335.01  4937.1  333.58  4943.1  334.66    4952  332.48
  4958.1  332.88  4965.7  326.24  4971.7   325.7    4979  323.63    4994  323.66
  4998.9   320.6  5001.7   320.1  5004.9   320.6  5008.9  323.78  5023.9  326.17
  5029.9  328.83  5050.9  330.25  5059.8  332.73  5116.7   335.9  5122.8  337.28
  5137.7  338.71  5159.1  339.74  5182.5  342.61  5201.5  343.84  5207.6  344.41
#Mann= 4 ,-1 , 0
  4875.9     .16       0  4998.9     .07       0  5004.9     .16       0
  5201.5     .12       0
Bank Sta=4998.9,5004.9
XS Rating Curve= 0 ,0
Exp/Cntr=0.3,0.1

Type RM Length L Ch R = 1 ,2288    ,367,367,367
BEGIN DESCRIPTION:
UNT 104 IN CACR 5.0
END DESCRIPTION:
XS GIS Cut Line= 2
      3691617.46     10725536.75       3691325.8     10725406.54
#Sta/Elev= 30
  4812.5  336.13    4816  335.49  4862.4  331.91  4885.6  330.92  4908.7   329.2
  4930.6  328.83  4944.7  327.43  4952.5  326.66  4960.7   325.1  4966.2  323.45
  4974.4  322.83    4984  319.71  4989.4  318.55  4993.3  314.57  4996.1  314.07
  4999.3  314.57  5007.2  318.47  5012.7  319.72  5018.2  323.87  5029.2  324.79
  5035.9   327.5  5041.3  327.11  5051.1  328.24  5059.1  330.04  5082.3  332.31
  5087.8  332.24  5094.9  333.59    5111  334.87  5116.8  335.89  5131.9  336.32
#Mann= 4 ,-1 , 0
  4812.5     .05       0  4944.7     .12       0  4993.3     .07       0
  4999.3     .12       0
Bank Sta=4993.3,4999.3
XS Rating Curve= 0 ,0
Exp/Cntr=0.3,0.1

Type RM Length L Ch R = 1 ,1921    ,449,449,449
BEGIN DESCRIPTION:
UNT 104 IN CACR 4.0
END DESCRIPTION:
XS GIS Cut Line= 3
       3691749.6     10725410.17      3691599.61     10725110.19
      3691299.62     10725210.18
#Sta/Elev= 30
    4635  335.35    4649  334.97  4679.7  332.47  4688.1  330.83  4710.4  329.11
  4724.4  328.84  4738.4  326.48  4746.8  326.36  4777.5  323.36  4850.2   320.8
    4867  319.56  4917.3  319.44  4953.6  318.17    4973  317.35  4991.5  313.06
    4999  312.26  5001.8  311.76    5005  312.26  5012.5  315.75  5044.2  322.83
  5054.7  323.06  5065.3  325.02  5086.3  326.84  5096.9  326.73  5202.3  332.03
  5223.4  334.64  5233.9  334.21  5244.4  335.86    5255  335.98  5286.6  338.79
#Mann= 4 ,-1 , 0
    4635     .05       0  4953.6     .16       0    4999     .07       0
    5005     .16       0
Bank Sta=4999,5005
XS Rating Curve= 0 ,0
Exp/Cntr=0.3,0.1

Type RM Length L Ch R = 1 ,1472    ,248,248,248
BEGIN DESCRIPTION:
UNT 104 IN CACR 3.0
END DESCRIPTION:
XS GIS Cut Line= 3
      3691999.57     10724810.18      3691699.61     10724760.19
       3691399.6     10724760.19
#Sta/Elev= 30
  4686.9  337.45  4689.4  337.45    4697  334.94  4727.4  331.11  4737.5  330.83
  4771.4   324.7  4780.6  324.53  4788.2     323  4859.2  315.27  4889.6  314.38
  4902.3  313.09  4930.2   313.3  4935.9  312.71  4993.5   311.3    4998  309.07
  5000.7  308.57    5004  309.07    5011  312.05    5031  311.71    5051  312.41
  5074.5   316.2    5141  320.99    5151  322.56    5201   327.2    5215  329.11
  5230.7  330.68    5241  332.64    5251     333    5281  336.38    5291  336.68
#Mann= 8 ,-1 , 0
  4686.9     .16       0  4771.4     .05       0  4935.9     .12       0
    4998     .07       0    5004     .12       0  5074.5     .16       0
    5215     .12       0  5230.7     .16       0
Bank Sta=4998,5004
XS Rating Curve= 0 ,0
Exp/Cntr=0.3,0.1

Type RM Length L Ch R = 1 ,1224    ,387,387,387
BEGIN DESCRIPTION:
Mapping XS 2206e7e8
END DESCRIPTION:
XS GIS Cut Line= 4
      3692002.24     10724645.34      3691778.25     10724519.02
      3691645.44     10724519.02      3691357.72     10724653.12
#Sta/Elev= 30
  4697.2  335.27  4701.7  335.24    4747  329.06  4755.2  327.11    4761   327.2
  4769.1  325.58  4782.6  324.95  4798.5  322.64  4804.3   322.8  4849.5  316.91
  4906.9  311.25  4929.8   310.3  4944.4  310.55    4990  308.12  4992.7  307.62
    4996  308.12    5013  309.35    5033  308.76  5087.2  309.29  5093.6  309.65
  5100.4  311.22  5109.6  311.13  5146.2  314.48  5184.2  316.98  5220.8  318.87
  5311.8  326.45    5332  329.02  5357.5   330.4  5369.4  332.39  5404.6  335.46
#Mann= 8 ,-1 , 0
  4697.2     .16       0    4747     .05       0    4990     .07       0
    4996     .05       0  5109.6     .16       0  5184.2     .12       0
  5220.8     .16       0    5332     .05       0
Bank Sta=4990,4996
XS Rating Curve= 0 ,0
Exp/Cntr=0.3,0.1

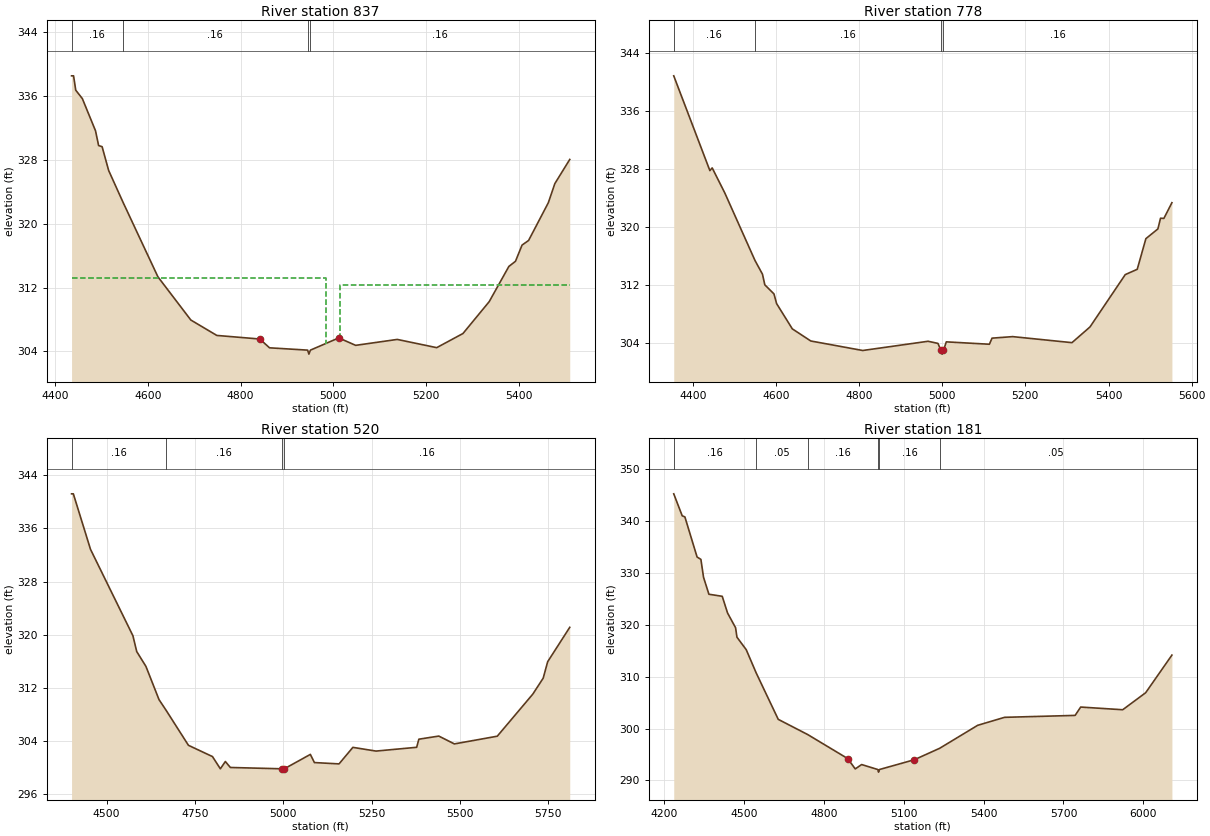
Type RM Length L Ch R = 1 ,837     ,59,59,59
BEGIN DESCRIPTION:
UNT 104 IN CACR 2.0
END DESCRIPTION:
XS GIS Cut Line= 4
      3692080.98     10724531.53      3691695.55     10724182.57
       3691601.8     10724177.36      3691284.38     10724510.39
#Sta/Elev= 30
  4435.7  338.51    4440  338.51  4444.7  336.71  4458.9  335.66  4487.3  331.63
    4494  329.78  4501.5  329.64  4515.7  326.65  4546.7  322.67  4621.8  313.35
  4692.8  307.94  4748.8  306.01  4841.5  305.56  4862.4  304.46  4944.6  304.17
  4947.3  303.67  4950.6  304.17  5011.7   305.7  5048.1  304.77  5137.8  305.51
  5222.8  304.48  5279.4  306.25    5336  310.24  5378.4  314.65  5392.6  315.29
  5406.8  317.32  5420.9   317.9  5463.4  322.62  5477.5  325.02  5509.6  328.04
#Mann= 4 ,-1 , 0
  4435.7     .16       0  4546.7     .16       0  4944.6     .07       0
  4950.6     .16       0
#XS Ineff= 2 , 0
         4983.64  313.17    5015          312.32
Permanent Ineff=
       F       F
Bank Sta=4841.5,5011.7
XS Rating Curve= 0 ,0
Exp/Cntr=0.3,0.1

Type RM Length L Ch R = 1 ,778     ,258,258,258
BEGIN DESCRIPTION:
Mapping XS 8c3caccd
END DESCRIPTION:
XS GIS Cut Line= 5
      3692116.64     10724519.07      3691983.01     10724265.18
      3691735.81     10724129.33      3691617.77      10724118.2
      3691217.85     10724435.91
#Sta/Elev= 30
  4354.2  340.83  4441.1  327.78  4446.7  328.15  4477.2  324.68  4549.6  315.41
  4567.6  313.52  4573.3  312.05  4595.3   310.8  4601.6  309.47  4639.4  305.99
  4683.8  304.32  4808.8  303.01  4965.9  304.28  4989.7  303.99    4997  303.01
  4999.8  302.51    5003  303.01  5009.8   304.2  5113.5  303.87  5119.8  304.71
  5169.5  304.92  5312.1  304.09  5355.4  306.25  5440.3  313.46  5469.1  314.19
  5489.9  318.41  5518.8  319.75  5525.1  321.22  5533.2   321.2  5552.5  323.36
#Mann= 4 ,-1 , 0
  4354.2     .16       0  4549.6     .16       0    4997     .03       0
    5003     .16       0
Bank Sta=4997,5003
XS Rating Curve= 0 ,0
Exp/Cntr=0.3,0.1

Type RM Length L Ch R = 1 ,520     ,339,339,339
BEGIN DESCRIPTION:
Mapping XS 2b1b86eb
END DESCRIPTION:
XS GIS Cut Line= 5
      3692132.24     10724514.66      3692003.05     10724133.79
      3691842.71     10723973.44      3691662.31     10724053.61
      3691188.93     10724395.87
#Sta/Elev= 30
  4400.7  341.21  4405.7  341.21  4454.3  332.85  4574.4  319.83  4585.2  317.45
  4611.3  315.21  4648.3  310.21  4668.3  308.61  4731.6  303.33  4799.7  301.63
    4822  299.79  4836.1  300.89  4850.3  299.99    4997  299.79  4999.8  299.29
    5003  299.79  5076.8  301.96  5088.2  300.73    5158  300.53  5197.2  303.02
  5262.6  302.46  5377.8  303.03    5384  304.25  5440.4  304.72  5484.6  303.54
    5606   304.7  5706.6  311.04    5736  313.44  5748.7  315.92  5811.2   321.1
#Mann= 4 ,-1 , 0
  4400.7     .16       0  4668.3     .16       0    4997     .03       0
    5003     .16       0
Bank Sta=4997,5003
XS Rating Curve= 0 ,0
Exp/Cntr=0.3,0.1

Type RM Length L Ch R = 1 ,181     ,0,0,0
BEGIN DESCRIPTION:
UNT 104 IN CACR 1.0
END DESCRIPTION:
XS GIS Cut Line= 4
      3692148.68     10724541.95      3692195.55     10723844.02
      3692020.07     10723770.04       3691216.4     10724333.59
#Sta/Elev= 30
    4236  345.24  4267.8  341.01  4277.9  340.79  4323.7  333.06    4338  332.61
    4348  329.14  4368.1  325.89  4418.2  325.49  4438.2  322.27  4468.3  319.44
  4473.5  317.61  4508.4   315.2  4545.5  310.75  4628.6  301.78  4738.9  298.86
  4889.2  294.23  4917.9  292.23  4941.9  293.07  5002.7  292.11  5005.4  291.61
  5008.7  292.11  5139.9     294  5234.9   296.2  5377.8  300.63  5478.9  302.17
  5743.9  302.54  5764.8  304.15  5922.6  303.63  6008.9  306.91  6107.5  314.16
#Mann= 6 ,-1 , 0
    4236     .16       0  4545.5     .05       0  4738.9     .16       0
  5002.7     .07       0  5008.7     .16       0  5234.9     .05       0
Bank Sta=4889.2,5139.9
XS Rating Curve= 0 ,0
Exp/Cntr=0.3,0.1

Chan Stop Cuts=-1
Use User Specified Reach Order=0
Composite Channel Slope=5