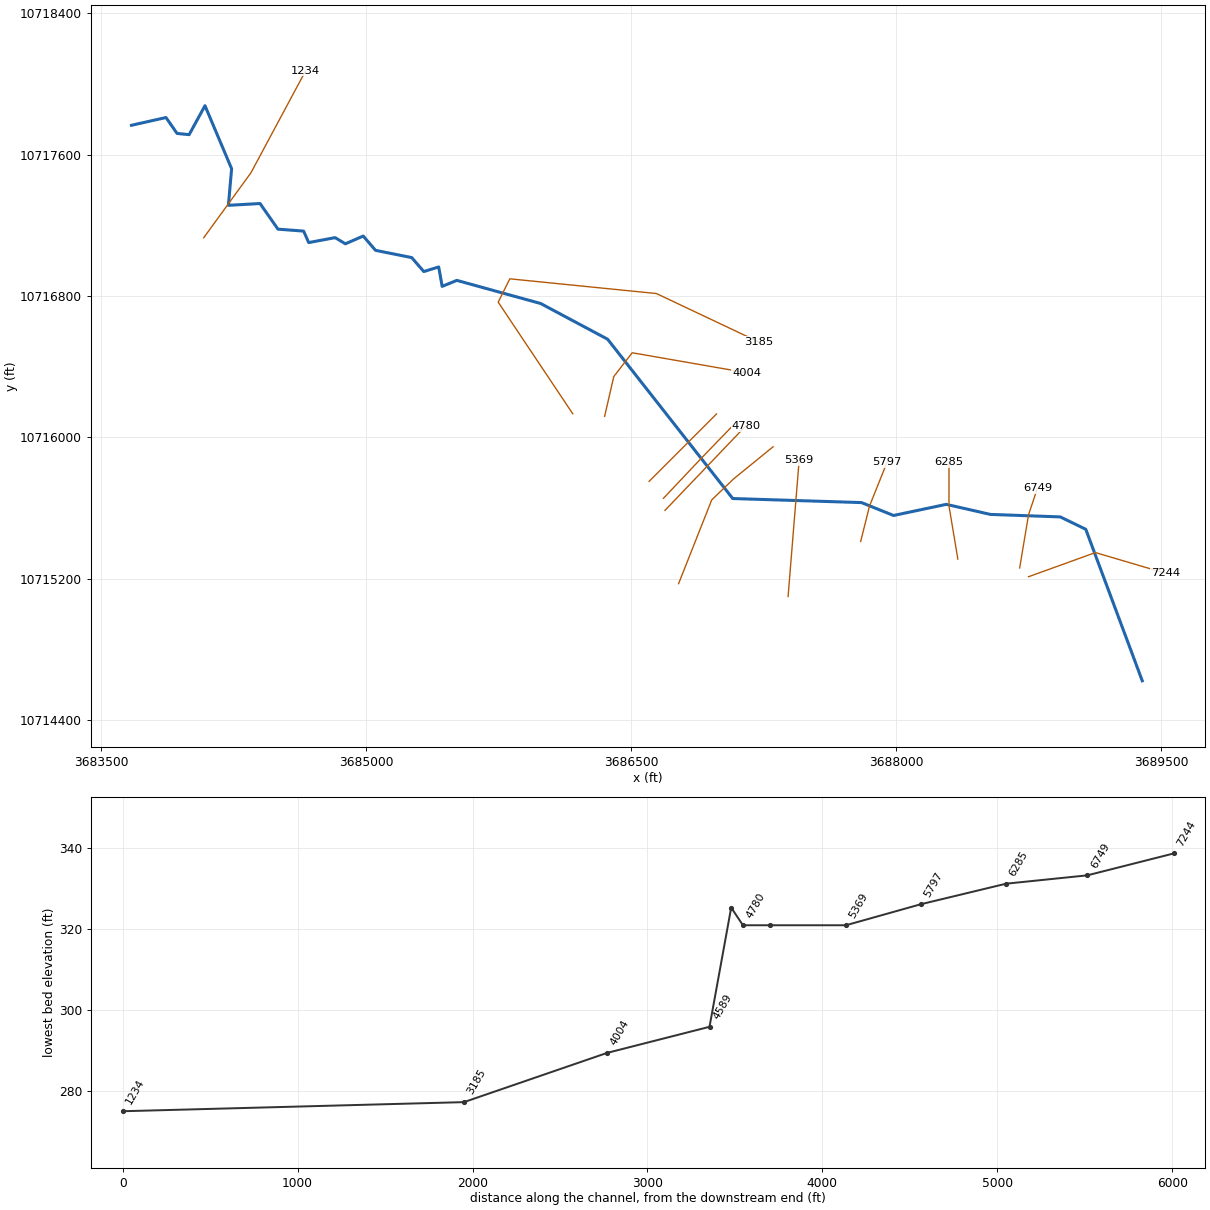
--- UNT 105 IN CACR.prj (project) ---

Proj Title=UNT 105 IN CACR Base Level Engineering
Current Plan=p01
Default Exp/Contr=0.3,0.1
English Units
Geom File=g01
Flow File=f01
Plan File=p01
BEGIN DESCRIPTION:
UNT 105 IN CACR
END DESCRIPTION:

--- UNT 105 IN CACR.p01 (plan) ---

Plan Title=Multiple Run
Short Identifier=Multiple
Geom File=g01
Flow File=f01
Subcritical Flow
K Sum by GR= 0
Std Step Tol= 0.01
Critical Tol= 0.01
Num of Std Step Trials= 20
Max Error Tol= 0.3
Flow Tol Ratio= 0.001
Split Flow NTrial= 30
Split Flow Tol= 0.02
Split Flow Ratio= 0.02
Log Output Level= 0
Friction Slope Method= 1
Unsteady Friction Slope Method= 2
Unsteady Bridges Friction Slope Method= 1
Parabolic Critical Depth
Global Vel Dist=  1 , 1 , 1
Global Log Level= 0
CheckData=True
Encroach Param= -1, 0, 0, 0
BEGIN DESCRIPTION:
Multiple Run
END DESCRIPTION:

--- UNT 105 IN CACR.f01 (steady flow) ---

Flow Title=Multiple
Number of Profiles=7
Profile Names=10-year,25-year,50-year,1pct_min,100-year,1pct_plu,500-year
River Rch & RM= UNT 105 IN CACR,Reach-1,7244
     497     669     810     721     975    1319    1419
Boundary for River Rch & Prof#=UNT 105 IN CACR,Reach-1,1
Up Type=0
Dn Type=3
Dn Slope=0.005
Boundary for River Rch & Prof#=UNT 105 IN CACR,Reach-1,2
Up Type=0
Dn Type=3
Dn Slope=0.005
Boundary for River Rch & Prof#=UNT 105 IN CACR,Reach-1,3
Up Type=0
Dn Type=3
Dn Slope=0.005
Boundary for River Rch & Prof#=UNT 105 IN CACR,Reach-1,4
Up Type=0
Dn Type=3
Dn Slope=0.005
Boundary for River Rch & Prof#=UNT 105 IN CACR,Reach-1,5
Up Type=0
Dn Type=3
Dn Slope=0.005
Boundary for River Rch & Prof#=UNT 105 IN CACR,Reach-1,6
Up Type=0
Dn Type=3
Dn Slope=0.005
Boundary for River Rch & Prof#=UNT 105 IN CACR,Reach-1,7
Up Type=0
Dn Type=3
Dn Slope=0.005

--- UNT 105 IN CACR.g01 (geometry) ---

Geom Title=Existing Conditions

River Reach=UNT 105 IN CACR,Reach-1
Reach XY= 30
      3689393.59     10714621.11      3689073.75     10715479.00
      3688929.25     10715549.00      3688534.25     10715563.00
      3688284.25     10715620.00      3687985.75     10715557.00
      3687804.50     10715630.00      3687075.25     10715653.00
      3686367.00     10716555.00      3685988.25     10716757.00
      3685513.50     10716888.00      3685430.50     10716854.00
      3685411.00     10716964.00      3685326.50     10716938.00
      3685258.25     10717017.00      3685053.50     10717058.00
      3684983.75     10717139.00      3684882.75     10717095.00
      3684824.50     10717130.00      3684675.25     10717102.00
      3684646.25     10717167.00      3684501.00     10717178.00
      3684399.75     10717323.00      3684220.50     10717313.00
      3684238.75     10717520.00      3684088.00     10717877.00
      3683998.25     10717713.00      3683929.75     10717720.00
      3683867.25     10717810.00      3683671.75     10717766.00

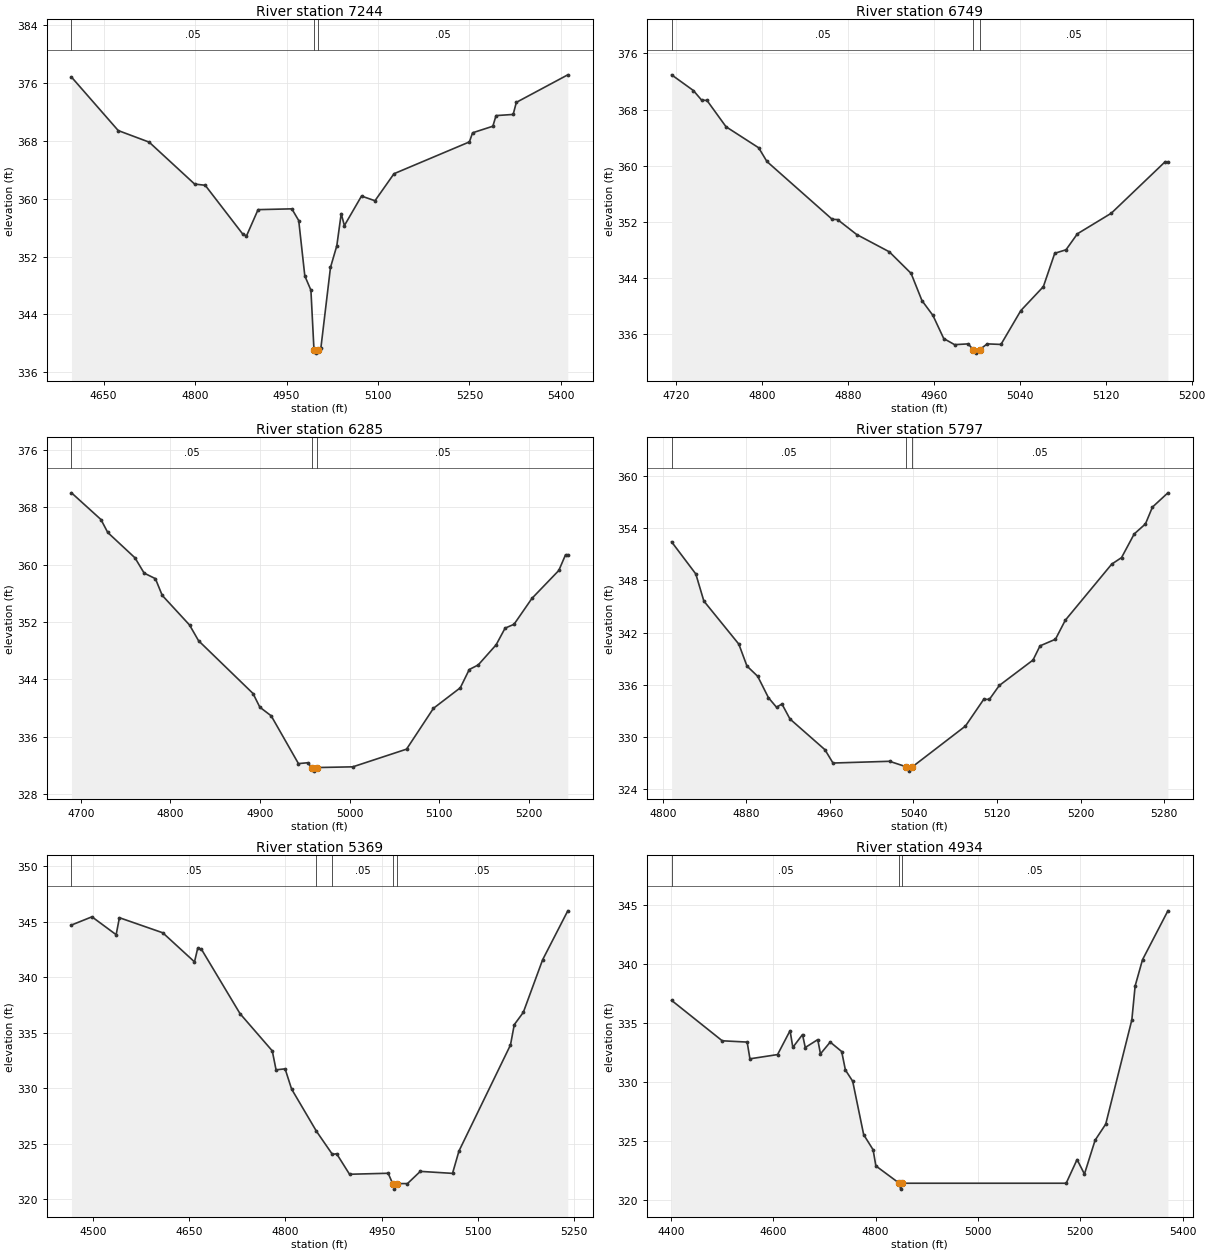
Type RM Length L Ch R = 1,7244,495,495,495
BEGIN DESCRIPTION:
UNT 105 IN CACR 8.0
END DESCRIPTION:
XS GIS Cut Line= 3
      3688749.57     10715210.18      3689128.43     10715346.97
      3689523.03     10715230.58
#Sta/Elev= 30
  4597.2  376.84  4673.9  369.44  4724.6  367.84  4799.2  362.04  4816.6  361.87
  4878.0  355.14  4884.3  354.86  4903.3  358.50  4958.7  358.61  4970.0  356.99
  4980.0  349.33  4990.0  347.36  4995.0  339.15  4997.7  338.65  5001.0  339.15
  5006.4  339.39  5022.1  350.50  5032.5  353.51  5039.7  357.95  5044.9  356.29
  5073.0  360.38  5095.1  359.73  5126.3  363.47  5250.0  367.87  5255.2  369.13
  5288.5  370.04  5293.7  371.51  5321.8  371.67  5327.0  373.34  5411.4  377.15
#Mann=3,-1,0
  4597.2    0.05       0  4995.0    0.03       0  5001.0    0.05       0
Bank Sta=4995,5001
Exp/Cntr=0.3,0.1

Type RM Length L Ch R = 1,6749,464,464,464
BEGIN DESCRIPTION:
UNT 105 IN CACR 7.0
END DESCRIPTION:
XS GIS Cut Line= 3
      3688699.60     10715260.14      3688749.61     10715560.19
      3688799.61     10715710.19
#Sta/Elev= 30
  4715.5  372.95  4735.8  370.71  4743.4  369.35  4748.5  369.29  4766.2  365.54
  4796.6  362.54  4804.3  360.58  4865.1  352.33  4870.1  352.29  4887.9  350.16
  4918.3  347.69  4938.6  344.61  4948.7  340.73  4958.9  338.62  4969.0  335.31
  4979.1  334.44  4991.8  334.55  4996.4  333.73  4999.2  333.23  5002.4  333.73
  5009.5  334.55  5022.3  334.47  5040.8  339.30  5061.8  342.72  5072.4  347.48
  5082.9  347.98  5093.5  350.26  5125.1  353.20  5175.2  360.54  5177.8  360.54
#Mann=3,-1,0
  4715.5    0.05       0  4996.4    0.03       0  5002.4    0.05       0
Bank Sta=4996.4,5002.4
Exp/Cntr=0.3,0.1

Type RM Length L Ch R = 1,6285,488,488,488
BEGIN DESCRIPTION:
UNT 105 IN CACR 6.0
END DESCRIPTION:
XS GIS Cut Line= 3
      3688349.60     10715310.22      3688299.61     10715610.19
      3688299.61     10715860.19
#Sta/Elev= 30
  4689.5  370.04  4722.4  366.31  4730.0  364.50  4760.4  360.96  4770.6  358.83
  4783.2  358.05  4790.8  355.72  4821.3  351.58  4831.4  349.38  4892.2  342.01
  4899.8  340.10  4912.5  338.89  4942.9  332.22  4953.1  332.34  4957.7  331.67
  4960.4  331.17  4963.7  331.67  5003.6  331.77  5063.6  334.24  5093.6  339.94
  5123.6  342.81  5133.6  345.36  5143.6  346.00  5163.6  348.81  5173.6  351.14
  5183.6  351.68  5203.6  355.30  5233.6  359.20  5241.1  361.39  5243.6  361.39
#Mann=3,-1,0
  4689.5    0.05       0  4957.7    0.03       0  4963.7    0.05       0
Bank Sta=4957.7,4963.7
Exp/Cntr=0.3,0.1

Type RM Length L Ch R = 1,5797,428,428,428
BEGIN DESCRIPTION:
UNT 105 IN CACR 5.0
END DESCRIPTION:
XS GIS Cut Line= 3
      3687799.61     10715410.19      3687849.61     10715610.19
      3687949.60     10715860.18
#Sta/Elev= 30
  4808.3  352.43  4831.5  348.74  4839.2  345.63  4872.7  340.68  4880.5  338.16
  4890.8  336.98  4901.1  334.52  4908.8  333.43  4914.0  333.80  4921.7  332.08
  4955.2  328.55  4962.9  327.02  5017.1  327.22  5033.0  326.59  5035.7  326.09
  5039.0  326.59  5089.8  331.27  5107.3  334.34  5112.7  334.33  5122.2  335.93
  5154.5  338.85  5161.2  340.48  5176.0  341.24  5185.4  343.42  5229.9  349.87
  5239.3  350.62  5251.4  353.33  5262.2  354.49  5268.9  356.42  5283.7  358.06
#Mann=3,-1,0
  4808.3    0.05       0  5033.0    0.03       0  5039.0    0.05       0
Bank Sta=5033,5039
Exp/Cntr=0.3,0.1

Type RM Length L Ch R = 1,5369,435,435,435
BEGIN DESCRIPTION:
UNT 105 IN CACR 4.0
END DESCRIPTION:
XS GIS Cut Line= 2
      3687388.77     10715098.34      3687451.27     10715869.22
#Sta/Elev= 30
  4466.6  344.70  4498.5  345.44  4536.2  343.83  4541.3  345.36  4608.9  344.00
  4658.3  341.38  4663.3  342.61  4669.1  342.52  4729.3  336.71  4779.5  333.36
  4785.4  331.65  4799.5  331.74  4809.6  329.92  4848.3  326.12  4873.2  324.03
  4879.8  324.09  4899.9  322.24  4960.1  322.33  4967.1  321.40  4969.8  320.90
  4973.1  321.40  4990.2  321.40  5010.2  322.50  5060.4  322.32  5070.4  324.33
  5150.7  333.89  5156.6  335.72  5170.7  336.83  5200.8  341.57  5240.0  345.98
#Mann=5,-1,0
  4466.6    0.05       0  4848.3    0.16       0  4873.2    0.05       0
  4967.1    0.03       0  4973.1    0.05       0
Bank Sta=4967.1,4973.1
Exp/Cntr=0.3,0.1

Type RM Length L Ch R = 1,4934,154,154,154
BEGIN DESCRIPTION:
UNT 105 IN CACR 3.0
END DESCRIPTION:
XS GIS Cut Line= 4
      3686768.99     10715171.29      3686956.48     10715645.23
      3687081.48     10715765.02      3687303.74     10715945.94
#Sta/Elev= 30
  4401.6  336.92  4500.5  333.49  4549.2  333.38  4554.6  331.96  4608.6  332.32
  4633.0  334.35  4638.4  332.93  4657.3  334.02  4662.7  332.92  4687.1  333.59
  4692.4  332.38  4711.4  333.38  4733.8  332.58  4741.1  331.01  4755.3  330.06
  4776.8  325.52  4795.2  324.24  4800.6  322.87  4846.3  321.40  4849.0  320.90
  4852.3  321.40  5172.3  321.40  5193.6  323.41  5208.0  322.18  5228.8  325.05
  5249.6  326.42  5300.6  335.27  5307.0  338.14  5321.4  340.37  5371.0  344.52
#Mann=3,-1,0
  4401.6    0.05       0  4846.3   0.033       0  4852.3    0.05       0
Bank Sta=4846.3,4852.3
Exp/Cntr=0.3,0.1

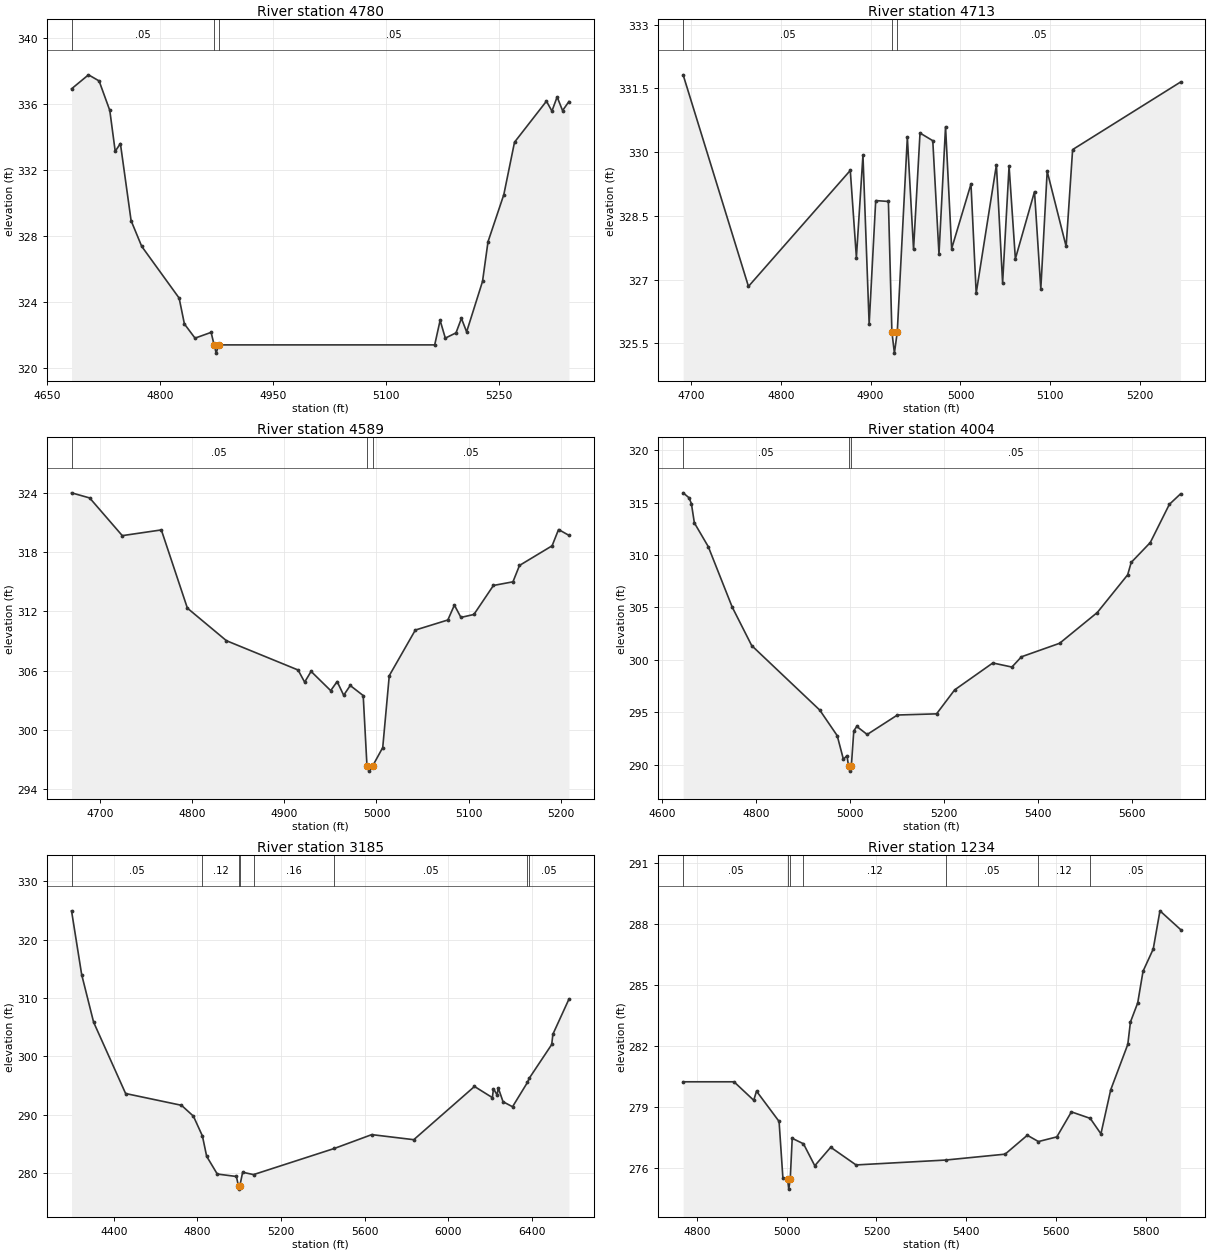
Type RM Length L Ch R = 1,4780,67,67,67
BEGIN DESCRIPTION:
Mapping XS c2d2f245
END DESCRIPTION:
XS GIS Cut Line= 2
      3686691.94     10715585.94      3687148.52     10716063.36
#Sta/Elev= 30
  4682.3  336.94  4704.8  337.79  4718.9  337.42  4733.1  335.63  4740.3  333.15
  4747.2  333.62  4761.4  328.94  4775.5  327.38  4825.2  324.24  4832.2  322.67
  4846.3  321.81  4867.7  322.16  4871.6  321.40  4874.4  320.90  4877.6  321.40
  5164.6  321.40  5171.8  322.89  5178.7  321.81  5192.9  322.13  5200.1  323.01
  5207.0  322.19  5228.1  325.25  5235.4  327.66  5256.4  330.52  5270.6  333.70
  5313.0  336.19  5320.3  335.59  5327.2  336.45  5334.4  335.62  5342.9  336.17
#Mann=3,-1,0
  4682.3    0.05       0  4871.6    0.03       0  4877.6    0.05       0
Bank Sta=4871.6,4877.6
Exp/Cntr=0.3,0.1

Type RM Length L Ch R = 1,4713,124,124,124
BEGIN DESCRIPTION:
Mapping XS 3dbfcac1
END DESCRIPTION:
XS GIS Cut Line= 3
      3686683.00     10715654.12      3686909.54     10715893.68
      3687065.17     10716054.50
#Sta/Elev= 30
  4691.4  331.82  4764.1  326.84  4877.4  329.57  4884.2  327.52  4891.5  329.93
  4898.4  325.95  4905.7  328.86  4919.8  328.84  4923.7  325.77  4926.5  325.27
  4929.7  325.77  4940.9  330.35  4947.8  327.71  4955.0  330.45  4969.2  330.27
  4976.1  327.60  4983.4  330.60  4990.2  327.73  5011.7  329.25  5017.5  326.68
  5040.0  329.70  5046.9  326.92  5054.1  329.67  5061.1  327.49  5082.4  329.07
  5089.4  326.78  5096.5  329.55  5117.6  327.78  5124.8  330.06  5244.9  331.65
#Mann=3,-1,0
  4691.4    0.05       0  4923.7    0.03       0  4929.7    0.05       0
Bank Sta=4923.7,4929.7
Exp/Cntr=0.3,0.1

Type RM Length L Ch R = 1,4589,585,585,585
BEGIN DESCRIPTION:
Mapping XS 174dca5b
END DESCRIPTION:
XS GIS Cut Line= 2
      3686601.88     10715750.01      3686983.79     10716131.92
#Sta/Elev= 30
  4668.9  324.02  4688.6  323.50  4724.0  319.68  4766.4  320.26  4794.7  312.33
  4837.1  309.03  4914.9  306.06  4922.0  304.83  4929.0  305.92  4950.3  303.97
  4957.3  304.89  4964.4  303.50  4971.5  304.49  4985.6  303.47  4989.7  296.31
  4992.4  295.81  4995.7  296.31  5006.8  298.20  5013.9  305.49  5042.2  310.11
  5077.5  311.13  5084.6  312.64  5091.7  311.39  5105.8  311.69  5127.0  314.63
  5148.2  315.00  5155.3  316.66  5190.7  318.65  5197.7  320.30  5209.0  319.71
#Mann=3,-1,0
  4668.9    0.05       0  4989.7    0.03       0  4995.7    0.05       0
Bank Sta=4989.7,4995.7
Exp/Cntr=0.3,0.1

Type RM Length L Ch R = 1,4004,819,819,819
BEGIN DESCRIPTION:
UNT 105 IN CACR 2.0
END DESCRIPTION:
XS GIS Cut Line= 4
      3686350.11     10716118.02      3686402.20     10716343.74
      3686506.37     10716478.28      3687153.09     10716365.43
#Sta/Elev= 30
  4644.6  315.95  4657.1  315.48  4662.2  314.92  4668.5  313.08  4698.1  310.81
  4748.9  305.05  4790.5  301.36  4935.3  295.20  4972.4  292.76  4985.6  290.50
  4993.2  290.85  4996.5  289.87  4999.3  289.37  5002.5  289.87  5007.7  293.21
  5014.0  293.64  5036.2  292.87  5100.5  294.73  5183.8  294.84  5222.3  297.13
  5303.5  299.70  5344.1  299.31  5364.4  300.29  5445.6  301.58  5525.8  304.52
  5590.4  308.12  5597.9  309.30  5638.5  311.20  5679.1  314.85  5702.9  315.85
#Mann=3,-1,0
  4644.6    0.05       0  4996.5    0.03       0  5002.5    0.05       0
Bank Sta=4996.5,5002.5
Exp/Cntr=0.3,0.1

Type RM Length L Ch R = 1,3185,1951,1951,1951
BEGIN DESCRIPTION:
Mapping XS d3d5bcfb
END DESCRIPTION:
XS GIS Cut Line= 5
      3686170.04     10716132.51      3685747.58     10716764.86
      3685813.55     10716896.80      3686643.30     10716813.49
      3687220.38     10716540.50
#Sta/Elev= 30
  4198.0  324.94  4246.5  314.00  4303.6  305.84  4456.8  293.60  4724.1  291.58
  4781.1  289.72  4824.3  286.32  4844.6  282.83  4895.3  279.79  4986.8  279.37
  4997.1  277.70  4999.8  277.20  5003.1  277.70  5016.8  280.10  5068.8  279.69
  5455.8  284.18  5634.7  286.55  5835.7  285.68  6126.2  294.81  6211.7  292.90
  6217.2  294.42  6234.5  293.35  6240.0  294.57  6262.8  292.20  6308.3  291.33
  6379.9  295.52  6387.9  296.20  6495.8  302.01  6501.4  303.77  6578.3  309.80
#Mann=8,-1,0
  4198.0    0.05       0  4824.3    0.12       0  4997.1    0.07       0
  5003.1    0.12       0  5068.8    0.16       0  5455.8    0.05       0
  6379.9    0.16       0  6387.9    0.05       0
Bank Sta=4997.1,5003.1
Exp/Cntr=0.3,0.1

Type RM Length L Ch R = 1,1234,0,0,0
BEGIN DESCRIPTION:
UNT 105 IN CACR 1.0
END DESCRIPTION:
XS GIS Cut Line= 3
      3684080.90     10717129.42      3684348.28     10717497.49
      3684657.28     10718073.85
#Sta/Elev= 30
  4769.1  280.23  4882.5  280.23  4926.5  279.32  4932.7  279.77  4983.0  278.28
  4991.5  275.50  5001.9  275.45  5004.6  274.95  5007.9  275.45  5012.3  277.45
  5037.4  277.18  5062.6  276.10  5098.1  277.01  5154.6  276.14  5354.1  276.38
  5486.9  276.67  5536.4  277.60  5561.2  277.29  5602.2  277.52  5634.7  278.75
  5676.7  278.43  5700.5  277.67  5722.4  279.84  5760.4  282.07  5766.3  283.17
  5782.5  284.11  5794.4  285.67  5817.1  286.76  5832.1  288.64  5878.0  287.72
#Mann=7,-1,0
  4769.1    0.05       0  5001.9    0.03       0  5007.9    0.05       0
  5037.4    0.12       0  5354.1    0.05       0  5561.2    0.12       0
  5676.7    0.05       0
Bank Sta=5001.9,5007.9
Exp/Cntr=0.3,0.1

Chan Stop Cuts=-1