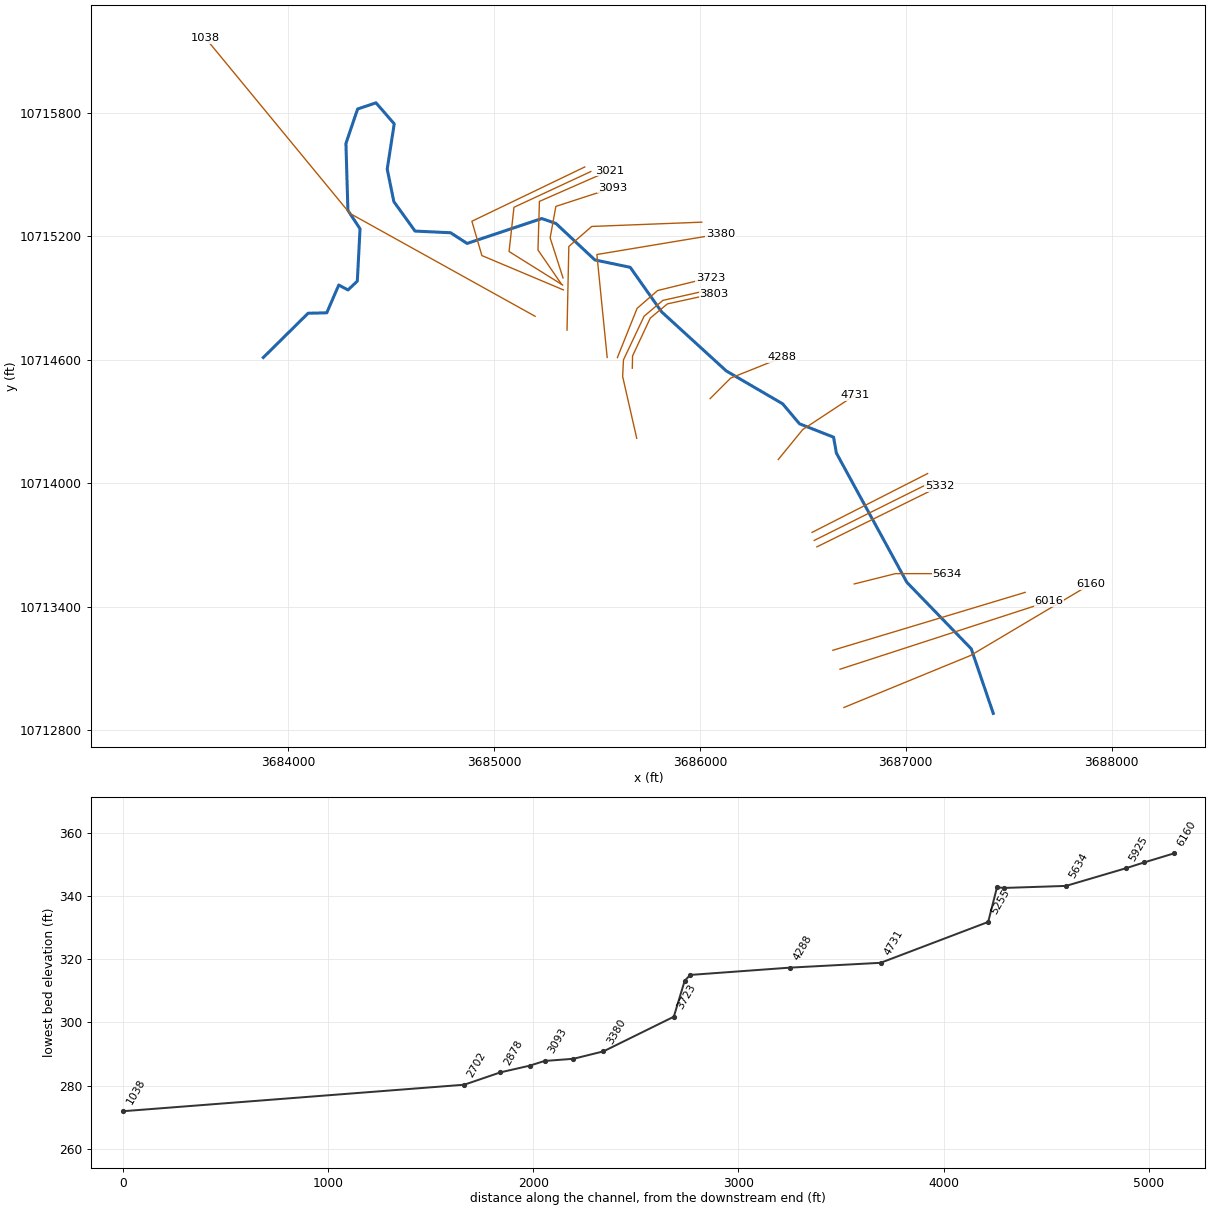
--- UNT 106 IN CACR.prj (project) ---

Proj Title=UNT 106 IN CACR Base Level Engineering
Current Plan=p01
Default Exp/Contr=0.3,0.1
English Units
Geom File=g01
Flow File=f01
Plan File=p01
Y Axis Title=Elevation
X Axis Title(PF)=Main Channel Distance
X Axis Title(XS)=Station
BEGIN DESCRIPTION:
UNT 106 IN CACR
END DESCRIPTION:
DSS Export Rating Curves= 0
DSS Export Rating Curve Sorted= 0
DSS Export Volume Flow Curves= 0
DXF OffsetX= 0
DXF OffsetY= 0
DXF ScaleX= 1
DXF ScaleY= 10

--- UNT 106 IN CACR.p01 (plan) ---

Plan Title=Multiple Run
Short Identifier=Multiple
Geom File=g01
Flow File=f01
Subcritical Flow
K Sum by GR= 0
Std Step Tol= 0.01
Critical Tol= 0.01
Num of Std Step Trials= 20
Max Error Tol= 0.3
Flow Tol Ratio= 0.001
Split Flow NTrial= 30
Split Flow Tol= 0.02
Split Flow Ratio= 0.02
Log Output Level= 0
Friction Slope Method= 1
Unsteady Friction Slope Method= 2
Unsteady Bridges Friction Slope Method= 1
Parabolic Critical Depth
Global Vel Dist=  1 , 1 , 1
Global Log Level= 0
CheckData=True
Encroach Param= -1, 0, 0, 0
BEGIN DESCRIPTION:
Multiple Run
END DESCRIPTION:

--- UNT 106 IN CACR.f01 (steady flow) ---

Flow Title=Multiple
Number of Profiles=7
Profile Names=10-year,25-year,50-year,1pct_min,100-year,1pct_plu,500-year
River Rch & RM= UNT 106 IN CACR,Reach-1,6160
     247     319     376     327     442     598     612
Boundary for River Rch & Prof#=UNT 106 IN CACR,Reach-1,1
Up Type=0
Dn Type=3
Dn Slope=0.005
Boundary for River Rch & Prof#=UNT 106 IN CACR,Reach-1,2
Up Type=0
Dn Type=3
Dn Slope=0.005
Boundary for River Rch & Prof#=UNT 106 IN CACR,Reach-1,3
Up Type=0
Dn Type=3
Dn Slope=0.005
Boundary for River Rch & Prof#=UNT 106 IN CACR,Reach-1,4
Up Type=0
Dn Type=3
Dn Slope=0.005
Boundary for River Rch & Prof#=UNT 106 IN CACR,Reach-1,5
Up Type=0
Dn Type=3
Dn Slope=0.005
Boundary for River Rch & Prof#=UNT 106 IN CACR,Reach-1,6
Up Type=0
Dn Type=3
Dn Slope=0.005
Boundary for River Rch & Prof#=UNT 106 IN CACR,Reach-1,7
Up Type=0
Dn Type=3
Dn Slope=0.005

--- UNT 106 IN CACR.g01 (geometry) ---

Geom Title=Existing Conditions
Program Version=4.10

River Reach=UNT 106 IN CACR ,Reach-1
Reach XY= 30
      3687424.84     10712881.52      3687317.97     10713195.14
      3687005.25       10713518.      3686662.75       10714146.
      3686649.25       10714223.      3686483.75       10714288.
        3686402.       10714385.      3686127.75       10714545.
      3685813.75       10714832.       3685661.5       10715048.
      3685489.75       10715084.      3685300.75       10715261.
      3685231.75       10715285.      3684869.25       10715164.
        3684789.       10715216.       3684616.5       10715224.
       3684513.5       10715367.      3684481.25       10715525.
      3684515.25       10715745.      3684426.75       10715847.
       3684337.5       10715817.      3684280.75       10715650.
      3684290.25       10715325.      3684349.25       10715235.
        3684336.       10714981.      3684290.75       10714938.
        3684246.       10714962.       3684187.5       10714827.
        3684097.       10714825.       3683879.5       10714610.

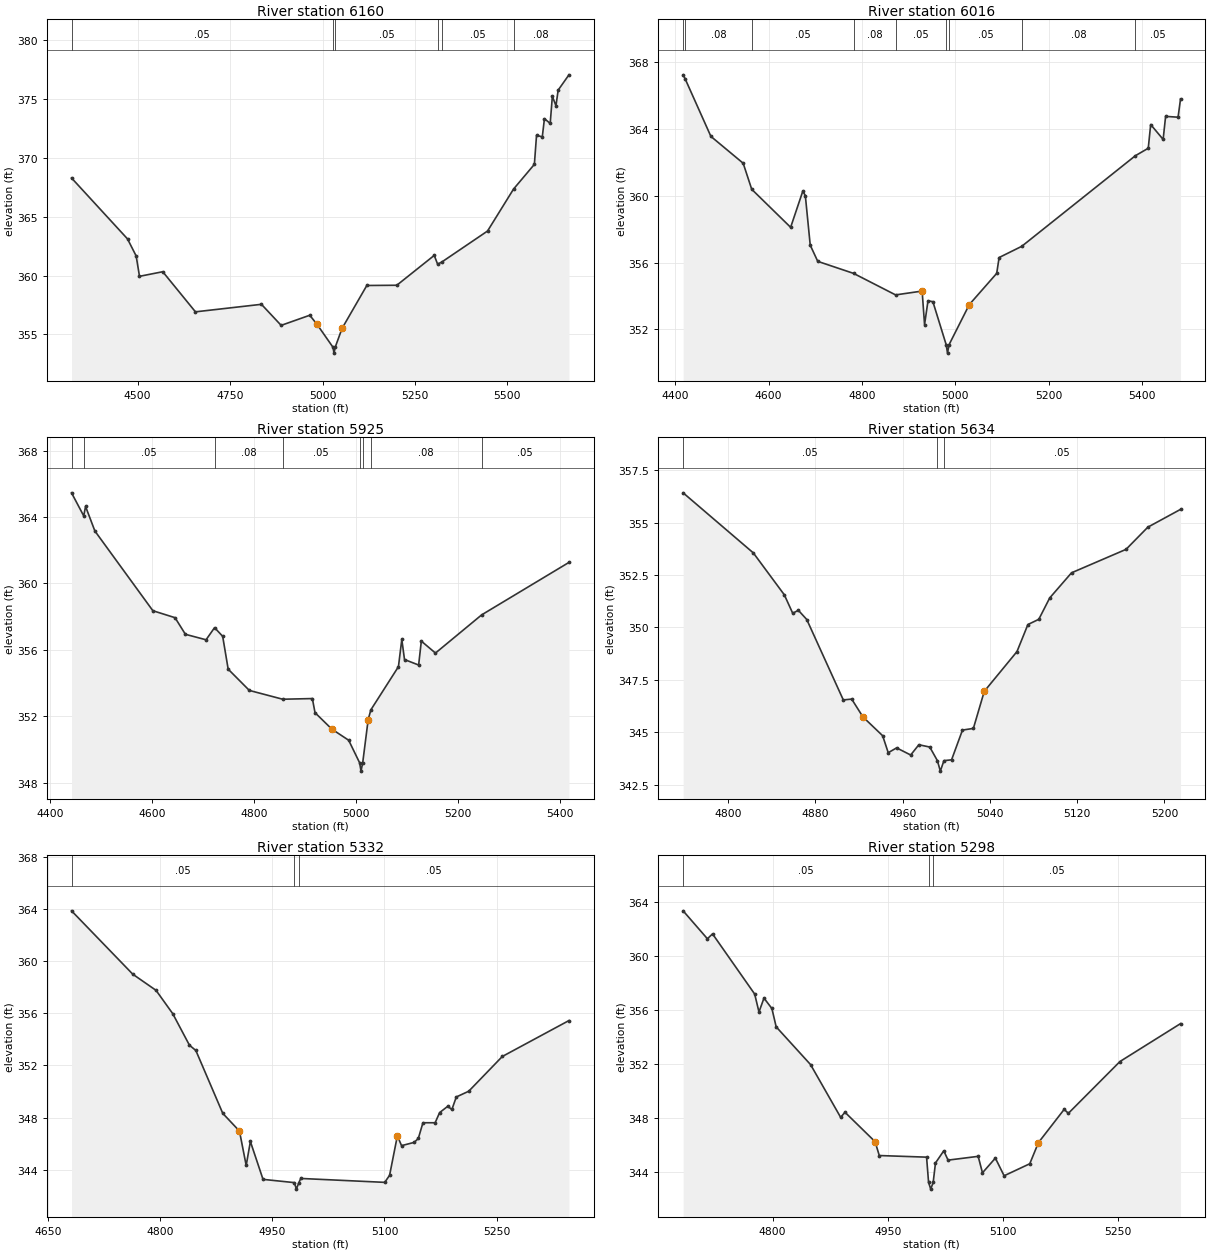
Type RM Length L Ch R = 1 ,6160    ,144,144,144
BEGIN DESCRIPTION:
UNT 106 IN CACR 10.0
END DESCRIPTION:
XS GIS Cut Line= 3
      3686699.58     10712910.18      3687313.94     10713162.29
      3687899.63      10713510.2
#Sta/Elev= 30
  4321.2   368.3  4472.6  363.12    4496  361.67    4505  359.94  4567.9  360.33
  4656.3  356.92  4834.8  357.56  4888.1  355.77  4965.5  356.63  4985.3  355.85
  5028.3  353.91  5031.1  353.41  5034.3  353.91  5052.8  355.51  5119.8  359.16
  5200.9  359.18  5302.2  361.72  5311.3  360.97  5323.3  361.17  5446.3  363.79
  5516.7  367.36    5573  369.46  5578.8  371.92  5594.4   371.8  5600.2  373.34
  5615.8  372.94  5621.6  375.24  5631.4  374.44  5637.3  375.77  5666.5  377.07
#Mann= 6 ,-1 , 0
  4321.2     .05       0  5028.3     .03       0  5034.3     .05       0
  5311.3     .08       0  5323.3     .05       0  5516.7     .08       0
Bank Sta=4985.3,5052.8
XS Rating Curve= 0 ,0
Exp/Cntr=0.3,0.1

Type RM Length L Ch R = 1 ,6016    ,91,91,91
BEGIN DESCRIPTION:
UNT 106 IN CACR 9.0
END DESCRIPTION:
XS GIS Cut Line= 2
       3686680.5       10713096.      3687694.36     10713425.29
#Sta/Elev= 30
  4416.8  367.26  4421.6  366.99  4476.3  363.57  4545.5  361.96  4563.8   360.4
  4647.2  358.12  4673.3  360.29  4678.7  360.02  4689.2  357.05  4705.3  356.08
    4782  355.36  4872.1  354.07    4929   354.3  4934.2  352.29  4941.6  353.72
  4952.1  353.66  4980.6  351.08  4983.4  350.58  4986.6  351.08  5030.1  353.49
  5088.8  355.36    5094  356.31  5142.4  356.98  5385.9  362.41  5413.6  362.86
  5418.8  364.28  5445.5  363.39  5450.8  364.77  5477.5  364.72  5482.8  365.82
#Mann= 9 ,-1 , 0
  4416.8     .05       0  4421.6     .08       0  4563.8     .05       0
    4782     .08       0  4872.1     .05       0  4980.6     .03       0
  4986.6     .05       0  5142.4     .08       0  5385.9     .05       0
Bank Sta=4929,5030.1
XS Rating Curve= 0 ,0
Exp/Cntr=0.3,0.1

Type RM Length L Ch R = 1 ,5925    ,291,291,291
BEGIN DESCRIPTION:
Mapping XS d0320898
END DESCRIPTION:
XS GIS Cut Line= 2
      3686645.76     10713188.01      3687579.83     10713469.28
#Sta/Elev= 30
  4442.4  365.46  4466.3  364.07  4469.9  364.64  4488.2  363.16  4601.9  358.36
  4645.4  357.94  4665.7  356.94  4706.2  356.61  4722.9  357.34  4738.8  356.82
  4749.6  354.84  4791.1  353.56  4856.5  353.03  4914.7  353.07  4919.9  352.22
  4952.9  351.23  4985.9  350.56  5007.4   349.2  5010.1   348.7  5013.4   349.2
  5024.1  351.79  5029.4  352.39  5083.5  354.99  5090.1  356.63  5095.4  355.42
  5123.1  355.09  5128.4  356.53  5156.1  355.81  5246.7  358.11  5417.9  361.27
#Mann= 8 ,-1 , 0
  4442.4     .08       0  4466.3     .05       0  4722.9     .08       0
  4856.5     .05       0  5007.4     .04       0  5013.4     .05       0
  5029.4     .08       0  5246.7     .05       0
Bank Sta=4952.9,5024.1
XS Rating Curve= 0 ,0
Exp/Cntr=0.3,0.1

Type RM Length L Ch R = 1 ,5634    ,302,302,302
BEGIN DESCRIPTION:
UNT 106 IN CACR 8.0
END DESCRIPTION:
XS GIS Cut Line= 3
      3686749.61     10713510.19      3686949.61     10713560.19
      3687199.65     10713560.19
#Sta/Elev= 30
  4758.6  356.43    4823  353.56  4851.4  351.56  4859.1  350.68  4864.3  350.82
    4872  350.38  4905.5  346.54  4913.2  346.58  4923.5  345.73  4941.6  344.83
  4946.7  344.02  4954.4  344.25  4967.3  343.91  4974.8   344.4  4984.8  344.29
  4991.8  343.64  4994.5  343.14  4997.8  343.64  5004.8  343.68  5014.8   345.1
  5024.8  345.18  5034.8  346.95  5064.8  348.85  5074.8  350.14  5084.8  350.39
  5094.8  351.41  5114.8  352.61  5164.8  353.73  5184.8  354.79  5214.8  355.64
#Mann= 3 ,-1 , 0
  4758.6     .05       0  4991.8     .03       0  4997.8     .05       0
Bank Sta=4923.5,5034.8
XS Rating Curve= 0 ,0
Exp/Cntr=0.3,0.1

Type RM Length L Ch R = 1 ,5332    ,34,34,34
BEGIN DESCRIPTION:
Mapping XS 480271c8
END DESCRIPTION:
XS GIS Cut Line= 2
      3686568.29     10713690.32      3687164.64     10713984.59
#Sta/Elev= 30
  4681.6  363.88  4763.5  359.01  4794.6  357.77  4816.9  355.98  4839.2  353.56
  4847.8  353.15  4883.8  348.32  4906.1  346.96  4915.1  344.32  4920.7  346.16
  4937.6  343.25  4979.5     343  4982.2   342.5  4985.5     343  4988.1  343.32
  5100.3  343.02  5106.8  343.56  5117.2  346.59  5122.8  345.84  5139.6  346.09
  5145.2  346.39  5151.4   347.6  5167.7   347.6  5173.7  348.38  5184.5  348.86
  5190.1  348.62    5196  349.58  5212.6  350.02  5257.5  352.69  5346.6  355.45
#Mann= 3 ,-1 , 0
  4681.6     .05       0  4979.5     .03       0  4985.5     .05       0
Bank Sta=4906.1,5117.2
XS Rating Curve= 0 ,0
Exp/Cntr=0.3,0.1

Type RM Length L Ch R = 1 ,5298    ,43,43,43
BEGIN DESCRIPTION:
Mapping XS 4525e074
END DESCRIPTION:
XS GIS Cut Line= 2
       3686555.3     10713721.58      3687135.32     10714010.29
#Sta/Elev= 30
  4683.5  363.34  4715.1  361.27  4721.8  361.63  4776.7  357.17  4782.3  355.84
  4788.8  356.87  4799.1   356.1  4804.7  354.74  4849.5  351.94  4888.7  348.03
  4894.3  348.41  4933.5  346.23    4939   345.2  5000.6  345.08  5003.2  343.21
    5006  342.71  5009.2  343.21  5012.2  344.65    5023  345.55  5028.6  344.86
  5067.8  345.14  5073.4  343.92  5090.2  345.01  5101.6   343.7    5135  344.59
  5146.3  346.16  5179.8  348.62  5185.3  348.33  5252.5  352.17  5331.4  354.98
#Mann= 3 ,-1 , 0
  4683.5     .05       0  5003.2     .03       0  5009.2     .05       0
Bank Sta=4933.5,5146.3
XS Rating Curve= 0 ,0
Exp/Cntr=0.3,0.1

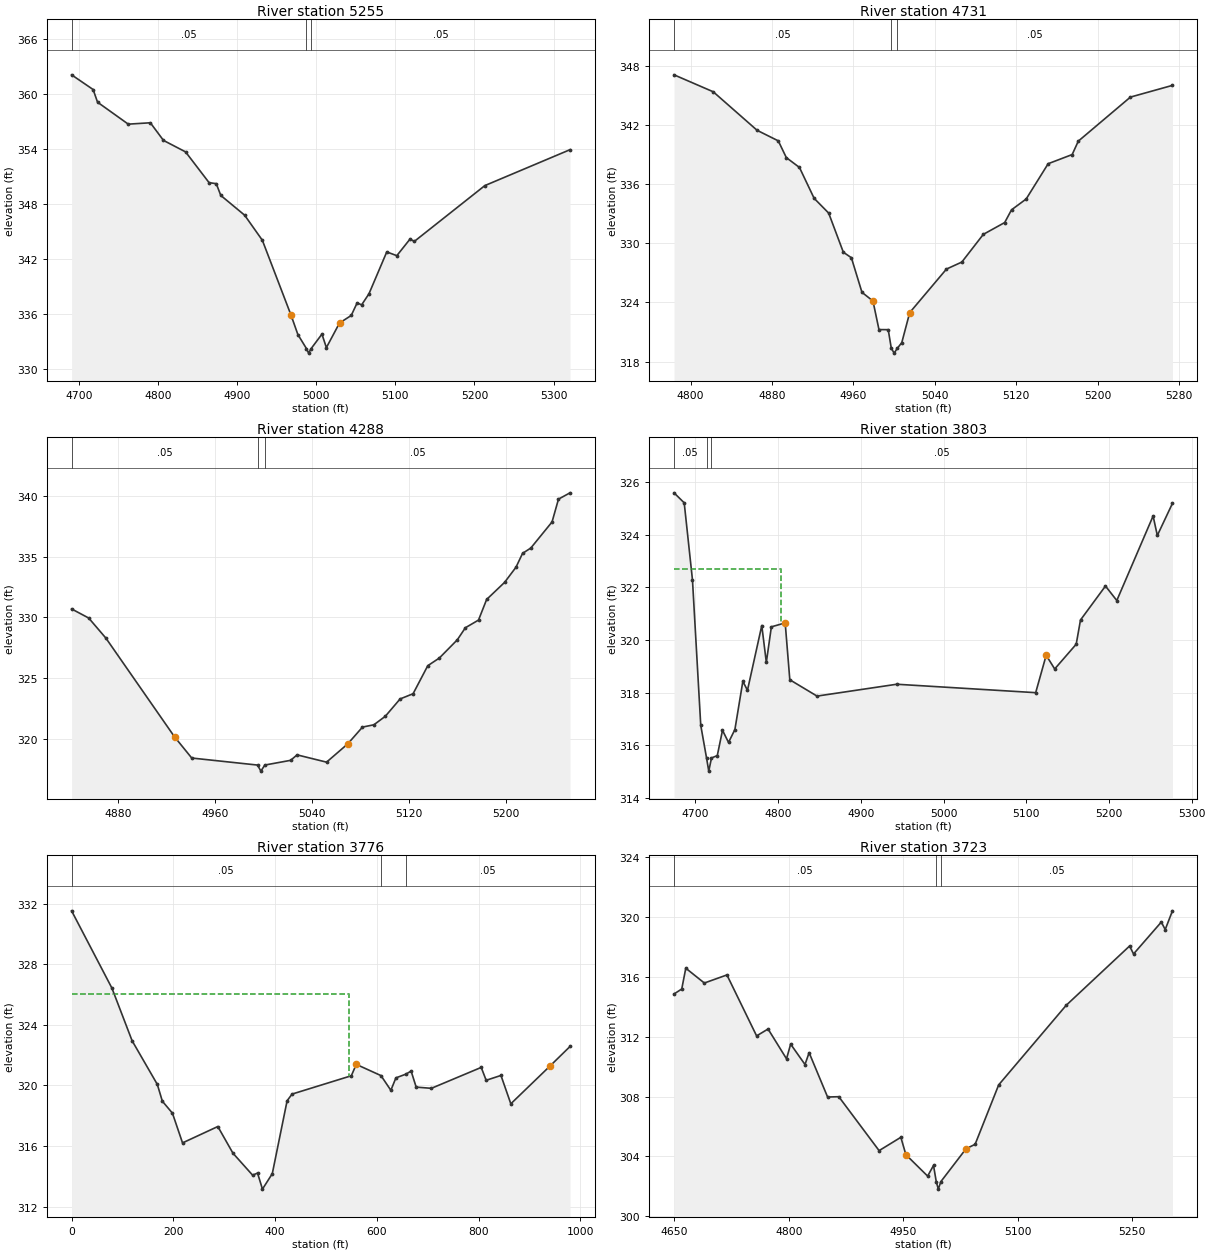
Type RM Length L Ch R = 1 ,5255    ,524,524,524
BEGIN DESCRIPTION:
UNT 106 IN CACR 7.0
END DESCRIPTION:
XS GIS Cut Line= 2
      3686544.82     10713760.61      3687105.94     10714046.37
#Sta/Elev= 30
    4691  362.06  4718.2  360.46  4723.8  359.08  4762.6  356.69  4790.5  356.84
  4807.1  354.92    4835  353.67  4864.7  350.32  4873.8  350.21  4879.5  348.93
  4909.6  346.78    4932  344.05  4968.4  335.86  4976.9  333.78  4987.7  332.26
  4990.4  331.76  4993.7  332.26  5007.3  333.83  5012.9  332.36  5029.5  335.04
  5044.3  335.86  5051.8  337.24  5057.4  337.01  5066.7  338.22  5089.2  342.78
  5101.9  342.37  5118.5  344.17  5124.1  343.93  5213.1     350  5320.7  353.91
#Mann= 3 ,-1 , 0
    4691     .05       0  4987.7     .03       0  4993.7     .05       0
Bank Sta=4968.4,5029.5
XS Rating Curve= 0 ,0
Exp/Cntr=0.3,0.1

Type RM Length L Ch R = 1 ,4731    ,443,443,443
BEGIN DESCRIPTION:
UNT 106 IN CACR 6.0
END DESCRIPTION:
XS GIS Cut Line= 3
      3686380.76     10714114.76      3686499.61     10714260.19
       3686751.6     10714426.25
#Sta/Elev= 30
  4783.8  347.09  4822.3  345.37  4865.4  341.46  4886.2  340.39  4894.1  338.69
    4907  337.69  4921.4  334.56  4935.7  333.06  4950.1  329.09    4958  328.53
  4968.4  325.02  4979.2  324.14  4985.1  321.24  4994.2  321.23  4997.2  319.35
    5000  318.85  5003.2  319.35  5007.5  319.91  5015.3  322.96  5051.4  327.38
  5066.5  328.09  5087.6   330.9  5108.6   332.1  5115.3  333.39  5129.7  334.49
  5151.3  338.07  5174.9     339  5180.9  340.36  5232.1  344.83  5273.4  346.02
#Mann= 3 ,-1 , 0
  4783.8     .05       0  4997.2     .03       0  5003.2     .05       0
Bank Sta=4979.2,5015.3
XS Rating Curve= 0 ,0
Exp/Cntr=0.3,0.1

Type RM Length L Ch R = 1 ,4288    ,485,485,485
BEGIN DESCRIPTION:
UNT 106 IN CACR 5.0
END DESCRIPTION:
XS GIS Cut Line= 3
      3686049.62      10714410.2      3686149.61     10714510.19
      3686399.64      10714610.2
#Sta/Elev= 30
    4842  330.69  4856.1  329.94  4870.3  328.28  4926.8  320.15    4941   318.4
  4995.2  317.82    4998  317.32  5001.2  317.82  5022.5  318.21  5027.8  318.66
  5052.1  318.06  5069.6  319.57  5081.7  320.95  5091.1  321.14  5100.5  321.84
  5112.7  323.27  5123.4   323.7  5135.5  326.01    5145  326.64  5159.8  328.14
  5166.5  329.14  5177.3  329.77    5184  331.47  5198.8  332.88  5208.2  334.13
  5213.6  335.27  5220.4  335.71  5237.9  337.86  5243.2  339.74  5252.7  340.26
#Mann= 3 ,-1 , 0
    4842     .05       0  4995.2     .03       0  5001.2     .05       0
Bank Sta=4926.8,5069.6
XS Rating Curve= 0 ,0
Exp/Cntr=0.3,0.1

Type RM Length L Ch R = 1 ,3803    ,27,27,27
BEGIN DESCRIPTION:
Mapping XS d5ca7f3d
END DESCRIPTION:
XS GIS Cut Line= 5
      3685671.64     10714557.94      3685672.95     10714617.83
      3685758.88     10714801.42      3685842.22     10714870.44
      3686068.76     10714919.91
#Sta/Elev= 30
  4674.1  325.59  4686.4  325.21  4696.4  322.28  4706.4  316.76  4713.4  315.52
  4716.1  315.02  4719.4  315.52  4726.4  315.61  4732.7  316.57    4740  316.11
  4747.7   316.6  4757.3  318.43  4762.9  318.09  4780.2  320.55  4785.7  319.15
  4791.8   320.5  4808.5  320.65  4814.1  318.49    4847  317.87  4943.4  318.32
  5111.4     318  5124.1  319.42  5134.4   318.9  5160.4  319.84  5165.6  320.76
  5195.8  322.05  5209.5   321.5  5253.4  324.71  5258.5  323.97  5276.8  325.19
#Mann= 3 ,-1 , 0
  4674.1     .05       0  4713.4     .03       0  4719.4     .05       0
#XS Ineff= 2 , 0
         4802.84  322.71
Permanent Ineff=
       F       F
Bank Sta=4808.5,5124.1
XS Rating Curve= 0 ,0
Exp/Cntr=0.3,0.1

Type RM Length L Ch R = 1 ,3776    ,53,53,53
BEGIN DESCRIPTION:
Mapping XS fb52fae0
END DESCRIPTION:
XS GIS Cut Line= 6
     3685693.089    10714217.733      3685624.77     10714517.52
      3685628.67      10714598.3      3685728.93     10714810.54
      3685820.08     10714887.36      3686051.89     10714939.46
#Sta/Elev= 30
       0  331.52    79.3  326.42  118.94  322.95   168.5  320.07  178.42  318.96
  198.24  318.17  218.07  316.21  287.45  317.29  317.19  315.53  355.84  314.08
  365.51  314.22  375.17  313.16   394.5  314.18  423.63  318.99  433.34  319.43
  549.86  320.64  559.57  321.39  608.12  320.65  627.54  319.68  637.49   320.5
  657.41  320.75  667.36  320.95  677.32  319.89  707.19  319.81  805.19  321.19
  814.88  320.34  843.97  320.66  863.36  318.79  940.92   321.3   979.7  322.57
#Mann= 3 ,-1 , 0
       0     .05       0  608.12     .03       0  657.41     .05       0
#XS Ineff= 2 , 0
          544.89  326.02
Permanent Ineff=
       F       F
Bank Sta=559.57,940.92
XS Rating Curve= 0 ,0
Exp/Cntr=0.3,0.1

Type RM Length L Ch R = 1 ,3723    ,343,343,343
BEGIN DESCRIPTION:
UNT 106 IN CACR 4.0
END DESCRIPTION:
XS GIS Cut Line= 4
      3685599.31     10714609.75       3685694.8     10714848.47
      3685794.63     10714935.28       3686050.7     10714998.21
#Sta/Elev= 30
  4649.7  314.85  4659.8  315.18  4665.1  316.57  4689.4  315.58    4719  316.12
  4757.9  312.05  4772.9  312.51  4797.1  310.52  4802.5   311.5  4821.3  310.14
  4826.7  310.93  4850.9  307.97  4865.6  307.99  4918.4  304.39  4946.9  305.28
  4953.5  304.12    4982  302.69  4989.7   303.4  4993.3  302.32    4996  301.82
  4999.3  302.32  5032.4  304.52  5044.2  304.81  5075.1  308.78  5163.5  314.09
  5246.6  318.05  5251.8  317.52  5288.2  319.65  5293.3  319.15  5302.8   320.4
#Mann= 3 ,-1 , 0
  4649.7     .05       0  4993.3     .03       0  4999.3     .05       0
Bank Sta=4953.5,5032.4
XS Rating Curve= 0 ,0
Exp/Cntr=0.3,0.1

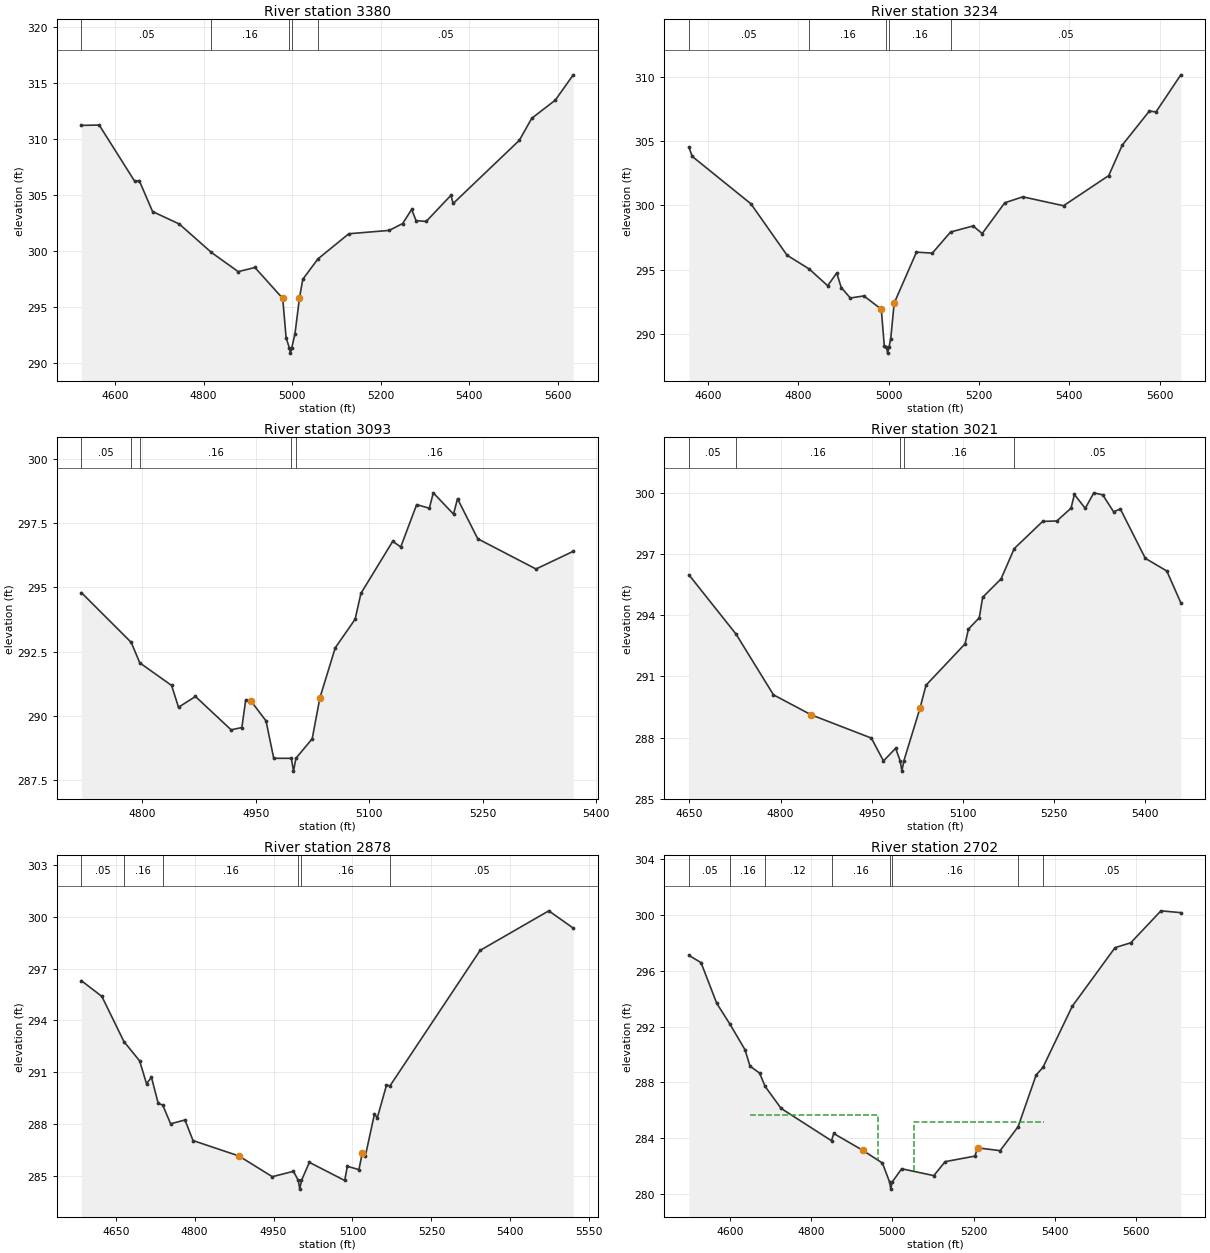
Type RM Length L Ch R = 1 ,3380    ,146,146,146
BEGIN DESCRIPTION:
UNT 106 IN CACR 3.0
END DESCRIPTION:
XS GIS Cut Line= 3
      3685549.61      10714610.2      3685499.61     10715110.19
      3686099.65      10715210.2
#Sta/Elev= 30
  4524.2  311.19  4564.4  311.22  4644.8  306.19  4654.8  306.27    4685   303.5
  4745.3  302.39  4817.9  299.85  4878.4  298.14  4916.1  298.51  4978.9  295.75
  4986.5  292.26  4993.5  291.37  4996.3  290.87  4999.5  291.37  5006.6  292.61
  5016.6  295.76  5024.2  297.46  5058.5  299.28  5128.1  301.52  5219.3  301.82
  5249.7  302.43    5270  303.69  5280.1  302.69  5302.9  302.62  5358.7  304.95
  5363.8  304.22  5513.3  309.86  5541.2  311.82  5594.4  313.44    5635   315.7
#Mann= 5 ,-1 , 0
  4524.2     .05       0  4817.9     .16       0  4993.5     .07       0
  4999.5     .16       0  5058.5     .05       0
Bank Sta=4978.9,5016.6
XS Rating Curve= 0 ,0
Exp/Cntr=0.3,0.1

Type RM Length L Ch R = 1 ,3234    ,141,141,141
BEGIN DESCRIPTION:
Mapping XS 5384dce6
END DESCRIPTION:
XS GIS Cut Line= 4
      3685354.65     10714743.02      3685363.33     10715149.29
      3685474.44     10715246.52      3686009.12     10715267.35
#Sta/Elev= 30
  4557.6  304.51  4564.8   303.8  4694.8  300.12  4774.8  296.13  4823.9  295.06
  4864.8  293.76  4884.8  294.75  4894.8  293.62  4914.9  292.81  4944.9  292.97
  4983.5  291.94  4990.2  289.06  4994.8  289.03  4997.5  288.53  5000.8  289.03
  5004.4  289.64    5012  292.41  5061.4  296.37  5096.5  296.29  5136.8  297.93
  5186.8   298.4  5206.9  297.81  5256.9   300.2  5296.9  300.66    5387  299.97
  5487.1  302.31  5517.1  304.68  5577.1  307.32  5591.7  307.25  5646.7  310.13
#Mann= 5 ,-1 , 0
  4557.6     .05       0  4823.9     .16       0  4994.8     .07       0
  5000.8     .16       0  5136.8     .05       0
Bank Sta=4983.5,5012
XS Rating Curve= 0 ,0
Exp/Cntr=0.3,0.1

Type RM Length L Ch R = 1 ,3093    ,72,72,72
BEGIN DESCRIPTION:
Mapping XS 620b6ad8
END DESCRIPTION:
XS GIS Cut Line= 4
      3685335.07     10714996.69      3685272.56     10715191.15
      3685300.34     10715343.93      3685576.39     10715433.65
#Sta/Elev= 30
  4719.6   294.8  4785.4  292.86  4796.8  292.06  4838.8  291.18  4847.9  290.33
  4870.3  290.75  4917.4  289.45  4931.6  289.54  4936.7  290.62  4943.2  290.59
  4963.5   289.8  4973.7  288.34    4997  288.34  4999.8  287.84    5003  288.34
  5024.5   289.1  5034.7   290.7    5055  292.65  5081.2  293.76  5088.9  294.77
  5130.9   296.8  5141.5  296.58  5162.5  298.23  5179.3  298.09  5184.5  298.69
  5211.2  297.86  5216.5  298.46  5243.2   296.9  5320.2  295.72  5369.4  296.41
#Mann= 5 ,-1 , 0
  4719.6     .05       0  4785.4     .16       0  4796.8     .16       0
    4997     .07       0    5003     .16       0
Bank Sta=4943.2,5034.7
XS Rating Curve= 0 ,0
Exp/Cntr=0.3,0.1

Type RM Length L Ch R = 1 ,3021    ,143,143,143
BEGIN DESCRIPTION:
Mapping XS 85246d3b
END DESCRIPTION:
XS GIS Cut Line= 4
      3685328.12     10714965.46      3685213.53     10715132.13
      3685220.48     10715368.24      3685560.79     10715517.56
#Sta/Elev= 30
  4649.1  295.98  4726.8  293.07  4788.3   290.1  4850.4  289.12  4949.5  287.98
  4969.5  286.86  4989.5  287.48    4997  286.86  4999.8  286.36    5003  286.86
  5029.5  289.43  5039.5  290.57  5103.9   292.6  5109.4  293.32  5127.3  293.88
  5132.8  294.88  5163.1  295.78  5184.9  297.27  5231.7   298.6    5255  298.62
  5278.4  299.25  5283.9  299.92  5301.8  299.24  5315.9     300  5330.6   299.9
  5348.5  299.07  5359.6  299.21  5400.7  296.79  5436.1  296.17  5459.2  294.61
#Mann= 5 ,-1 , 0
  4649.1     .05       0  4726.8     .16       0    4997     .07       0
    5003     .16       0  5184.9     .05       0
Bank Sta=4850.4,5029.5
XS Rating Curve= 0 ,0
Exp/Cntr=0.3,0.1

Type RM Length L Ch R = 1 ,2878    ,176,176,176
BEGIN DESCRIPTION:
Mapping XS ab029513
END DESCRIPTION:
XS GIS Cut Line= 4
      3685333.46       10714962.      3685073.05     10715124.75
      3685096.93     10715339.59      3685470.18      10715513.2
#Sta/Elev= 30
  4584.7   296.3  4623.6  295.39  4665.5  292.78  4695.4  291.66  4708.5  290.34
  4717.9  290.71  4730.7   289.2  4739.2  289.11  4754.3  288.02  4781.6  288.24
  4796.9  287.05    4884  286.16  4947.6  284.96  4987.8  285.27    4997  284.74
  4999.8  284.24    5003  284.74    5018  285.79  5085.2  284.74  5090.2  285.56
  5112.2  285.37  5118.8  286.35  5124.3  286.14  5141.7  288.58  5147.2  288.37
  5164.6  290.25  5171.4  290.22  5342.5  298.05  5473.1  300.34  5519.6  299.34
#Mann= 6 ,-1 , 0
  4584.7     .05       0  4665.5     .16       0  4739.2     .16       0
    4997     .07       0    5003     .16       0  5171.4     .05       0
Bank Sta=4884,5118.8
XS Rating Curve= 0 ,0
Exp/Cntr=0.3,0.1

Type RM Length L Ch R = 1 ,2702    ,1664,1664,1664
BEGIN DESCRIPTION:
UNT 106 IN CACR 2.0
END DESCRIPTION:
XS GIS Cut Line= 4
      3685336.96     10714938.39      3684941.11     10715105.06
       3684892.5     10715271.72      3685440.67      10715535.4
#Sta/Elev= 30
  4498.9   297.1  4528.6  296.59  4567.3  293.67  4599.9  292.17  4637.1  290.33
  4649.3  289.16    4673  288.66  4686.2  287.72  4725.9  286.13    4850  283.81
  4855.5  284.33  4926.5  283.13  4975.4  282.21  4993.2  280.84    4996  280.34
  4999.2  280.84  5022.7   281.8    5102  281.31  5129.8  282.31  5203.3  282.71
  5209.8   283.3  5265.3   283.1  5309.6  284.82    5354  288.53  5370.7  289.07
  5442.8  293.45  5548.3  297.66  5587.1  298.01  5661.4   300.3  5710.3  300.17
#Mann= 8 ,-1 , 0
  4498.9     .05       0  4599.9     .16       0  4686.2     .12       0
    4850     .16       0  4993.2     .07       0  4999.2     .16       0
  5309.6     .16       0  5370.7     .05       0
#XS Ineff= 2 ,-1
 4649.77 4964.77  285.63 5052.27 5372.84  285.16
Permanent Ineff=
       F       F
Bank Sta=4926.5,5209.8
XS Rating Curve= 0 ,0
Exp/Cntr=0.3,0.1

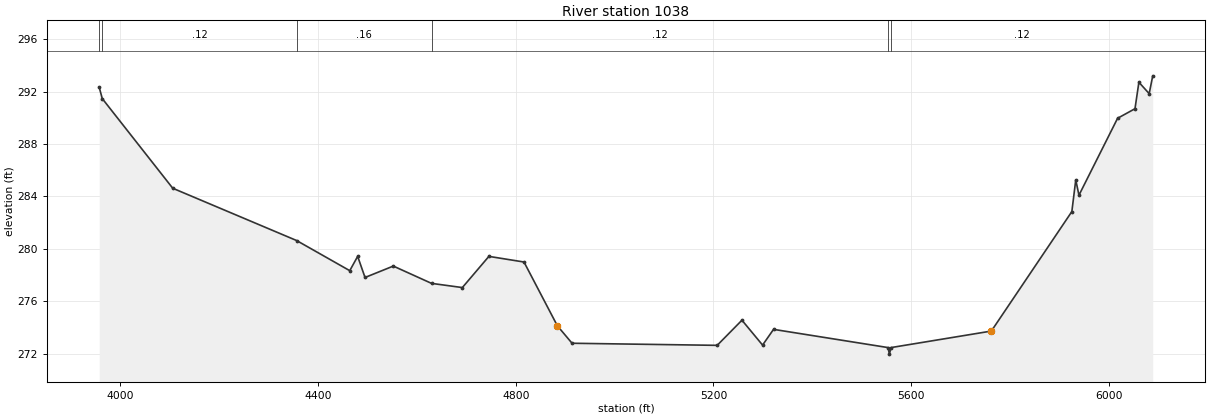
Type RM Length L Ch R = 1 ,1038    ,0,0,0
BEGIN DESCRIPTION:
UNT 106 IN CACR 1.0
END DESCRIPTION:
XS GIS Cut Line= 3
      3685199.57     10714810.21      3684299.61     10715310.19
      3683599.58     10716160.22
#Sta/Elev= 30
  3957.7  292.32  3963.9  291.46  4106.4  284.62  4356.9  280.63  4464.4  278.33
  4480.4  279.42  4495.3  277.81  4552.5  278.68  4629.8  277.36  4692.1  277.04
  4745.8  279.42  4816.8  278.99  4884.3  274.12    4914  272.79  5207.5  272.63
  5257.6  274.55  5299.3  272.65  5321.5  273.85  5553.1  272.46  5555.8  271.96
  5559.1  272.46    5762  273.72  5924.8  282.84  5932.7  285.25  5939.2  284.09
  6017.3  289.96  6052.5  290.69  6060.4  292.71  6081.2  291.84  6088.4   293.2
#Mann= 6 ,-1 , 0
  3957.7     .05       0  3963.9     .12       0  4356.9     .16       0
  4629.8     .12       0  5553.1     .07       0  5559.1     .12       0
Bank Sta=4884.3,5762
XS Rating Curve= 0 ,0
Exp/Cntr=0.3,0.1

Chan Stop Cuts=-1
Use User Specified Reach Order=0
Composite Channel Slope=5