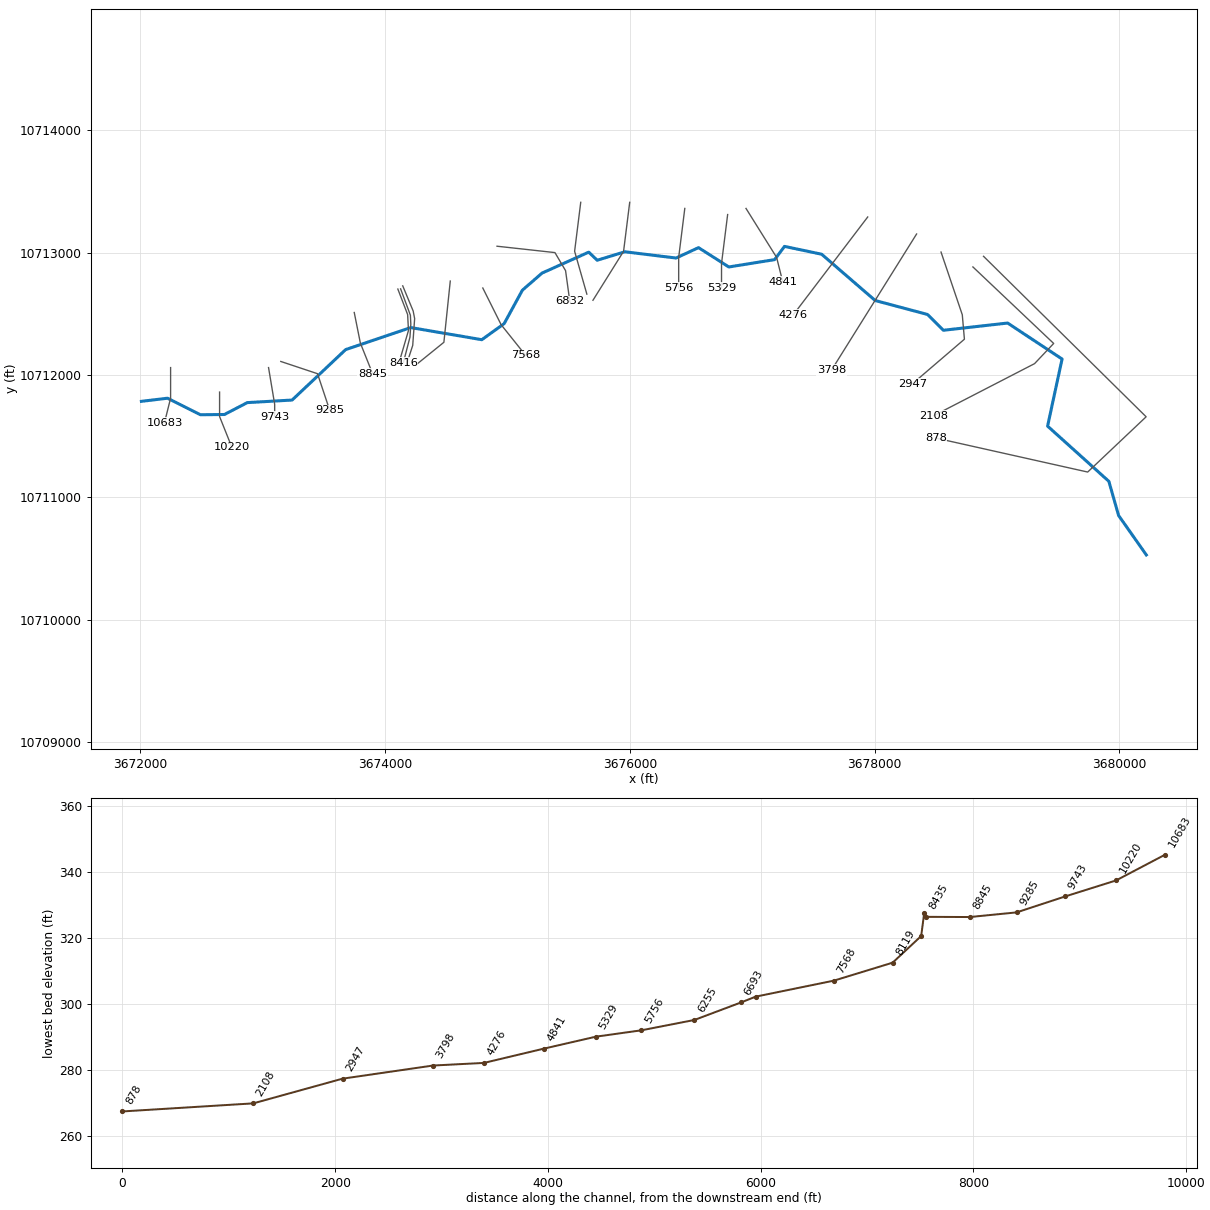
--- UNT 107 IN CACR.prj (project) ---

Proj Title=UNT 107 IN CACR Base Level Engineering
Current Plan=p01
Default Exp/Contr=0.3,0.1
English Units
Geom File=g01
Flow File=f01
Plan File=p01
BEGIN DESCRIPTION:
UNT 107 IN CACR
END DESCRIPTION:

--- UNT 107 IN CACR.p01 (plan) ---

Plan Title=Multiple Run
Short Identifier=Multiple
Geom File=g01
Flow File=f01
Subcritical Flow
K Sum by GR= 0
Std Step Tol= 0.01
Critical Tol= 0.01
Num of Std Step Trials= 20
Max Error Tol= 0.3
Flow Tol Ratio= 0.001
Split Flow NTrial= 30
Split Flow Tol= 0.02
Split Flow Ratio= 0.02
Log Output Level= 0
Friction Slope Method= 1
Unsteady Friction Slope Method= 2
Unsteady Bridges Friction Slope Method= 1
Parabolic Critical Depth
Global Vel Dist=  1 , 1 , 1
Global Log Level= 0
CheckData=True
Encroach Param= -1, 0, 0, 0
BEGIN DESCRIPTION:
Multiple Run
END DESCRIPTION:

--- UNT 107 IN CACR.f01 (steady flow) ---

Flow Title=Multiple
Number of Profiles=7
Profile Names=10-year,25-year,50-year,1pct_min,100-year,1pct_plu,500-year
River Rch & RM= UNT 107 IN CACR,Reach-1,10683
     596     821    1010     915    1237    1673    1862
River Rch & RM= UNT 107 IN CACR,Reach-1,7568
     827    1161    1446    1324    1790    2421    2757
River Rch & RM= UNT 107 IN CACR,Reach-1,6693
    1174    1670    2099    1936    2618    3540    4092
Boundary for River Rch & Prof#=UNT 107 IN CACR,Reach-1,1
Up Type=0
Dn Type=3
Dn Slope=0.005
Boundary for River Rch & Prof#=UNT 107 IN CACR,Reach-1,2
Up Type=0
Dn Type=3
Dn Slope=0.005
Boundary for River Rch & Prof#=UNT 107 IN CACR,Reach-1,3
Up Type=0
Dn Type=3
Dn Slope=0.005
Boundary for River Rch & Prof#=UNT 107 IN CACR,Reach-1,4
Up Type=0
Dn Type=3
Dn Slope=0.005
Boundary for River Rch & Prof#=UNT 107 IN CACR,Reach-1,5
Up Type=0
Dn Type=3
Dn Slope=0.005
Boundary for River Rch & Prof#=UNT 107 IN CACR,Reach-1,6
Up Type=0
Dn Type=3
Dn Slope=0.005
Boundary for River Rch & Prof#=UNT 107 IN CACR,Reach-1,7
Up Type=0
Dn Type=3
Dn Slope=0.005

--- UNT 107 IN CACR.g01 (geometry) ---

Geom Title=Existing Conditions

River Reach=UNT 107 IN CACR,Reach-1
Reach XY= 30
      3672011.15     10711784.40      3672224.25     10711810.00
      3672493.00     10711675.00      3672689.25     10711677.00
      3672876.00     10711774.00      3673242.25     10711795.00
      3673679.25     10712207.00      3674211.25     10712387.00
      3674791.75     10712288.00      3674974.00     10712419.00
      3675122.75     10712692.00      3675283.50     10712832.00
      3675665.00     10713003.00      3675734.00     10712937.00
      3675960.00     10713006.00      3676378.50     10712955.00
      3676561.75     10713040.00      3676809.25     10712882.00
      3677183.50     10712942.00      3677264.00     10713050.00
      3677567.50     10712986.00      3678004.75     10712608.00
      3678432.25     10712494.00      3678562.25     10712365.00
      3679086.75     10712424.00      3679531.25     10712130.00
      3679413.00     10711582.00      3679913.50     10711131.00
      3679993.00     10710852.00      3680219.50     10710530.00

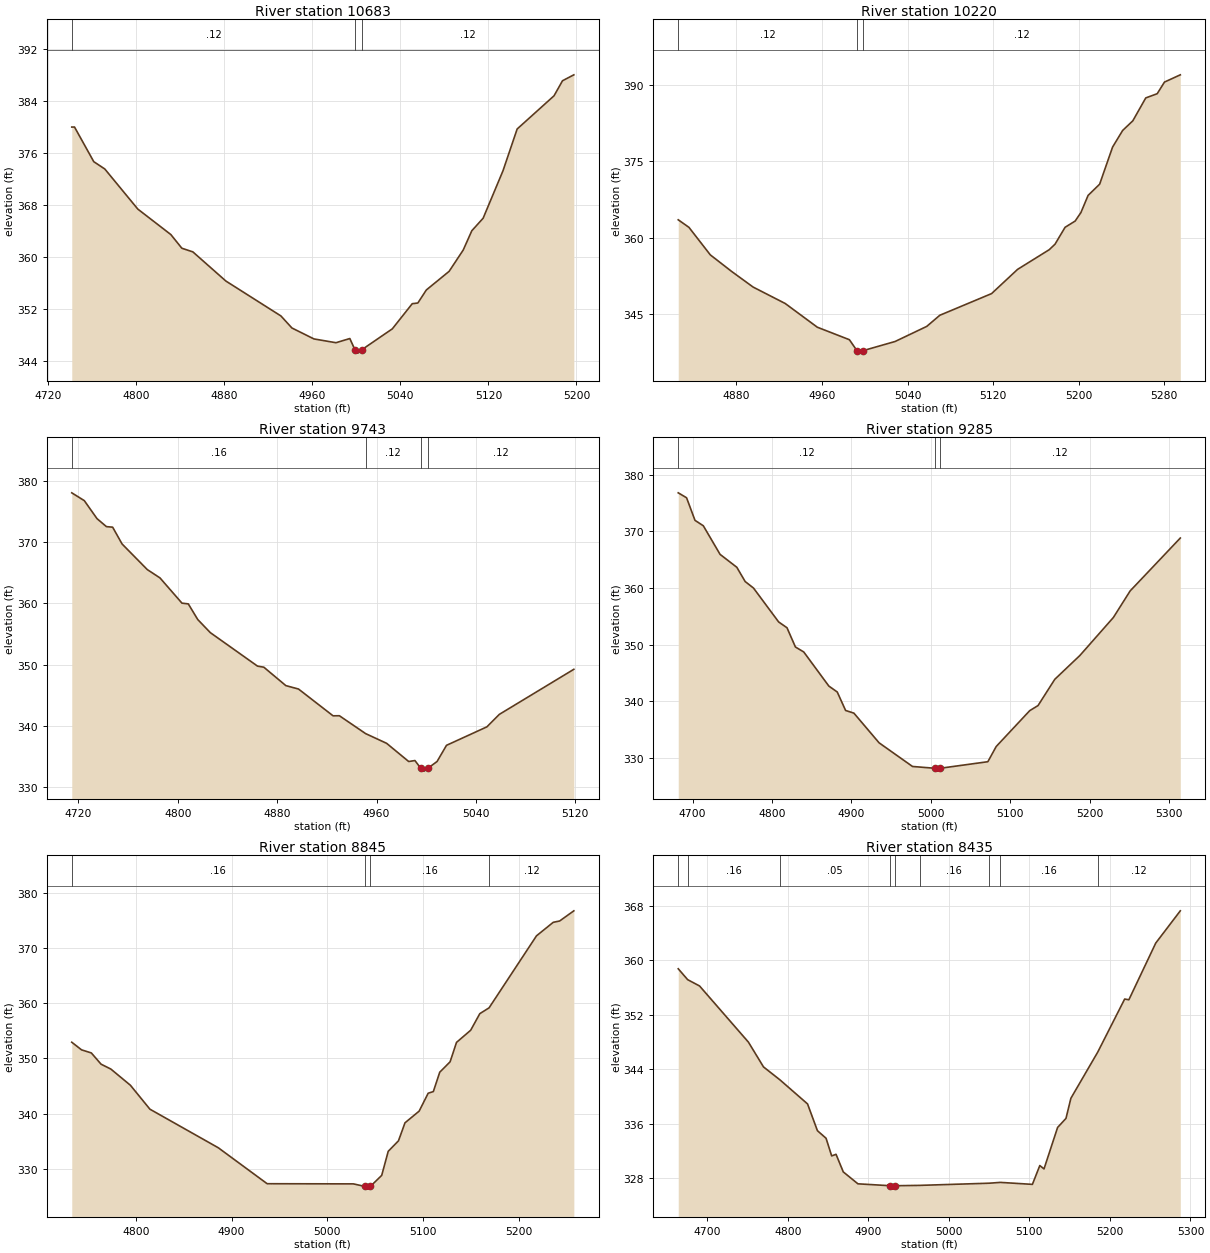
Type RM Length L Ch R = 1,10683,463,463,463
BEGIN DESCRIPTION:
UNT 107 IN CACR 19.0
END DESCRIPTION:
XS GIS Cut Line= 3
      3672249.61     10712060.18      3672249.61     10711810.19
      3672199.62     10711610.23
#Sta/Elev= 30
  4741.5  379.98  4744.0  379.98  4761.5  374.66  4771.5  373.54  4801.5  367.38
  4831.5  363.47  4841.5  361.37  4851.5  360.81  4881.5  356.33  4931.5  350.97
  4941.5  349.12  4961.5  347.44  4981.5  346.86  4994.1  347.50  4998.8  345.76
  5001.5  345.26  5004.8  345.76  5032.7  348.99  5050.8  352.85  5055.9  352.96
  5063.6  354.96  5084.3  357.82  5097.1  361.09  5104.9  364.05  5115.2  365.98
  5133.2  373.25  5146.1  379.68  5179.6  384.78  5187.3  387.09  5197.6  388.00
#Mann=3,-1,0
  4741.5    0.12       0  4998.8    0.07       0  5004.8    0.12       0
Bank Sta=4998.8,5004.8
Exp/Cntr=0.3,0.1

Type RM Length L Ch R = 1,10220,477,477,477
BEGIN DESCRIPTION:
UNT 107 IN CACR 18.0
END DESCRIPTION:
XS GIS Cut Line= 3
      3672649.61     10711860.21      3672649.61     10711660.19
      3672749.62     10711410.17
#Sta/Elev= 30
  4825.7  363.55  4835.7  362.07  4855.7  356.67  4875.7  353.41  4895.7  350.36
  4925.7  347.14  4955.7  342.49  4985.7  340.04  4992.7  337.91  4995.5  337.41
  4998.7  337.91  5028.4  339.69  5058.0  342.65  5070.2  344.83  5118.6  349.08
  5142.9  353.83  5172.5  357.69  5177.9  358.77  5187.3  362.08  5196.7  363.30
  5202.1  364.97  5208.8  368.33  5219.6  370.53  5231.7  377.81  5241.1  381.06
  5250.6  382.95  5262.7  387.44  5273.4  388.27  5280.2  390.55  5295.0  391.97
#Mann=3,-1,0
  4825.7    0.12       0  4992.7    0.07       0  4998.7    0.12       0
Bank Sta=4992.7,4998.7
Exp/Cntr=0.3,0.1

Type RM Length L Ch R = 1,9743,458,458,458
BEGIN DESCRIPTION:
UNT 107 IN CACR 17.0
END DESCRIPTION:
XS GIS Cut Line= 3
      3673049.61     10712060.17      3673099.61     10711760.19
      3673099.61     10711660.21
#Sta/Elev= 30
  4714.7  378.10  4724.8  376.82  4735.0  373.88  4742.6  372.57  4747.6  372.48
  4755.2  369.73  4775.5  365.54  4785.7  364.18  4803.4  360.05  4808.5  359.93
  4816.1  357.37  4826.2  355.23  4864.2  349.75  4869.3  349.57  4887.0  346.56
  4897.2  346.00  4925.0  341.62  4930.1  341.63  4951.2  338.71  4968.1  337.12
  4985.9  334.14  4990.9  334.30  4995.5  333.07  4998.3  332.57  5001.5  333.07
  5008.7  334.14  5016.3  336.79  5048.8  339.81  5058.8  341.85  5118.8  349.23
#Mann=4,-1,0
  4714.7    0.16       0  4951.2    0.12       0  4995.5    0.07       0
  5001.5    0.12       0
Bank Sta=4995.5,5001.5
Exp/Cntr=0.3,0.1

Type RM Length L Ch R = 1,9285,440,440,440
BEGIN DESCRIPTION:
UNT 107 IN CACR 16.0
END DESCRIPTION:
XS GIS Cut Line= 3
      3673149.63     10712110.18      3673449.61     10712010.19
      3673549.60     10711710.22
#Sta/Elev= 30
  4681.8  376.79  4692.3  375.92  4702.9  371.94  4713.4  370.98  4734.5  365.94
  4755.6  363.66  4766.1  361.15  4776.6  360.00  4808.3  354.02  4818.8  353.00
  4829.4  349.61  4839.9  348.73  4871.5  342.72  4882.1  341.67  4892.6  338.42
  4903.1  337.94  4934.8  332.71  4976.9  328.54  5005.5  328.22  5008.3  327.72
  5011.5  328.22  5071.8  329.38  5082.3  332.06  5124.5  338.38  5135.0  339.28
  5156.1  343.91  5187.7  348.11  5229.9  354.81  5251.0  359.49  5314.2  368.82
#Mann=3,-1,0
  4681.8    0.12       0  5005.5    0.07       0  5011.5    0.12       0
Bank Sta=5005.5,5011.5
Exp/Cntr=0.3,0.1

Type RM Length L Ch R = 1,8845,410,410,410
BEGIN DESCRIPTION:
UNT 107 IN CACR 15.0
END DESCRIPTION:
XS GIS Cut Line= 3
      3673749.60     10712510.21      3673799.61     10712260.19
      3673899.60     10712010.22
#Sta/Elev= 30
  4733.2  352.92  4743.4  351.54  4753.6  350.98  4763.8  348.94  4774.0  348.06
  4794.4  345.13  4814.8  340.79  4886.2  333.80  4937.2  327.29  5027.2  327.26
  5039.0  326.81  5041.8  326.31  5045.0  326.81  5056.8  328.80  5063.6  333.16
  5074.3  335.06  5081.1  338.32  5095.9  340.44  5105.3  343.68  5110.7  343.98
  5117.4  347.49  5128.2  349.37  5134.9  352.89  5149.7  355.09  5159.2  358.09
  5168.9  359.15  5218.4  372.19  5235.9  374.64  5242.6  374.88  5257.4  376.72
#Mann=4,-1,0
  4733.2    0.16       0  5039.0    0.07       0  5045.0    0.16       0
  5168.9    0.12       0
Bank Sta=5039,5045
Exp/Cntr=0.3,0.1

Type RM Length L Ch R = 1,8435,19,19,19
BEGIN DESCRIPTION:
UNT 107 IN CACR 14.0
END DESCRIPTION:
XS GIS Cut Line= 4
      3674105.78     10712701.63      3674185.66     10712493.26
      3674192.60     10712363.05      3674116.59     10712103.92
#Sta/Elev= 30
  4663.8  358.77  4675.5  357.17  4690.3  356.24  4751.0  347.98  4769.7  344.34
  4790.0  342.45  4824.4  338.90  4836.7  334.96  4847.4  333.85  4854.4  331.25
  4859.8  331.49  4868.8  328.90  4887.0  327.15  4927.1  326.87  4929.8  326.37
  4933.1  326.87  4963.5  326.92  5050.0  327.24  5063.9  327.36  5103.7  327.07
  5112.9  329.84  5118.1  329.34  5135.0  335.44  5145.4  336.77  5151.5  339.73
  5184.9  346.53  5218.3  354.32  5223.5  354.21  5256.9  362.55  5287.4  367.29
#Mann=9,-1,0
  4663.8    0.12       0  4675.5    0.16       0  4790.0    0.05       0
  4927.1    0.07       0  4933.1    0.05       0  4963.5    0.16       0
  5050.0    0.05       0  5063.9    0.16       0  5184.9    0.12       0
Bank Sta=4927.1,4933.1
Exp/Cntr=0.3,0.1

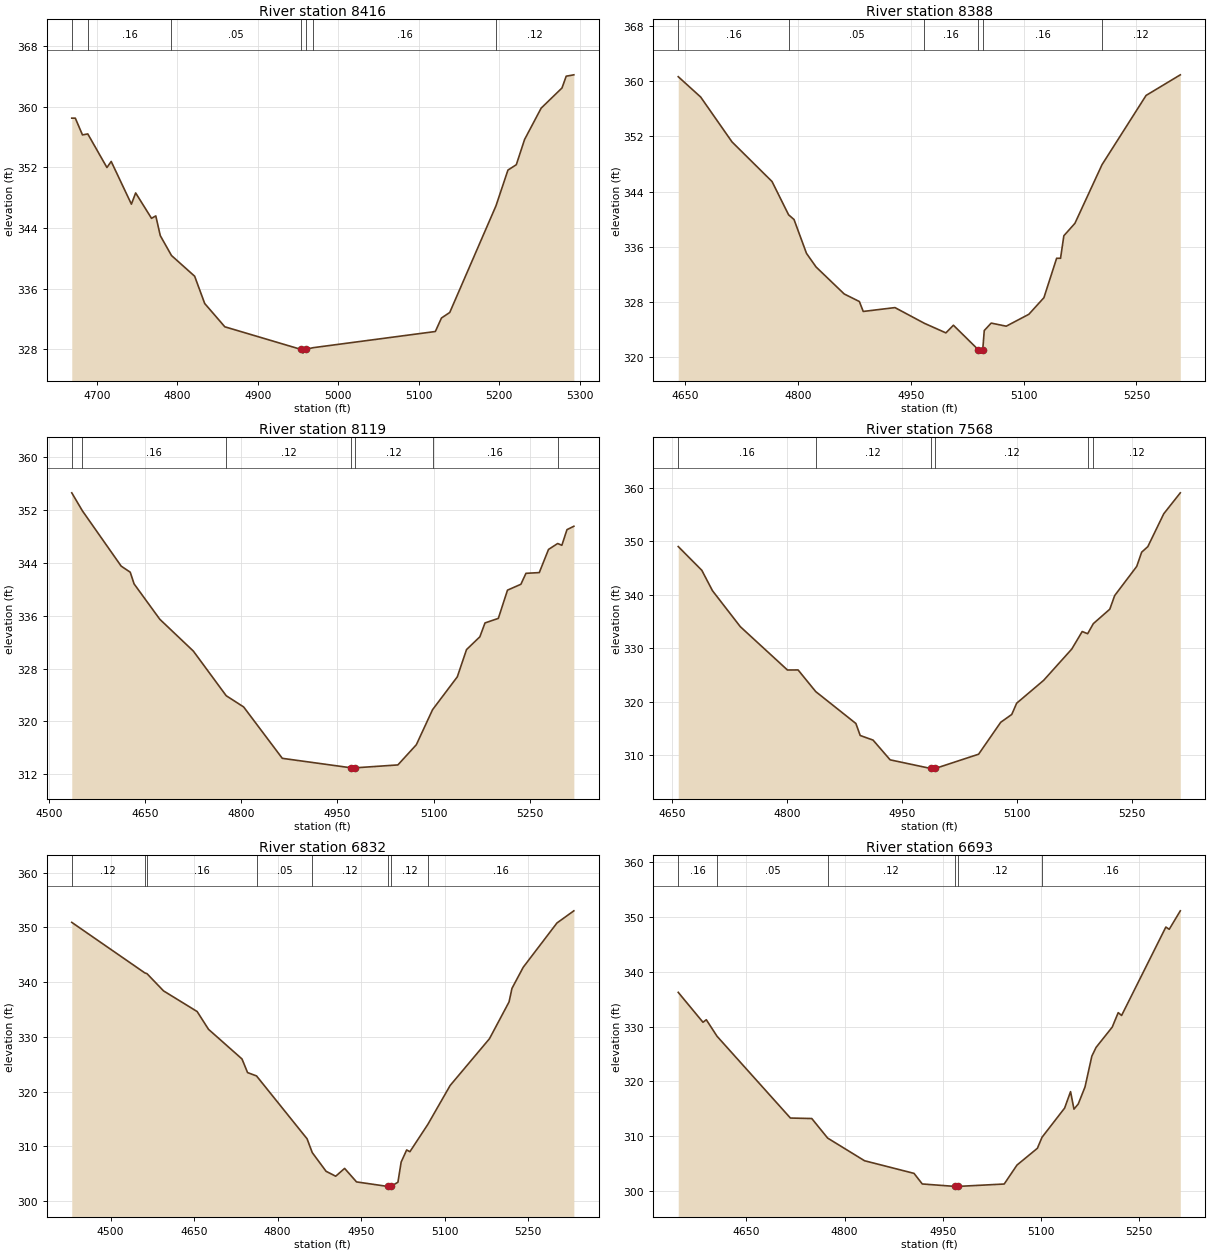
Type RM Length L Ch R = 1,8416,28,28,28
BEGIN DESCRIPTION:
Mapping XS 6e6e9641
END DESCRIPTION:
XS GIS Cut Line= 5
      3674128.36     10712703.34      3674208.23     10712488.05
      3674211.70     10712415.13      3674204.76     10712309.23
      3674150.94     10712100.92
#Sta/Elev= 30
  4668.7  358.47  4673.1  358.47  4682.0  356.26  4688.6  356.39  4712.4  351.96
  4717.7  352.76  4742.8  347.13  4748.1  348.61  4767.8  345.26  4773.1  345.58
  4778.7  342.98  4792.6  340.36  4821.4  337.63  4833.9  334.03  4858.9  330.96
  4953.3  327.99  4956.0  327.49  4959.3  327.99  4968.8  328.21  5120.5  330.34
  5128.1  332.12  5138.4  332.85  5195.8  346.90  5210.7  351.62  5221.1  352.33
  5231.4  355.66  5252.0  359.79  5277.9  362.45  5283.1  364.00  5292.6  364.18
#Mann=7,-1,0
  4668.7    0.12       0  4688.6    0.16       0  4792.6    0.05       0
  4953.3    0.07       0  4959.3    0.05       0  4968.8    0.16       0
  5195.8    0.12       0
Bank Sta=4953.3,4959.3
Exp/Cntr=0.3,0.1

Type RM Length L Ch R = 1,8388,269,269,269
BEGIN DESCRIPTION:
Mapping XS d0ac49af
END DESCRIPTION:
XS GIS Cut Line= 5
      3674145.71     10712727.68      3674230.80     10712522.77
      3674242.95     10712460.27      3674227.33     10712241.52
      3674176.97     10712086.97
#Sta/Elev= 30
  4641.0  360.68  4670.8  357.73  4712.5  351.21  4765.7  345.46  4787.7  340.63
  4794.9  339.95  4811.5  335.03  4824.2  333.06  4861.6  329.14  4881.8  328.04
  4886.9  326.60  4929.1  327.16  4968.2  324.88  4996.8  323.49  5006.8  324.60
  5039.8  321.05  5042.5  320.55  5045.8  321.05  5047.8  323.83  5057.0  324.91
  5077.0  324.46  5107.1  326.19  5127.1  328.60  5144.0  334.32  5149.2  334.32
  5153.6  337.59  5168.3  339.39  5204.3  347.90  5262.9  357.96  5308.4  360.95
#Mann=6,-1,0
  4641.0    0.16       0  4787.7    0.05       0  4968.2    0.16       0
  5039.8    0.07       0  5045.8    0.16       0  5204.3    0.12       0
Bank Sta=5039.8,5045.8
Exp/Cntr=0.3,0.1

Type RM Length L Ch R = 1,8119,551,551,551
BEGIN DESCRIPTION:
UNT 107 IN CACR 13.0
END DESCRIPTION:
XS GIS Cut Line= 3
      3674533.95     10712766.85      3674481.86     10712266.81
      3674263.88     10712090.35
#Sta/Elev= 30
  4535.5  354.64  4552.1  351.91  4612.6  343.53  4626.7  342.61  4632.7  340.84
  4672.9  335.47  4725.2  330.65  4776.4  323.89  4803.6  322.19  4863.9  314.40
  4971.5  312.96  4974.3  312.46  4977.5  312.96  5044.2  313.40  5073.0  316.46
  5098.3  321.77  5136.9  326.75  5151.3  330.88  5172.1  332.82  5180.1  334.92
  5200.9  335.61  5215.2  339.89  5236.1  340.78  5244.0  342.44  5264.8  342.55
  5279.2  346.06  5293.5  346.96  5300.0  346.69  5308.0  349.06  5318.7  349.57
#Mann=7,-1,0
  4535.5    0.12       0  4552.1    0.16       0  4776.4    0.12       0
  4971.5    0.07       0  4977.5    0.12       0  5098.3    0.16       0
  5293.5    0.12       0
Bank Sta=4971.5,4977.5
Exp/Cntr=0.3,0.1

Type RM Length L Ch R = 1,7568,736,736,736
BEGIN DESCRIPTION:
UNT 107 IN CACR 12.0
END DESCRIPTION:
XS GIS Cut Line= 3
      3674799.61     10712710.19      3674949.61     10712410.19
      3675149.63     10712160.17
#Sta/Elev= 30
  4658.0  348.99  4688.8  344.55  4702.7  340.74  4739.1  334.01  4800.6  325.92
  4814.5  325.93  4837.5  321.89  4890.0  315.92  4895.6  313.68  4912.4  312.82
  4934.7  309.13  4987.6  307.52  4990.4  307.02  4993.6  307.52  5050.2  310.18
  5079.1  316.15  5093.5  317.61  5099.9  319.71  5135.1  323.98  5171.9  329.84
  5185.5  333.11  5192.6  332.70  5200.0  334.58  5221.5  337.28  5227.9  339.83
  5256.7  345.28  5263.1  347.93  5271.2  348.98  5292.0  355.12  5313.6  359.03
#Mann=6,-1,0
  4658.0    0.16       0  4837.5    0.12       0  4987.6    0.07       0
  4993.6    0.12       0  5192.6    0.16       0  5200.0    0.12       0
Bank Sta=4987.6,4993.6
Exp/Cntr=0.3,0.1

Type RM Length L Ch R = 1,6832,139,139,139
BEGIN DESCRIPTION:
UNT 107 IN CACR 11.0
END DESCRIPTION:
XS GIS Cut Line= 4
      3674915.88     10713051.53      3675388.98     10712999.45
      3675475.79     10712851.88      3675510.51     10712600.13
#Sta/Elev= 30
  4430.4  350.92  4561.6  341.68  4565.4  341.55  4595.1  338.40  4655.5  334.62
  4675.9  331.37  4736.0  325.95  4746.0  323.46  4762.1  322.85  4852.8  311.36
  4862.1  308.84  4886.9  305.42  4904.2  304.52  4920.2  305.95  4941.6  303.48
  4997.2  302.66  5000.0  302.16  5003.2  302.66  5015.9  303.42  5021.7  307.11
  5031.6  309.32  5037.4  309.00  5069.7  314.01  5109.6  321.10  5180.2  329.65
  5215.4  336.38  5220.6  338.85  5240.8  342.71  5301.4  350.81  5331.7  353.03
#Mann=8,-1,0
  4430.4    0.12       0  4561.6    0.05       0  4565.4    0.16       0
  4762.1    0.05       0  4862.1    0.12       0  4997.2    0.07       0
  5003.2    0.12       0  5069.7    0.16       0
Bank Sta=4997.2,5003.2
Exp/Cntr=0.3,0.1

Type RM Length L Ch R = 1,6693,438,438,438
BEGIN DESCRIPTION:
UNT 107 IN CACR 10.0
END DESCRIPTION:
XS GIS Cut Line= 3
      3675599.61     10713410.22      3675549.61     10713010.19
      3675649.62     10712660.15
#Sta/Elev= 30
  4545.9  336.24  4583.7  330.79  4588.8  331.25  4605.2  328.24  4717.3  313.34
  4750.0  313.25  4774.2  309.69  4830.6  305.56  4906.2  303.26  4918.8  301.33
  4968.1  300.89  4970.9  300.39  4974.1  300.89  5044.0  301.32  5063.5  304.77
  5094.7  307.83  5101.8  309.84  5136.3  315.15  5145.4  318.15  5150.6  314.96
  5157.1  315.89  5167.5  319.01  5177.9  324.61  5184.4  326.21  5209.1  329.91
  5218.2  332.54  5223.4  332.03  5291.0  348.13  5296.2  347.73  5313.1  351.09
#Mann=6,-1,0
  4545.9    0.16       0  4605.2    0.05       0  4774.2    0.12       0
  4968.1    0.07       0  4974.1    0.12       0  5101.8    0.16       0
Bank Sta=4968.1,4974.1
Exp/Cntr=0.3,0.1

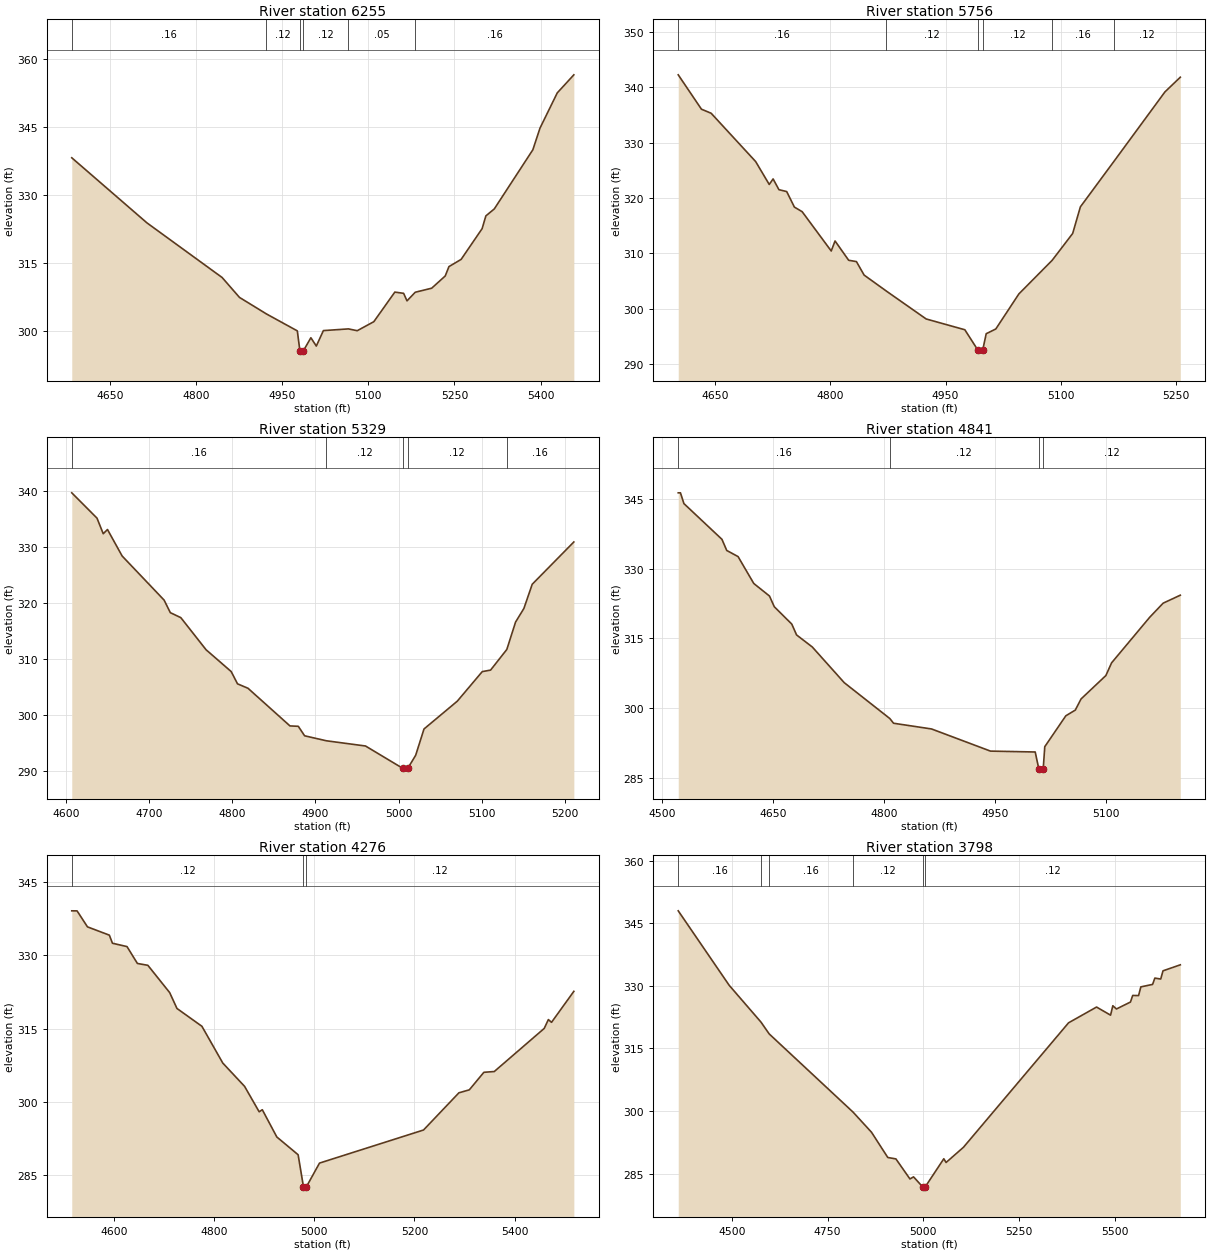
Type RM Length L Ch R = 1,6255,499,499,499
BEGIN DESCRIPTION:
UNT 107 IN CACR 9.0
END DESCRIPTION:
XS GIS Cut Line= 3
      3675999.60     10713410.14      3675949.61     10713010.19
      3675699.59     10712610.16
#Sta/Elev= 30
  4583.3  338.20  4714.3  323.83  4845.3  311.77  4875.5  307.38  4922.5  303.73
  4976.3  299.99  4980.8  295.58  4983.6  295.08  4986.8  295.58  4999.9  298.48
  5009.4  296.64  5021.7  300.05  5065.3  300.43  5080.7  300.03  5109.6  302.02
  5146.2  308.55  5161.5  308.28  5167.4  306.62  5181.8  308.52  5210.4  309.41
  5234.0  312.11  5240.5  314.18  5261.7  315.77  5298.3  322.56  5304.8  325.37
  5319.5  326.91  5386.7  339.97  5399.1  344.74  5429.2  352.52  5458.1  356.51
#Mann=6,-1,0
  4583.3    0.16       0  4922.5    0.12       0  4980.8    0.07       0
  4986.8    0.12       0  5065.3    0.05       0  5181.8    0.16       0
Bank Sta=4980.8,4986.8
Exp/Cntr=0.3,0.1

Type RM Length L Ch R = 1,5756,427,427,427
BEGIN DESCRIPTION:
UNT 107 IN CACR 8.0
END DESCRIPTION:
XS GIS Cut Line= 3
      3676449.61     10713360.16      3676399.61     10712960.19
      3676399.61     10712710.17
#Sta/Elev= 30
  4602.3  342.29  4632.5  336.07  4645.1  335.34  4703.0  326.60  4720.7  322.45
  4725.7  323.46  4733.3  321.51  4743.4  321.17  4753.4  318.36  4763.5  317.53
  4801.3  310.42  4806.3  312.23  4824.0  308.74  4834.1  308.50  4844.1  306.06
  4873.2  303.15  4924.8  298.12  4975.1  296.17  4992.3  292.44  4995.1  291.94
  4998.3  292.44  5002.9  295.45  5015.4  296.31  5045.4  302.65  5088.7  308.73
  5115.4  313.59  5125.4  318.40  5168.9  326.60  5235.4  339.20  5255.4  341.86
#Mann=6,-1,0
  4602.3    0.16       0  4873.2    0.12       0  4992.3    0.07       0
  4998.3    0.12       0  5088.7    0.16       0  5168.9    0.12       0
Bank Sta=4992.3,4998.3
Exp/Cntr=0.3,0.1

Type RM Length L Ch R = 1,5329,488,488,488
BEGIN DESCRIPTION:
UNT 107 IN CACR 7.0
END DESCRIPTION:
XS GIS Cut Line= 3
      3676799.61     10713310.22      3676749.61     10712910.19
      3676749.61     10712710.23
#Sta/Elev= 30
  4607.3  339.62  4637.6  335.11  4645.1  332.33  4650.2  333.08  4667.8  328.36
  4718.2  320.50  4725.7  318.26  4738.3  317.37  4768.6  311.65  4798.8  307.76
  4806.4  305.57  4819.0  304.78  4869.4  298.07  4879.4  298.00  4887.0  296.31
  4913.1  295.42  4960.1  294.49  5004.9  290.51  5007.7  290.01  5010.9  290.51
  5020.4  292.83  5030.4  297.52  5070.4  302.48  5100.4  307.75  5110.4  308.02
  5129.9  311.70  5140.4  316.58  5150.4  319.01  5160.4  323.32  5210.4  330.86
#Mann=5,-1,0
  4607.3    0.16       0  4913.1    0.12       0  5004.9    0.07       0
  5010.9    0.12       0  5129.9    0.16       0
Bank Sta=5004.9,5010.9
Exp/Cntr=0.3,0.1

Type RM Length L Ch R = 1,4841,565,565,565
BEGIN DESCRIPTION:
UNT 107 IN CACR 6.0
END DESCRIPTION:
XS GIS Cut Line= 3
      3676949.60     10713360.20      3677199.61     10712960.19
      3677249.62     10712760.16
#Sta/Elev= 30
  4521.9  346.31  4524.9  346.31  4529.6  343.99  4580.9  336.30  4587.4  333.90
  4602.7  332.58  4623.9  326.79  4645.1  324.09  4651.6  321.78  4675.2  318.05
  4681.7  315.71  4702.9  313.12  4746.0  305.44  4807.6  297.71  4812.6  296.70
  4863.9  295.47  4943.5  290.70  5003.9  290.51  5008.7  286.89  5011.4  286.39
  5014.7  286.89  5016.8  291.65  5045.2  298.30  5058.0  299.53  5065.8  301.93
  5099.3  306.97  5107.0  309.70  5158.5  319.52  5176.6  322.55  5199.8  324.27
#Mann=4,-1,0
  4521.9    0.16       0  4807.6    0.12       0  5008.7    0.07       0
  5014.7    0.12       0
Bank Sta=5008.7,5014.7
Exp/Cntr=0.3,0.1

Type RM Length L Ch R = 1,4276,478,478,478
BEGIN DESCRIPTION:
UNT 107 IN CACR 5.0
END DESCRIPTION:
XS GIS Cut Line= 2
      3677943.64     10713290.21      3677336.06     10712491.68
#Sta/Elev= 30
  4515.1  339.15  4525.7  339.14  4546.5  335.86  4590.2  334.16  4596.4  332.50
  4625.5  331.81  4646.3  328.35  4667.2  327.97  4710.8  322.37  4725.3  319.12
  4775.2  315.46  4816.9  307.92  4860.5  303.13  4889.6  297.92  4895.9  298.34
  4924.9  292.75  4967.5  289.10  4978.1  282.55  4980.9  282.05  4984.1  282.55
  5010.2  287.39  5218.1  294.18  5288.8  301.81  5309.6  302.42  5338.7  306.02
  5359.5  306.18  5459.3  315.02  5467.6  316.84  5473.9  316.27  5518.5  322.63
#Mann=3,-1,0
  4515.1    0.12       0  4978.1    0.07       0  4984.1    0.12       0
Bank Sta=4978.1,4984.1
Exp/Cntr=0.3,0.1

Type RM Length L Ch R = 1,3798,851,851,851
BEGIN DESCRIPTION:
UNT 107 IN CACR 4.0
END DESCRIPTION:
XS GIS Cut Line= 2
      3678342.98     10713151.37      3677648.52     10712040.24
#Sta/Elev= 30
  4360.2  347.95  4493.2  330.10  4576.2  321.28  4597.5  318.46  4816.5  299.71
  4864.7  294.88  4907.1  288.84  4928.3  288.50  4964.9  283.70  4974.3  284.20
  4998.5  281.76  5001.2  281.26  5004.5  281.76  5053.3  288.54  5059.2  287.64
  5104.5  291.28  5378.8  321.11  5451.9  324.89  5488.5  322.95  5494.4  325.20
  5503.8  324.43  5540.4  326.09  5546.3  327.67  5561.6  327.64  5567.5  329.72
  5598.2  330.32  5604.1  331.83  5619.4  331.60  5625.3  333.57  5670.5  335.01
#Mann=6,-1,0
  4360.2    0.16       0  4576.2    0.12       0  4597.5    0.16       0
  4816.5    0.12       0  4998.5    0.07       0  5004.5    0.12       0
Bank Sta=4998.5,5004.5
Exp/Cntr=0.3,0.1

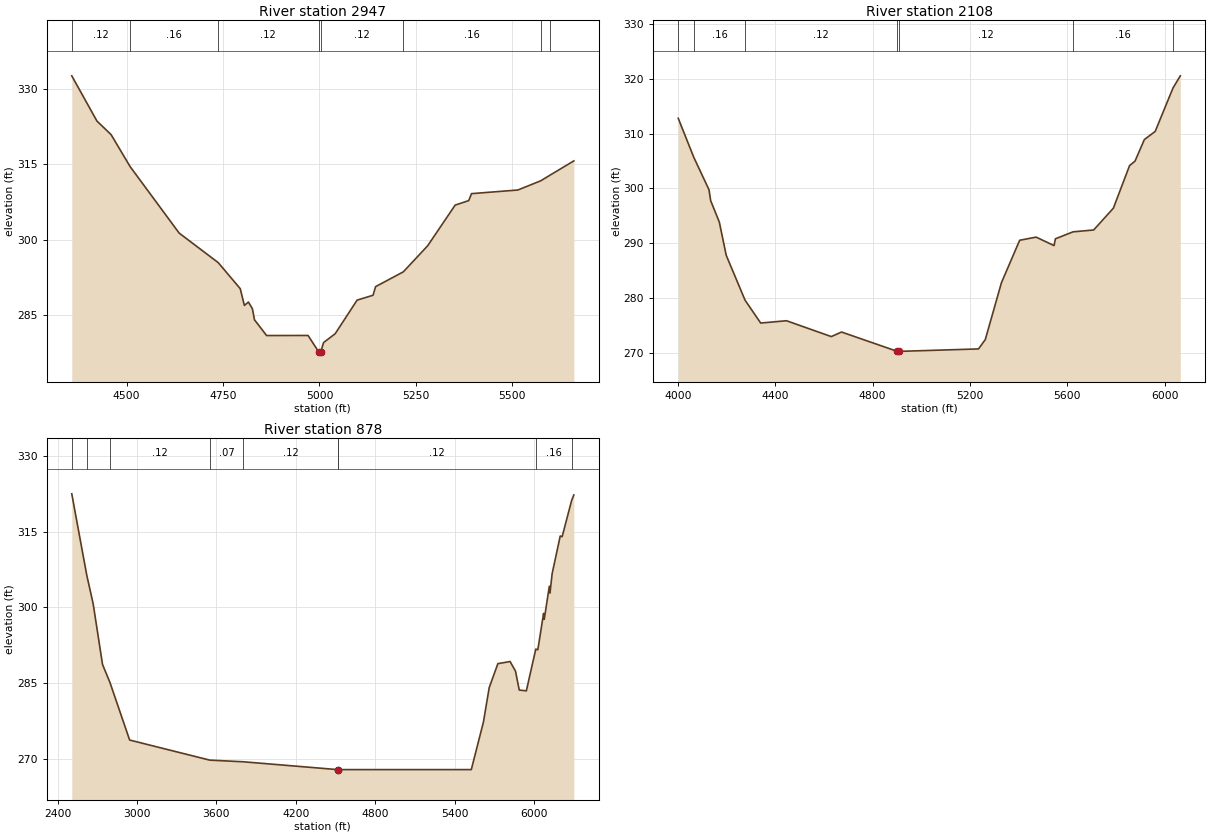
Type RM Length L Ch R = 1,2947,839,839,839
BEGIN DESCRIPTION:
UNT 107 IN CACR 3.0
END DESCRIPTION:
XS GIS Cut Line= 4
      3678542.62     10713003.82      3678716.24     10712491.64
      3678733.60     10712291.98      3678308.27     10711927.42
#Sta/Elev= 30
  4357.9  332.62  4423.1  323.63  4459.8  320.93  4509.4  314.54  4636.3  301.34
  4737.5  295.47  4794.6  290.29  4805.3  286.95  4815.8  287.63  4826.2  286.28
  4831.5  284.10  4862.9  280.97  4970.4  280.98  4997.5  277.77  5000.3  277.27
  5003.5  277.77  5010.6  279.57  5040.7  281.33  5097.5  288.01  5138.8  288.98
  5145.4  290.69  5217.4  293.64  5280.4  298.82  5351.7  306.91  5386.8  307.80
  5394.1  309.19  5514.2  309.91  5573.5  311.74  5598.6  312.91  5659.3  315.70
#Mann=8,-1,0
  4357.9    0.12       0  4509.4    0.16       0  4737.5    0.12       0
  4997.5    0.07       0  5003.5    0.12       0  5217.4    0.16       0
  5573.5    0.05       0  5598.6    0.12       0
Bank Sta=4997.5,5003.5
Exp/Cntr=0.3,0.1

Type RM Length L Ch R = 1,2108,1230,1230,1230
BEGIN DESCRIPTION:
UNT 107 IN CACR 2.0
END DESCRIPTION:
XS GIS Cut Line= 4
      3678803.06     10712882.24      3679462.77     10712257.26
      3679306.52     10712092.33      3678483.21     10711667.68
#Sta/Elev= 30
  4001.6  312.80  4065.2  305.71  4127.9  299.77  4134.8  297.78  4170.4  293.86
  4198.7  287.81  4276.2  279.61  4340.3  275.45  4446.3  275.87  4630.3  272.98
  4672.4  273.81  4901.7  270.28  4904.5  269.78  4907.7  270.28  5235.0  270.73
  5262.8  272.43  5329.3  282.82  5404.1  290.55  5471.6  291.12  5545.3  289.58
  5550.9  290.82  5623.7  292.09  5707.9  292.42  5789.0  296.40  5855.5  304.17
  5877.7  304.97  5916.3  308.92  5960.7  310.40  6033.8  318.31  6063.9  320.54
#Mann=7,-1,0
  4001.6    0.12       0  4065.2    0.16       0  4276.2    0.12       0
  4901.7    0.07       0  4907.7    0.12       0  5623.7    0.16       0
  6033.8    0.12       0
Bank Sta=4901.7,4907.7
Exp/Cntr=0.3,0.1

Type RM Length L Ch R = 1,878,0,0,0
BEGIN DESCRIPTION:
UNT 107 IN CACR 1.0
END DESCRIPTION:
XS GIS Cut Line= 4
      3678889.82     10712969.10      3680217.97     10711658.30
      3679740.54     10711206.92      3678499.23     10711484.69
#Sta/Elev= 30
  2506.7  322.49  2620.2  306.35  2668.4  300.70  2739.1  288.68  2795.4  285.09
  2944.2  273.69  3549.4  269.71  3803.2  269.38  4515.9  267.83  4518.7  267.33
  4521.9  267.83  5526.7  267.83  5618.6  277.28  5662.0  284.07  5727.6  288.83
  5819.8  289.25  5860.8  287.35  5889.2  283.60  5942.8  283.44  6014.0  291.71
  6029.6  291.58  6073.0  298.78  6078.1  297.62  6116.4  304.17  6121.5  302.82
  6137.5  306.63  6198.9  314.13  6213.4  314.00  6284.7  321.14  6301.8  322.26
#Mann=9,-1,0
  2506.7    0.12       0  2620.2    0.16       0  2795.4    0.12       0
  3549.4    0.07       0  3803.2    0.12       0  4515.9    0.07       0
  4521.9    0.12       0  6014.0    0.16       0  6284.7    0.12       0
Bank Sta=4515.9,4521.9
Exp/Cntr=0.3,0.1

Chan Stop Cuts=-1