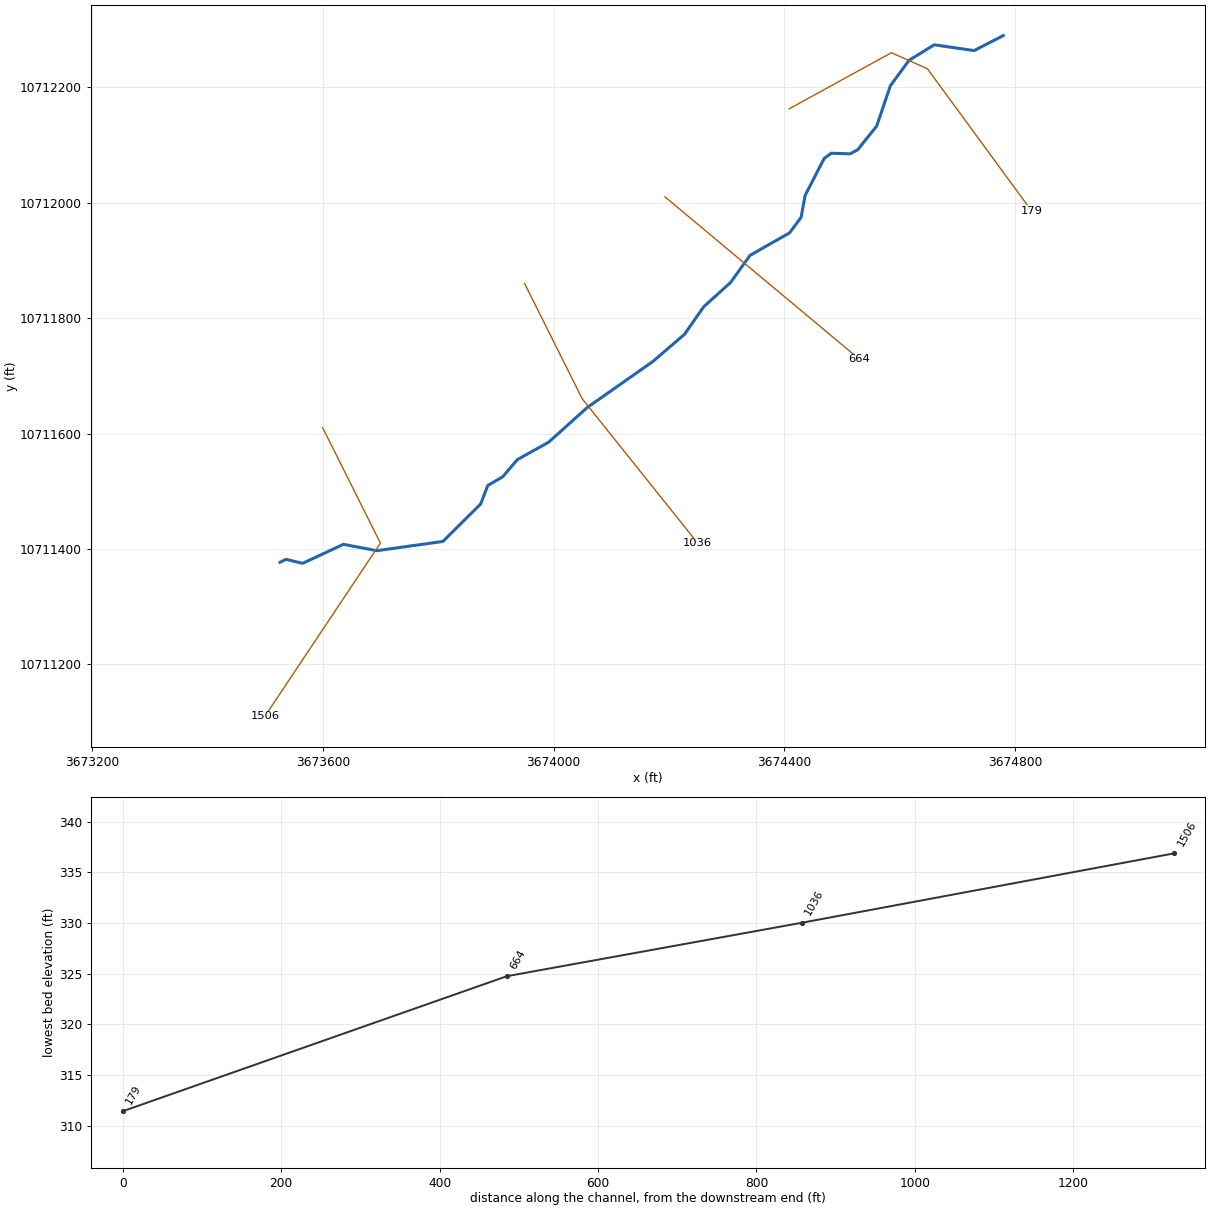
--- UNT 108 IN CACR.prj (project) ---

Proj Title=UNT 108 IN CACR Base Level Engineering
Current Plan=p01
Default Exp/Contr=0.3,0.1
English Units
Geom File=g01
Flow File=f01
Plan File=p01
Y Axis Title=Elevation
X Axis Title(PF)=Main Channel Distance
X Axis Title(XS)=Station
BEGIN DESCRIPTION:
UNT 108 IN CACR
END DESCRIPTION:
DSS Export Rating Curves= 0
DSS Export Rating Curve Sorted= 0
DSS Export Volume Flow Curves= 0
DXF OffsetX= 0
DXF OffsetY= 0
DXF ScaleX= 1
DXF ScaleY= 10

--- UNT 108 IN CACR.p01 (plan) ---

Plan Title=Multiple Run
Short Identifier=Multiple
Geom File=g01
Flow File=f01
Subcritical Flow
K Sum by GR= 0
Std Step Tol= 0.01
Critical Tol= 0.01
Num of Std Step Trials= 20
Max Error Tol= 0.3
Flow Tol Ratio= 0.001
Split Flow NTrial= 30
Split Flow Tol= 0.02
Split Flow Ratio= 0.02
Log Output Level= 0
Friction Slope Method= 1
Unsteady Friction Slope Method= 2
Unsteady Bridges Friction Slope Method= 1
Parabolic Critical Depth
Global Vel Dist=  1 , 1 , 1
Global Log Level= 0
CheckData=True
Encroach Param= -1, 0, 0, 0
BEGIN DESCRIPTION:
Multiple Run
END DESCRIPTION:

--- UNT 108 IN CACR.f01 (steady flow) ---

Flow Title=Multiple
Program Version=4.10
Number of Profiles= 7
Profile Names=10-year,25-year,50-year,1pct_min,100-year,1pct_plu,500-year
River Rch & RM=UNT 108 IN CACR,Reach-1         ,1506
     337     449     539     478     646     873     930
Boundary for River Rch & Prof#=UNT 108 IN CACR,Reach-1         , 1
Up Type= 0
Dn Type= 3
Dn Slope=0.02753
Boundary for River Rch & Prof#=UNT 108 IN CACR,Reach-1         , 2
Up Type= 0
Dn Type= 3
Dn Slope=0.02753
Boundary for River Rch & Prof#=UNT 108 IN CACR,Reach-1         , 3
Up Type= 0
Dn Type= 3
Dn Slope=0.02753
Boundary for River Rch & Prof#=UNT 108 IN CACR,Reach-1         , 4
Up Type= 0
Dn Type= 3
Dn Slope=0.02753
Boundary for River Rch & Prof#=UNT 108 IN CACR,Reach-1         , 5
Up Type= 0
Dn Type= 3
Dn Slope=0.02753
Boundary for River Rch & Prof#=UNT 108 IN CACR,Reach-1         , 6
Up Type= 0
Dn Type= 3
Dn Slope=0.02753
Boundary for River Rch & Prof#=UNT 108 IN CACR,Reach-1         , 7
Up Type= 0
Dn Type= 3
Dn Slope=0.02753
DSS Import GetInterval= 0
DSS Import GetPeak= 0
DSS Import FillOption= 0

--- UNT 108 IN CACR.g01 (geometry) ---

Geom Title=Existing Conditions
Program Version=4.10

River Reach=UNT 108 IN CACR ,Reach-1
Reach XY= 30
      3673525.68     10711376.94      3673536.25       10711382.
      3673564.75       10711375.       3673635.5       10711408.
       3673693.5       10711397.        3673808.       10711413.
       3673873.5       10711478.      3673885.75       10711510.
       3673911.5       10711525.      3673937.25       10711555.
      3673991.25       10711585.        3674058.       10711645.
        3674172.       10711725.      3674226.75       10711772.
      3674260.25       10711820.      3674306.75       10711862.
       3674340.5       10711909.        3674409.       10711948.
        3674429.       10711975.        3674436.       10712013.
        3674469.       10712077.      3674481.25       10712086.
        3674514.       10712085.        3674527.       10712092.
        3674560.       10712133.      3674583.75       10712203.
        3674616.       10712247.      3674659.75       10712274.
        3674729.       10712264.       3674779.5       10712290.

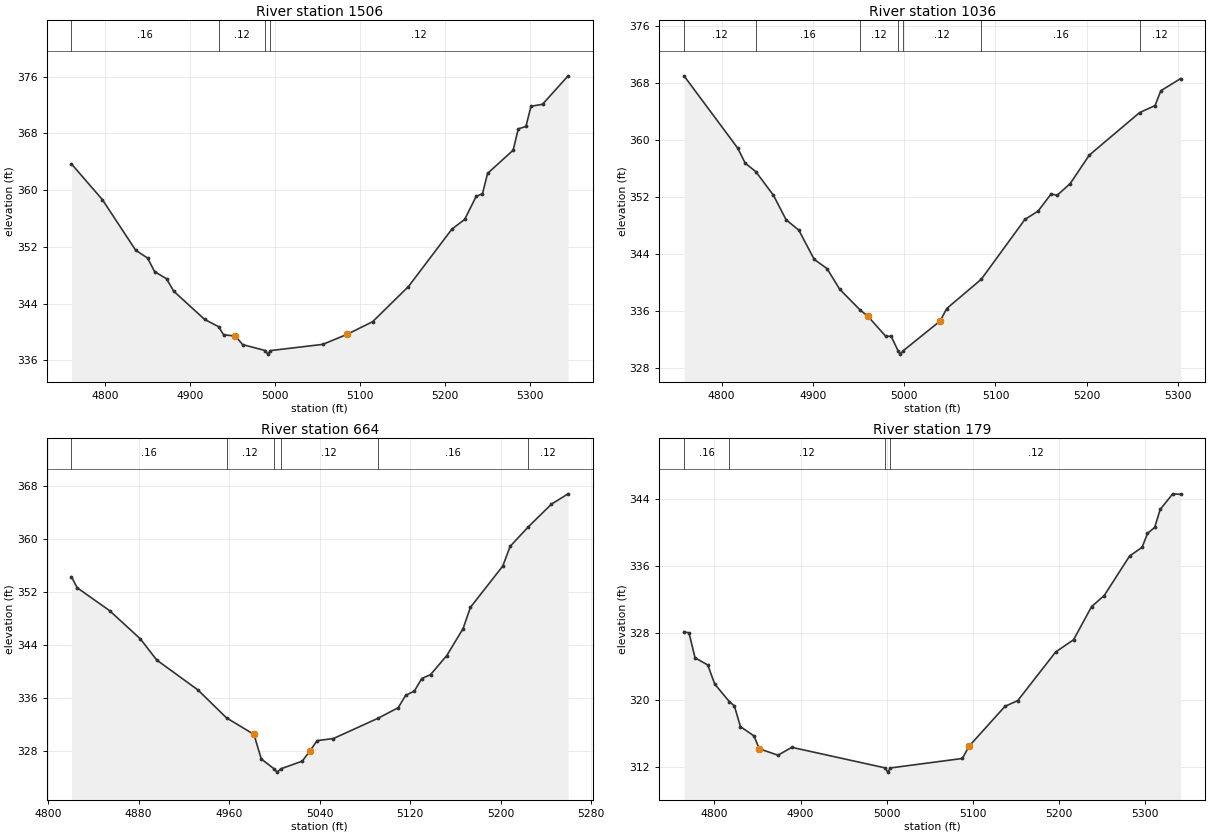
Type RM Length L Ch R = 1 ,1506    ,470,470,470
BEGIN DESCRIPTION:
UNT 108 IN CACR 3.0
END DESCRIPTION:
XS GIS Cut Line= 3
       3673599.6      10711610.2      3673699.61     10711410.19
       3673499.6     10711110.17
#Sta/Elev= 30
  4760.8   363.7  4797.1  358.67  4836.3  351.53  4850.3  350.42  4858.6   348.5
  4872.6   347.5    4881  345.75  4917.3  341.77  4933.9  340.73  4939.7   339.6
  4953.7   339.4  4962.1  338.21  4988.9  337.36  4991.7  336.86  4994.9  337.36
  5056.5  338.24  5085.1  339.66  5115.1  341.44  5157.2   346.4  5208.3   354.5
  5223.3  355.87  5236.8  359.11  5244.3  359.51  5250.3  362.37  5280.4  365.65
  5286.4  368.65  5295.4     369  5301.4  371.85  5314.9  372.12    5345  376.14
#Mann= 4 ,-1 , 0
  4760.8     .16       0  4933.9     .12       0  4988.9     .07       0
  4994.9     .12       0
Bank Sta=4953.7,5085.1
XS Rating Curve= 0 ,0
Exp/Cntr=0.3,0.1

Type RM Length L Ch R = 1 ,1036    ,372,372,372
BEGIN DESCRIPTION:
UNT 108 IN CACR 2.0
END DESCRIPTION:
XS GIS Cut Line= 3
      3673949.59     10711860.23      3674049.61     10711660.19
       3674249.6     10711410.19
#Sta/Elev= 30
  4758.9  369.07  4817.6  358.95    4826   356.8  4837.5  355.63  4856.8  352.32
  4870.7  348.87  4884.7   347.4  4901.5  343.31  4915.5  342.02  4929.4  339.12
  4951.8   336.2  4960.2  335.34  4979.8  332.52  4985.8  332.52  4993.2  330.51
  4995.9  330.01  4999.2  330.51  5039.4  334.66  5046.6  336.41  5084.4  340.51
  5132.2  348.91  5146.6  350.08    5161   352.5  5167.4  352.29  5181.8  353.94
  5202.7  357.94  5257.9  363.92  5274.7  364.89  5281.1  366.98  5302.7  368.68
#Mann= 7 ,-1 , 0
  4758.9     .12       0  4837.5     .16       0  4951.8     .12       0
  4993.2     .09       0  4999.2     .12       0  5084.4     .16       0
  5257.9     .12       0
Bank Sta=4960.2,5039.4
XS Rating Curve= 0 ,0
Exp/Cntr=0.3,0.1

Type RM Length L Ch R = 1 ,664     ,485,485,485
BEGIN DESCRIPTION:
Mapping XS 7171cb66
END DESCRIPTION:
XS GIS Cut Line= 2
      3674193.09      10712010.3       3674529.9     10711729.05
#Sta/Elev= 30
  4820.7  354.24  4825.7  352.58  4854.3  349.13  4881.6  344.85    4896  341.67
  4932.4  337.15  4957.7  332.93  4981.9  330.44  4988.4  326.73  4999.7  325.24
  5002.4  324.74  5005.7  325.24  5024.6   326.4  5031.3  327.93  5037.8   329.5
  5052.1  329.81  5091.4  332.86  5109.4  334.47  5115.9  336.32  5123.7  336.99
  5130.2  338.87    5138  339.47  5152.3  342.34  5166.7  346.41  5173.2  349.62
  5201.8  355.86  5208.3  358.83  5224.2  361.75  5244.7  365.19  5259.5  366.76
#Mann= 6 ,-1 , 0
  4820.7     .16       0  4957.7     .12       0  4999.7     .09       0
  5005.7     .12       0  5091.4     .16       0  5224.2     .12       0
Bank Sta=4981.9,5031.3
XS Rating Curve= 0 ,0
Exp/Cntr=0.3,0.1

Type RM Length L Ch R = 1 ,179     ,0,0,0
BEGIN DESCRIPTION:
UNT 108 IN CACR 1.0
END DESCRIPTION:
XS GIS Cut Line= 4
       3674408.4     10712163.05      3674585.49     10712260.27
      3674647.99     10712232.49      3674828.55     10711985.96
#Sta/Elev= 30
  4764.8  328.17  4770.6  328.02  4777.6  325.06  4792.4  324.19  4800.4  321.93
  4817.5  319.81  4823.2  319.32  4830.3  316.84    4846  315.73  4852.1   314.2
  4873.8  313.43  4889.9  314.37  4998.3  311.91  5001.1  311.41  5004.3  311.91
  5087.7  313.04  5095.5  314.51  5137.2  319.27  5151.9  319.94  5195.9  325.75
  5216.7  327.21  5237.6  331.17  5252.2  332.48  5281.6  337.19  5296.2  338.25
  5302.4  339.89  5310.8  340.62  5317.1  342.75  5331.7  344.62  5340.8  344.56
#Mann= 4 ,-1 , 0
  4764.8     .16       0  4817.5     .12       0  4998.3     .12       0
  5004.3     .12       0
Bank Sta=4852.1,5095.5
XS Rating Curve= 0 ,0
Exp/Cntr=0.3,0.1

Chan Stop Cuts=-1
Use User Specified Reach Order=0
Composite Channel Slope=5