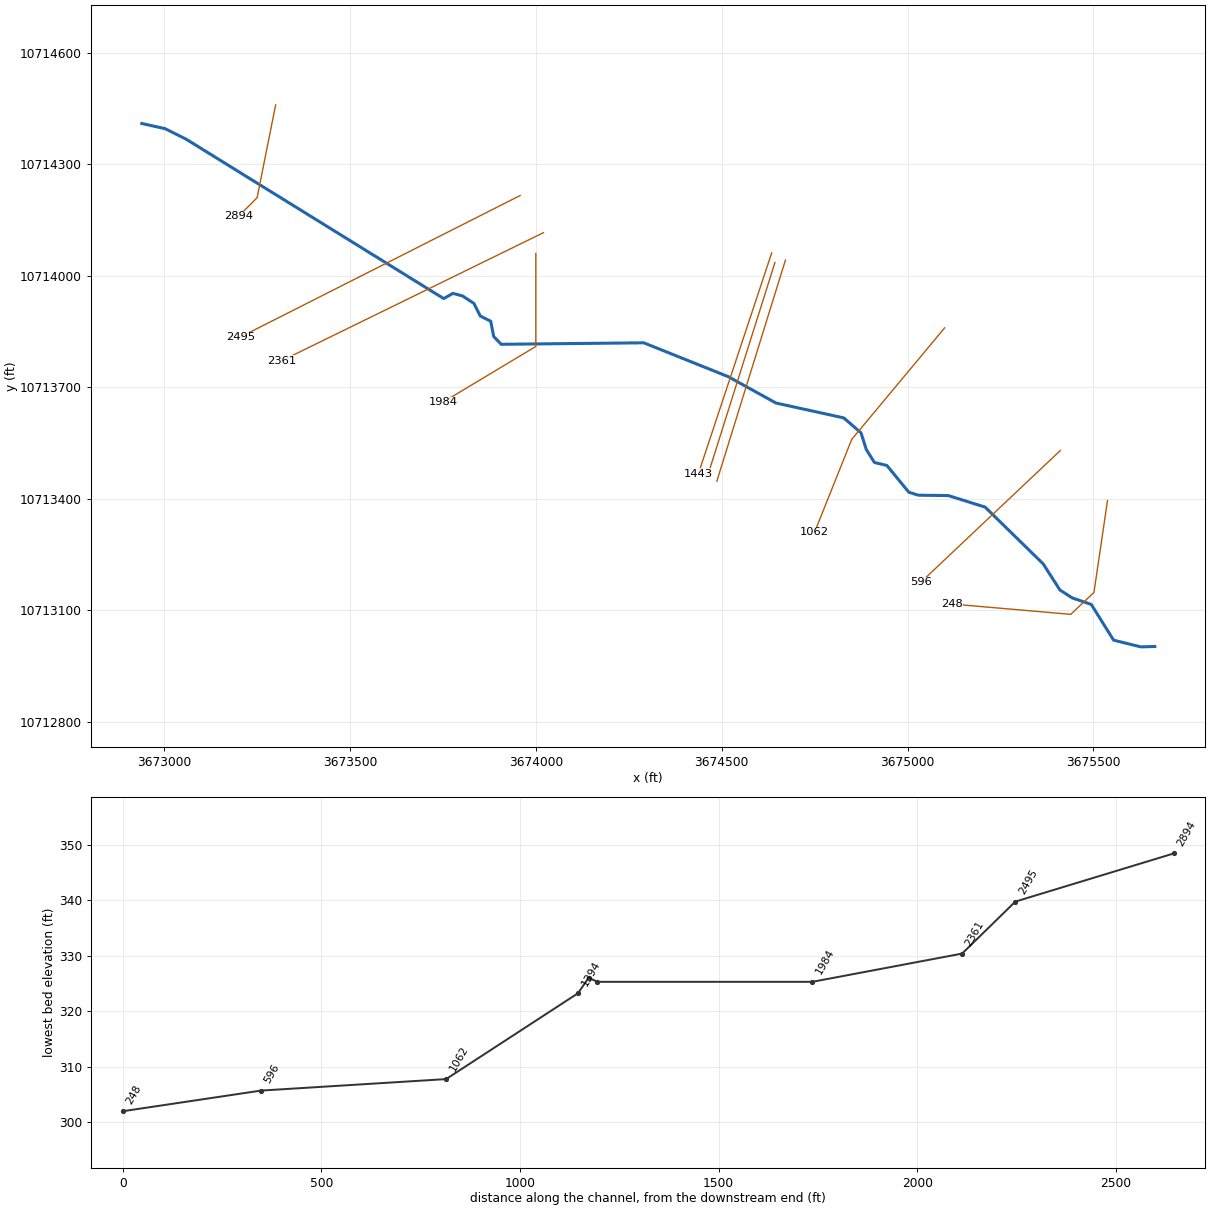
--- UNT 109 IN CACR.prj (project) ---

Proj Title=UNT 109 IN CACR Base Level Engineering
Current Plan=p01
Default Exp/Contr=0.3,0.1
English Units
Geom File=g01
Flow File=f01
Plan File=p01
Y Axis Title=Elevation
X Axis Title(PF)=Main Channel Distance
X Axis Title(XS)=Station
BEGIN DESCRIPTION:
UNT 109 IN CACR
END DESCRIPTION:
DSS Export Rating Curves= 0
DSS Export Rating Curve Sorted= 0
DSS Export Volume Flow Curves= 0
DXF OffsetX= 0
DXF OffsetY= 0
DXF ScaleX= 1
DXF ScaleY= 10

--- UNT 109 IN CACR.p01 (plan) ---

Plan Title=Multiple Run
Short Identifier=Multiple
Geom File=g01
Flow File=f01
Subcritical Flow
K Sum by GR= 0
Std Step Tol= 0.01
Critical Tol= 0.01
Num of Std Step Trials= 20
Max Error Tol= 0.3
Flow Tol Ratio= 0.001
Split Flow NTrial= 30
Split Flow Tol= 0.02
Split Flow Ratio= 0.02
Log Output Level= 0
Friction Slope Method= 1
Unsteady Friction Slope Method= 2
Unsteady Bridges Friction Slope Method= 1
Parabolic Critical Depth
Global Vel Dist=  1 , 1 , 1
Global Log Level= 0
CheckData=True
Encroach Param= -1, 0, 0, 0
BEGIN DESCRIPTION:
Multiple Run
END DESCRIPTION:

--- UNT 109 IN CACR.f01 (steady flow) ---

Flow Title=Multiple
Program Version=4.10
Number of Profiles= 7
Profile Names=10-year,25-year,50-year,1pct_min,100-year,1pct_plu,500-year
River Rch & RM=UNT 109 IN CACR,Reach-1         ,2894
     522     716     877     792    1071    1448    1601
River Rch & RM=UNT 109 IN CACR,Reach-1         ,248
    1074    1670    2099    1936    2618    3540    4092
Boundary for River Rch & Prof#=UNT 109 IN CACR,Reach-1         , 1
Up Type= 0
Dn Type= 3
Dn Slope=0.01065
Boundary for River Rch & Prof#=UNT 109 IN CACR,Reach-1         , 2
Up Type= 0
Dn Type= 3
Dn Slope=0.01065
Boundary for River Rch & Prof#=UNT 109 IN CACR,Reach-1         , 3
Up Type= 0
Dn Type= 3
Dn Slope=0.01065
Boundary for River Rch & Prof#=UNT 109 IN CACR,Reach-1         , 4
Up Type= 0
Dn Type= 3
Dn Slope=0.01065
Boundary for River Rch & Prof#=UNT 109 IN CACR,Reach-1         , 5
Up Type= 0
Dn Type= 3
Dn Slope=0.01065
Boundary for River Rch & Prof#=UNT 109 IN CACR,Reach-1         , 6
Up Type= 0
Dn Type= 3
Dn Slope=0.01065
Boundary for River Rch & Prof#=UNT 109 IN CACR,Reach-1         , 7
Up Type= 0
Dn Type= 3
Dn Slope=0.01065
DSS Import GetInterval= 0
DSS Import GetPeak= 0
DSS Import FillOption= 0

--- UNT 109 IN CACR.g01 (geometry) ---

Geom Title=Existing Conditions
Program Version=4.10

River Reach=UNT 109 IN CACR ,Reach-1
Reach XY= 30
       3672939.5       10714410.       3673002.5       10714396.
       3673058.5       10714368.      3673751.75       10713939.
       3673776.5       10713953.       3673802.5       10713946.
        3673833.       10713926.      3673850.25       10713892.
      3673878.25       10713878.      3673886.25       10713837.
       3673906.5       10713816.        3674290.       10713820.
      3674517.25       10713729.      3674645.75       10713658.
        3674828.       10713618.       3674874.5       10713578.
      3674888.75       10713533.      3674910.75       10713498.
      3674944.25       10713490.      3675003.25       10713418.
      3675028.75       10713410.       3675109.5       10713409.
       3675208.5       10713378.        3675365.       10713225.
      3675409.75       10713155.      3675442.25       10713134.
      3675494.25       10713116.      3675554.25       10713020.
      3675627.25       10713002.        3675665.       10713003.

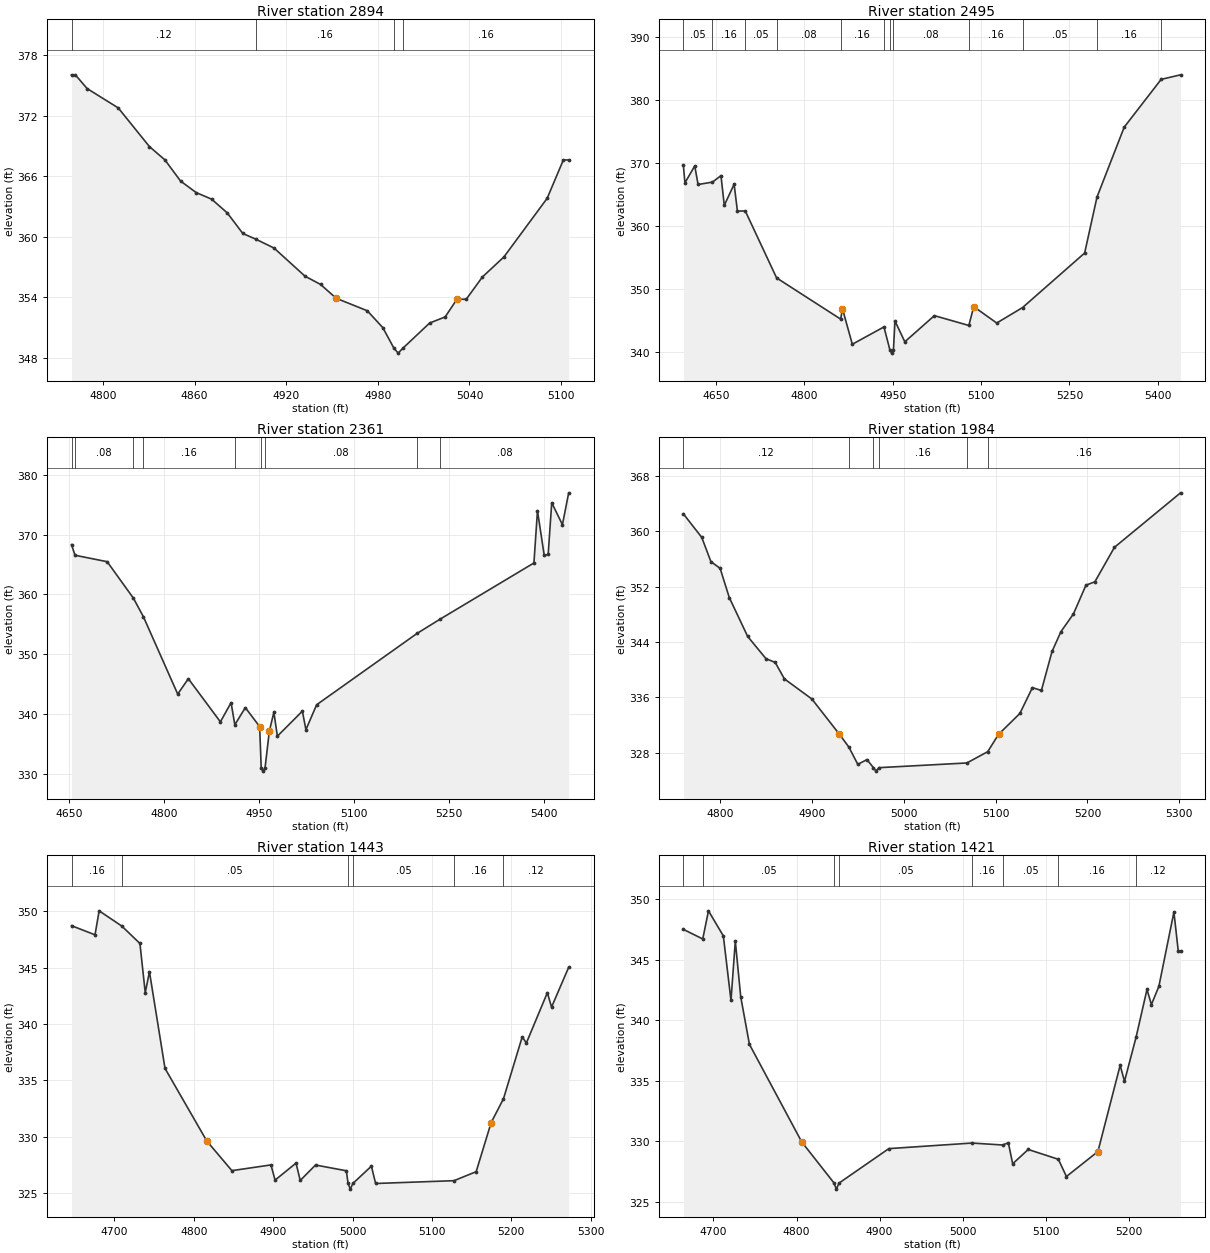
Type RM Length L Ch R = 1 ,2894    ,399,399,399
BEGIN DESCRIPTION:
UNT 109 IN CACR 6.0
END DESCRIPTION:
XS GIS Cut Line= 3
       3673299.6     10714460.17      3673249.61     10714210.19
      3673199.64     10714160.22
#Sta/Elev= 30
  4779.4  376.06  4781.9  376.06  4789.6   374.7    4810  372.78  4830.4  368.95
  4840.6  367.62  4850.8  365.53    4861  364.39  4871.2  363.73  4881.4  362.37
  4891.6  360.33  4899.9  359.78    4912  358.89  4932.3   356.1  4942.5  355.28
  4952.7  353.91  4973.1  352.67  4983.3  350.99  4990.5  348.97  4993.3  348.47
  4996.5  348.97  5013.9  351.45  5024.1  352.06  5031.8  353.81  5037.9  353.81
  5048.5  356.02  5062.6  358.01  5090.9  363.82  5101.5  367.62    5105  367.62
#Mann= 4 ,-1 , 0
  4779.4     .12       0  4899.9     .16       0  4990.5     .07       0
  4996.5     .16       0
Bank Sta=4952.7,5031.8
XS Rating Curve= 0 ,0
Exp/Cntr=0.3,0.1

Type RM Length L Ch R = 1 ,2495    ,134,134,134
BEGIN DESCRIPTION:
UNT 109 IN CACR 5.0
END DESCRIPTION:
XS GIS Cut Line= 2
      3673957.29     10714216.16      3673204.31     10713835.34
#Sta/Elev= 30
  4594.8  369.59  4597.4  366.82  4614.1  369.51  4619.7  366.56  4644.2  366.94
  4658.6  367.97  4664.2  363.25  4680.9   366.6  4686.5  362.35  4699.9  362.35
    4753  351.73  4861.7  345.19  4864.8  346.83  4881.5   341.2  4935.2  343.95
  4945.3  340.29  4948.1  339.79  4951.3  340.29  4953.9  344.89  4970.6  341.59
  5020.8  345.74  5079.3  344.18  5087.6  347.17  5126.6  344.57  5170.4  347.02
  5275.8  355.68  5296.8  364.57    5343  375.67  5405.7  383.25  5438.6  383.97
#Mann= 12 ,-1 , 0
  4594.8     .05       0  4644.2     .16       0  4699.9     .05       0
    4753     .08       0  4861.7     .16       0  4935.2     .08       0
  4945.3     .07       0  4951.3     .08       0  5079.3     .16       0
  5170.4     .05       0  5296.8     .16       0  5405.7     .08       0
Bank Sta=4864.8,5087.6
XS Rating Curve= 0 ,0
Exp/Cntr=0.3,0.1

Type RM Length L Ch R = 1 ,2361    ,377,377,377
BEGIN DESCRIPTION:
Mapping XS b86b154b
END DESCRIPTION:
XS GIS Cut Line= 2
      3674020.23     10714116.33      3673314.91     10713771.27
#Sta/Elev= 30
  4654.3  368.34  4659.8  366.56  4710.6  365.48    4752  359.38  4767.9  356.25
    4822  343.32  4838.8  345.89  4889.4  338.67  4906.3  341.88  4912.2  338.18
  4928.8  341.05  4951.4  337.88  4953.9  330.92  4956.7  330.42  4959.9  330.92
  4966.7  337.11  4973.9  340.27  4979.4  336.27  5018.9  340.46  5024.5  337.36
  5041.4  341.53  5200.4   353.5  5236.7  355.88  5384.6  365.27  5390.2     374
  5400.9  366.52  5407.1   366.7  5412.7  375.35  5429.6  371.68  5439.5  377.01
#Mann= 9 ,-1 , 0
  4654.3     .16       0  4659.8     .08       0    4752     .12       0
  4767.9     .16       0  4912.2     .08       0  4953.9     .07       0
  4959.9     .08       0  5200.4     .05       0  5236.7     .08       0
Bank Sta=4951.4,4966.7
XS Rating Curve= 0 ,0
Exp/Cntr=0.3,0.1

Type RM Length L Ch R = 1 ,1984    ,541,541,541
BEGIN DESCRIPTION:
UNT 109 IN CACR 4.0
END DESCRIPTION:
XS GIS Cut Line= 3
      3673999.61      10714060.2      3673999.61     10713810.19
      3673749.57     10713660.17
#Sta/Elev= 30
  4759.8  362.55  4779.8  359.14  4789.8  355.63  4799.8  354.67  4809.8  350.44
  4829.8  344.82  4849.8  341.59  4859.8  341.06  4869.8  338.68  4899.8  335.76
  4929.8  330.66  4940.1   328.8  4949.8  326.31  4959.8     327  4966.8  325.83
  4969.6  325.33  4972.8  325.83  5068.6  326.51  5091.3  328.14  5103.1  330.64
  5126.4  333.68    5140  337.41  5149.8     337  5161.4  342.64  5171.1  345.51
  5184.7  348.07  5198.3  352.22  5208.1  352.73  5229.4  357.71  5301.4  365.59
#Mann= 6 ,-1 , 0
  4759.8     .12       0  4940.1     .16       0  4966.8     .07       0
  4972.8     .16       0  5068.6     .12       0  5091.3     .16       0
Bank Sta=4929.8,5103.1
XS Rating Curve= 0 ,0
Exp/Cntr=0.3,0.1

Type RM Length L Ch R = 1 ,1443    ,22,22,22
BEGIN DESCRIPTION:
UNT 109 IN CACR 3.0
END DESCRIPTION:
XS GIS Cut Line= 2
      3674634.34     10714062.02      3674436.87     10713467.46
#Sta/Elev= 30
  4645.9  348.72  4675.5  347.91  4680.7  350.04  4709.2  348.69  4732.1  347.14
  4738.8  342.77  4744.1  344.63  4763.7  336.05  4816.4   329.6    4848  326.97
  4897.2  327.48  4902.4  326.13  4928.8  327.64  4934.1   326.1  4953.4  327.47
  4992.2  326.96  4994.4  325.83  4997.2  325.33  5000.4  325.83  5023.8  327.37
  5029.1  325.83  5127.9  326.08  5155.8  326.88  5174.7  331.24  5190.2  333.35
  5213.8  338.84  5219.1  338.31  5245.5  342.77  5250.8  341.49  5272.4  345.03
#Mann= 6 ,-1 , 0
  4645.9     .16       0  4709.2     .05       0  4994.4    .033       0
  5000.4     .05       0  5127.9     .16       0  5190.2     .12       0
Bank Sta=4816.4,5174.7
XS Rating Curve= 0 ,0
Exp/Cntr=0.3,0.1

Type RM Length L Ch R = 1 ,1421    ,27,27,27
BEGIN DESCRIPTION:
Mapping XS 94ef1a15
END DESCRIPTION:
XS GIS Cut Line= 2
      3674643.03     10714036.02      3674462.91     10713465.27
#Sta/Elev= 30
  4663.8  347.49  4687.1   346.7    4694  349.02  4711.9  346.95  4721.1  341.63
  4726.3  346.53  4732.8  341.94  4743.3  338.01  4806.2  329.97  4845.2  326.57
  4847.9  326.07  4851.2  326.57  4911.1  329.41  5011.2  329.87    5048  329.71
    5055  329.89  5060.2  328.16  5078.9  329.34  5115.2  328.53  5124.9  327.11
  5162.8  329.17  5189.6  336.28  5194.8  334.96  5208.8  338.61  5221.9  342.54
  5227.2  341.29  5236.2  342.79  5254.3  348.92  5259.5  345.72  5262.3  345.72
#Mann= 8 ,-1 , 0
  4663.8     .16       0  4687.1     .05       0  4845.2     .03       0
  4851.2     .05       0  5011.2     .16       0    5048     .05       0
  5115.2     .16       0  5208.8     .12       0
Bank Sta=4806.2,5162.8
XS Rating Curve= 0 ,0
Exp/Cntr=0.3,0.1

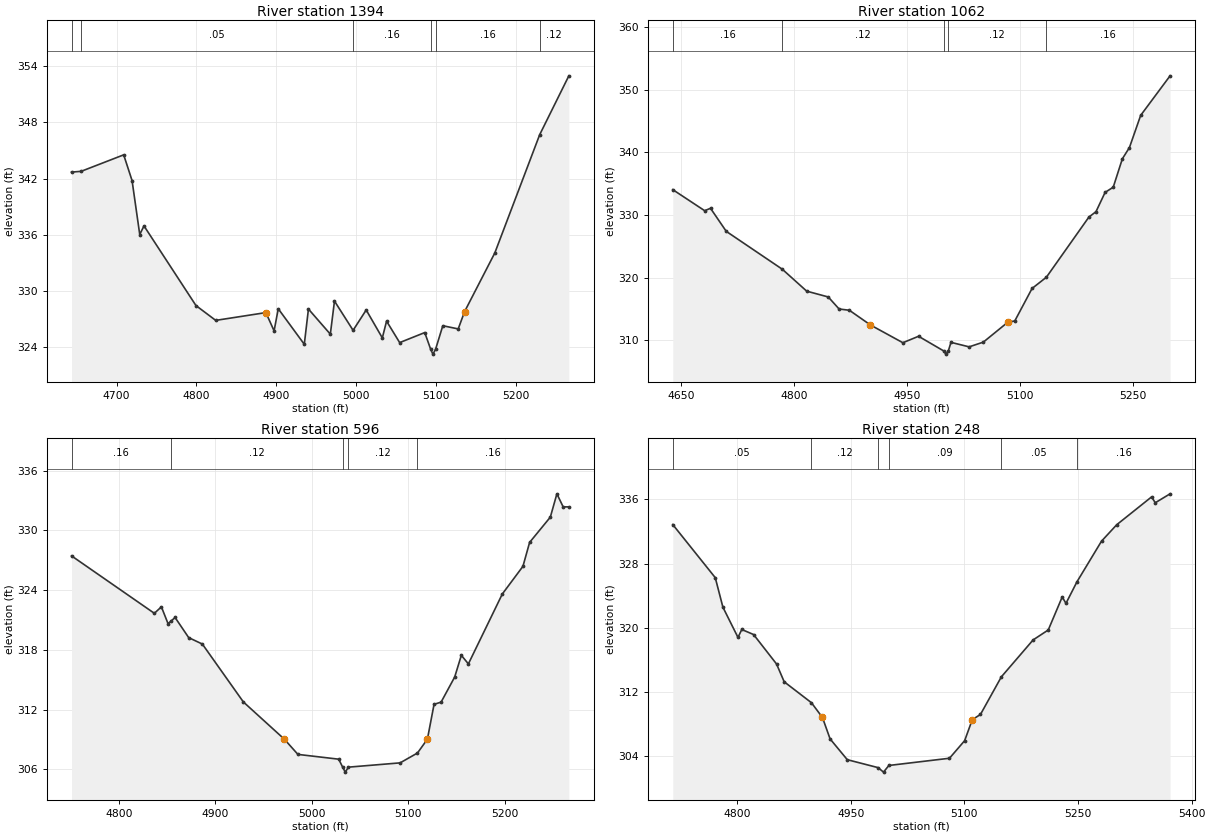
Type RM Length L Ch R = 1 ,1394    ,332,332,332
BEGIN DESCRIPTION:
Mapping XS a95f36bf
END DESCRIPTION:
XS GIS Cut Line= 2
      3674671.25     10714042.54      3674486.78      10713447.9
#Sta/Elev= 30
  4643.7  342.69  4655.7  342.77    4709  344.53  4719.5  341.78  4729.1  336.03
  4734.4  336.95  4799.5  328.45  4824.2  326.87    4887   327.7  4897.3  325.75
  4902.5  328.11  4935.1  324.32  4940.3  328.08  4967.7   325.4  4972.9  328.93
  4996.2  325.81  5012.6  327.98  5032.8     325  5038.1  326.79  5054.5   324.5
  5085.9  325.57  5093.4  323.77  5096.1  323.27  5099.4  323.77  5108.5   326.3
  5127.8  325.96  5135.8  327.81  5173.6  334.06  5229.8  346.68  5266.3  352.96
#Mann= 6 ,-1 , 0
  4643.7     .16       0  4655.7     .05       0  4996.2     .16       0
  5093.4     .07       0  5099.4     .16       0  5229.8     .12       0
Bank Sta=4887,5135.8
XS Rating Curve= 0 ,0
Exp/Cntr=0.3,0.1

Type RM Length L Ch R = 1 ,1062    ,466,466,466
BEGIN DESCRIPTION:
UNT 109 IN CACR 2.0
END DESCRIPTION:
XS GIS Cut Line= 3
      3675099.63     10713860.21      3674849.61     10713560.19
      3674749.61     10713310.19
#Sta/Elev= 30
  4639.2  334.05  4681.5  330.69  4689.3  331.07  4710.2  327.39  4784.6  321.34
  4816.9  317.85  4845.5  316.92  4859.9     315  4873.5   314.8  4901.5  312.45
  4944.5  309.62  4965.3  310.65  4998.8   308.3  5001.5   307.8  5004.8   308.3
  5008.3  309.68  5032.4  308.96  5051.3  309.72  5083.6  312.88    5093   313.1
  5115.9  318.28  5134.9  320.07  5191.3  329.67  5200.7  330.53  5212.8  333.61
  5223.6  334.44  5235.7  338.97  5245.1  340.77    5260   345.9    5299  352.21
#Mann= 5 ,-1 , 0
  4639.2     .16       0  4784.6     .12       0  4998.8     .07       0
  5004.8     .12       0  5134.9     .16       0
Bank Sta=4901.5,5083.6
XS Rating Curve= 0 ,0
Exp/Cntr=0.3,0.1

Type RM Length L Ch R = 1 ,596     ,348,348,348
BEGIN DESCRIPTION:
Mapping XS 11b33488
END DESCRIPTION:
XS GIS Cut Line= 2
      3675411.09     10713530.42       3675036.1     10713176.26
#Sta/Elev= 30
  4750.7  327.45  4836.6  321.68  4843.9  322.33  4850.8  320.64  4853.8  320.89
  4858.1  321.26  4872.2  319.24  4886.4  318.59  4928.9  312.78  4971.4  309.04
  4985.5  307.51  5027.8  307.03  5031.9  306.23  5034.6  305.73  5037.9  306.23
  5091.5  306.66  5109.5  307.65  5119.8  309.04  5126.7  312.54    5134  312.76
  5148.1  315.28    5155  317.46  5162.3   316.6  5197.5  323.62  5218.9   326.4
  5225.8   328.8  5247.3  331.34  5254.1  333.68  5260.6  332.37  5266.5  332.37
#Mann= 5 ,-1 , 0
  4750.7     .16       0  4853.8     .12       0  5031.9     .07       0
  5037.9     .12       0  5109.5     .16       0
Bank Sta=4971.4,5119.8
XS Rating Curve= 0 ,0
Exp/Cntr=0.3,0.1

Type RM Length L Ch R = 1 ,248     ,0,0,0
BEGIN DESCRIPTION:
UNT 109 IN CACR 1.0
END DESCRIPTION:
XS GIS Cut Line= 4
      3675537.85     10713395.71      3675501.39     10713148.49
      3675438.89     10713089.47      3675119.45     10713117.24
#Sta/Elev= 30
    4715  332.87  4771.1  326.25  4781.2  322.57  4801.1   318.8  4806.1  319.79
  4821.7  319.16    4852  315.49  4862.1  313.27  4898.1  310.66  4912.6  308.82
  4922.7  306.15  4945.4  303.56  4986.1  302.57  4993.2  302.01  5000.3  302.84
  5080.3  303.74  5100.3  305.93  5110.4  308.55  5121.2   309.2  5148.8  313.89
  5190.7  318.49  5210.7  319.73  5229.1  323.84  5234.1  323.05  5248.5  325.72
    5281   330.8  5301.1  332.85    5347  336.31    5352  335.59  5371.5   336.7
#Mann= 6 ,-1 , 0
    4715     .05       0  4898.1     .12       0  4986.1     .07       0
  5000.3     .09       0  5148.8     .05       0  5248.5     .16       0
Bank Sta=4912.6,5110.4
XS Rating Curve= 0 ,0
Exp/Cntr=0.3,0.1

Chan Stop Cuts=-1
Use User Specified Reach Order=0
Composite Channel Slope=5