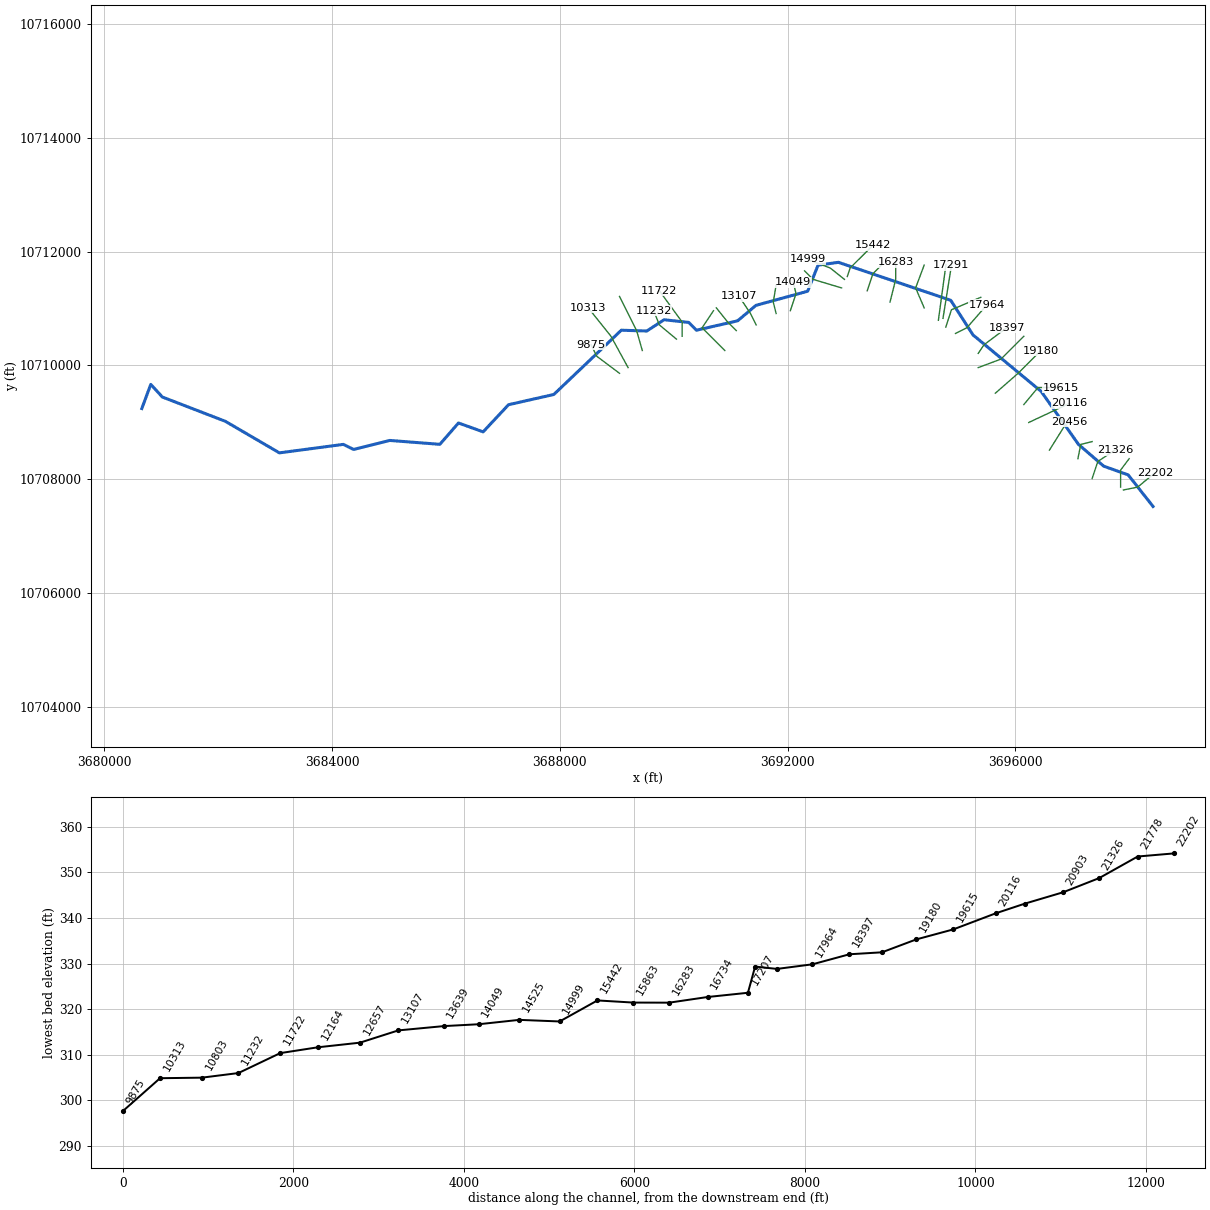
--- UNT 110 IN CACR.prj (project) ---

Proj Title=UNT 110 IN CACR Base Level Engineering
Current Plan=p01
Default Exp/Contr=0.3,0.1
English Units
Geom File=g01
Flow File=f01
Plan File=p01
Y Axis Title=Elevation
X Axis Title(PF)=Main Channel Distance
X Axis Title(XS)=Station
BEGIN DESCRIPTION:
UNT 110 IN CACR
END DESCRIPTION:
DSS Export Rating Curves= 0
DSS Export Rating Curve Sorted= 0
DSS Export Volume Flow Curves= 0
DXF OffsetX= 0
DXF OffsetY= 0
DXF ScaleX= 1
DXF ScaleY= 10

--- UNT 110 IN CACR.p01 (plan) ---

Plan Title=Multiple Run
Short Identifier=Multiple
Geom File=g01
Flow File=f01
Subcritical Flow
K Sum by GR= 0
Std Step Tol= 0.01
Critical Tol= 0.01
Num of Std Step Trials= 20
Max Error Tol= 0.3
Flow Tol Ratio= 0.001
Split Flow NTrial= 30
Split Flow Tol= 0.02
Split Flow Ratio= 0.02
Log Output Level= 0
Friction Slope Method= 1
Unsteady Friction Slope Method= 2
Unsteady Bridges Friction Slope Method= 1
Parabolic Critical Depth
Global Vel Dist=  1 , 1 , 1
Global Log Level= 0
CheckData=True
Encroach Param= -1, 0, 0, 0
BEGIN DESCRIPTION:
Multiple Run
END DESCRIPTION:

--- UNT 110 IN CACR.f01 (steady flow) ---

Flow Title=Multiple
Program Version=4.10
Number of Profiles= 7
Profile Names=10-year,25-year,50-year,1pct_min,100-year,1pct_plu,500-year
River Rch & RM=UNT 110 IN CACR,Reach-1         ,22202
     624     856    1050     947    1281    1732    1914
River Rch & RM=UNT 110 IN CACR,Reach-1         ,20456
     738    1022    1262    1145    1548    2093    2340
River Rch & RM=UNT 110 IN CACR,Reach-1         ,20116
     963    1353    1685    1542    2085    2820    3207
River Rch & RM=UNT 110 IN CACR,Reach-1         ,19180
    1248    1773    2226    2050    2772    3749    4321
River Rch & RM=UNT 110 IN CACR,Reach-1         ,17291
    1814    2613    3311    3072    4155    5619    6579
River Rch & RM=UNT 110 IN CACR,Reach-1         ,11722
    2007    2900    3682    3423    4629    6260    7356
River Rch & RM=UNT 110 IN CACR,Reach-1         ,9486
    2086    3013    3824    3553    4805    6498    7625
River Rch & RM=UNT 110 IN CACR,Reach-1         ,5529
    2331    3379    4301    4005    5416    7325    8635
River Rch & RM=UNT 110 IN CACR,Reach-1         ,3735
    2385    3455    4395    4090    5531    7480    8806
Boundary for River Rch & Prof#=UNT 110 IN CACR,Reach-1         , 1
Up Type= 0
Dn Type= 3
Dn Slope=0.00043
Boundary for River Rch & Prof#=UNT 110 IN CACR,Reach-1         , 2
Up Type= 0
Dn Type= 3
Dn Slope=0.00043
Boundary for River Rch & Prof#=UNT 110 IN CACR,Reach-1         , 3
Up Type= 0
Dn Type= 3
Dn Slope=0.00043
Boundary for River Rch & Prof#=UNT 110 IN CACR,Reach-1         , 4
Up Type= 0
Dn Type= 3
Dn Slope=0.00043
Boundary for River Rch & Prof#=UNT 110 IN CACR,Reach-1         , 5
Up Type= 0
Dn Type= 3
Dn Slope=0.00043
Boundary for River Rch & Prof#=UNT 110 IN CACR,Reach-1         , 6
Up Type= 0
Dn Type= 3
Dn Slope=0.00043
Boundary for River Rch & Prof#=UNT 110 IN CACR,Reach-1         , 7
Up Type= 0
Dn Type= 3
Dn Slope=0.00043
DSS Import GetInterval= 0
DSS Import GetPeak= 0
DSS Import FillOption= 0

--- UNT 110 IN CACR.g01 (geometry) ---

Geom Title=Existing Conditions
Program Version=4.10

River Reach=UNT 110 IN CACR ,Reach-1
Reach XY= 30
       3698419.5       10707520.       3697982.5       10708075.
       3697553.5       10708228.       3697110.5       10708610.
        3696454.       10709542.       3695257.5       10710534.
      3694866.25       10711143.      3692894.25       10711810.
      3692536.25       10711760.      3692353.75       10711302.
       3691445.5       10711054.      3691123.75       10710782.
      3690399.75       10710617.      3690265.25       10710754.
      3689832.75       10710801.       3689528.5       10710603.
        3689081.       10710617.        3687896.       10709488.
       3687100.5       10709308.        3686654.       10708831.
      3686221.25       10708987.        3685894.       10708612.
        3685015.       10708680.       3684378.5       10708522.
      3684199.75       10708611.      3683075.75       10708462.
        3682128.       10709016.      3681020.75       10709443.
      3680817.25       10709665.      3680659.75       10709241.

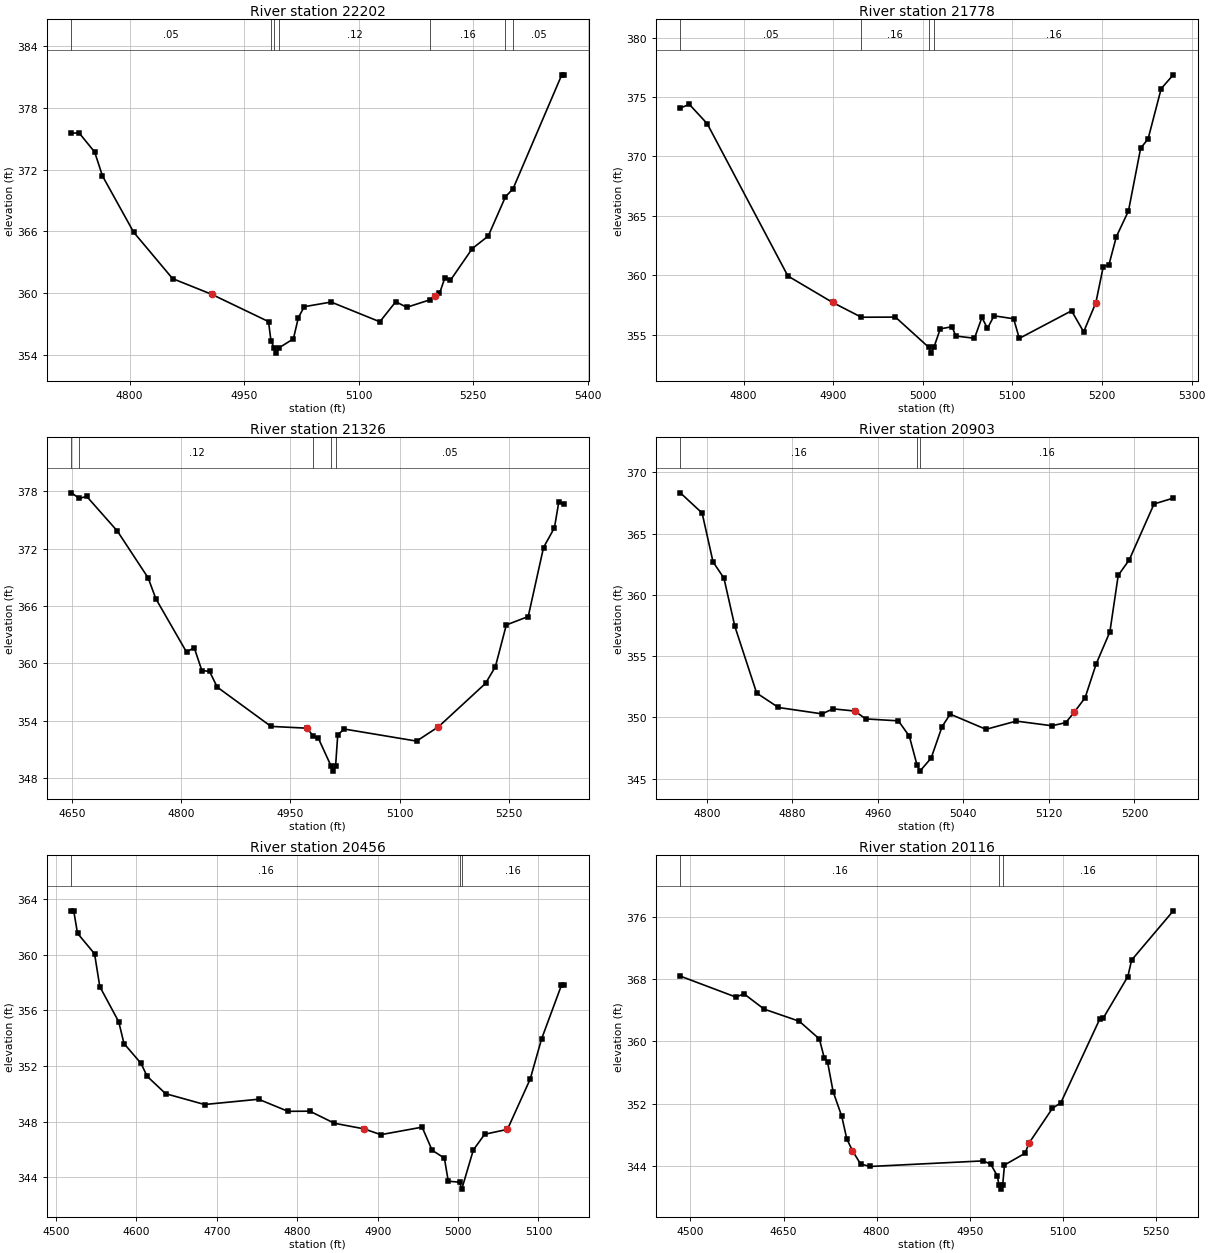
Type RM Length L Ch R = 1 ,22202   ,424,424,424
BEGIN DESCRIPTION:
UNT 110 IN CACR 49.0
END DESCRIPTION:
XS GIS Cut Line= 3
       3697899.6     10707810.19      3698149.61     10707860.19
      3698449.63     10708110.21
#Sta/Elev= 30
  4723.8  375.54    4734  375.57  4754.4   373.7  4764.6  371.38  4805.4  365.91
  4856.4  361.39  4907.4  359.87    4982  357.21  4985.2  355.36  4989.4  354.64
  4992.2  354.14  4995.4  354.64  5014.6  355.53  5021.1   357.6  5028.9  358.66
    5064  359.11  5127.8  357.19  5148.6  359.14    5163   358.6  5193.9  359.34
  5199.4  359.71  5205.9  359.95  5213.1  361.49  5220.2  361.23  5248.9  364.32
  5269.7  365.53  5292.2  369.34  5302.3  370.15    5366  381.22  5369.3  381.22
#Mann= 7 ,-1 , 0
  4723.8     .05       0  4985.2     .12       0  4989.4     .07       0
  4995.4     .12       0  5193.9     .16       0  5292.2     .12       0
  5302.3     .05       0
Bank Sta=4907.4,5199.4
XS Rating Curve= 0 ,0
Exp/Cntr=0.3,0.1

Type RM Length L Ch R = 1 ,21778   ,452,452,452
BEGIN DESCRIPTION:
UNT 110 IN CACR 48.0
END DESCRIPTION:
XS GIS Cut Line= 3
      3697849.61     10707860.16      3697849.61     10708160.19
      3697999.59     10708360.16
#Sta/Elev= 30
  4729.5  374.07  4739.5  374.39  4759.5  372.76  4849.5  359.95  4899.5  357.72
  4931.5  356.48  4969.5  356.49  5006.5  353.96  5009.3  353.46  5012.5  353.96
  5019.5   355.5  5032.7  355.68  5036.8   354.9  5057.7  354.71    5066  356.46
  5072.2  355.54  5079.5   356.6  5101.4  356.35  5107.7   354.7    5166  357.02
  5179.5  355.25  5193.1   357.7  5201.4  360.74  5207.7  360.89    5216  363.26
  5229.5  365.42  5243.1   370.7  5251.4  371.48    5266  375.71  5279.5  376.87
#Mann= 4 ,-1 , 0
  4729.5     .05       0  4931.5     .16       0  5006.5     .07       0
  5012.5     .16       0
Bank Sta=4899.5,5193.1
XS Rating Curve= 0 ,0
Exp/Cntr=0.3,0.1

Type RM Length L Ch R = 1 ,21326   ,423,423,423
BEGIN DESCRIPTION:
UNT 110 IN CACR 47.0
END DESCRIPTION:
XS GIS Cut Line= 3
      3697349.59     10708010.15      3697449.61     10708310.19
      3697749.59     10708510.17
#Sta/Elev= 30
  4649.1  377.84  4660.2  377.26  4670.2  377.47  4712.4  373.83  4754.6  368.94
  4765.1  366.77  4807.3  361.18  4817.8  361.65  4828.3  359.25  4838.9  359.16
  4849.4  357.52  4923.2  353.41  4972.9  353.22  4981.4  352.37  4987.9  352.23
  5005.9  349.23  5008.7  348.73  5011.9  349.23  5014.9  352.55    5024  353.13
  5123.1  351.87  5153.2  353.37  5217.8  357.91  5231.3  359.65  5246.3  364.02
  5276.4   364.9  5297.4  372.12  5312.4  374.19  5318.4   376.9  5325.9  376.63
#Mann= 5 ,-1 , 0
  4649.1     .16       0  4660.2     .12       0  4981.4     .05       0
  5005.9     .03       0  5011.9     .05       0
Bank Sta=4972.9,5153.2
XS Rating Curve= 0 ,0
Exp/Cntr=0.3,0.1

Type RM Length L Ch R = 1 ,20903   ,447,447,447
BEGIN DESCRIPTION:
UNT 110 IN CACR 46.0
END DESCRIPTION:
XS GIS Cut Line= 3
      3697099.61     10708360.18      3697149.61     10708610.19
       3697349.6     10708660.19
#Sta/Elev= 30
  4775.2  368.32  4795.6  366.67  4805.8  362.69    4816  361.36  4826.2  357.43
  4846.6  351.99    4867  350.81  4907.8  350.29    4918   350.7  4938.4  350.52
  4948.6  349.88  4979.2  349.72  4989.4  348.47  4996.6  346.12  4999.3  345.62
  5009.8  346.68    5020  349.24  5027.6  350.27  5061.1  349.03  5089.4   349.7
  5122.9  349.32  5135.8  349.58  5143.5  350.41  5153.8   351.6  5164.2  354.37
    5177  356.98  5184.8  361.59  5195.1  362.85  5218.3  367.41  5236.3  367.89
#Mann= 3 ,-1 , 0
  4775.2     .16       0  4996.6     .07       0  4999.3     .16       0
Bank Sta=4938.4,5143.5
XS Rating Curve= 0 ,0
Exp/Cntr=0.3,0.1

Type RM Length L Ch R = 1 ,20456   ,340,340,340
BEGIN DESCRIPTION:
UNT 110 IN CACR 45.0
END DESCRIPTION:
XS GIS Cut Line= 3
       3696599.6     10708510.18      3696849.61     10708910.19
      3696949.59     10709010.17
#Sta/Elev= 30
    4519  363.17    4522  363.17  4526.7  361.55  4547.9  360.08  4554.4  357.72
    4578  355.18  4584.5  353.62  4605.7  352.19  4613.3  351.26  4636.3  350.01
  4684.7  349.23  4751.9  349.61  4788.5  348.74  4815.6  348.75  4846.2  347.88
  4882.8  347.48    4904  347.06  4955.3   347.6  4967.7  345.94    4983  345.37
  4987.8  343.71  5001.8  343.64  5004.6  343.14    5019  345.96  5033.1  347.09
  5061.4  347.44  5089.7  351.06  5103.8  353.94  5128.6  357.82  5132.1  357.82
#Mann= 3 ,-1 , 0
    4519     .16       0  5001.8     .07       0  5004.6     .16       0
Bank Sta=4882.8,5061.4
XS Rating Curve= 0 ,0
Exp/Cntr=0.3,0.1

Type RM Length L Ch R = 1 ,20116   ,501,501,501
BEGIN DESCRIPTION:
UNT 110 IN CACR 44.0
END DESCRIPTION:
XS GIS Cut Line= 2
      3696236.67     10708995.68      3696955.84      10709333.6
#Sta/Elev= 30
  4483.6   368.4  4573.1  365.71  4586.3  366.12  4618.7  364.16  4675.4   362.6
  4707.8  360.32  4715.5  357.92    4721  357.35  4729.9  353.56  4743.8  350.39
    4752  347.47  4761.1  345.97  4774.1  344.26  4789.4  343.94  4971.9  344.66
    4984  344.23  4994.7  342.71  4997.2  341.53  4999.9  341.03  5003.2  341.53
  5006.1  344.13  5039.3  345.64  5045.8  346.96  5083.5  351.42  5096.9  352.12
  5159.8   362.9  5165.4  363.02    5205  368.35    5211  370.46  5278.2  376.79
#Mann= 3 ,-1 , 0
  4483.6     .16       0  4997.2     .03       0  5003.2     .16       0
Bank Sta=4761.1,5045.8
XS Rating Curve= 0 ,0
Exp/Cntr=0.3,0.1

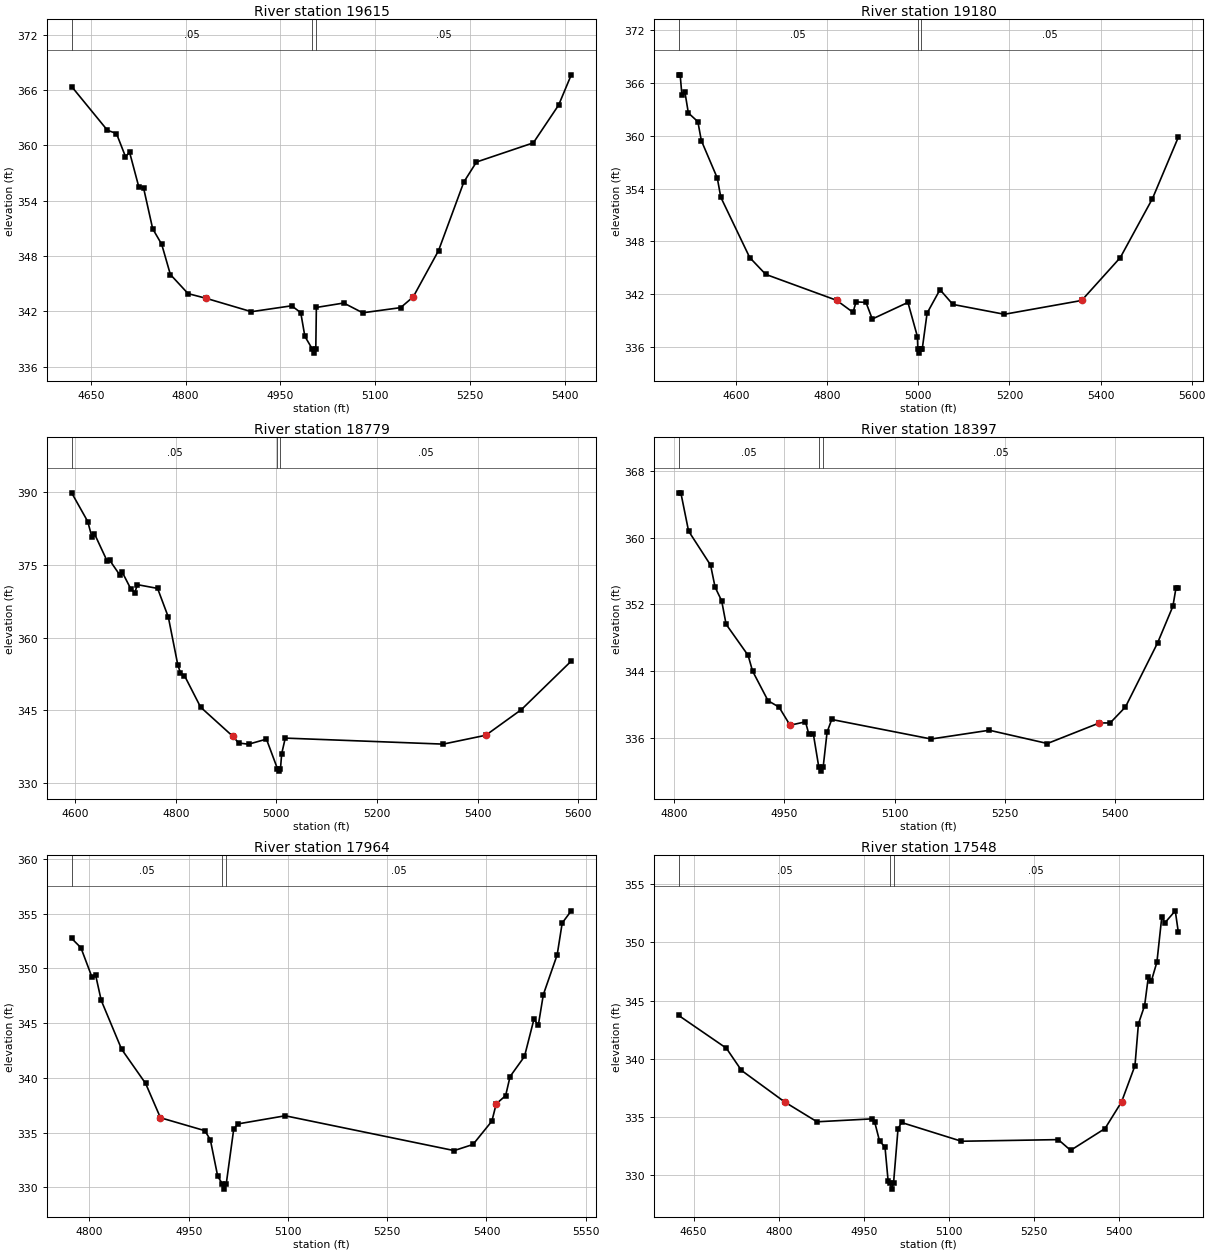
Type RM Length L Ch R = 1 ,19615   ,435,435,435
BEGIN DESCRIPTION:
UNT 110 IN CACR 43.0
END DESCRIPTION:
XS GIS Cut Line= 3
      3696149.63     10709310.21      3696399.61     10709610.19
      3696799.62     10709610.19
#Sta/Elev= 30
  4619.8  366.37  4676.4  361.63  4690.7  361.28    4705  358.77  4711.5  359.24
  4725.9  355.53  4733.7  355.35    4748  350.96  4762.3  349.27    4776     346
    4804  343.93  4832.6  343.42  4904.2  341.97    4968  342.61  4982.3  341.86
  4988.8   339.3  5000.1  337.98  5002.9  337.48  5006.1  337.98    5007  342.43
  5050.3  342.91  5080.3  341.85  5140.3  342.41  5160.3  343.58  5200.3  348.59
  5240.3  356.02  5260.3  358.19  5350.3  360.27  5390.3  364.36  5410.3  367.64
#Mann= 3 ,-1 , 0
  4619.8     .05       0  5000.1     .03       0  5006.1     .05       0
Bank Sta=4832.6,5160.3
XS Rating Curve= 0 ,0
Exp/Cntr=0.3,0.1

Type RM Length L Ch R = 1 ,19180   ,401,401,401
BEGIN DESCRIPTION:
UNT 110 IN CACR 42.0
END DESCRIPTION:
XS GIS Cut Line= 3
      3695649.63     10709510.21      3696049.61     10709860.19
      3696449.64     10710260.22
#Sta/Elev= 30
  4473.5  366.94  4476.8  366.94  4480.6  364.69  4487.2  364.99  4494.8   362.6
  4515.7  361.61  4523.3  359.46  4558.4  355.19    4566  353.02  4629.6  346.15
  4664.7  344.24  4820.4  341.29  4856.4  339.92  4863.1  341.11  4884.9  341.05
  4898.7  339.16    4977  341.05  4997.9  337.15  4998.7  335.78  5001.4  335.28
  5004.7  335.78  5008.5  335.78  5019.1  339.83  5047.4   342.5  5075.7  340.82
  5188.8   339.7  5358.5  341.27  5443.4  346.15  5514.1  352.87  5570.7  359.83
#Mann= 3 ,-1 , 0
  4473.5     .05       0  4998.7     .03       0  5004.7     .05       0
Bank Sta=4820.4,5358.5
XS Rating Curve= 0 ,0
Exp/Cntr=0.3,0.1

Type RM Length L Ch R = 1 ,18779   ,382,382,382
BEGIN DESCRIPTION:
UNT 110 IN CACR 41.0
END DESCRIPTION:
XS GIS Cut Line= 3
      3695349.64      10709960.2      3695749.61     10710110.19
      3696149.64     10710510.22
#Sta/Elev= 30
  4593.2  389.85  4625.2  383.93  4633.2  380.82  4638.6  381.39  4663.5  375.84
  4668.8  375.94  4688.4  372.98  4693.7   373.5  4710.6  370.07  4718.7  369.29
    4724  370.91    4764  370.14  4785.4   364.2  4804.1   354.4  4809.4  352.72
  4817.4  352.16  4849.5  345.65  4913.6  339.63  4925.1  338.26  4944.7  338.01
  4980.3  339.06  5002.2  332.96    5005  332.46  5008.2  332.96  5010.6  336.04
  5017.7  339.27  5331.5  338.03  5416.3  339.86  5487.1  345.16  5586.1  355.16
#Mann= 3 ,-1 , 0
  4593.2     .05       0  5002.2     .03       0  5008.2     .05       0
Bank Sta=4913.6,5416.3
XS Rating Curve= 0 ,0
Exp/Cntr=0.3,0.1

Type RM Length L Ch R = 1 ,18397   ,433,433,433
BEGIN DESCRIPTION:
UNT 110 IN CACR 40.0
END DESCRIPTION:
XS GIS Cut Line= 3
      3695349.62     10710210.21      3695449.61     10710360.19
      3695849.65     10710660.22
#Sta/Elev= 30
  4805.9  365.38  4808.9  365.38  4819.4   360.8  4849.4  356.71  4855.5  354.08
  4864.5  352.43  4870.5  349.63  4900.5   345.9  4906.5  344.03  4927.6  340.47
  4942.6   339.7  4957.6  337.53  4978.6  337.94  4983.1  336.48  4989.3  336.48
  4996.7  332.53  4999.4  332.03  5002.7  332.53    5008   336.7  5014.3  338.22
  5149.7  335.88  5228.9  336.93    5308  335.34  5378.9  337.81  5393.4   337.8
  5414.3  339.72    5458  347.39  5478.9  351.79    5483  353.94  5486.2  353.94
#Mann= 3 ,-1 , 0
  4805.9     .05       0  4996.7     .03       0  5002.7     .05       0
Bank Sta=4957.6,5378.9
XS Rating Curve= 0 ,0
Exp/Cntr=0.3,0.1

Type RM Length L Ch R = 1 ,17964   ,416,416,416
BEGIN DESCRIPTION:
UNT 110 IN CACR 39.0
END DESCRIPTION:
XS GIS Cut Line= 3
       3694949.6     10710560.18      3695149.61     10710660.19
      3695499.59     10711060.17
#Sta/Elev= 30
  4773.1  352.73  4787.1  351.88  4803.9  349.18  4809.4  349.36  4817.8  347.07
  4848.6  342.61  4884.9  339.48  4907.3  336.35  4974.4  335.17  4982.7  334.34
  4993.9  330.99  5000.8  330.33  5003.6  329.83  5006.8  330.33  5018.1  335.33
  5024.7  335.79  5095.9  336.53  5351.2  333.35  5379.7  333.91  5408.2  336.04
  5414.8  337.62    5429  338.37  5435.7  340.11  5457.5  341.95  5471.8  345.35
  5478.4   344.8    5486   347.6  5506.9  351.23  5514.5  354.14  5528.2  355.25
#Mann= 3 ,-1 , 0
  4773.1     .05       0  5000.8     .03       0  5006.8     .05       0
Bank Sta=4907.3,5414.8
XS Rating Curve= 0 ,0
Exp/Cntr=0.3,0.1

Type RM Length L Ch R = 1 ,17548   ,257,257,257
BEGIN DESCRIPTION:
UNT 110 IN CACR 38.0
END DESCRIPTION:
XS GIS Cut Line= 3
      3694779.78     10710671.91      3694878.74      10710976.6
       3695394.2     10711195.28
#Sta/Elev= 30
  4623.6  343.73  4707.6  340.92  4734.3  339.01  4811.1  336.28  4867.4   334.6
  4963.6  334.85    4969  334.58  4977.5  332.96  4987.2  332.42  4992.7  329.51
  4996.2  329.32    4999  328.82  5002.2  329.32  5010.1  333.99  5016.3  334.54
  5121.9  332.93  5292.5  333.07  5314.2  332.15  5374.8  334.02  5403.9   336.3
  5427.6  339.42  5433.7  343.01  5444.6  344.58  5451.2  347.05  5456.7  346.72
  5466.3  348.32  5474.9   352.2  5480.3  351.68  5498.6  352.71  5503.9  350.91
#Mann= 3 ,-1 , 0
  4623.6     .05       0  4996.2     .03       0  5002.2     .05       0
Bank Sta=4811.1,5403.9
XS Rating Curve= 0 ,0
Exp/Cntr=0.3,0.1

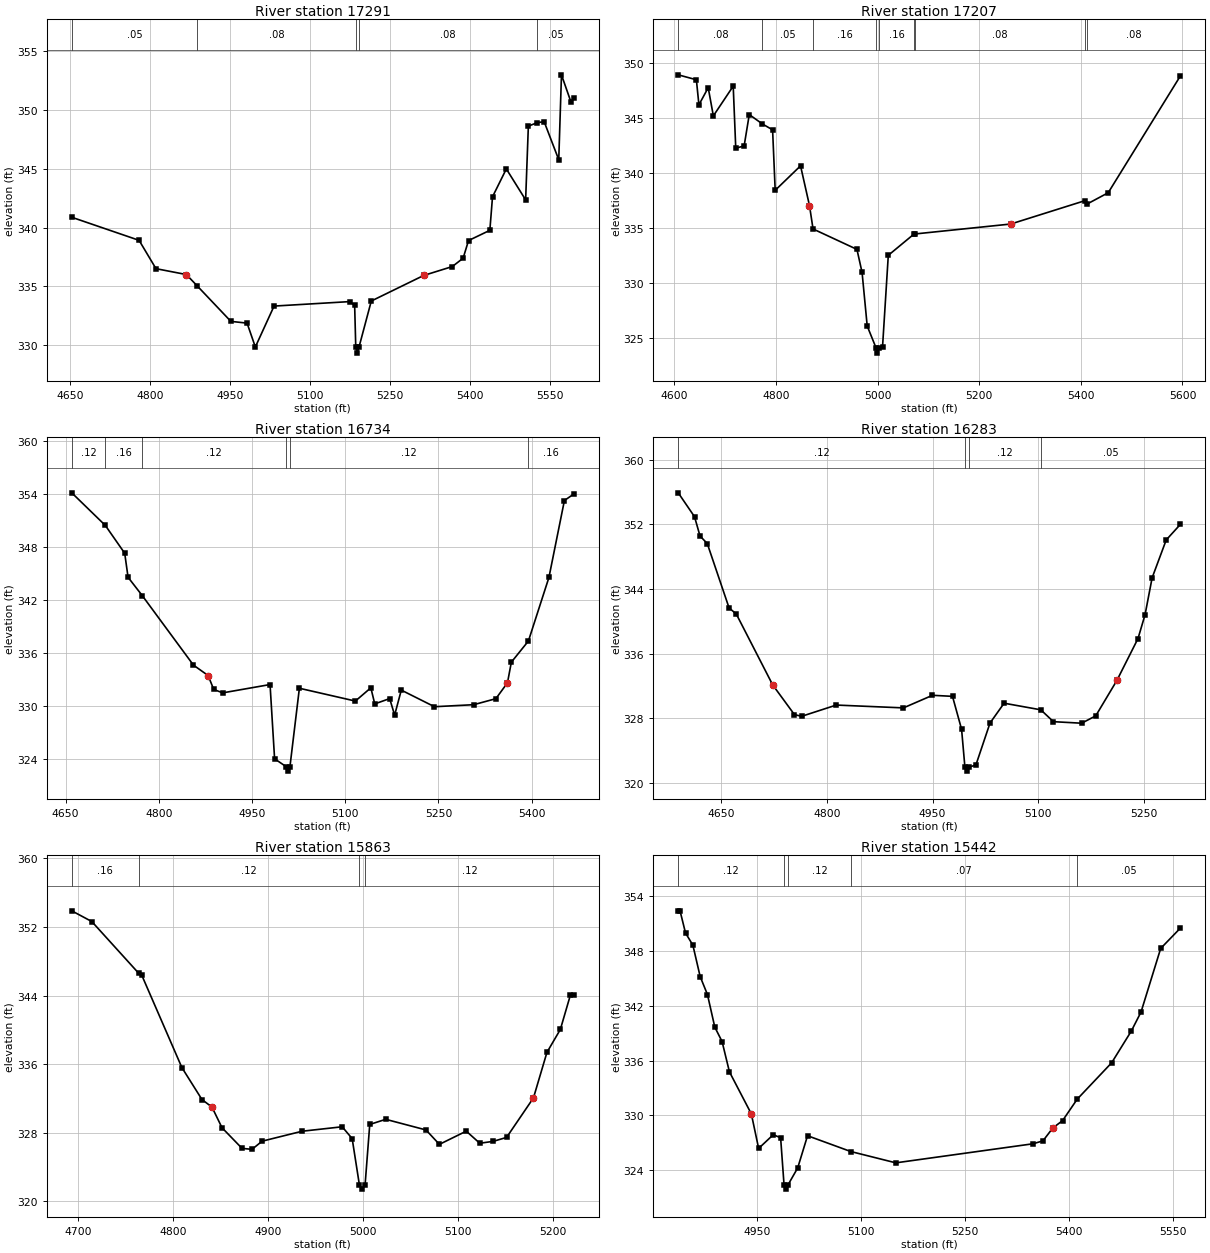
Type RM Length L Ch R = 1 ,17291   ,84,84,84
BEGIN DESCRIPTION:
Mapping XS 7cafa478
END DESCRIPTION:
XS GIS Cut Line= 2
      3694730.31     10710825.59      3694878.73     10711755.22
#Sta/Elev= 30
  4652.9  340.88  4779.1  338.92  4810.8  336.51  4867.8  336.01    4888  335.05
  4951.2  332.03  4981.6  331.88  4997.1  329.85  5032.2  333.33    5174  333.71
  5183.3   333.4  5185.4  329.83  5188.1  329.33  5191.4  329.83  5214.5  333.76
  5312.6  335.93  5366.4  336.69  5386.7   337.4  5396.8   338.9  5436.8  339.77
  5441.8  342.62  5467.7  344.99  5503.9  342.36    5509  348.63  5525.6  348.92
  5538.6  349.01    5566  345.77  5571.1  352.99  5589.2  350.64  5594.3  351.05
#Mann= 5 ,-1 , 0
  4652.9     .05       0    4888     .08       0  5185.4     .07       0
  5191.4     .08       0  5525.6     .05       0
Bank Sta=4867.8,5312.6
XS Rating Curve= 0 ,0
Exp/Cntr=0.3,0.1

Type RM Length L Ch R = 1 ,17207   ,473,473,473
BEGIN DESCRIPTION:
UNT 110 IN CACR 37.0
END DESCRIPTION:
XS GIS Cut Line= 2
      3694649.57     10710791.69      3694782.38     10711770.83
#Sta/Elev= 30
  4607.7  348.94  4643.4  348.49  4648.4  346.21  4666.7  347.77  4676.8   345.2
  4715.9  347.91  4720.9  342.25  4737.4  342.47  4747.5  345.32  4773.5  344.46
  4793.4  343.93  4798.5  338.42  4848.4  340.65    4866  337.03    4873   334.9
  4959.4  333.04  4969.5  330.94  4979.6  326.06  4996.8  324.09  4999.5  323.59
  5002.8  324.09  5009.8  324.18  5021.1   332.5  5071.8  334.44  5072.7  334.44
  5262.1  335.35    5409  337.49  5413.1  337.19  5453.9   338.2  5595.8  348.83
#Mann= 9 ,-1 , 0
  4607.7     .08       0  4773.5     .05       0    4873     .16       0
  4996.8     .07       0  5002.8     .16       0  5071.8     .12       0
  5072.7     .08       0    5409     .05       0  5413.1     .08       0
Bank Sta=4866,5262.1
XS Rating Curve= 0 ,0
Exp/Cntr=0.3,0.1

Type RM Length L Ch R = 1 ,16734   ,451,451,451
BEGIN DESCRIPTION:
UNT 110 IN CACR 36.0
END DESCRIPTION:
XS GIS Cut Line= 3
       3694399.6      10711010.2      3694249.61     10711360.19
      3694399.62     10711760.21
#Sta/Elev= 30
    4660  354.16    4714  350.47  4745.2  347.32  4750.6   344.6  4773.4  342.53
  4855.8  334.66  4879.4  333.48  4888.5   331.9    4903  331.52  4979.1  332.46
  4986.4  324.06  5005.1  323.16  5007.9  322.66  5011.1  323.16  5026.3  332.04
  5116.4  330.59  5141.3  332.09  5147.6  330.27  5171.6  330.87  5179.6     329
  5190.3  331.83  5243.7  329.95  5306.9  330.18  5342.5  330.86  5361.2  332.66
  5367.4  334.99  5394.9  337.39  5427.9  344.58  5452.8  353.29    5468  354.03
#Mann= 6 ,-1 , 0
    4660     .12       0    4714     .16       0  4773.4     .12       0
  5005.1     .07       0  5011.1     .12       0  5394.9     .16       0
Bank Sta=4879.4,5361.2
XS Rating Curve= 0 ,0
Exp/Cntr=0.3,0.1

Type RM Length L Ch R = 1 ,16283   ,420,420,420
BEGIN DESCRIPTION:
UNT 110 IN CACR 35.0
END DESCRIPTION:
XS GIS Cut Line= 3
      3693799.62     10711110.23      3693899.61     10711510.19
      3693899.61     10711810.22
#Sta/Elev= 30
  4589.1  355.92  4612.2  352.96    4620  350.57  4630.3  349.63  4661.2  341.66
  4671.5  340.89  4723.1  332.11    4754  328.42  4764.3  328.22  4813.3  329.61
  4908.6  329.26  4949.8  330.82  4978.2  330.69  4991.1   326.6  4995.8  321.92
  4998.5  321.42  5001.8  321.92  5011.4  322.18  5031.4  327.38  5051.4  329.84
  5103.5  329.02  5121.4  327.55  5161.4  327.36  5181.4  328.27  5211.4  332.66
  5241.4  337.86  5251.4  340.82  5261.4  345.38  5281.4  350.08  5301.4     352
#Mann= 4 ,-1 , 0
  4589.1     .12       0  4995.8     .07       0  5001.8     .12       0
  5103.5     .05       0
Bank Sta=4723.1,5211.4
XS Rating Curve= 0 ,0
Exp/Cntr=0.3,0.1

Type RM Length L Ch R = 1 ,15863   ,421,421,421
BEGIN DESCRIPTION:
UNT 110 IN CACR 34.0
END DESCRIPTION:
XS GIS Cut Line= 3
      3693399.61     10711310.19      3693499.61     10711610.19
      3693649.64     10711760.22
#Sta/Elev= 30
  4693.2  353.89  4714.3  352.64  4763.8  346.59    4767  346.35  4809.1  335.61
  4830.2  331.89  4840.8     331  4851.3   328.6  4872.4  326.19  4882.9  326.08
  4893.5  327.03  4935.6  328.19  4977.8  328.71  4988.3  327.33  4995.9  321.94
  4998.6  321.44  5001.9  321.94  5006.8  328.98  5023.6  329.58    5066  328.34
  5080.1  326.66  5108.4   328.2  5122.6  326.79  5136.7  327.01  5150.8  327.47
  5179.1  332.08  5193.3  337.39  5207.4  340.06    5218  344.08  5221.6  344.08
#Mann= 4 ,-1 , 0
  4693.2     .16       0  4763.8     .12       0  4995.9     .07       0
  5001.9     .12       0
Bank Sta=4840.8,5179.1
XS Rating Curve= 0 ,0
Exp/Cntr=0.3,0.1

Type RM Length L Ch R = 1 ,15442   ,443,443,443
BEGIN DESCRIPTION:
UNT 110 IN CACR 33.0
END DESCRIPTION:
XS GIS Cut Line= 3
      3693049.62     10711560.21      3693099.61     10711710.19
      3693499.62      10712110.2
#Sta/Elev= 30
  4836.6   352.4  4839.2   352.4  4847.1  349.97  4857.7  348.64  4868.2   345.2
  4878.7  343.23  4889.3  339.66  4899.8  338.08  4910.4  334.76    4942  330.15
  4952.5  326.37  4973.6  327.87  4984.2  327.54  4989.1  322.41  4991.8  321.91
  4995.1  322.41  5008.8  324.23    5023  327.76  5085.3  326.03  5150.3  324.79
  5348.2  326.88  5362.4   327.2  5376.5   328.6  5390.7  329.42  5411.8  331.77
  5461.4  335.75  5489.7  339.22  5503.8  341.32  5532.1  348.28  5560.4   350.5
#Mann= 5 ,-1 , 0
  4836.6     .12       0  4989.1     .07       0  4995.1     .12       0
  5085.3     .07       0  5411.8     .05       0
Bank Sta=4942,5376.5
XS Rating Curve= 0 ,0
Exp/Cntr=0.3,0.1

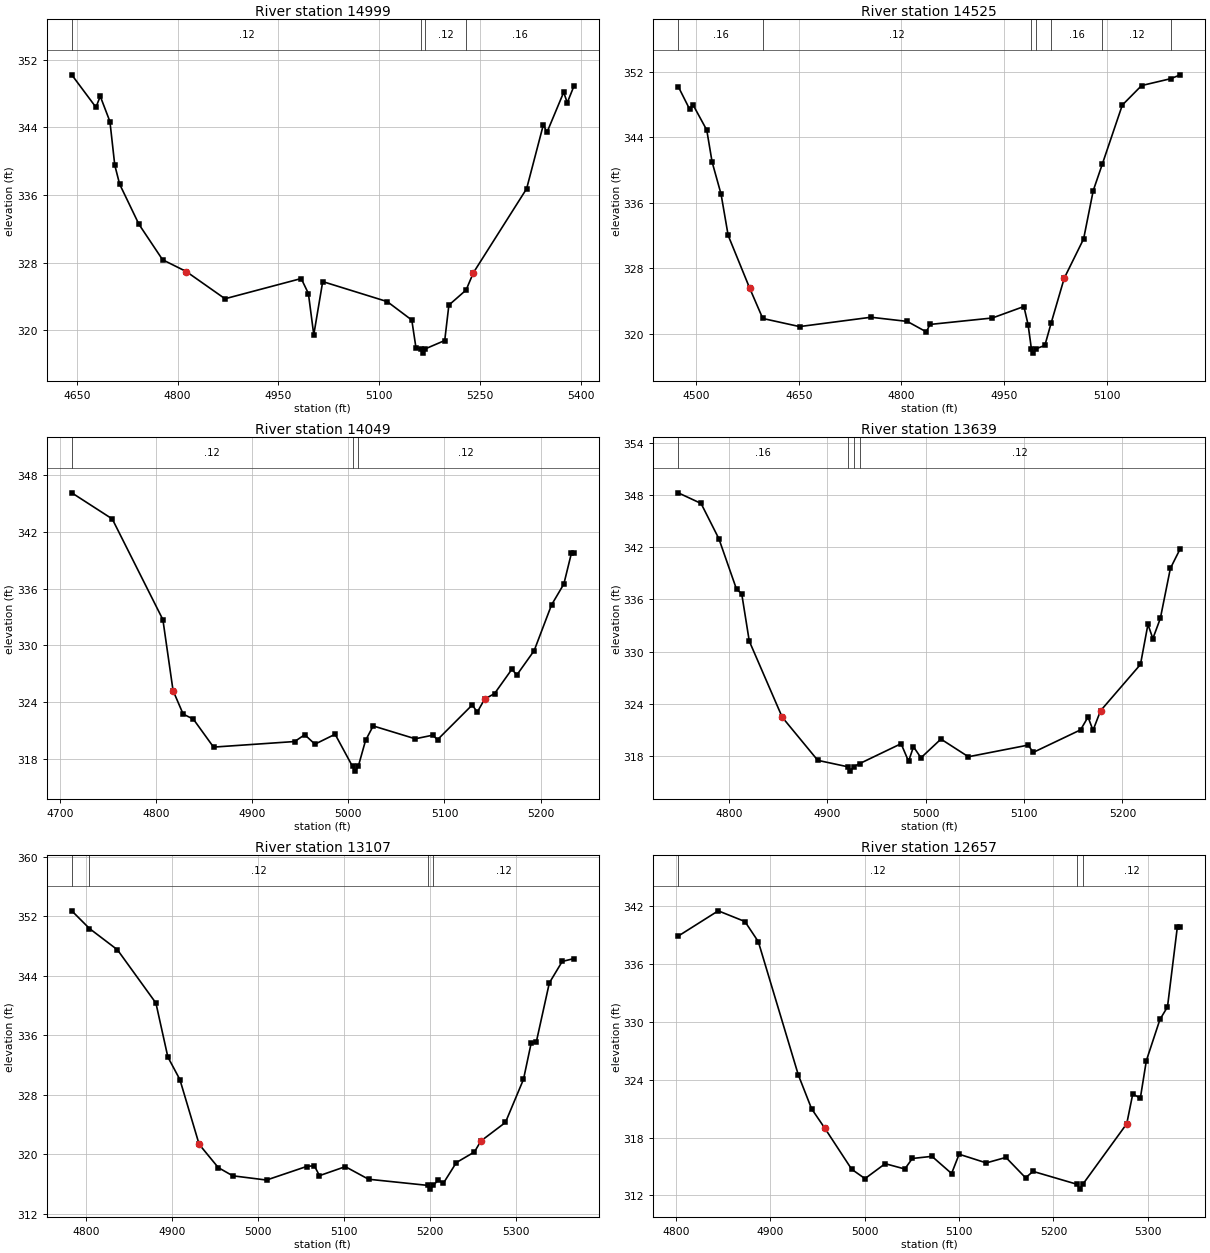
Type RM Length L Ch R = 1 ,14999   ,474,474,474
BEGIN DESCRIPTION:
UNT 110 IN CACR 32.0
END DESCRIPTION:
XS GIS Cut Line= 3
      3692999.58     10711510.21      3692749.61     10711710.19
      3692349.63     10711860.18
#Sta/Elev= 30
  4642.5  350.21  4678.5  346.37  4684.9  347.68  4699.3  344.68  4706.5  339.53
  4713.7  337.29  4742.5  332.53  4777.7  328.34  4812.9  326.95  4870.6  323.73
    4984  326.12  4994.7  324.35  5002.7  319.47    5016  325.76  5112.1  323.39
  5148.6  321.21  5154.9  317.88  5162.5   317.8  5165.3   317.3  5168.5   317.8
  5197.6  318.79  5203.8  322.98  5229.4  324.76  5240.3  326.81  5319.5  336.74
  5344.4   344.3  5349.8  343.41  5374.7  348.15    5380  346.91  5389.8  348.85
#Mann= 4 ,-1 , 0
  4642.5     .12       0  5162.5     .07       0  5168.5     .12       0
  5229.4     .16       0
Bank Sta=4812.9,5240.3
XS Rating Curve= 0 ,0
Exp/Cntr=0.3,0.1

Type RM Length L Ch R = 1 ,14525   ,476,476,476
BEGIN DESCRIPTION:
UNT 110 IN CACR 31.0
END DESCRIPTION:
XS GIS Cut Line= 3
      3692949.57      10711360.2      3692449.61     10711510.19
      3692299.61     10711660.18
#Sta/Elev= 30
  4473.6  350.19  4490.1  347.45  4495.3  347.95  4515.3  344.88  4523.1  340.99
  4536.2  337.06  4546.6  332.02    4578  325.59  4597.2  321.88    4651  320.89
  4755.4  322.03  4808.5  321.52  4836.4  320.24  4841.6  321.15  4932.9  321.94
    4979  323.34  4985.1  321.14    4990  318.15  4992.7  317.65    4996  318.15
  5009.7   318.6  5018.7  321.28    5038   326.8  5066.3  331.59  5080.4  337.49
  5093.6  340.71  5122.9  347.93  5151.1  350.31  5193.7  351.15  5207.7  351.62
#Mann= 7 ,-1 , 0
  4473.6     .16       0  4597.2     .12       0    4990     .07       0
    4996     .12       0  5018.7     .16       0  5093.6     .12       0
  5193.7     .05       0
Bank Sta=4578,5038
XS Rating Curve= 0 ,0
Exp/Cntr=0.3,0.1

Type RM Length L Ch R = 1 ,14049   ,410,410,410
BEGIN DESCRIPTION:
UNT 110 IN CACR 30.0
END DESCRIPTION:
XS GIS Cut Line= 3
      3692049.62     10710960.22      3692149.61     10711260.19
       3692099.6     10711460.24
#Sta/Elev= 30
  4712.2  346.12  4754.3  343.36    4807  332.71  4817.6   325.2  4828.1  322.72
  4838.7  322.19  4859.7  319.23  4944.1  319.82  4954.6  320.54  4965.2  319.54
  4986.2  320.59  5004.3  317.19  5007.1  316.69  5010.3  317.19  5017.9  319.94
  5025.8  321.47  5069.6  320.11  5087.7  320.49  5092.8  320.02  5128.9  323.69
  5134.1  322.93  5141.8  324.31  5152.1  324.89  5170.1  327.46  5175.3  326.86
  5193.3  329.43  5211.4  334.27  5224.2  336.48    5232  339.71  5234.6  339.71
#Mann= 3 ,-1 , 0
  4712.2     .12       0  5004.3     .07       0  5010.3     .12       0
Bank Sta=4817.6,5141.8
XS Rating Curve= 0 ,0
Exp/Cntr=0.3,0.1

Type RM Length L Ch R = 1 ,13639   ,532,532,532
BEGIN DESCRIPTION:
UNT 110 IN CACR 29.0
END DESCRIPTION:
XS GIS Cut Line= 3
      3691799.62     10710910.16      3691749.61     10711110.19
       3691799.6     10711410.16
#Sta/Elev= 30
  4748.5  348.24  4771.7  347.02  4789.8  342.97  4807.8  337.15    4813  336.66
  4820.7  331.21  4854.2  322.47  4890.3  317.52  4920.8  316.78  4923.5  316.28
  4926.8  316.78  4932.8  317.14    4975  319.43  4982.6  317.41  4987.6  319.08
  4995.2  317.81  5015.5  319.96  5043.4  317.93  5104.2  319.27  5109.3  318.43
  5157.4  321.02    5165  322.49  5170.1  320.97  5177.7  323.21  5218.3  328.53
  5225.9  333.13  5230.9   331.5  5238.5  333.82  5248.7  339.56  5258.8  341.84
#Mann= 4 ,-1 , 0
  4748.5     .16       0  4920.8     .07       0  4926.8     .16       0
  4932.8     .12       0
Bank Sta=4854.2,5177.7
XS Rating Curve= 0 ,0
Exp/Cntr=0.3,0.1

Type RM Length L Ch R = 1 ,13107   ,450,450,450
BEGIN DESCRIPTION:
UNT 110 IN CACR 28.0
END DESCRIPTION:
XS GIS Cut Line= 3
      3691449.63     10710710.16      3691349.61     10710910.19
      3691149.61     10711210.19
#Sta/Elev= 30
  4783.1  352.73  4803.7  350.35  4836.2   347.5    4881  340.34  4894.9  333.09
  4908.9  330.06  4931.3  321.36  4953.6  318.23  4970.4  317.13  5009.7  316.56
  5056.3  318.38  5065.3  318.49  5071.3  317.15  5101.4  318.36  5128.4  316.67
  5197.5  315.84  5200.3  315.34  5203.5  315.84  5209.6  316.54  5215.6  316.15
  5230.6  318.91  5251.6  320.33  5259.1   321.8  5287.7   324.3  5308.7  330.09
  5317.7  334.99  5323.7  335.15  5338.8  343.05  5353.8  345.93  5367.3  346.31
#Mann= 4 ,-1 , 0
  4783.1     .16       0  4803.7     .12       0  5197.5     .07       0
  5203.5     .12       0
Bank Sta=4931.3,5259.1
XS Rating Curve= 0 ,0
Exp/Cntr=0.3,0.1

Type RM Length L Ch R = 1 ,12657   ,493,493,493
BEGIN DESCRIPTION:
UNT 110 IN CACR 27.0
END DESCRIPTION:
XS GIS Cut Line= 3
      3691099.62     10710610.18      3690949.61     10710760.19
      3690749.61     10711010.18
#Sta/Elev= 30
  4802.2   338.9  4844.6  341.52  4872.9  340.41  4887.1  338.32  4929.5   324.5
  4943.6  320.98  4957.8  318.94  4986.1  314.71  5000.2  313.74  5021.6  315.29
  5042.4  314.74  5050.4  315.83  5071.2  316.05    5092  314.27    5100  316.27
  5128.8  315.37  5149.6  315.94  5170.4  313.83  5178.4  314.49  5225.1  313.15
  5227.8  312.65  5231.1  313.15  5277.7  319.43  5284.1  322.53  5292.1  322.08
  5298.5  325.98  5312.9  330.25  5320.9  331.55  5331.3   339.8  5334.5   339.8
#Mann= 3 ,-1 , 0
  4802.2     .12       0  5225.1     .07       0  5231.1     .12       0
Bank Sta=4957.8,5277.7
XS Rating Curve= 0 ,0
Exp/Cntr=0.3,0.1

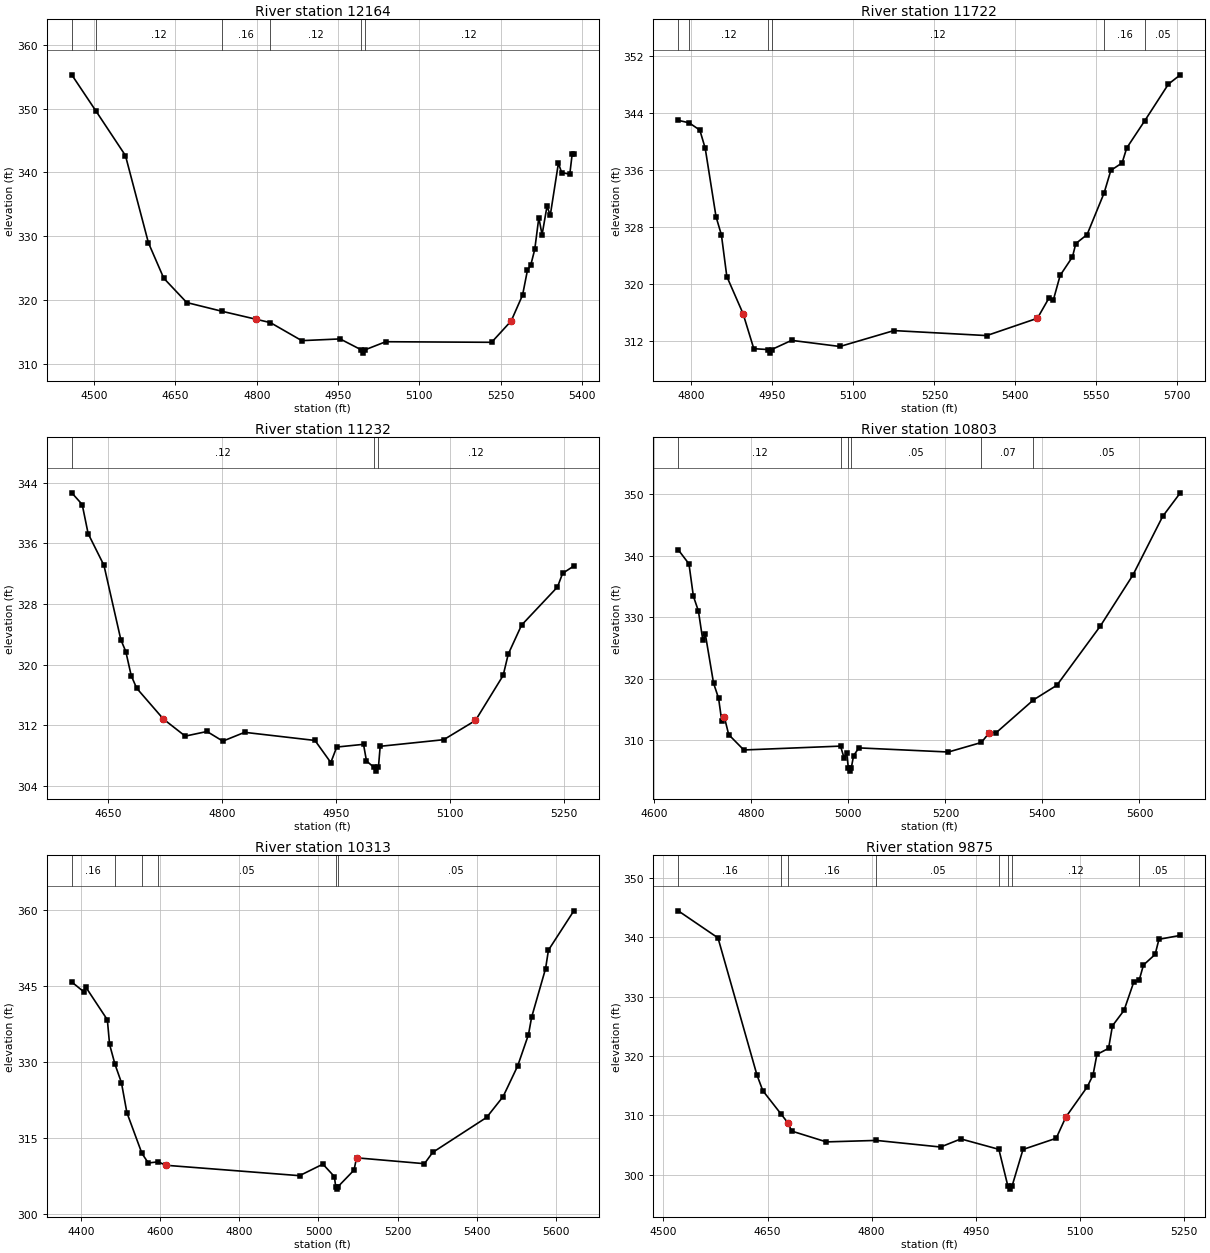
Type RM Length L Ch R = 1 ,12164   ,442,442,442
BEGIN DESCRIPTION:
UNT 110 IN CACR 26.0
END DESCRIPTION:
XS GIS Cut Line= 3
      3690899.61     10710260.19      3690499.61     10710660.19
      3690699.59     10710960.16
#Sta/Elev= 30
  4458.8  355.33    4503   349.7  4557.8  342.66  4600.2  328.96  4628.5   323.4
  4670.9  319.58  4735.9  318.21  4798.2  316.97  4825.2  316.43  4883.1   313.6
  4953.8  313.87  4993.2  312.14  4995.9  311.64  4999.2  312.14    5038  313.43
  5233.3  313.34  5269.4  316.69  5290.4  320.75  5299.4  324.65  5305.4  325.42
  5312.9  327.93  5320.4  332.92  5326.4  330.22  5335.5  334.71  5341.5  333.27
  5356.5  341.45  5362.5  339.99  5377.5  339.73    5382  342.94    5385  342.94
#Mann= 6 ,-1 , 0
  4458.8     .16       0    4503     .12       0  4735.9     .16       0
  4825.2     .12       0  4993.2     .07       0  4999.2     .12       0
Bank Sta=4798.2,5269.4
XS Rating Curve= 0 ,0
Exp/Cntr=0.3,0.1

Type RM Length L Ch R = 1 ,11722   ,490,490,490
BEGIN DESCRIPTION:
UNT 110 IN CACR 25.0
END DESCRIPTION:
XS GIS Cut Line= 3
      3690149.61     10710510.16      3690149.61     10710760.19
      3689749.61     10711310.19
#Sta/Elev= 30
  4775.5     343  4795.7  342.65  4815.5  341.63  4825.5  339.07  4845.5  329.49
  4855.5  326.93  4865.5   321.1  4895.5  315.91  4915.5  310.98  4942.5  310.86
  4945.3  310.36  4948.5  310.86  4985.5  312.15    5075  311.29  5175.1  313.52
    5347  312.82  5440.9  315.25  5461.8  318.02  5470.3  317.78    5483  321.26
  5505.8  323.85    5512  325.72  5532.9  326.98  5564.4  332.81  5576.9  335.98
  5597.8  337.03  5606.3  339.12  5639.9  342.96  5683.6  348.08  5705.6  349.38
#Mann= 6 ,-1 , 0
  4775.5     .16       0  4795.7     .12       0  4942.5     .07       0
  4948.5     .12       0  5564.4     .16       0  5639.9     .05       0
Bank Sta=4895.5,5440.9
XS Rating Curve= 0 ,0
Exp/Cntr=0.3,0.1

Type RM Length L Ch R = 1 ,11232   ,429,429,429
BEGIN DESCRIPTION:
UNT 110 IN CACR 24.0
END DESCRIPTION:
XS GIS Cut Line= 3
      3690049.63     10710460.17      3689749.61     10710710.19
      3689649.61      10710960.2
#Sta/Elev= 30
  4602.7  342.64  4616.4   341.1  4624.2  337.27    4645  333.09  4667.2  323.29
  4673.7  321.74  4680.8  318.57    4688  316.91  4723.1  312.85  4751.8   310.6
  4780.4  311.21  4801.2  309.94  4829.9   311.1  4922.3  310.03  4943.1  307.12
  4950.9  309.16  4986.1  309.52    4990  307.33  4999.7  306.49  5002.4  305.99
  5005.7  306.49    5008  309.26  5091.5  310.13  5133.2  312.66  5169.6  318.59
  5176.3   321.4  5193.8  325.22    5241  330.24  5247.7  332.03  5262.5  333.01
#Mann= 3 ,-1 , 0
  4602.7     .12       0  4999.7     .07       0  5005.7     .12       0
Bank Sta=4723.1,5133.2
XS Rating Curve= 0 ,0
Exp/Cntr=0.3,0.1

Type RM Length L Ch R = 1 ,10803   ,490,490,490
BEGIN DESCRIPTION:
UNT 110 IN CACR 23.0
END DESCRIPTION:
XS GIS Cut Line= 3
       3689449.6     10710260.23      3689349.61     10710610.19
       3689049.6      10711210.2
#Sta/Elev= 30
  4649.4  340.99  4671.5  338.69  4680.6  333.44    4691  331.02  4700.1  326.25
  4705.3  327.23  4722.2  319.29  4732.6  316.82  4739.1   313.1  4744.3  313.82
  4753.4  310.92  4784.6  308.42  4983.9  309.05  4991.3  307.09  4996.5     308
    5000  305.48  5002.7  304.98    5006  305.48  5010.8  307.49  5021.7  308.76
  5206.2  308.09  5274.1  309.64  5290.1  311.19  5304.1  311.19  5381.6  316.57
  5429.8  318.95  5519.3  328.57  5586.4  336.86  5647.8  346.41  5684.2  350.25
#Mann= 6 ,-1 , 0
  4649.4     .12       0  4983.9     .05       0    5000     .03       0
    5006     .05       0  5274.1     .07       0  5381.6     .05       0
Bank Sta=4744.3,5290.1
XS Rating Curve= 0 ,0
Exp/Cntr=0.3,0.1

Type RM Length L Ch R = 1 ,10313   ,438,438,438
BEGIN DESCRIPTION:
UNT 110 IN CACR 22.0
END DESCRIPTION:
XS GIS Cut Line= 3
      3689199.63     10709960.15      3688899.61     10710510.19
      3688499.58     10711010.22
#Sta/Elev= 30
  4377.5   345.8  4407.4  343.91  4413.1  344.77  4467.3  338.34  4472.9  333.48
  4486.5  329.55  4502.8  325.92  4516.6  319.98  4554.6  311.91  4570.7  310.03
  4595.8  310.26  4614.4  309.58  4952.3  307.52  5011.2   309.8  5040.1  307.34
  5043.5  305.36  5046.2  304.86  5049.5  305.36  5089.7  308.62  5096.1  311.05
  5267.4  309.89  5288.2  312.12  5424.3  319.04  5465.9  323.15  5502.7  329.22
  5529.9  335.41  5537.9  338.86  5573.1  348.47  5580.3  352.11  5644.4  359.88
#Mann= 6 ,-1 , 0
  4377.5     .16       0  4486.5     .12       0  4554.6     .16       0
  4595.8     .05       0  5043.5     .03       0  5049.5     .05       0
Bank Sta=4614.4,5096.1
XS Rating Curve= 0 ,0
Exp/Cntr=0.3,0.1

Type RM Length L Ch R = 1 ,9875    ,389,389,389
BEGIN DESCRIPTION:
UNT 110 IN CACR 21.0
END DESCRIPTION:
XS GIS Cut Line= 3
      3689049.59      10709860.2      3688649.61     10710160.19
       3688549.6      10710360.2
#Sta/Elev= 30
  4521.3  344.41  4578.6  339.86  4634.8  316.79  4643.2  314.17  4669.9  310.18
  4679.4  308.75  4684.8  307.38  4734.8  305.56  4806.8  305.81  4899.4   304.7
  4928.6  306.06  4983.4  304.31  4996.4  298.12  4999.2  297.62  5002.4  298.12
  5018.2  304.29    5066  306.17    5080  309.75  5110.7   314.8  5119.1   316.8
  5124.7  320.26  5141.5  321.29  5147.1  325.08  5163.8  327.68  5177.8  332.43
  5185.6  332.74  5191.8   335.3  5208.6  337.08  5214.1  339.62  5244.9  340.28
#Mann= 8 ,-1 , 0
  4521.3     .16       0  4669.9     .12       0  4679.4     .16       0
  4806.8     .05       0  4983.4     .12       0  4996.4     .07       0
  5002.4     .12       0  5185.6     .05       0
Bank Sta=4679.4,5080
XS Rating Curve= 0 ,0
Exp/Cntr=0.3,0.1