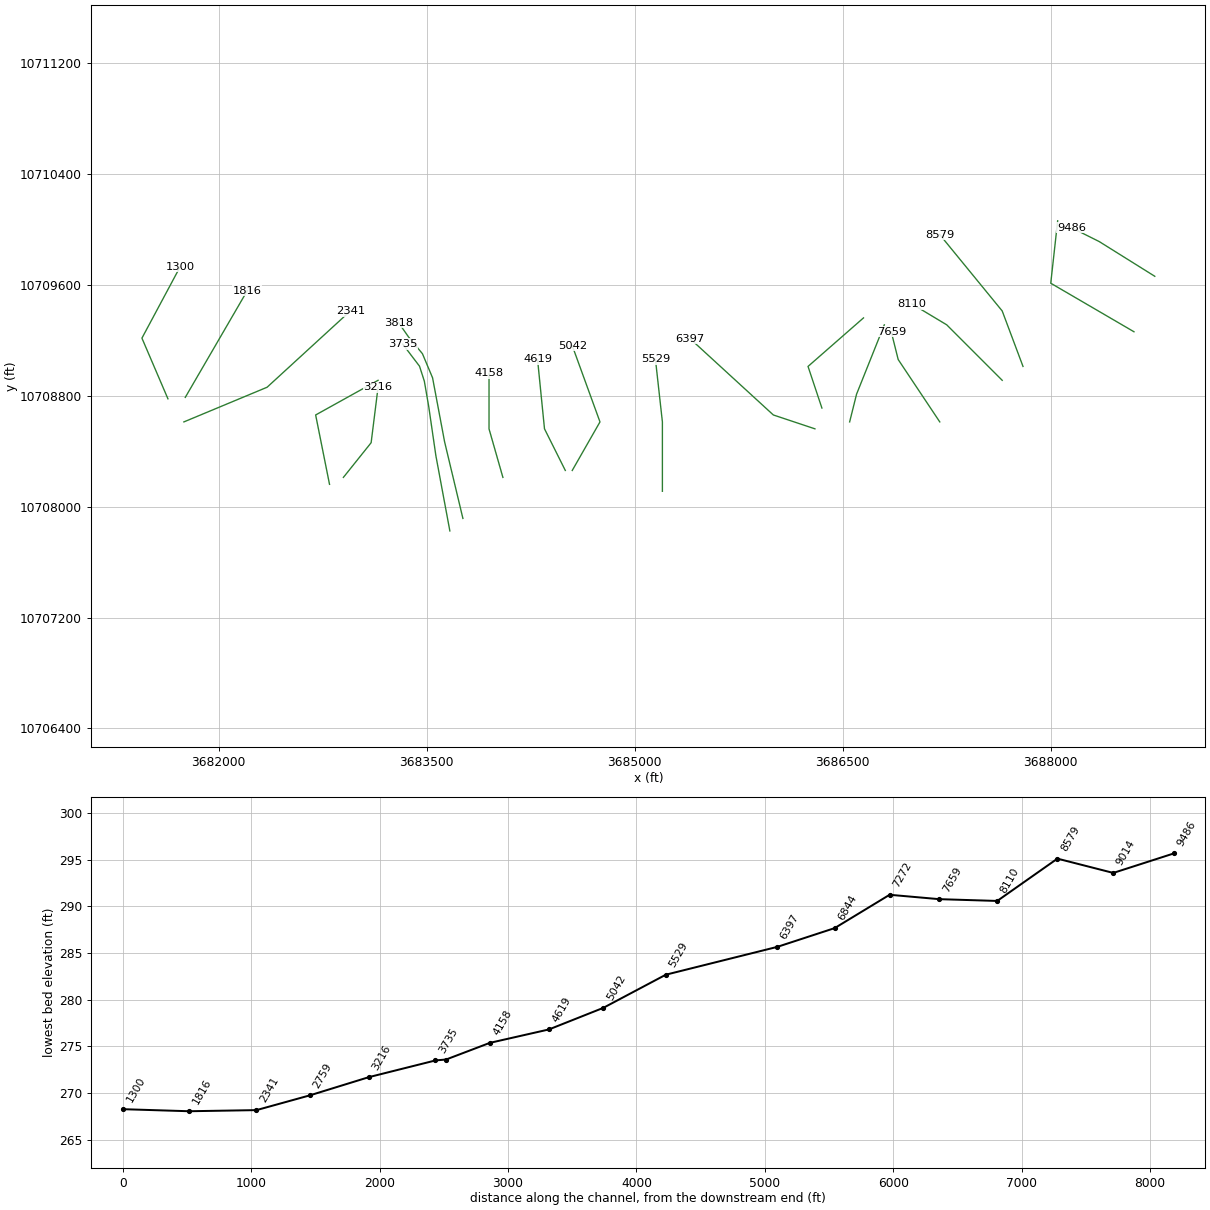
HEC-RAS study UNT 110 IN CACR.prj: UNT 110 IN CACR Base Level Engineering

--- UNT 110 IN CACR.g01 (geometry) --- (continued)

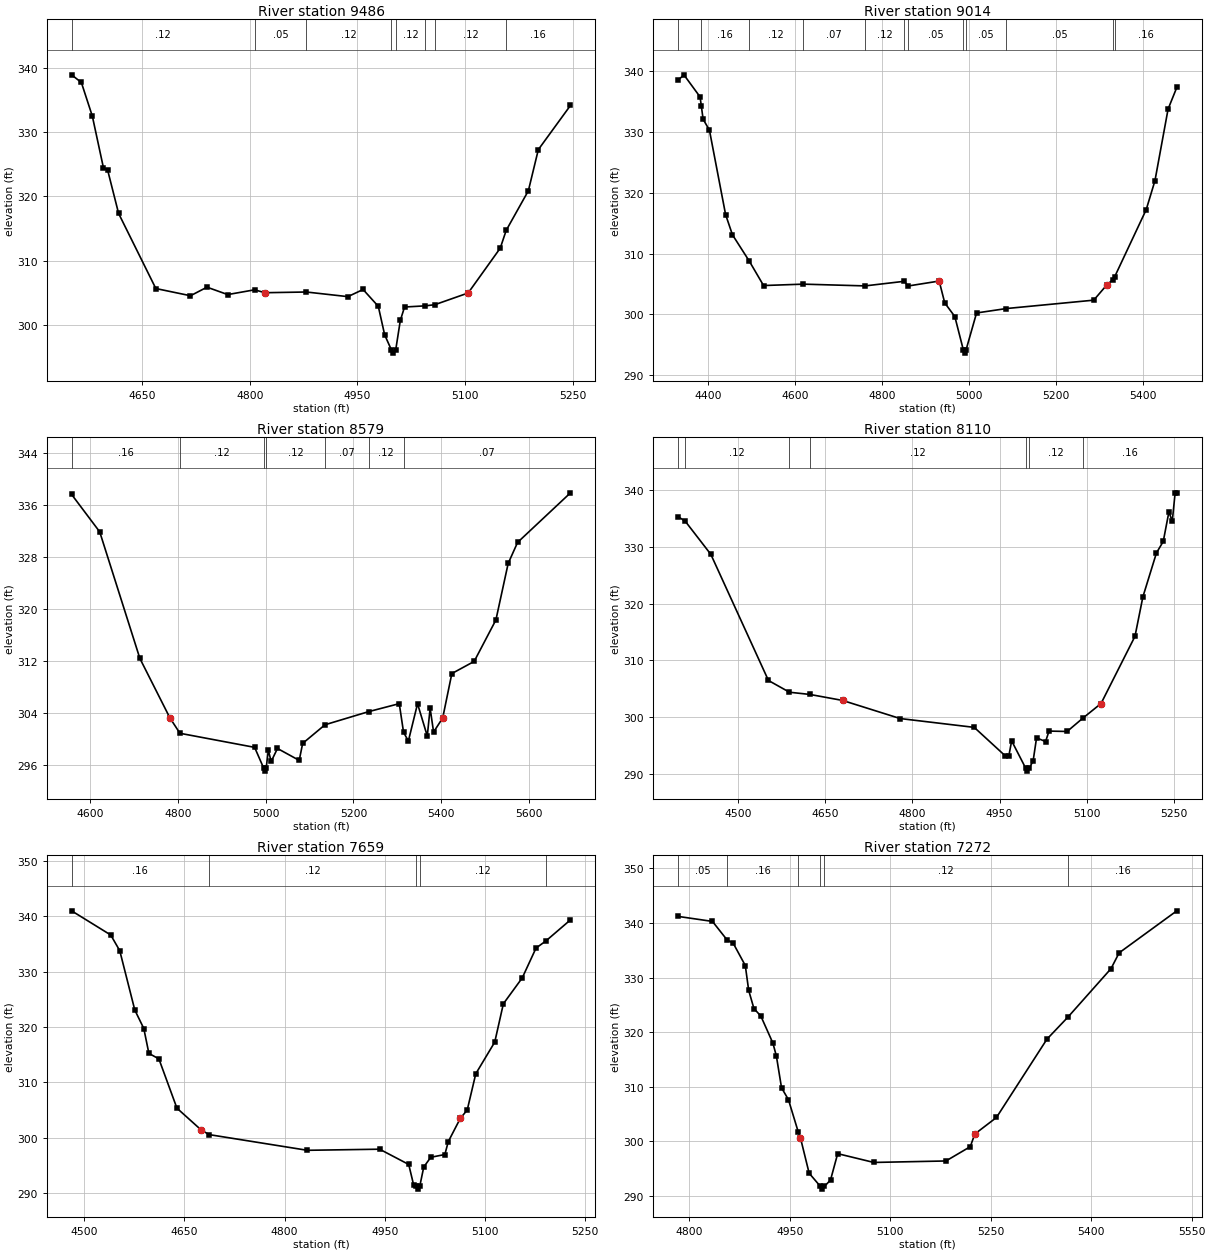
Type RM Length L Ch R = 1 ,9486    ,472,472,472
BEGIN DESCRIPTION:
UNT 110 IN CACR 20.0
END DESCRIPTION:
XS GIS Cut Line= 3
      3688749.65     10709660.16      3688349.61     10709910.19
      3688149.57     10710010.21
#Sta/Elev= 30
  4551.6  338.88  4565.2  337.69  4580.5  332.46  4595.9  324.48  4601.8   324.1
  4617.1  317.36    4669   305.7  4717.3  304.58  4740.3  305.91  4769.2  304.76
  4806.6   305.5  4821.1  305.05  4878.8  305.16  4936.7  304.44  4957.9  305.55
  4979.1  302.94    4988   298.5  4997.4  296.17  5000.1  295.67  5003.4  296.17
  5009.8  300.74  5015.7  302.83  5044.6  303.01  5057.9  303.19  5104.4  305.01
  5149.1  311.97  5157.4  314.73  5188.3  320.88  5202.2  327.27    5247  334.13
#Mann= 8 ,-1 , 0
  4551.6     .12       0  4806.6     .05       0  4878.8     .12       0
  4997.4     .07       0  5003.4     .12       0  5044.6     .16       0
  5057.9     .12       0  5157.4     .16       0
Bank Sta=4821.1,5104.4
XS Rating Curve= 0 ,0
Exp/Cntr=0.3,0.1

Type RM Length L Ch R = 1 ,9014    ,435,435,435
BEGIN DESCRIPTION:
UNT 110 IN CACR 19.0
END DESCRIPTION:
XS GIS Cut Line= 3
      3688599.65     10709260.17      3687999.61     10709610.19
       3688049.6     10710060.15
#Sta/Elev= 30
  4330.9  338.54  4344.6  339.45  4381.8  335.81  4384.8  334.23  4388.8  332.13
  4403.3  330.33  4440.5  316.41  4456.2  313.09    4495  308.74  4527.8  304.72
  4619.3  304.95  4761.2  304.66  4851.7  305.42  4859.8  304.64  4931.7  305.46
  4944.5  301.86  4967.7  299.61  4987.4  294.08  4990.2  293.58  4993.4  294.08
  5017.7   300.2  5086.5  300.93  5287.2  302.31  5317.4  304.83  5331.5  305.71
  5335.2  306.14  5407.9  317.23    5428     322  5458.2   333.8  5478.3  337.38
#Mann= 12 ,-1 , 0
  4330.9     .12       0  4384.8     .16       0    4495     .12       0
  4619.3     .07       0  4761.2     .12       0  4851.7     .07       0
  4859.8     .05       0  4987.4     .07       0  4993.4     .05       0
  5086.5     .05       0  5331.5     .12       0  5335.2     .16       0
Bank Sta=4931.7,5317.4
XS Rating Curve= 0 ,0
Exp/Cntr=0.3,0.1

Type RM Length L Ch R = 1 ,8579    ,469,469,469
BEGIN DESCRIPTION:
UNT 110 IN CACR 18.0
END DESCRIPTION:
XS GIS Cut Line= 3
       3687799.6      10709010.2      3687649.61     10709410.19
      3687199.62     10709960.17
#Sta/Elev= 30
  4557.2  337.59  4621.3  331.85  4712.9  312.41  4781.5  303.27  4804.3  300.92
  4974.6  298.76    4995  295.61  4997.8  295.11    5001  295.61  5005.9   298.3
  5012.4  296.59  5026.7  298.59  5076.3  296.76  5084.2  299.37  5135.2  302.23
  5234.4  304.24  5304.5  305.47  5314.3  301.07  5325.3  299.73  5346.2  305.46
  5368.4   300.5  5374.9  304.77  5382.8  301.11  5403.6  303.28  5424.4  310.09
  5475.4  311.96  5524.9  318.32  5552.9     327  5574.4  330.23    5695  337.84
#Mann= 7 ,-1 , 0
  4557.2     .16       0  4804.3     .12       0    4995     .07       0
    5001     .12       0  5135.2     .07       0  5234.4     .12       0
  5314.3     .07       0
Bank Sta=4781.5,5403.6
XS Rating Curve= 0 ,0
Exp/Cntr=0.3,0.1

Type RM Length L Ch R = 1 ,8110    ,451,451,451
BEGIN DESCRIPTION:
UNT 110 IN CACR 17.0
END DESCRIPTION:
XS GIS Cut Line= 3
      3687649.58     10708910.22      3687249.61     10709310.19
       3686999.6      10709460.2
#Sta/Elev= 30
  4397.3  335.25  4409.7  334.46  4453.8  328.63  4552.8  306.49  4588.9  304.43
    4624  304.04  4680.1  302.99  4779.1  299.81  4906.4  298.26  4959.4  293.29
  4965.9  293.29  4970.7  295.89  4994.9  291.08  4997.7  290.58  5000.9  291.08
  5007.6  292.39  5013.5  296.42    5029  295.77  5034.9  297.61    5066  297.54
  5092.7  299.85  5124.3  302.45  5182.6  314.24  5196.2  321.17  5219.5  328.88
  5231.2   330.9  5240.9  336.08  5246.7  334.45  5251.6  339.43  5254.5  339.43
#Mann= 7 ,-1 , 0
  4397.3     .16       0  4409.7     .12       0  4588.9     .16       0
    4624     .12       0  4994.9     .07       0  5000.9     .12       0
  5092.7     .16       0
Bank Sta=4680.1,5124.3
XS Rating Curve= 0 ,0
Exp/Cntr=0.3,0.1

Type RM Length L Ch R = 1 ,7659    ,387,387,387
BEGIN DESCRIPTION:
UNT 110 IN CACR 16.0
END DESCRIPTION:
XS GIS Cut Line= 3
       3687199.6      10708610.2      3686899.61     10709060.19
       3686849.6     10709260.22
#Sta/Elev= 30
  4481.1  340.95  4539.7  336.59  4553.2  333.76  4575.7  323.07  4589.2  319.73
  4596.8  315.25  4611.8  314.25  4638.8  305.37  4674.9  301.46    4687   300.6
  4834.1  297.77  4942.3  297.97  4985.9  295.22  4993.4  291.44  4996.4  291.27
  4999.1  290.77  5002.4  291.27  5008.4  294.76  5018.9  296.51    5040  297.01
  5045.1  299.33  5063.1  303.52  5073.5  305.04  5086.3  311.57  5114.7  317.28
  5127.6  324.19  5155.9  328.86  5176.5  334.23  5191.2  335.51  5228.1  339.32
#Mann= 5 ,-1 , 0
  4481.1     .16       0    4687     .12       0  4996.4     .07       0
  5002.4     .12       0  5191.2     .16       0
Bank Sta=4674.9,5063.1
XS Rating Curve= 0 ,0
Exp/Cntr=0.3,0.1

Type RM Length L Ch R = 1 ,7272    ,428,428,428
BEGIN DESCRIPTION:
UNT 110 IN CACR 15.0
END DESCRIPTION:
XS GIS Cut Line= 3
      3686549.61     10708610.21      3686599.61     10708810.19
      3686799.59     10709310.14
#Sta/Elev= 30
  4783.3  341.22  4834.8   340.3  4856.6  336.91  4865.7  336.32  4883.8  332.22
  4888.9  327.65  4896.7  324.33    4907  322.96    4925     318  4930.2  315.64
  4937.9  309.81  4948.2  307.64  4962.9   301.7  4966.2  300.61  4979.1  294.16
  4995.9  291.74  4998.6  291.24  5001.9  291.74    5011   292.9  5021.7  297.74
  5075.6  296.13  5183.3   296.4  5219.6  299.02  5226.4  301.34  5258.7  304.37
  5334.1  318.73  5365.5  322.78  5429.7  331.65  5441.8  334.54  5527.9  342.24
#Mann= 6 ,-1 , 0
  4783.3     .05       0  4856.6     .16       0  4962.9     .12       0
  4995.9     .07       0  5001.9     .12       0  5365.5     .16       0
Bank Sta=4966.2,5226.4
XS Rating Curve= 0 ,0
Exp/Cntr=0.3,0.1

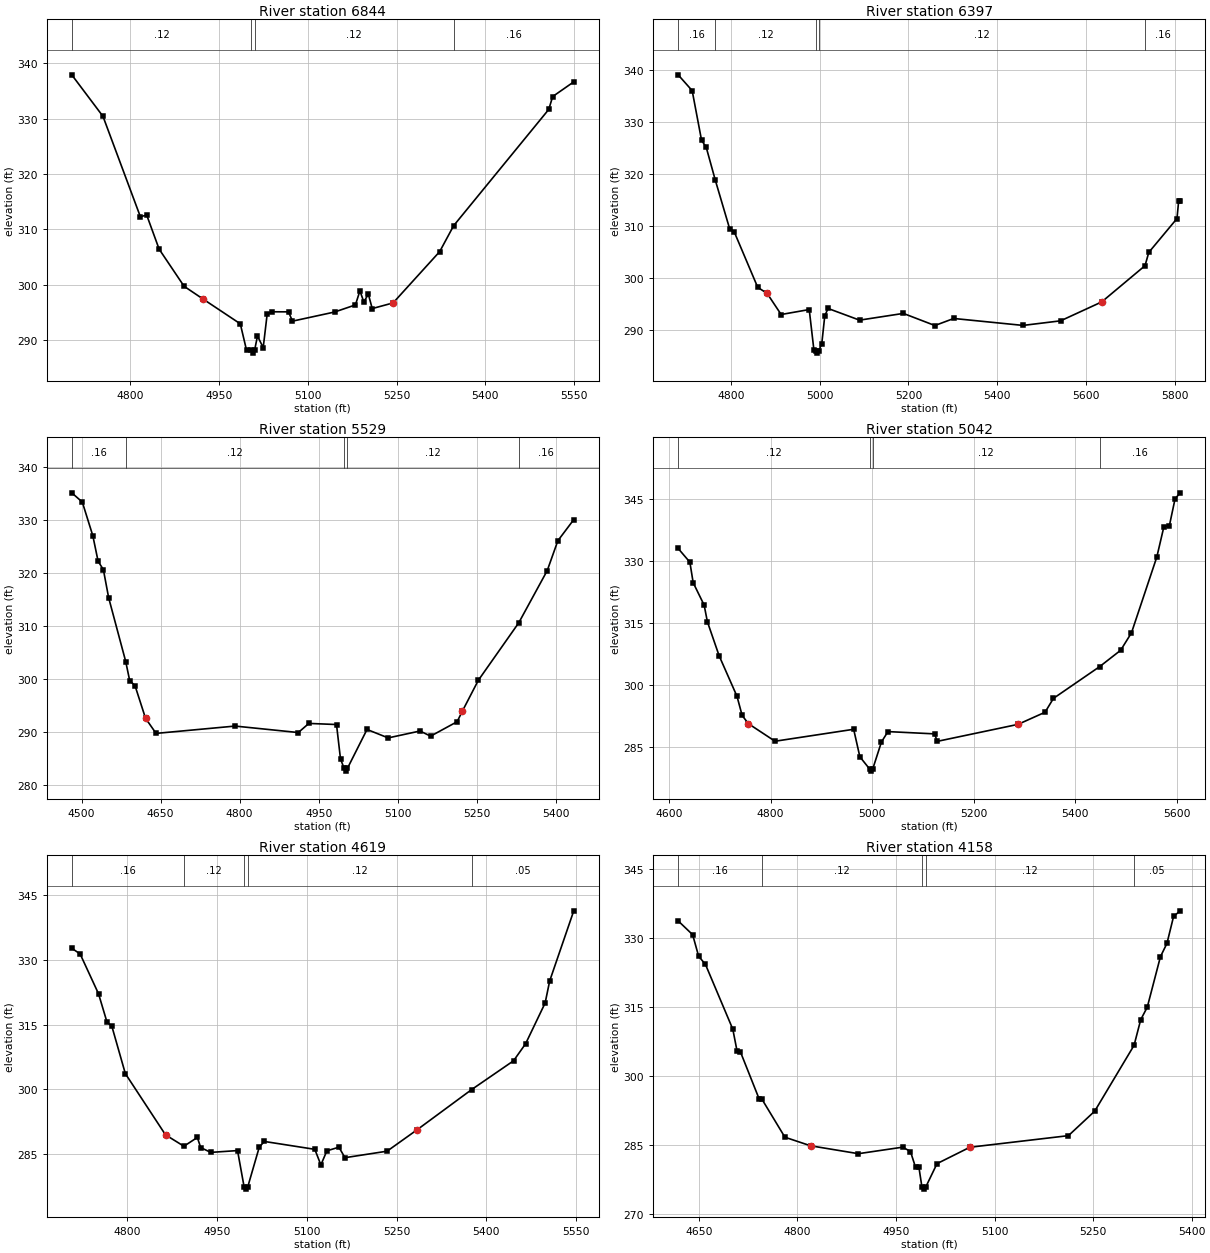
Type RM Length L Ch R = 1 ,6844    ,447,447,447
BEGIN DESCRIPTION:
UNT 110 IN CACR 14.0
END DESCRIPTION:
XS GIS Cut Line= 3
       3686349.6     10708710.22      3686249.61     10709010.19
      3686649.61     10709360.19
#Sta/Elev= 30
  4701.5  337.89  4754.2   330.4  4817.4  312.27    4828   312.6    4849  306.44
  4891.2  299.73  4922.8  297.46  4986.1  292.96  4996.6  288.21  5004.2  288.17
  5006.9  287.67  5010.2  288.17  5015.1  290.75  5024.8  288.67  5031.5  294.74
  5039.1  295.13  5067.5  295.12  5074.2  293.44  5145.4  295.09  5180.5  296.37
  5188.1  298.91  5194.7  296.91  5202.3  298.31  5208.9  295.71  5244.1  296.73
  5322.8  305.99  5346.4  310.67    5507  331.65  5513.6  333.97  5549.2  336.62
#Mann= 4 ,-1 , 0
  4701.5     .12       0  5004.2     .07       0  5010.2     .12       0
  5346.4     .16       0
Bank Sta=4922.8,5244.1
XS Rating Curve= 0 ,0
Exp/Cntr=0.3,0.1

Type RM Length L Ch R = 1 ,6397    ,868,868,868
BEGIN DESCRIPTION:
UNT 110 IN CACR 13.0
END DESCRIPTION:
XS GIS Cut Line= 3
      3686299.58      10708560.2      3685999.61     10708660.19
      3685399.64     10709210.16
#Sta/Elev= 30
  4681.5  338.99  4713.1  335.96  4734.2  326.45  4744.7  325.11  4765.2  318.79
  4797.4  309.51    4808  308.85  4860.7  298.26  4881.7  297.12  4913.4  293.06
  4976.6  294.01  4987.2  286.22  4992.1  286.16  4994.8  285.66  4998.1  286.16
  5004.8  287.42  5011.6   292.8    5019  294.22  5089.9  291.98  5188.5  293.27
  5259.5  290.95    5302   292.3    5458  290.97  5542.5  291.85    5635  295.47
  5732.6  302.42    5741  304.96  5804.5  311.45  5808.2  314.74  5811.6  314.74
#Mann= 5 ,-1 , 0
  4681.5     .16       0  4765.2     .12       0  4992.1     .07       0
  4998.1     .12       0  5732.6     .16       0
Bank Sta=4881.7,5635
XS Rating Curve= 0 ,0
Exp/Cntr=0.3,0.1

Type RM Length L Ch R = 1 ,5529    ,487,487,487
BEGIN DESCRIPTION:
UNT 110 IN CACR 11.0
END DESCRIPTION:
XS GIS Cut Line= 3
      3685199.61     10708110.17      3685199.61     10708610.19
      3685149.61      10709060.2
#Sta/Elev= 30
  4481.3  335.12  4501.3  333.38  4521.3  327.02  4531.3  322.22  4541.3  320.65
  4551.3  315.36  4583.7  303.33  4591.3  299.71  4601.3   298.8  4621.3  292.64
  4641.3  289.79  4791.3  291.17  4911.3  289.95  4931.3  291.67  4983.8  291.46
  4991.4  284.95  4998.4  283.18  5001.2  282.68  5004.4  283.18  5041.7  290.53
  5081.9  288.94  5142.3  290.24  5162.4  289.27  5212.7  291.99  5222.8  294.01
    5253   299.8  5329.7  310.63  5383.8  320.48  5403.9  326.09  5434.1  330.07
#Mann= 5 ,-1 , 0
  4481.3     .16       0  4583.7     .12       0  4998.4     .07       0
  5004.4     .12       0  5329.7     .16       0
Bank Sta=4621.3,5222.8
XS Rating Curve= 0 ,0
Exp/Cntr=0.3,0.1

Type RM Length L Ch R = 1 ,5042    ,423,423,423
BEGIN DESCRIPTION:
UNT 110 IN CACR 10.0
END DESCRIPTION:
XS GIS Cut Line= 3
      3684549.59     10708260.15      3684749.61     10708610.19
      3684549.61     10709160.19
#Sta/Elev= 30
  4617.9  332.99    4641  329.67  4647.5  324.71  4669.1  319.28  4675.5  315.26
  4698.6  307.03  4733.8  297.22  4743.9   292.6  4756.2  290.61  4808.7  286.36
  4963.5  289.25  4975.7   282.6    4995  279.63  4997.8  279.13    5001  279.63
  5018.2  286.18    5031  288.69  5122.8  288.14  5128.1  286.33  5287.1  290.44
  5340.3  293.37  5356.9  296.73    5448  304.42  5489.2  308.36  5510.5  312.58
  5560.4  330.92  5574.4  338.29    5585  338.42  5596.3  344.98  5606.3  346.44
#Mann= 4 ,-1 , 0
  4617.9     .12       0    4995     .07       0    5001     .12       0
    5448     .16       0
Bank Sta=4756.2,5287.1
XS Rating Curve= 0 ,0
Exp/Cntr=0.3,0.1

Type RM Length L Ch R = 1 ,4619    ,461,461,461
BEGIN DESCRIPTION:
UNT 110 IN CACR 9.0
END DESCRIPTION:
XS GIS Cut Line= 3
      3684499.59     10708260.22      3684349.61     10708560.19
      3684299.61     10709060.22
#Sta/Elev= 30
  4707.9  332.74  4721.8  331.44  4752.6  322.17  4766.6  315.64  4774.9  314.59
  4797.3  303.65  4864.4  289.42  4895.1  286.78  4917.5  288.82  4923.1  286.47
  4939.9  285.35  4984.6  285.77  4995.6  277.32  4998.3  276.82  5001.6  277.32
  5020.9  286.58  5029.3  287.89  5113.6  286.06  5123.7  282.44  5133.7  285.71
  5153.8  286.56  5163.9  284.12  5234.2  285.63  5284.5  290.62  5375.4  299.94
  5445.3  306.62  5465.4  310.57    5498  320.03  5505.6  325.15  5545.8  341.44
#Mann= 5 ,-1 , 0
  4707.9     .16       0  4895.1     .12       0  4995.6     .07       0
  5001.6     .12       0  5375.4     .05       0
Bank Sta=4864.4,5284.5
XS Rating Curve= 0 ,0
Exp/Cntr=0.3,0.1

Type RM Length L Ch R = 1 ,4158    ,340,340,340
BEGIN DESCRIPTION:
UNT 110 IN CACR 8.0
END DESCRIPTION:
XS GIS Cut Line= 3
      3684049.62     10708210.15      3683949.61     10708560.19
      3683949.61     10708960.14
#Sta/Elev= 30
  4618.5  333.67  4640.6  330.66  4649.7  325.98  4660.1   324.2  4701.7  310.13
  4708.2  305.36  4713.4  305.17    4742   294.9  4746.1   294.9    4781  286.66
    4820   284.8  4892.8  283.08  4960.4   284.5  4972.1  283.55  4979.9  280.08
    4985  280.08  4989.5  275.88  4992.3  275.38  4995.5  275.88  5012.5  280.92
  5062.5  284.48  5212.5     287  5252.5  292.32  5312.4  306.63  5322.5  312.19
  5332.5  314.92  5352.5  325.87  5362.5   328.8  5372.5  334.62  5382.5  335.85
#Mann= 5 ,-1 , 0
  4618.5     .16       0  4746.1     .12       0  4989.5     .07       0
  4995.5     .12       0  5312.4     .05       0
Bank Sta=4820,5062.5
XS Rating Curve= 0 ,0
Exp/Cntr=0.3,0.1

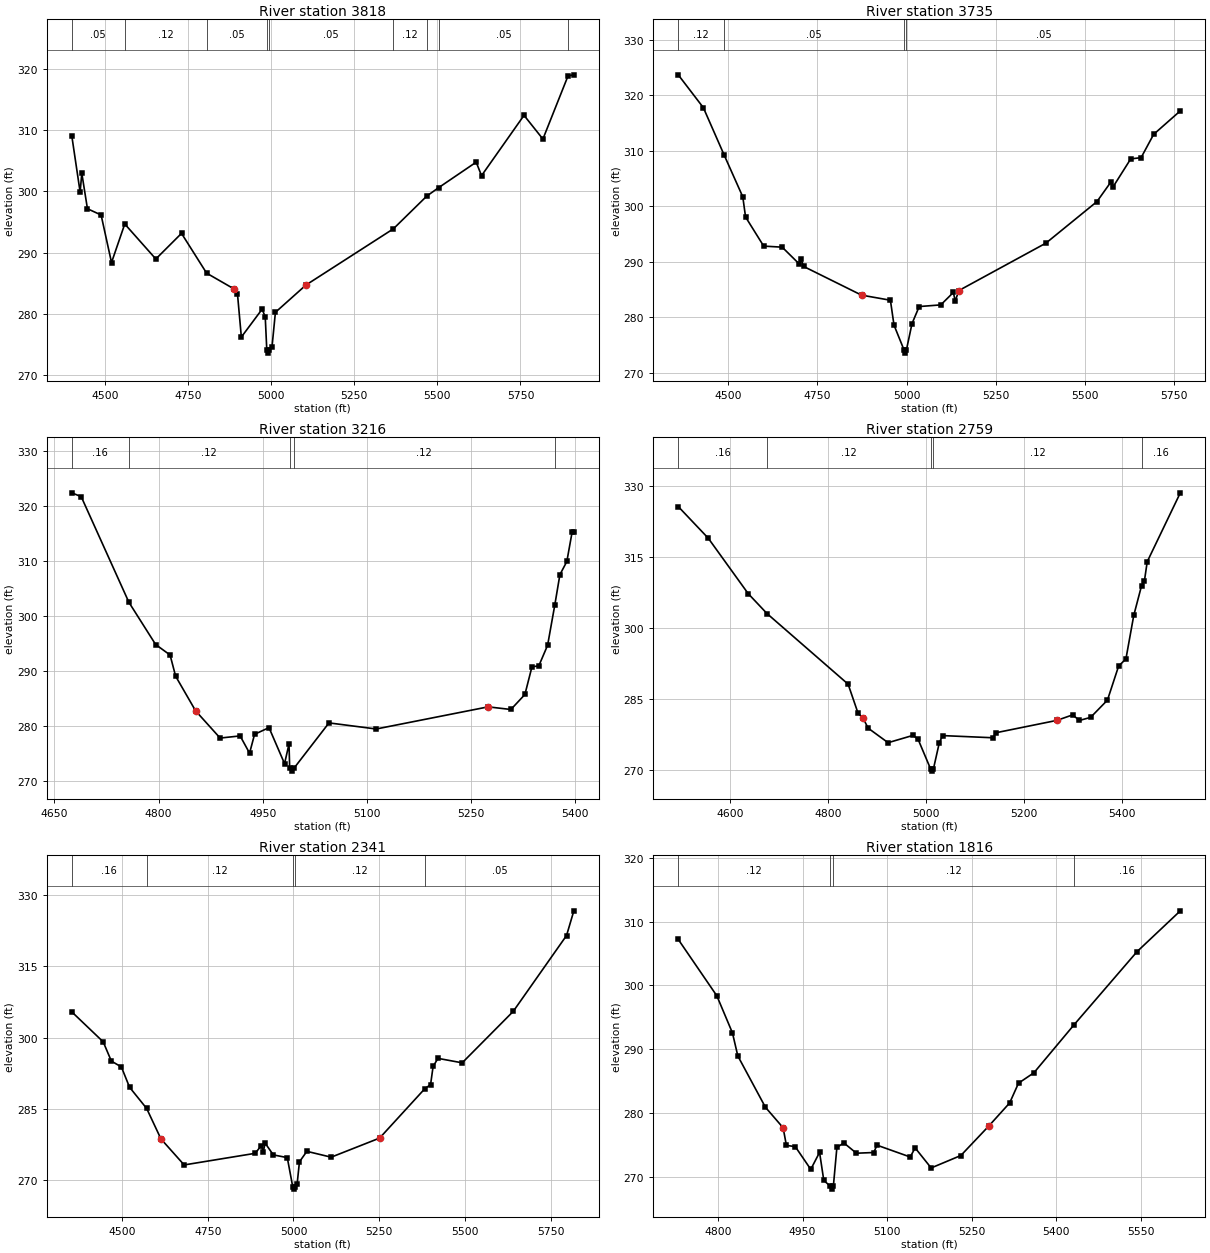
Type RM Length L Ch R = 1 ,3818    ,83,83,83
BEGIN DESCRIPTION:
Mapping XS 5ff09615
END DESCRIPTION:
XS GIS Cut Line= 6
       3683761.3     10707914.37      3683629.37      10708466.4
      3683542.56     10708928.21      3683469.64     10709101.82
      3683368.95     10709223.35      3683296.82     10709326.39
#Sta/Elev= 30
    4401  309.08  4426.1  299.88  4431.2  302.94  4448.1  297.16  4489.2  296.14
  4520.5  288.38  4560.3  294.67  4653.7  288.96  4730.9  293.14  4806.4  286.65
  4890.2  284.03  4899.2  283.25  4910.8  276.22  4973.1  280.76  4982.6  279.55
  4987.3   274.1    4990   273.6  4993.3   274.1    5003  274.63  5013.2  280.26
    5105  284.71  5367.8  293.88  5468.4  299.23  5503.9   300.6  5616.8  304.76
  5632.9  302.56  5760.6   312.4  5817.4  308.53  5893.1  318.86  5910.4  319.01
#Mann= 9 ,-1 , 0
    4401     .05       0  4560.3     .12       0  4806.4     .05       0
  4987.3     .04       0  4993.3     .05       0  5367.8     .12       0
  5468.4     .16       0  5503.9     .05       0  5893.1     .08       0
Bank Sta=4890.2,5105
XS Rating Curve= 0 ,0
Exp/Cntr=0.3,0.1

Type RM Length L Ch R = 1 ,3735    ,519,519,519
BEGIN DESCRIPTION:
UNT 110 IN CACR 7.0
END DESCRIPTION:
XS GIS Cut Line= 6
      3683667.22     10707824.37      3683566.52     10708366.08
      3683514.44     10708723.72      3683483.19     10708904.28
      3683448.46     10709011.92      3683326.96      10709171.6
#Sta/Elev= 30
  4359.2  323.69  4429.7  317.77  4488.2  309.21  4540.4  301.69  4548.2  298.05
  4599.1   292.8    4651  292.61  4698.7  289.59  4703.8  290.54  4710.9  289.14
  4873.7  283.96  4954.8  283.04  4964.9  278.55  4993.5     274  4996.3   273.5
  4999.5     274  5015.4  278.82  5035.6   281.9  5096.2   282.2  5131.6  284.45
  5136.7  282.88  5146.8  284.78  5391.4  293.34  5534.6  300.83  5573.2  304.31
  5579.5  303.45  5629.4  308.53  5658.5  308.75  5693.8  312.96  5768.6  317.19
#Mann= 4 ,-1 , 0
  4359.2     .12       0  4488.2     .05       0  4993.5     .04       0
  4999.5     .05       0
Bank Sta=4873.7,5146.8
XS Rating Curve= 0 ,0
Exp/Cntr=0.3,0.1

Type RM Length L Ch R = 1 ,3216    ,457,457,457
BEGIN DESCRIPTION:
UNT 110 IN CACR 6.0
END DESCRIPTION:
XS GIS Cut Line= 3
      3682899.64     10708210.23      3683099.61     10708460.19
      3683149.61     10708860.17
#Sta/Elev= 30
  4674.9  322.37  4688.5  321.67  4757.2  302.44  4795.7  294.76  4816.5  292.85
  4824.5  288.99  4853.3  282.68  4888.6  277.73  4917.4  278.12    4931  274.98
  4938.2  278.41    4959  279.63  4981.4  273.07  4987.8  276.65  4988.8  272.21
  4991.6  271.71  4994.8  272.21  5045.4  280.49  5113.4  279.38  5274.7  283.41
  5307.4  282.93  5327.6  285.66  5337.7  290.68  5347.7  290.89  5360.3  294.62
  5370.7  301.98    5378  307.47    5388  309.87  5395.6  315.22  5398.1  315.22
#Mann= 5 ,-1 , 0
  4674.9     .16       0  4757.2     .12       0  4988.8     .07       0
  4994.8     .12       0  5370.7     .16       0
Bank Sta=4853.3,5274.7
XS Rating Curve= 0 ,0
Exp/Cntr=0.3,0.1

Type RM Length L Ch R = 1 ,2759    ,418,418,418
BEGIN DESCRIPTION:
UNT 110 IN CACR 5.0
END DESCRIPTION:
XS GIS Cut Line= 3
      3682799.61     10708160.19      3682699.61     10708660.19
      3683149.63      10708910.2
#Sta/Elev= 30
    4494  325.69  4555.2  319.01  4636.8  307.28  4675.2  303.07  4840.7  288.15
  4861.1  281.98  4871.3  280.96  4881.5  278.86  4922.3  275.78  4973.3  277.33
  4983.5   276.5  5008.9  270.27  5011.7  269.77  5014.9  270.27  5026.8  275.76
  5033.6  277.28  5136.6  276.82  5142.3  277.88    5267   280.5    5299  281.66
  5312.8  280.48  5335.6  281.13    5370  284.78  5392.8  291.98  5407.7  293.48
  5423.7  302.69  5439.6  308.96  5445.5  310.02  5451.2  314.04  5518.7  328.59
#Mann= 5 ,-1 , 0
    4494     .16       0  4675.2     .12       0  5008.9     .07       0
  5014.9     .12       0  5439.6     .16       0
Bank Sta=4871.3,5267
XS Rating Curve= 0 ,0
Exp/Cntr=0.3,0.1

Type RM Length L Ch R = 1 ,2341    ,525,525,525
BEGIN DESCRIPTION:
UNT 110 IN CACR 4.0
END DESCRIPTION:
XS GIS Cut Line= 3
      3681749.58     10708610.18      3682349.61     10708860.19
      3682949.63     10709410.21
#Sta/Elev= 30
  4353.5  305.42  4445.1  299.12  4468.9  295.08  4498.2  293.84    4522  289.58
  4571.9  285.12  4613.5  278.73  4681.2  273.26  4888.2   275.7    4906   277.3
    4912  276.08  4917.4  277.83  4941.2  275.37  4981.9   274.8  4997.8  268.68
  5000.6  268.18  5003.8  268.68  5010.6  269.24  5017.4  273.92    5039  276.12
  5109.9  274.89  5251.1   278.9  5383.4  289.31  5399.7  290.12  5407.1  293.95
  5421.3  295.65  5491.9  294.71  5640.8  305.52  5796.2  321.45  5817.5  326.64
#Mann= 5 ,-1 , 0
  4353.5     .16       0  4571.9     .12       0  4997.8     .07       0
  5003.8     .12       0  5383.4     .05       0
Bank Sta=4613.5,5251.1
XS Rating Curve= 0 ,0
Exp/Cntr=0.3,0.1

Type RM Length L Ch R = 1 ,1816    ,516,516,516
BEGIN DESCRIPTION:
UNT 110 IN CACR 3.0
END DESCRIPTION:
XS GIS Cut Line= 2
      3681759.64      10708787.1      3682206.74     10709556.53
#Sta/Elev= 30
  4729.7  307.21  4798.1  298.37  4825.8  292.55  4835.3  288.94  4884.2   280.9
  4915.6  277.68  4921.4  274.92  4937.2  274.72  4964.6  271.16  4980.2  273.82
  4987.7  269.42  4998.7  268.56  5001.5  268.06  5004.7  268.56  5010.9  274.59
  5023.2  275.31  5045.5  273.69  5076.2   273.8    5082  274.95  5140.8   273.1
  5149.6  274.52    5178  271.38  5230.6  273.33  5279.8  277.92  5317.1  281.57
  5332.8  284.67  5360.1   286.3  5431.3  293.83  5542.9  305.29  5619.6  311.69
#Mann= 4 ,-1 , 0
  4729.7     .12       0  4998.7     .07       0  5004.7     .12       0
  5431.3     .16       0
Bank Sta=4915.6,5279.8
XS Rating Curve= 0 ,0
Exp/Cntr=0.3,0.1

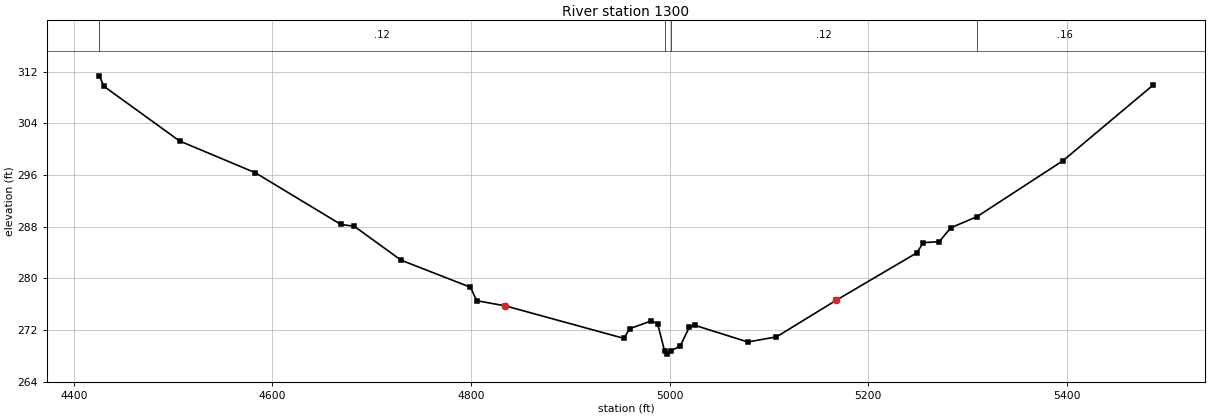
Type RM Length L Ch R = 1 ,1300    ,749,749,749
BEGIN DESCRIPTION:
UNT 110 IN CACR 2.0
END DESCRIPTION:
XS GIS Cut Line= 3
      3681634.61     10708776.66      3681447.12     10709214.15
      3681723.14     10709729.74
#Sta/Elev= 30
  4425.8  311.34  4430.4  309.72  4506.6  301.26  4582.8  296.35    4669  288.35
  4682.5  288.06  4729.6  282.82  4799.5  278.63  4805.8  276.55  4834.8  275.74
    4954  270.72  4959.8  272.21  4981.8  273.43    4988  272.98    4995  268.78
  4997.8  268.28    5001  268.78  5010.7   269.5    5020  272.48  5025.7  272.73
  5078.8  270.16  5107.7  270.95  5167.9  276.62  5248.9  283.94  5255.6  285.53
  5271.6  285.68  5283.2  287.83  5309.4  289.53  5396.4  298.23  5486.6  309.86
#Mann= 4 ,-1 , 0
  4425.8     .12       0    4995     .07       0    5001     .12       0
  5309.4     .16       0
Bank Sta=4834.8,5167.9
XS Rating Curve= 0 ,0
Exp/Cntr=0.3,0.1