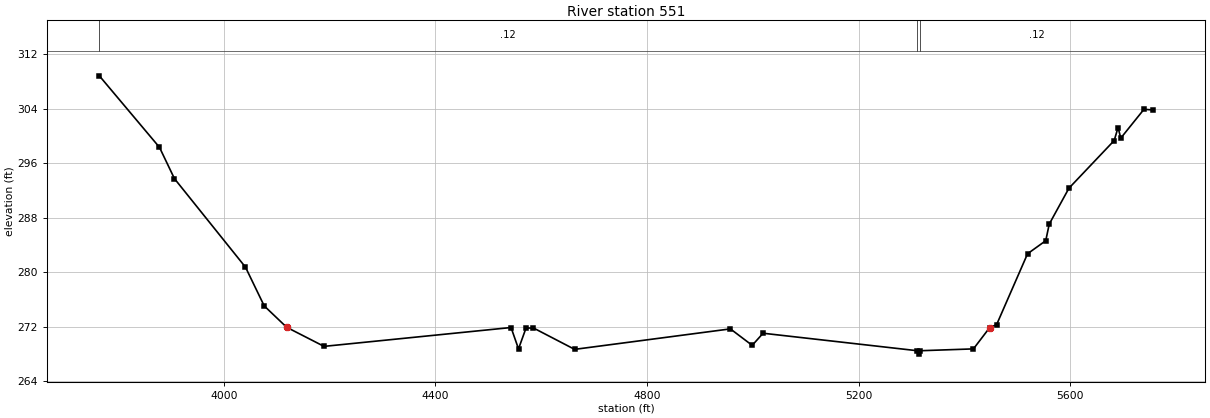
HEC-RAS study UNT 110 IN CACR.prj: UNT 110 IN CACR Base Level Engineering

--- UNT 110 IN CACR.g01 (geometry) --- (continued)

Type RM Length L Ch R = 1 ,551     ,0,0,0
BEGIN DESCRIPTION:
UNT 110 IN CACR 1.0
END DESCRIPTION:
XS GIS Cut Line= 4
      3681452.29      10708662.1      3680785.66     10709323.52
       3680874.2      10709682.9      3681540.83     10709828.72
#Sta/Elev= 30
  3764.5  308.86  3878.2  298.35  3906.5  293.75  4040.8  280.74  4076.2  275.05
  4118.6  271.91  4189.3   269.1  4542.9  271.87    4557  268.73  4571.2  271.79
  4585.3   271.8  4663.1  268.66  4957.6  271.67  4998.8  269.25  5019.4  271.03
    5311  268.46  5313.7  267.96    5317  268.46  5417.1  268.73  5447.8  271.86
  5460.9  272.29  5519.4  282.71  5553.8  284.63  5560.4  287.07  5597.7  292.35
  5683.2  299.35  5690.5  301.26  5695.7  299.71  5739.5  303.94  5756.1  303.85
#Mann= 3 ,-1 , 0
  3764.5     .12       0    5311     .07       0    5317     .12       0
Bank Sta=4118.6,5447.8
XS Rating Curve= 0 ,0
Exp/Cntr=0.3,0.1

Chan Stop Cuts=-1
Use User Specified Reach Order=0
Composite Channel Slope=5