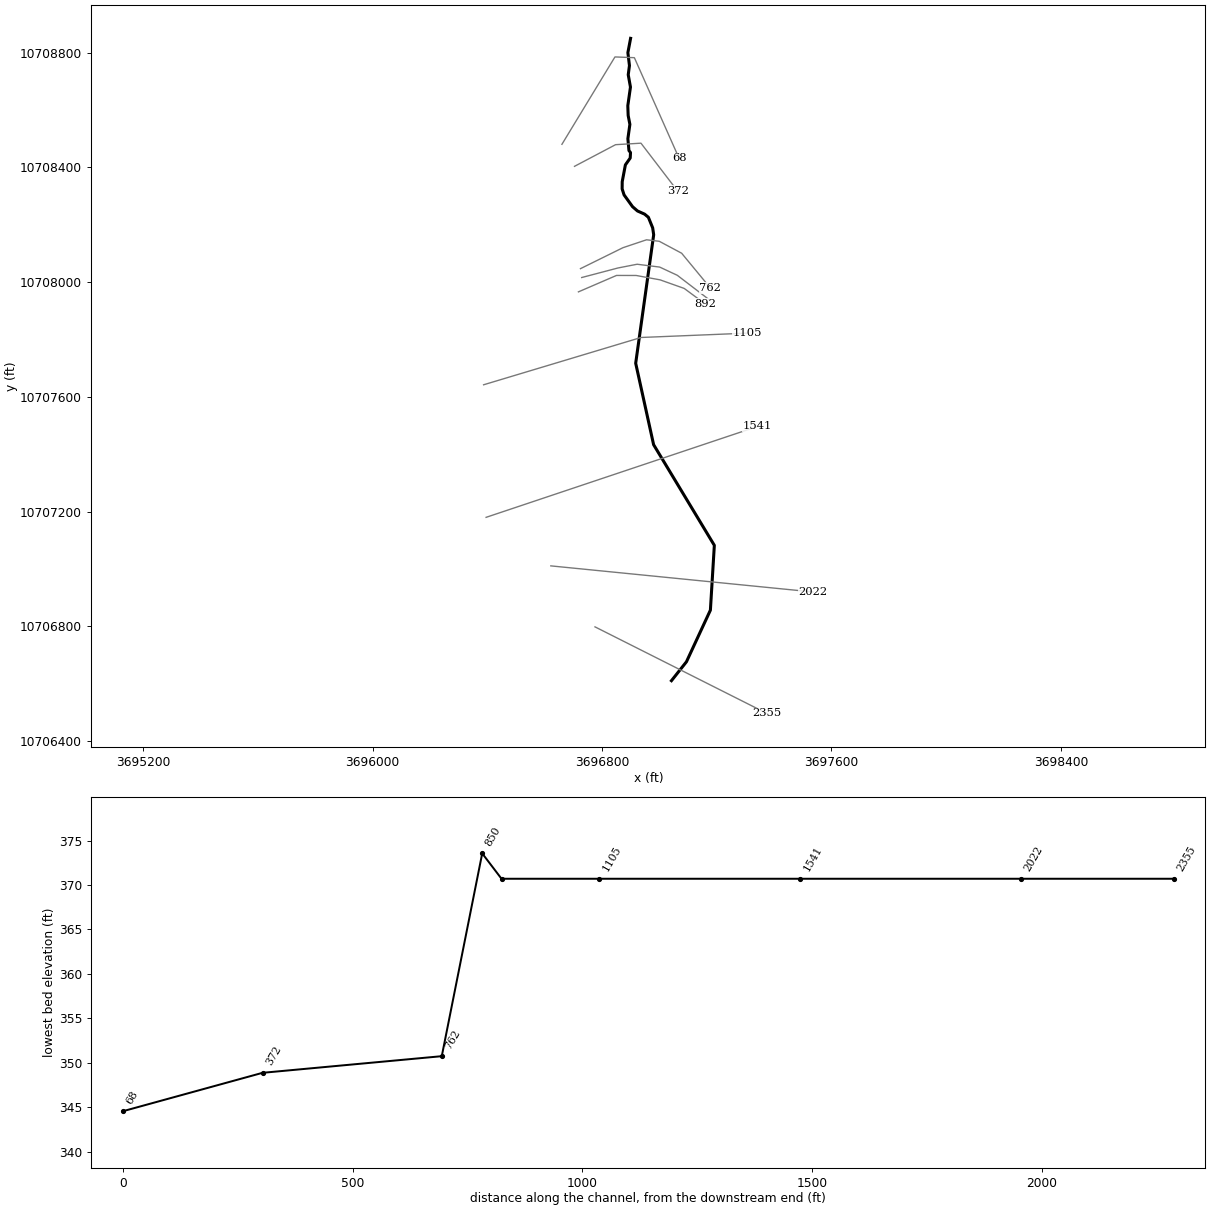
--- UNT 111 IN CACR.prj (project) ---

Proj Title=UNT 111 IN CACR Base Level Engineering
Current Plan=p01
Default Exp/Contr=0.3,0.1
English Units
Geom File=g01
Flow File=f01
Plan File=p01
Y Axis Title=Elevation
X Axis Title(PF)=Main Channel Distance
X Axis Title(XS)=Station
BEGIN DESCRIPTION:
UNT 111 IN CACR
END DESCRIPTION:
DSS Export Rating Curves= 0
DSS Export Rating Curve Sorted= 0
DSS Export Volume Flow Curves= 0
DXF OffsetX= 0
DXF OffsetY= 0
DXF ScaleX= 1
DXF ScaleY= 10

--- UNT 111 IN CACR.p01 (plan) ---

Plan Title=Multiple Run
Short Identifier=Multiple
Geom File=g01
Flow File=f01
Subcritical Flow
K Sum by GR= 0
Std Step Tol= 0.01
Critical Tol= 0.01
Num of Std Step Trials= 20
Max Error Tol= 0.3
Flow Tol Ratio= 0.001
Split Flow NTrial= 30
Split Flow Tol= 0.02
Split Flow Ratio= 0.02
Log Output Level= 0
Friction Slope Method= 1
Unsteady Friction Slope Method= 2
Unsteady Bridges Friction Slope Method= 1
Parabolic Critical Depth
Global Vel Dist=  1 , 1 , 1
Global Log Level= 0
CheckData=True
Encroach Param= -1, 0, 0, 0
BEGIN DESCRIPTION:
Multiple Run
END DESCRIPTION:

--- UNT 111 IN CACR.f01 (steady flow) ---

Flow Title=Multiple
Number of Profiles=7
Profile Names=10-year,25-year,50-year,1pct_min,100-year,1pct_plu,500-year
River Rch & RM= UNT 111 IN CACR,Reach-1,2355
     240     311     367     320     433     585     603
River Rch & RM= UNT 111 IN CACR,Reach-1,68
     738    1022    1262    1145    1548    2093    2340
Boundary for River Rch & Prof#=UNT 111 IN CACR,Reach-1,1
Up Type=0
Dn Type=3
Dn Slope=0.005
Boundary for River Rch & Prof#=UNT 111 IN CACR,Reach-1,2
Up Type=0
Dn Type=3
Dn Slope=0.005
Boundary for River Rch & Prof#=UNT 111 IN CACR,Reach-1,3
Up Type=0
Dn Type=3
Dn Slope=0.005
Boundary for River Rch & Prof#=UNT 111 IN CACR,Reach-1,4
Up Type=0
Dn Type=3
Dn Slope=0.005
Boundary for River Rch & Prof#=UNT 111 IN CACR,Reach-1,5
Up Type=0
Dn Type=3
Dn Slope=0.005
Boundary for River Rch & Prof#=UNT 111 IN CACR,Reach-1,6
Up Type=0
Dn Type=3
Dn Slope=0.005
Boundary for River Rch & Prof#=UNT 111 IN CACR,Reach-1,7
Up Type=0
Dn Type=3
Dn Slope=0.005

--- UNT 111 IN CACR.g01 (geometry) ---

Geom Title=Existing Conditions
Program Version=4.10

River Reach=UNT 111 IN CACR ,Reach-1
Reach XY= 29
      3697041.96     10706610.03      3697094.25       10706676.
      3697177.75       10706856.       3697191.5       10707082.
      3696979.75       10707433.      3696973.95     10707459.34
      3696917.25       10707717.        3696980.       10708165.
       3696976.5       10708189.       3696961.5       10708226.
      3696948.25       10708237.       3696923.5       10708248.
      3696906.25       10708263.      3696876.75       10708304.
        3696870.       10708325.      3696870.25       10708350.
       3696881.3     10708408.64      3696898.16     10708432.64
       3696899.2     10708451.74      3696893.77     10708458.58
        3696890.       10708500.        3696897.       10708550.
        3696891.       10708581.      3696889.75       10708615.
        3696899.       10708680.      3696891.25       10708723.
       3696895.5       10708755.        3696890.       10708800.
       3696899.5       10708850.

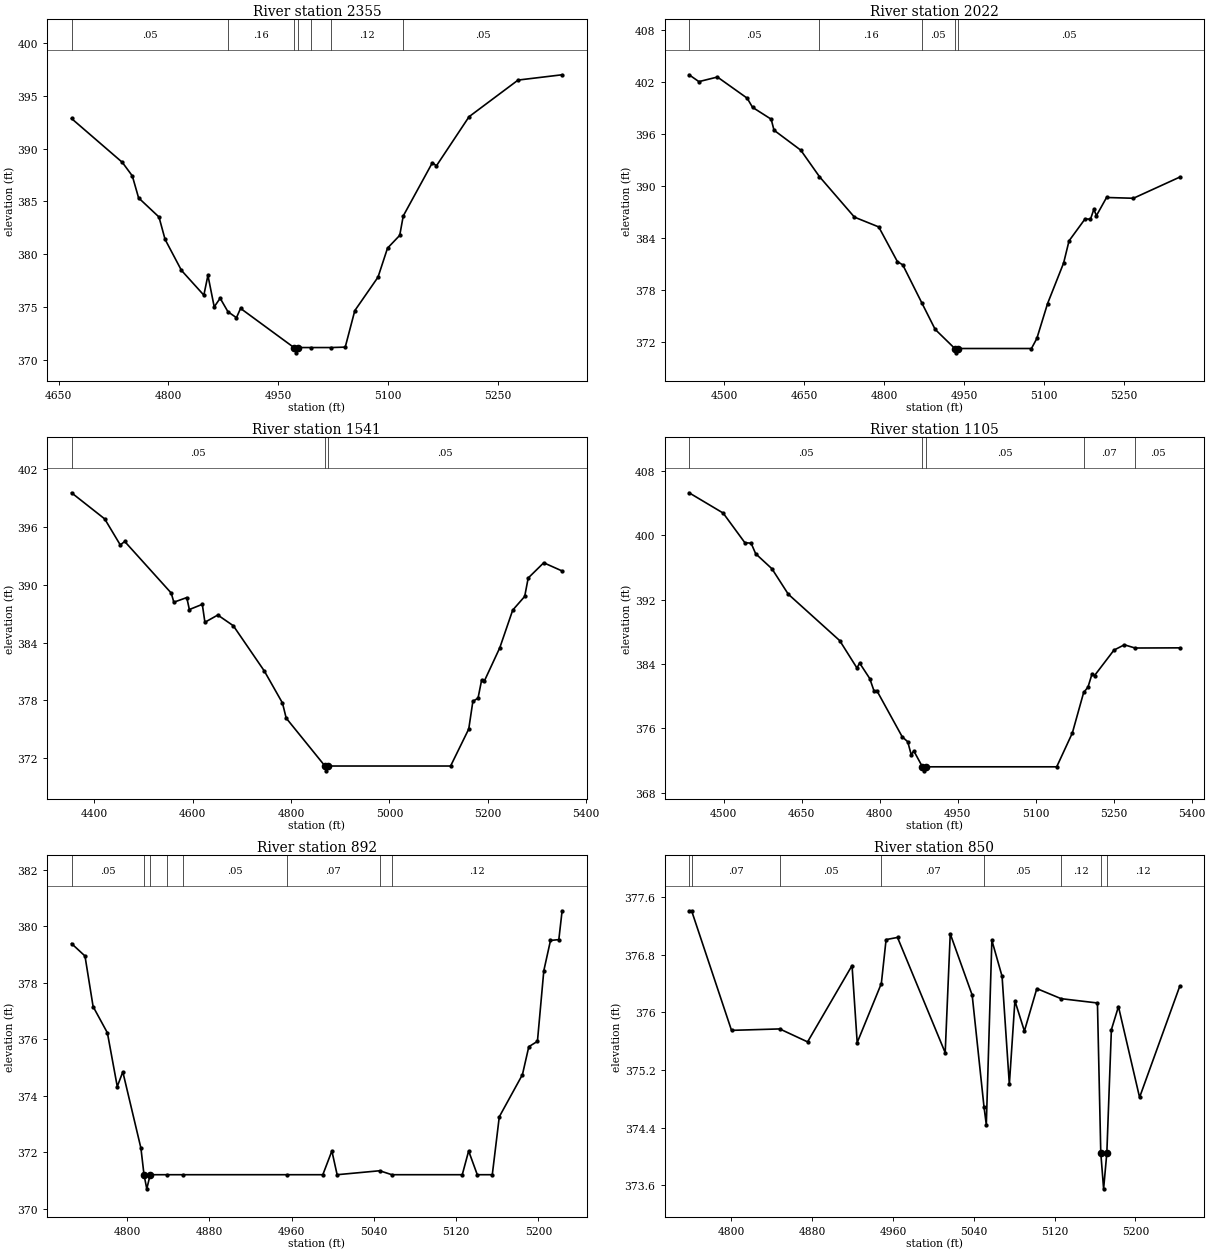
Type RM Length L Ch R = 1 ,2355    ,333,333,333
BEGIN DESCRIPTION:
UNT 111 IN CACR 2.0
END DESCRIPTION:
XS GIS Cut Line= 2
      3696775.36     10706797.74      3697374.38     10706496.06
#Sta/Elev= 30
  4667.6  392.84    4737   388.7  4750.7  387.42  4759.3  385.34  4787.2  383.53
  4795.5  381.42  4817.9  378.49  4848.5  376.15  4854.1  378.02  4862.7  375.04
  4870.8  375.86  4881.5  374.58  4893.1  374.02  4898.7   374.9  4971.7   371.2
  4974.4   370.7  4977.7   371.2  4994.6   371.2  5022.5   371.2  5041.8  371.24
  5054.9  374.69  5086.6  377.85  5099.6  380.59  5116.3   381.8  5121.1  383.63
  5160.9  388.66  5166.5  388.37  5211.1  393.01  5278.1  396.47  5338.3  396.97
#Mann= 7 ,-1 , 0
  4667.6     .05       0  4881.5     .16       0  4971.7     .07       0
  4977.7     .16       0  4994.6     .07       0  5022.5     .12       0
  5121.1     .05       0
Bank Sta=4971.7,4977.7
XS Rating Curve= 0 ,0
Exp/Cntr=0.3,0.1

Type RM Length L Ch R = 1 ,2022    ,481,481,481
BEGIN DESCRIPTION:
Mapping XS f81c1388
END DESCRIPTION:
XS GIS Cut Line= 2
      3696621.32      10707010.4       3697535.9     10706919.38
#Sta/Elev= 30
  4434.8  402.81  4453.2  402.02  4487.9  402.55  4543.6  400.11  4553.7  399.05
  4588.6  397.68  4593.9  396.41  4644.1   394.1    4679  391.05  4744.6  386.37
  4790.1  385.24    4825  381.24  4835.1  380.86  4870.8  376.47  4895.8  373.41
  4932.6   371.2  4935.3   370.7  4938.6   371.2  5076.2   371.2  5086.3  372.36
  5106.4  376.39  5136.5  381.08  5146.6  383.63  5176.7  386.17  5186.8  386.13
    5193  387.26    5198  386.55  5216.9  388.64  5267.2  388.55  5353.9  390.99
#Mann= 5 ,-1 , 0
  4434.8     .05       0    4679     .16       0  4870.8     .05       0
  4932.6    .033       0  4938.6     .05       0
Bank Sta=4932.6,4938.6
XS Rating Curve= 0 ,0
Exp/Cntr=0.3,0.1

Type RM Length L Ch R = 1 ,1541    ,436,436,436
BEGIN DESCRIPTION:
Mapping XS 5beeb363
END DESCRIPTION:
XS GIS Cut Line= 2
      3696395.58     10707179.66      3697341.74      10707496.5
#Sta/Elev= 30
  4353.4  399.54  4420.9  396.83  4452.6  394.13  4461.6  394.49  4556.2  389.14
  4561.5  388.19  4587.8  388.67  4593.1  387.43  4619.4  387.97  4624.7  386.11
  4650.9  386.86  4682.5  385.75  4745.6  381.05  4782.5  377.73    4790  376.17
  4868.9   371.2  4871.7   370.7  4874.9   371.2  5124.4   371.2  5161.3  375.04
  5169.7  377.91  5180.2  378.24  5187.6  380.14  5192.8  379.99  5224.4  383.46
  5250.7  387.37  5275.1  388.79  5282.2   390.7  5313.8  392.28  5351.2  391.43
#Mann= 3 ,-1 , 0
  4353.4     .05       0  4868.9    .033       0  4874.9     .05       0
Bank Sta=4868.9,4874.9
XS Rating Curve= 0 ,0
Exp/Cntr=0.3,0.1

Type RM Length L Ch R = 1 ,1105    ,213,213,213
BEGIN DESCRIPTION:
Mapping XS 167e02cc
END DESCRIPTION:
XS GIS Cut Line= 3
      3696386.92     10707641.91      3696935.97     10707806.84
      3697305.87     10707821.98
#Sta/Elev= 30
  4433.4  405.27  4498.9  402.75  4540.6  399.07  4552.7     399  4561.5  397.69
  4592.8  395.82  4624.2  392.66  4723.1  386.89  4756.2  383.49  4761.4   384.1
  4780.8  382.18  4789.2  380.61  4794.4  380.68  4843.4  374.92  4853.9  374.32
  4860.5  372.73  4865.7  373.16  4882.2   371.2  4884.9   370.7  4888.2   371.2
  5140.4   371.2  5170.5  375.41  5192.2  380.44  5200.5   381.1  5208.1   382.7
  5213.1  382.54  5250.5  385.71  5270.5  386.37  5291.1  385.97  5376.9  385.99
#Mann= 5 ,-1 , 0
  4433.4     .05       0  4882.2    .033       0  4888.2     .05       0
  5192.2     .07       0  5291.1     .05       0
Bank Sta=4882.2,4888.2
XS Rating Curve= 0 ,0
Exp/Cntr=0.3,0.1

Type RM Length L Ch R = 1 ,892     ,42,42,42
BEGIN DESCRIPTION:
Mapping XS 1a4d35df
END DESCRIPTION:
XS GIS Cut Line= 6
      3696717.58     10707965.91      3696850.35     10708023.19
      3696919.03     10708023.06      3697002.36     10708007.78
      3697086.39     10707977.92      3697158.71     10707924.46
#Sta/Elev= 30
    4746  379.38  4759.1  378.94    4767  377.15  4780.9  376.22  4790.5  374.32
  4795.9  374.84  4813.5  372.14  4816.5   371.2  4819.2   370.7  4822.5   371.2
    4839   371.2  4854.2   371.2  4955.6   371.2  4990.4   371.2  4999.2  372.04
  5004.3   371.2  5045.7  371.34  5057.5   371.2    5126   371.2  5132.2  372.04
  5140.6   371.2  5155.2   371.2    5162  373.25  5184.5  374.74  5190.7  375.73
  5199.1  375.92  5205.3  378.42  5211.8  379.49  5219.9  379.52  5223.1  380.54
#Mann= 8 ,-1 , 0
    4746     .05       0  4816.5     .07       0  4822.5     .05       0
    4839     .07       0  4854.2     .05       0  4955.6     .07       0
  5045.7     .05       0  5057.5     .12       0
Bank Sta=4816.5,4822.5
XS Rating Curve= 0 ,0
Exp/Cntr=0.3,0.1

Type RM Length L Ch R = 1 ,850     ,88,88,88
BEGIN DESCRIPTION:
Mapping XS 566d084b
END DESCRIPTION:
XS GIS Cut Line= 6
      3696728.97     10708015.89      3696855.56     10708049.23
      3696922.23     10708062.25      3697000.87     10708052.35
      3697062.33     10708023.71      3697173.27     10707938.81
#Sta/Elev= 30
  4758.2  377.41  4760.7  377.41  4800.2  375.75  4847.9  375.77  4875.5  375.59
  4919.5  376.65  4924.6  375.58  4948.5   376.4  4953.2  377.01  4964.5  377.04
  5011.7  375.44  5016.7  377.09  5038.4  376.24  5050.1  374.69  5052.4  374.44
  5057.9     377    5068   376.5  5075.2     375  5080.7  376.16  5090.1  375.74
  5102.4  376.33  5126.4  376.19  5162.4  376.13  5165.7  374.05  5168.5  373.55
  5171.7  374.05  5176.2  375.76  5183.2  376.08  5204.1  374.82  5243.8  376.36
#Mann= 8 ,-1 , 0
  4758.2     .05       0  4760.7     .07       0  4847.9     .05       0
  4948.5     .07       0  5050.1     .05       0  5126.4     .12       0
  5165.7     .07       0  5171.7     .12       0
Bank Sta=5165.7,5171.7
XS Rating Curve= 0 ,0
Exp/Cntr=0.3,0.1

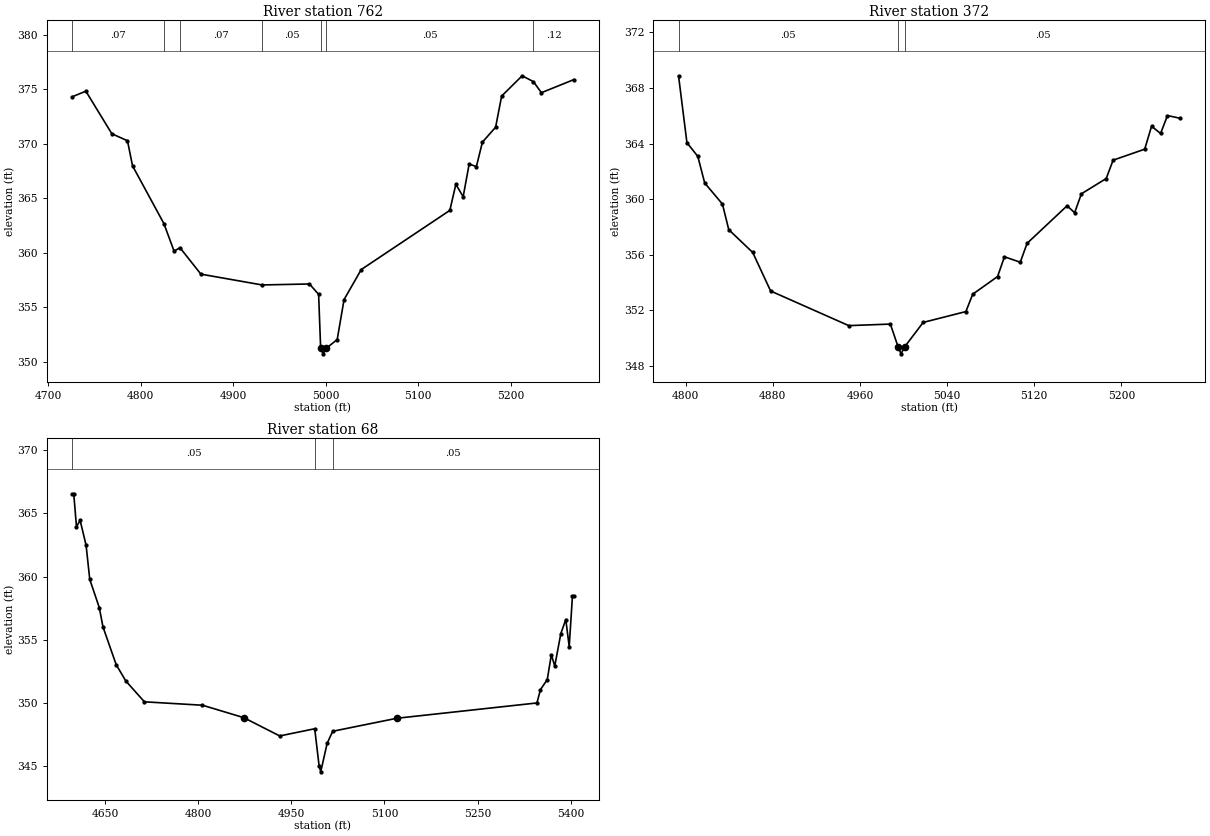
Type RM Length L Ch R = 1 ,762     ,390,390,390
BEGIN DESCRIPTION:
Mapping XS b17432ae
END DESCRIPTION:
XS GIS Cut Line= 6
      3696724.68     10708046.86      3696872.81     10708119.92
       3696955.1     10708147.52      3696999.38     10708142.32
       3697077.5     10708100.65      3697177.81      10707979.2
#Sta/Elev= 30
  4725.8  374.29  4740.7  374.81  4768.8  370.91  4785.7  370.27  4791.2  367.97
  4825.1  362.68  4836.1  360.16  4842.5  360.47  4865.1  358.05  4931.3  357.06
  4982.5  357.15  4992.4   356.2  4994.6  351.25  4997.3  350.75  5000.6  351.25
  5012.5  352.06  5019.9  355.72  5038.5  358.47  5134.3  363.89  5140.8  366.28
  5148.7  365.14  5155.2  368.14    5163   367.9  5169.5  370.14  5183.8  371.51
  5190.3  374.36  5212.5  376.22  5224.7  375.68  5233.3  374.67  5268.4  375.87
#Mann= 7 ,-1 , 0
  4725.8     .07       0  4825.1     .05       0  4842.5     .07       0
  4931.3     .05       0  4994.6    .033       0  5000.6     .05       0
  5224.7     .12       0
Bank Sta=4994.6,5000.6
XS Rating Curve= 0 ,0
Exp/Cntr=0.3,0.1

Type RM Length L Ch R = 1 ,372     ,304,304,304
BEGIN DESCRIPTION:
Mapping XS a7a48c8f
END DESCRIPTION:
XS GIS Cut Line= 4
      3696703.92     10708403.67       3696847.1     10708479.17
      3696935.65     10708484.38      3697063.27     10708317.69
#Sta/Elev= 30
  4793.5  368.88  4801.2  364.07  4811.2  363.08  4817.5  361.17  4833.8  359.65
  4839.6  357.81  4861.6  356.17    4878   353.4  4949.7  350.91  4987.9  351.02
    4995  349.38  4997.7  348.88    5001  349.38    5018  351.14  5057.2  351.92
  5063.5  353.17  5086.3  354.44  5092.6  355.86  5107.1  355.47  5113.4  356.83
  5150.1  359.53    5157  359.03  5163.2  360.39    5186  361.49  5192.3  362.81
  5221.3   363.6  5227.6  365.25  5235.9  364.73  5242.2  366.02    5254  365.82
#Mann= 3 ,-1 , 0
  4793.5     .05       0    4995     .03       0    5001     .05       0
Bank Sta=4995,5001
XS Rating Curve= 0 ,0
Exp/Cntr=0.3,0.1

Type RM Length L Ch R = 1 ,68      ,0,0,0
BEGIN DESCRIPTION:
UNT 111 IN CACR 1.0
END DESCRIPTION:
XS GIS Cut Line= 4
      3696660.06      10708480.5      3696844.93     10708785.16
      3696912.64     10708782.55      3697068.87     10708431.03
#Sta/Elev= 30
  4596.5  366.56  4599.2  366.56  4603.6  363.96  4609.5  364.45  4619.1  362.49
    4625  359.79  4640.4  357.55  4646.3  356.03  4667.6  353.04  4683.1  351.75
  4713.1   350.1  4806.7  349.83  4873.1  348.85  4931.2   347.4  4987.6  347.97
  4994.6  345.06  4997.3  344.56  5007.6  346.81  5016.6  347.77  5120.1   348.8
  5345.8  350.01  5351.5  351.07  5362.4  351.85    5369  353.83  5374.5  352.93
  5384.3   355.5  5392.3  356.61  5397.8  354.47    5403  358.45  5405.3  358.45
#Mann= 3 ,-1 , 0
  4596.5     .05       0  4987.6     .03       0  5016.6     .05       0
Bank Sta=4873.1,5120.1
XS Rating Curve= 0 ,0
Exp/Cntr=0.3,0.1

Chan Stop Cuts=-1
Use User Specified Reach Order=0
Composite Channel Slope=5