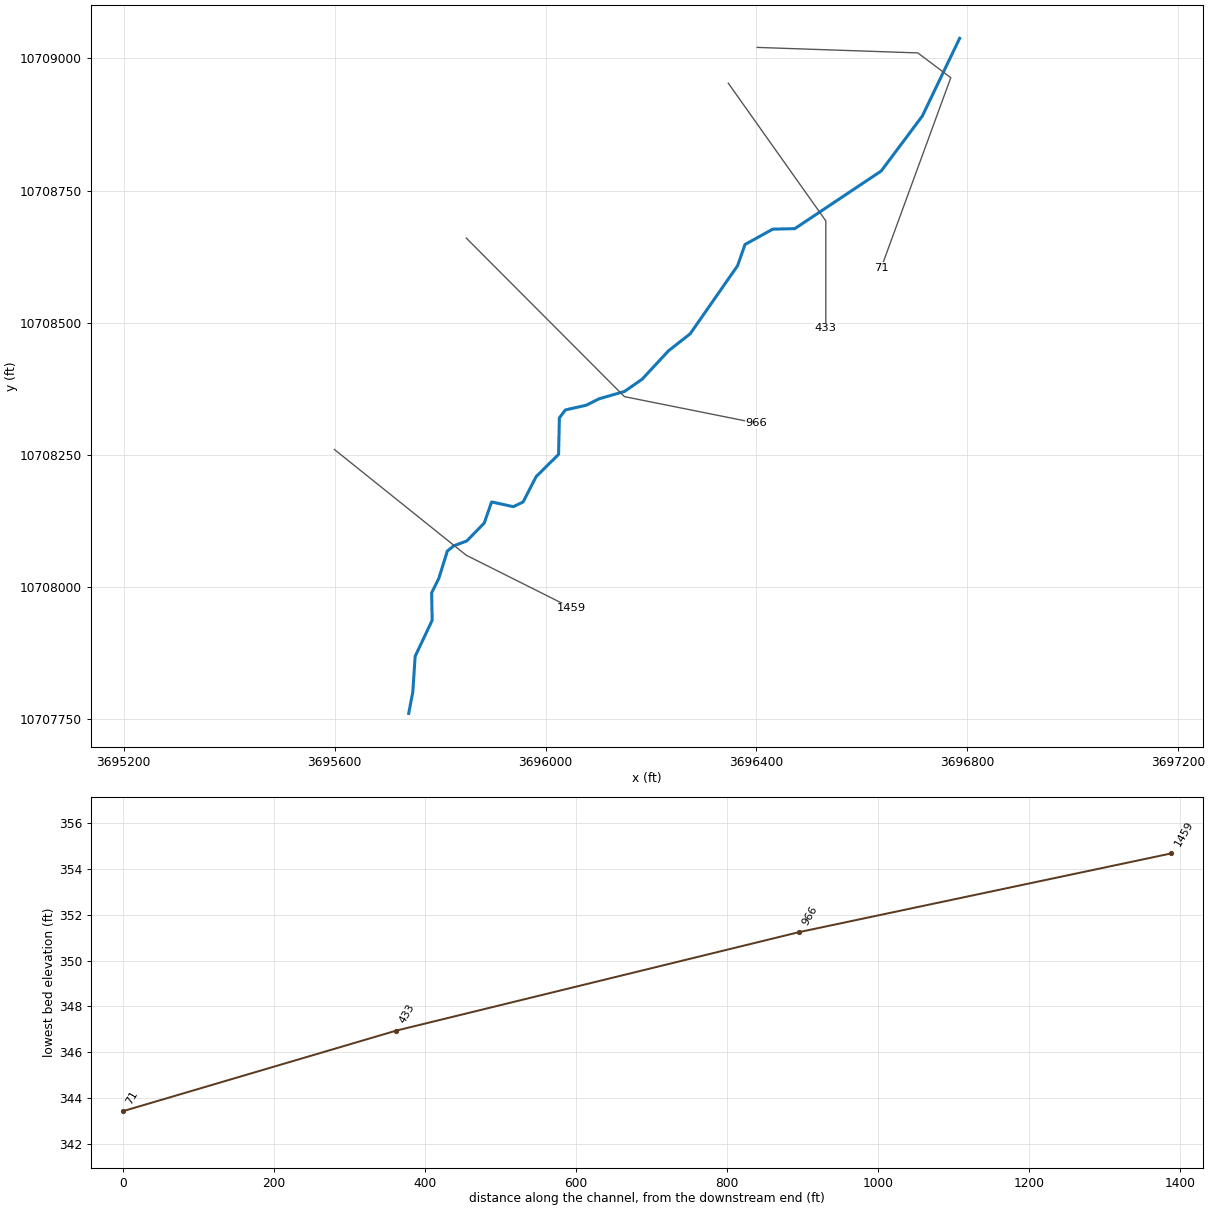
--- UNT 112 IN CACR.prj (project) ---

Proj Title=UNT 112 IN CACR Base Level Engineering
Current Plan=p01
Default Exp/Contr=0.3,0.1
English Units
Geom File=g01
Flow File=f01
Plan File=p01
BEGIN DESCRIPTION:
UNT 112 IN CACR
END DESCRIPTION:

--- UNT 112 IN CACR.p01 (plan) ---

Plan Title=Multiple Run
Short Identifier=Multiple
Geom File=g01
Flow File=f01
Subcritical Flow
K Sum by GR= 0
Std Step Tol= 0.01
Critical Tol= 0.01
Num of Std Step Trials= 20
Max Error Tol= 0.3
Flow Tol Ratio= 0.001
Split Flow NTrial= 30
Split Flow Tol= 0.02
Split Flow Ratio= 0.02
Log Output Level= 0
Friction Slope Method= 1
Unsteady Friction Slope Method= 2
Unsteady Bridges Friction Slope Method= 1
Parabolic Critical Depth
Global Vel Dist=  1 , 1 , 1
Global Log Level= 0
CheckData=True
Encroach Param= -1, 0, 0, 0
BEGIN DESCRIPTION:
Multiple Run
END DESCRIPTION:

--- UNT 112 IN CACR.f01 (steady flow) ---

Flow Title=Multiple
Number of Profiles=7
Profile Names=10-year,25-year,50-year,1pct_min,100-year,1pct_plu,500-year
River Rch & RM= UNT 112 IN CACR,Reach-1,1459
     369     490     587     519     702     949    1005
Boundary for River Rch & Prof#=UNT 112 IN CACR,Reach-1,1
Up Type=0
Dn Type=3
Dn Slope=0.005
Boundary for River Rch & Prof#=UNT 112 IN CACR,Reach-1,2
Up Type=0
Dn Type=3
Dn Slope=0.005
Boundary for River Rch & Prof#=UNT 112 IN CACR,Reach-1,3
Up Type=0
Dn Type=3
Dn Slope=0.005
Boundary for River Rch & Prof#=UNT 112 IN CACR,Reach-1,4
Up Type=0
Dn Type=3
Dn Slope=0.005
Boundary for River Rch & Prof#=UNT 112 IN CACR,Reach-1,5
Up Type=0
Dn Type=3
Dn Slope=0.005
Boundary for River Rch & Prof#=UNT 112 IN CACR,Reach-1,6
Up Type=0
Dn Type=3
Dn Slope=0.005
Boundary for River Rch & Prof#=UNT 112 IN CACR,Reach-1,7
Up Type=0
Dn Type=3
Dn Slope=0.005

--- UNT 112 IN CACR.g01 (geometry) ---

Geom Title=Existing Conditions

River Reach=UNT 112 IN CACR,Reach-1
Reach XY= 30
      3695740.50     10707761.00      3695748.25     10707801.00
      3695752.75     10707869.00      3695785.00     10707937.00
      3695784.00     10707989.00      3695797.50     10708016.00
      3695813.75     10708068.00      3695826.00     10708078.00
      3695850.50     10708087.00      3695883.75     10708121.00
      3695897.75     10708161.00      3695939.00     10708152.00
      3695957.50     10708161.00      3695982.25     10708209.00
      3696024.75     10708251.00      3696026.25     10708320.00
      3696037.50     10708335.00      3696077.50     10708344.00
      3696101.25     10708356.00      3696149.75     10708370.00
      3696183.00     10708393.00      3696233.25     10708447.00
      3696274.25     10708479.00      3696364.25     10708608.00
      3696378.25     10708648.00      3696430.75     10708677.00
      3696472.75     10708678.00      3696636.50     10708787.00
      3696714.50     10708891.00      3696785.25     10709038.00

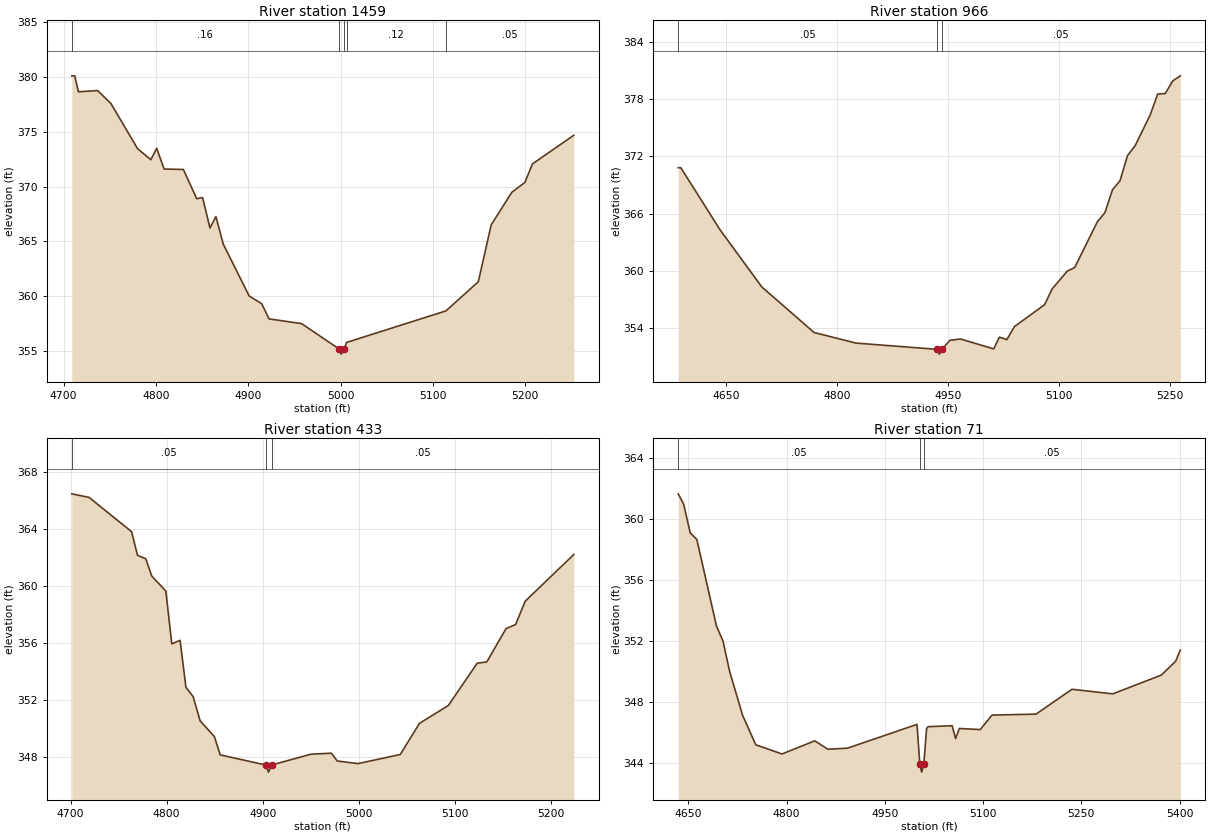
Type RM Length L Ch R = 1,1459,493,493,493
BEGIN DESCRIPTION:
UNT 112 IN CACR 3.0
END DESCRIPTION:
XS GIS Cut Line= 3
      3695599.61     10708260.19      3695849.61     10708060.19
      3696049.64     10707960.17
#Sta/Elev= 30
  4708.9  380.12  4712.1  380.12  4716.1  378.66  4736.9  378.77  4751.3  377.59
  4780.1  373.47  4794.5  372.45  4800.9  373.49  4808.9  371.60  4829.8  371.56
  4844.2  368.89  4850.6  368.99  4858.6  366.21  4865.0  367.26  4873.0  364.73
  4901.0  360.00  4914.6  359.29  4922.6  357.90  4957.8  357.47  4998.0  355.18
  5000.8  354.68  5004.0  355.18  5006.6  355.75  5114.1  358.63  5149.2  361.29
  5163.2  366.50  5185.6  369.48  5199.6  370.37  5207.9  372.07  5252.7  374.69
#Mann=5,-1,0
  4708.9    0.16       0  4998.0    0.07       0  5004.0    0.16       0
  5006.6    0.12       0  5114.1    0.05       0
Bank Sta=4998,5004
Exp/Cntr=0.3,0.1

Type RM Length L Ch R = 1,966,533,533,533
BEGIN DESCRIPTION:
UNT 112 IN CACR 2.0
END DESCRIPTION:
XS GIS Cut Line= 3
      3695849.64     10708660.16      3696149.61     10708360.19
      3696399.64     10708310.18
#Sta/Elev= 30
  4585.4  370.81  4588.9  370.81  4641.9  364.30  4698.5  358.29  4769.2  353.51
  4825.8  352.40  4935.9  351.74  4938.7  351.24  4941.9  351.74  4953.0  352.69
  4967.2  352.83  5012.2  351.79  5019.8  353.02  5030.0  352.77  5040.2  354.13
  5081.0  356.43  5091.2  358.08  5111.6  359.95  5121.8  360.34  5152.4  365.14
  5162.6  366.09  5172.8  368.49  5183.0  369.44  5193.2  372.09  5203.4  373.11
  5223.8  376.34  5234.0  378.55  5244.2  378.60  5254.4  379.93  5264.6  380.46
#Mann=3,-1,0
  4585.4    0.05       0  4935.9    0.03       0  4941.9    0.05       0
Bank Sta=4935.9,4941.9
Exp/Cntr=0.3,0.1

Type RM Length L Ch R = 1,433,362,362,362
BEGIN DESCRIPTION:
Mapping XS 671b1318
END DESCRIPTION:
XS GIS Cut Line= 3
      3696346.56     10708953.16      3696531.48     10708692.71
      3696531.48     10708489.63
#Sta/Elev= 30
  4701.3  366.49  4719.3  366.24  4763.6  363.83  4769.7  362.17  4778.3  361.93
  4784.5  360.72  4799.2  359.66  4805.4  355.95  4814.0  356.20  4820.1  352.90
  4827.6  352.24  4834.9  350.54  4849.7  349.44  4855.8  348.15  4903.3  347.44
  4906.0  346.94  4909.3  347.44  4950.2  348.20  4971.5  348.27  4977.6  347.72
  4999.3  347.54  5043.2  348.18  5063.2  350.37  5093.2  351.62  5123.2  354.59
  5133.2  354.68  5153.2  357.02  5163.2  357.31  5173.2  358.95  5223.8  362.23
#Mann=3,-1,0
  4701.3    0.05       0  4903.3    0.03       0  4909.3    0.05       0
Bank Sta=4903.3,4909.3
Exp/Cntr=0.3,0.1

Type RM Length L Ch R = 1,71,0,0,0
BEGIN DESCRIPTION:
UNT 112 IN CACR 1.0
END DESCRIPTION:
XS GIS Cut Line= 4
      3696401.27     10709020.84      3696705.96     10709010.42
      3696768.46     10708963.54      3696636.32     10708603.41
#Sta/Elev= 30
  4634.5  361.66  4642.8  360.98  4652.8  359.10  4662.9  358.67  4692.9  352.99
  4702.9  352.01  4712.9  350.03  4732.9  347.13  4752.9  345.21  4792.9  344.61
  4843.0  345.47  4863.0  344.92  4893.0  344.99  4999.1  346.55  5003.4  343.92
  5006.2  343.42  5009.4  343.92  5013.7  346.27  5016.1  346.40  5052.7  346.46
  5058.0  345.62  5063.7  346.28  5095.6  346.21  5113.7  347.16  5180.8  347.22
  5235.7  348.85  5298.0  348.55  5372.1  349.78  5393.9  350.68  5401.1  351.42
#Mann=3,-1,0
  4634.5    0.05       0  5003.4    0.03       0  5009.4    0.05       0
Bank Sta=5003.4,5009.4
Exp/Cntr=0.3,0.1

Chan Stop Cuts=-1