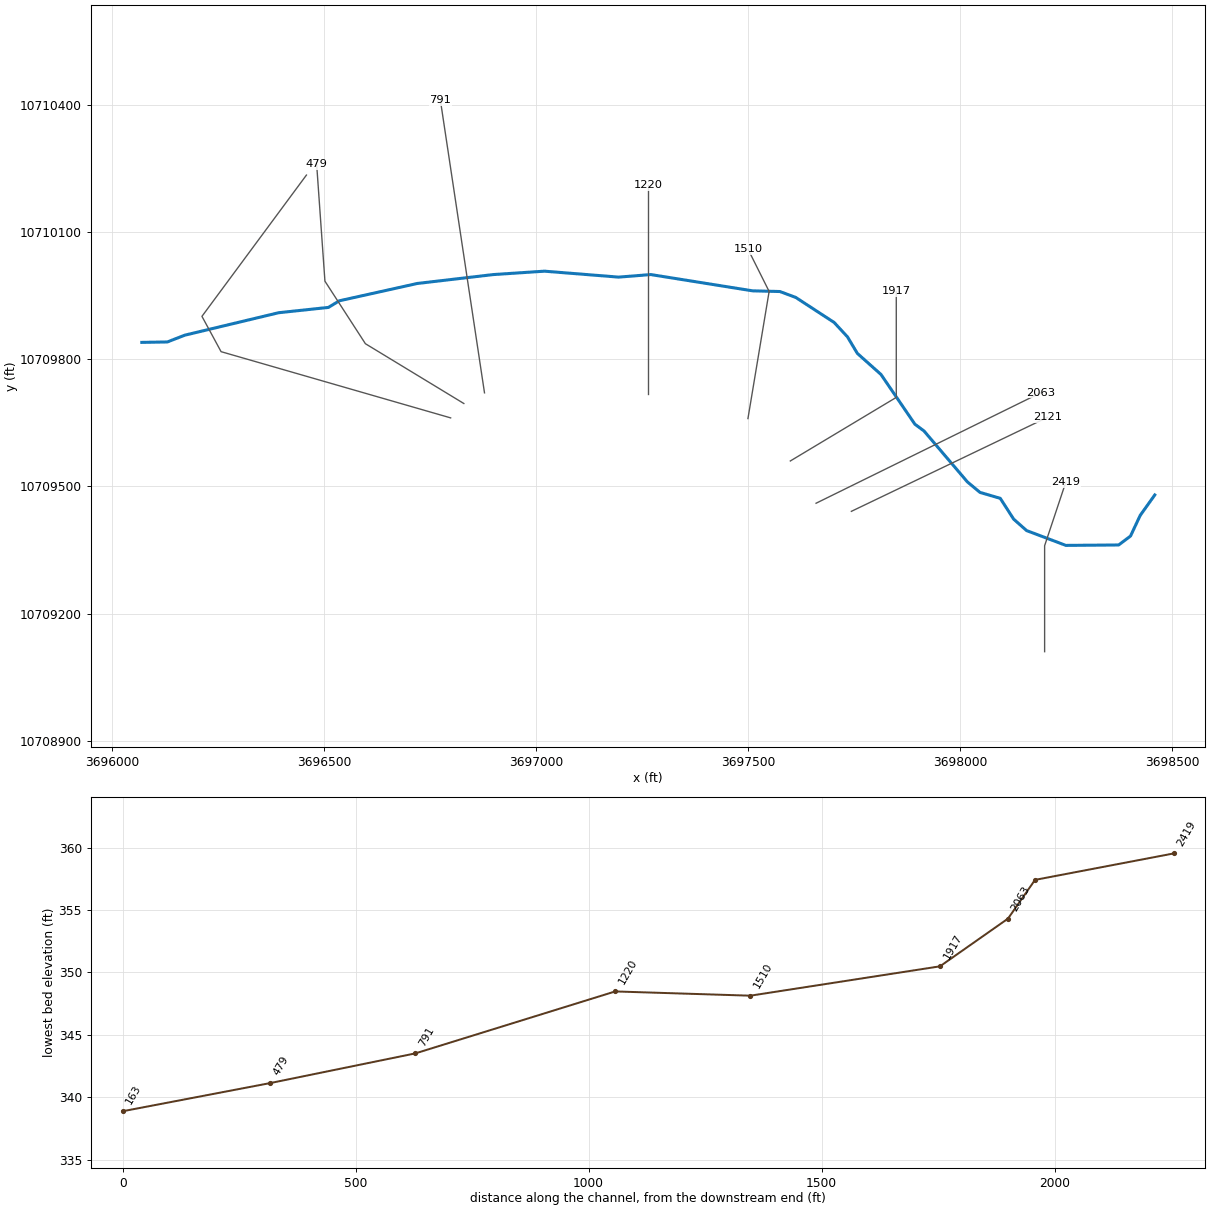
--- UNT 113 IN CACR.prj (project) ---

Proj Title=UNT 113 IN CACR Base Level Engineering
Current Plan=p01
Default Exp/Contr=0.3,0.1
English Units
Geom File=g01
Flow File=f01
Plan File=p01
BEGIN DESCRIPTION:
UNT 113 IN CACR
END DESCRIPTION:

--- UNT 113 IN CACR.p01 (plan) ---

Plan Title=Multiple Run
Short Identifier=Multiple
Geom File=g01
Flow File=f01
Subcritical Flow
K Sum by GR= 0
Std Step Tol= 0.01
Critical Tol= 0.01
Num of Std Step Trials= 20
Max Error Tol= 0.3
Flow Tol Ratio= 0.001
Split Flow NTrial= 30
Split Flow Tol= 0.02
Split Flow Ratio= 0.02
Log Output Level= 0
Friction Slope Method= 1
Unsteady Friction Slope Method= 2
Unsteady Bridges Friction Slope Method= 1
Parabolic Critical Depth
Global Vel Dist=  1 , 1 , 1
Global Log Level= 0
CheckData=True
Encroach Param= -1, 0, 0, 0
BEGIN DESCRIPTION:
Multiple Run
END DESCRIPTION:

--- UNT 113 IN CACR.f01 (steady flow) ---

Flow Title=Multiple
Number of Profiles=7
Profile Names=10-year,25-year,50-year,1pct_min,100-year,1pct_plu,500-year
River Rch & RM= UNT 113 IN CACR,Reach-1,2419
     427     574     695     620     838    1133    1222
River Rch & RM= UNT 113 IN CACR,Reach-1,2063
     470     635     771     689     931    1260    1365
Boundary for River Rch & Prof#=UNT 113 IN CACR,Reach-1,1
Up Type=0
Dn Type=3
Dn Slope=0.005
Boundary for River Rch & Prof#=UNT 113 IN CACR,Reach-1,2
Up Type=0
Dn Type=3
Dn Slope=0.005
Boundary for River Rch & Prof#=UNT 113 IN CACR,Reach-1,3
Up Type=0
Dn Type=3
Dn Slope=0.005
Boundary for River Rch & Prof#=UNT 113 IN CACR,Reach-1,4
Up Type=0
Dn Type=3
Dn Slope=0.005
Boundary for River Rch & Prof#=UNT 113 IN CACR,Reach-1,5
Up Type=0
Dn Type=3
Dn Slope=0.005
Boundary for River Rch & Prof#=UNT 113 IN CACR,Reach-1,6
Up Type=0
Dn Type=3
Dn Slope=0.005
Boundary for River Rch & Prof#=UNT 113 IN CACR,Reach-1,7
Up Type=0
Dn Type=3
Dn Slope=0.005

--- UNT 113 IN CACR.g01 (geometry) ---

Geom Title=Existing Conditions

River Reach=UNT 113 IN CACR,Reach-1
Reach XY= 30
      3698459.50     10709480.00      3698425.25     10709432.00
      3698402.25     10709383.00      3698374.25     10709362.00
      3698249.75     10709361.00      3698157.00     10709396.00
      3698126.50     10709423.00      3698095.00     10709472.00
      3698047.25     10709486.00      3698017.25     10709511.00
      3697915.00     10709631.00      3697893.50     10709647.00
      3697813.44     10709764.42      3697757.75     10709814.00
      3697734.50     10709853.00      3697703.00     10709887.00
      3697612.50     10709946.00      3697575.00     10709960.00
      3697510.57     10709961.62      3697270.50     10710000.00
      3697194.50     10709994.00      3697019.50     10710008.00
      3696899.00     10710000.00      3696719.50     10709979.00
      3696535.32     10709938.05      3696509.84     10709922.50
      3696392.50     10709910.00      3696171.00     10709857.00
      3696129.75     10709841.00      3696069.50     10709840.00

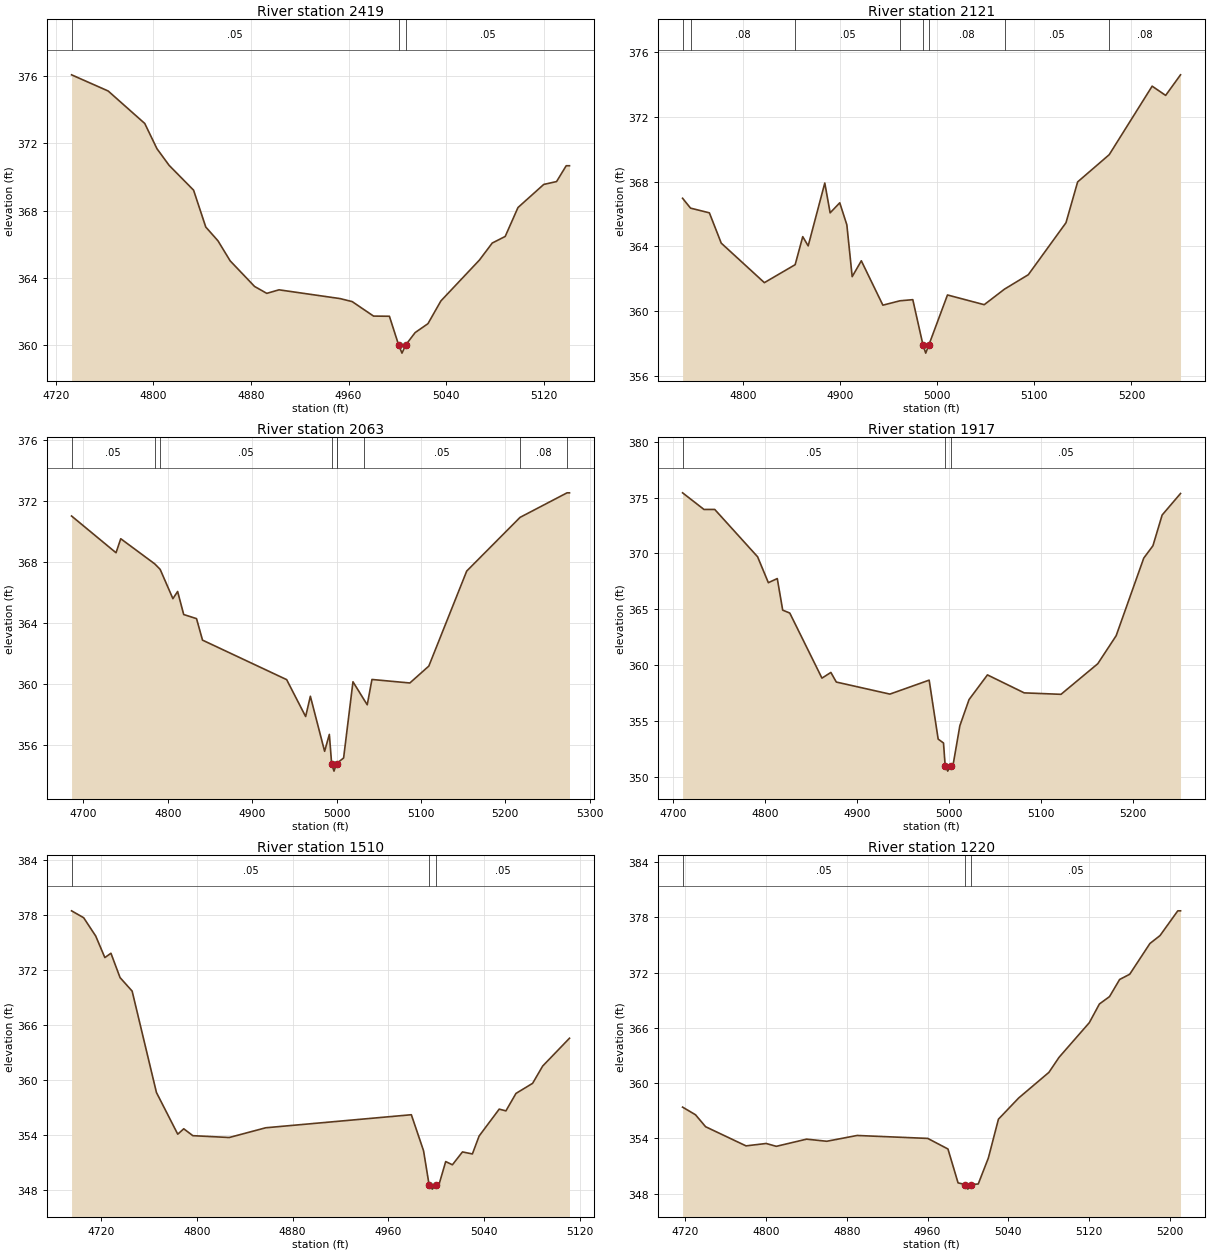
Type RM Length L Ch R = 1,2419,298,298,298
BEGIN DESCRIPTION:
UNT 113 IN CACR 5.0
END DESCRIPTION:
XS GIS Cut Line= 3
      3698199.61     10709110.23      3698199.61     10709360.19
      3698249.62     10709510.22
#Sta/Elev= 30
  4733.0  376.06  4763.0  375.10  4793.0  373.17  4803.0  371.67  4813.0  370.68
  4833.0  369.21  4843.0  367.02  4853.0  366.20  4863.0  365.01  4883.0  363.49
  4893.0  363.08  4903.0  363.29  4953.0  362.77  4963.0  362.59  4980.5  361.73
  4993.5  361.72  5001.0  360.03  5003.8  359.53  5007.0  360.03  5014.6  360.75
  5025.1  361.28  5035.7  362.63  5067.3  365.06  5077.8  366.07  5088.4  366.46
  5098.9  368.18  5120.0  369.55  5130.5  369.72  5138.4  370.66  5141.1  370.66
#Mann=3,-1,0
  4733.0    0.05       0  5001.0    0.03       0  5007.0    0.05       0
Bank Sta=5001,5007
Exp/Cntr=0.3,0.1

Type RM Length L Ch R = 1,2121,58,58,58
BEGIN DESCRIPTION:
Mapping XS dbaab127
END DESCRIPTION:
XS GIS Cut Line= 2
      3697743.69     10709441.37      3698205.92     10709662.97
#Sta/Elev= 30
  4737.9  366.97  4746.1  366.36  4765.5  366.07  4777.7  364.20  4822.1  361.76
  4853.8  362.87  4861.6  364.60  4867.2  364.03  4884.3  367.91  4889.8  366.07
  4899.7  366.69  4907.0  365.33  4912.5  362.13  4921.9  363.11  4944.1  360.37
  4961.6  360.64  4974.9  360.71  4985.4  357.91  4988.2  357.41  4991.4  357.91
  5010.6  361.00  5048.4  360.40  5069.3  361.36  5093.8  362.25  5132.6  365.46
  5144.6  367.98  5177.1  369.66  5221.3  373.89  5235.2  373.32  5250.5  374.59
#Mann=8,-1,0
  4737.9    0.05       0  4746.1    0.08       0  4853.8    0.05       0
  4961.6    0.08       0  4985.4    0.07       0  4991.4    0.08       0
  5069.3    0.05       0  5177.1    0.08       0
Bank Sta=4985.4,4991.4
Exp/Cntr=0.3,0.1

Type RM Length L Ch R = 1,2063,146,146,146
BEGIN DESCRIPTION:
Mapping XS 842e4521
END DESCRIPTION:
XS GIS Cut Line= 2
      3697660.34     10709460.46      3698189.87     10709720.88
#Sta/Elev= 30
  4685.9  371.04  4738.6  368.63  4744.2  369.55  4784.5  367.90  4790.9  367.54
  4806.0  365.62  4811.6  366.09  4818.8  364.58  4834.0  364.31  4841.1  362.90
  4940.8  360.31  4963.3  357.89  4968.9  359.22  4985.8  355.61  4991.4  356.72
  4994.1  354.81  4996.9  354.31  5000.1  354.81  5000.9  354.85  5008.3  355.17
  5019.4  360.17  5032.0  359.04  5036.3  358.66  5041.9  360.32  5086.8  360.09
  5109.3  361.20  5154.2  367.43  5217.4  370.95  5273.1  372.56  5276.0  372.56
#Mann=9,-1,0
  4685.9    0.05       0  4784.5    0.08       0  4790.9    0.05       0
  4994.1    0.04       0  5000.1    0.05       0  5000.9    0.08       0
  5032.0    0.05       0  5217.4    0.08       0  5273.1    0.05       0
Bank Sta=4994.1,5000.1
Exp/Cntr=0.3,0.1

Type RM Length L Ch R = 1,1917,407,407,407
BEGIN DESCRIPTION:
UNT 113 IN CACR 4.0
END DESCRIPTION:
XS GIS Cut Line= 3
      3697599.60     10709560.18      3697849.61     10709710.19
      3697849.61     10709960.22
#Sta/Elev= 30
  4710.1  375.42  4733.4  373.93  4745.1  373.93  4791.7  369.69  4803.4  367.37
  4813.1  367.74  4819.0  364.91  4826.7  364.65  4861.7  358.82  4871.4  359.33
  4877.3  358.47  4935.6  357.39  4978.3  358.64  4988.1  353.36  4993.9  353.01
  4995.7  350.99  4998.5  350.49  5001.7  350.99  5004.2  350.99  5011.7  354.56
  5021.7  356.90  5041.7  359.11  5081.7  357.50  5121.7  357.37  5161.7  360.11
  5181.7  362.62  5211.7  369.57  5221.7  370.68  5231.7  373.43  5251.7  375.36
#Mann=3,-1,0
  4710.1    0.05       0  4995.7    0.03       0  5001.7    0.05       0
Bank Sta=4995.7,5001.7
Exp/Cntr=0.3,0.1

Type RM Length L Ch R = 1,1510,290,290,290
BEGIN DESCRIPTION:
UNT 113 IN CACR 3.0
END DESCRIPTION:
XS GIS Cut Line= 3
      3697499.62     10709660.23      3697549.61     10709960.19
      3697499.61     10710060.19
#Sta/Elev= 30
  4695.4  378.44  4705.5  377.69  4715.6  375.69  4723.2  373.35  4728.3  373.82
  4735.9  371.17  4746.0  369.70  4766.3  358.66  4784.1  354.12  4789.1  354.71
  4796.7  353.96  4827.1  353.76  4857.6  354.82  4979.2  356.24  4989.4  352.32
  4994.0  348.64  4996.7  348.14  5000.0  348.64  5002.3  348.64  5007.9  351.14
  5013.5  350.79  5021.9  352.19  5030.2  351.97  5035.8  353.92  5052.6  356.85
  5058.2  356.66  5066.6  358.56  5080.5  359.66  5088.9  361.54  5111.3  364.57
#Mann=3,-1,0
  4695.4    0.05       0  4994.0    0.03       0  5000.0    0.05       0
Bank Sta=4994,5000
Exp/Cntr=0.3,0.1

Type RM Length L Ch R = 1,1220,429,429,429
BEGIN DESCRIPTION:
Mapping XS e04b9bee
END DESCRIPTION:
XS GIS Cut Line= 2
      3697263.47     10709717.40      3697263.47     10710210.50
#Sta/Elev= 30
  4717.4  357.39  4730.2  356.56  4740.2  355.26  4780.2  353.18  4800.2  353.44
  4810.2  353.13  4840.2  353.91  4860.2  353.68  4890.2  354.31  4960.2  353.99
  4980.2  352.84  4990.2  349.16  4997.2  348.98  4999.9  348.48  5003.2  348.98
  5010.2  349.04  5020.2  351.86  5030.2  356.08  5050.2  358.38  5080.2  361.17
  5090.2  362.80  5120.2  366.57  5130.2  368.60  5140.2  369.40  5150.2  371.26
  5160.2  371.83  5180.2  375.17  5190.2  376.03  5207.8  378.72  5210.5  378.72
#Mann=3,-1,0
  4717.4    0.05       0  4997.2    0.03       0  5003.2    0.05       0
Bank Sta=4997.2,5003.2
Exp/Cntr=0.3,0.1

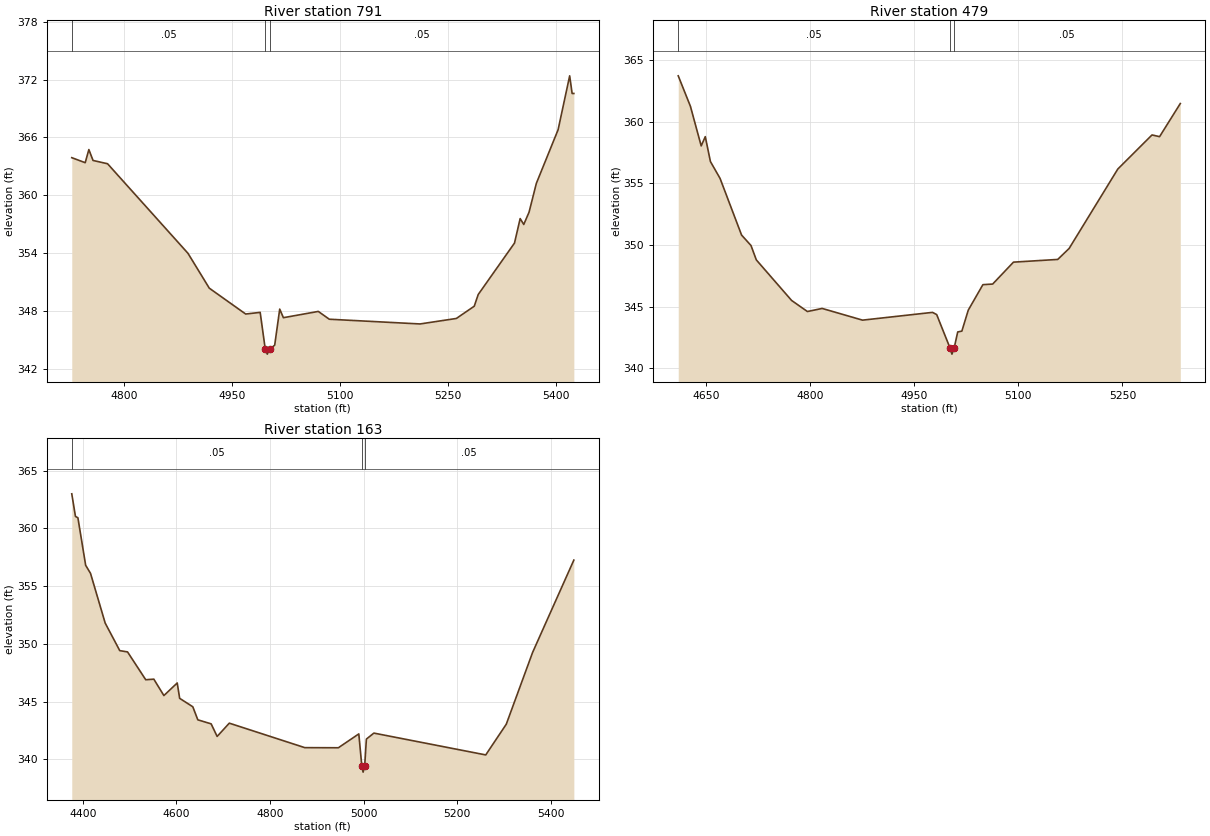
Type RM Length L Ch R = 1,791,312,312,312
BEGIN DESCRIPTION:
UNT 113 IN CACR 2.0
END DESCRIPTION:
XS GIS Cut Line= 2
      3696878.04     10709720.93      3696773.89     10710411.82
#Sta/Elev= 30
  4726.7  363.90  4745.4  363.38  4750.5  364.74  4756.3  363.61  4776.5  363.27
  4888.4  353.98  4918.1  350.36  4968.7  347.68  4988.9  347.85  4996.0  344.02
  4998.8  343.52  5002.0  344.02  5009.1  344.45  5016.1  348.19  5021.2  347.30
  5069.8  347.95  5085.1  347.14  5211.4  346.65  5261.9  347.22  5286.8  348.49
  5292.3  349.70  5342.8  355.04  5350.7  357.58  5355.7  356.97  5363.1  358.25
  5373.2  361.23  5403.5  366.80  5419.6  372.39  5423.0  370.56  5425.4  370.56
#Mann=3,-1,0
  4726.7    0.05       0  4996.0    0.03       0  5002.0    0.05       0
Bank Sta=4996,5002
Exp/Cntr=0.3,0.1

Type RM Length L Ch R = 1,479,316,316,316
BEGIN DESCRIPTION:
Mapping XS 21e5c102
END DESCRIPTION:
XS GIS Cut Line= 4
      3696829.28     10709695.79      3696597.04     10709836.87
      3696501.55     10709984.44      3696482.02     10710260.04
#Sta/Elev= 30
  4609.7  363.74  4627.3  361.26  4642.8  358.05  4648.7  358.80  4656.1  356.78
  4670.0  355.41  4701.0  350.81  4714.6  349.96  4722.3  348.79  4773.1  345.50
  4795.9  344.60  4817.2  344.85  4875.4  343.90  4976.3  344.53  4982.3  344.35
  5001.5  341.64  5004.3  341.14  5007.5  341.64  5012.6  342.94  5018.6  343.01
  5027.8  344.71  5048.9  346.78  5063.0  346.83  5093.0  348.61  5156.8  348.83
  5173.2  349.72  5243.4  356.17  5292.7  358.94  5303.6  358.80  5333.5  361.49
#Mann=3,-1,0
  4609.7    0.05       0  5001.5    0.03       0  5007.5    0.05       0
Bank Sta=5001.5,5007.5
Exp/Cntr=0.3,0.1

Type RM Length L Ch R = 1,163,0,0,0
BEGIN DESCRIPTION:
UNT 113 IN CACR 1.0
END DESCRIPTION:
XS GIS Cut Line= 4
      3696798.17     10709661.86      3696256.52     10709818.10
      3696211.38     10709901.43      3696457.91     10710234.77
#Sta/Elev= 30
  4376.3  362.99  4384.2  361.03  4389.4  360.92  4406.0  356.80  4416.4  356.10
  4447.7  351.80  4478.9  349.41  4495.5  349.30  4534.4  346.89  4551.7  346.94
  4573.2  345.52  4601.7  346.61  4606.9  345.28  4635.0  344.55  4645.7  343.42
  4674.2  343.07  4687.0  341.98  4713.0  343.13  4874.4  341.01  4946.1  341.00
  4989.8  342.20  4996.3  339.39  4999.0  338.89  5002.3  339.39  5006.0  341.75
  5022.0  342.27  5261.1  340.38  5305.0  343.04  5361.3  349.26  5449.4  357.25
#Mann=3,-1,0
  4376.3    0.05       0  4996.3    0.03       0  5002.3    0.05       0
Bank Sta=4996.3,5002.3
Exp/Cntr=0.3,0.1

Chan Stop Cuts=-1