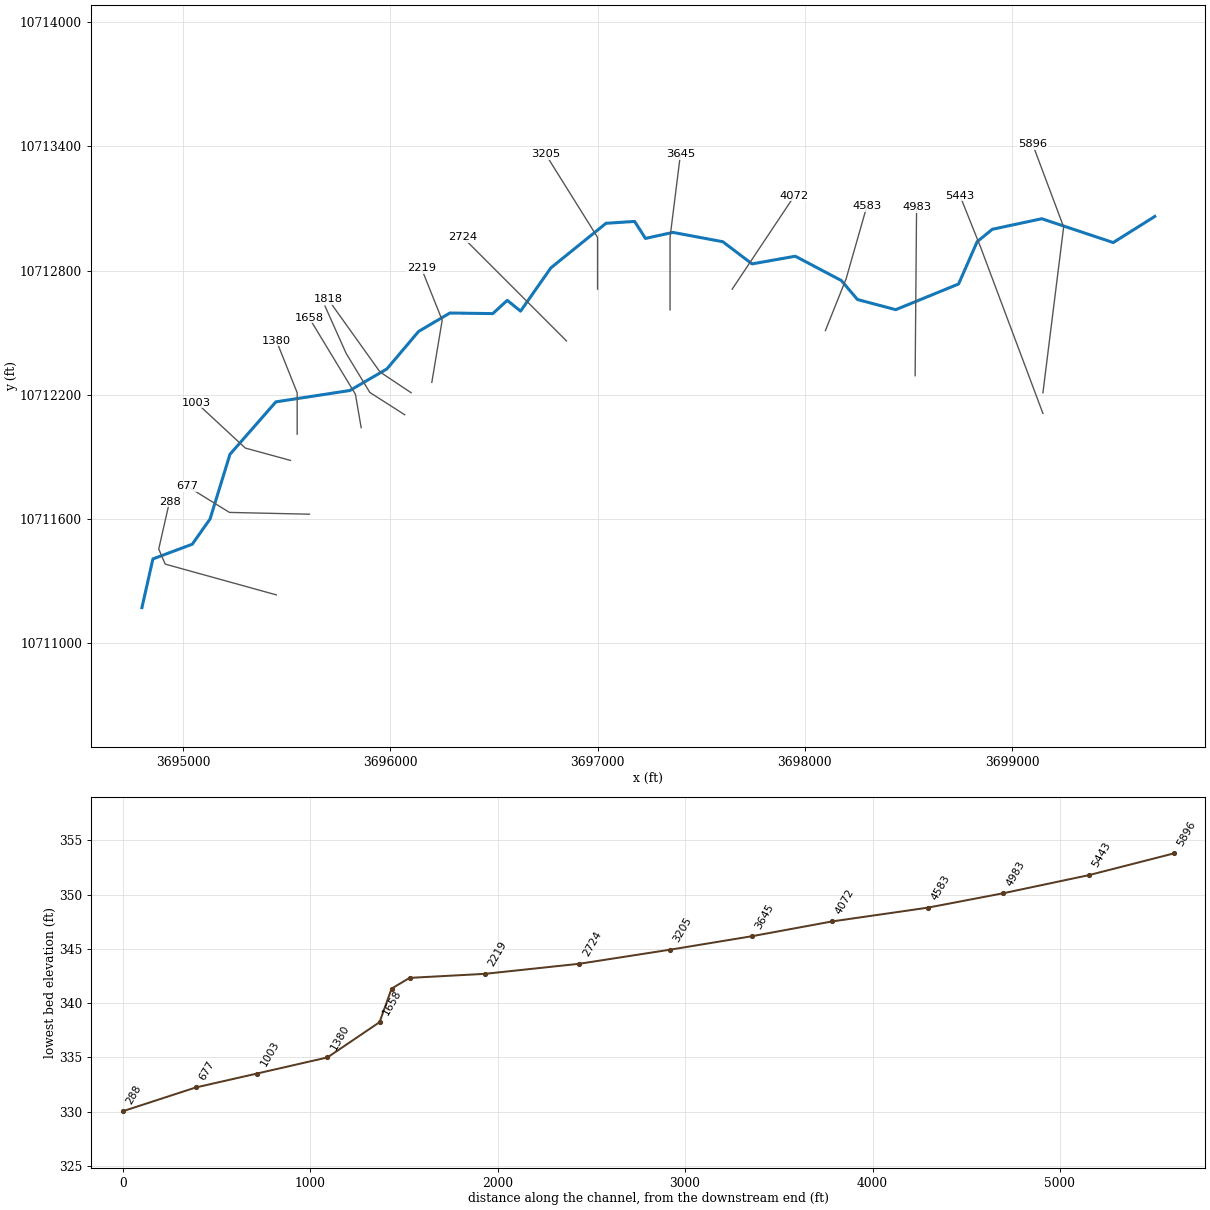
--- UNT 114 IN CACR.prj (project) ---

Proj Title=UNT 114 IN CACR Base Level Engineering
Current Plan=p01
Default Exp/Contr=0.3,0.1
English Units
Geom File=g01
Flow File=f01
Plan File=p01
BEGIN DESCRIPTION:
UNT 114 IN CACR
END DESCRIPTION:

--- UNT 114 IN CACR.p01 (plan) ---

Plan Title=Multiple Run
Short Identifier=Multiple
Geom File=g01
Flow File=f01
Subcritical Flow
K Sum by GR= 0
Std Step Tol= 0.01
Critical Tol= 0.01
Num of Std Step Trials= 20
Max Error Tol= 0.3
Flow Tol Ratio= 0.001
Split Flow NTrial= 30
Split Flow Tol= 0.02
Split Flow Ratio= 0.02
Log Output Level= 0
Friction Slope Method= 1
Unsteady Friction Slope Method= 2
Unsteady Bridges Friction Slope Method= 1
Parabolic Critical Depth
Global Vel Dist=  1 , 1 , 1
Global Log Level= 0
CheckData=True
Encroach Param= -1, 0, 0, 0
BEGIN DESCRIPTION:
Multiple Run
END DESCRIPTION:

--- UNT 114 IN CACR.f01 (steady flow) ---

Flow Title=Multiple
Number of Profiles=7
Profile Names=10-year,25-year,50-year,1pct_min,100-year,1pct_plu,500-year
River Rch & RM= UNT 114 IN CACR,Reach-1,5896
     787    1091    1348    1224    1655    2238    2504
Boundary for River Rch & Prof#=UNT 114 IN CACR,Reach-1,1
Up Type=0
Dn Type=3
Dn Slope=0.005
Boundary for River Rch & Prof#=UNT 114 IN CACR,Reach-1,2
Up Type=0
Dn Type=3
Dn Slope=0.005
Boundary for River Rch & Prof#=UNT 114 IN CACR,Reach-1,3
Up Type=0
Dn Type=3
Dn Slope=0.005
Boundary for River Rch & Prof#=UNT 114 IN CACR,Reach-1,4
Up Type=0
Dn Type=3
Dn Slope=0.005
Boundary for River Rch & Prof#=UNT 114 IN CACR,Reach-1,5
Up Type=0
Dn Type=3
Dn Slope=0.005
Boundary for River Rch & Prof#=UNT 114 IN CACR,Reach-1,6
Up Type=0
Dn Type=3
Dn Slope=0.005
Boundary for River Rch & Prof#=UNT 114 IN CACR,Reach-1,7
Up Type=0
Dn Type=3
Dn Slope=0.005

--- UNT 114 IN CACR.g01 (geometry) ---

Geom Title=Existing Conditions

River Reach=UNT 114 IN CACR,Reach-1
Reach XY= 30
      3699689.50     10713061.00      3699489.00     10712935.00
      3699144.25     10713050.00      3698905.00     10712999.00
      3698832.00     10712939.00      3698742.50     10712735.00
      3698439.00     10712611.00      3698254.50     10712660.00
      3698176.00     10712752.00      3697954.25     10712869.00
      3697745.50     10712832.00      3697604.25     10712939.00
      3697363.50     10712984.00      3697231.00     10712955.00
      3697178.50     10713037.00      3697040.50     10713028.00
      3696774.50     10712813.00      3696628.00     10712604.00
      3696563.75     10712656.00      3696494.00     10712592.00
      3696287.00     10712595.00      3696135.75     10712506.00
      3695982.75     10712325.00      3695804.00     10712221.00
      3695446.75     10712166.00      3695225.25     10711913.00
      3695129.25     10711601.00      3695043.25     10711479.00
      3694853.25     10711408.00      3694800.25     10711173.00

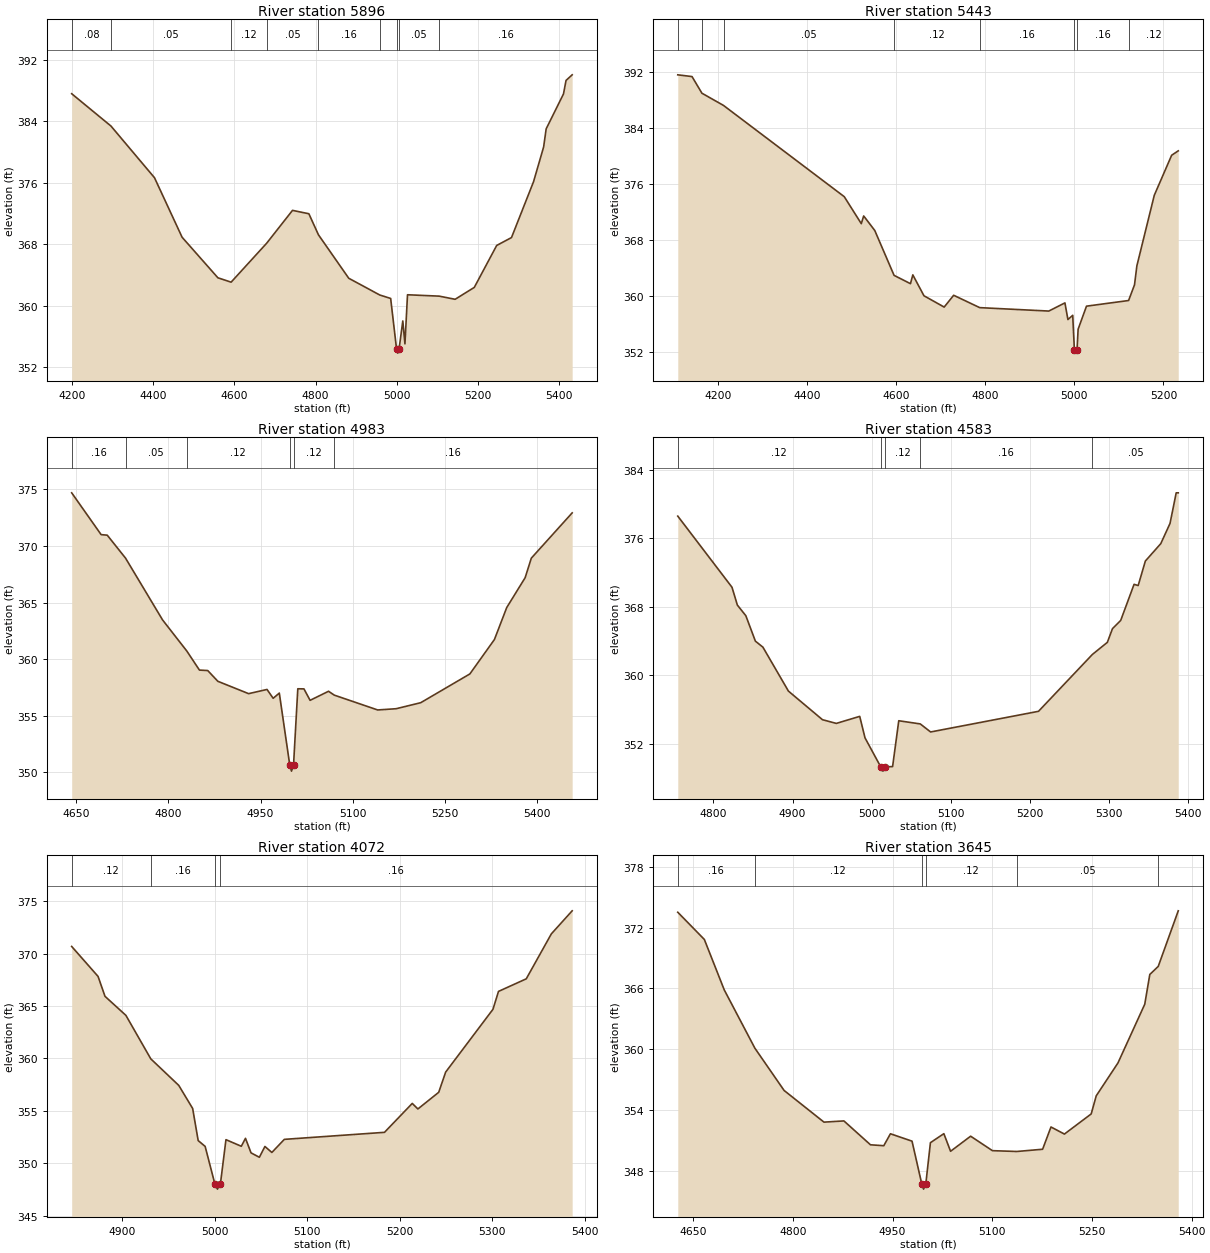
Type RM Length L Ch R = 1,5896,453,453,453
BEGIN DESCRIPTION:
UNT 114 IN CACR 13.0
END DESCRIPTION:
XS GIS Cut Line= 3
      3699149.61     10712210.21      3699249.61     10713010.19
      3699099.61     10713410.18
#Sta/Elev= 30
  4198.9  387.58  4295.7  383.37  4403.0  376.64  4471.0  368.89  4559.2  363.61
  4591.8  363.04  4679.4  368.11  4743.1  372.39  4783.4  371.95  4807.0  369.21
  4881.7  363.55  4958.1  361.37  4985.0  360.92  4999.6  354.30  5002.3  353.80
  5005.6  354.30  5014.9  357.99  5020.2  355.01  5026.5  361.40  5104.6  361.22
  5143.9  360.81  5191.1  362.36  5246.3  367.82  5282.8  368.85  5337.1  376.12
  5362.0  380.65  5368.2  383.00  5410.9  387.55  5417.2  389.31  5432.3  390.04
#Mann=9,-1,0
  4198.9    0.08       0  4295.7    0.05       0  4591.8    0.12       0
  4679.4    0.05       0  4807.0    0.16       0  4958.1    0.05       0
  4999.6    0.03       0  5005.6    0.05       0  5104.6    0.16       0
Bank Sta=4999.6,5005.6
Exp/Cntr=0.3,0.1

Type RM Length L Ch R = 1,5443,460,460,460
BEGIN DESCRIPTION:
UNT 114 IN CACR 12.0
END DESCRIPTION:
XS GIS Cut Line= 3
      3699149.60     10712110.21      3698849.61     10712910.19
      3698749.62     10713160.16
#Sta/Elev= 30
  4109.6  391.63  4141.6  391.38  4163.8  389.00  4212.3  387.25  4483.4  374.19
  4521.6  370.33  4527.0  371.43  4551.9  369.35  4595.2  362.93  4632.0  361.74
  4637.3  363.00  4662.3  360.01  4707.7  358.39  4729.0  360.08  4787.5  358.31
  4942.6  357.82  4978.8  358.99  4985.5  356.61  4996.3  357.21  5000.0  352.30
  5002.8  351.80  5006.0  352.30  5008.4  355.22  5027.2  358.52  5121.7  359.33
  5135.0  361.57  5140.3  364.29  5179.4  374.39  5218.4  380.12  5233.2  380.75
#Mann=8,-1,0
  4109.6    0.05       0  4163.8    0.08       0  4212.3    0.05       0
  4595.2    0.12       0  4787.5    0.16       0  5000.0    0.07       0
  5006.0    0.16       0  5121.7    0.12       0
Bank Sta=5000,5006
Exp/Cntr=0.3,0.1

Type RM Length L Ch R = 1,4983,400,400,400
BEGIN DESCRIPTION:
UNT 114 IN CACR 11.0
END DESCRIPTION:
XS GIS Cut Line= 2
      3698532.74     10712292.25      3698539.67     10713106.72
#Sta/Elev= 30
  4642.6  374.69  4690.5  371.00  4700.5  370.95  4730.3  368.92  4790.5  363.47
  4830.0  360.72  4850.5  359.04  4864.0  359.00  4880.5  358.05  4930.5  356.96
  4960.5  357.33  4970.5  356.55  4980.5  357.01  4997.6  350.62  5000.3  350.12
  5003.6  350.62  5010.6  357.39  5020.6  357.38  5030.6  356.37  5060.6  357.17
  5069.9  356.83  5140.6  355.52  5170.6  355.63  5210.6  356.16  5290.6  358.70
  5330.6  361.74  5350.6  364.56  5380.6  367.20  5390.6  368.92  5457.1  372.92
#Mann=6,-1,0
  4642.6    0.16       0  4730.3    0.05       0  4830.0    0.12       0
  4997.6    0.07       0  5003.6    0.12       0  5069.9    0.16       0
Bank Sta=4997.6,5003.6
Exp/Cntr=0.3,0.1

Type RM Length L Ch R = 1,4583,511,511,511
BEGIN DESCRIPTION:
UNT 114 IN CACR 10.0
END DESCRIPTION:
XS GIS Cut Line= 3
      3698099.62     10712510.22      3698199.61     10712760.19
      3698299.60     10713110.16
#Sta/Elev= 30
  4754.8  378.56  4823.4  370.26  4830.2  368.18  4840.9  366.94  4853.0  363.97
  4862.5  363.27  4894.8  358.14  4937.9  354.80  4955.4  354.37  4985.0  355.19
  4991.7  352.68  5011.6  349.30  5014.4  348.80  5017.6  349.30  5026.6  349.33
  5034.4  354.68  5061.6  354.31  5074.7  353.37  5211.2  355.78  5279.4  362.42
  5298.3  363.83  5304.8  365.43  5315.2  366.39  5332.1  370.60  5337.3  370.46
  5346.4  373.32  5365.9  375.35  5377.6  377.71  5385.4  381.28  5388.0  381.28
#Mann=5,-1,0
  4754.8    0.12       0  5011.6    0.07       0  5017.6    0.12       0
  5061.6    0.16       0  5279.4    0.05       0
Bank Sta=5011.6,5017.6
Exp/Cntr=0.3,0.1

Type RM Length L Ch R = 1,4072,427,427,427
BEGIN DESCRIPTION:
UNT 114 IN CACR 9.0
END DESCRIPTION:
XS GIS Cut Line= 3
      3697649.62     10712710.20      3697749.61     10712860.19
      3697949.60     10713160.18
#Sta/Elev= 30
  4845.6  370.69  4874.1  367.83  4881.6  365.93  4904.2  364.11  4931.1  359.96
  4961.3  357.43  4976.3  355.23  4982.3  352.16  4989.8  351.61  5000.3  348.03
  5003.1  347.53  5006.3  348.03  5012.3  352.25  5028.9  351.62  5033.4  352.38
  5039.4  350.99  5048.4  350.57  5054.4  351.60  5061.9  351.03  5075.4  352.28
  5183.6  352.95  5213.6  355.71  5219.7  355.18  5242.2  356.77  5249.7  358.70
  5300.8  364.69  5306.8  366.40  5336.8  367.60  5363.9  371.89  5386.4  374.09
#Mann=4,-1,0
  4845.6    0.12       0  4931.1    0.16       0  5000.3    0.07       0
  5006.3    0.16       0
Bank Sta=5000.3,5006.3
Exp/Cntr=0.3,0.1

Type RM Length L Ch R = 1,3645,440,440,440
BEGIN DESCRIPTION:
UNT 114 IN CACR 8.0
END DESCRIPTION:
XS GIS Cut Line= 3
      3697349.61     10712610.19      3697349.61     10712960.19
      3697399.61     10713360.18
#Sta/Elev= 30
  4626.8  373.53  4666.8  370.84  4696.8  365.85  4742.9  360.09  4786.8  355.92
  4846.8  352.79  4876.8  352.91  4916.8  350.55  4936.8  350.46  4946.8  351.64
  4979.3  350.91  4994.0  346.67  4996.7  346.17  5000.0  346.67  5007.0  350.76
  5027.2  351.65  5037.3  349.91  5067.5  351.40  5100.3  349.97  5137.0  349.89
  5175.8  350.11  5188.4  352.31  5208.6  351.61  5248.9  353.60  5256.5  355.39
  5289.2  358.64  5329.5  364.44  5337.1  367.38  5349.8  368.18  5379.9  373.67
#Mann=6,-1,0
  4626.8    0.16       0  4742.9    0.12       0  4994.0    0.07       0
  5000.0    0.12       0  5137.0    0.05       0  5349.8    0.16       0
Bank Sta=4994,5000
Exp/Cntr=0.3,0.1

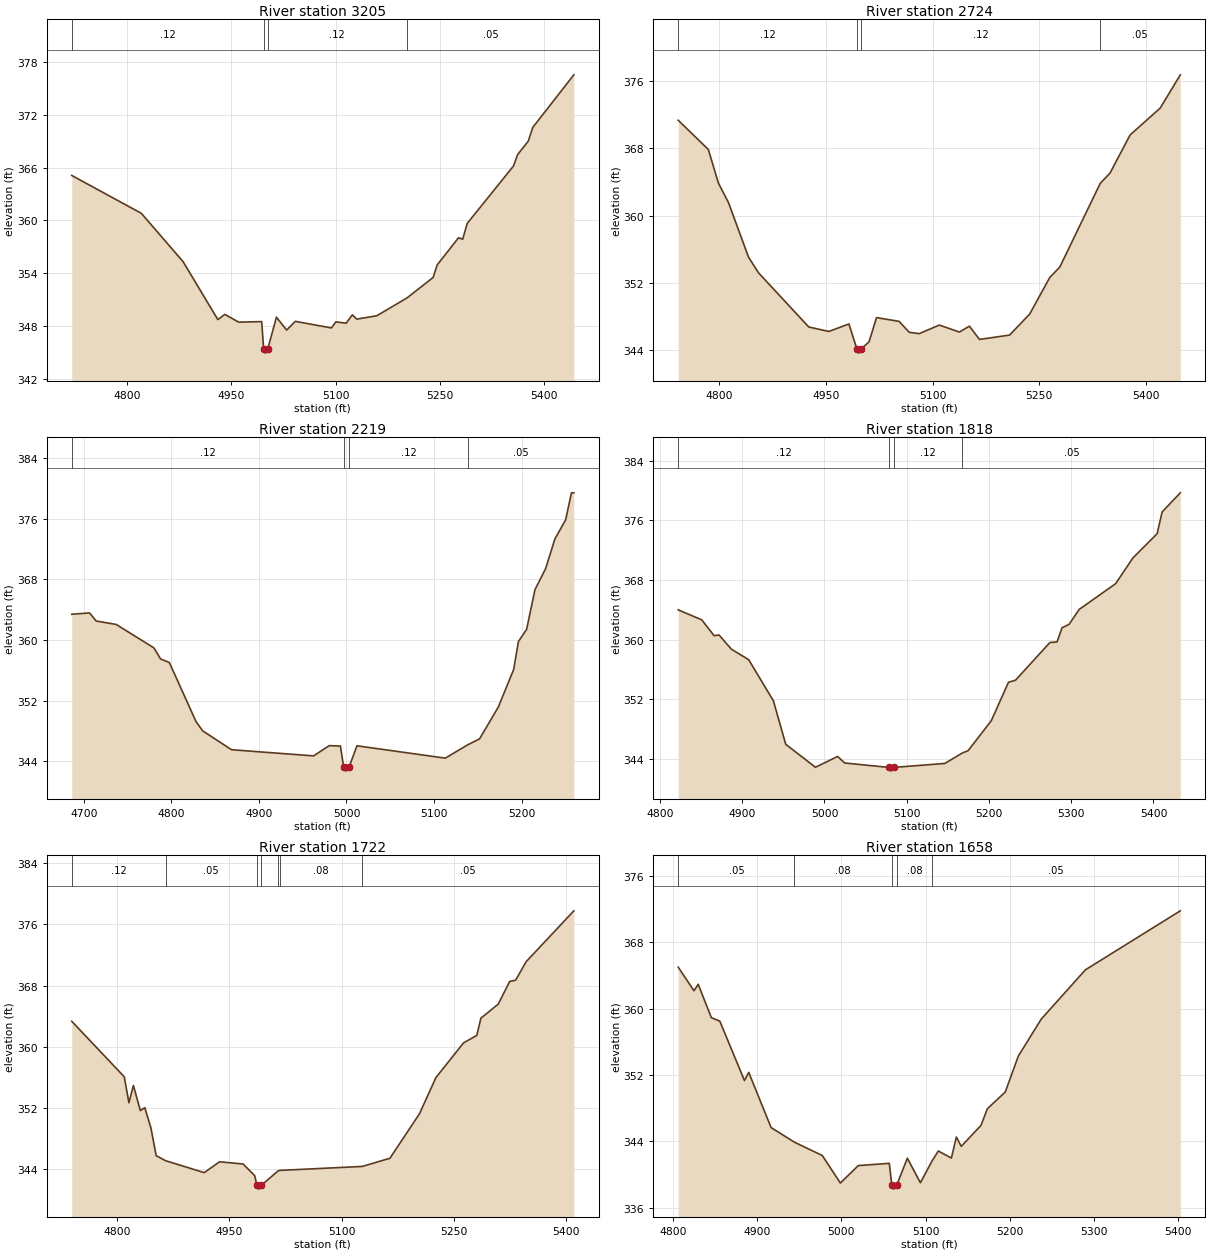
Type RM Length L Ch R = 1,3205,481,481,481
BEGIN DESCRIPTION:
UNT 114 IN CACR 7.0
END DESCRIPTION:
XS GIS Cut Line= 3
      3696999.61     10712710.23      3696999.61     10712960.19
      3696749.59     10713360.23
#Sta/Elev= 30
  4720.7  365.10  4820.7  360.80  4880.7  355.31  4930.7  348.73  4940.7  349.32
  4960.7  348.44  4993.7  348.50  4996.5  345.42  4999.3  344.92  5002.5  345.42
  5014.9  349.00  5029.6  347.54  5042.0  348.53  5093.9  347.78  5100.4  348.47
  5115.1  348.32  5124.0  349.27  5130.4  348.78  5159.3  349.17  5202.4  351.18
  5240.1  353.51  5246.0  354.94  5276.7  358.03  5282.6  357.86  5289.1  359.65
  5355.7  366.18  5361.6  367.47  5376.9  369.00  5383.4  370.56  5442.4  376.53
#Mann=4,-1,0
  4720.7    0.12       0  4996.5    0.07       0  5002.5    0.12       0
  5202.4    0.05       0
Bank Sta=4996.5,5002.5
Exp/Cntr=0.3,0.1

Type RM Length L Ch R = 1,2724,505,505,505
BEGIN DESCRIPTION:
UNT 114 IN CACR 6.0
END DESCRIPTION:
XS GIS Cut Line= 3
      3696849.61     10712460.18      3696649.61     10712660.19
      3696349.62     10712960.18
#Sta/Elev= 30
  4741.9  371.36  4784.3  367.88  4798.5  363.87  4812.6  361.57  4840.9  355.06
  4855.0  353.19  4925.8  346.74  4954.0  346.21  4982.3  347.10  4993.5  344.13
  4996.2  343.63  4999.5  344.13  5010.6  344.97  5021.2  347.86  5053.0  347.41
  5067.2  346.11  5081.3  345.95  5109.6  346.97  5137.9  346.14  5152.0  346.84
  5166.2  345.26  5208.6  345.78  5236.9  348.29  5265.2  352.64  5279.3  353.88
  5336.2  363.84  5350.0  365.07  5378.3  369.61  5420.7  372.81  5449.0  376.77
#Mann=4,-1,0
  4741.9    0.12       0  4993.5    0.07       0  4999.5    0.12       0
  5336.2    0.05       0
Bank Sta=4993.5,4999.5
Exp/Cntr=0.3,0.1

Type RM Length L Ch R = 1,2219,401,401,401
BEGIN DESCRIPTION:
UNT 114 IN CACR 5.0
END DESCRIPTION:
XS GIS Cut Line= 3
      3696199.61     10712260.20      3696249.61     10712560.19
      3696149.60     10712810.20
#Sta/Elev= 30
  4686.3  363.38  4706.6  363.56  4714.2  362.49  4737.0  362.04  4780.1  358.95
  4787.7  357.49  4797.8  357.01  4828.2  349.23  4835.8  348.01  4868.8  345.52
  4962.5  344.71  4980.3  346.06  4993.1  346.01  4996.9  343.20  4999.6  342.70
  5002.9  343.20  5012.0  346.04  5112.9  344.41  5138.8  346.19  5152.0  346.95
  5173.5  351.16  5191.0  356.11  5196.4  359.78  5205.8  361.40  5215.3  366.62
  5227.4  369.38  5238.1  373.32  5250.3  375.82  5257.0  379.39  5259.7  379.39
#Mann=4,-1,0
  4686.3    0.12       0  4996.9    0.07       0  5002.9    0.12       0
  5138.8    0.05       0
Bank Sta=4996.9,5002.9
Exp/Cntr=0.3,0.1

Type RM Length L Ch R = 1,1818,96,96,96
BEGIN DESCRIPTION:
UNT 114 IN CACR 4.0
END DESCRIPTION:
XS GIS Cut Line= 3
      3696099.63     10712210.17      3695949.61     10712310.19
      3695699.62     10712660.17
#Sta/Elev= 30
  4822.2  363.98  4850.8  362.64  4865.8  360.51  4871.8  360.61  4886.8  358.70
  4907.9  357.28  4937.9  351.77  4952.9  345.93  4989.0  342.85  5016.0  344.30
  5024.6  343.42  5078.2  342.83  5080.9  342.33  5084.2  342.83  5146.3  343.36
  5167.7  344.77  5174.6  345.07  5202.8  349.10  5223.7  354.26  5232.3  354.54
  5274.1  359.60  5282.7  359.67  5288.8  361.57  5297.4  362.04  5309.7  364.04
  5354.0  367.50  5374.9  370.94  5404.4  374.20  5410.5  377.13  5432.6  379.69
#Mann=4,-1,0
  4822.2    0.12       0  5078.2    0.07       0  5084.2    0.12       0
  5167.7    0.05       0
Bank Sta=5078.2,5084.2
Exp/Cntr=0.3,0.1

Type RM Length L Ch R = 1,1722,64,64,64
BEGIN DESCRIPTION:
Mapping XS d4d7a95d
END DESCRIPTION:
XS GIS Cut Line= 4
      3696068.67     10712103.91      3695900.25     10712211.56
      3695785.67     10712400.80      3695683.94     10712628.39
#Sta/Elev= 30
  4739.7  363.31  4809.8  356.05  4816.0  352.65  4822.0  354.91  4831.3  351.62
  4837.2  352.01  4845.4  349.36  4852.4  345.72  4865.0  345.06  4916.6  343.50
  4937.0  344.92  4968.5  344.63  4984.0  343.10  4986.8  341.84  4989.6  341.34
  4992.8  341.84  5015.5  343.75  5017.2  343.79  5127.5  344.31  5164.5  345.38
  5204.0  351.21  5225.9  355.94  5262.8  360.49  5280.5  361.47  5286.0  363.72
  5309.2  365.57  5324.4  368.53  5332.4  368.70  5346.4  371.12  5410.1  377.78
#Mann=7,-1,0
  4739.7    0.12       0  4865.0    0.05       0  4986.8    0.04       0
  4992.8    0.05       0  5015.5    0.12       0  5017.2    0.08       0
  5127.5    0.05       0
Bank Sta=4986.8,4992.8
Exp/Cntr=0.3,0.1

Type RM Length L Ch R = 1,1658,278,278,278
BEGIN DESCRIPTION:
Mapping XS 59ce514d
END DESCRIPTION:
XS GIS Cut Line= 3
      3695858.57     10712041.47      3695830.80     10712202.88
      3695606.85     10712572.67
#Sta/Elev= 30
  4806.4  365.02  4825.1  362.18  4830.1  362.96  4845.7  358.94  4855.8  358.51
  4885.0  351.35  4890.1  352.33  4916.7  345.67  4944.4  343.91  4977.5  342.30
  4998.9  338.98  5020.2  341.09  5057.0  341.36  5059.9  338.75  5062.6  338.25
  5065.9  338.75  5078.4  341.98  5093.9  339.02  5108.0  341.69  5115.2  342.85
  5130.7  342.00  5136.6  344.54  5142.4  343.41  5165.8  345.93  5173.4  347.94
  5194.7  349.97  5210.2  354.30  5237.4  358.76  5289.8  364.70  5402.5  371.82
#Mann=5,-1,0
  4806.4    0.05       0  4944.4    0.08       0  5059.9    0.07       0
  5065.9    0.08       0  5108.0    0.05       0
Bank Sta=5059.9,5065.9
Exp/Cntr=0.3,0.1

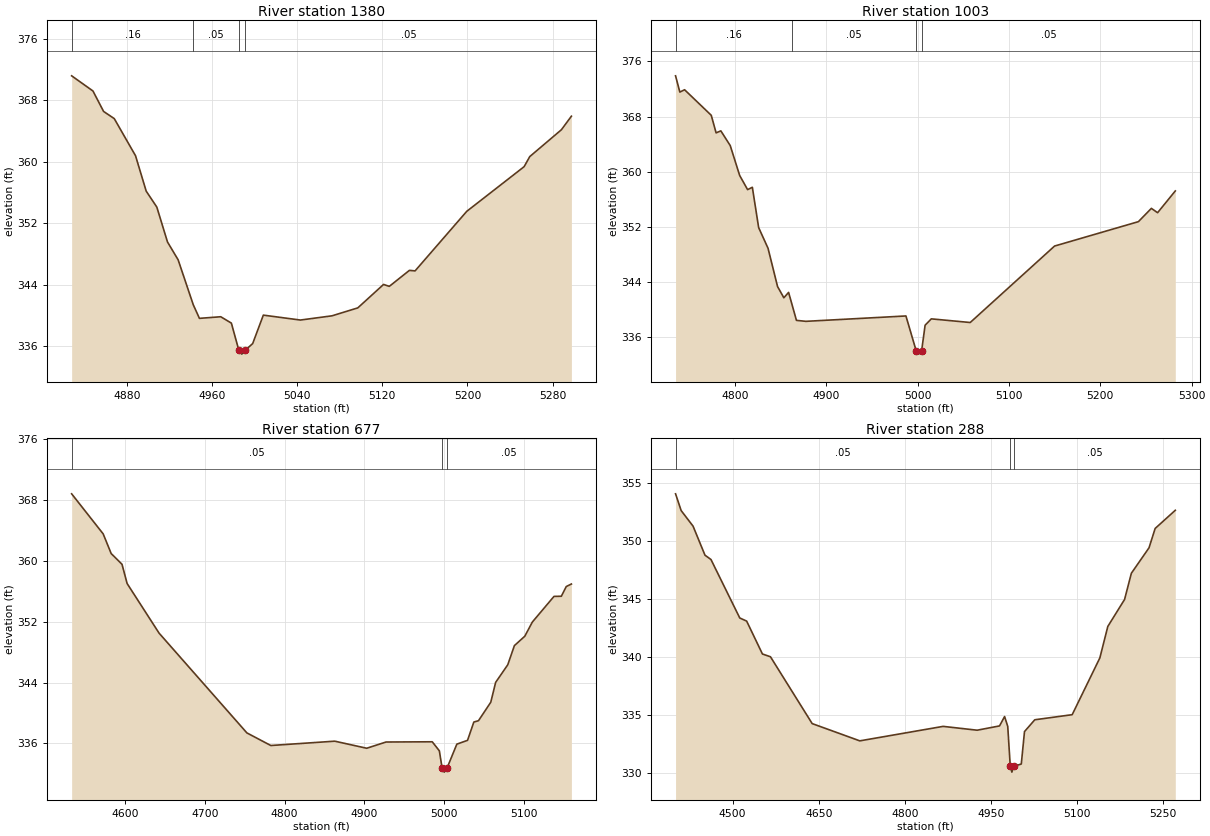
Type RM Length L Ch R = 1,1380,377,377,377
BEGIN DESCRIPTION:
UNT 114 IN CACR 3.0
END DESCRIPTION:
XS GIS Cut Line= 3
      3695549.61     10712010.16      3695549.61     10712210.19
      3695449.61     10712460.20
#Sta/Elev= 30
  4828.3  371.18  4848.3  369.21  4858.3  366.55  4868.3  365.62  4888.3  360.79
  4898.3  356.19  4908.3  354.11  4918.3  349.58  4928.3  347.26  4942.5  341.42
  4948.3  339.65  4968.3  339.86  4978.3  339.03  4985.3  335.50  4988.1  335.00
  4991.3  335.50  4998.3  336.37  5008.3  340.07  5043.1  339.43  5072.8  339.98
  5097.0  341.01  5121.2  344.06  5126.6  343.81  5145.5  345.89  5150.8  345.82
  5199.3  353.56  5253.2  359.37  5258.5  360.68  5288.2  364.17  5297.6  365.93
#Mann=4,-1,0
  4828.3    0.16       0  4942.5    0.05       0  4985.3    0.03       0
  4991.3    0.05       0
Bank Sta=4985.3,4991.3
Exp/Cntr=0.3,0.1

Type RM Length L Ch R = 1,1003,326,326,326
BEGIN DESCRIPTION:
Mapping XS a3ecc1f9
END DESCRIPTION:
XS GIS Cut Line= 3
      3695517.34     10711883.43      3695299.21     10711943.12
      3695063.64     10712161.39
#Sta/Elev= 30
  4734.8  373.91  4739.5  371.55  4744.7  371.89  4773.9  368.18  4779.2  365.63
  4784.4  365.92  4794.7  363.78  4805.0  359.45  4813.7  357.39  4818.9  357.73
  4825.8  351.88  4836.1  348.87  4846.5  343.32  4853.4  341.69  4858.6  342.47
  4862.8  340.49  4867.2  338.41  4877.6  338.27  4987.1  339.05  4998.3  334.01
  5001.1  333.51  5004.3  334.01  5008.1  337.71  5014.9  338.63  5057.5  338.10
  5149.9  349.20  5241.7  352.74  5255.9  354.67  5262.7  354.04  5282.1  357.20
#Mann=4,-1,0
  4734.8    0.16       0  4862.8    0.05       0  4998.3    0.03       0
  5004.3    0.05       0
Bank Sta=4998.3,5004.3
Exp/Cntr=0.3,0.1

Type RM Length L Ch R = 1,677,389,389,389
BEGIN DESCRIPTION:
UNT 114 IN CACR 2.0
END DESCRIPTION:
XS GIS Cut Line= 3
      3695609.08     10711623.80      3695222.84     10711632.48
      3695018.88     10711758.33
#Sta/Elev= 30
  4533.2  368.83  4572.7  363.56  4582.7  360.98  4596.3  359.56  4602.7  357.03
  4642.7  350.51  4752.7  337.39  4782.7  335.73  4862.8  336.30  4902.8  335.37
  4927.0  336.19  4984.9  336.22  4993.8  335.03  4997.3  332.73  5000.0  332.23
  5003.3  332.73  5015.7  335.91  5029.1  336.41  5037.0  338.82  5042.8  338.99
  5058.2  341.42  5064.3  344.03  5079.5  346.35  5087.8  348.87  5100.8  350.10
  5110.3  351.97  5137.4  355.34  5146.6  355.36  5152.8  356.64  5159.2  356.97
#Mann=3,-1,0
  4533.2    0.05       0  4997.3    0.03       0  5003.3    0.05       0
Bank Sta=4997.3,5003.3
Exp/Cntr=0.3,0.1

Type RM Length L Ch R = 1,288,0,0,0
BEGIN DESCRIPTION:
UNT 114 IN CACR 1.0
END DESCRIPTION:
XS GIS Cut Line= 4
      3695449.04     10711234.42      3694912.59     10711382.85
      3694881.34     10711455.77      3694933.41     10711684.89
#Sta/Elev= 30
  4400.5  354.07  4410.3  352.62  4431.0  351.28  4451.8  348.77  4462.2  348.40
  4512.4  343.35  4524.4  343.08  4551.9  340.24  4565.9  340.00  4638.6  334.23
  4721.6  332.74  4866.8  333.99  4926.1  333.66  4965.1  334.03  4973.9  334.84
  4979.4  333.99  4983.8  330.54  4986.6  330.04  4989.8  330.54  5003.0  330.74
  5008.6  333.54  5026.5  334.56  5091.7  335.00  5139.9  339.90  5153.8  342.62
  5183.0  344.95  5194.8  347.21  5225.6  349.41  5236.3  351.08  5271.4  352.65
#Mann=3,-1,0
  4400.5    0.05       0  4983.8    0.03       0  4989.8    0.05       0
Bank Sta=4983.8,4989.8
Exp/Cntr=0.3,0.1

Chan Stop Cuts=-1