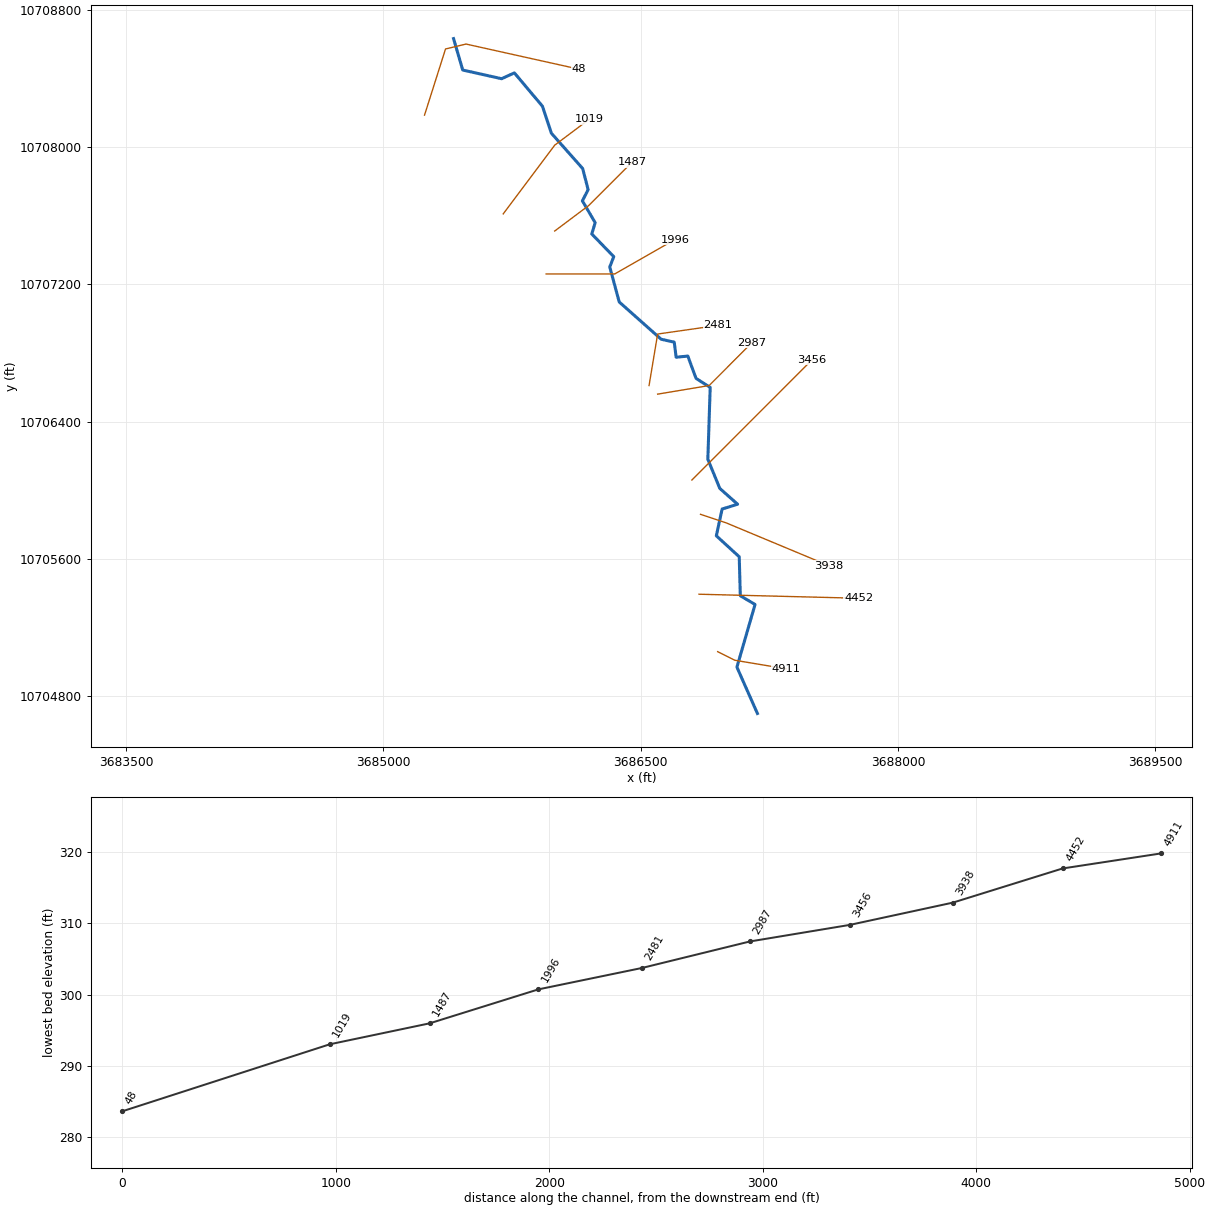
--- UNT 115 IN CACR.prj (project) ---

Proj Title=UNT 115 IN CACR Base Level Engineering
Current Plan=p01
Default Exp/Contr=0.3,0.1
English Units
Geom File=g01
Flow File=f01
Plan File=p01
BEGIN DESCRIPTION:
UNT 115 IN CACR
END DESCRIPTION:

--- UNT 115 IN CACR.p01 (plan) ---

Plan Title=Multiple Run
Short Identifier=Multiple
Geom File=g01
Flow File=f01
Subcritical Flow
K Sum by GR= 0
Std Step Tol= 0.01
Critical Tol= 0.01
Num of Std Step Trials= 20
Max Error Tol= 0.3
Flow Tol Ratio= 0.001
Split Flow NTrial= 30
Split Flow Tol= 0.02
Split Flow Ratio= 0.02
Log Output Level= 0
Friction Slope Method= 1
Unsteady Friction Slope Method= 2
Unsteady Bridges Friction Slope Method= 1
Parabolic Critical Depth
Global Vel Dist=  1 , 1 , 1
Global Log Level= 0
CheckData=True
Encroach Param= -1, 0, 0, 0
BEGIN DESCRIPTION:
Multiple Run
END DESCRIPTION:

--- UNT 115 IN CACR.f01 (steady flow) ---

Flow Title=Multiple
Number of Profiles=7
Profile Names=10-year,25-year,50-year,1pct_min,100-year,1pct_plu,500-year
River Rch & RM= UNT 115 IN CACR,Reach-1,4911
     535     722     875     779    1054    1426    1536
Boundary for River Rch & Prof#=UNT 115 IN CACR,Reach-1,1
Up Type=0
Dn Type=3
Dn Slope=0.005
Boundary for River Rch & Prof#=UNT 115 IN CACR,Reach-1,2
Up Type=0
Dn Type=3
Dn Slope=0.005
Boundary for River Rch & Prof#=UNT 115 IN CACR,Reach-1,3
Up Type=0
Dn Type=3
Dn Slope=0.005
Boundary for River Rch & Prof#=UNT 115 IN CACR,Reach-1,4
Up Type=0
Dn Type=3
Dn Slope=0.005
Boundary for River Rch & Prof#=UNT 115 IN CACR,Reach-1,5
Up Type=0
Dn Type=3
Dn Slope=0.005
Boundary for River Rch & Prof#=UNT 115 IN CACR,Reach-1,6
Up Type=0
Dn Type=3
Dn Slope=0.005
Boundary for River Rch & Prof#=UNT 115 IN CACR,Reach-1,7
Up Type=0
Dn Type=3
Dn Slope=0.005

--- UNT 115 IN CACR.g01 (geometry) ---

Geom Title=Existing Conditions

River Reach=UNT 115 IN CACR,Reach-1
Reach XY= 30
      3687181.16     10704700.20      3687061.75     10704970.00
      3687167.50     10705335.00      3687081.50     10705386.00
      3687075.25     10705613.00      3686941.75     10705735.00
      3686975.50     10705891.00      3687065.75     10705919.00
      3686962.00     10706011.00      3686892.25     10706181.00
      3686906.00     10706599.00      3686823.50     10706652.00
      3686775.50     10706782.00      3686707.50     10706775.00
      3686696.25     10706863.00      3686620.00     10706880.00
      3686375.75     10707097.00      3686320.50     10707301.00
      3686344.00     10707361.00      3686215.75     10707493.00
      3686235.50     10707559.00      3686161.00     10707686.00
      3686194.50     10707751.00      3686162.75     10707874.00
      3685980.25     10708080.00      3685928.33     10708236.90
      3685764.52     10708431.40      3685690.14     10708397.31
      3685463.50     10708448.00      3685410.00     10708631.00

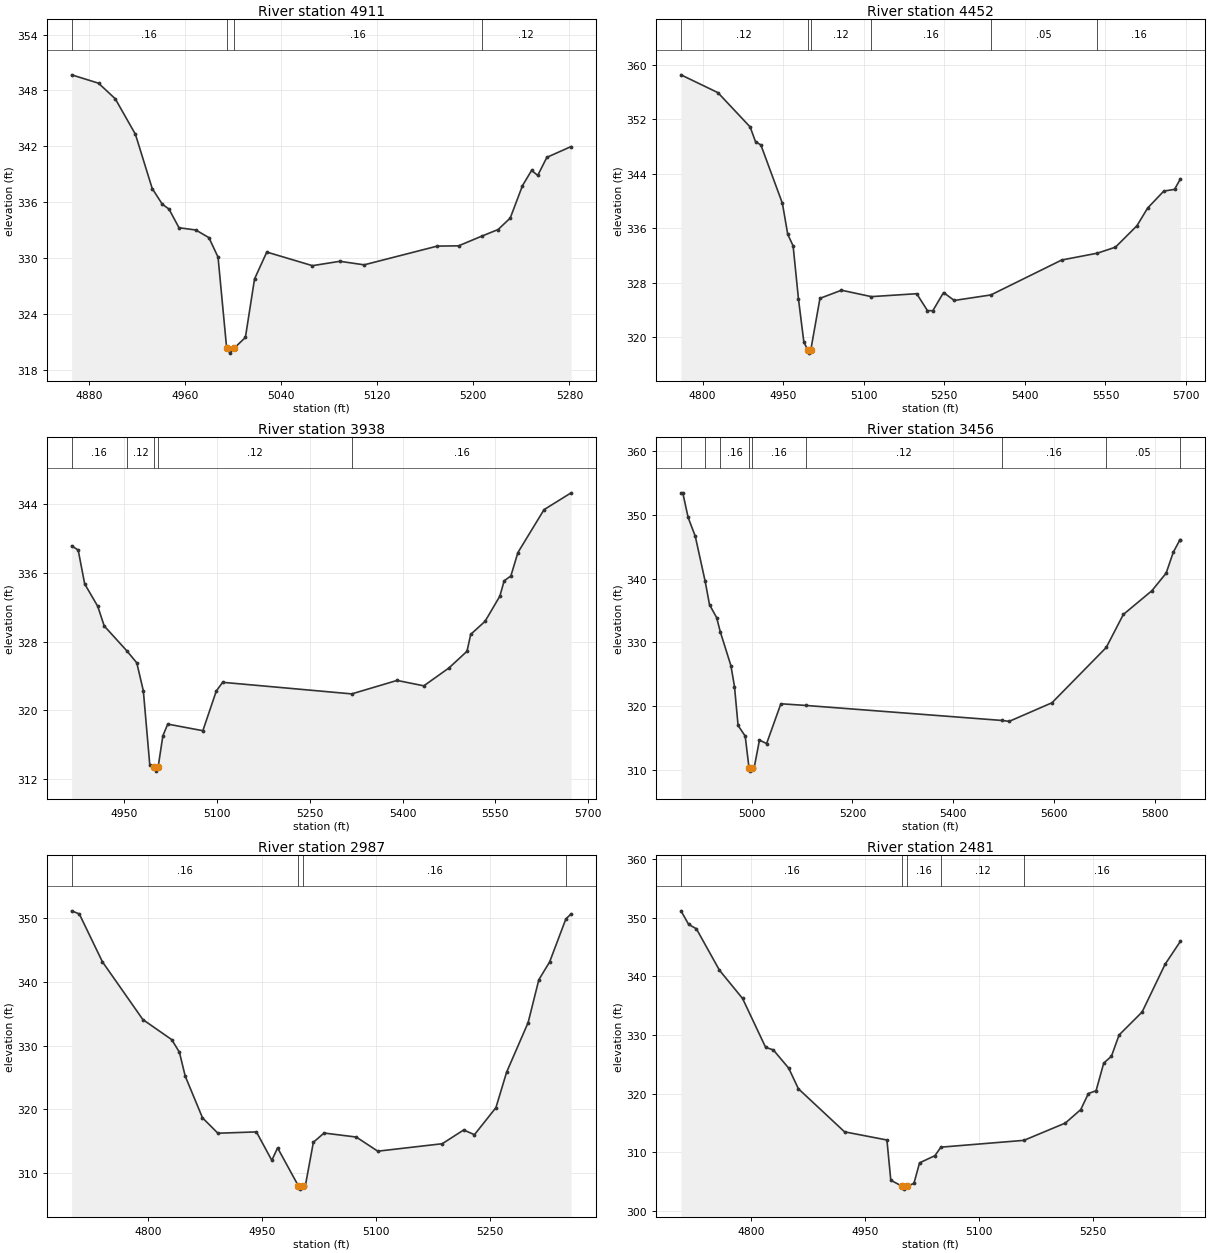
Type RM Length L Ch R = 1,4911,459,459,459
BEGIN DESCRIPTION:
UNT 115 IN CACR 10.0
END DESCRIPTION:
XS GIS Cut Line= 3
      3686949.61     10705060.19      3687049.61     10705010.19
      3687349.57     10704960.19
#Sta/Elev= 30
  4865.5  349.68  4887.9  348.78  4901.8  347.11  4918.6  343.30  4932.6  337.47
  4941.0  335.79  4946.6  335.26  4954.9  333.26  4968.9  333.02  4979.8  332.20
  4987.4  330.11  4994.6  320.30  4997.3  319.80  5000.6  320.30  5010.2  321.49
  5017.8  327.77  5028.0  330.65  5066.0  329.19  5088.8  329.66  5109.1  329.28
  5169.9  331.29  5187.7  331.32  5206.8  332.35  5220.6  333.07  5230.7  334.30
  5240.9  337.78  5248.5  339.42  5253.6  338.88  5261.2  340.82  5281.4  341.98
#Mann=4,-1,0
  4865.5    0.16       0  4994.6    0.07       0  5000.6    0.16       0
  5206.8    0.12       0
Bank Sta=4994.6,5000.6
Exp/Cntr=0.3,0.1

Type RM Length L Ch R = 1,4452,514,514,514
BEGIN DESCRIPTION:
UNT 115 IN CACR 9.0
END DESCRIPTION:
XS GIS Cut Line= 2
      3686840.85     10705394.79      3687770.56     10705371.35
#Sta/Elev= 30
  4759.6  358.49  4828.4  355.88  4888.4  350.85  4898.4  348.69  4908.4  348.21
  4948.4  339.67  4958.4  335.12  4968.4  333.42  4978.4  325.62  4988.4  319.33
  4995.4  318.20  4998.2  317.70  5001.4  318.20  5018.4  325.73  5058.5  326.92
  5114.1  325.98  5198.5  326.41  5218.5  323.94  5228.5  323.91  5248.5  326.58
  5268.5  325.42  5336.7  326.23  5468.6  331.35  5534.9  332.35  5568.6  333.23
  5608.6  336.37  5628.6  338.97  5658.6  341.45  5678.6  341.70  5689.6  343.25
#Mann=6,-1,0
  4759.6    0.12       0  4995.4    0.07       0  5001.4    0.12       0
  5114.1    0.16       0  5336.7    0.05       0  5534.9    0.16       0
Bank Sta=4995.4,5001.4
Exp/Cntr=0.3,0.1

Type RM Length L Ch R = 1,3938,482,482,482
BEGIN DESCRIPTION:
UNT 115 IN CACR 8.0
END DESCRIPTION:
XS GIS Cut Line= 3
      3686849.59     10705860.19      3686999.61     10705810.19
      3687599.58     10705560.20
#Sta/Elev= 30
  4864.5  339.16  4875.1  338.67  4885.6  334.73  4906.7  332.12  4917.2  329.83
  4954.0  326.91  4969.9  325.53  4980.5  322.27  4991.0  313.57  4998.5  313.41
  5001.3  312.91  5004.5  313.41  5012.1  317.03  5020.0  318.39  5076.8  317.62
  5098.5  322.24  5108.8  323.26  5317.7  321.91  5391.0  323.48  5434.3  322.85
  5474.9  324.93  5504.2  326.88  5510.1  328.84  5533.4  330.37  5557.3  333.30
  5564.3  335.09  5575.1  335.65  5586.5  338.38  5628.8  343.38  5672.6  345.34
#Mann=5,-1,0
  4864.5    0.16       0  4954.0    0.12       0  4998.5    0.07       0
  5004.5    0.12       0  5317.7    0.16       0
Bank Sta=4998.5,5004.5
Exp/Cntr=0.3,0.1

Type RM Length L Ch R = 1,3456,469,469,469
BEGIN DESCRIPTION:
UNT 115 IN CACR 7.0
END DESCRIPTION:
XS GIS Cut Line= 3
      3686799.59     10706060.17      3686899.61     10706160.19
      3687499.63     10706760.21
#Sta/Elev= 30
  4860.2  353.46  4863.8  353.46  4874.4  349.59  4888.5  346.66  4908.2  339.56
  4916.8  335.90  4930.9  333.88  4938.2  331.64  4959.2  326.34  4966.3  323.06
  4973.4  316.95  4987.5  315.29  4995.1  310.29  4997.9  309.79  5001.1  310.29
  5005.2  310.29  5015.8  314.67  5029.9  314.11  5058.2  320.36  5107.2  320.10
  5496.7  317.74  5510.8  317.60  5595.6  320.52  5703.1  329.19  5737.0  334.37
  5793.6  338.10  5821.9  340.86  5836.0  344.14  5848.7  346.01  5850.2  346.01
#Mann=9,-1,0
  4860.2    0.16       0  4908.2    0.12       0  4938.2    0.16       0
  4995.1    0.07       0  5001.1    0.16       0  5107.2    0.12       0
  5496.7    0.16       0  5703.1    0.05       0  5848.7    0.16       0
Bank Sta=4995.1,5001.1
Exp/Cntr=0.3,0.1

Type RM Length L Ch R = 1,2987,506,506,506
BEGIN DESCRIPTION:
UNT 115 IN CACR 6.0
END DESCRIPTION:
XS GIS Cut Line= 3
      3686599.63     10706560.19      3686899.61     10706610.19
      3687149.63     10706860.21
#Sta/Elev= 30
  4699.2  351.17  4709.3  350.68  4739.7  343.17  4793.0  334.09  4831.0  330.94
  4841.1  328.97  4848.7  325.23  4871.5  318.66  4891.8  316.24  4942.5  316.45
  4962.8  311.98  4970.4  313.94  4997.8  307.96  5000.5  307.46  5003.8  307.96
  5006.9  307.96  5017.5  314.82  5031.6  316.27  5074.0  315.64  5102.3  313.42
  5187.2  314.59  5215.4  316.75  5229.6  316.01  5257.9  320.26  5272.0  325.84
  5300.3  333.62  5314.4  340.35  5328.6  343.14  5350.0  349.90  5356.9  350.69
#Mann=4,-1,0
  4699.2    0.16       0  4997.8    0.07       0  5003.8    0.16       0
  5350.0    0.05       0
Bank Sta=4997.8,5003.8
Exp/Cntr=0.3,0.1

Type RM Length L Ch R = 1,2481,485,485,485
BEGIN DESCRIPTION:
UNT 115 IN CACR 5.0
END DESCRIPTION:
XS GIS Cut Line= 3
      3686549.61     10706610.20      3686599.61     10706910.19
      3686949.62     10706960.19
#Sta/Elev= 30
  4707.3  351.15  4717.4  348.84  4727.6  348.09  4758.0  341.03  4788.4  336.22
  4818.8  327.89  4828.9  327.46  4849.2  324.34  4861.9  320.84  4922.7  313.50
  4978.5  312.11  4983.6  305.26  4998.3  304.24  5001.0  303.74  5004.3  304.24
  5014.0  304.70  5021.5  308.22  5041.7  309.44  5049.6  310.89  5158.9  312.05
  5213.5  315.00  5233.7  317.29  5243.8  320.03  5253.9  320.50  5264.0  325.21
  5274.1  326.37  5284.2  330.00  5314.5  333.91  5344.8  342.05  5365.0  345.97
#Mann=5,-1,0
  4707.3    0.16       0  4998.3    0.07       0  5004.3    0.16       0
  5049.6    0.12       0  5158.9    0.16       0
Bank Sta=4998.3,5004.3
Exp/Cntr=0.3,0.1

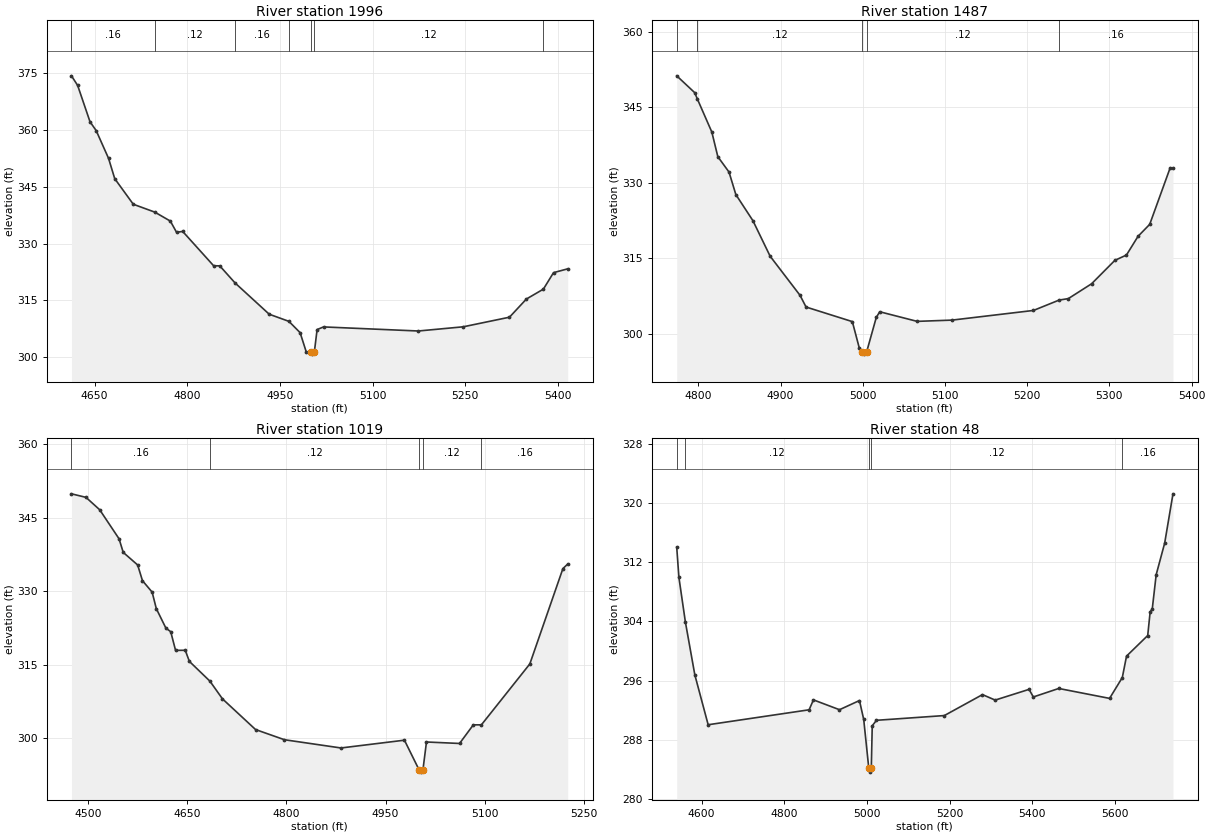
Type RM Length L Ch R = 1,1996,509,509,509
BEGIN DESCRIPTION:
UNT 115 IN CACR 4.0
END DESCRIPTION:
XS GIS Cut Line= 3
      3685949.58     10707260.19      3686349.61     10707260.19
      3686699.57     10707460.17
#Sta/Elev= 30
  4612.6  374.38  4622.6  371.83  4642.6  362.22  4652.6  359.88  4672.6  352.54
  4682.6  347.17  4712.6  340.40  4747.5  338.31  4772.6  335.94  4782.6  332.99
  4792.6  333.20  4842.6  324.13  4852.6  324.09  4877.3  319.58  4932.6  311.30
  4964.5  309.41  4982.6  306.42  4992.6  301.29  4999.6  301.24  5002.4  300.74
  5005.6  301.24  5010.1  307.24  5020.5  307.94  5173.9  306.86  5246.6  307.97
  5321.4  310.51  5348.8  315.32  5376.3  317.94  5392.7  322.30  5415.7  323.31
#Mann=7,-1,0
  4612.6    0.16       0  4747.5    0.12       0  4877.3    0.16       0
  4964.5    0.12       0  4999.6    0.07       0  5005.6    0.12       0
  5376.3    0.16       0
Bank Sta=4999.6,5005.6
Exp/Cntr=0.3,0.1

Type RM Length L Ch R = 1,1487,468,468,468
BEGIN DESCRIPTION:
UNT 115 IN CACR 3.0
END DESCRIPTION:
XS GIS Cut Line= 3
      3685999.59     10707510.18      3686199.61     10707660.19
      3686449.63     10707910.21
#Sta/Elev= 30
  4773.7  351.28  4795.6  347.93  4798.8  346.68  4816.4  340.11  4823.7  335.21
  4837.3  332.16  4845.6  327.69  4866.4  322.49  4887.3  315.44  4923.7  307.66
  4931.0  305.34  4987.3  302.44  4995.6  297.29  4998.8  296.48  5001.6  295.98
  5004.8  296.48  5016.4  303.26  5020.6  304.40  5066.1  302.49  5108.6  302.74
  5207.6  304.66  5238.8  306.72  5250.0  307.01  5278.3  309.96  5306.6  314.61
  5320.7  315.67  5334.8  319.39  5349.0  321.77  5373.7  332.92  5377.3  332.92
#Mann=5,-1,0
  4773.7    0.16       0  4798.8    0.12       0  4998.8    0.07       0
  5004.8    0.12       0  5238.8    0.16       0
Bank Sta=4998.8,5004.8
Exp/Cntr=0.3,0.1

Type RM Length L Ch R = 1,1019,971,971,971
BEGIN DESCRIPTION:
UNT 115 IN CACR 2.0
END DESCRIPTION:
XS GIS Cut Line= 3
      3685699.59     10707610.16      3685999.61     10708010.19
      3686199.58     10708160.17
#Sta/Elev= 30
  4475.4  349.84  4497.3  349.12  4518.1  346.58  4547.3  340.66  4553.6  337.89
  4575.4  335.32  4582.7  332.11  4597.3  329.78  4603.6  326.41  4618.1  322.43
  4625.4  321.70  4632.7  317.89  4647.3  317.91  4653.6  315.64  4684.6  311.61
  4703.6  307.99  4753.6  301.73  4797.3  299.65  4882.7  297.97  4978.6  299.56
  5000.6  293.54  5003.3  293.04  5006.6  293.54  5011.9  299.19  5061.9  298.89
  5082.7  302.69  5094.9  302.69  5168.1  315.12  5218.1  334.58  5225.4  335.51
#Mann=5,-1,0
  4475.4    0.16       0  4684.6    0.12       0  5000.6    0.07       0
  5006.6    0.12       0  5094.9    0.16       0
Bank Sta=5000.6,5006.6
Exp/Cntr=0.3,0.1

Type RM Length L Ch R = 1,48,0,0,0
BEGIN DESCRIPTION:
UNT 115 IN CACR 1.0
END DESCRIPTION:
XS GIS Cut Line= 4
      3685240.82     10708185.14      3685363.22     10708570.57
      3685483.01     10708599.21      3686139.24     10708453.39
#Sta/Elev= 30
  4540.1  314.03  4545.4  309.94  4561.0  303.94  4583.9  296.78  4616.1  290.05
  4860.2  292.07  4870.6  293.41  4933.6  292.08  4981.9  293.32  4992.2  290.76
  5004.5  284.15  5007.2  283.65  5010.5  284.15  5012.8  289.91  5023.0  290.65
  5187.1  291.29  5279.3  294.12  5310.0  293.38  5392.0  294.83  5402.2  293.80
  5463.7  294.95  5586.6  293.61  5617.4  296.43  5627.6  299.32  5678.8  302.10
  5684.7  305.30  5689.8  305.69  5699.3  310.32  5719.8  314.58  5739.9  321.24
#Mann=5,-1,0
  4540.1    0.16       0  4561.0    0.12       0  5004.5    0.07       0
  5010.5    0.12       0  5617.4    0.16       0
Bank Sta=5004.5,5010.5
Exp/Cntr=0.3,0.1

Chan Stop Cuts=-1