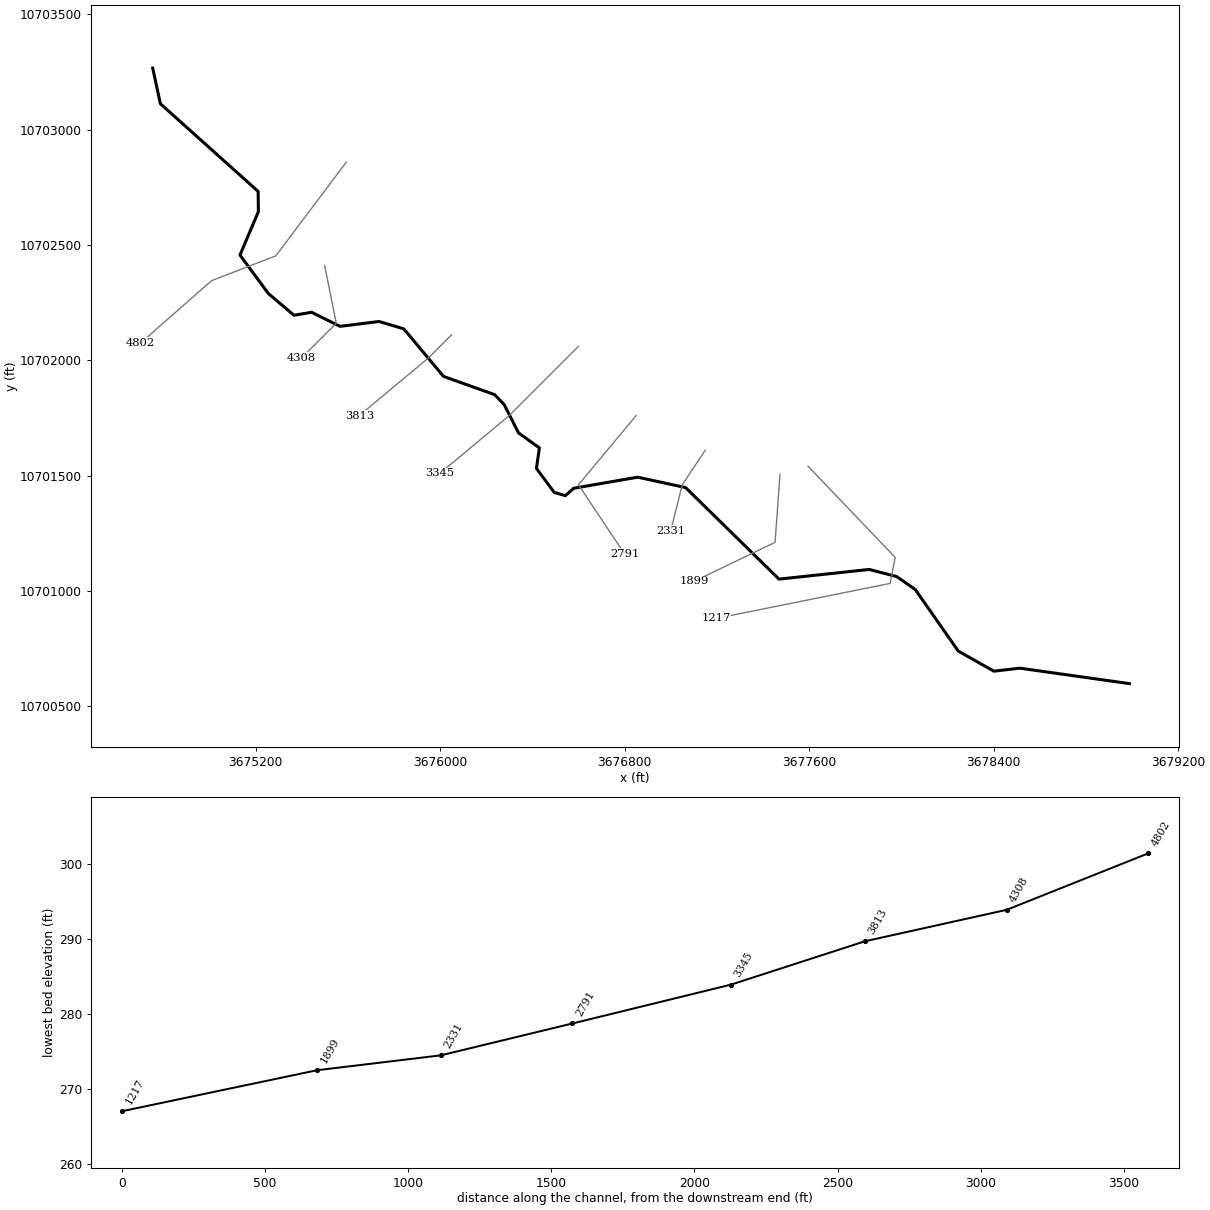
--- UNT 116 IN CACR.prj (project) ---

Proj Title=UNT 116 IN CACR Base Level Engineering
Current Plan=p01
Default Exp/Contr=0.3,0.1
English Units
Geom File=g01
Flow File=f01
Plan File=p01
Y Axis Title=Elevation
X Axis Title(PF)=Main Channel Distance
X Axis Title(XS)=Station
BEGIN DESCRIPTION:
UNT 116 IN CACR
END DESCRIPTION:
DSS Export Rating Curves= 0
DSS Export Rating Curve Sorted= 0
DSS Export Volume Flow Curves= 0
DXF OffsetX= 0
DXF OffsetY= 0
DXF ScaleX= 1
DXF ScaleY= 10

--- UNT 116 IN CACR.p01 (plan) ---

Plan Title=Multiple Run
Short Identifier=Multiple
Geom File=g01
Flow File=f01
Subcritical Flow
K Sum by GR= 0
Std Step Tol= 0.01
Critical Tol= 0.01
Num of Std Step Trials= 20
Max Error Tol= 0.3
Flow Tol Ratio= 0.001
Split Flow NTrial= 30
Split Flow Tol= 0.02
Split Flow Ratio= 0.02
Log Output Level= 0
Friction Slope Method= 1
Unsteady Friction Slope Method= 2
Unsteady Bridges Friction Slope Method= 1
Parabolic Critical Depth
Global Vel Dist=  1 , 1 , 1
Global Log Level= 0
CheckData=True
Encroach Param= -1, 0, 0, 0
BEGIN DESCRIPTION:
Multiple Run
END DESCRIPTION:

--- UNT 116 IN CACR.f01 (steady flow) ---

Flow Title=Multiple
Program Version=4.10
Number of Profiles= 7
Profile Names=10-year,25-year,50-year,1pct_min,100-year,1pct_plu,500-year
River Rch & RM=UNT 116 IN CACR,Reach-1         ,4802
     591     811     995     898    1214    1642    1816
Boundary for River Rch & Prof#=UNT 116 IN CACR,Reach-1         , 1
Up Type= 0
Dn Type= 3
Dn Slope=0.00804
Boundary for River Rch & Prof#=UNT 116 IN CACR,Reach-1         , 2
Up Type= 0
Dn Type= 3
Dn Slope=0.00804
Boundary for River Rch & Prof#=UNT 116 IN CACR,Reach-1         , 3
Up Type= 0
Dn Type= 3
Dn Slope=0.00804
Boundary for River Rch & Prof#=UNT 116 IN CACR,Reach-1         , 4
Up Type= 0
Dn Type= 3
Dn Slope=0.00804
Boundary for River Rch & Prof#=UNT 116 IN CACR,Reach-1         , 5
Up Type= 0
Dn Type= 3
Dn Slope=0.00804
Boundary for River Rch & Prof#=UNT 116 IN CACR,Reach-1         , 6
Up Type= 0
Dn Type= 3
Dn Slope=0.00804
Boundary for River Rch & Prof#=UNT 116 IN CACR,Reach-1         , 7
Up Type= 0
Dn Type= 3
Dn Slope=0.00804
DSS Import GetInterval= 0
DSS Import GetPeak= 0
DSS Import FillOption= 0

--- UNT 116 IN CACR.g01 (geometry) ---

Geom Title=Existing Conditions
Program Version=4.10

River Reach=UNT 116 IN CACR ,Reach-1
Reach XY= 30
       3674753.9     10703266.64      3674787.25       10703112.
        3675211.       10702732.        3675212.       10702644.
      3675132.25       10702456.       3675255.5       10702289.
       3675366.5       10702195.        3675443.       10702208.
      3675565.75       10702147.      3675735.25       10702168.
       3675842.5       10702136.       3676014.5       10701930.
        3676236.       10701851.       3676277.5       10701808.
        3676340.       10701685.      3676430.25       10701620.
       3676417.5       10701531.       3676494.5       10701427.
        3676543.       10701413.        3676579.       10701445.
      3676856.25       10701493.        3677064.       10701448.
        3677469.       10701051.        3677860.       10701093.
       3677979.5       10701062.      3678059.75       10701006.
      3678246.25       10700739.       3678400.5       10700652.
        3678513.       10700665.      3678988.25       10700598.

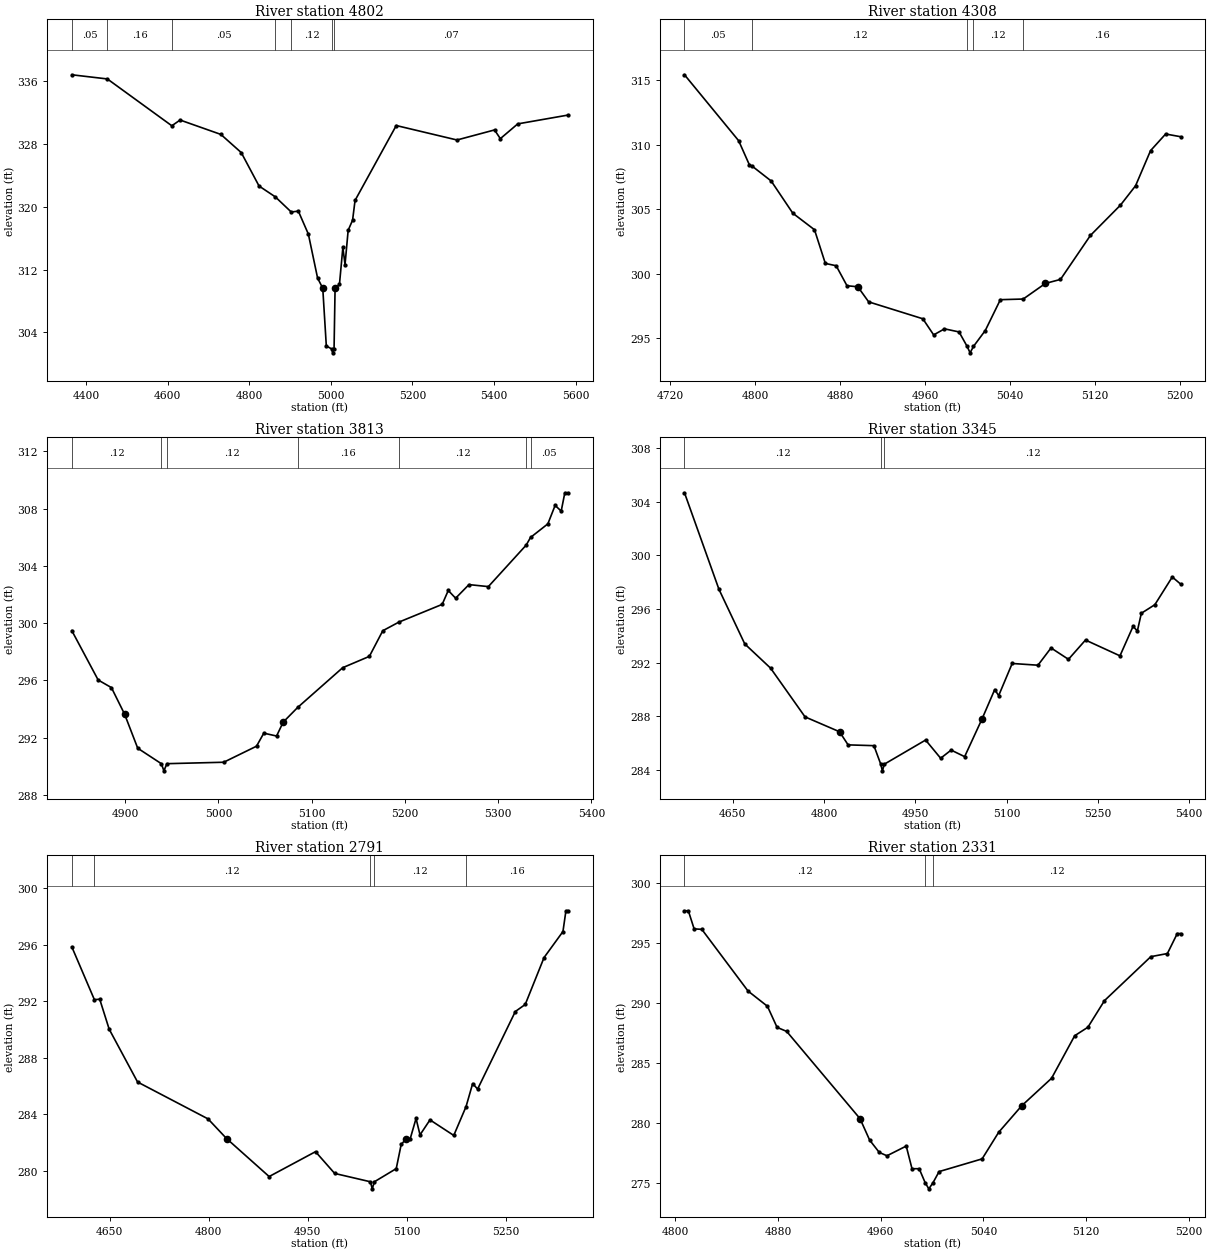
Type RM Length L Ch R = 1 ,4802    ,494,494,494
BEGIN DESCRIPTION:
UNT 116 IN CACR 7.0
END DESCRIPTION:
XS GIS Cut Line= 4
      3675593.22     10702858.78      3675287.68     10702452.55
      3675008.97     10702345.01      3674701.49     10702074.62
#Sta/Elev= 30
  4364.7  336.79  4451.9  336.26    4610   330.3  4630.3  331.03  4730.2   329.2
  4780.2  326.89  4823.9  322.63  4863.8  321.25  4902.9  319.32  4920.2  319.44
  4944.8  316.51  4967.4  310.92  4980.1  309.62  4988.8  302.28  5001.8   301.9
  5004.5   301.4  5007.8   301.9  5010.3   309.6    5021   310.1  5029.4  314.81
  5034.7  312.64  5042.4     317  5053.2  318.28  5059.3   320.8  5160.3  330.33
  5309.2  328.49  5401.3  329.77  5415.5  328.66  5458.2  330.54  5581.2  331.66
#Mann= 7 ,-1 , 0
  4364.7     .05       0  4451.9     .16       0    4610     .05       0
  4863.8     .16       0  4902.9     .12       0  5001.8     .09       0
  5007.8     .07       0
Bank Sta=4980.1,5010.3
XS Rating Curve= 0 ,0
Exp/Cntr=0.3,0.1

Type RM Length L Ch R = 1 ,4308    ,495,495,495
BEGIN DESCRIPTION:
UNT 116 IN CACR 6.0
END DESCRIPTION:
XS GIS Cut Line= 3
      3675499.61      10702410.2      3675549.61     10702160.19
       3675399.6     10702010.18
#Sta/Elev= 30
  4733.3  315.43  4784.3  310.32  4794.5  308.43    4797  308.35  4814.9   307.2
  4835.3   304.7  4855.7  303.42  4865.9  300.81  4876.1  300.63  4886.3  299.08
  4896.5     299  4906.7  297.83  4957.7  296.52  4967.9  295.27  4978.1  295.74
  4991.8   295.5  4999.4  294.38  5002.2  293.88  5005.4  294.38  5016.5  295.61
  5030.7     298  5052.2  298.05  5073.1  299.26  5087.3  299.57  5115.5  302.98
  5143.8  305.33    5158  306.83  5172.1  309.55  5186.3  310.84  5200.4  310.63
#Mann= 5 ,-1 , 0
  4733.3     .05       0    4797     .12       0  4999.4     .07       0
  5005.4     .12       0  5052.2     .16       0
Bank Sta=4896.5,5073.1
XS Rating Curve= 0 ,0
Exp/Cntr=0.3,0.1

Type RM Length L Ch R = 1 ,3813    ,468,468,468
BEGIN DESCRIPTION:
UNT 116 IN CACR 5.0
END DESCRIPTION:
XS GIS Cut Line= 3
      3676049.63     10702110.21      3675949.61     10702010.19
      3675649.58     10701760.17
#Sta/Elev= 30
  4842.7  299.48    4871  296.03  4885.2   295.5  4899.3  293.65  4913.4  291.27
  4938.7  290.19  4941.5  289.69  4944.7  290.19  5005.6  290.29  5040.8  291.41
  5048.6  292.32  5062.3  292.12  5069.4  293.09    5085  294.12  5133.2  296.89
  5161.8  297.68  5176.2  299.47  5193.4  300.07  5239.9  301.31  5246.4  302.28
  5254.3  301.74  5268.6  302.69  5289.4  302.55    5330  305.45  5334.6  305.98
  5353.2  306.93    5361  308.22  5367.5  307.82  5371.4   309.1  5374.7   309.1
#Mann= 7 ,-1 , 0
  4842.7     .12       0  4938.7     .07       0  4944.7     .12       0
    5085     .16       0  5193.4     .12       0    5330     .16       0
  5334.6     .05       0
Bank Sta=4899.3,5069.4
XS Rating Curve= 0 ,0
Exp/Cntr=0.3,0.1

Type RM Length L Ch R = 1 ,3345    ,554,554,554
BEGIN DESCRIPTION:
UNT 116 IN CACR 4.0
END DESCRIPTION:
XS GIS Cut Line= 3
      3676599.61     10702060.19      3676299.61     10701760.19
       3675999.6     10701510.18
#Sta/Elev= 30
    4571  304.68  4627.6  297.47    4670  293.39  4712.4  291.58    4769  287.94
  4825.6  286.83  4839.7  285.85  4882.1  285.79  4893.3  284.41    4896  283.91
  4899.3  284.41    4967  286.21  4991.7  284.85  5008.9  285.46  5031.1  284.97
  5059.7  287.79  5080.5  289.98    5087  289.53  5109.2  291.93  5151.5   291.8
    5173  293.09  5201.6  292.24  5229.6  293.68  5286.2   292.5  5307.7   294.7
  5314.8  294.36  5321.3  295.68  5343.5  296.32  5372.1  298.39  5385.8  297.86
#Mann= 3 ,-1 , 0
    4571     .12       0  4893.3     .07       0  4899.3     .12       0
Bank Sta=4825.6,5059.7
XS Rating Curve= 0 ,0
Exp/Cntr=0.3,0.1

Type RM Length L Ch R = 1 ,2791    ,460,460,460
BEGIN DESCRIPTION:
UNT 116 IN CACR 3.0
END DESCRIPTION:
XS GIS Cut Line= 3
      3676849.62      10701760.2      3676599.61     10701460.19
      3676799.62     10701160.17
#Sta/Elev= 30
  4592.8  295.86    4627  292.12  4635.1  292.15  4649.4  290.03  4692.4  286.29
  4799.1  283.68  4827.1  282.29  4891.6   279.6  4961.8  281.36  4990.8  279.82
  5044.9  279.23  5047.7  278.73  5050.9  279.23    5084  280.16  5091.5  281.87
    5099  282.27    5105  282.25    5114  283.71    5120  282.55  5135.1  283.61
  5171.1  282.51  5189.7  284.55  5199.7  286.18  5207.2  285.79  5264.3  291.28
  5279.3  291.78  5307.8   295.1  5336.4  296.94  5340.9  298.41  5343.9  298.41
#Mann= 5 ,-1 , 0
  4592.8     .16       0    4627     .12       0  5044.9     .07       0
  5050.9     .12       0  5189.7     .16       0
Bank Sta=4827.1,5099
XS Rating Curve= 0 ,0
Exp/Cntr=0.3,0.1

Type RM Length L Ch R = 1 ,2331    ,432,432,432
BEGIN DESCRIPTION:
UNT 116 IN CACR 2.0
END DESCRIPTION:
XS GIS Cut Line= 3
      3677149.59     10701610.15      3677049.61     10701460.19
      3676999.61     10701260.18
#Sta/Elev= 30
  4807.2  297.69  4810.2  297.69  4814.7  296.18  4820.7  296.14  4856.7  290.99
  4871.8  289.72  4879.3  287.96  4886.8  287.62  4943.9  280.34  4951.4  278.55
  4958.9  277.52  4964.9  277.24  4979.9  278.05  4984.4  276.16    4990  276.16
  4994.7  274.98  4997.5  274.48  5000.7  274.98  5005.5  275.92    5039  276.98
  5051.9   279.2  5069.9  281.42  5093.1  283.71  5111.1  287.26  5121.4  287.97
  5134.3  290.19  5170.4  293.86  5183.3  294.12    5191  295.79  5193.6  295.79
#Mann= 3 ,-1 , 0
  4807.2     .12       0  4994.7     .07       0  5000.7     .12       0
Bank Sta=4943.9,5069.9
XS Rating Curve= 0 ,0
Exp/Cntr=0.3,0.1

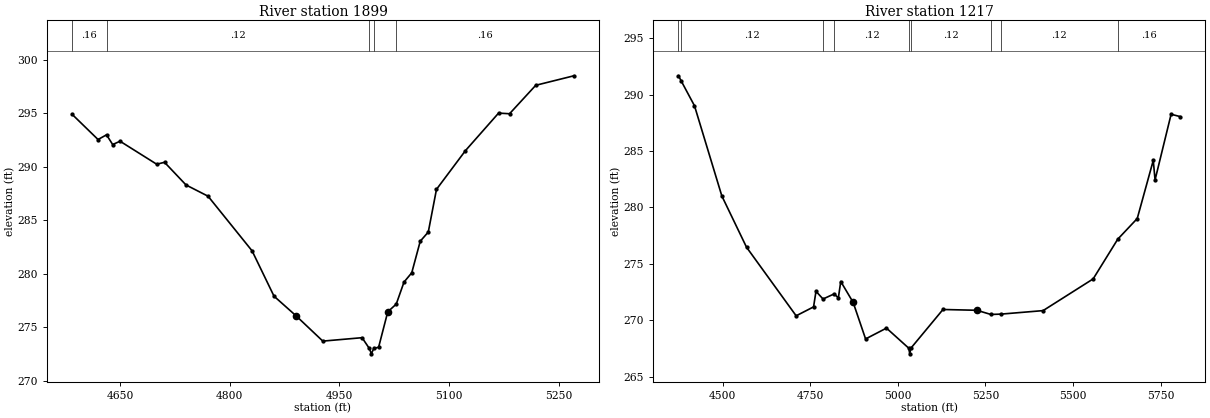
Type RM Length L Ch R = 1 ,1899    ,682,682,682
BEGIN DESCRIPTION:
Mapping XS 093900df
END DESCRIPTION:
XS GIS Cut Line= 3
      3677473.56     10701505.58      3677451.86     10701210.46
       3677100.3     10701041.19
#Sta/Elev= 30
  4584.5   294.9    4620  292.54  4631.6  292.98    4640  292.07  4650.1  292.38
  4700.2  290.23  4710.9  290.41  4740.3  288.29  4770.4  287.24  4830.6  282.13
  4860.6  277.89  4890.5  276.07  4927.3  273.69    4981  274.01  4990.9     273
  4993.7   272.5  4996.9     273  5003.6  273.12  5016.1  276.43  5027.7  277.15
  5038.3  279.21  5048.9  280.08  5060.5  283.03  5071.5  283.89  5082.7  287.88
  5122.3   291.5  5167.6  295.01  5182.6  294.95  5218.4  297.61  5270.6   298.5
#Mann= 5 ,-1 , 0
  4584.5     .16       0  4631.6     .12       0  4990.9     .07       0
  4996.9     .12       0  5027.7     .16       0
Bank Sta=4890.5,5016.1
XS Rating Curve= 0 ,0
Exp/Cntr=0.3,0.1

Type RM Length L Ch R = 1 ,1217    ,0,0,0
BEGIN DESCRIPTION:
UNT 116 IN CACR 1.0
END DESCRIPTION:
XS GIS Cut Line= 4
      3677595.07     10701540.35       3677972.7     10701145.36
        3677951.     10701032.51       3677195.8      10700880.6
#Sta/Elev= 30
  4374.4  291.67  4382.2  291.21  4420.1  289.01  4498.1  281.02  4568.5  276.48
  4710.1   270.4  4759.8  271.19  4766.7  272.57  4786.8  271.89  4818.5  272.34
  4830.5  271.99  4837.4  273.44  4872.7  271.59  4908.2  268.35  4967.8  269.31
  5031.4  267.53  5034.2  267.03  5037.4  267.53    5129  270.96  5225.5  270.89
  5265.7  270.52  5294.4  270.55  5414.6  270.86  5557.4  273.67  5627.6  277.19
  5683.2  279.02  5728.9  284.17    5734  282.44  5779.8  288.26  5806.1  288.05
#Mann= 9 ,-1 , 0
  4374.4     .16       0  4382.2     .12       0  4786.8     .16       0
  4818.5     .12       0  5031.4     .07       0  5037.4     .12       0
  5265.7     .16       0  5294.4     .12       0  5627.6     .16       0
Bank Sta=4872.7,5225.5
XS Rating Curve= 0 ,0
Exp/Cntr=0.3,0.1

Chan Stop Cuts=-1
Use User Specified Reach Order=0
Composite Channel Slope=5