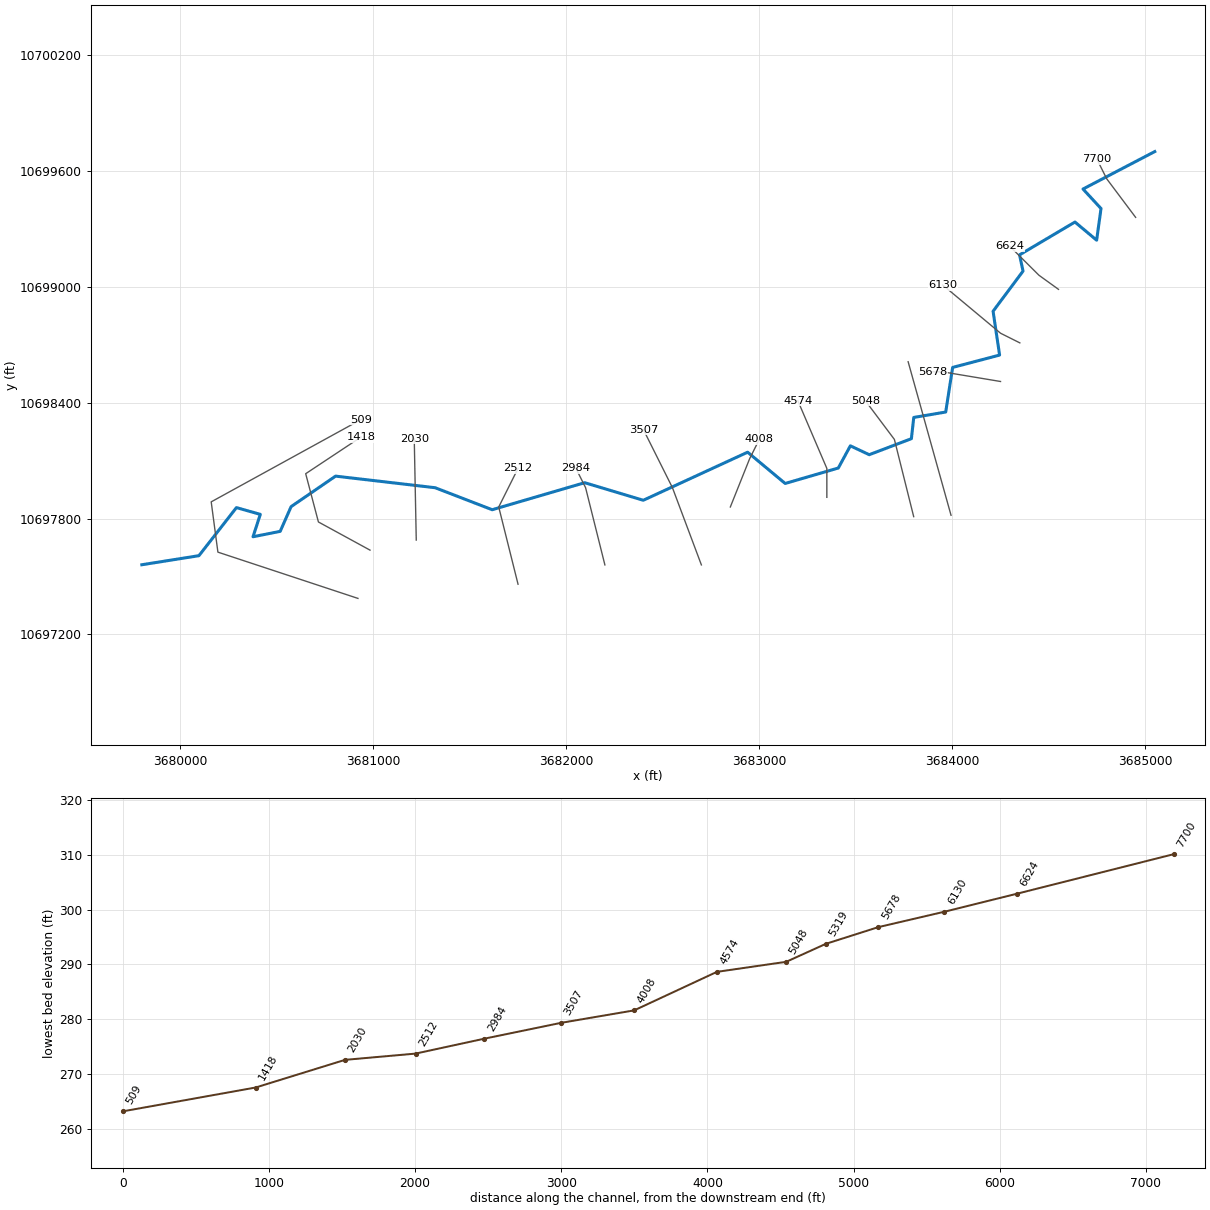
--- UNT 117 IN CACR.prj (project) ---

Proj Title=UNT 117 IN CACR Base Level Engineering
Current Plan=p01
Default Exp/Contr=0.3,0.1
English Units
Geom File=g01
Flow File=f01
Plan File=p01
Y Axis Title=Elevation
X Axis Title(PF)=Main Channel Distance
X Axis Title(XS)=Station
BEGIN DESCRIPTION:
UNT 117 IN CACR
END DESCRIPTION:
DSS Export Rating Curves= 0
DSS Export Rating Curve Sorted= 0
DSS Export Volume Flow Curves= 0
DXF OffsetX= 0
DXF OffsetY= 0
DXF ScaleX= 1
DXF ScaleY= 10

--- UNT 117 IN CACR.p01 (plan) ---

Plan Title=Multiple Run
Short Identifier=Multiple
Geom File=g01
Flow File=f01
Subcritical Flow
K Sum by GR= 0
Std Step Tol= 0.01
Critical Tol= 0.01
Num of Std Step Trials= 20
Max Error Tol= 0.3
Flow Tol Ratio= 0.001
Split Flow NTrial= 30
Split Flow Tol= 0.02
Split Flow Ratio= 0.02
Log Output Level= 0
Friction Slope Method= 1
Unsteady Friction Slope Method= 2
Unsteady Bridges Friction Slope Method= 1
Parabolic Critical Depth
Global Vel Dist=  1 , 1 , 1
Global Log Level= 0
CheckData=True
Encroach Param= -1, 0, 0, 0
BEGIN DESCRIPTION:
Multiple Run
END DESCRIPTION:

--- UNT 117 IN CACR.f01 (steady flow) ---

Flow Title=Multiple
Program Version=4.10
Number of Profiles= 7
Profile Names=10-year,25-year,50-year,1pct_min,100-year,1pct_plu,500-year
River Rch & RM=UNT 117 IN CACR,Reach-1         ,7700
     471     632     764     680     919    1243    1336
River Rch & RM=UNT 117 IN CACR,Reach-1         ,5319
     471     632     764     680     919    1243    1336
Boundary for River Rch & Prof#=UNT 117 IN CACR,Reach-1         , 1
Up Type= 0
Dn Type= 3
Dn Slope=0.00487
Boundary for River Rch & Prof#=UNT 117 IN CACR,Reach-1         , 2
Up Type= 0
Dn Type= 3
Dn Slope=0.00487
Boundary for River Rch & Prof#=UNT 117 IN CACR,Reach-1         , 3
Up Type= 0
Dn Type= 3
Dn Slope=0.00487
Boundary for River Rch & Prof#=UNT 117 IN CACR,Reach-1         , 4
Up Type= 0
Dn Type= 3
Dn Slope=0.00487
Boundary for River Rch & Prof#=UNT 117 IN CACR,Reach-1         , 5
Up Type= 0
Dn Type= 3
Dn Slope=0.00487
Boundary for River Rch & Prof#=UNT 117 IN CACR,Reach-1         , 6
Up Type= 0
Dn Type= 3
Dn Slope=0.00487
Boundary for River Rch & Prof#=UNT 117 IN CACR,Reach-1         , 7
Up Type= 0
Dn Type= 3
Dn Slope=0.00487
DSS Import GetInterval= 0
DSS Import GetPeak= 0
DSS Import FillOption= 0

--- UNT 117 IN CACR.g01 (geometry) ---

Geom Title=Existing Conditions
Program Version=4.10

River Reach=UNT 117 IN CACR ,Reach-1
Reach XY= 30
      3685048.75       10699701.        3684677.       10699507.
      3684770.25       10699406.       3684747.5       10699242.
      3684635.25       10699336.        3684348.       10699166.
      3684366.25       10699082.        3684211.       10698874.
      3684244.75       10698647.       3684001.5       10698583.
       3683965.5       10698352.        3683800.       10698324.
      3683787.75       10698214.      3683569.25       10698131.
       3683471.5       10698177.        3683409.       10698062.
      3683133.75       10697982.      3682939.25       10698144.
       3682398.5       10697895.        3682095.       10697986.
      3681615.75       10697846.        3681320.       10697960.
      3680804.25       10698020.      3680573.75       10697862.
      3680517.25       10697734.       3680376.5       10697706.
      3680414.25       10697822.       3680290.5       10697857.
      3680096.25       10697608.      3679800.25       10697561.

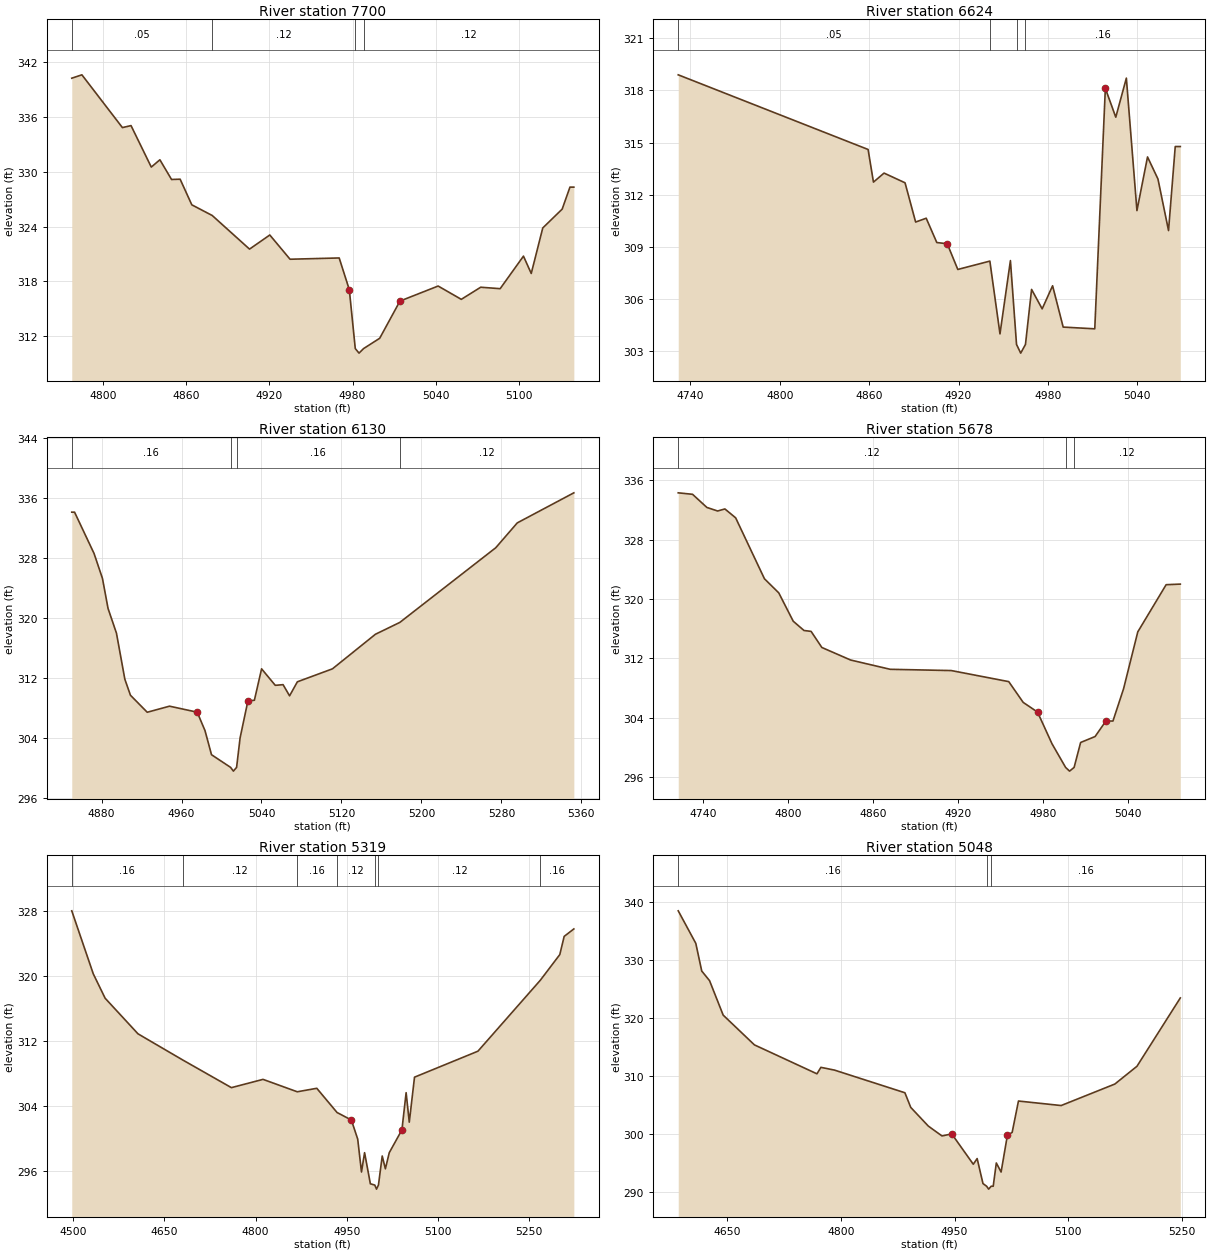
Type RM Length L Ch R = 1 ,7700    ,1076,1076,1076
BEGIN DESCRIPTION:
UNT 117 IN CACR 12.0
END DESCRIPTION:
XS GIS Cut Line= 3
      3684949.61     10699360.19      3684799.61     10699560.19
      3684749.61     10699660.19
#Sta/Elev= 30
  4777.7  340.27    4785  340.64  4814.2  334.85  4820.4  335.07    4835  330.52
  4841.2  331.32  4849.6  329.16  4855.8  329.19  4864.2  326.38  4878.9  325.21
  4905.8  321.52  4920.4  323.07    4935  320.41  4970.4  320.55  4977.7  317.07
    4982  310.61  4984.7  310.11    4988  310.61  4999.6  311.74  5014.2  315.82
  5041.7  317.47  5058.4  316.01  5072.4  317.34  5086.4  317.18  5103.2  320.75
  5108.8  318.85  5117.1  323.84  5131.1  325.91  5136.7  328.32  5139.5  328.32
#Mann= 4 ,-1 , 0
  4777.7     .05       0  4878.9     .12       0    4982     .07       0
    4988     .12       0
Bank Sta=4977.7,5014.2
XS Rating Curve= 0 ,0
Exp/Cntr=0.3,0.1

Type RM Length L Ch R = 1 ,6624    ,494,494,494
BEGIN DESCRIPTION:
Mapping XS b28fb36b
END DESCRIPTION:
XS GIS Cut Line= 3
      3684549.91     10698987.46      3684449.04     10699060.13
      3684298.19      10699209.9
#Sta/Elev= 30
  4731.9   318.9  4859.3   314.6  4862.9  312.72    4870  313.24  4884.1  312.68
  4891.2  310.42  4898.3  310.64  4905.4  309.24  4912.4  309.17  4919.5  307.69
    4941  308.17  4947.8  303.98  4954.8   308.2  4958.9  303.37  4961.7  302.87
  4964.9  303.37    4969  306.54  4976.1  305.42  4983.1  306.75  4990.2  304.37
  5011.4  304.27  5018.5  318.12  5025.5  316.46  5032.6  318.71  5039.7  311.08
  5046.8  314.17  5053.8   312.9  5060.9  309.93  5065.4  314.77  5068.8  314.77
#Mann= 4 ,-1 , 0
  4731.9     .05       0    4941     .16       0  4958.9     .07       0
  4964.9     .16       0
Bank Sta=4912.4,5018.5
XS Rating Curve= 0 ,0
Exp/Cntr=0.3,0.1

Type RM Length L Ch R = 1 ,6130    ,452,452,452
BEGIN DESCRIPTION:
UNT 117 IN CACR 10.0
END DESCRIPTION:
XS GIS Cut Line= 3
       3684349.6     10698710.19      3684249.61     10698760.19
      3683949.61     10699010.19
#Sta/Elev= 30
  4850.2  334.13    4853  334.13  4872.5  328.62  4880.9   325.3  4886.5  321.29
  4894.9     318  4903.3  311.86  4908.9  309.72  4925.7  307.45    4948  308.26
  4975.7  307.46  4983.5     305    4990  301.79  5009.1   300.1  5011.9   299.6
  5015.1   300.1  5018.6  304.03  5026.4  308.95  5032.9  309.05  5040.1  313.24
  5053.8  311.04  5061.6  311.13  5068.1  309.64  5075.9  311.51    5111  313.24
    5154  317.85  5178.4  319.43  5274.4  329.39  5295.9   332.7  5352.5  336.71
#Mann= 4 ,-1 , 0
  4850.2     .16       0  5009.1     .07       0  5015.1     .16       0
  5178.4     .12       0
Bank Sta=4975.7,5026.4
XS Rating Curve= 0 ,0
Exp/Cntr=0.3,0.1

Type RM Length L Ch R = 1 ,5678    ,359,359,359
BEGIN DESCRIPTION:
UNT 117 IN CACR 9.0
END DESCRIPTION:
XS GIS Cut Line= 3
      3684249.58     10698510.19      3683949.61     10698560.19
      3683899.62     10698560.19
#Sta/Elev= 30
  4722.7  334.29  4732.8  334.09  4742.9  332.32  4750.5  331.84  4755.6  332.12
  4763.2  330.92  4783.5  322.71  4793.6  320.81  4803.8  316.99  4811.4  315.74
  4816.4  315.62    4824  313.45  4844.3  311.76  4872.2  310.51  4915.3  310.34
  4955.8  308.85    4966  306.05  4976.1  304.75  4986.3  300.48  4995.9  297.29
  4998.7  296.79  5001.9  297.29  5006.5  300.65  5016.7  301.45  5024.3  303.54
  5029.3  303.54  5036.8   307.9  5046.8  315.55  5066.8  321.91  5076.8  321.99
#Mann= 3 ,-1 , 0
  4722.7     .12       0  4995.9     .07       0  5001.9     .12       0
Bank Sta=4976.1,5024.3
XS Rating Curve= 0 ,0
Exp/Cntr=0.3,0.1

Type RM Length L Ch R = 1 ,5319    ,271,271,271
BEGIN DESCRIPTION:
Mapping XS 39135fca
END DESCRIPTION:
XS GIS Cut Line= 2
      3683993.09     10697817.34      3683770.87     10698612.47
#Sta/Elev= 30
  4497.6  328.02    4533  320.25  4552.5  317.25  4606.5  312.87    4680  309.65
  4760.1  306.24  4812.1  307.26  4868.4  305.73  4900.5  306.16  4933.8  303.18
  4957.4  302.25  4967.8   299.9    4974  295.85  4979.1  298.23  4988.6   294.4
  4995.9  294.24  4998.7  293.74  5001.9  294.24  5008.1  297.82  5013.3  296.24
  5019.7  298.23  5040.5  301.04  5047.4  305.62  5052.6  301.99  5061.2  307.53
  5165.5  310.73  5268.1  319.47  5300.1  322.63  5307.3  324.87  5323.2  325.79
#Mann= 7 ,-1 , 0
  4497.6     .16       0    4680     .12       0  4868.4     .16       0
  4933.8     .12       0  4995.9     .07       0  5001.9     .12       0
  5268.1     .16       0
Bank Sta=4957.4,5040.5
XS Rating Curve= 0 ,0
Exp/Cntr=0.3,0.1

Type RM Length L Ch R = 1 ,5048    ,474,474,474
BEGIN DESCRIPTION:
UNT 117 IN CACR 8.0
END DESCRIPTION:
XS GIS Cut Line= 3
      3683799.62     10697810.15      3683699.61     10698210.19
      3683549.64     10698410.15
#Sta/Elev= 30
  4585.5  338.54  4608.7  332.91  4616.5  328.14  4626.8  326.48  4644.8  320.52
    4686  315.38  4768.5  310.38  4773.7   311.5  4791.7  311.02  4884.5  307.11
  4892.2  304.58  4915.4  301.35  4933.4  299.65  4946.3     300  4974.7  294.76
  4979.8  295.74  4987.5  291.42  4992.3  290.96    4995  290.46  4998.3  290.96
    5001  290.96  5005.1  294.98  5011.4  293.41  5019.7  299.76    5026  300.26
  5034.3  305.68  5090.6   304.9  5161.4  308.61  5190.6  311.68  5247.8  323.49
#Mann= 3 ,-1 , 0
  4585.5     .16       0  4992.3     .07       0  4998.3     .16       0
Bank Sta=4946.3,5019.7
XS Rating Curve= 0 ,0
Exp/Cntr=0.3,0.1

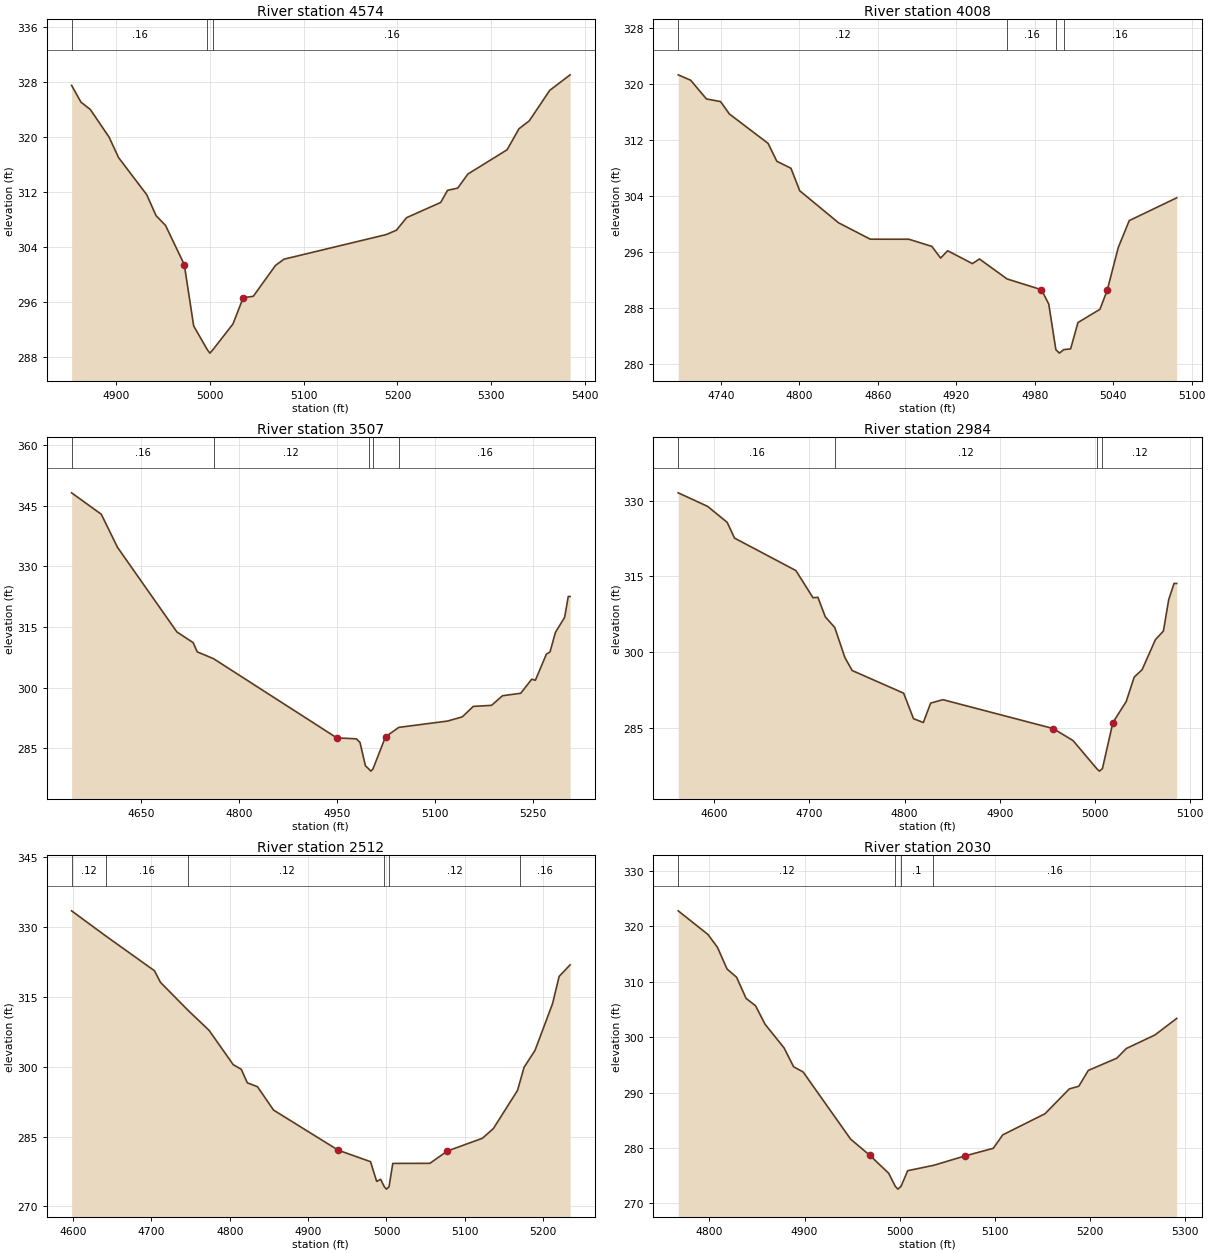
Type RM Length L Ch R = 1 ,4574    ,566,566,566
BEGIN DESCRIPTION:
UNT 117 IN CACR 7.0
END DESCRIPTION:
XS GIS Cut Line= 3
      3683349.61     10697910.17      3683349.61     10698060.19
      3683199.61     10698410.18
#Sta/Elev= 30
    4853  327.53    4863  325.09    4873  324.02    4893  319.99    4903  317.04
    4933  311.65    4943  308.59    4953  307.19    4973  301.49    4983  292.58
  4997.5  289.13  5000.3  288.63  5003.5  289.13  5024.8  292.86  5035.7  296.67
  5046.5  296.89  5070.1  301.37  5079.2  302.28    5188  305.85  5198.9  306.49
  5209.7  308.31    5246  310.52  5253.3  312.28  5264.1   312.6    5275  314.65
  5316.7  318.17  5329.4  321.23  5340.3  322.37  5362.1   326.8  5383.8  329.06
#Mann= 3 ,-1 , 0
    4853     .16       0  4997.5     .07       0  5003.5     .16       0
Bank Sta=4973,5035.7
XS Rating Curve= 0 ,0
Exp/Cntr=0.3,0.1

Type RM Length L Ch R = 1 ,4008    ,501,501,501
BEGIN DESCRIPTION:
UNT 117 IN CACR 6.0
END DESCRIPTION:
XS GIS Cut Line= 3
      3682849.59     10697860.15      3682949.61     10698110.19
      3682999.61     10698210.19
#Sta/Elev= 30
  4707.5  321.36    4717  320.59  4729.1  317.91  4739.9  317.54  4746.6  315.77
  4776.2  311.57  4782.9  309.01  4793.7  308.01  4800.4   304.8  4830.1  300.22
  4854.3  297.88  4883.9  297.87  4901.4  296.85  4908.1  295.18  4913.5  296.23
  4932.4  294.39  4937.8  295.05  4958.9   292.2  4985.2  290.66  4990.8   288.6
  4996.2   282.1  4998.9   281.6  5002.2   282.1  5007.5  282.21  5013.1  285.97
  5029.9  287.86  5035.5   290.6  5043.9  296.67  5052.3  300.53  5088.6  303.79
#Mann= 4 ,-1 , 0
  4707.5     .12       0  4958.9     .16       0  4996.2     .07       0
  5002.2     .16       0
Bank Sta=4985.2,5035.5
XS Rating Curve= 0 ,0
Exp/Cntr=0.3,0.1

Type RM Length L Ch R = 1 ,3507    ,523,523,523
BEGIN DESCRIPTION:
UNT 117 IN CACR 5.0
END DESCRIPTION:
XS GIS Cut Line= 3
      3682699.61      10697560.2      3682549.61     10697960.19
      3682399.61     10698260.19
#Sta/Elev= 30
  4544.1  348.16  4589.5  342.87  4614.4  334.66  4705.2  313.75  4730.1   311.1
  4736.3  308.83  4761.4  307.12  4949.9  287.54  4979.7  287.31  4985.3  286.42
  4993.6  280.64    4999  279.82  5001.8  279.32    5005  279.82  5024.4  287.82
  5044.7  290.14  5119.4  291.71  5141.8  292.75  5158.6  295.33  5186.5  295.59
  5203.3  297.97  5231.2  298.58    5248  302.06  5253.6   301.8  5270.4  308.25
    5276  308.81  5284.3  313.65  5298.3  317.35  5303.9  322.52  5306.7  322.52
#Mann= 5 ,-1 , 0
  4544.1     .16       0  4761.4     .12       0    4999     .07       0
    5005     .12       0  5044.7     .16       0
Bank Sta=4949.9,5024.4
XS Rating Curve= 0 ,0
Exp/Cntr=0.3,0.1

Type RM Length L Ch R = 1 ,2984    ,472,472,472
BEGIN DESCRIPTION:
UNT 117 IN CACR 4.0
END DESCRIPTION:
XS GIS Cut Line= 3
       3682199.6     10697560.22      3682099.61     10697960.19
       3682049.6     10698060.21
#Sta/Elev= 30
    4562  331.52  4592.9  328.84  4613.5  325.68  4621.2  322.56  4685.7  316.14
  4703.7  310.76  4708.9  310.83  4716.6  306.99  4726.6  304.86  4737.2  298.94
  4744.9  296.35    4799  291.87  4809.4  286.82  4819.7  286.06  4827.4   289.9
  4840.3  290.58  4956.2  284.87  4977.1  282.49    5002  276.94  5004.8  276.44
    5008  276.94    5019  286.05    5033  290.21  5041.4  295.05  5049.7  296.51
  5063.7  302.46  5072.1  304.16  5077.7  310.39  5083.3  313.58  5086.1  313.58
#Mann= 4 ,-1 , 0
    4562     .16       0  4726.6     .12       0    5002     .07       0
    5008     .12       0
Bank Sta=4956.2,5019
XS Rating Curve= 0 ,0
Exp/Cntr=0.3,0.1

Type RM Length L Ch R = 1 ,2512    ,482,482,482
BEGIN DESCRIPTION:
UNT 117 IN CACR 3.0
END DESCRIPTION:
XS GIS Cut Line= 3
      3681749.62     10697460.15      3681649.61     10697860.19
      3681749.63     10698060.23
#Sta/Elev= 30
  4598.3  333.47  4641.6  328.11    4704  320.61  4711.7  318.11  4747.4  312.02
  4773.6  307.83  4804.5  300.44  4814.8  299.44  4822.5  296.54  4835.4  295.71
    4856  290.68  4938.5  282.07  4979.7   279.6  4987.5  275.37  4992.6  275.82
  4997.3  274.21  5000.1  273.71  5003.3  274.21  5008.1  279.23  5055.4  279.25
  5077.7  281.89  5122.4  284.63  5136.4  286.71  5167.2   294.9  5170.7  296.97
  5175.6  299.87  5189.5  303.49  5211.9  313.52  5220.3  319.38  5234.3  321.87
#Mann= 6 ,-1 , 0
  4598.3     .12       0  4641.6     .16       0  4747.4     .12       0
  4997.3     .07       0  5003.3     .12       0  5170.7     .16       0
Bank Sta=4938.5,5077.7
XS Rating Curve= 0 ,0
Exp/Cntr=0.3,0.1

Type RM Length L Ch R = 1 ,2030    ,612,612,612
BEGIN DESCRIPTION:
UNT 117 IN CACR 2.0
END DESCRIPTION:
XS GIS Cut Line= 2
      3681222.26     10697688.85      3681211.85     10698213.14
#Sta/Elev= 30
  4767.1  322.83  4798.4  318.56  4808.4  316.24  4818.5  312.32  4828.5  310.84
  4838.5  307.02  4848.5  305.68  4858.5  302.34  4878.5  298.06  4888.5  294.67
  4898.5  293.73  4948.5  281.59  4968.5   278.7  4988.5  275.44  4995.5  273.07
  4998.2  272.57  5001.5  273.07  5008.5   275.9  5035.6  276.86  5068.5  278.55
  5098.5  279.94  5108.5  282.37    5153  286.19  5178.5  290.67  5188.5  291.15
  5198.5  294.01  5228.5  296.22  5238.5  297.97  5268.5   300.4  5291.5   303.4
#Mann= 4 ,-1 , 0
  4767.1     .12       0  4995.5     .07       0  5001.5      .1       0
  5035.6     .16       0
Bank Sta=4968.5,5068.5
XS Rating Curve= 0 ,0
Exp/Cntr=0.3,0.1

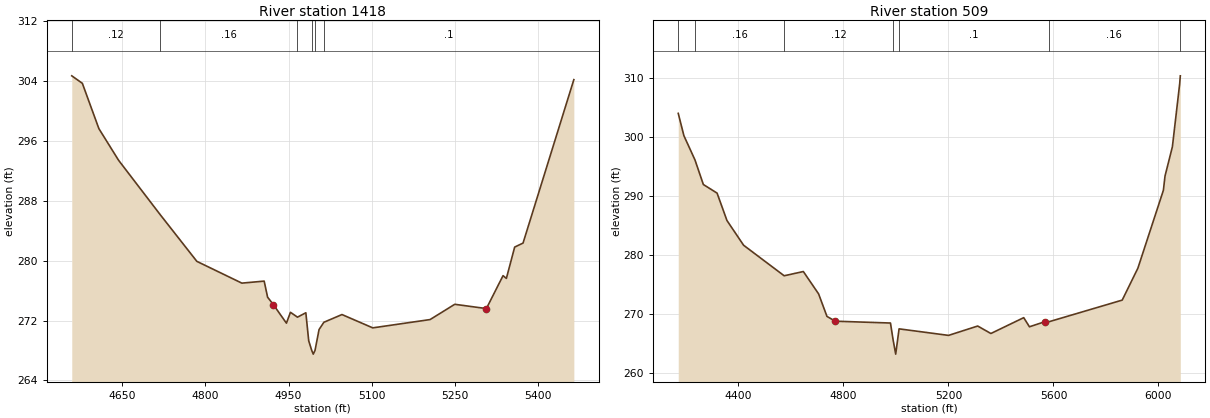
Type RM Length L Ch R = 1 ,1418    ,909,909,909
BEGIN DESCRIPTION:
Mapping XS b9a92d29
END DESCRIPTION:
XS GIS Cut Line= 4
      3680982.67     10697636.76      3680715.32     10697782.58
      3680649.35     10698032.58      3680936.11     10698222.61
#Sta/Elev= 30
  4558.4  304.72  4577.5  303.72  4607.4  297.66    4643  293.43  4718.1  286.17
  4784.4  279.92  4865.7  277.01    4906  277.28  4912.2  275.13  4922.5  274.15
  4946.2  271.66  4953.5  273.11  4966.2  272.46  4981.3  273.05  4986.5   269.3
  4991.9  268.02  4994.7  267.52  4997.9  268.02  5005.2  270.81  5013.9  271.78
  5046.6  272.81  5102.2  271.03  5205.8  272.14  5250.3  274.18  5307.5  273.61
  5337.6  278.01  5343.6  277.64  5358.6  281.83  5373.7  282.36  5465.5  304.21
#Mann= 6 ,-1 , 0
  4558.4     .12       0  4718.1     .16       0  4966.2     .09       0
  4991.9      .7       0  4997.9     .09       0  5013.9      .1       0
Bank Sta=4922.5,5307.5
XS Rating Curve= 0 ,0
Exp/Cntr=0.3,0.1

Type RM Length L Ch R = 1 ,509     ,0,0,0
BEGIN DESCRIPTION:
UNT 117 IN CACR 1.0
END DESCRIPTION:
XS GIS Cut Line= 4
      3680920.17     10697386.75      3680194.49     10697626.33
      3680159.76     10697886.75      3680936.09     10698313.04
#Sta/Elev= 30
  4170.7  304.04  4192.3  300.25  4234.6  296.12  4266.4  291.96  4318.7   290.5
  4356.3  285.85  4419.8  281.65  4574.3  276.47  4647.3  277.19  4705.5  273.39
  4737.3  269.57    4769  268.76  4979.2  268.45  4989.2   265.6  4999.1  263.17
    5012  267.46  5200.4  266.35  5311.5  267.94  5361.7  266.67  5486.8  269.36
  5508.6  267.81  5568.3  268.69  5581.6  268.65    5862  272.34  5921.7  277.76
  6018.9  290.99    6025  293.39  6053.1  298.36    6081  309.09  6083.3  310.41
#Mann= 7 ,-1 , 0
  4170.7     .12       0  4234.6     .16       0  4574.3     .12       0
  4989.2     .07       0    5012      .1       0  5581.6     .16       0
    6081     .12       0
Bank Sta=4769,5568.3
XS Rating Curve= 0 ,0
Exp/Cntr=0.3,0.1

Chan Stop Cuts=-1
Use User Specified Reach Order=0
Composite Channel Slope=5