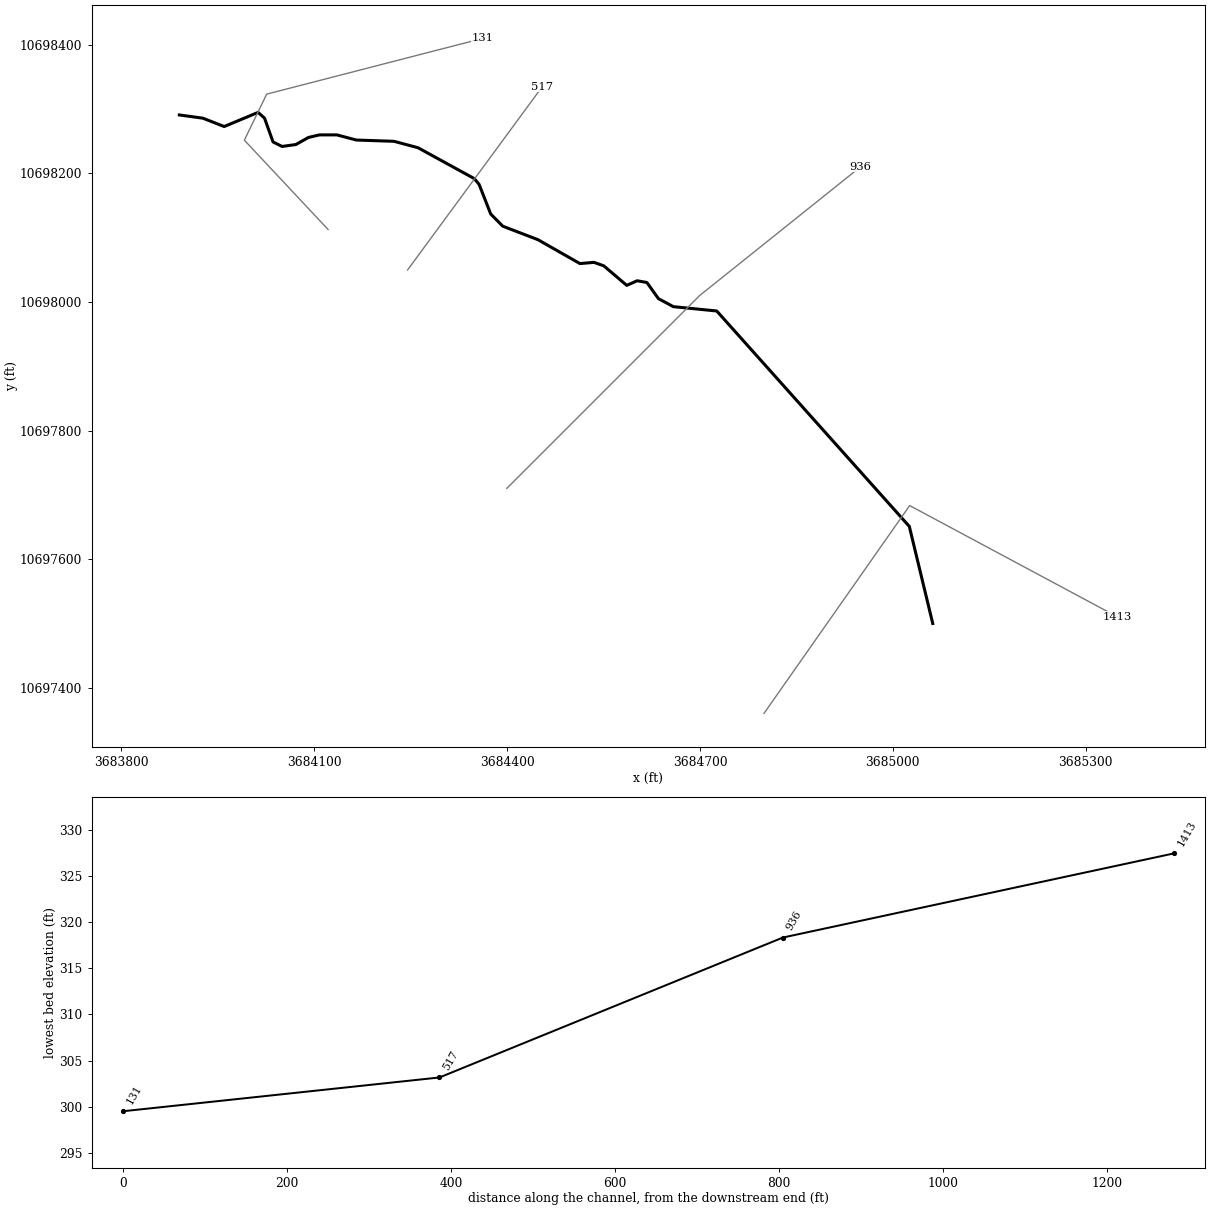
--- UNT 118 IN CACR.prj (project) ---

Proj Title=UNT 118 IN CACR Base Level Engineering
Current Plan=p01
Default Exp/Contr=0.3,0.1
English Units
Geom File=g01
Flow File=f01
Plan File=p01
BEGIN DESCRIPTION:
UNT 118 IN CACR
END DESCRIPTION:

--- UNT 118 IN CACR.p01 (plan) ---

Plan Title=Multiple Run
Short Identifier=Multiple
Geom File=g01
Flow File=f01
Subcritical Flow
K Sum by GR= 0
Std Step Tol= 0.01
Critical Tol= 0.01
Num of Std Step Trials= 20
Max Error Tol= 0.3
Flow Tol Ratio= 0.001
Split Flow NTrial= 30
Split Flow Tol= 0.02
Split Flow Ratio= 0.02
Log Output Level= 0
Friction Slope Method= 1
Unsteady Friction Slope Method= 2
Unsteady Bridges Friction Slope Method= 1
Parabolic Critical Depth
Global Vel Dist=  1 , 1 , 1
Global Log Level= 0
CheckData=True
Encroach Param= -1, 0, 0, 0
BEGIN DESCRIPTION:
Multiple Run
END DESCRIPTION:

--- UNT 118 IN CACR.f01 (steady flow) ---

Flow Title=Multiple
Number of Profiles=7
Profile Names=10-year,25-year,50-year,1pct_min,100-year,1pct_plu,500-year
River Rch & RM= UNT 118 IN CACR,Reach-1,1413
     134     167     191     163     221     298     292
Boundary for River Rch & Prof#=UNT 118 IN CACR,Reach-1,1
Up Type=0
Dn Type=3
Dn Slope=0.005
Boundary for River Rch & Prof#=UNT 118 IN CACR,Reach-1,2
Up Type=0
Dn Type=3
Dn Slope=0.005
Boundary for River Rch & Prof#=UNT 118 IN CACR,Reach-1,3
Up Type=0
Dn Type=3
Dn Slope=0.005
Boundary for River Rch & Prof#=UNT 118 IN CACR,Reach-1,4
Up Type=0
Dn Type=3
Dn Slope=0.005
Boundary for River Rch & Prof#=UNT 118 IN CACR,Reach-1,5
Up Type=0
Dn Type=3
Dn Slope=0.005
Boundary for River Rch & Prof#=UNT 118 IN CACR,Reach-1,6
Up Type=0
Dn Type=3
Dn Slope=0.005
Boundary for River Rch & Prof#=UNT 118 IN CACR,Reach-1,7
Up Type=0
Dn Type=3
Dn Slope=0.005

--- UNT 118 IN CACR.g01 (geometry) ---

Geom Title=Existing Conditions

River Reach=UNT 118 IN CACR,Reach-1
Reach XY= 30
      3685062.09     10697499.99      3685025.63     10697651.04
      3684726.12     10697986.08      3684658.62     10697992.83
      3684635.36     10698005.36      3684617.47     10698030.41
      3684602.26     10698033.09      3684586.16     10698025.93
      3684550.38     10698056.35      3684535.17     10698061.72
      3684513.27     10698059.84      3684448.00     10698097.00
      3684393.25     10698118.00      3684374.50     10698137.00
      3684356.50     10698183.00      3684349.00     10698192.00
      3684261.50     10698240.00      3684224.25     10698250.00
      3684165.50     10698252.00      3684135.25     10698260.00
      3684108.25     10698260.00      3684091.00     10698256.00
      3684071.50     10698245.00      3684050.00     10698242.00
      3684036.00     10698249.00      3684022.75     10698286.00
      3684012.75     10698295.00      3683960.00     10698273.00
      3683926.75     10698286.00      3683890.25     10698291.00

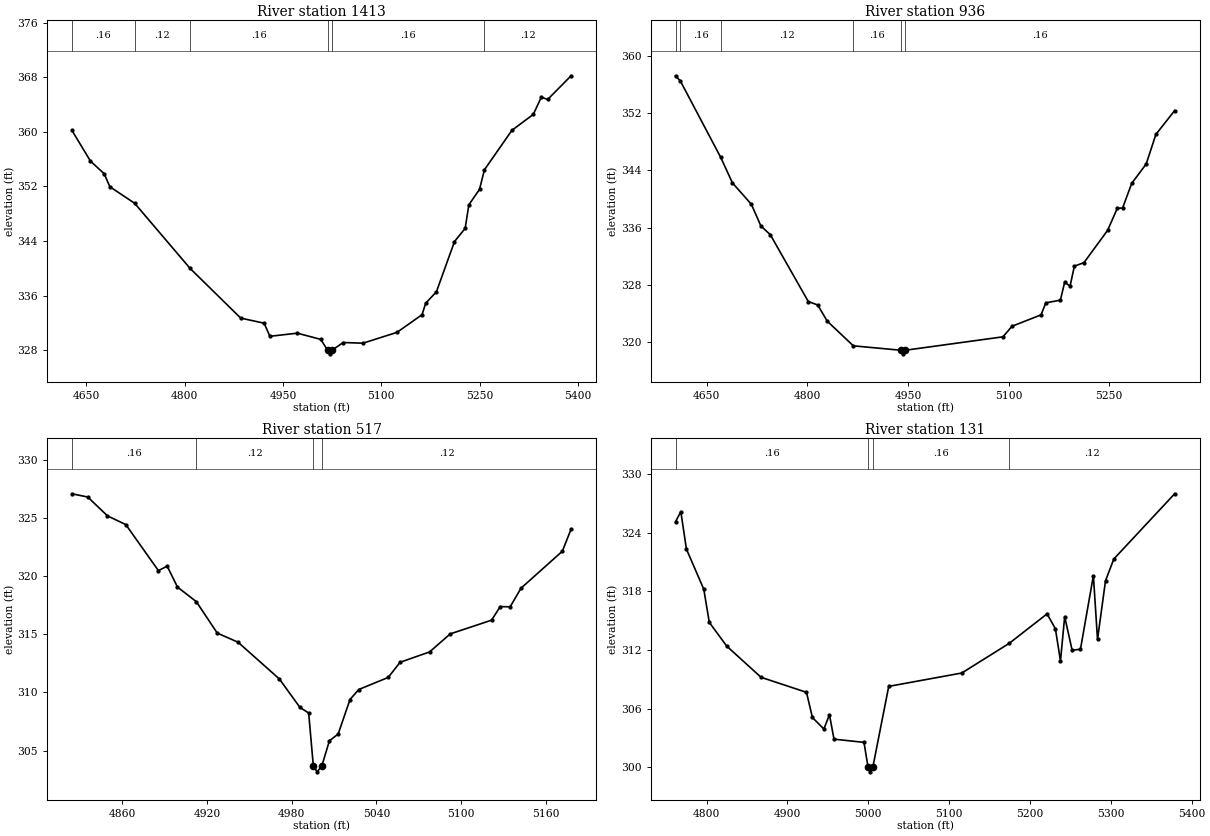
Type RM Length L Ch R = 1,1413,477,477,477
BEGIN DESCRIPTION:
UNT 118 IN CACR 3.0
END DESCRIPTION:
XS GIS Cut Line= 3
      3684799.63     10697360.22      3685026.22     10697683.45
      3685349.60     10697510.19
#Sta/Elev= 30
  4627.9  360.21  4656.2  355.71  4677.1  353.86  4685.8  351.95  4723.6  349.53
  4808.1  339.99  4885.4  332.70  4921.2  331.95  4929.9  330.03  4971.7  330.49
  5007.5  329.58  5018.2  327.96  5021.0  327.46  5024.2  327.96  5041.8  329.12
  5071.9  329.02  5123.9  330.61  5162.1  333.20  5167.7  334.89  5184.0  336.55
  5211.6  343.92  5227.9  345.86  5233.5  349.30  5249.8  351.58  5257.3  354.45
  5299.3  360.23  5331.8  362.56  5344.1  365.08  5353.8  364.75  5389.5  368.22
#Mann=6,-1,0
  4627.9    0.16       0  4723.6    0.12       0  4808.1    0.16       0
  5018.2    0.07       0  5024.2    0.16       0  5257.3    0.12       0
Bank Sta=5018.2,5024.2
Exp/Cntr=0.3,0.1

Type RM Length L Ch R = 1,936,419,419,419
BEGIN DESCRIPTION:
UNT 118 IN CACR 2.0
END DESCRIPTION:
XS GIS Cut Line= 3
      3684399.60     10697710.18      3684699.61     10698010.19
      3684949.58     10698210.17
#Sta/Elev= 30
  4603.3  357.23  4610.5  356.51  4670.6  345.84  4688.2  342.25  4716.5  339.25
  4730.6  336.23  4744.7  335.00  4801.3  325.66  4815.4  325.17  4829.6  322.91
  4868.5  319.46  4939.7  318.84  4942.5  318.34  4945.7  318.84  5091.6  320.72
  5105.2  322.20  5148.4  323.79  5155.6  325.47  5177.3  325.85  5183.7  328.37
  5191.7  327.79  5198.1  330.60  5212.5  331.10  5247.7  335.61  5262.1  338.68
  5270.1  338.75  5283.7  342.19  5305.3  344.90  5319.7  349.03  5347.7  352.36
#Mann=6,-1,0
  4603.3    0.05       0  4610.5    0.16       0  4670.6    0.12       0
  4868.5    0.16       0  4939.7    0.07       0  4945.7    0.16       0
Bank Sta=4939.7,4945.7
Exp/Cntr=0.3,0.1

Type RM Length L Ch R = 1,517,386,386,386
BEGIN DESCRIPTION:
Mapping XS bfdaf642
END DESCRIPTION:
XS GIS Cut Line= 2
      3684245.25     10698049.92      3684454.75     10698335.02
#Sta/Elev= 30
  4824.2  327.08  4835.4  326.80  4849.4  325.18  4862.4  324.43  4885.5  320.47
  4891.7  320.86  4899.0  319.06  4912.4  317.80  4927.2  315.10  4941.9  314.32
  4971.2  311.16  4985.8  308.71  4992.0  308.23  4995.3  303.67  4998.0  303.17
  5001.3  303.67  5006.7  305.84  5012.9  306.42  5021.3  309.39  5027.5  310.25
  5048.4  311.29  5056.8  312.59  5077.7  313.48  5092.3  315.03  5121.6  316.21
  5127.8  317.38  5134.8  317.36  5142.5  318.96  5171.8  322.14  5178.0  324.04
#Mann=4,-1,0
  4824.2    0.16       0  4912.4    0.12       0  4995.3    0.07       0
  5001.3    0.12       0
Bank Sta=4995.3,5001.3
Exp/Cntr=0.3,0.1

Type RM Length L Ch R = 1,131,0,0,0
BEGIN DESCRIPTION:
UNT 118 IN CACR 1.0
END DESCRIPTION:
XS GIS Cut Line= 4
      3684121.55     10698112.90      3683991.36     10698251.77
      3684026.08     10698323.38      3684362.42     10698410.18
#Sta/Elev= 30
  4761.6  325.14  4768.2  326.18  4775.1  322.34  4796.6  318.22  4803.4  314.83
  4824.9  312.40  4867.4  309.20  4923.6  307.66  4930.9  305.08  4945.1  303.90
  4952.0  305.37  4957.6  302.86  4994.7  302.53  4999.7  300.01  5002.5  299.51
  5005.7  300.01  5025.3  308.27  5115.7  309.64  5174.3  312.68  5221.1  315.70
  5231.4  314.18  5237.7  310.88  5242.9  315.42  5252.1  311.98  5262.4  312.07
  5278.4  319.62  5283.5  313.08  5293.4  319.10  5303.7  321.33  5378.9  328.01
#Mann=4,-1,0
  4761.6    0.16       0  4999.7    0.07       0  5005.7    0.16       0
  5174.3    0.12       0
Bank Sta=4999.7,5005.7
Exp/Cntr=0.3,0.1

Chan Stop Cuts=-1