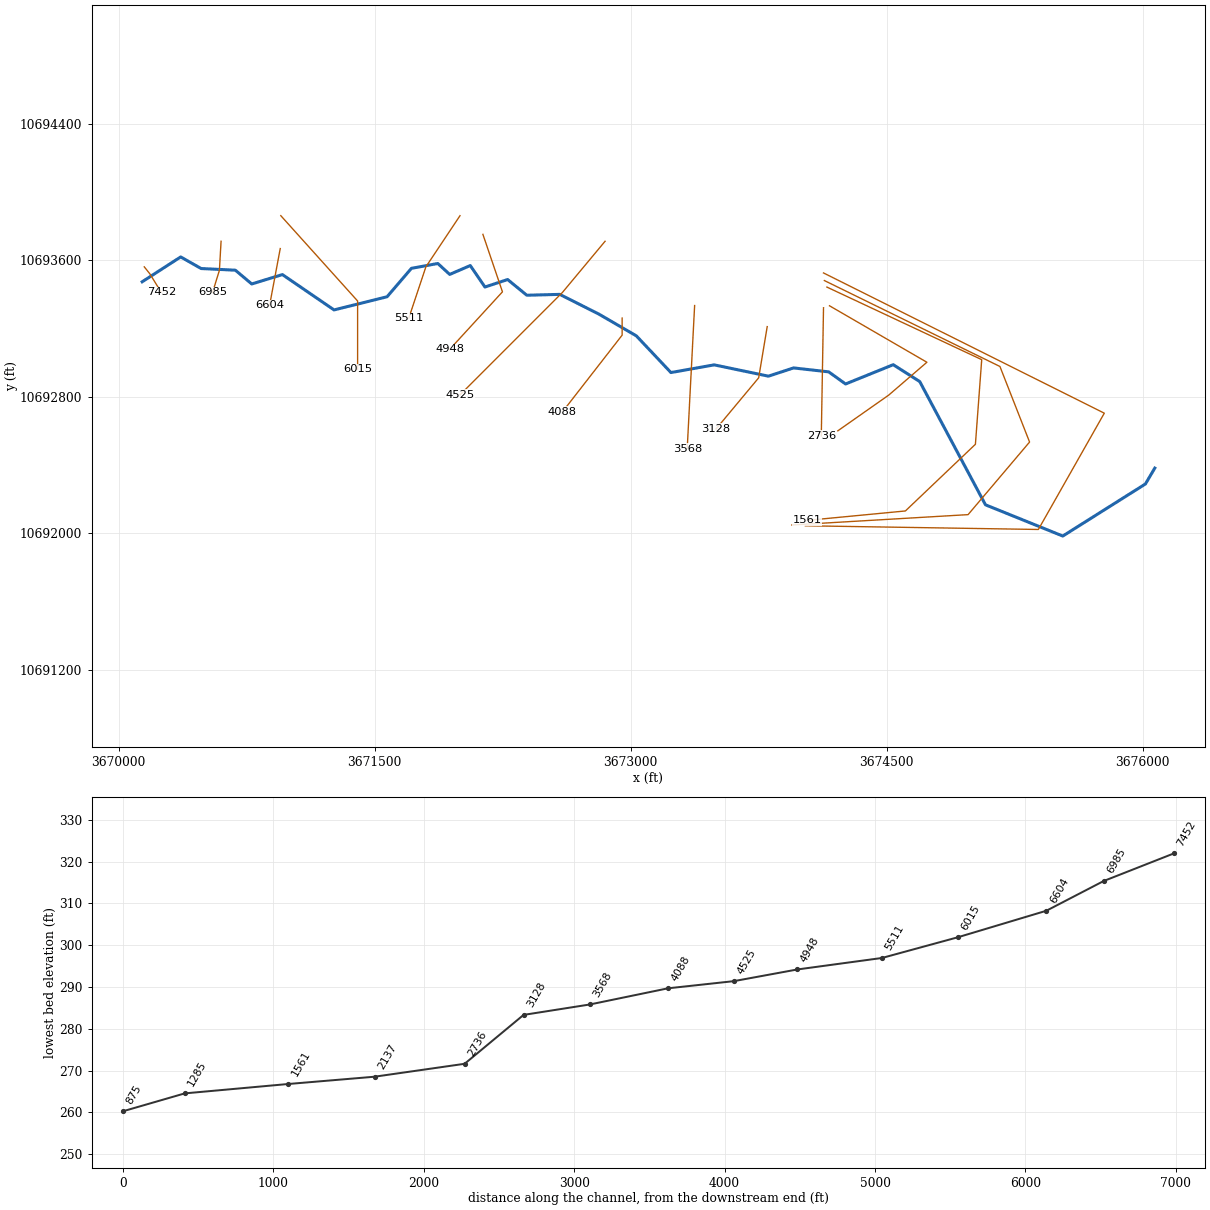
--- UNT 122 IN CACR.prj (project) ---

Proj Title=UNT 122 IN CACR Base Level Engineering
Current Plan=p01
Default Exp/Contr=0.3,0.1
English Units
Geom File=g01
Flow File=f01
Plan File=p01
Y Axis Title=Elevation
X Axis Title(PF)=Main Channel Distance
X Axis Title(XS)=Station
BEGIN DESCRIPTION:
UNT 122 IN CACR
END DESCRIPTION:
DSS Export Rating Curves= 0
DSS Export Rating Curve Sorted= 0
DSS Export Volume Flow Curves= 0
DXF OffsetX= 0
DXF OffsetY= 0
DXF ScaleX= 1
DXF ScaleY= 10

--- UNT 122 IN CACR.p01 (plan) ---

Plan Title=Multiple Run
Short Identifier=Multiple
Geom File=g01
Flow File=f01
Subcritical Flow
K Sum by GR= 0
Std Step Tol= 0.01
Critical Tol= 0.01
Num of Std Step Trials= 20
Max Error Tol= 0.3
Flow Tol Ratio= 0.001
Split Flow NTrial= 30
Split Flow Tol= 0.02
Split Flow Ratio= 0.02
Log Output Level= 0
Friction Slope Method= 1
Unsteady Friction Slope Method= 2
Unsteady Bridges Friction Slope Method= 1
Parabolic Critical Depth
Global Vel Dist=  1 , 1 , 1
Global Log Level= 0
CheckData=True
Encroach Param= -1, 0, 0, 0
BEGIN DESCRIPTION:
Multiple Run
END DESCRIPTION:

--- UNT 122 IN CACR.f01 (steady flow) ---

Flow Title=Multiple
Program Version=4.10
Number of Profiles= 7
Profile Names=10-year,25-year,50-year,1pct_min,100-year,1pct_plu,500-year
River Rch & RM=UNT 122 IN CACR,Reach-1         ,7452
     103     125     141     118     160     216     204
River Rch & RM=UNT 122 IN CACR,Reach-1         ,4948
     291     380     451     394     533     721     746
Boundary for River Rch & Prof#=UNT 122 IN CACR,Reach-1         , 1
Up Type= 0
Dn Type= 3
Dn Slope=0.00947
Boundary for River Rch & Prof#=UNT 122 IN CACR,Reach-1         , 2
Up Type= 0
Dn Type= 3
Dn Slope=0.00947
Boundary for River Rch & Prof#=UNT 122 IN CACR,Reach-1         , 3
Up Type= 0
Dn Type= 3
Dn Slope=0.00947
Boundary for River Rch & Prof#=UNT 122 IN CACR,Reach-1         , 4
Up Type= 0
Dn Type= 3
Dn Slope=0.00947
Boundary for River Rch & Prof#=UNT 122 IN CACR,Reach-1         , 5
Up Type= 0
Dn Type= 3
Dn Slope=0.00947
Boundary for River Rch & Prof#=UNT 122 IN CACR,Reach-1         , 6
Up Type= 0
Dn Type= 3
Dn Slope=0.00947
Boundary for River Rch & Prof#=UNT 122 IN CACR,Reach-1         , 7
Up Type= 0
Dn Type= 3
Dn Slope=0.00947
DSS Import GetInterval= 0
DSS Import GetPeak= 0
DSS Import FillOption= 0

--- UNT 122 IN CACR.g01 (geometry) ---

Geom Title=Existing Conditions
Program Version=4.10

River Reach=UNT 122 IN CACR ,Reach-1
Reach XY= 30
       3670137.3     10693472.81        3670363.     10693618.38
      3670482.73     10693550.46      3670683.37     10693540.68
      3670779.25       10693460.        3670959.       10693515.
      3671261.61     10693307.96      3671572.25       10693385.
      3671714.74     10693551.54       3671869.5       10693580.
      3671939.25       10693516.      3672059.75       10693568.
      3672145.75       10693442.       3672278.5       10693486.
        3672391.       10693394.        3672584.       10693399.
      3672812.25       10693284.      3673032.75       10693156.
       3673235.5       10692941.        3673489.       10692986.
      3673806.71     10692919.76        3673954.       10692968.
      3674159.75       10692945.      3674258.75       10692874.
        3674538.       10692987.      3674693.43     10692887.99
       3675078.5       10692166.       3675531.5       10691983.
       3676015.5       10692288.       3676070.5       10692381.

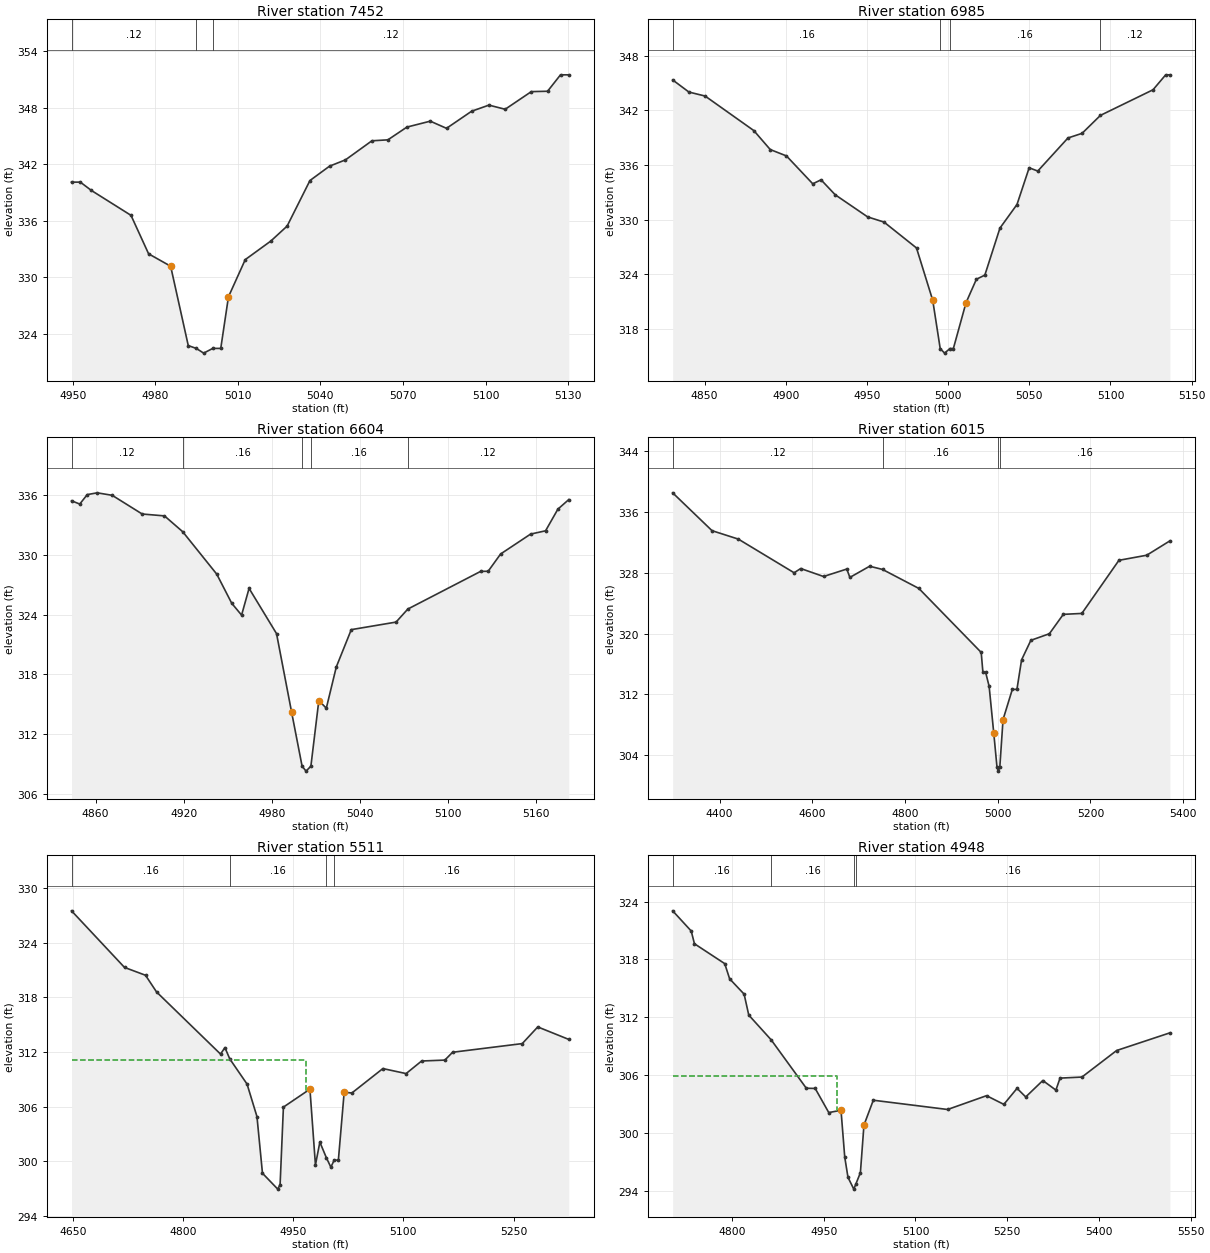
Type RM Length L Ch R = 1 ,7452    ,467,467,467
BEGIN DESCRIPTION:
UNT 122 IN CACR 12.0
END DESCRIPTION:
XS GIS Cut Line= 3
      3670149.59     10693560.21      3670181.94     10693519.88
      3670249.62     10693410.17
#Sta/Elev= 30
  4949.6   340.1  4952.8   340.1  4956.8  339.22  4971.2  336.58  4977.6   332.5
  4985.6  331.19    4992  322.78  4994.9  322.48  4997.6  321.98  5000.9  322.48
  5003.8  322.48  5006.6  327.95  5012.7  331.89    5022  333.86  5027.9  335.44
  5036.2  340.27  5043.3  341.79  5049.1  342.46  5058.7  344.48  5064.5  344.58
  5071.4  345.93  5079.9  346.56  5085.8   345.8  5094.9  347.61  5101.2  348.26
  5107.1  347.82  5116.6  349.69  5122.5  349.73  5127.2  351.47  5130.2  351.47
#Mann= 3 ,-1 , 0
  4949.6     .12       0  4994.9     .07       0  5000.9     .12       0
Bank Sta=4985.6,5006.6
XS Rating Curve= 0 ,0
Exp/Cntr=0.3,0.1

Type RM Length L Ch R = 1 ,6985    ,381,381,381
BEGIN DESCRIPTION:
UNT 122 IN CACR 11.0
END DESCRIPTION:
XS GIS Cut Line= 3
      3670599.61     10693710.14      3670589.89     10693540.06
      3670549.62     10693410.22
#Sta/Elev= 30
  4830.3  345.35  4840.3  344.02  4850.3  343.58  4880.3  339.79  4890.4  337.71
  4900.4  337.01  4916.6  333.95  4921.7  334.39  4930.4  332.75  4950.4  330.32
  4960.5  329.75  4980.5  326.91  4990.5  321.16  4995.1  315.87  4997.8  315.37
  5001.1  315.87  5003.2  315.87    5011   320.9  5017.4  323.48  5022.6  323.93
  5031.9  329.09  5042.4  331.68  5049.9  335.71  5055.2  335.35  5073.8  338.98
  5082.5  339.49  5093.8  341.46  5126.2  344.27    5134  345.91  5136.6  345.91
#Mann= 4 ,-1 , 0
  4830.3     .16       0  4995.1     .07       0  5001.1     .16       0
  5093.8     .12       0
Bank Sta=4990.5,5011
XS Rating Curve= 0 ,0
Exp/Cntr=0.3,0.1

Type RM Length L Ch R = 1 ,6604    ,589,589,589
BEGIN DESCRIPTION:
UNT 122 IN CACR 10.0
END DESCRIPTION:
XS GIS Cut Line= 2
      3670946.26     10693667.43      3670883.86     10693334.63
#Sta/Elev= 30
  4843.6  335.45  4849.2  335.12  4854.3  336.07  4861.1  336.25  4871.3     336
  4891.7  334.12  4906.9  333.93  4919.3  332.34  4942.5  328.07  4952.7  325.14
  4959.4  323.95  4964.5  326.64  4983.2  322.09  4993.4  314.24  5000.6  308.76
  5003.3  308.26  5006.6  308.76    5012  315.36  5017.1  314.59  5023.9  318.74
  5034.1  322.49  5064.6  323.25  5072.6  324.56  5122.2  328.35  5127.3  328.36
  5135.8   330.1  5156.2   332.1  5166.4  332.43  5174.8  334.61  5182.2  335.57
#Mann= 5 ,-1 , 0
  4843.6     .12       0  4919.3     .16       0  5000.6     .07       0
  5006.6     .16       0  5072.6     .12       0
Bank Sta=4993.4,5012
XS Rating Curve= 0 ,0
Exp/Cntr=0.3,0.1

Type RM Length L Ch R = 1 ,6015    ,504,504,504
BEGIN DESCRIPTION:
UNT 122 IN CACR 9.0
END DESCRIPTION:
XS GIS Cut Line= 3
      3670949.59     10693860.21      3671399.61     10693360.19
      3671399.61     10692960.19
#Sta/Elev= 30
  4298.8  338.53  4383.7  333.55  4440.5  332.44  4560.8  328.01    4575  328.57
  4624.3  327.52  4674.4   328.5  4681.1   327.4  4723.7  328.87  4751.5  328.45
  4829.9  325.95  4964.4  317.53  4968.1   314.9    4974   314.9  4981.5  313.07
  4991.5  306.91  4998.5  302.41  5001.3  301.91  5004.5  302.41  5011.5  308.69
  5031.5  312.66  5041.5  312.67  5051.5  316.55  5071.5  319.12  5111.5  319.99
  5141.5  322.54  5181.5  322.66  5261.5  329.65  5321.5  330.32  5371.5  332.21
#Mann= 4 ,-1 , 0
  4298.8     .12       0  4751.5     .16       0  5001.3     .07       0
  5004.5     .16       0
Bank Sta=4991.5,5011.5
XS Rating Curve= 0 ,0
Exp/Cntr=0.3,0.1

Type RM Length L Ch R = 1 ,5511    ,563,563,563
BEGIN DESCRIPTION:
UNT 122 IN CACR 8.0
END DESCRIPTION:
XS GIS Cut Line= 3
      3671999.61     10693860.19      3671799.61     10693560.19
       3671699.6     10693260.17
#Sta/Elev= 30
  4648.4   327.5  4720.5  321.29  4749.1  320.43  4764.1   318.6  4851.2  311.78
  4857.2  312.49  4863.8  311.25  4887.3  308.49  4900.8  304.92  4908.3   298.7
  4929.1  296.96  4932.3  297.46  4936.8  305.96  4972.9  307.93  4980.4  299.61
  4986.4  302.12  4995.4  300.38  5001.4  299.37  5005.9  300.14  5011.6  300.14
  5019.5  307.59    5030  307.51  5072.2  310.19  5103.8  309.64  5124.9  311.02
  5156.5  311.12  5167.1  311.98  5261.9  312.93    5283  314.76  5325.2  313.39
#Mann= 4 ,-1 , 0
  4648.4     .16       0  4863.8     .16       0  4995.4     .07       0
  5005.9     .16       0
#XS Ineff= 2 , 0
         4967.73   311.1
Permanent Ineff=
       F       F
Bank Sta=4972.9,5019.5
XS Rating Curve= 0 ,0
Exp/Cntr=0.3,0.1

Type RM Length L Ch R = 1 ,4948    ,423,423,423
BEGIN DESCRIPTION:
UNT 122 IN CACR 7.0
END DESCRIPTION:
XS GIS Cut Line= 3
      3672133.76     10693750.74      3672248.34     10693413.93
      3671939.28      10693077.1
#Sta/Elev= 30
  4703.1  323.04  4733.4  320.95  4738.7  319.63  4788.2  317.57  4796.2     316
  4819.9  314.41  4827.5  312.24  4864.2  309.67  4921.6  304.66  4936.1  304.64
  4958.3  302.14  4978.3  302.38  4984.4  297.53  4989.7  295.43  4999.2  294.21
  5002.4  294.71    5010  295.91  5015.8  300.84  5031.1  303.42  5152.6  302.46
  5216.2  303.89  5244.5  302.99  5266.1  304.65  5280.3  303.76  5308.2  305.46
  5329.6  304.47  5336.4  305.71  5372.2  305.82  5428.9  308.57    5516   310.4
#Mann= 4 ,-1 , 0
  4703.1     .16       0  4864.2     .16       0  4999.2     .07       0
  5002.4     .16       0
#XS Ineff= 2 , 0
         4972.16  305.97
Permanent Ineff=
       F       F
Bank Sta=4978.3,5015.8
XS Rating Curve= 0 ,0
Exp/Cntr=0.3,0.1

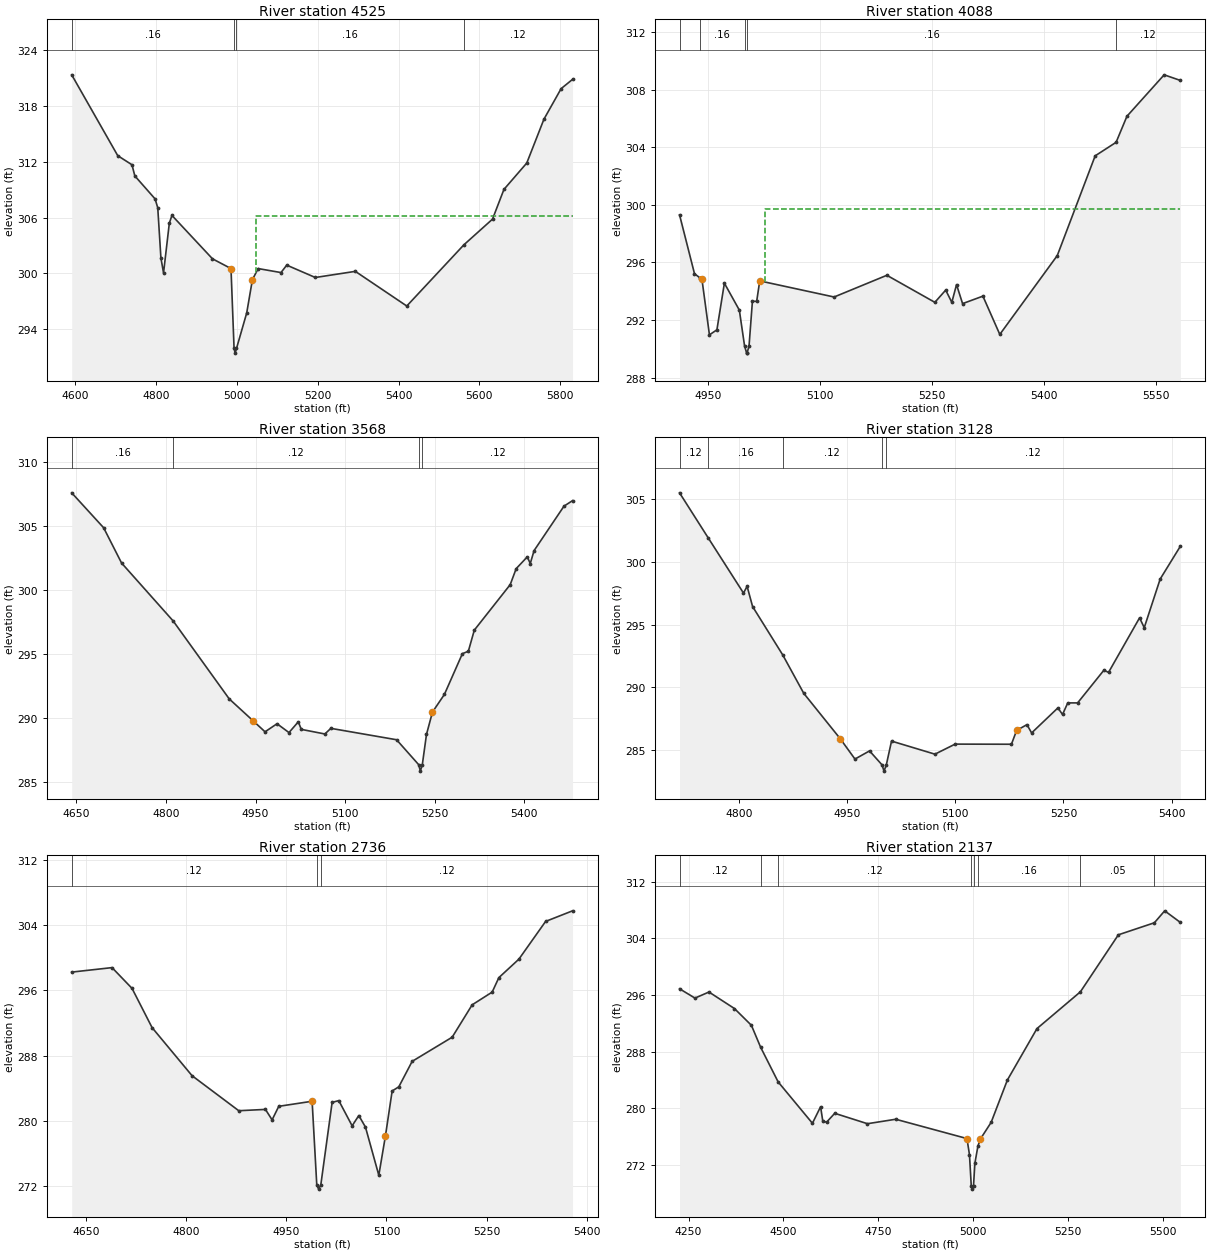
Type RM Length L Ch R = 1 ,4525    ,437,437,437
BEGIN DESCRIPTION:
UNT 122 IN CACR 6.0
END DESCRIPTION:
XS GIS Cut Line= 3
      3672849.64     10693710.22      3672599.61     10693410.19
       3671999.6     10692810.18
#Sta/Elev= 30
  4591.3  321.36  4705.2  312.66  4740.4  311.68  4747.5  310.48  4797.7     308
  4804.2  307.04    4812  301.65  4818.5  300.04  4832.8  305.39  4839.3  306.23
  4939.6  301.56  4985.4  300.51    4993  291.91  4995.7  291.41    4999  291.91
  5024.3  295.74  5038.4  299.32  5052.6  300.51  5109.1  300.08  5123.3  300.88
    5194  299.55    5293  300.21  5420.3  296.48  5561.7  303.07  5632.4  305.83
  5660.7  309.03  5717.2  311.87  5759.7  316.59  5802.1  319.87  5830.4  320.87
#Mann= 4 ,-1 , 0
  4591.3     .16       0    4993     .07       0    4999     .16       0
  5561.7     .12       0
#XS Ineff= 2 , 0
                         5047.27          306.15
Permanent Ineff=
       F       F
Bank Sta=4985.4,5038.4
XS Rating Curve= 0 ,0
Exp/Cntr=0.3,0.1

Type RM Length L Ch R = 1 ,4088    ,520,520,520
BEGIN DESCRIPTION:
UNT 122 IN CACR 5.0
END DESCRIPTION:
XS GIS Cut Line= 3
      3672949.61     10693260.21      3672949.61     10693160.19
      3672599.62      10692710.2
#Sta/Elev= 30
  4912.3  299.31  4932.3  295.22  4939.8  294.92  4942.3  294.82  4952.3  290.97
  4962.3  291.32  4972.3  294.56  4992.3  292.69  4999.3   290.2  5002.1   289.7
  5002.6   289.7  5005.3   290.2  5009.8   293.3  5015.5   293.3  5019.6  294.72
  5119.1   293.6  5189.7  295.11  5253.9  293.23  5268.4  294.08  5276.6  293.23
  5282.9  294.46    5291  293.14  5318.2  293.66  5340.8     291  5417.7  296.48
  5468.4  303.41  5496.4  304.35  5510.9  306.16  5560.7  309.04  5582.4  308.65
#Mann= 5 ,-1 , 0
  4912.3     .12       0  4939.8     .16       0  4999.3     .07       0
  5002.6     .16       0  5496.4     .12       0
#XS Ineff= 2 , 0
                         5026.08           299.7
Permanent Ineff=
       F       F
Bank Sta=4942.3,5019.6
XS Rating Curve= 0 ,0
Exp/Cntr=0.3,0.1

Type RM Length L Ch R = 1 ,3568    ,440,440,440
BEGIN DESCRIPTION:
UNT 122 IN CACR 4.0
END DESCRIPTION:
XS GIS Cut Line= 2
      3673374.28      10693333.6      3673330.88     10692495.92
#Sta/Elev= 30
    4642  307.56  4695.5  304.83  4725.5  302.08    4812  297.55  4905.8  291.47
  4945.8  289.76  4965.8   288.9  4985.9  289.53  5005.9  288.84  5021.5  289.68
  5026.5  289.09    5066  288.73    5076  289.17  5186.1  288.28  5223.2  286.33
  5225.9  285.83  5229.2  286.33  5236.2   288.7  5246.2  290.44  5266.2  291.82
  5296.3     295  5306.3  295.19  5316.3  296.84  5376.4  300.39  5386.4  301.64
    5405  302.56    5410  302.04  5416.4  303.05  5466.5  306.52  5480.8  306.95
#Mann= 4 ,-1 , 0
    4642     .16       0    4812     .12       0  5223.2     .07       0
  5229.2     .12       0
Bank Sta=4945.8,5246.2
XS Rating Curve= 0 ,0
Exp/Cntr=0.3,0.1

Type RM Length L Ch R = 1 ,3128    ,392,392,392
BEGIN DESCRIPTION:
UNT 122 IN CACR 3.0
END DESCRIPTION:
XS GIS Cut Line= 3
       3673799.6     10693210.15      3673749.61     10692910.19
      3673499.62      10692610.2
#Sta/Elev= 30
  4717.5  305.49  4757.3   301.9  4806.2  297.51  4811.2  298.05  4818.8  296.44
  4860.6  292.59  4889.8  289.53  4940.5  285.91  4960.8   284.3    4981  284.95
  4998.3  283.84  5001.1  283.34  5004.3  283.84  5011.5  285.73  5071.7  284.69
  5099.7  285.49  5177.8  285.48    5185  286.58  5199.3  287.04  5205.8  286.38
  5242.2  288.37  5248.7  287.85  5255.9  288.77  5269.6  288.77    5306  291.37
  5312.5   291.2  5355.5  295.54    5362  294.76  5384.1  298.63  5412.1  301.24
#Mann= 5 ,-1 , 0
  4717.5     .12       0  4757.3     .16       0  4860.6     .12       0
  4998.3     .07       0  5004.3     .12       0
Bank Sta=4940.5,5185
XS Rating Curve= 0 ,0
Exp/Cntr=0.3,0.1

Type RM Length L Ch R = 1 ,2736    ,599,599,599
BEGIN DESCRIPTION:
UNT 122 IN CACR 2.0
END DESCRIPTION:
XS GIS Cut Line= 2
      3674129.49     10693320.64      3674116.47     10692569.75
#Sta/Elev= 30
    4628  298.24  4688.5  298.79  4718.5  296.24  4748.5  291.44  4808.5  285.54
  4878.5  281.25  4918.5  281.41  4928.5  280.13  4938.5  281.79  4988.5  282.41
  4995.5  272.14  4998.3  271.64  5001.5  272.14  5018.5  282.27  5028.5  282.49
  5048.5   279.4  5058.5  280.66  5068.5  279.24  5088.5  273.34  5098.5  278.19
  5108.5  283.67  5118.5  284.18  5138.5   287.3  5198.5  290.26  5228.5  294.23
  5258.5  295.79  5268.5  297.56  5298.6  299.83  5338.6  304.45    5379  305.75
#Mann= 3 ,-1 , 0
    4628     .12       0  4995.5     .07       0  5001.5     .12       0
Bank Sta=4988.5,5098.5
XS Rating Curve= 0 ,0
Exp/Cntr=0.3,0.1

Type RM Length L Ch R = 1 ,2137    ,576,576,576
BEGIN DESCRIPTION:
Mapping XS c4653bd3
END DESCRIPTION:
XS GIS Cut Line= 4
      3674164.47     10693332.28      3674735.23     10693001.29
      3674511.44     10692808.75       3674213.4     10692599.61
#Sta/Elev= 30
  4226.3  296.88  4266.9  295.56  4303.8  296.42    4371  294.08  4415.6  291.71
  4439.8  288.62    4486  283.71  4576.3  277.86  4597.8   280.2  4603.6  278.16
  4613.6  278.02  4635.1  279.27  4721.2   277.8  4795.7  278.43  4983.3   275.7
  4989.9  273.43  4994.6  269.05  4997.4  268.55  5000.6  269.05  5004.2  272.22
  5012.2  274.64  5018.5  275.62    5047  277.99  5089.8  283.98  5167.7  291.25
  5282.1  296.45  5382.1  304.51  5476.9  306.21  5504.1   307.9  5545.4  306.26
#Mann= 8 ,-1 , 0
  4226.3     .12       0  4439.8     .16       0    4486     .12       0
  4994.6     .07       0  5000.6     .12       0  5012.2     .16       0
  5282.1     .05       0  5476.9     .16       0
Bank Sta=4983.3,5018.5
XS Rating Curve= 0 ,0
Exp/Cntr=0.3,0.1

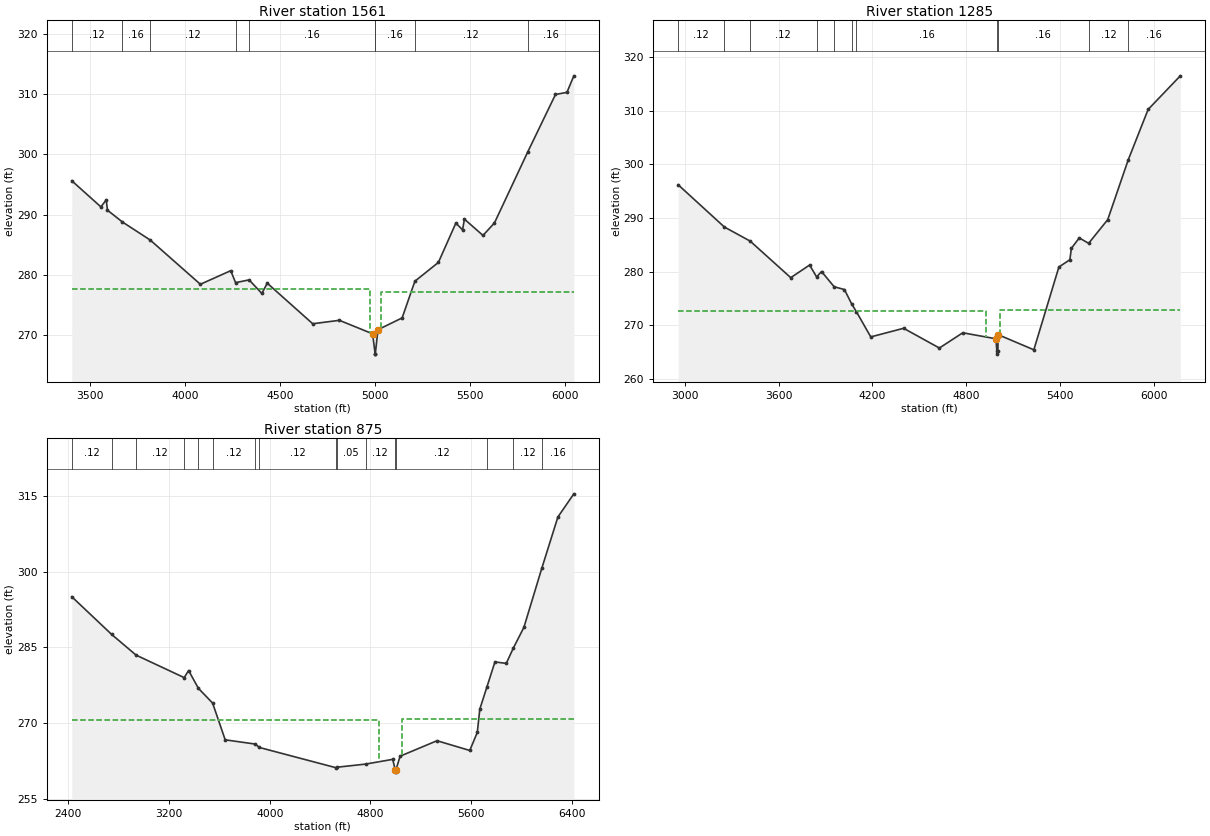
Type RM Length L Ch R = 1 ,1561    ,686,686,686
BEGIN DESCRIPTION:
Mapping XS 3f847599
END DESCRIPTION:
XS GIS Cut Line= 5
      3674149.32     10693441.81      3675056.41     10693016.48
       3675019.5     10692520.65      3674609.34     10692130.03
      3674033.34     10692074.76
#Sta/Elev= 30
  3403.5  295.62  3556.7  291.28    3585  292.43  3591.6  290.72  3670.5  288.76
  3816.8  285.76  4080.8  278.41  4240.6  280.67  4266.2  278.68  4337.4  279.14
  4404.4  276.89  4433.1  278.59  4672.4  271.85  4812.8  272.42  4987.6  270.18
  5001.5   266.8    5002   266.8  5015.9  270.86  5143.3  272.82  5210.5  278.92
  5334.2  282.04  5426.4  288.59  5461.6  287.45  5471.3  289.24  5569.1  286.53
  5629.4   288.6  5804.2  300.37  5950.9  309.96  6011.2  310.31  6047.6  313.06
#Mann= 9 ,-1 , 0
  3403.5     .12       0  3670.5     .16       0  3816.8     .12       0
  4266.2     .05       0  4337.4     .16       0  5001.5     .07       0
    5002     .16       0  5210.5     .12       0  5804.2     .16       0
#XS Ineff= 2 , 0
         4972.73  277.57  5030.4          277.11
Permanent Ineff=
       F       F
Bank Sta=4987.6,5015.9
XS Rating Curve= 0 ,0
Exp/Cntr=0.3,0.1

Type RM Length L Ch R = 1 ,1285    ,410,410,410
BEGIN DESCRIPTION:
Mapping XS 391a3862
END DESCRIPTION:
XS GIS Cut Line= 5
      3674134.56       10693480.      3675163.21     10692976.52
      3675336.82     10692533.81      3674976.58     10692108.46
      3673944.06     10692047.73
#Sta/Elev= 30
  2957.9   296.2  3253.3  288.31  3417.8  285.69  3677.8  278.85  3798.5  281.21
  3843.3  278.99  3874.8     280  3955.6  277.15  4021.2  276.63  4067.9  273.93
  4098.4  272.46  4189.8  267.78    4400  269.39  4628.9   265.7  4778.4  268.55
  4990.3  267.43    4997  265.06  4999.8  264.56    5003  265.06  5004.6   268.2
  5233.2  265.37  5393.5  280.84  5463.6   282.2  5473.6  284.33  5523.7  286.28
  5583.8  285.27  5705.9  289.69  5837.1  300.86  5964.5  310.29  6170.4  316.57
#Mann= 11 ,-1 , 0
  2957.9     .12       0  3253.3     .16       0  3417.8     .12       0
  3843.3     .05       0  3955.6     .16       0  4067.9     .12       0
  4098.4     .16       0    4997     .07       0    5003     .16       0
  5583.8     .12       0  5837.1     .16       0
#XS Ineff= 2 , 0
         4925.37  272.65 5013.62          272.85
Permanent Ineff=
       F       F
Bank Sta=4990.3,5004.6
XS Rating Curve= 0 ,0
Exp/Cntr=0.3,0.1

Type RM Length L Ch R = 1 ,875     ,0,0,0
BEGIN DESCRIPTION:
UNT 122 IN CACR 1.0
END DESCRIPTION:
XS GIS Cut Line= 4
      3674129.45     10693524.63      3675774.71     10692702.94
      3675388.42     10692021.52      3674022.92     10692043.19
#Sta/Elev= 30
  2427.9  295.04  2745.1  287.56  2938.7  283.47    3321  279.01  3355.8  280.42
  3433.8  276.89  3546.6  273.97  3646.5  266.69    3885  265.85  3918.7  265.17
  4527.1  261.16  4530.8  261.25  4761.2  261.88  4976.9  262.82    4997  260.79
  4999.8  260.29    5003  260.79  5036.1  263.45  5329.1  266.51  5589.1  264.58
  5649.1  268.16  5669.1  272.78  5725.4  277.16  5789.1  282.12  5879.1  281.83
  5935.4  284.87  6019.2  288.97  6160.9  300.64  6289.2  310.83  6415.9  315.42
#Mann= 16 ,-1 , 0
  2427.9     .12       0  2745.1     .16       0  2938.7     .12       0
    3321     .05       0  3433.8     .16       0  3546.6     .12       0
    3885     .16       0  3918.7     .12       0  4527.1     .16       0
  4530.8     .05       0  4761.2     .12       0    4997     .07       0
    5003     .12       0  5725.4     .05       0  5935.4     .12       0
  6160.9     .16       0
#XS Ineff= 2 , 0
         4866.48  270.59 5053.98          270.72
Permanent Ineff=
       F       F
Bank Sta=4997,5003
XS Rating Curve= 0 ,0
Exp/Cntr=0.3,0.1

Chan Stop Cuts=-1
Use User Specified Reach Order=0
Composite Channel Slope=5