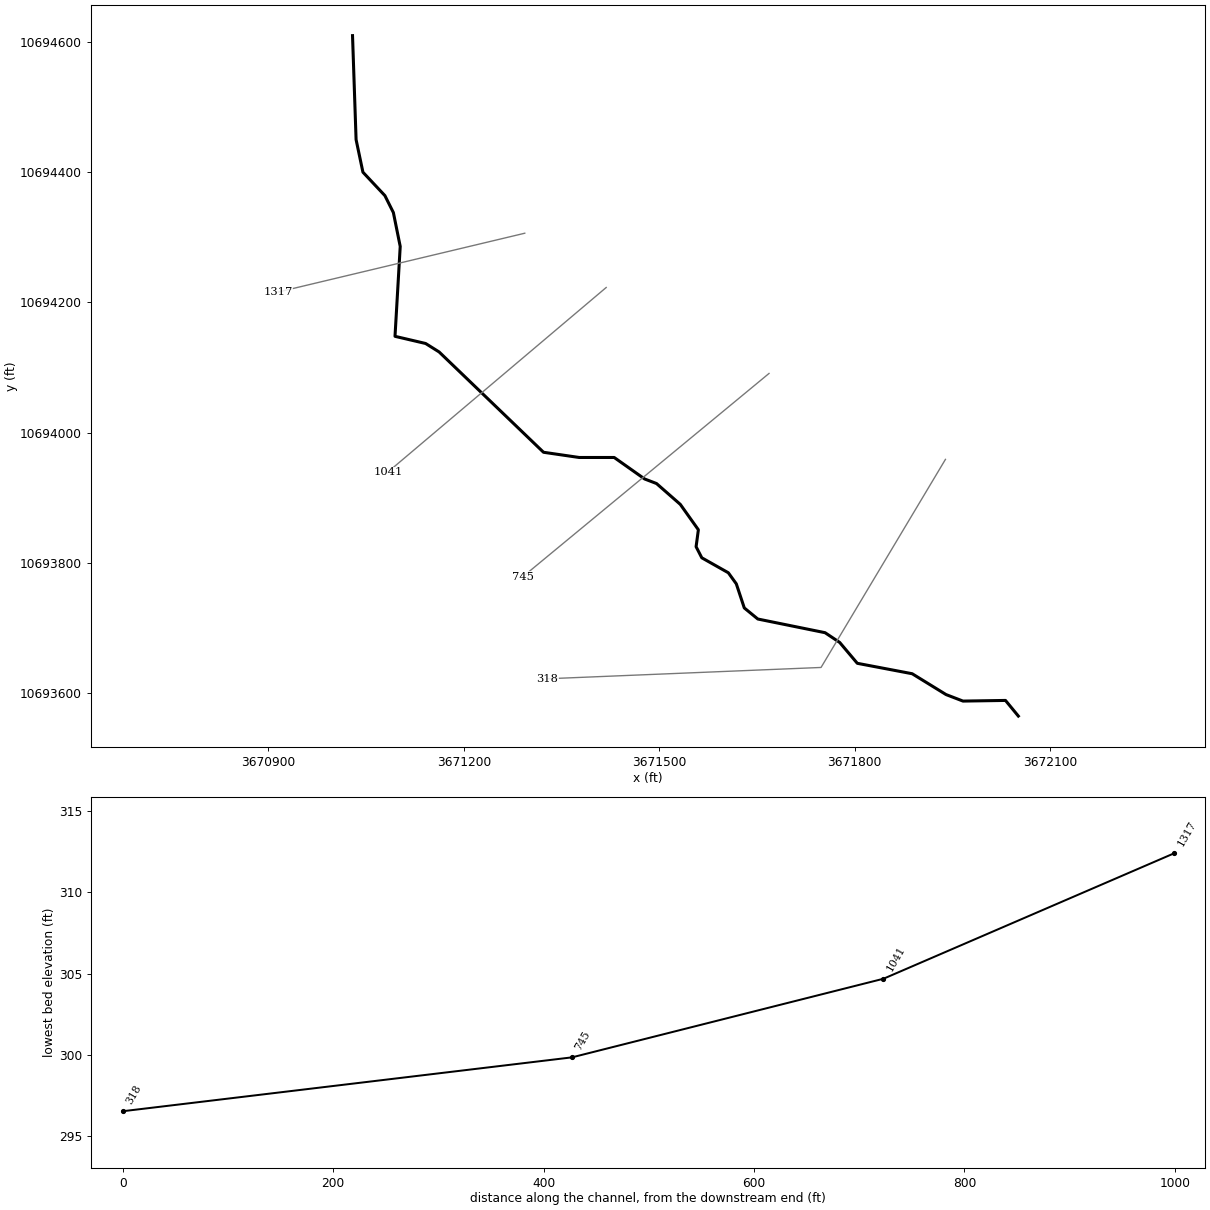
--- UNT 123 IN CACR.prj (project) ---

Proj Title=UNT 123 IN CACR Base Level Engineering
Current Plan=p01
Default Exp/Contr=0.3,0.1
English Units
Geom File=g01
Flow File=f01
Plan File=p01
BEGIN DESCRIPTION:
UNT 123 IN CACR
END DESCRIPTION:

--- UNT 123 IN CACR.p01 (plan) ---

Plan Title=Multiple Run
Short Identifier=Multiple
Geom File=g01
Flow File=f01
Subcritical Flow
K Sum by GR= 0
Std Step Tol= 0.01
Critical Tol= 0.01
Num of Std Step Trials= 20
Max Error Tol= 0.3
Flow Tol Ratio= 0.001
Split Flow NTrial= 30
Split Flow Tol= 0.02
Split Flow Ratio= 0.02
Log Output Level= 0
Friction Slope Method= 1
Unsteady Friction Slope Method= 2
Unsteady Bridges Friction Slope Method= 1
Parabolic Critical Depth
Global Vel Dist=  1 , 1 , 1
Global Log Level= 0
CheckData=True
Encroach Param= -1, 0, 0, 0
BEGIN DESCRIPTION:
Multiple Run
END DESCRIPTION:

--- UNT 123 IN CACR.f01 (steady flow) ---

Flow Title=Multiple
Number of Profiles=7
Profile Names=10-year,25-year,50-year,1pct_min,100-year,1pct_plu,500-year
River Rch & RM= UNT 123 IN CACR,Reach-1,1317
     106     129     147     124     168     227     218
Boundary for River Rch & Prof#=UNT 123 IN CACR,Reach-1,1
Up Type=0
Dn Type=3
Dn Slope=0.005
Boundary for River Rch & Prof#=UNT 123 IN CACR,Reach-1,2
Up Type=0
Dn Type=3
Dn Slope=0.005
Boundary for River Rch & Prof#=UNT 123 IN CACR,Reach-1,3
Up Type=0
Dn Type=3
Dn Slope=0.005
Boundary for River Rch & Prof#=UNT 123 IN CACR,Reach-1,4
Up Type=0
Dn Type=3
Dn Slope=0.005
Boundary for River Rch & Prof#=UNT 123 IN CACR,Reach-1,5
Up Type=0
Dn Type=3
Dn Slope=0.005
Boundary for River Rch & Prof#=UNT 123 IN CACR,Reach-1,6
Up Type=0
Dn Type=3
Dn Slope=0.005
Boundary for River Rch & Prof#=UNT 123 IN CACR,Reach-1,7
Up Type=0
Dn Type=3
Dn Slope=0.005

--- UNT 123 IN CACR.g01 (geometry) ---

Geom Title=Existing Conditions

River Reach=UNT 123 IN CACR,Reach-1
Reach XY= 30
      3671029.03     10694609.63      3671034.50     10694450.00
      3671045.00     10694400.00      3671078.75     10694364.00
      3671091.75     10694338.00      3671102.25     10694286.00
      3671094.25     10694148.00      3671141.25     10694137.00
      3671162.00     10694124.00      3671322.25     10693970.00
      3671377.00     10693962.00      3671430.75     10693962.00
      3671477.50     10693929.00      3671495.75     10693922.00
      3671532.25     10693890.00      3671560.00     10693851.00
      3671556.50     10693825.00      3671565.25     10693808.00
      3671606.00     10693785.00      3671618.25     10693768.00
      3671630.50     10693731.00      3671651.25     10693714.00
      3671754.50     10693693.00      3671777.00     10693678.00
      3671804.00     10693646.00      3671888.25     10693630.00
      3671940.25     10693598.00      3671966.25     10693588.00
      3672031.50     10693589.00      3672051.25     10693565.00

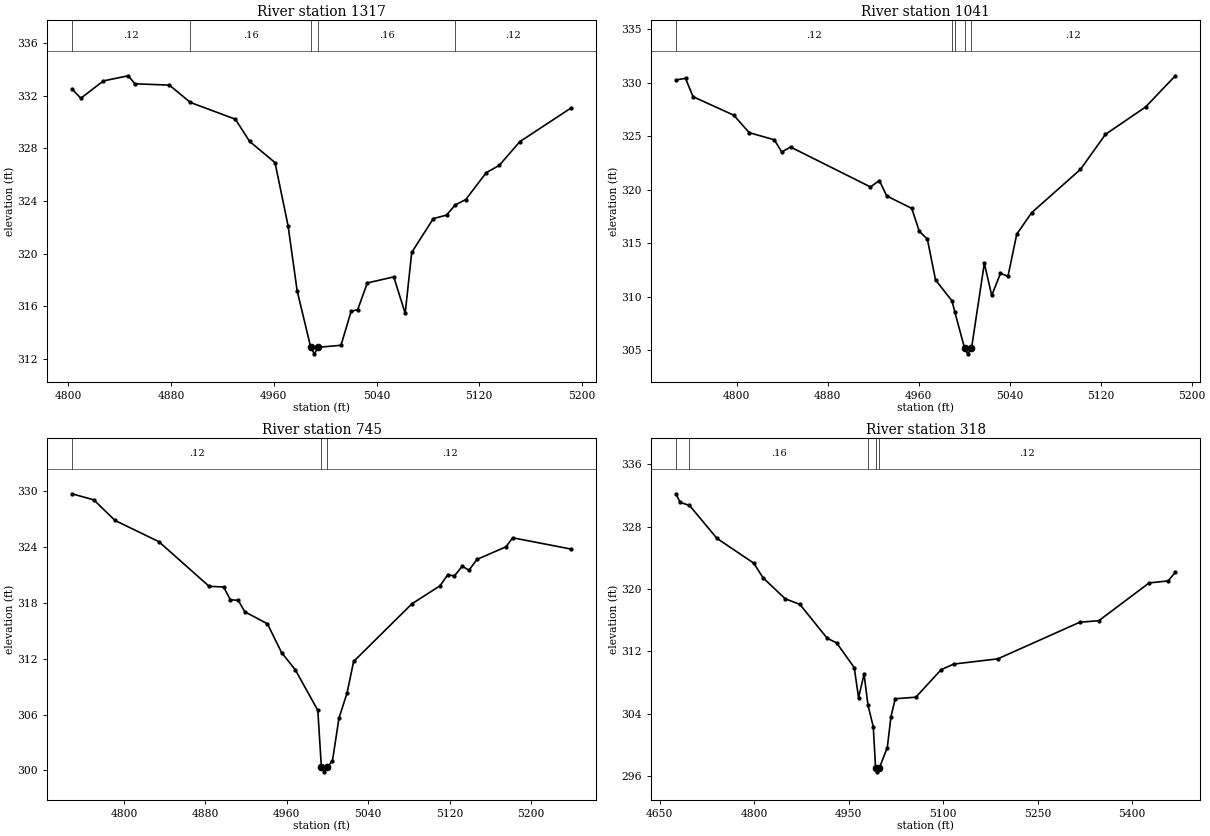
Type RM Length L Ch R = 1,1317,276,276,276
BEGIN DESCRIPTION:
UNT 123 IN CACR 2.0
END DESCRIPTION:
XS GIS Cut Line= 2
      3671293.46     10694306.29      3670914.98     10694216.01
#Sta/Elev= 30
  4802.7  332.52  4809.6  331.81  4827.2  333.13  4846.6  333.52  4851.7  332.91
  4878.6  332.81  4895.0  331.49  4930.0  330.22  4941.1  328.53  4960.9  326.92
  4971.1  322.10  4978.1  317.19  4988.7  312.88  4991.5  312.38  4994.7  312.88
  5012.3  313.03  5020.2  315.61  5025.3  315.74  5032.8  317.77  5053.4  318.23
  5062.3  315.46  5067.4  320.09  5084.2  322.66  5094.5  322.93  5101.4  323.71
  5109.5  324.11  5125.4  326.15  5135.6  326.71  5151.6  328.51  5191.8  331.09
#Mann=5,-1,0
  4802.7    0.12       0  4895.0    0.16       0  4988.7    0.07       0
  4994.7    0.16       0  5101.4    0.12       0
Bank Sta=4988.7,4994.7
Exp/Cntr=0.3,0.1

Type RM Length L Ch R = 1,1041,296,296,296
BEGIN DESCRIPTION:
Mapping XS cbeafdc7
END DESCRIPTION:
XS GIS Cut Line= 2
      3671418.47     10694222.96      3671083.14     10693939.48
#Sta/Elev= 30
  4746.5  330.25  4755.0  330.40  4761.6  328.69  4797.4  326.96  4811.0  325.33
  4833.1  324.66  4839.6  323.52  4847.3  323.99  4917.6  320.26  4925.4  320.86
  4931.9  319.42  4953.9  318.26  4960.5  316.12  4967.6  315.40  4974.8  311.58
  4989.3  309.62  4991.8  308.57  5000.4  305.18  5003.1  304.68  5006.4  305.18
  5017.7  313.13  5024.2  310.13  5031.9  312.19  5038.5  311.93  5046.2  315.85
  5059.3  317.86  5102.2  321.90  5124.2  325.17  5159.4  327.72  5185.6  330.64
#Mann=5,-1,0
  4746.5    0.12       0  4989.3    0.16       0  4991.8    0.12       0
  5000.4    0.07       0  5006.4    0.12       0
Bank Sta=5000.4,5006.4
Exp/Cntr=0.3,0.1

Type RM Length L Ch R = 1,745,427,427,427
BEGIN DESCRIPTION:
Mapping XS db84e085
END DESCRIPTION:
XS GIS Cut Line= 2
      3671668.49     10694091.03      3671290.03     10693778.54
#Sta/Elev= 30
  4748.9  329.68  4770.3  329.03  4791.2  326.82  4834.2  324.55  4883.7  319.75
  4898.0  319.68  4904.5  318.31  4912.3  318.25  4918.8  317.02  4941.0  315.73
  4954.9  312.64  4968.3  310.81  4990.5  306.45  4994.0  300.35  4996.7  299.85
  5000.0  300.35  5004.9  301.05  5011.3  305.61  5019.2  308.30  5025.7  311.69
  5083.0  317.88  5110.6  319.81  5118.2  320.99  5124.7  320.87  5132.5  321.91
  5139.0  321.48  5146.9  322.64  5175.4  323.99  5182.0  324.96  5239.7  323.74
#Mann=3,-1,0
  4748.9    0.12       0  4994.0    0.07       0  5000.0    0.12       0
Bank Sta=4994,5000
Exp/Cntr=0.3,0.1

Type RM Length L Ch R = 1,318,0,0,0
BEGIN DESCRIPTION:
UNT 123 IN CACR 1.0
END DESCRIPTION:
XS GIS Cut Line= 3
      3671939.32     10693959.08      3671748.34     10693639.63
      3671328.18     10693622.27
#Sta/Elev= 30
  4675.7  332.22  4682.6  331.11  4697.3  330.73  4740.9  326.50  4799.3  323.32
  4814.2  321.43  4849.2  318.75  4872.5  318.03  4916.0  313.67  4930.7  313.10
  4958.8  309.92  4965.7  306.05  4974.4  309.09  4980.6  305.11  4989.0  302.33
  4992.7  297.04  4995.5  296.54  4998.7  297.04  5011.3  299.66  5017.1  303.62
  5023.9  305.92  5056.6  306.12  5096.7  309.65  5116.7  310.37  5186.7  311.04
  5316.8  315.74  5346.9  315.93  5426.9  320.78  5457.0  321.04  5468.4  322.15
#Mann=5,-1,0
  4675.7    0.12       0  4697.3    0.16       0  4980.6    0.12       0
  4992.7    0.07       0  4998.7    0.12       0
Bank Sta=4992.7,4998.7
Exp/Cntr=0.3,0.1

Chan Stop Cuts=-1