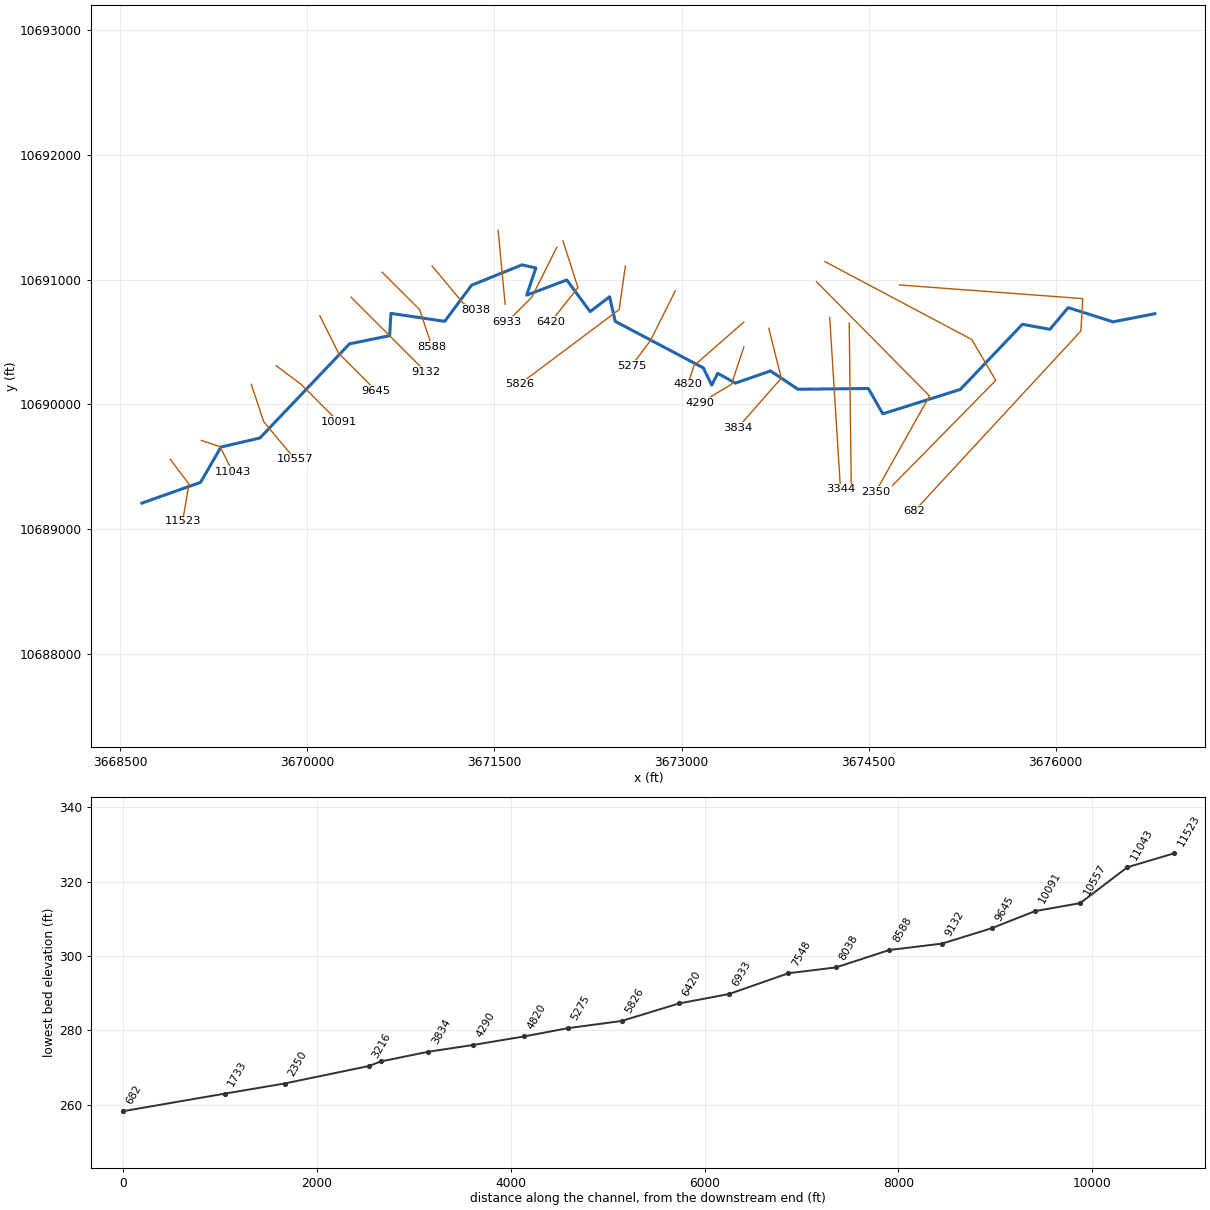
--- UNT 124 IN CACR.prj (project) ---

Proj Title=UNT 124 IN CACR Base Level Engineering
Current Plan=p01
Default Exp/Contr=0.3,0.1
English Units
Geom File=g01
Flow File=f01
Plan File=p01
Y Axis Title=Elevation
X Axis Title(PF)=Main Channel Distance
X Axis Title(XS)=Station
BEGIN DESCRIPTION:
UNT 124 IN CACR
END DESCRIPTION:
DSS Export Rating Curves= 0
DSS Export Rating Curve Sorted= 0
DSS Export Volume Flow Curves= 0
DXF OffsetX= 0
DXF OffsetY= 0
DXF ScaleX= 1
DXF ScaleY= 10

--- UNT 124 IN CACR.p01 (plan) ---

Plan Title=Multiple Run
Short Identifier=Multiple
Geom File=g01
Flow File=f01
Subcritical Flow
K Sum by GR= 0
Std Step Tol= 0.01
Critical Tol= 0.01
Num of Std Step Trials= 20
Max Error Tol= 0.3
Flow Tol Ratio= 0.001
Split Flow NTrial= 30
Split Flow Tol= 0.02
Split Flow Ratio= 0.02
Log Output Level= 0
Friction Slope Method= 1
Unsteady Friction Slope Method= 2
Unsteady Bridges Friction Slope Method= 1
Parabolic Critical Depth
Global Vel Dist=  1 , 1 , 1
Global Log Level= 0
CheckData=True
Encroach Param= -1, 0, 0, 0
BEGIN DESCRIPTION:
Multiple Run
END DESCRIPTION:

--- UNT 124 IN CACR.f01 (steady flow) ---

Flow Title=Multiple
Number of Profiles=7
Profile Names=10-year,25-year,50-year,1pct_min,100-year,1pct_plu,500-year
River Rch & RM= UNT 124 IN CACR,Reach-1,11523
     481     646     781     694     938    1269    1361
River Rch & RM= UNT 124 IN CACR,Reach-1,6933
     665     907    1107     993    1343    1817    1985
Boundary for River Rch & Prof#=UNT 124 IN CACR,Reach-1,1
Up Type=0
Dn Type=3
Dn Slope=0.005
Boundary for River Rch & Prof#=UNT 124 IN CACR,Reach-1,2
Up Type=0
Dn Type=3
Dn Slope=0.005
Boundary for River Rch & Prof#=UNT 124 IN CACR,Reach-1,3
Up Type=0
Dn Type=3
Dn Slope=0.005
Boundary for River Rch & Prof#=UNT 124 IN CACR,Reach-1,4
Up Type=0
Dn Type=3
Dn Slope=0.005
Boundary for River Rch & Prof#=UNT 124 IN CACR,Reach-1,5
Up Type=0
Dn Type=3
Dn Slope=0.005
Boundary for River Rch & Prof#=UNT 124 IN CACR,Reach-1,6
Up Type=0
Dn Type=3
Dn Slope=0.005
Boundary for River Rch & Prof#=UNT 124 IN CACR,Reach-1,7
Up Type=0
Dn Type=3
Dn Slope=0.005

--- UNT 124 IN CACR.g01 (geometry) ---

Geom Title=Existing Conditions
Program Version=4.10

River Reach=UNT 124 IN CACR ,Reach-1
Reach XY= 30
      3668673.08     10689207.29       3669143.5       10689374.
       3669306.5       10689657.       3669619.5       10689730.
        3670337.       10690485.      3670659.25       10690551.
      3670669.75       10690730.      3671101.25       10690666.
       3671316.5       10690956.        3671720.       10691119.
        3671832.       10691094.        3671758.       10690876.
      3672079.75       10690998.      3672266.75       10690744.
        3672423.       10690863.        3672468.       10690666.
       3673175.5       10690292.      3673241.75       10690154.
        3673290.       10690249.       3673431.5       10690170.
       3673713.5       10690268.      3673933.25       10690121.
      3674497.75       10690127.        3674614.       10689924.
      3675235.52      10690119.6      3675732.75       10690642.
      3675954.25       10690602.        3676100.       10690776.
      3676459.75       10690662.       3676794.5       10690727.

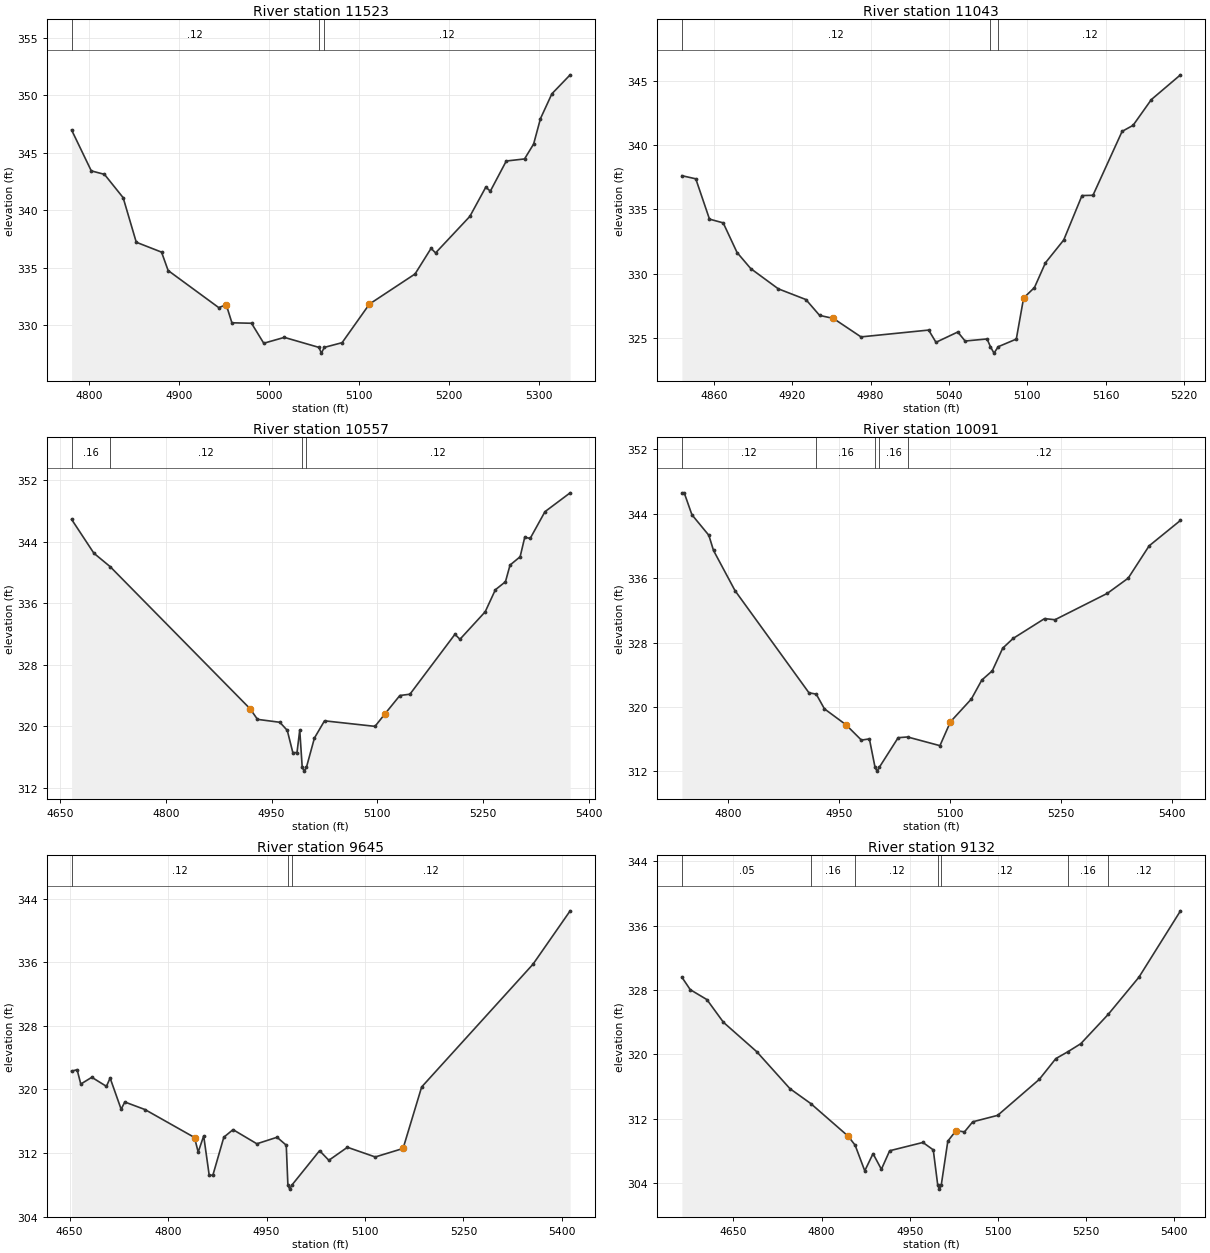
Type RM Length L Ch R = 1 ,11523   ,480,480,480
BEGIN DESCRIPTION:
UNT 124 IN CACR 18.0
END DESCRIPTION:
XS GIS Cut Line= 3
      3668899.58     10689560.22      3669049.61     10689360.19
      3668999.61     10689060.17
#Sta/Elev= 30
  4780.4  346.99  4802.3  343.43  4816.9  343.13  4837.7   341.1  4852.3  337.22
  4880.4  336.36  4887.7  334.76    4944  331.53  4952.3  331.78  4958.6  330.21
  4980.4  330.17    4994  328.43  5016.9  328.94  5055.3  328.07  5058.1  327.57
  5061.3  328.07  5081.1  328.48  5111.5  331.84  5162.2  334.46    5180  336.69
    5185  336.29  5223.1  339.47  5240.8  342.01  5245.9  341.67  5263.6  344.29
  5283.9  344.47    5294  345.77  5301.6  347.98  5314.3  350.14  5334.6  351.79
#Mann= 3 ,-1 , 0
  4780.4     .12       0  5055.3     .07       0  5061.3     .12       0
Bank Sta=4952.3,5111.5
XS Rating Curve= 0 ,0
Exp/Cntr=0.3,0.1

Type RM Length L Ch R = 1 ,11043   ,486,486,486
BEGIN DESCRIPTION:
UNT 124 IN CACR 17.0
END DESCRIPTION:
XS GIS Cut Line= 3
      3669149.59      10689710.2      3669299.61     10689660.19
      3669399.59     10689460.23
#Sta/Elev= 30
  4835.6  337.62  4846.2  337.38  4856.7  334.25  4867.2  333.96  4877.8  331.66
  4888.3  330.41  4909.4  328.84  4930.5  328.01    4941  326.78  4951.6  326.54
  4972.7  325.11  5024.5  325.64  5030.1  324.69  5046.8  325.49  5052.4  324.79
  5069.2  324.95  5071.8  324.35  5074.5  323.85  5077.8  324.35  5091.6  324.94
  5097.2  328.13  5105.5  328.94  5113.9  330.86  5127.9  332.63  5141.9  336.08
  5150.3   336.1  5172.6  341.06    5181  341.53    5195  343.53  5217.3  345.45
#Mann= 3 ,-1 , 0
  4835.6     .12       0  5071.8     .07       0  5077.8     .12       0
Bank Sta=4951.6,5097.2
XS Rating Curve= 0 ,0
Exp/Cntr=0.3,0.1

Type RM Length L Ch R = 1 ,10557   ,466,466,466
BEGIN DESCRIPTION:
UNT 124 IN CACR 16.0
END DESCRIPTION:
XS GIS Cut Line= 3
      3669549.61      10690160.2      3669649.61     10689860.19
      3669899.58     10689560.23
#Sta/Elev= 30
  4666.5  346.92  4698.1  342.52  4721.2  340.77  4919.5   322.3    4930  320.92
  4961.7  320.54  4972.2  319.49  4980.1   316.6    4986   316.6  4989.9  319.52
  4993.4  314.69  4996.2  314.19  4999.4  314.69  5010.7  318.49    5025  320.73
  5096.6  320.01    5111  321.67  5131.8  324.02  5146.1  324.19  5209.9  331.98
    5217  331.33  5252.8  334.91  5267.2  337.77  5281.5  338.81    5288  340.98
  5302.3  342.06  5308.8  344.58  5316.6  344.45  5337.5  347.92  5373.2  350.37
#Mann= 4 ,-1 , 0
  4666.5     .16       0  4721.2     .12       0  4993.4     .07       0
  4999.4     .12       0
Bank Sta=4919.5,5111
XS Rating Curve= 0 ,0
Exp/Cntr=0.3,0.1

Type RM Length L Ch R = 1 ,10091   ,446,446,446
BEGIN DESCRIPTION:
UNT 124 IN CACR 15.0
END DESCRIPTION:
XS GIS Cut Line= 3
      3669749.65     10690310.16      3669949.61     10690160.19
       3670249.6      10689860.2
#Sta/Elev= 30
  4737.6  346.58  4740.7  346.58  4751.1  343.86    4774  341.31  4780.3  339.43
  4809.4  334.44  4909.4  321.76  4919.2   321.6  4930.3  319.77  4959.4   317.8
  4980.3  315.89  4991.1  316.04  4998.7  312.54  5001.4  312.04  5004.7  312.54
    5030  316.19  5042.7  316.28  5086.5   315.2  5100.7  318.16    5129  320.99
  5143.1  323.34  5157.3  324.49  5171.4   327.3  5185.5  328.51    5228  330.97
  5242.1  330.83  5312.8   334.1  5341.1  335.99  5369.4     340  5411.8  343.16
#Mann= 5 ,-1 , 0
  4737.6     .12       0  4919.2     .16       0  4998.7     .07       0
  5004.7     .16       0  5042.7     .12       0
Bank Sta=4959.4,5100.7
XS Rating Curve= 0 ,0
Exp/Cntr=0.3,0.1

Type RM Length L Ch R = 1 ,9645    ,513,513,513
BEGIN DESCRIPTION:
UNT 124 IN CACR 14.0
END DESCRIPTION:
XS GIS Cut Line= 3
       3670099.6     10690710.21      3670249.61     10690410.19
      3670549.61     10690110.19
#Sta/Elev= 30
    4653   322.3  4661.4  322.49    4667  320.68  4683.8  321.53  4706.1  320.39
  4711.7  321.44  4728.5  317.51  4734.1  318.42  4764.8  317.47  4840.3  313.95
  4845.9  312.11  4854.3  314.15  4862.7  309.19  4868.3  309.21    4885  313.99
    4899  314.94  4935.3  313.16  4966.1  313.98  4980.1  312.98  4982.6  307.95
  4985.4  307.45  4988.6  307.95  5030.9  312.29    5045  311.08  5073.3  312.72
  5115.7   311.5  5158.1  312.57  5186.4  320.31  5356.1  335.77  5412.7  342.49
#Mann= 3 ,-1 , 0
    4653     .12       0  4982.6     .07       0  4988.6     .12       0
Bank Sta=4840.3,5158.1
XS Rating Curve= 0 ,0
Exp/Cntr=0.3,0.1

Type RM Length L Ch R = 1 ,9132    ,544,544,544
BEGIN DESCRIPTION:
UNT 124 IN CACR 13.0
END DESCRIPTION:
XS GIS Cut Line= 3
      3670349.58     10690860.22      3670649.61     10690560.19
      3670949.63     10690260.17
#Sta/Elev= 30
  4562.4  329.58  4576.6  328.04  4604.9  326.81  4633.1  323.99  4689.7  320.35
  4746.3  315.76  4781.6  313.92  4845.3  309.87  4857.2  308.75  4873.6  305.57
  4887.7   307.7  4901.9  305.76    4916  308.06  4972.6  309.09  4990.2  308.17
  4997.8   303.8  5000.6   303.3  5003.8   303.8    5015  309.26  5029.1  310.56
  5043.3   310.4  5057.4  311.65  5099.8  312.45  5170.6  316.91  5198.8  319.49
  5218.8  320.32  5241.3  321.34  5287.9  324.97  5340.3  329.59    5411  337.82
#Mann= 7 ,-1 , 0
  4562.4     .05       0  4781.6     .16       0  4857.2     .12       0
  4997.8     .07       0  5003.8     .12       0  5218.8     .16       0
  5287.9     .12       0
Bank Sta=4845.3,5029.1
XS Rating Curve= 0 ,0
Exp/Cntr=0.3,0.1

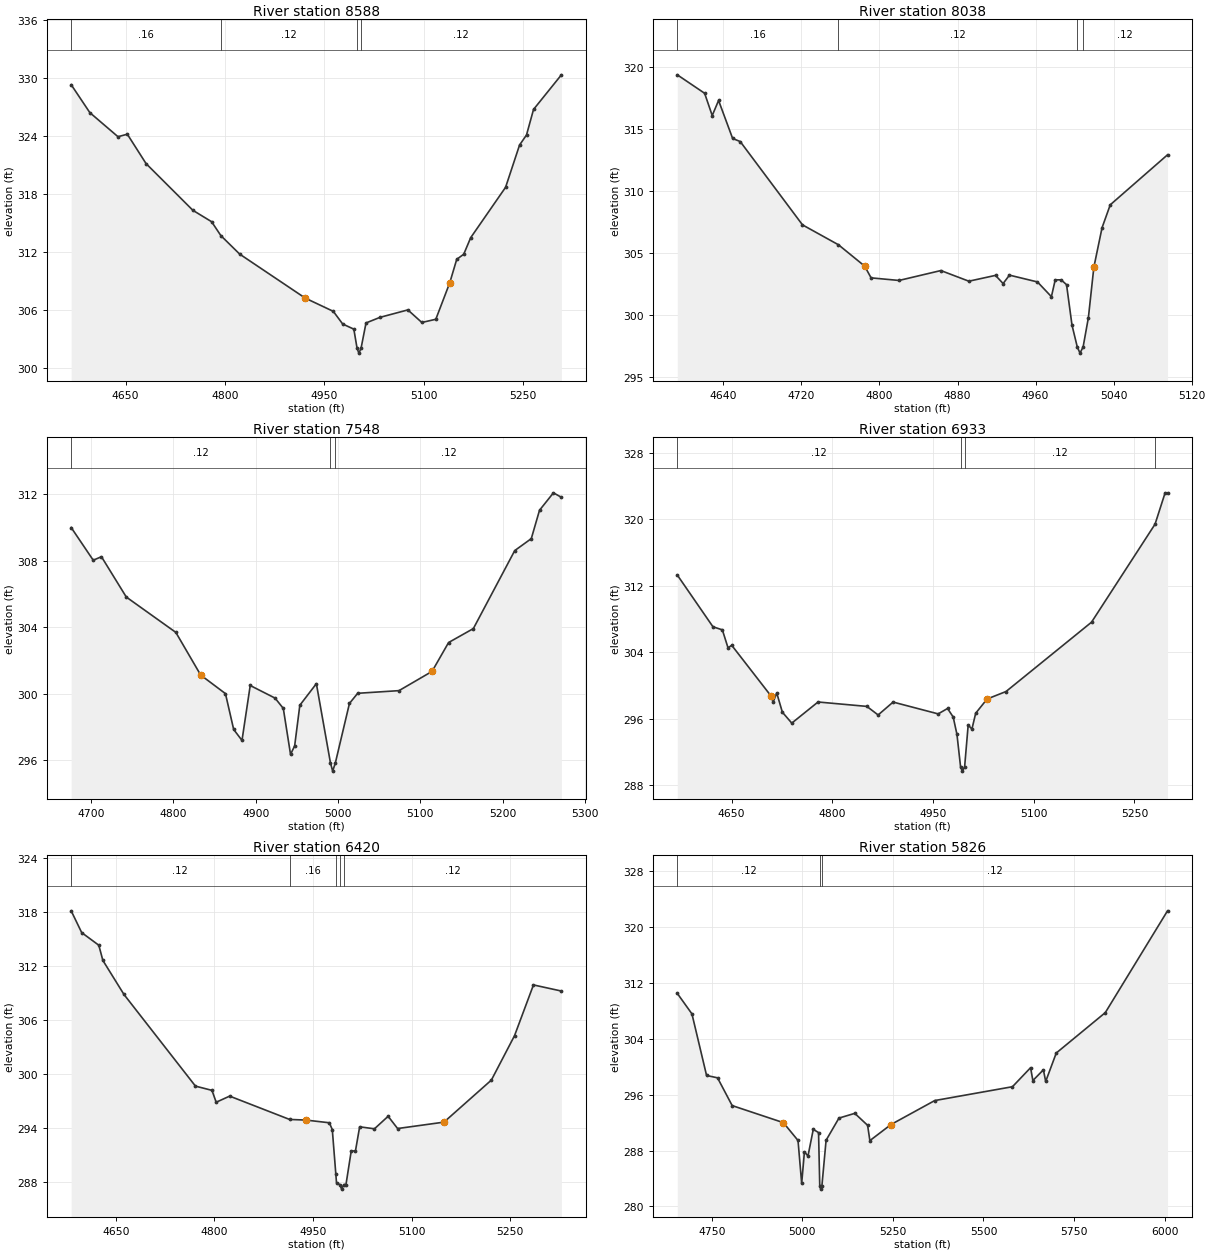
Type RM Length L Ch R = 1 ,8588    ,550,550,550
BEGIN DESCRIPTION:
UNT 124 IN CACR 12.0
END DESCRIPTION:
XS GIS Cut Line= 3
      3670599.64     10691060.16      3670899.61     10690760.19
      3670999.59     10690460.23
#Sta/Elev= 30
  4567.7  329.34  4595.9  326.45  4638.4  323.96  4652.5  324.22  4680.8  321.18
  4751.5  316.35  4779.8  315.17  4793.8  313.73  4822.2  311.82  4921.2  307.27
  4963.6   305.9  4977.8  304.59  4994.6  304.06  4999.5  302.08  5002.2  301.58
  5005.5  302.08    5013   304.7  5034.1  305.28  5076.2  306.05  5097.3  304.75
  5118.4  305.08  5139.5  308.86    5150  311.28  5160.6  311.81  5171.1  313.52
  5223.8  318.73  5244.9   323.1  5255.4  324.14    5266  326.78  5308.1  330.36
#Mann= 4 ,-1 , 0
  4567.7     .16       0  4793.8     .12       0  4999.5     .07       0
  5005.5     .12       0
Bank Sta=4921.2,5139.5
XS Rating Curve= 0 ,0
Exp/Cntr=0.3,0.1

Type RM Length L Ch R = 1 ,8038    ,490,490,490
BEGIN DESCRIPTION:
UNT 124 IN CACR 11.0
END DESCRIPTION:
XS GIS Cut Line= 3
      3670999.58     10691110.22      3671249.61     10690810.19
      3671349.65     10690760.17
#Sta/Elev= 30
  4592.8  319.38  4620.8  317.89  4628.6  316.09  4635.1  317.31  4649.5  314.24
  4657.3  313.99  4721.1  307.26    4758  305.65  4784.8  303.93  4791.4  302.98
    4820  302.77  4862.9  303.57  4891.6  302.71  4918.9  303.18  4926.7  302.52
  4933.2   303.2  4961.9  302.65  4976.2  301.46  4980.1  302.82  4986.2  302.82
  4991.7  302.43  4997.3  299.16  5002.7   297.4  5005.5   296.9  5008.7   297.4
  5014.1  299.77  5019.7  303.84  5028.1  307.03  5036.5  308.88  5095.2  312.92
#Mann= 4 ,-1 , 0
  4592.8     .16       0    4758     .12       0  5002.7     .07       0
  5008.7     .12       0
Bank Sta=4784.8,5019.7
XS Rating Curve= 0 ,0
Exp/Cntr=0.3,0.1

Type RM Length L Ch R = 1 ,7548    ,615,615,615
BEGIN DESCRIPTION:
UNT 124 IN CACR 10.0
END DESCRIPTION:
XS GIS Cut Line= 2
      3671529.07     10691396.84      3671585.35     10690803.71
#Sta/Elev= 30
  4675.7  310.01  4702.5  308.04  4712.5  308.25  4742.7  305.82  4802.9  303.69
  4833.1  301.12  4863.2     300  4873.2  297.84  4883.3  297.18  4893.3  300.49
  4923.5  299.73  4933.5  299.11  4942.3  296.34  4947.3  296.85  4953.6   299.3
  4973.7   300.6  4990.8  295.83  4993.5  295.33  4996.8  295.83  5013.9  299.41
  5023.9  300.02  5074.1  300.18  5114.3  301.34  5134.4  303.08  5164.5  303.92
  5214.8  308.62  5234.9  309.34  5244.9  311.05  5261.8   312.1  5271.5  311.83
#Mann= 3 ,-1 , 0
  4675.7     .12       0  4990.8     .07       0  4996.8     .12       0
Bank Sta=4833.1,5114.3
XS Rating Curve= 0 ,0
Exp/Cntr=0.3,0.1

Type RM Length L Ch R = 1 ,6933    ,513,513,513
BEGIN DESCRIPTION:
UNT 124 IN CACR 9.0
END DESCRIPTION:
XS GIS Cut Line= 3
      3671999.61      10691260.2      3671799.61     10690860.19
      3671599.58     10690660.16
#Sta/Elev= 30
  4569.1  313.29  4622.2  307.07  4636.2   306.7  4644.6  304.55  4650.2  304.84
  4708.9  298.73  4711.7  297.99  4717.2  299.11  4725.6   296.8  4739.6  295.49
  4778.7  298.03  4851.4   297.5  4868.2  296.47  4890.5  298.02  4957.6   296.6
  4971.6  297.25    4980  296.22  4985.6  294.13    4991  290.22  4993.7  289.72
    4997  290.22  5002.3  295.25  5007.9  294.78  5013.5  296.68  5030.5  298.39
  5058.7  299.29    5186  307.62  5280.6   319.4  5295.6  323.17  5299.2  323.17
#Mann= 4 ,-1 , 0
  4569.1     .12       0    4991     .07       0    4997     .12       0
  5280.6     .16       0
Bank Sta=4708.9,5030.5
XS Rating Curve= 0 ,0
Exp/Cntr=0.3,0.1

Type RM Length L Ch R = 1 ,6420    ,594,594,594
BEGIN DESCRIPTION:
UNT 124 IN CACR 8.0
END DESCRIPTION:
XS GIS Cut Line= 3
      3672049.62     10691310.15      3672169.37     10690936.28
      3671949.58     10690660.16
#Sta/Elev= 30
  4582.3  318.12  4598.3   315.7  4624.3   314.3  4630.5  312.61  4662.6  308.83
  4771.3  298.65  4796.4  298.18  4802.8  296.86  4823.3  297.54  4914.4  294.95
  4939.3  294.88  4974.9  294.58  4979.4  293.82  4984.7  288.93  4985.8  287.91
  4990.8  287.71  4993.6  287.21  4996.8  287.71  5000.2  287.72  5008.2  291.45
  5014.6  291.45    5021  294.13  5043.5  293.91  5064.3   295.3  5078.7  293.94
  5149.2  294.65  5221.3  299.32  5256.5  304.25  5285.3  309.89  5327.8  309.21
#Mann= 5 ,-1 , 0
  4582.3     .12       0  4914.4     .16       0  4984.7     .12       0
  4990.8     .07       0  4996.8     .12       0
Bank Sta=4939.3,5149.2
XS Rating Curve= 0 ,0
Exp/Cntr=0.3,0.1

Type RM Length L Ch R = 1 ,5826    ,551,551,551
BEGIN DESCRIPTION:
UNT 124 IN CACR 7.0
END DESCRIPTION:
XS GIS Cut Line= 3
      3672549.61     10691110.18      3672499.61     10690760.19
      3671699.64     10690160.21
#Sta/Elev= 30
  4654.7  310.48  4695.1  307.55  4735.5  298.74  4765.8   298.4  4806.2  294.43
  4947.6  291.99    4988  289.44  4998.1  283.29  5005.7  287.83  5015.5  287.21
  5030.1  291.03  5044.7  290.57    5048  282.98  5050.7  282.48    5054  282.98
  5065.5  289.47    5101  292.64  5144.7  293.32  5180.1  291.61  5186.4  289.42
  5244.7  291.72  5365.5  295.15  5580.1  297.13  5630.1  299.85  5636.4  298.01
  5665.5  299.55  5671.8  297.88    5701  301.95  5836.4  307.73  6008.2  322.29
#Mann= 3 ,-1 , 0
  4654.7     .12       0    5048     .07       0    5054     .12       0
Bank Sta=4947.6,5244.7
XS Rating Curve= 0 ,0
Exp/Cntr=0.3,0.1

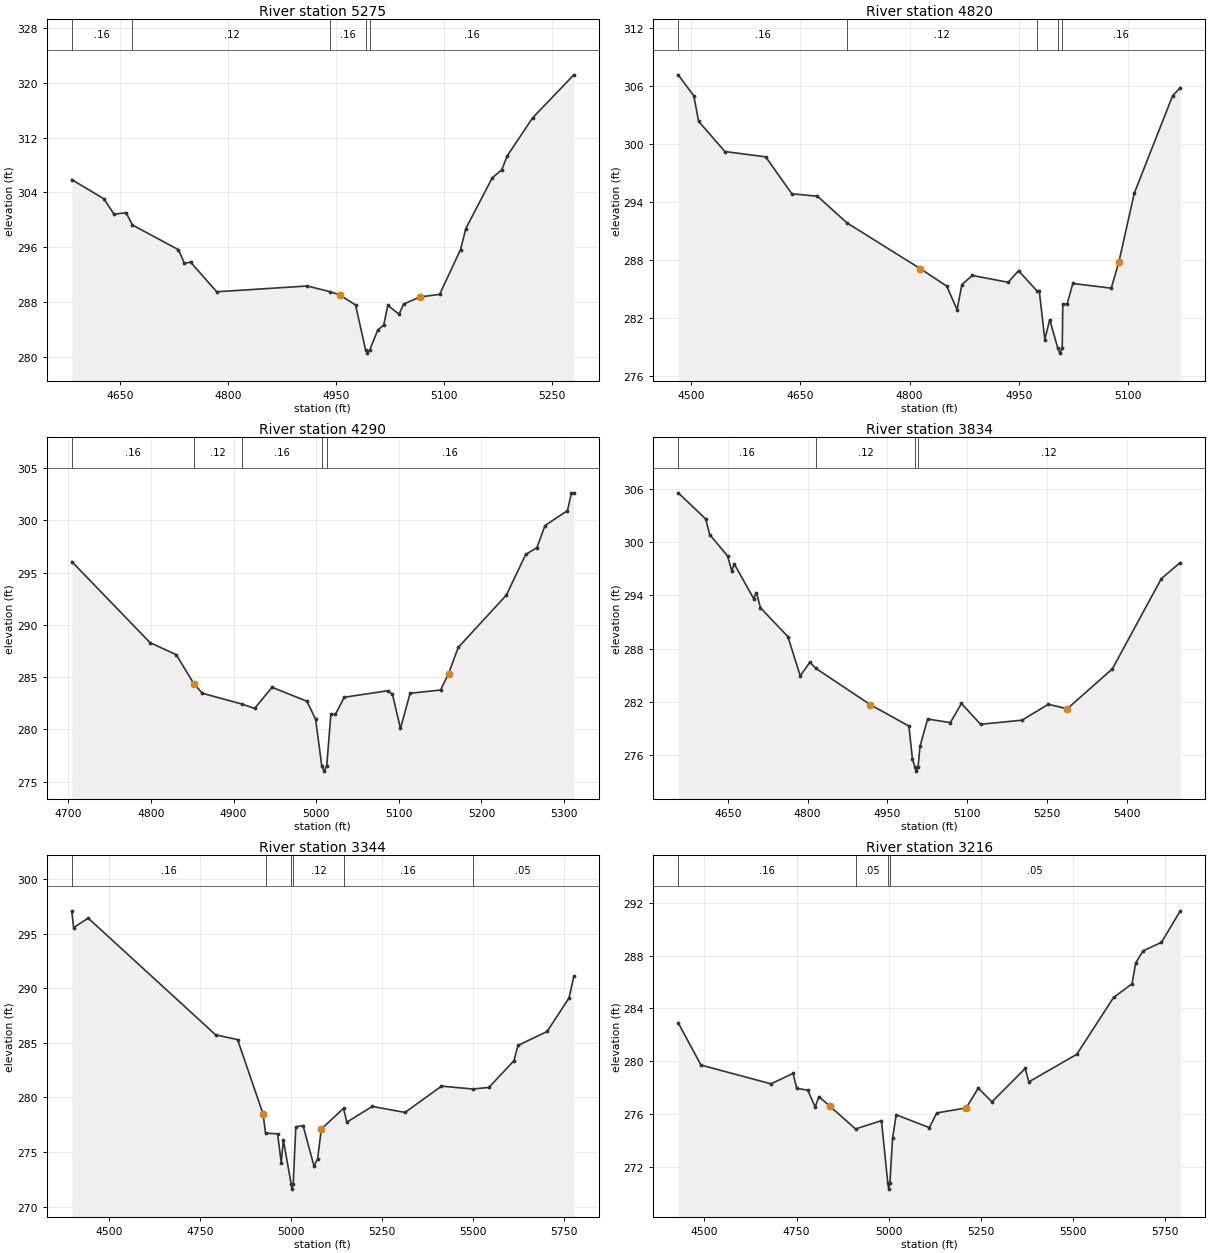
Type RM Length L Ch R = 1 ,5275    ,455,455,455
BEGIN DESCRIPTION:
UNT 124 IN CACR 6.0
END DESCRIPTION:
XS GIS Cut Line= 3
      3672949.62      10690910.2      3672749.61     10690510.19
      3672599.63     10690310.21
#Sta/Elev= 30
    4583  305.87  4627.7  303.06  4641.7  300.82  4658.5  301.04  4667.2  299.25
  4731.2  295.64  4739.5  293.64  4747.9  293.84  4784.3  289.51    4910  290.35
  4942.2  289.51  4954.8  289.07  4977.1  287.58  4990.9  281.06  4993.6  280.56
  4996.9  281.06  5007.9  283.92  5016.3  284.69  5021.8  287.52  5037.5  286.24
  5043.8  287.71  5066.7  288.76  5093.8  289.13  5122.9  295.67  5130.2  298.73
  5166.7  306.09  5180.2  307.33  5187.5   309.3  5222.9  314.87  5280.2  321.15
#Mann= 5 ,-1 , 0
    4583     .16       0  4667.2     .12       0  4942.2     .16       0
  4990.9     .07       0  4996.9     .16       0
Bank Sta=4954.8,5066.7
XS Rating Curve= 0 ,0
Exp/Cntr=0.3,0.1

Type RM Length L Ch R = 1 ,4820    ,530,530,530
BEGIN DESCRIPTION:
UNT 124 IN CACR 5.0
END DESCRIPTION:
XS GIS Cut Line= 3
      3673499.61     10690660.19      3673099.61     10690310.19
      3673049.62     10690160.21
#Sta/Elev= 30
  4482.3  307.16  4503.7  304.98  4510.3  302.34  4546.4  299.21  4602.4  298.66
  4638.4  294.83  4673.5  294.58    4714  291.82    4815  287.06    4851  285.27
  4865.3  282.83  4871.9  285.42  4886.1  286.37  4935.5  285.66  4949.7  286.86
  4975.5  284.73  4978.2  284.75  4985.8  279.73  4992.5  281.79  5003.7  278.82
  5006.4  278.32  5009.7  278.82  5010.5  283.42  5016.4  283.42  5024.3  285.54
  5077.1  285.05  5087.6   287.8  5108.7   294.9  5161.4     305  5171.9  305.83
#Mann= 5 ,-1 , 0
  4482.3     .16       0    4714     .12       0  4975.5     .16       0
  5003.7     .07       0  5009.7     .16       0
Bank Sta=4815,5087.6
XS Rating Curve= 0 ,0
Exp/Cntr=0.3,0.1

Type RM Length L Ch R = 1 ,4290    ,456,456,456
BEGIN DESCRIPTION:
UNT 124 IN CACR 4.0
END DESCRIPTION:
XS GIS Cut Line= 3
       3673499.6     10690460.15      3673399.61     10690160.19
      3673149.64     10690010.21
#Sta/Elev= 30
  4704.2  296.06    4799   288.3  4830.7  287.15    4852  284.37  4862.3  283.46
  4910.5  282.42  4925.5  282.01  4946.6  284.03  4988.8   282.7  4999.3  280.98
  5006.8  276.51  5009.6  276.01  5012.8  276.51  5017.8  281.44  5023.3  281.44
    5034  283.08  5086.5   283.7  5092.3  283.39    5102  280.09  5113.7  283.46
  5150.6  283.77  5160.3  285.35    5172  287.85  5230.3  292.86  5253.6  296.74
  5267.2   297.4    5277  299.51  5304.2  300.94    5309  302.64  5311.9  302.64
#Mann= 5 ,-1 , 0
  4704.2     .16       0    4852     .12       0  4910.5     .16       0
  5006.8     .07       0  5012.8     .16       0
Bank Sta=4852,5160.3
XS Rating Curve= 0 ,0
Exp/Cntr=0.3,0.1

Type RM Length L Ch R = 1 ,3834    ,490,490,490
BEGIN DESCRIPTION:
UNT 124 IN CACR 3.0
END DESCRIPTION:
XS GIS Cut Line= 3
      3673699.62     10690610.16      3673799.61     10690210.19
       3673449.6     10689810.18
#Sta/Elev= 30
  4556.7  305.52  4608.2  302.59  4615.9  300.82  4649.4  298.42  4657.2  296.76
  4662.3  297.49  4698.4  293.63  4703.6  294.29  4711.3  292.58  4762.8  289.35
    4786  284.94  4804.1  286.45  4815.7  285.76  4917.4   281.7  4990.3  279.28
    4997  275.55  5001.6  274.71  5004.3  274.21  5007.6  274.71  5011.2  277.01
  5025.5  280.07  5068.2  279.67    5089  281.82  5125.1  279.48  5202.9  279.94
  5252.3  281.73  5287.9  281.22  5372.8  285.72  5464.9  295.87  5500.5  297.68
#Mann= 4 ,-1 , 0
  4556.7     .16       0  4815.7     .12       0  5001.6     .07       0
  5007.6     .12       0
Bank Sta=4917.4,5287.9
XS Rating Curve= 0 ,0
Exp/Cntr=0.3,0.1

Type RM Length L Ch R = 1 ,3344    ,128,128,128
BEGIN DESCRIPTION:
Mapping XS b64e48e4
END DESCRIPTION:
XS GIS Cut Line= 2
      3674188.01     10690695.28      3674274.71      10689316.8
#Sta/Elev= 30
  4397.1  297.11  4402.2  295.57  4442.3  296.44    4793  285.74  4853.1  285.31
  4923.2  278.51  4930.2  276.73  4963.3  276.67  4973.3  274.04  4979.2  276.12
  5000.4   272.1  5003.1   271.6  5006.4   272.1  5013.4  277.31  5033.4  277.43
  5063.5  273.71  5073.5  274.38  5083.5   277.1  5144.7  279.01  5153.7  277.74
  5223.8  279.18    5314  278.63  5414.2  281.04    5500  280.78  5544.5  280.92
  5613.5  283.37  5624.6  284.77  5704.8  286.05  5764.9  289.12  5778.3  291.11
#Mann= 6 ,-1 , 0
  4397.1     .16       0  4930.2     .12       0  5000.4     .07       0
  5006.4     .12       0  5144.7     .16       0    5500     .05       0
Bank Sta=4923.2,5083.5
XS Rating Curve= 0 ,0
Exp/Cntr=0.3,0.1

Type RM Length L Ch R = 1 ,3216    ,866,866,866
BEGIN DESCRIPTION:
UNT 124 IN CACR 2.0
END DESCRIPTION:
XS GIS Cut Line= 2
      3674344.26     10690651.86      3674361.62     10689289.07
#Sta/Elev= 30
  4428.8  282.91  4490.5  279.72  4680.5   278.3  4740.5  279.09  4750.5  277.96
  4780.5  277.82  4800.5  276.54  4810.5  277.34  4840.5  276.61  4910.1  274.89
  4980.5  275.52  4997.5  270.84  5000.3  270.34  5003.5  270.84  5010.5  274.17
  5020.5  275.96  5110.5  274.99  5130.5   276.1  5210.5  276.48  5243.2  277.97
  5280.5  276.94  5370.6  279.46  5380.6  278.45  5510.6  280.53  5610.6  284.83
  5660.6  285.86  5670.6  287.44  5690.6  288.35  5740.6     289  5791.7  291.38
#Mann= 4 ,-1 , 0
  4428.8     .16       0  4910.1     .05       0  4997.5     .04       0
  5003.5     .05       0
Bank Sta=4840.5,5210.5
XS Rating Curve= 0 ,0
Exp/Cntr=0.3,0.1

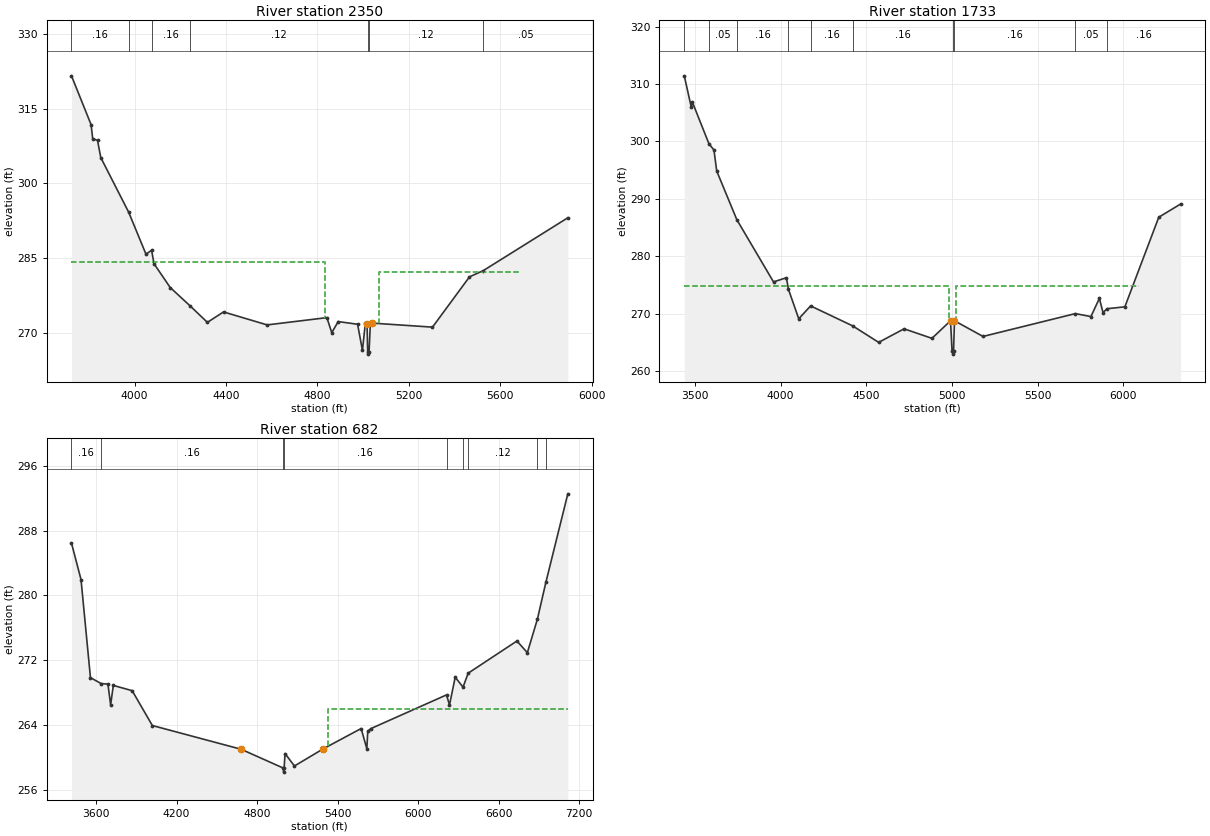
Type RM Length L Ch R = 1 ,2350    ,617,617,617
BEGIN DESCRIPTION:
Mapping XS f940c028
END DESCRIPTION:
XS GIS Cut Line= 3
      3674082.02     10690983.89      3674988.29      10690067.2
      3674556.01     10689296.39
#Sta/Elev= 30
  3723.4  321.65  3809.2  311.83  3816.2  309.04  3837.5  308.64  3851.6  305.21
    3974  294.19  4049.6  285.76    4074  286.56  4084.9  283.84  4155.6  279.06
  4243.3  275.34  4318.3  272.05    4389  274.15  4579.9  271.54  4841.5     273
  4862.8  269.98  4891.1  272.21  4975.9  271.67  4997.1  266.42  5009.8  271.88
  5017.4  271.64  5020.1  266.16  5022.8  265.66  5026.1  266.16    5032  271.94
  5039.1   271.9  5303.8  271.09  5465.8  281.21  5526.2  282.46  5896.2  293.09
#Mann= 7 ,-1 , 0
  3723.4     .16       0    3974     .05       0    4074     .16       0
  4243.3     .12       0  5020.1     .07       0  5026.1     .12       0
  5526.2     .05       0
#XS Ineff= 2 ,-1
  3723.4 4832.39  284.27  5069.6 5686.08  282.17
Permanent Ineff=
       F       F
Bank Sta=5017.4,5039.1
XS Rating Curve= 0 ,0
Exp/Cntr=0.3,0.1

Type RM Length L Ch R = 1 ,1733    ,1051,1051,1051
BEGIN DESCRIPTION:
Mapping XS acfa7cf2
END DESCRIPTION:
XS GIS Cut Line= 4
      3674149.77     10691145.32      3675326.83     10690520.32
      3675519.54      10690192.2       3674691.4     10689348.43
#Sta/Elev= 30
  3437.7  311.41  3478.9  305.91  3484.5  306.87  3581.7  299.57  3610.8  298.49
  3627.1  294.82  3744.3  286.35  3958.3  275.51  4033.5  276.24  4045.7   274.2
  4105.5  269.09  4174.8  271.33  4420.2  267.85  4571.8  264.98    4720  267.34
  4882.6  265.68  4990.9  268.74  4999.8  263.52  5005.4  262.93  5008.6  263.43
  5014.1  268.74  5180.6  266.01  5719.3  269.99    5810  269.47  5859.4  272.64
  5880.7  270.16  5903.9  270.84    6008  271.17  6205.9  286.78  6333.2  289.08
#Mann= 10 ,-1 , 0
  3437.7     .16       0  3581.7     .05       0  3744.3     .16       0
  4045.7     .12       0  4174.8     .16       0  4420.2     .16       0
  5005.4     .07       0  5008.6     .16       0  5719.3     .05       0
  5903.9     .16       0
#XS Ineff= 2 ,-1
 3433.72 4980.68 274.789 5022.44 6092.33 274.789
Permanent Ineff=
       F       F
Bank Sta=4990.9,5014.1
XS Rating Curve= 0 ,0
Exp/Cntr=0.3,0.1

Type RM Length L Ch R = 1 ,682     ,0,0,0
BEGIN DESCRIPTION:
UNT 124 IN CACR 1.0
END DESCRIPTION:
XS GIS Cut Line= 4
       3674748.7     10690957.83      3676217.46     10690848.45
      3676201.83     10690588.03      3674868.49     10689145.32
#Sta/Elev= 30
  3416.9  286.46    3488  281.96  3558.2  269.86  3637.8  269.13  3688.6  269.06
  3708.6  266.51  3728.7   268.9  3869.1  268.25  4019.5  263.95  4681.3  261.02
  4995.2   258.7  4997.9   258.2  5001.2   258.7  5008.2  260.49  5078.3  258.96
  5292.3  261.07  5575.2  263.58  5617.7  261.08  5624.5  263.24  5646.1  263.56
  6211.4  267.73  6233.5  266.48    6276  269.91  6334.4  268.69  6372.8  270.41
  6735.9  274.38  6813.6  272.94  6888.3  277.06  6951.9  281.64  7115.1  292.54
#Mann= 9 ,-1 , 0
  3416.9     .16       0  3637.8     .16       0  4995.2     .07       0
  5001.2     .16       0  6211.4     .05       0  6334.4     .16       0
  6372.8     .12       0  6888.3     .16       0  6951.9     .05       0
#XS Ineff= 2 , 0
                         5329.26          265.96
Permanent Ineff=
       F       F
Bank Sta=4681.3,5292.3
XS Rating Curve= 0 ,0
Exp/Cntr=0.3,0.1

Chan Stop Cuts=-1
Use User Specified Reach Order=0
Composite Channel Slope=5