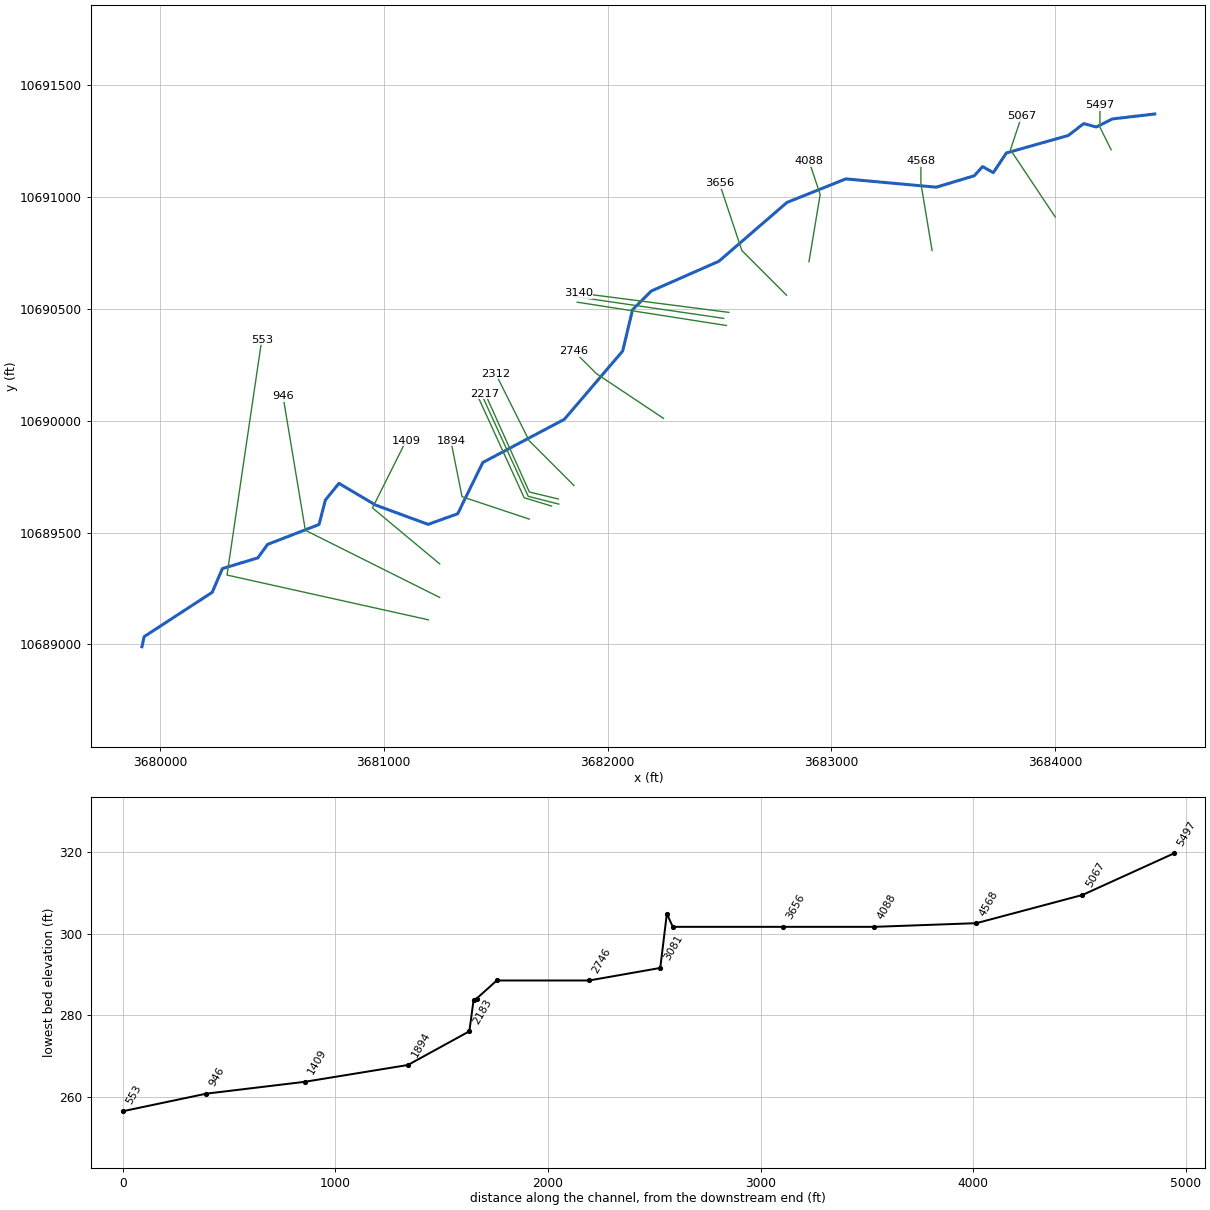
--- UNT 125 IN CACR.prj (project) ---

Proj Title=UNT 125 IN CACR Base Level Engineering
Current Plan=p01
Default Exp/Contr=0.3,0.1
English Units
Geom File=g01
Flow File=f01
Plan File=p01
BEGIN DESCRIPTION:
UNT 125 IN CACR
END DESCRIPTION:

--- UNT 125 IN CACR.p01 (plan) ---

Plan Title=Multiple Run
Short Identifier=Multiple
Geom File=g01
Flow File=f01
Subcritical Flow
K Sum by GR= 0
Std Step Tol= 0.01
Critical Tol= 0.01
Num of Std Step Trials= 20
Max Error Tol= 0.3
Flow Tol Ratio= 0.001
Split Flow NTrial= 30
Split Flow Tol= 0.02
Split Flow Ratio= 0.02
Log Output Level= 0
Friction Slope Method= 1
Unsteady Friction Slope Method= 2
Unsteady Bridges Friction Slope Method= 1
Parabolic Critical Depth
Global Vel Dist=  1 , 1 , 1
Global Log Level= 0
CheckData=True
Encroach Param= -1, 0, 0, 0
BEGIN DESCRIPTION:
Multiple Run
END DESCRIPTION:

--- UNT 125 IN CACR.f01 (steady flow) ---

Flow Title=Multiple
Number of Profiles=7
Profile Names=10-year,25-year,50-year,1pct_min,100-year,1pct_plu,500-year
River Rch & RM= UNT 125 IN CACR,Reach-1,5497
     451     610     743     666     900    1217    1327
Boundary for River Rch & Prof#=UNT 125 IN CACR,Reach-1,1
Up Type=0
Dn Type=3
Dn Slope=0.005
Boundary for River Rch & Prof#=UNT 125 IN CACR,Reach-1,2
Up Type=0
Dn Type=3
Dn Slope=0.005
Boundary for River Rch & Prof#=UNT 125 IN CACR,Reach-1,3
Up Type=0
Dn Type=3
Dn Slope=0.005
Boundary for River Rch & Prof#=UNT 125 IN CACR,Reach-1,4
Up Type=0
Dn Type=3
Dn Slope=0.005
Boundary for River Rch & Prof#=UNT 125 IN CACR,Reach-1,5
Up Type=0
Dn Type=3
Dn Slope=0.005
Boundary for River Rch & Prof#=UNT 125 IN CACR,Reach-1,6
Up Type=0
Dn Type=3
Dn Slope=0.005
Boundary for River Rch & Prof#=UNT 125 IN CACR,Reach-1,7
Up Type=0
Dn Type=3
Dn Slope=0.005

--- UNT 125 IN CACR.g01 (geometry) ---

Geom Title=Existing Conditions

River Reach=UNT 125 IN CACR,Reach-1
Reach XY= 30
      3684444.50     10691370.00      3684255.25     10691348.00
      3684183.75     10691312.00      3684127.00     10691327.00
      3684058.00     10691274.00      3683781.75     10691196.00
      3683723.00     10691108.00      3683675.25     10691135.00
      3683638.00     10691094.00      3683468.25     10691043.00
      3683064.50     10691080.00      3682801.50     10690975.00
      3682497.00     10690712.00      3682194.75     10690579.00
      3682111.50     10690496.00      3682067.25     10690311.00
      3681806.75     10690006.00      3681442.25     10689813.00
      3681330.25     10689584.00      3681198.01     10689536.58
      3680963.00     10689623.00      3680799.50     10689720.00
      3680739.00     10689645.00      3680710.75     10689536.00
      3680480.75     10689447.00      3680437.50     10689387.00
      3680279.00     10689339.00      3680233.50     10689233.00
      3679929.50     10689035.00      3679919.50     10688990.00

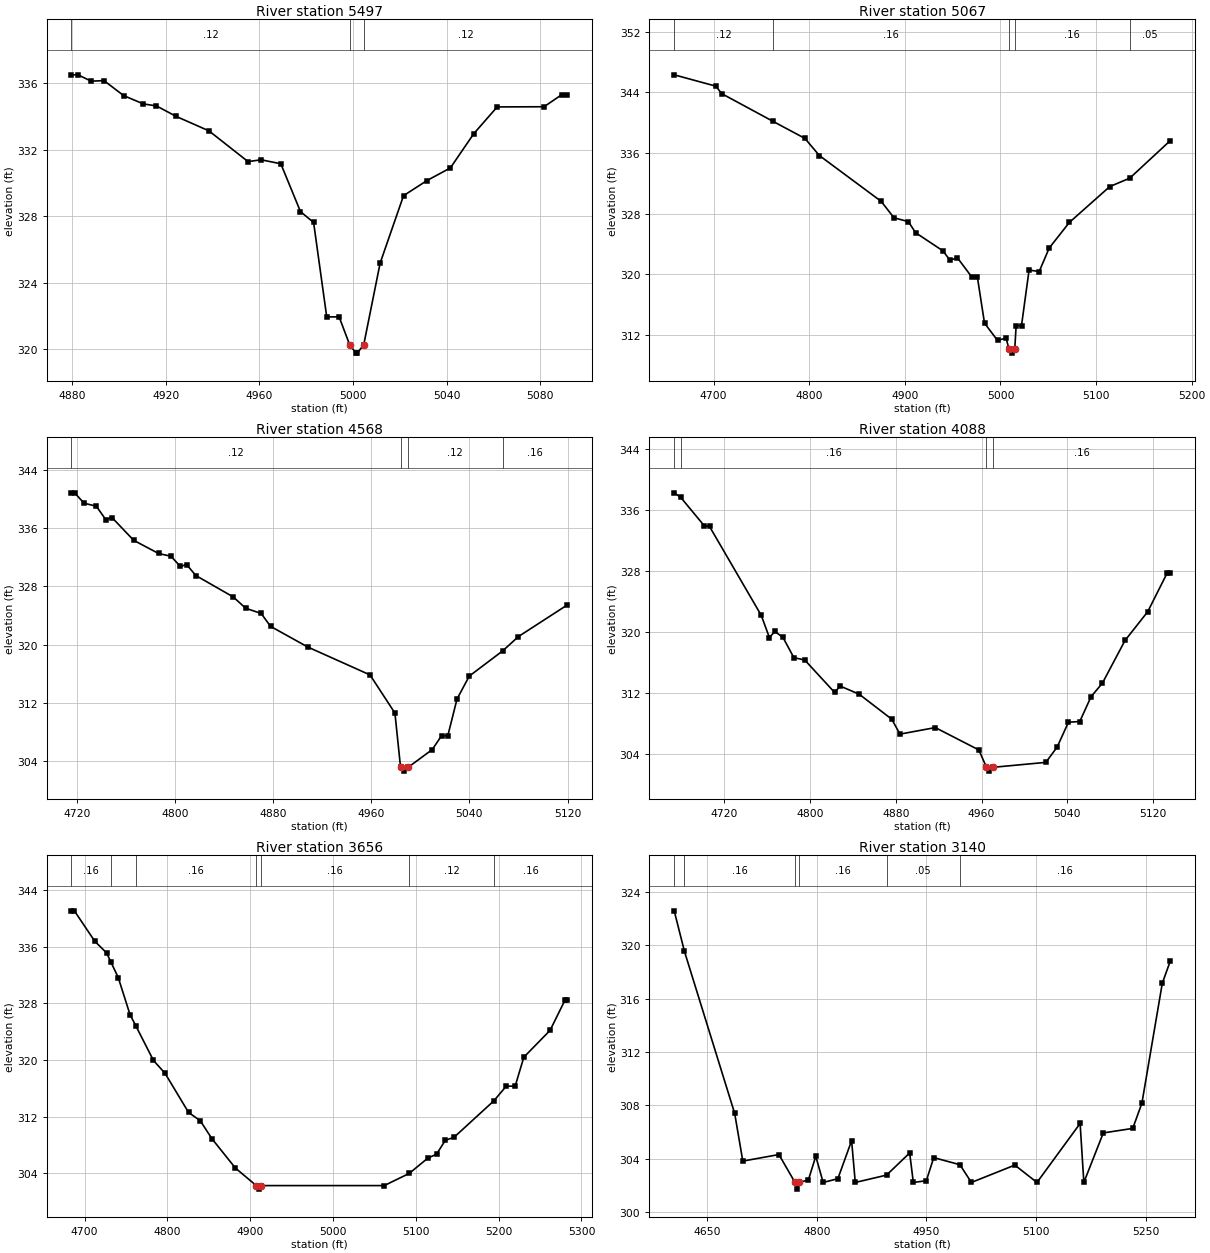
Type RM Length L Ch R = 1,5497,430,430,430
BEGIN DESCRIPTION:
UNT 125 IN CACR 12.0
END DESCRIPTION:
XS GIS Cut Line= 3
      3684249.59     10691210.22      3684199.61     10691310.19
      3684199.61     10691410.22
#Sta/Elev= 29
  4879.8  336.51  4882.6  336.51  4888.2  336.13  4893.7  336.16  4902.1  335.26
  4910.5  334.76  4916.1  334.64  4924.5  334.01  4938.5  333.14  4955.2  331.29
  4960.8  331.40  4969.2  331.16  4977.6  328.28  4983.2  327.63  4988.8  321.95
  4994.1  321.95  4998.6  320.27  5001.3  319.77  5001.8  319.77  5004.6  320.27
  5011.6  325.18  5021.6  329.24  5031.6  330.15  5041.6  330.91  5051.6  332.97
  5061.6  334.58  5081.6  334.59  5089.1  335.31  5091.6  335.31
#Mann=3,-1,0
  4879.8    0.12       0  4998.6    0.07       0  5004.6    0.12       0
Bank Sta=4998.6,5004.6
Exp/Cntr=0.3,0.1

Type RM Length L Ch R = 1,5067,499,499,499
BEGIN DESCRIPTION:
UNT 125 IN CACR 11.0
END DESCRIPTION:
XS GIS Cut Line= 3
      3683999.63     10690910.16      3683799.61     10691210.19
      3683849.61     10691360.19
#Sta/Elev= 30
  4658.8  346.32  4702.4  344.82  4708.4  343.84  4762.2  340.17  4795.5  337.92
  4810.6  335.66  4875.2  329.61  4888.7  327.43  4903.7  326.93  4911.2  325.47
  4939.8  323.07  4947.3  321.82  4954.8  322.18  4969.8  319.65  4975.8  319.65
  4983.3  313.52  4996.9  311.24  5005.9  311.55  5008.9  310.06  5011.6  309.56
  5014.9  310.06  5016.4  313.20  5022.0  313.20  5029.9  320.53  5040.5  320.34
  5051.0  323.45  5072.1  326.83  5114.3  331.56  5135.2  332.67  5177.5  337.62
#Mann=5,-1,0
  4658.8    0.12       0  4762.2    0.16       0  5008.9    0.07       0
  5014.9    0.16       0  5135.2    0.05       0
Bank Sta=5008.9,5014.9
Exp/Cntr=0.3,0.1

Type RM Length L Ch R = 1,4568,480,480,480
BEGIN DESCRIPTION:
UNT 125 IN CACR 10.0
END DESCRIPTION:
XS GIS Cut Line= 3
      3683449.61     10690760.16      3683399.61     10691060.19
      3683399.61     10691160.22
#Sta/Elev= 30
  4715.7  340.84  4718.3  340.84  4725.9  339.42  4736.0  339.00  4743.6  337.17
  4748.7  337.45  4766.4  334.32  4786.7  332.51  4796.8  332.13  4804.4  330.74
  4809.5  330.99  4817.1  329.48  4847.5  326.55  4857.7  324.99  4870.3  324.28
  4877.9  322.51  4908.4  319.66  4959.0  315.84  4979.3  310.60  4983.9  303.13
  4986.7  302.63  4989.9  303.13  5009.7  305.59  5017.3  307.49  5022.4  307.49
  5029.9  312.53  5039.9  315.68  5067.2  319.15  5079.9  321.10  5119.9  325.46
#Mann=4,-1,0
  4715.7    0.12       0  4983.9    0.07       0  4989.9    0.12       0
  5067.2    0.16       0
Bank Sta=4983.9,4989.9
Exp/Cntr=0.3,0.1

Type RM Length L Ch R = 1,4088,432,432,432
BEGIN DESCRIPTION:
UNT 125 IN CACR 9.0
END DESCRIPTION:
XS GIS Cut Line= 3
      3682899.61     10690710.20      3682949.61     10691010.19
      3682899.62     10691160.15
#Sta/Elev= 30
  4673.6  338.28  4679.5  337.71  4701.5  333.97  4706.5  333.86  4754.7  322.19
  4762.3  319.27  4767.4  320.08  4775.0  319.28  4785.1  316.63  4795.2  316.33
  4823.1  312.06  4828.2  312.90  4845.9  311.84  4876.3  308.55  4884.0  306.59
  4916.9  307.45  4957.5  304.51  4964.6  302.23  4967.3  301.73  4970.6  302.23
  5019.9  302.88  5030.4  304.88  5041.0  308.16  5051.5  308.24  5062.1  311.52
  5072.6  313.28  5093.7  318.89  5114.8  322.66  5133.2  327.81  5135.8  327.81
#Mann=4,-1,0
  4673.6    0.12       0  4679.5    0.16       0  4964.6    0.07       0
  4970.6    0.16       0
Bank Sta=4964.6,4970.6
Exp/Cntr=0.3,0.1

Type RM Length L Ch R = 1,3656,516,516,516
BEGIN DESCRIPTION:
UNT 125 IN CACR 8.0
END DESCRIPTION:
XS GIS Cut Line= 3
      3682799.58     10690560.22      3682599.61     10690760.19
      3682499.62     10691060.16
#Sta/Elev= 30
  4684.1  341.10  4687.6  341.10  4712.3  336.79  4726.5  335.15  4731.9  333.81
  4740.6  331.66  4754.8  326.42  4761.7  324.86  4783.1  319.94  4797.2  318.10
  4825.5  312.58  4839.6  311.41  4853.8  308.85  4882.1  304.71  4907.3  302.23
  4910.1  301.73  4913.3  302.23  5061.8  302.23  5092.0  303.95  5114.5  306.12
  5125.0  306.67  5135.6  308.64  5146.1  309.06  5194.1  314.21  5209.3  316.31
  5219.9  316.28  5230.4  320.39  5262.1  324.19  5280.5  328.55  5283.1  328.55
#Mann=7,-1,0
  4684.1    0.16       0  4731.9    0.12       0  4761.7    0.16       0
  4907.3   0.033       0  4913.3    0.16       0  5092.0    0.12       0
  5194.1    0.16       0
Bank Sta=4907.3,4913.3
Exp/Cntr=0.3,0.1

Type RM Length L Ch R = 1,3140,28,28,28
BEGIN DESCRIPTION:
Mapping XS 9aaf82fd
END DESCRIPTION:
XS GIS Cut Line= 2
      3682541.60     10690483.69      3681868.88     10690570.49
#Sta/Elev= 30
  4605.0  322.58  4619.0  319.54  4687.7  307.40  4698.8  303.83  4748.2  304.32
  4770.2  302.23  4772.9  301.73  4776.2  302.23  4788.5  302.42  4798.6  304.19
  4808.7  302.23  4828.8  302.51  4847.6  305.36  4852.6  302.23  4895.4  302.78
  4927.0  304.44  4932.0  302.23  4949.8  302.36  4959.9  304.09  4995.7  303.56
  5011.4  302.23  5070.8  303.53  5101.1  302.23  5160.1  306.65  5165.2  302.23
  5191.8  305.94  5232.1  306.28  5244.6  308.17  5272.5  317.16  5283.3  318.80
#Mann=6,-1,0
  4605.0    0.05       0  4619.0    0.16       0  4770.2    0.07       0
  4776.2    0.16       0  4895.4    0.05       0  4995.7    0.16       0
Bank Sta=4770.2,4776.2
Exp/Cntr=0.3,0.1

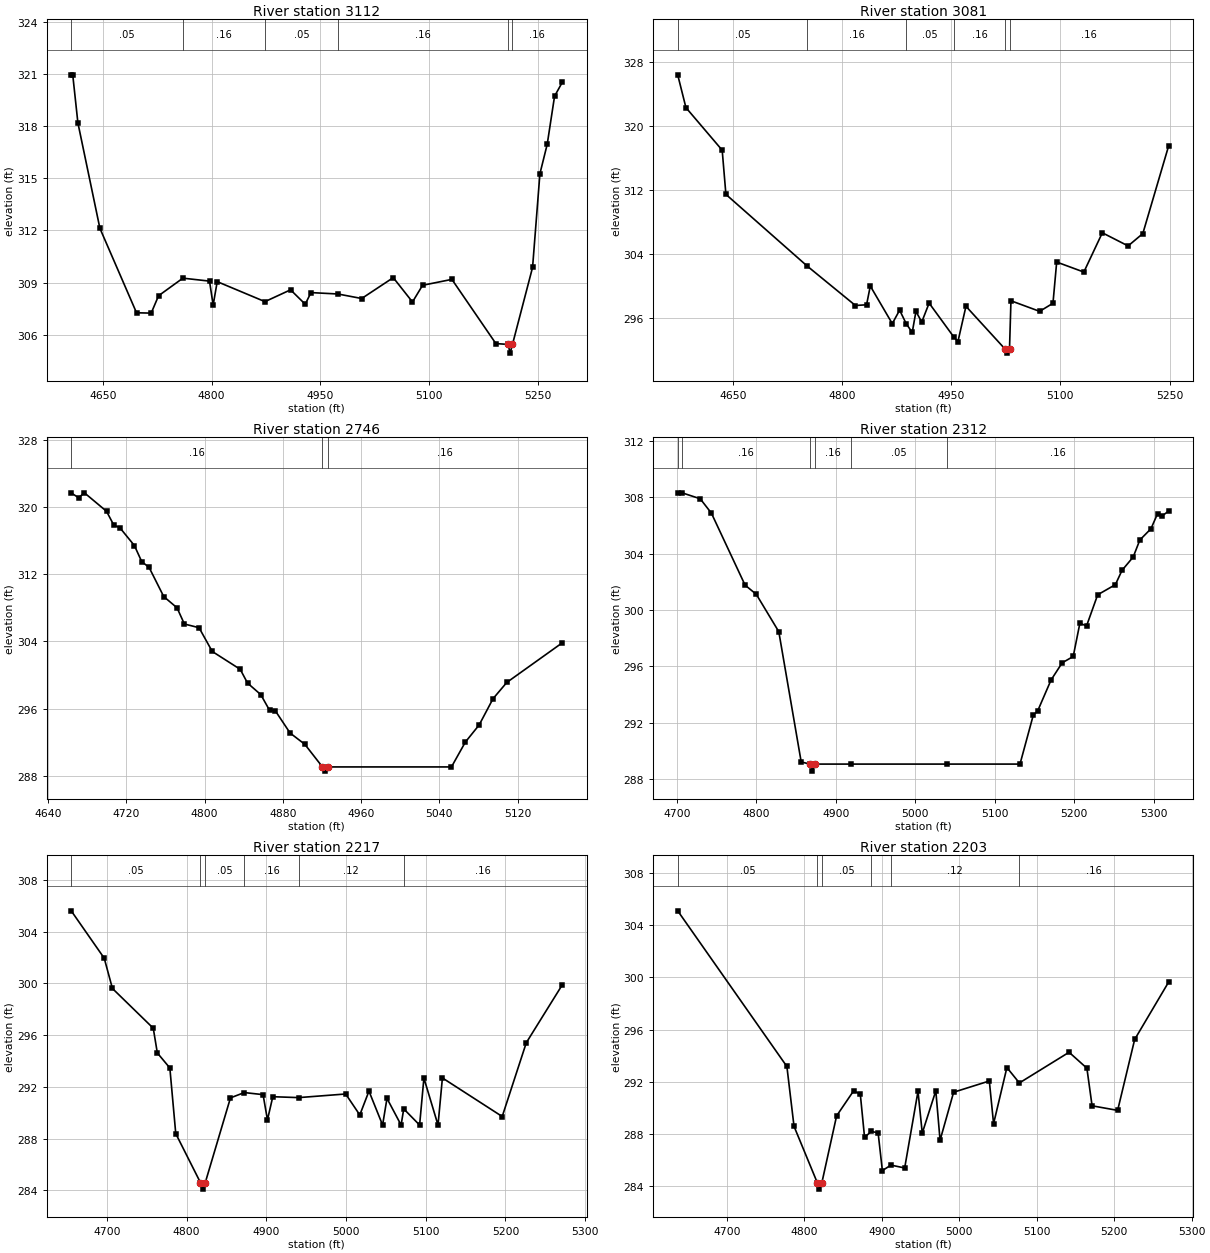
Type RM Length L Ch R = 1,3112,31,31,31
BEGIN DESCRIPTION:
Mapping XS d5b6d046
END DESCRIPTION:
XS GIS Cut Line= 2
      3682518.70     10690456.95      3681849.22     10690554.87
#Sta/Elev= 30
  4606.6  320.94  4608.7  320.94  4615.8  318.18  4646.1  312.12  4696.6  307.26
  4716.8  307.24  4727.0  308.24  4760.5  309.25  4797.2  309.08  4802.2  307.70
  4807.8  309.05  4873.6  307.90  4908.9  308.58  4929.1  307.75  4937.0  308.42
  4974.1  308.34  5006.9  308.08  5050.4  309.28  5076.9  307.88  5090.8  308.84
  5131.2  309.18  5191.8  305.49  5208.7  305.44  5211.4  304.94  5214.7  305.44
  5242.4  309.87  5252.5  315.25  5262.6  316.95  5272.7  319.71  5283.2  320.50
#Mann=6,-1,0
  4606.6    0.05       0  4760.5    0.16       0  4873.6    0.05       0
  4974.1    0.16       0  5208.7    0.07       0  5214.7    0.16       0
Bank Sta=5208.7,5214.7
Exp/Cntr=0.3,0.1

Type RM Length L Ch R = 1,3081,335,335,335
BEGIN DESCRIPTION:
UNT 125 IN CACR 7.0
END DESCRIPTION:
XS GIS Cut Line= 2
      3682530.76     10690425.09      3681864.55     10690529.25
#Sta/Elev= 30
  4574.4  326.34  4585.7  322.25  4635.5  316.94  4640.6  311.43  4752.1  302.50
  4818.5  297.57  4833.8  297.66  4838.9  300.00  4869.1  295.31  4879.2  296.99
  4888.3  295.29  4896.5  294.21  4901.6  296.83  4909.6  295.51  4919.7  297.87
  4953.7  293.63  4959.3  293.08  4970.3  297.47  5024.1  292.13  5026.8  291.63
  5030.1  292.13  5032.1  298.16  5071.5  296.84  5089.8  297.85  5094.9  302.99
  5132.2  301.74  5157.6  306.64  5193.0  305.00  5213.2  306.54  5248.7  317.49
#Mann=6,-1,0
  4574.4    0.05       0  4752.1    0.16       0  4888.3    0.05       0
  4953.7    0.16       0  5024.1    0.07       0  5030.1    0.16       0
Bank Sta=5024.1,5030.1
Exp/Cntr=0.3,0.1

Type RM Length L Ch R = 1,2746,434,434,434
BEGIN DESCRIPTION:
UNT 125 IN CACR 6.0
END DESCRIPTION:
XS GIS Cut Line= 3
      3682249.61     10690010.19      3681949.61     10690210.19
      3681849.59     10690310.21
#Sta/Elev= 30
  4663.6  321.70  4671.1  321.13  4677.1  321.71  4699.7  319.51  4707.2  317.85
  4713.2  317.57  4728.2  315.43  4735.7  313.51  4743.2  312.83  4758.2  309.35
  4771.8  308.01  4779.3  306.08  4794.3  305.64  4807.8  302.81  4836.4  300.68
  4843.9  299.04  4857.4  297.67  4866.4  295.80  4872.4  295.72  4887.4  293.09
  4902.5  291.74  4920.5  289.05  4923.2  288.55  4926.5  289.05  5052.4  289.05
  5066.6  292.01  5080.7  294.05  5094.9  297.18  5109.0  299.12  5165.6  303.83
#Mann=3,-1,0
  4663.6    0.16       0  4920.5    0.07       0  4926.5    0.16       0
Bank Sta=4920.5,4926.5
Exp/Cntr=0.3,0.1

Type RM Length L Ch R = 1,2312,95,95,95
BEGIN DESCRIPTION:
UNT 125 IN CACR 5.0
END DESCRIPTION:
XS GIS Cut Line= 3
      3681849.59     10689710.20      3681649.61     10689910.19
      3681499.62     10690210.16
#Sta/Elev= 30
  4700.8  308.31  4706.3  308.31  4729.1  307.89  4743.2  306.87  4785.6  301.76
  4799.8  301.10  4828.1  298.45  4856.3  289.20  4867.5  289.05  4870.2  288.55
  4873.5  289.05  4919.6  289.05  5039.6  289.05  5131.8  289.05  5148.5  292.52
  5154.1  292.83  5170.9  295.02  5184.9  296.24  5198.8  296.69  5207.2  299.05
  5215.6  298.86  5229.6  301.07  5251.9  301.79  5260.3  302.81  5274.3  303.75
  5282.7  304.96  5296.7  305.76  5305.1  306.84  5310.6  306.66  5319.0  307.02
#Mann=6,-1,0
  4700.8    0.05       0  4706.3    0.16       0  4867.5   0.033       0
  4873.5    0.16       0  4919.6    0.05       0  5039.6    0.16       0
Bank Sta=4867.5,4873.5
Exp/Cntr=0.3,0.1

Type RM Length L Ch R = 1,2217,14,14,14
BEGIN DESCRIPTION:
Mapping XS 4732dd06
END DESCRIPTION:
XS GIS Cut Line= 3
      3681779.88     10689649.92      3681650.32     10689681.19
      3681452.64     10690121.25
#Sta/Elev= 30
  4655.4  305.60  4696.8  301.94  4707.1  299.60  4758.3  296.53  4763.4  294.62
  4779.1  293.46  4786.5  288.39  4817.5  284.60  4820.2  284.10  4823.5  284.60
  4855.1  291.15  4872.5  291.56  4896.0  291.40  4901.5  289.45  4908.2  291.24
  4940.7  291.17  4999.6  291.45  5017.3  289.83  5028.8  291.67  5045.9  289.05
  5051.4  291.11  5069.1  289.05  5072.4  290.30  5092.3  289.05  5097.7  292.68
  5115.4  289.05  5120.9  292.69  5195.9  289.71  5226.1  295.41  5271.1  299.87
#Mann=6,-1,0
  4655.4    0.05       0  4817.5    0.07       0  4823.5    0.05       0
  4872.5    0.16       0  4940.7    0.12       0  5072.4    0.16       0
Bank Sta=4817.5,4823.5
Exp/Cntr=0.3,0.1

Type RM Length L Ch R = 1,2203,20,20,20
BEGIN DESCRIPTION:
Mapping XS 5053004d
END DESCRIPTION:
XS GIS Cut Line= 3
      3681782.01     10689627.14      3681645.34     10689661.86
      3681440.19     10690110.13
#Sta/Elev= 30
  4636.3  305.10  4777.3  293.18  4786.5  288.60  4816.5  284.29  4819.2  283.79
  4822.5  284.29  4841.5  289.40  4863.5  291.32  4872.1  291.06  4877.6  287.75
  4886.2  288.21  4895.1  288.10  4900.6  285.21  4911.7  285.63  4929.4  285.41
  4946.6  291.28  4952.1  288.08  4969.6  291.32  4975.1  287.53  4992.6  291.21
  5038.7  292.07  5044.2  288.80  5061.4  293.10  5077.5  291.92  5141.7  294.27
  5164.7  293.05  5171.4  290.17  5204.4  289.82  5226.4  295.25  5270.3  299.65
#Mann=6,-1,0
  4636.3    0.05       0  4816.5    0.07       0  4822.5    0.05       0
  4886.2    0.16       0  4911.7    0.12       0  5077.5    0.16       0
Bank Sta=4816.5,4822.5
Exp/Cntr=0.3,0.1

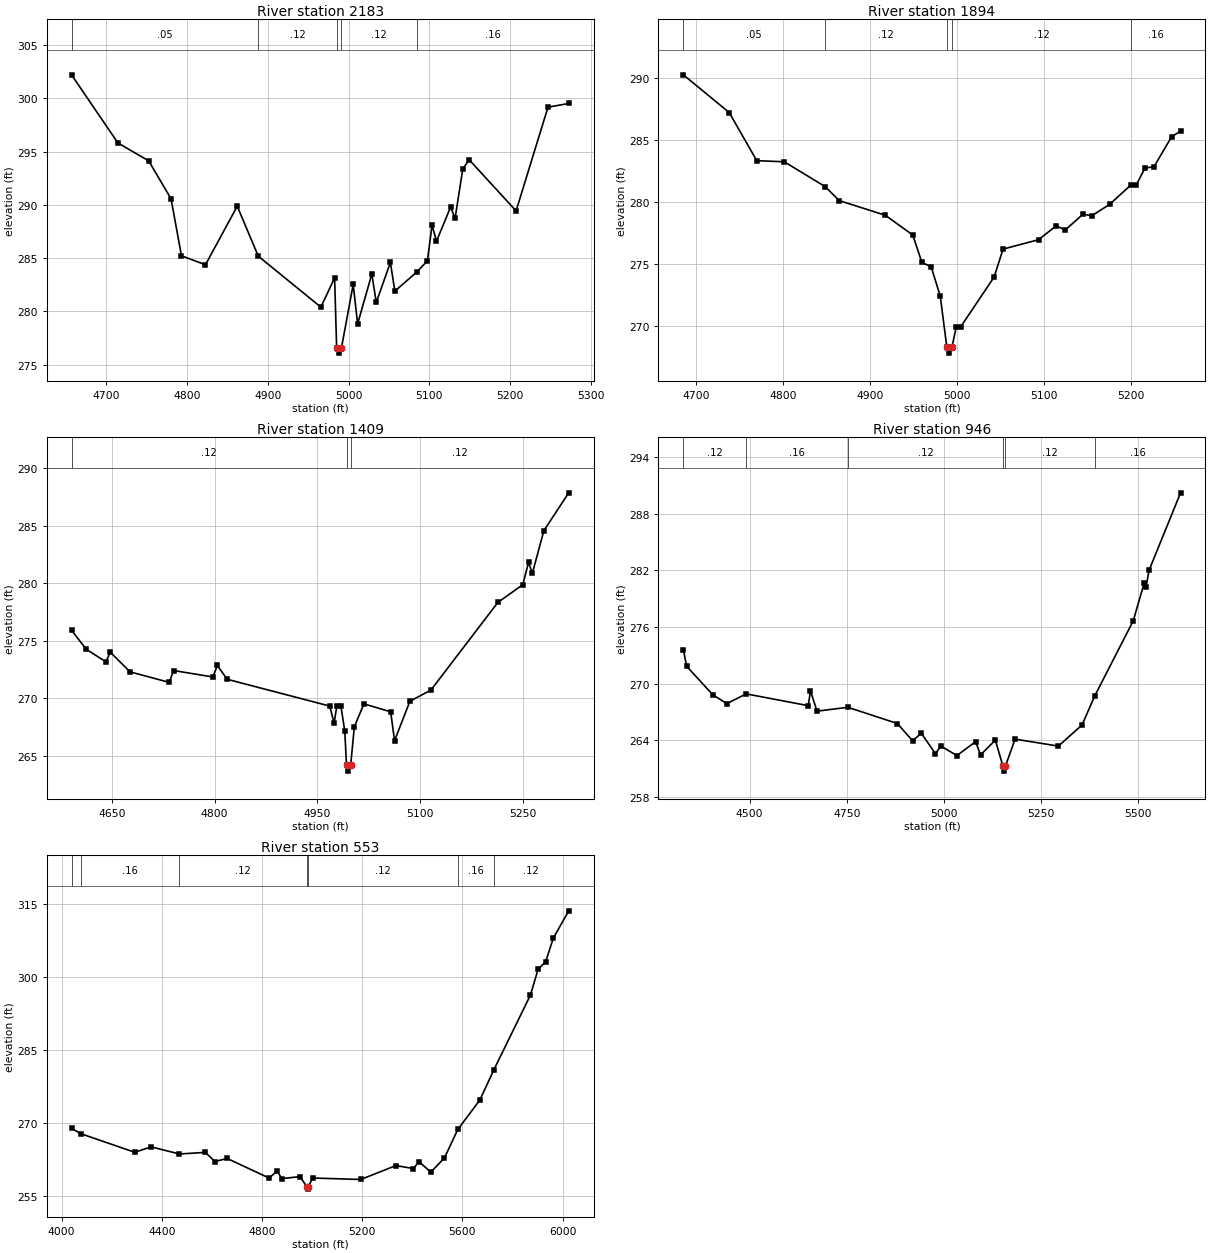
Type RM Length L Ch R = 1,2183,289,289,289
BEGIN DESCRIPTION:
Mapping XS 8e77ccdf
END DESCRIPTION:
XS GIS Cut Line= 3
      3681749.48     10689618.46      3681627.13     10689655.55
      3681424.37     10690099.49
#Sta/Elev= 30
  4656.9  302.21  4714.4  295.81  4752.5  294.13  4780.2  290.56  4793.1  285.21
  4822.8  284.37  4862.2  289.87  4888.2  285.18  4965.8  280.39  4982.8  283.14
  4985.3  276.57  4988.1  276.07  4991.3  276.57  5005.8  282.52  5011.3  278.82
  5028.9  283.50  5034.4  280.84  5051.9  284.59  5057.4  281.89  5084.3  283.67
  5097.7  284.73  5103.5  288.09  5109.0  286.59  5126.5  289.79  5132.0  288.72
  5141.6  293.38  5149.5  294.23  5207.6  289.43  5247.1  299.17  5272.8  299.52
#Mann=5,-1,0
  4656.9    0.05       0  4888.2    0.12       0  4985.3    0.07       0
  4991.3    0.12       0  5084.3    0.16       0
Bank Sta=4985.3,4991.3
Exp/Cntr=0.3,0.1

Type RM Length L Ch R = 1,1894,485,485,485
BEGIN DESCRIPTION:
UNT 125 IN CACR 4.0
END DESCRIPTION:
XS GIS Cut Line= 3
      3681649.56     10689560.20      3681349.61     10689660.19
      3681299.62     10689910.16
#Sta/Elev= 30
  4685.8  290.29  4738.5  287.24  4770.1  283.35  4801.7  283.26  4848.5  281.26
  4864.9  280.12  4917.7  278.94  4949.3  277.34  4959.8  275.12  4970.4  274.78
  4980.9  272.39  4988.4  268.29  4991.2  267.79  4994.4  268.29  4999.3  269.93
  5004.5  269.93  5042.8  273.95  5053.0  276.20  5093.8  276.96  5114.2  278.09
  5124.4  277.74  5144.8  279.02  5155.0  278.90  5175.3  279.81  5200.1  281.40
  5205.9  281.37  5216.1  282.76  5226.3  282.85  5246.7  285.29  5256.9  285.74
#Mann=5,-1,0
  4685.8    0.05       0  4848.5    0.12       0  4988.4    0.07       0
  4994.4    0.12       0  5200.1    0.16       0
Bank Sta=4988.4,4994.4
Exp/Cntr=0.3,0.1

Type RM Length L Ch R = 1,1409,463,463,463
BEGIN DESCRIPTION:
UNT 125 IN CACR 3.0
END DESCRIPTION:
XS GIS Cut Line= 3
      3681249.63     10689360.18      3680949.61     10689610.19
      3681099.59     10689910.15
#Sta/Elev= 30
  4591.2  275.91  4612.7  274.26  4641.3  273.17  4647.8  274.01  4676.5  272.30
  4733.8  271.38  4740.3  272.41  4797.5  271.85  4804.1  272.85  4818.4  271.65
  4968.1  269.32  4974.6  267.84  4978.5  269.31  4984.5  269.31  4990.1  267.16
  4992.7  264.16  4995.5  263.66  4998.7  264.16  5004.1  267.52  5018.1  269.51
  5057.2  268.82  5062.8  266.30  5085.2  269.74  5115.9  270.71  5213.7  278.34
  5250.1  279.88  5258.4  281.82  5264.0  280.87  5280.8  284.58  5317.1  287.87
#Mann=3,-1,0
  4591.2    0.12       0  4992.7    0.07       0  4998.7    0.12       0
Bank Sta=4992.7,4998.7
Exp/Cntr=0.3,0.1

Type RM Length L Ch R = 1,946,393,393,393
BEGIN DESCRIPTION:
UNT 125 IN CACR 2.0
END DESCRIPTION:
XS GIS Cut Line= 3
      3681249.61     10689210.19      3680649.61     10689510.19
      3680549.61     10690110.19
#Sta/Elev= 30
  4329.7  273.62  4338.1  271.86  4405.2  268.84  4441.5  267.90  4491.5  268.93
  4651.1  267.68  4656.7  269.26  4673.5  267.10  4753.1  267.51  4880.3  265.79
  4919.5  263.96  4941.8  264.76  4978.2  262.60  4992.1  263.40  5033.5  262.40
  5081.6  263.87  5094.3  262.47  5132.3  264.03  5152.1  261.25  5154.9  260.75
  5158.1  261.25  5183.0  264.14  5294.5  263.40  5355.4  265.64  5388.0  268.71
  5487.1  276.67  5515.0  280.64  5520.1  280.24  5527.7  282.01  5608.8  290.22
#Mann=6,-1,0
  4329.7    0.12       0  4491.5    0.16       0  4753.1    0.12       0
  5152.1    0.07       0  5158.1    0.12       0  5388.0    0.16       0
Bank Sta=5152.1,5158.1
Exp/Cntr=0.3,0.1

Type RM Length L Ch R = 1,553,0,0,0
BEGIN DESCRIPTION:
UNT 125 IN CACR 1.0
END DESCRIPTION:
XS GIS Cut Line= 3
      3681199.65     10689110.18      3680299.61     10689310.19
      3680454.82     10690361.19
#Sta/Elev= 30
  4039.9  268.94  4075.8  267.84  4292.2  264.00  4357.5  265.11  4470.8  263.65
  4573.9  263.98  4612.3  262.10  4661.0  262.73  4828.7  258.70  4859.5  260.13
  4879.9  258.60  4951.7  259.00  4979.1  256.93  4981.9  256.43  4985.1  256.93
  5002.3  258.71  5194.4  258.41  5334.6  261.27  5404.2  260.66  5426.9  262.07
  5473.8  259.92  5528.0  262.81  5581.8  268.70  5669.5  274.73  5724.5  280.84
  5871.7  296.33  5902.0  301.62  5932.3  303.16  5962.6  307.98  6024.3  313.61
#Mann=7,-1,0
  4039.9    0.12       0  4075.8    0.16       0  4470.8    0.12       0
  4979.1    0.07       0  4985.1    0.12       0  5581.8    0.16       0
  5724.5    0.12       0
Bank Sta=4979.1,4985.1
Exp/Cntr=0.3,0.1

Chan Stop Cuts=-1