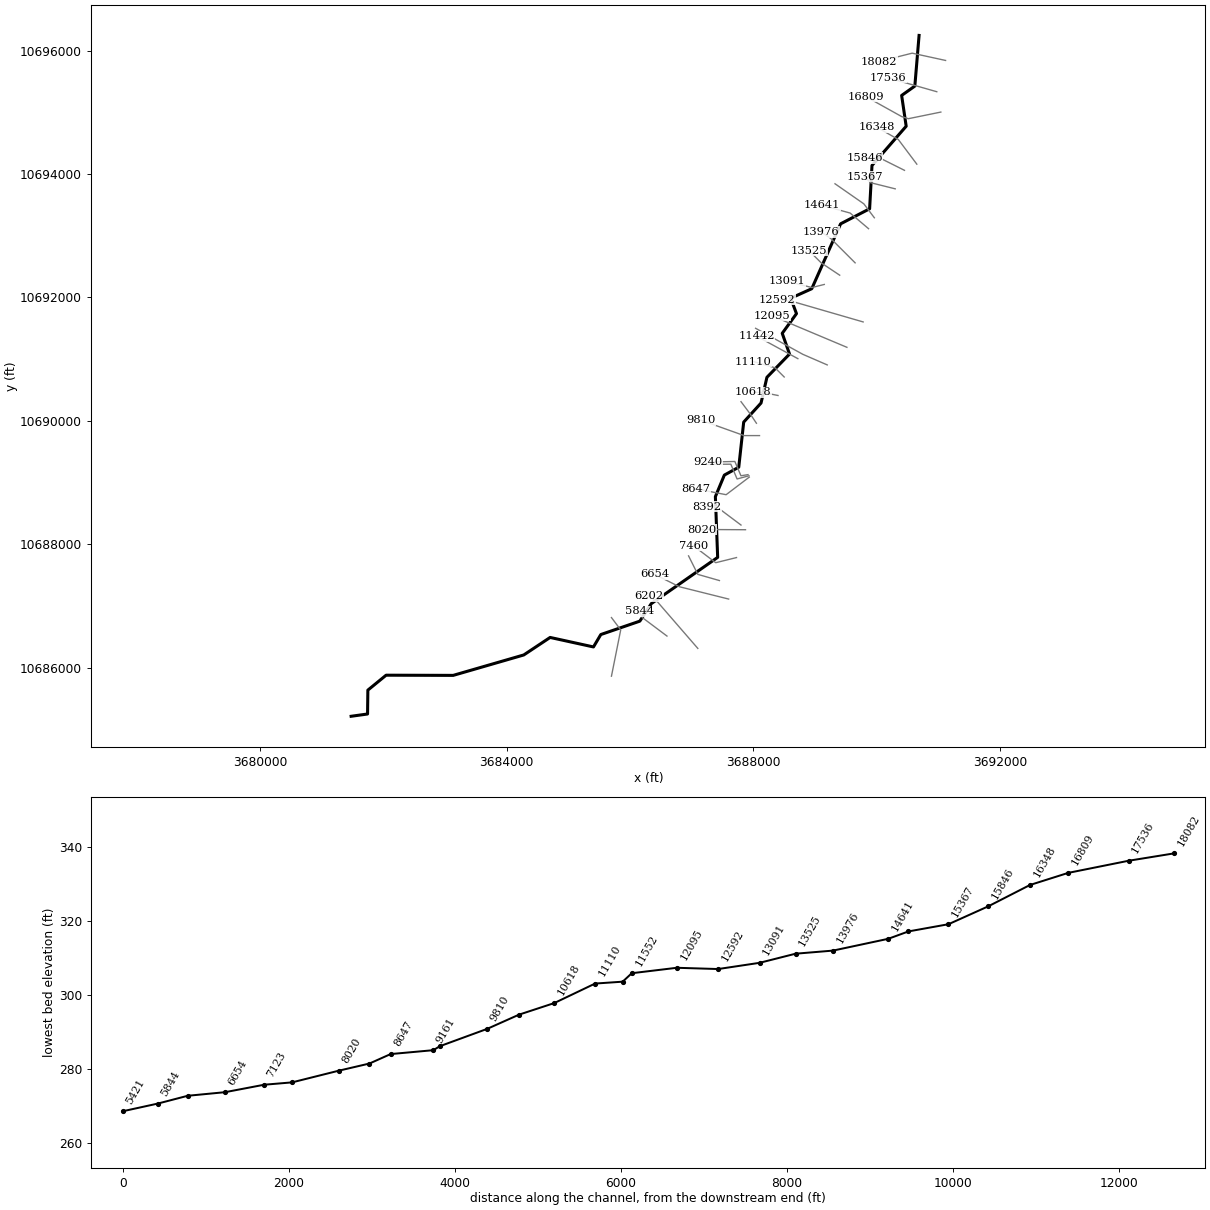
--- UNT 126 IN CACR.prj (project) ---

Proj Title=UNT 126 IN CACR Base Level Engineering
Current Plan=p01
Default Exp/Contr=0.3,0.1
English Units
Geom File=g01
Flow File=f01
Plan File=p01
Y Axis Title=Elevation
X Axis Title(PF)=Main Channel Distance
X Axis Title(XS)=Station
BEGIN DESCRIPTION:
UNT 126 IN CACR
END DESCRIPTION:
DSS Export Rating Curves= 0
DSS Export Rating Curve Sorted= 0
DSS Export Volume Flow Curves= 0
DXF OffsetX= 0
DXF OffsetY= 0
DXF ScaleX= 1
DXF ScaleY= 10

--- UNT 126 IN CACR.p01 (plan) ---

Plan Title=Multiple Run
Short Identifier=Multiple
Geom File=g01
Flow File=f01
Subcritical Flow
K Sum by GR= 0
Std Step Tol= 0.01
Critical Tol= 0.01
Num of Std Step Trials= 20
Max Error Tol= 0.3
Flow Tol Ratio= 0.001
Split Flow NTrial= 30
Split Flow Tol= 0.02
Split Flow Ratio= 0.02
Log Output Level= 0
Friction Slope Method= 1
Unsteady Friction Slope Method= 2
Unsteady Bridges Friction Slope Method= 1
Parabolic Critical Depth
Global Vel Dist=  1 , 1 , 1
Global Log Level= 0
CheckData=True
Encroach Param= -1, 0, 0, 0
BEGIN DESCRIPTION:
Multiple Run
END DESCRIPTION:

--- UNT 126 IN CACR.f01 (steady flow) ---

Flow Title=Multiple
Program Version=4.10
Number of Profiles= 7
Profile Names=10-year,25-year,50-year,1pct_min,100-year,1pct_plu,500-year
River Rch & RM=UNT 126 IN CACR,Reach-1         ,18082
     946    1322    1641    1495    2022    2734    3085
River Rch & RM=UNT 126 IN CACR,Reach-1         ,8392
    1737    2496    3158    2926    3957    5351    6245
River Rch & RM=UNT 126 IN CACR,Reach-1         ,8020
    1737    2496    3158    2926    3957    5351    6245
River Rch & RM=UNT 126 IN CACR,Reach-1         ,2650
    1798    2585    3270    3030    4098    5542    6468
Boundary for River Rch & Prof#=UNT 126 IN CACR,Reach-1         , 1
Up Type= 0
Dn Type= 3
Dn Slope=0.00155
Boundary for River Rch & Prof#=UNT 126 IN CACR,Reach-1         , 2
Up Type= 0
Dn Type= 3
Dn Slope=0.00155
Boundary for River Rch & Prof#=UNT 126 IN CACR,Reach-1         , 3
Up Type= 0
Dn Type= 3
Dn Slope=0.00155
Boundary for River Rch & Prof#=UNT 126 IN CACR,Reach-1         , 4
Up Type= 0
Dn Type= 3
Dn Slope=0.00155
Boundary for River Rch & Prof#=UNT 126 IN CACR,Reach-1         , 5
Up Type= 0
Dn Type= 3
Dn Slope=0.00155
Boundary for River Rch & Prof#=UNT 126 IN CACR,Reach-1         , 6
Up Type= 0
Dn Type= 3
Dn Slope=0.00155
Boundary for River Rch & Prof#=UNT 126 IN CACR,Reach-1         , 7
Up Type= 0
Dn Type= 3
Dn Slope=0.00155
DSS Import GetInterval= 0
DSS Import GetPeak= 0
DSS Import FillOption= 0

--- UNT 126 IN CACR.g01 (geometry) ---

Geom Title=Existing Conditions
Program Version=4.10

River Reach=UNT 126 IN CACR ,Reach-1
Reach XY= 30
      3690686.25       10696247.       3690617.5       10695426.
      3690403.75       10695274.      3690477.25       10694775.
        3689923.       10694139.       3689884.5       10693437.
       3689414.5       10693193.       3688946.5       10692141.
      3688605.25       10691987.        3688699.       10691737.
        3688468.       10691418.      3688586.25       10691082.
      3688219.75       10690705.       3688124.5       10690288.
      3687843.25       10689979.       3687763.1     10689247.79
      3687529.75       10689120.      3687384.25       10688770.
      3687421.25       10687786.      3686346.25       10687037.
        3686159.       10686752.        3685527.       10686535.
        3685408.       10686334.      3684705.25       10686488.
        3684278.       10686204.        3683134.       10685873.
       3682046.5       10685876.      3681750.75       10685634.
      3681745.75       10685247.       3681479.5       10685210.

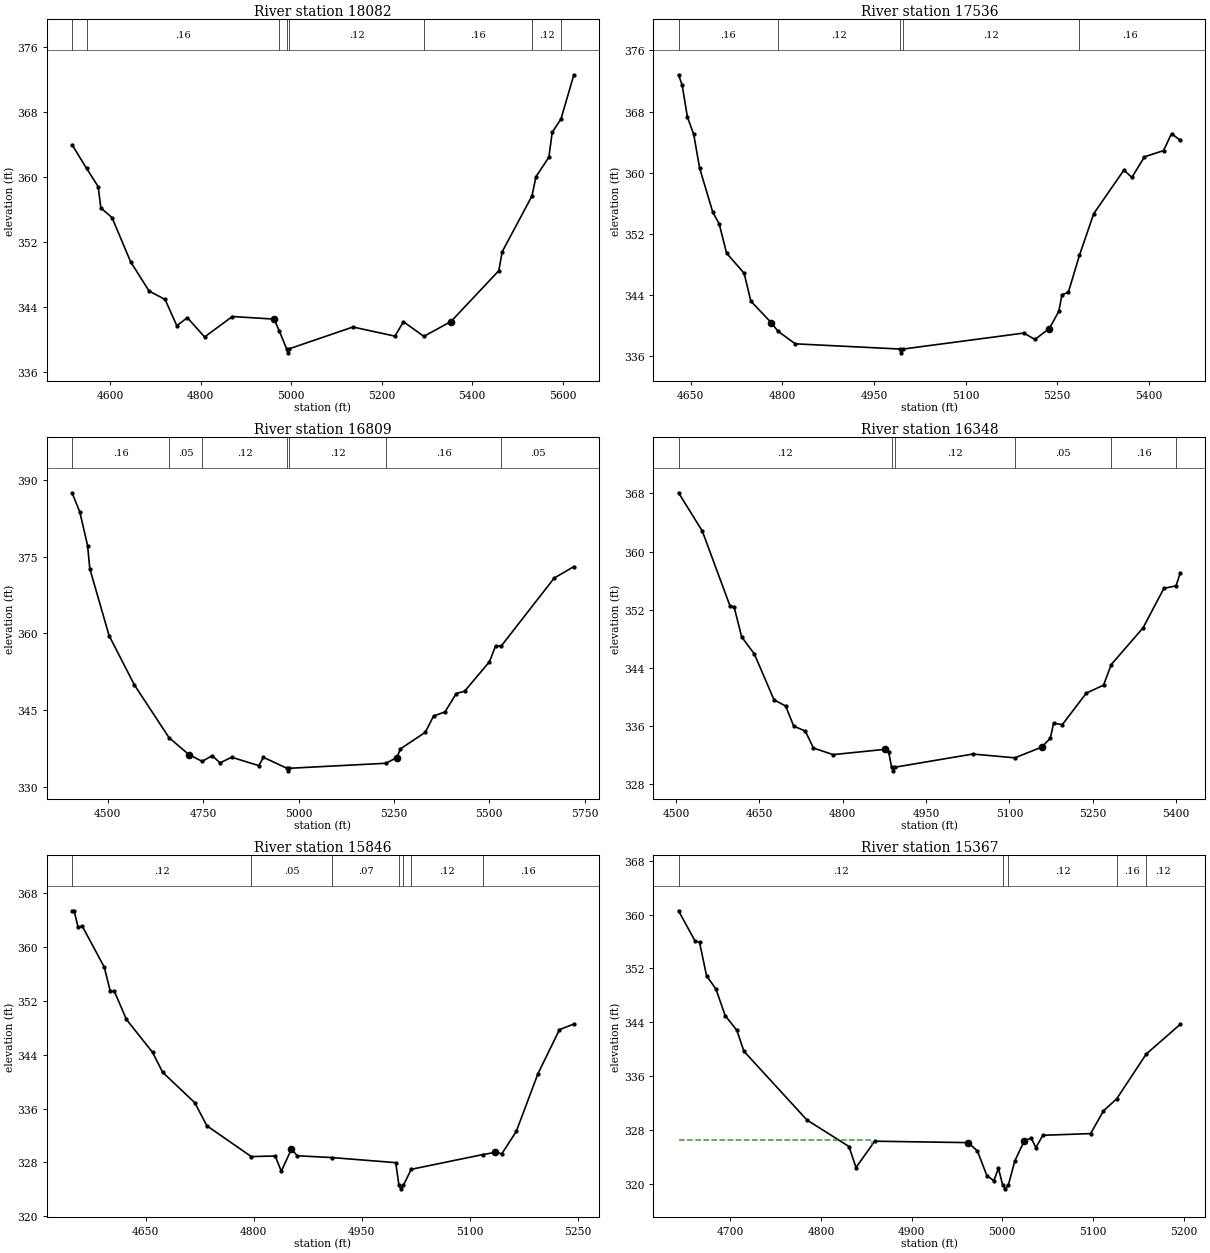
Type RM Length L Ch R = 1 ,18082   ,546,546,546
BEGIN DESCRIPTION:
UNT 126 IN CACR 35.0
END DESCRIPTION:
XS GIS Cut Line= 3
      3691115.92     10695841.44      3690574.22      10695959.5
      3690036.01     10695824.08
#Sta/Elev= 30
  4515.6  363.94  4547.6  361.04  4573.2  358.81  4579.3  356.18  4603.9     355
  4644.9  349.59  4685.8  345.98  4721.3  344.94  4747.2  341.72  4770.4  342.71
  4808.6  340.34    4870  342.85  4962.2  342.53    4974  341.05  4989.9  338.89
  4992.6  338.39  4995.9  338.89  5136.6  341.56  5229.4  340.44  5248.3  342.21
  5293.3  340.41  5353.2  342.23    5459  348.47  5466.6  350.81  5532.3  357.64
  5541.2  360.01  5569.7  362.41  5577.2  365.47  5596.5   367.1    5625  372.53
#Mann= 8 ,-1 , 0
  4515.6     .12       0  4547.6     .16       0    4974     .12       0
  4989.9     .07       0  4995.9     .12       0  5293.3     .16       0
  5532.3     .12       0  5596.5     .16       0
Bank Sta=4962.2,5353.2
XS Rating Curve= 0 ,0
Exp/Cntr=0.3,0.1

Type RM Length L Ch R = 1 ,17536   ,727,727,727
BEGIN DESCRIPTION:
UNT 126 IN CACR 34.0
END DESCRIPTION:
XS GIS Cut Line= 2
      3690973.52      10695334.5       3690183.2     10695559.81
#Sta/Elev= 30
  4629.8  372.81  4635.7  371.46  4644.3  367.29  4654.7     365  4664.3   360.6
  4685.9  354.81  4696.3  353.31  4708.5  349.45  4737.2  346.83  4748.2  343.17
  4781.4  340.37  4792.8  339.22    4821  337.58  4991.8   336.9  4994.6   336.4
  4997.8   336.9  5195.4  338.99  5213.4  338.15    5237  339.58  5252.5  341.82
  5257.8     344  5268.2  344.33  5286.3  349.15  5309.8  354.63  5359.2  360.33
  5372.2  359.36  5392.9  362.07  5424.1  362.88  5437.2  365.11  5451.6  364.22
#Mann= 5 ,-1 , 0
  4629.8     .16       0  4792.8     .12       0  4991.8     .07       0
  4997.8     .12       0  5286.3     .16       0
Bank Sta=4781.4,5237
XS Rating Curve= 0 ,0
Exp/Cntr=0.3,0.1

Type RM Length L Ch R = 1 ,16809   ,461,461,461
BEGIN DESCRIPTION:
UNT 126 IN CACR 33.0
END DESCRIPTION:
XS GIS Cut Line= 4
      3691039.45     10695004.63      3690511.72       10694897.
      3690404.08     10694931.72       3689824.4     10695254.54
#Sta/Elev= 30
  4406.3  387.49  4426.6  383.72    4447  377.16  4452.8  372.64  4503.3  359.57
  4569.4  349.95  4660.5   339.6  4712.3  336.31  4747.3  334.97  4773.6   336.1
    4794  334.67  4824.6  335.78    4896  334.13  4907.6  335.77  4969.5  333.62
  4972.2  333.12  4975.5  333.62  5228.8   334.6  5257.7  335.72    5267  337.42
  5332.2  340.66  5353.9  343.86  5383.6  344.62  5413.4  348.24  5435.1  348.69
  5500.3  354.45  5516.3  357.54  5531.2  357.53  5669.8   370.8  5721.5  373.06
#Mann= 7 ,-1 , 0
  4406.3     .16       0  4660.5     .05       0  4747.3     .12       0
  4969.5     .07       0  4975.5     .12       0  5228.8     .16       0
  5531.2     .05       0
Bank Sta=4712.3,5257.7
XS Rating Curve= 0 ,0
Exp/Cntr=0.3,0.1

Type RM Length L Ch R = 1 ,16348   ,502,502,502
BEGIN DESCRIPTION:
UNT 126 IN CACR 32.0
END DESCRIPTION:
XS GIS Cut Line= 3
      3690649.64     10694160.15      3690349.61     10694560.19
      3689999.58     10694760.21
#Sta/Elev= 30
  4504.5  368.09  4547.3  362.82  4597.3  352.49  4604.5   352.4  4618.1  348.27
    4641  345.91  4676.4   339.6  4697.3  338.76  4711.8  335.99  4732.7  335.31
  4747.3  332.98  4782.7  332.07  4876.4   332.8  4882.7  332.44    4888  330.34
  4890.8  329.84    4894  330.34  5034.1  332.15  5109.8  331.63  5157.9  333.09
  5173.7  334.31  5179.5  336.38  5195.3   336.2  5238.5  340.53  5269.5  341.63
  5283.4  344.46  5340.7  349.52  5378.1  354.94  5399.9  355.29  5407.7  357.08
#Mann= 6 ,-1 , 0
  4504.5     .12       0    4888     .07       0    4894     .12       0
  5109.8     .05       0  5283.4     .16       0  5399.9     .05       0
Bank Sta=4876.4,5157.9
XS Rating Curve= 0 ,0
Exp/Cntr=0.3,0.1

Type RM Length L Ch R = 1 ,15846   ,479,479,479
BEGIN DESCRIPTION:
UNT 126 IN CACR 31.0
END DESCRIPTION:
XS GIS Cut Line= 3
      3690449.62     10694060.18      3690049.61     10694260.19
      3689799.63     10694260.19
#Sta/Elev= 30
  4547.5  365.37  4550.3  365.37  4555.9  362.89  4561.5  363.12  4592.2  357.01
  4600.6  353.41  4606.2  353.43    4623  349.23  4659.3  344.35  4673.3  341.39
    4718  336.86  4734.8  333.44  4796.5  328.86  4829.8  328.95  4838.2  326.68
  4852.2  329.96  4860.6  328.98  4909.3  328.71  4997.2  327.96  5001.7  324.57
  5004.5  324.07  5007.7  324.57  5018.8  326.97  5117.8  329.15  5134.7  329.47
  5144.7  329.29  5164.7   332.6  5194.7  341.14  5224.7  347.72  5244.7  348.54
#Mann= 7 ,-1 , 0
  4547.5     .12       0  4796.5     .05       0  4909.3     .07       0
  5001.7     .07       0  5007.7     .07       0  5018.8     .12       0
  5117.8     .16       0
Bank Sta=4852.2,5134.7
XS Rating Curve= 0 ,0
Exp/Cntr=0.3,0.1

Type RM Length L Ch R = 1 ,15367   ,482,482,482
BEGIN DESCRIPTION:
UNT 126 IN CACR 30.0
END DESCRIPTION:
XS GIS Cut Line= 3
       3690299.6     10693760.19      3689899.61     10693860.19
      3689799.63     10693960.17
#Sta/Elev= 30
  4642.7  360.56  4660.7  356.12  4665.9  355.86  4673.6   350.9  4683.9  348.95
  4694.2  344.98  4707.1  342.78  4714.8  339.69  4784.4  329.46  4830.8  325.52
  4838.5   322.4  4859.2  326.31  4962.2   326.1  4972.5  324.86  4982.9  321.21
  4990.6  320.44  4995.7  322.28  5000.5  319.73  5003.2  319.23  5006.5  319.73
  5013.8  323.38  5024.1  326.33  5031.8   326.8    5037  325.35  5044.7  327.19
  5097.4  327.44  5111.6  330.82  5126.3  332.63  5158.7  339.25  5196.4   343.7
#Mann= 5 ,-1 , 0
  4642.7     .12       0  5000.5     .07       0  5006.5     .12       0
  5126.3     .16       0  5158.7     .12       0
#XS Ineff= 2 , 0
         4855.89  326.51
Permanent Ineff=
       F       F
Bank Sta=4962.2,5024.1
XS Rating Curve= 0 ,0
Exp/Cntr=0.3,0.1

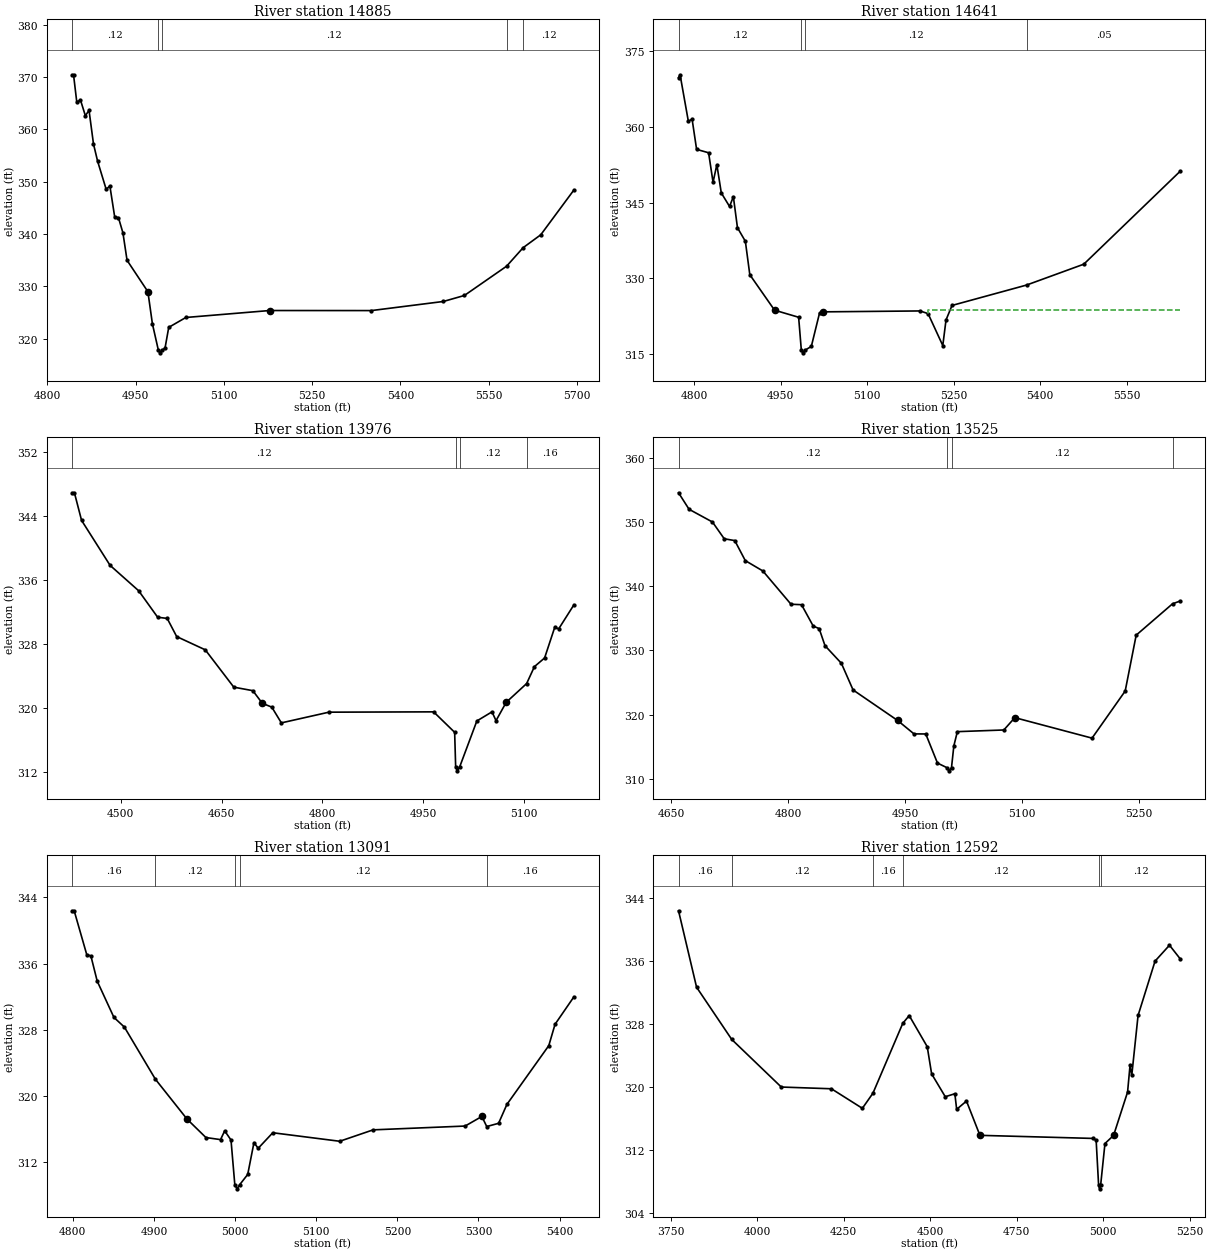
Type RM Length L Ch R = 1 ,14885   ,244,244,244
BEGIN DESCRIPTION:
UNT 126 IN CACR 29.0
END DESCRIPTION:
XS GIS Cut Line= 3
       3689961.2     10693291.16      3689791.06     10693516.85
      3689323.48     10693842.43
#Sta/Elev= 30
  4842.2  370.44  4844.7  370.44  4850.2  365.22  4856.5  365.61  4864.8  362.61
    4871  363.65  4878.6   357.2  4885.6  353.91  4900.2  348.52  4906.4  349.21
  4914.7  343.19    4921  343.12  4928.6  340.22  4935.6  334.97    4971  328.97
  4978.7  322.81  4988.8  317.78  4991.5  317.28  4994.8  317.78  5000.1  318.17
  5006.4  322.15  5035.5  324.04  5177.9  325.37  5350.7  325.36  5472.9   327.1
  5508.7  328.25  5580.3  333.84  5608.4  337.38  5638.4  339.85  5694.6   348.4
#Mann= 5 ,-1 , 0
  4842.2     .12       0  4988.8     .07       0  4994.8     .12       0
  5580.3     .16       0  5608.4     .12       0
Bank Sta=4971,5177.9
XS Rating Curve= 0 ,0
Exp/Cntr=0.3,0.1

Type RM Length L Ch R = 1 ,14641   ,665,665,665
BEGIN DESCRIPTION:
UNT 126 IN CACR 28.0
END DESCRIPTION:
XS GIS Cut Line= 3
      3689867.43     10693114.09      3689568.84     10693367.55
      3689108.48     10693495.62
#Sta/Elev= 30
  4773.2  369.75  4775.9   370.3  4790.2   361.1  4796.7  361.52  4804.5  355.54
  4825.3  354.87    4833  349.03  4839.6  352.52  4847.3  346.92  4861.6  344.24
  4868.2  346.18  4875.3  340.04    4889  337.35  4896.7  330.74  4939.6  323.72
  4981.3  322.32    4986  315.78  4988.7  315.28    4992  315.78  5003.3  316.55
  5017.6  323.19  5024.1  323.39  5191.7  323.57  5205.6  323.04  5231.1  316.72
  5236.7  321.79  5247.1  324.66  5376.2  328.69  5475.4  332.82  5642.7  351.24
#Mann= 4 ,-1 , 0
  4773.2     .12       0    4986     .07       0    4992     .12       0
  5376.2     .05       0
#XS Ineff= 2 , 0
                         5205.82          323.78
Permanent Ineff=
       F       F
Bank Sta=4939.6,5024.1
XS Rating Curve= 0 ,0
Exp/Cntr=0.3,0.1

Type RM Length L Ch R = 1 ,13976   ,451,451,451
BEGIN DESCRIPTION:
UNT 126 IN CACR 27.0
END DESCRIPTION:
XS GIS Cut Line= 3
      3689649.58     10692560.22      3689249.61     10692960.19
      3689099.63     10693060.18
#Sta/Elev= 30
  4427.8  346.88  4431.3  346.88  4441.9  343.43  4484.3   337.8  4526.8  334.62
    4555  331.31  4569.2  331.16  4583.3  328.89  4625.8  327.23  4668.2  322.56
  4696.5  322.12  4710.6  320.54  4724.7  320.06  4738.9  318.09  4809.6  319.43
  4965.2  319.47  4996.5  316.91    4998  312.59  5000.7  312.09    5004  312.59
  5029.5  318.33    5052  319.47    5058  318.37  5073.1  320.66  5103.5  323.01
  5115.1  325.13  5130.2  326.21  5145.2  330.03  5151.2  329.86  5173.7  332.85
#Mann= 4 ,-1 , 0
  4427.8     .12       0    4998     .07       0    5004     .12       0
  5103.5     .16       0
Bank Sta=4710.6,5073.1
XS Rating Curve= 0 ,0
Exp/Cntr=0.3,0.1

Type RM Length L Ch R = 1 ,13525   ,434,434,434
BEGIN DESCRIPTION:
UNT 126 IN CACR 26.0
END DESCRIPTION:
XS GIS Cut Line= 3
      3689399.59      10692360.2      3689099.61     10692560.19
      3688899.59     10692760.21
#Sta/Elev= 30
  4659.6  354.53  4673.1  351.96  4703.1  349.98  4718.2  347.37  4731.7  347.09
  4745.2  343.97  4767.7  342.36  4803.8  337.18  4817.3  337.11  4832.3  333.78
  4839.9  333.39  4847.4  330.73  4868.4  327.99  4883.4  323.84  4940.5  319.09
  4961.5     317  4976.6  316.99  4991.6  312.46  5003.6  311.75  5006.4  311.25
  5009.6  311.75  5012.6  315.13  5017.1  317.35  5076.7  317.61  5090.8  319.53
  5189.8  316.34  5232.3  323.67  5246.4  332.37    5293  337.25    5303  337.69
#Mann= 4 ,-1 , 0
  4659.6     .12       0  5003.6     .07       0  5009.6     .12       0
    5293     .16       0
Bank Sta=4940.5,5090.8
XS Rating Curve= 0 ,0
Exp/Cntr=0.3,0.1

Type RM Length L Ch R = 1 ,13091   ,499,499,499
BEGIN DESCRIPTION:
UNT 126 IN CACR 25.0
END DESCRIPTION:
XS GIS Cut Line= 3
      3689149.64      10692210.2      3688949.61     10692160.19
      3688549.61     10692260.19
#Sta/Elev= 30
  4799.1  342.39  4801.7  342.39  4817.2  337.09  4822.3  336.93  4830.1  333.88
  4850.7   329.5  4863.6  328.33  4901.8  322.03  4940.9   317.2  4964.1  314.98
  4982.1  314.73  4987.2  315.79    4995  314.68  4999.7  309.28  5002.5  308.78
  5005.7  309.28  5015.6  310.52  5023.3  314.37  5028.5  313.68  5046.5  315.56
    5129  314.53  5170.2  315.91  5283.6  316.37  5304.2  317.53  5310.2  316.31
  5324.8   316.7  5335.1  318.99  5386.7  326.09  5394.4  328.67  5417.6  331.98
#Mann= 5 ,-1 , 0
  4799.1     .16       0  4901.8     .12       0  4999.7     .07       0
  5005.7     .12       0  5310.2     .16       0
Bank Sta=4940.9,5304.2
XS Rating Curve= 0 ,0
Exp/Cntr=0.3,0.1

Type RM Length L Ch R = 1 ,12592   ,497,497,497
BEGIN DESCRIPTION:
Mapping XS 8b74d735
END DESCRIPTION:
XS GIS Cut Line= 3
      3689779.64     10691602.58      3688665.08     10691925.49
      3688378.62     10691964.55
#Sta/Elev= 30
  3773.1  342.39  3825.2  332.69  3926.8  326.06  4069.9  320.02  4214.7   319.8
  4304.1  317.32  4334.7  319.24  4420.8   328.1  4439.4  329.09  4491.5  325.14
  4504.2  321.69  4543.6  318.79  4571.3  319.17  4576.5  317.19  4604.9  318.24
  4643.7  313.89  4969.3   313.5  4979.4  313.29  4986.5   307.6  4989.2   307.1
  4992.5   307.6  5004.9  312.85  5029.8  313.88  5070.2  319.38  5077.3  322.77
  5082.3  321.49  5100.5   329.1  5149.6     336  5191.3  338.02  5222.6  336.27
#Mann= 6 ,-1 , 0
  3773.1     .16       0  3926.8     .12       0  4334.7     .16       0
  4420.8     .12       0  4986.5     .07       0  4992.5     .12       0
Bank Sta=4643.7,5029.8
XS Rating Curve= 0 ,0
Exp/Cntr=0.3,0.1

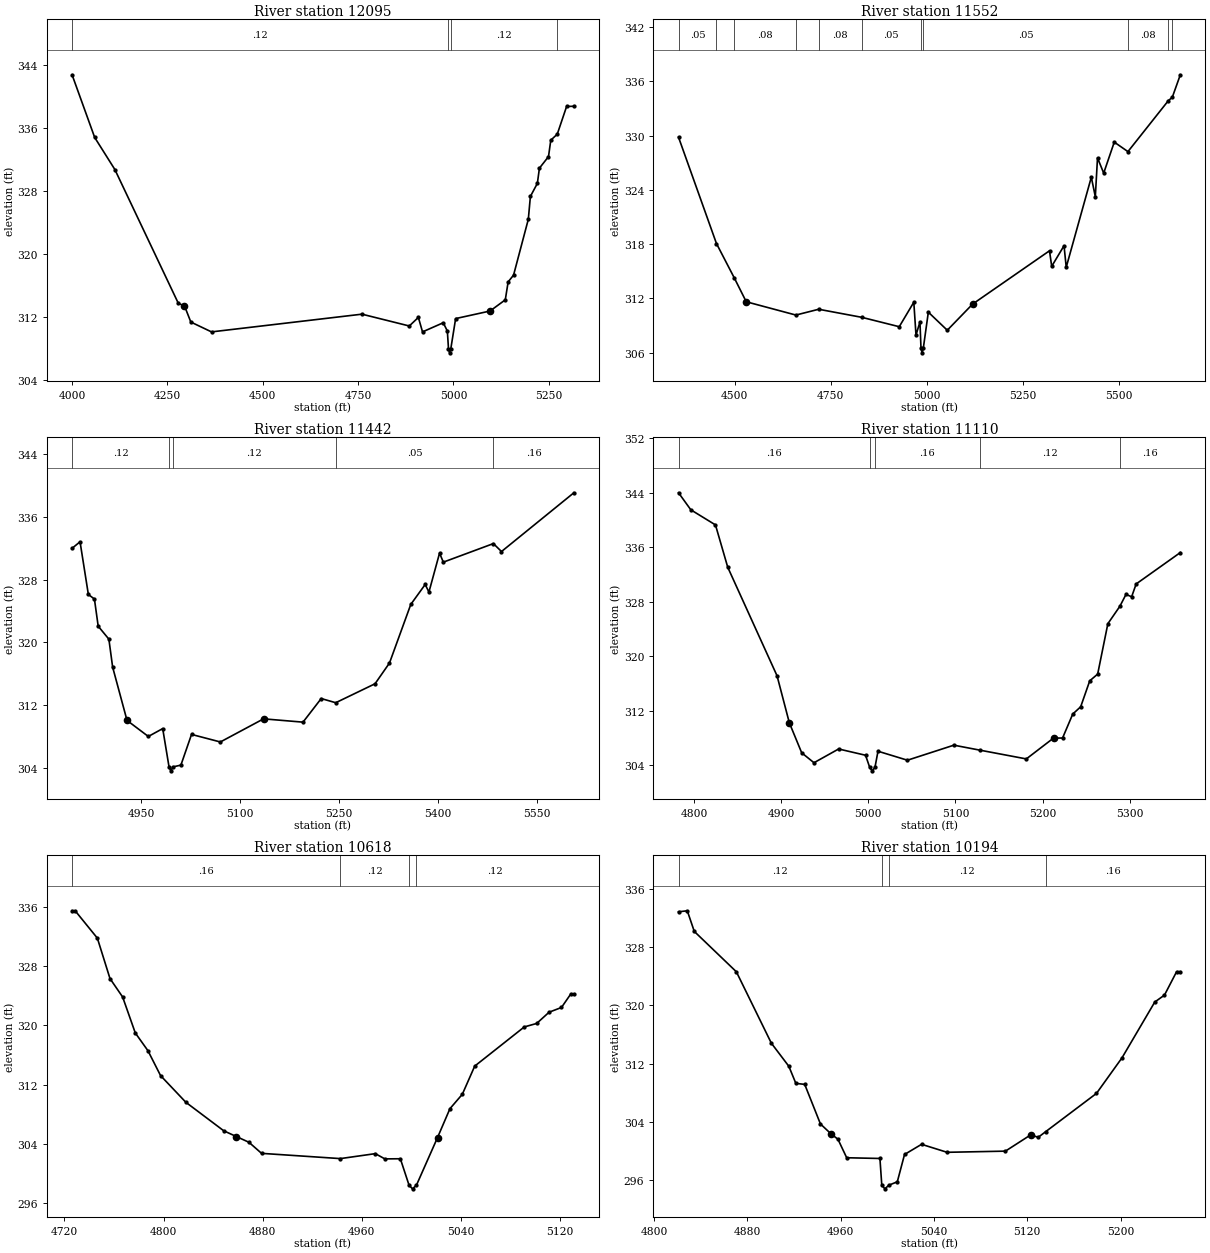
Type RM Length L Ch R = 1 ,12095   ,543,543,543
BEGIN DESCRIPTION:
Mapping XS 9bcc6160
END DESCRIPTION:
XS GIS Cut Line= 2
      3689516.65     10691191.11      3688303.85     10691701.21
#Sta/Elev= 30
  3999.9  342.75  4059.2  334.79  4112.1  330.72  4278.7  313.71  4294.6  313.41
  4311.3  311.35  4365.5   310.1    4760  312.35  4884.1  310.85  4907.9  311.94
  4918.8   310.1  4973.1  311.26  4983.9  310.21  4986.9  307.94  4989.7  307.44
  4992.9  307.94  5005.6  311.79  5095.8  312.75  5135.8  314.17  5143.3  316.45
  5157.5  317.31  5196.2   324.4  5201.6   327.3  5219.9  328.96  5225.3  330.89
  5249.1  332.36  5255.1  334.44  5272.1  335.21  5296.6  338.73  5315.6  338.75
#Mann= 4 ,-1 , 0
  3999.9     .12       0  4986.9     .07       0  4992.9     .12       0
  5272.1     .16       0
Bank Sta=4294.6,5095.8
XS Rating Curve= 0 ,0
Exp/Cntr=0.3,0.1

Type RM Length L Ch R = 1 ,11552   ,110,110,110
BEGIN DESCRIPTION:
UNT 126 IN CACR 24.0
END DESCRIPTION:
XS GIS Cut Line= 3
      3689197.85     10690905.71      3688802.05     10691077.57
      3688036.39     10691499.47
#Sta/Elev= 30
  4353.9  329.82  4452.6  318.06  4499.2  314.24  4530.1  311.62  4659.2  310.15
  4718.6  310.79  4830.6   309.9  4928.2  308.86  4966.1  311.57  4971.8  307.93
  4982.1  309.39  4984.8  306.47  4987.6  305.97  4990.8  306.47  5003.9  310.47
  5053.2  308.47  5119.3  311.37  5319.2  317.26  5324.9  315.54    5357  317.82
  5362.7  315.44    5428   325.4  5438.4  323.24  5444.1  327.54  5460.2  325.85
  5487.7  329.28  5523.3  328.23  5628.5  333.87  5638.7  334.24  5659.6  336.73
#Mann= 11 ,-1 , 0
  4353.9     .05       0  4452.6     .12       0  4499.2     .08       0
  4659.2     .05       0  4718.6     .08       0  4830.6     .05       0
  4984.8     .04       0  4990.8     .05       0  5523.3     .08       0
  5628.5     .16       0  5638.7     .05       0
Bank Sta=4530.1,5119.3
XS Rating Curve= 0 ,0
Exp/Cntr=0.3,0.1

Type RM Length L Ch R = 1 ,11442   ,332,332,332
BEGIN DESCRIPTION:
UNT 126 IN CACR 23.0
END DESCRIPTION:
XS GIS Cut Line= 2
      3688721.31     10691007.27       3688053.3     10691371.17
#Sta/Elev= 30
  4845.6  331.97  4857.7   332.8  4870.3   326.1  4879.5  325.52  4885.2  322.07
  4901.4  320.42  4907.1  316.87  4928.9  310.09  4961.2  308.05    4983  309.05
  4992.6  304.18  4995.3  303.68  4998.6  304.18  5010.6  304.41  5026.7  308.31
  5070.4  307.35  5135.9  310.29  5195.7  309.87  5223.3  312.87  5245.3  312.34
  5304.9  314.75  5326.8  317.39  5359.1  324.84  5380.9  327.37  5386.6  326.41
  5402.7  331.36  5408.4  330.21  5484.3  332.57  5496.6  331.56  5606.3  339.03
#Mann= 5 ,-1 , 0
  4845.6     .12       0  4992.6     .07       0  4998.6     .12       0
  5245.3     .05       0  5484.3     .16       0
Bank Sta=4928.9,5135.9
XS Rating Curve= 0 ,0
Exp/Cntr=0.3,0.1

Type RM Length L Ch R = 1 ,11110   ,492,492,492
BEGIN DESCRIPTION:
UNT 126 IN CACR 22.0
END DESCRIPTION:
XS GIS Cut Line= 3
      3688499.59     10690710.21      3688349.61     10690860.19
      3687999.62     10690960.19
#Sta/Elev= 30
  4782.1  344.01  4796.2  341.51  4824.5  339.29  4838.6  333.07  4895.2  317.13
  4909.3  310.23  4923.5  305.82  4937.6  304.36  4965.9  306.38  4996.8  305.46
  5001.6  303.67  5004.4  303.17  5007.6  303.67  5011.1  306.05  5044.9  304.73
  5098.2  306.94    5128  306.21  5181.4  304.92  5212.6  307.98    5223  307.99
  5234.7  311.51  5243.8  312.58  5254.2  316.39  5263.3  317.38    5275  324.78
  5288.8  327.34  5295.8  329.08  5302.3  328.74  5307.5  330.62  5358.2  335.23
#Mann= 5 ,-1 , 0
  4782.1     .16       0  5001.6     .07       0  5007.6     .16       0
    5128     .12       0  5288.8     .16       0
Bank Sta=4909.3,5212.6
XS Rating Curve= 0 ,0
Exp/Cntr=0.3,0.1

Type RM Length L Ch R = 1 ,10618   ,424,424,424
BEGIN DESCRIPTION:
UNT 126 IN CACR 21.0
END DESCRIPTION:
XS GIS Cut Line= 3
      3688399.59     10690410.19      3688149.61     10690460.19
      3687999.64     10690460.19
#Sta/Elev= 30
  4726.2   335.5  4728.7   335.5  4746.6   331.8  4756.8  326.33    4767  323.84
  4777.2  318.98  4787.4  316.58  4797.6  313.21    4818   309.6  4848.6  305.74
  4858.8  304.96  4868.9  304.19  4879.1  302.69  4942.7  301.98  4970.9  302.65
  4978.6  301.94  4991.1  301.96  4998.1  298.39  5000.9  297.89  5004.1  298.39
  5021.1  304.83  5031.1  308.73  5041.1  310.68  5051.1  314.49  5091.1  319.79
  5101.1  320.26  5111.1  321.78  5121.1  322.42  5128.6  324.24  5131.1  324.24
#Mann= 4 ,-1 , 0
  4726.2     .16       0  4942.7     .12       0  4998.1     .07       0
  5004.1     .12       0
Bank Sta=4858.8,5021.1
XS Rating Curve= 0 ,0
Exp/Cntr=0.3,0.1

Type RM Length L Ch R = 1 ,10194   ,384,384,384
BEGIN DESCRIPTION:
UNT 126 IN CACR 20.0
END DESCRIPTION:
XS GIS Cut Line= 3
       3688049.6      10689960.2      3687949.61     10690110.19
      3687799.59     10690310.22
#Sta/Elev= 30
    4821   332.9  4828.5  333.04  4834.5   330.2  4870.6  324.64  4900.6  314.81
  4915.6  311.63  4921.6  309.28  4929.2  309.14  4942.7  303.69  4951.7  302.34
  4957.7  301.59  4965.2  299.04  4993.7  298.94  4995.3  295.26    4998  294.76
  5001.3  295.26  5008.6  295.73  5014.8  299.49  5029.4  300.89  5051.3  299.79
  5101.3  299.95  5123.1   302.2  5129.4  301.85    5136  302.65  5179.4   307.9
  5201.3   312.8  5229.4  320.48  5237.7  321.43  5248.1  324.65  5251.3  324.65
#Mann= 4 ,-1 , 0
    4821     .12       0  4995.3     .07       0  5001.3     .12       0
    5136     .16       0
Bank Sta=4951.7,5123.1
XS Rating Curve= 0 ,0
Exp/Cntr=0.3,0.1

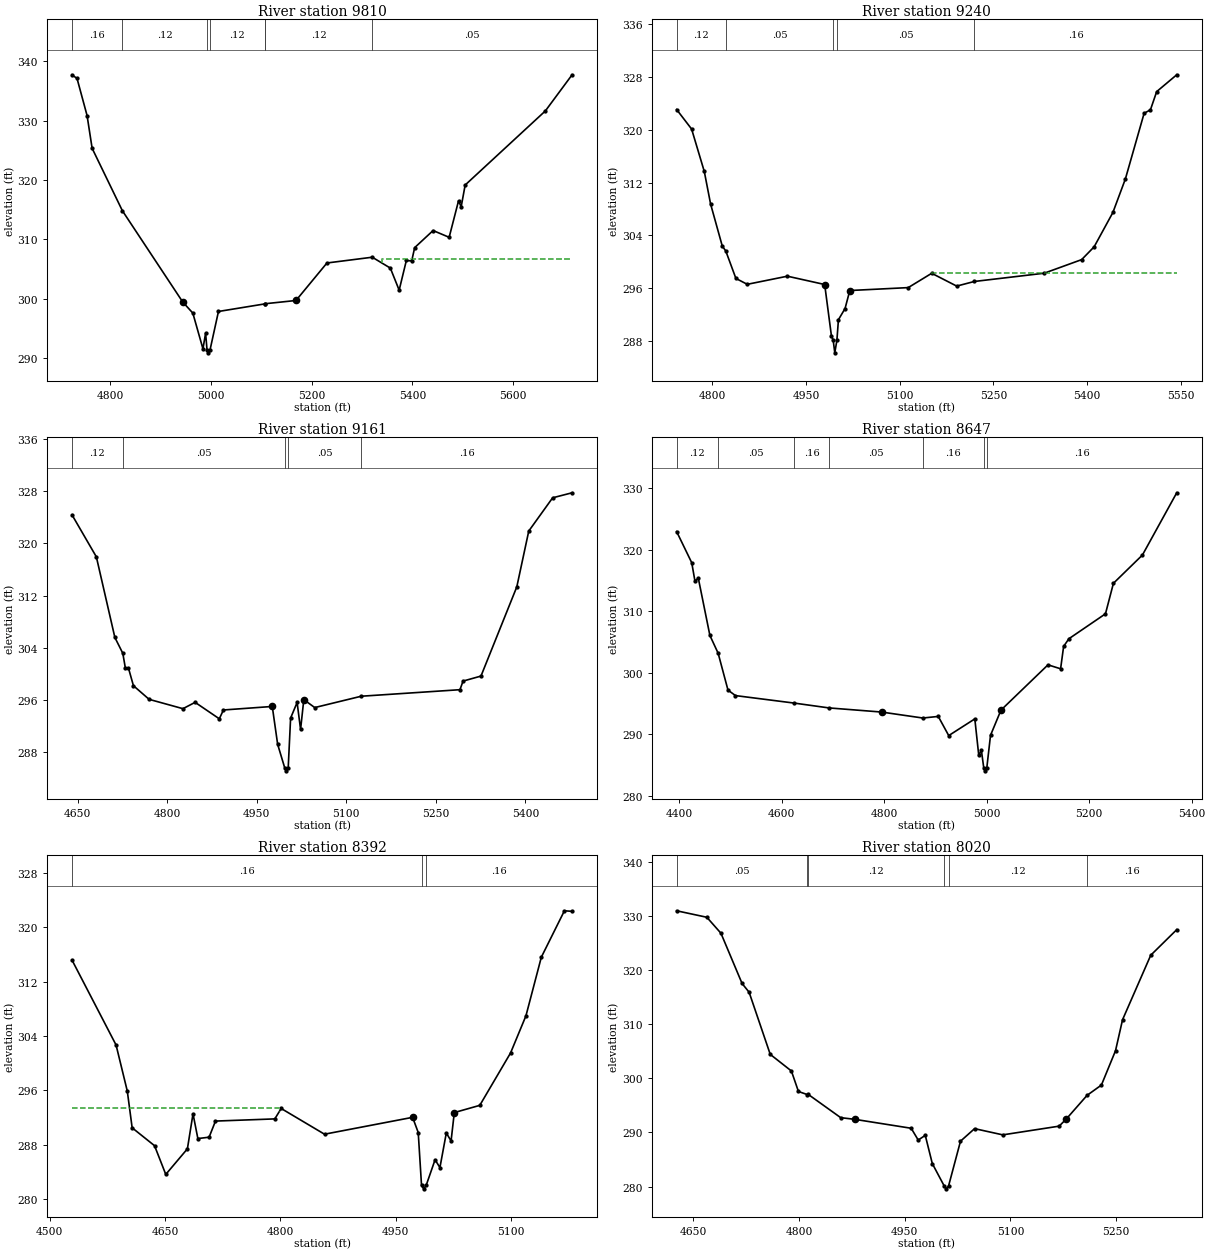
Type RM Length L Ch R = 1 ,9810    ,570,570,570
BEGIN DESCRIPTION:
UNT 126 IN CACR 19.0
END DESCRIPTION:
XS GIS Cut Line= 3
      3688099.61     10689760.19      3687849.61     10689760.19
      3687149.61     10690010.19
#Sta/Elev= 30
  4723.7  337.68  4733.7  337.09  4753.7  330.83  4763.7  325.33  4823.8  314.82
  4943.7  299.46  4963.7   297.6  4983.8  291.59  4989.1  294.23  4991.9  291.41
  4994.7  290.91  4997.9  291.41  5014.6  297.87  5106.3  299.14  5106.9  299.17
  5168.6  299.72  5230.1  306.03  5320.1     307    5356  305.17  5373.5  301.46
  5387.8  306.45  5398.4  306.37  5404.3  308.61  5440.9  311.49  5472.8  310.35
  5491.4  316.48  5496.7   315.5  5504.6  319.15  5663.9  331.62    5717   337.7
#Mann= 7 ,-1 , 0
  4723.7     .16       0  4823.8     .12       0  4991.9     .07       0
  4997.9     .12       0  5106.3     .16       0  5106.9     .12       0
  5320.1     .05       0
#XS Ineff= 2 , 0
                         5340.21          306.76
Permanent Ineff=
       F       F
Bank Sta=4943.7,5168.6
XS Rating Curve= 0 ,0
Exp/Cntr=0.3,0.1

Type RM Length L Ch R = 1 ,9240    ,79,79,79
BEGIN DESCRIPTION:
UNT 126 IN CACR 18.0
END DESCRIPTION:
XS GIS Cut Line= 4
      3687913.35     10689127.23      3687798.73       10689109.
      3687699.77     10689340.77      3687267.47     10689330.35
#Sta/Elev= 30
  4742.8  323.08  4766.8  320.12  4787.1  313.69  4797.2  308.76  4815.9  302.39
  4821.5  301.65  4837.7  297.49  4855.9   296.6  4920.1  297.83  4979.8  296.57
  4990.6  288.78  4993.4  288.15 4995.97  286.22  4999.4  288.15  5001.8  291.24
  5012.4  292.93    5020  295.66  5113.5   296.1  5151.1  298.27  5191.1  296.33
  5219.3  297.03  5331.1  298.28  5391.1  300.34  5411.1  302.28  5441.1  307.48
  5461.1  312.56  5491.1  322.51  5501.2  323.03  5511.2  325.79  5543.3  328.34
#Mann= 5 ,-1 , 0
  4742.8     .12       0  4821.5     .05       0  4993.4     .04       0
  4999.4     .05       0  5219.3     .16       0
#XS Ineff= 2 , 0
                         5150.71          298.32
Permanent Ineff=
       F       F
Bank Sta=4979.8,5020
XS Rating Curve= 0 ,0
Exp/Cntr=0.3,0.1

Type RM Length L Ch R = 1 ,9161    ,514,514,514
BEGIN DESCRIPTION:
Mapping XS f194b56a
END DESCRIPTION:
XS GIS Cut Line= 4
      3687928.97       10689109.      3687736.23     10689056.91
      3687634.66      10689296.5      3687257.05     10689293.89
#Sta/Elev= 30
  4640.6  324.39  4681.4  317.95  4712.4  305.59  4725.7  303.16  4729.9  300.95
  4735.1  300.92  4743.5  298.19  4769.8   296.1  4826.4  294.67  4846.8  295.64
  4887.3  293.12  4894.2  294.47    4976  295.01    4985  289.21  4996.7  285.64
  4999.5  285.14  5002.7  285.64  5006.7  293.23  5017.6  295.62  5023.4  291.48
  5028.8  296.06  5047.1  294.84  5125.1  296.58  5290.3  297.58  5295.5   298.9
  5325.5  299.67  5385.5  313.35  5405.5   321.9  5445.5     327  5478.1  327.77
#Mann= 5 ,-1 , 0
  4640.6     .12       0  4725.7     .05       0  4996.7     .04       0
  5002.7     .05       0  5125.1     .16       0
Bank Sta=4976,5028.8
XS Rating Curve= 0 ,0
Exp/Cntr=0.3,0.1

Type RM Length L Ch R = 1 ,8647    ,255,255,255
BEGIN DESCRIPTION:
UNT 126 IN CACR 17.0
END DESCRIPTION:
XS GIS Cut Line= 3
      3687933.31     10689086.67      3687558.28     10688801.92
      3687063.16     10688898.87
#Sta/Elev= 30
  4395.4  322.92  4424.9  317.86  4431.2  314.86  4437.7  315.36  4460.3  306.06
  4476.4  303.17  4495.6  297.19  4510.2   296.3  4625.1  295.08  4692.5   294.3
  4795.1  293.63  4875.6  292.66  4905.7  292.92  4926.1  289.81    4977  292.52
  4984.7  286.59  4989.8  287.42  4994.4  284.59  4997.1  284.09  5000.4  284.59
  5007.6  289.85    5028  293.94  5119.7  301.29  5144.3  300.65  5150.2  304.28
  5160.4  305.52  5231.8  309.57  5247.3  314.52  5303.9  319.11  5370.8  329.21
#Mann= 7 ,-1 , 0
  4395.4     .12       0  4476.4     .05       0  4625.1     .16       0
  4692.5     .05       0  4875.6     .16       0  4994.4     .07       0
  5000.4     .16       0
Bank Sta=4795.1,5028
XS Rating Curve= 0 ,0
Exp/Cntr=0.3,0.1

Type RM Length L Ch R = 1 ,8392    ,372,372,372
BEGIN DESCRIPTION:
UNT 126 IN CACR 16.0
END DESCRIPTION:
XS GIS Cut Line= 3
      3687799.64     10688310.16      3687399.61     10688610.19
      3687249.65     10688610.19
#Sta/Elev= 30
  4529.1  315.16  4586.4  302.67    4601  295.89  4607.3   290.5  4636.4  287.87
    4651  283.65  4679.1  287.41  4686.4  292.56  4692.7  288.92  4707.3  289.12
  4715.6  291.49  4792.7  291.81    4801  293.34  4857.3  289.56  4971.8  292.04
  4979.1  289.81  4983.4  282.03  4986.2  281.53  4989.4  282.03    5001  285.81
  5007.3  284.65  5015.6  289.74  5021.8  288.57    5026  292.74  5059.1   293.8
  5099.1   301.5  5119.1  306.96  5139.1  315.58  5169.1   322.4  5179.1  322.32
#Mann= 3 ,-1 , 0
  4529.1     .16       0  4983.4     .07       0  4989.4     .16       0
#XS Ineff= 2 , 0
         4798.11  293.48
Permanent Ineff=
       F       F
Bank Sta=4971.8,5026
XS Rating Curve= 0 ,0
Exp/Cntr=0.3,0.1

Type RM Length L Ch R = 1 ,8020    ,560,560,560
BEGIN DESCRIPTION:
UNT 126 IN CACR 15.0
END DESCRIPTION:
XS GIS Cut Line= 2
      3687872.49     10688234.21       3687162.7     10688237.68
#Sta/Elev= 30
  4626.2  330.99  4669.1  329.79  4689.1  326.84  4719.1  317.55  4729.1  315.93
  4759.1  304.44  4789.1  301.37  4799.1  297.58  4811.4  297.02    4813  297.04
  4859.1  292.74  4879.1  292.43  4959.1  290.78  4969.1   288.6  4979.1  289.47
  4989.1  284.25  5006.1  280.08  5008.8  279.58  5012.1  280.08  5029.1  288.39
  5049.1  290.71  5089.1  289.56  5169.1  291.17  5179.1  292.47  5208.7  296.86
  5229.1  298.77  5249.1  305.11  5259.1  310.85  5299.1  322.77    5336   327.5
#Mann= 6 ,-1 , 0
  4626.2     .05       0  4811.4     .16       0    4813     .12       0
  5006.1     .07       0  5012.1     .12       0  5208.7     .16       0
Bank Sta=4879.1,5179.1
XS Rating Curve= 0 ,0
Exp/Cntr=0.3,0.1

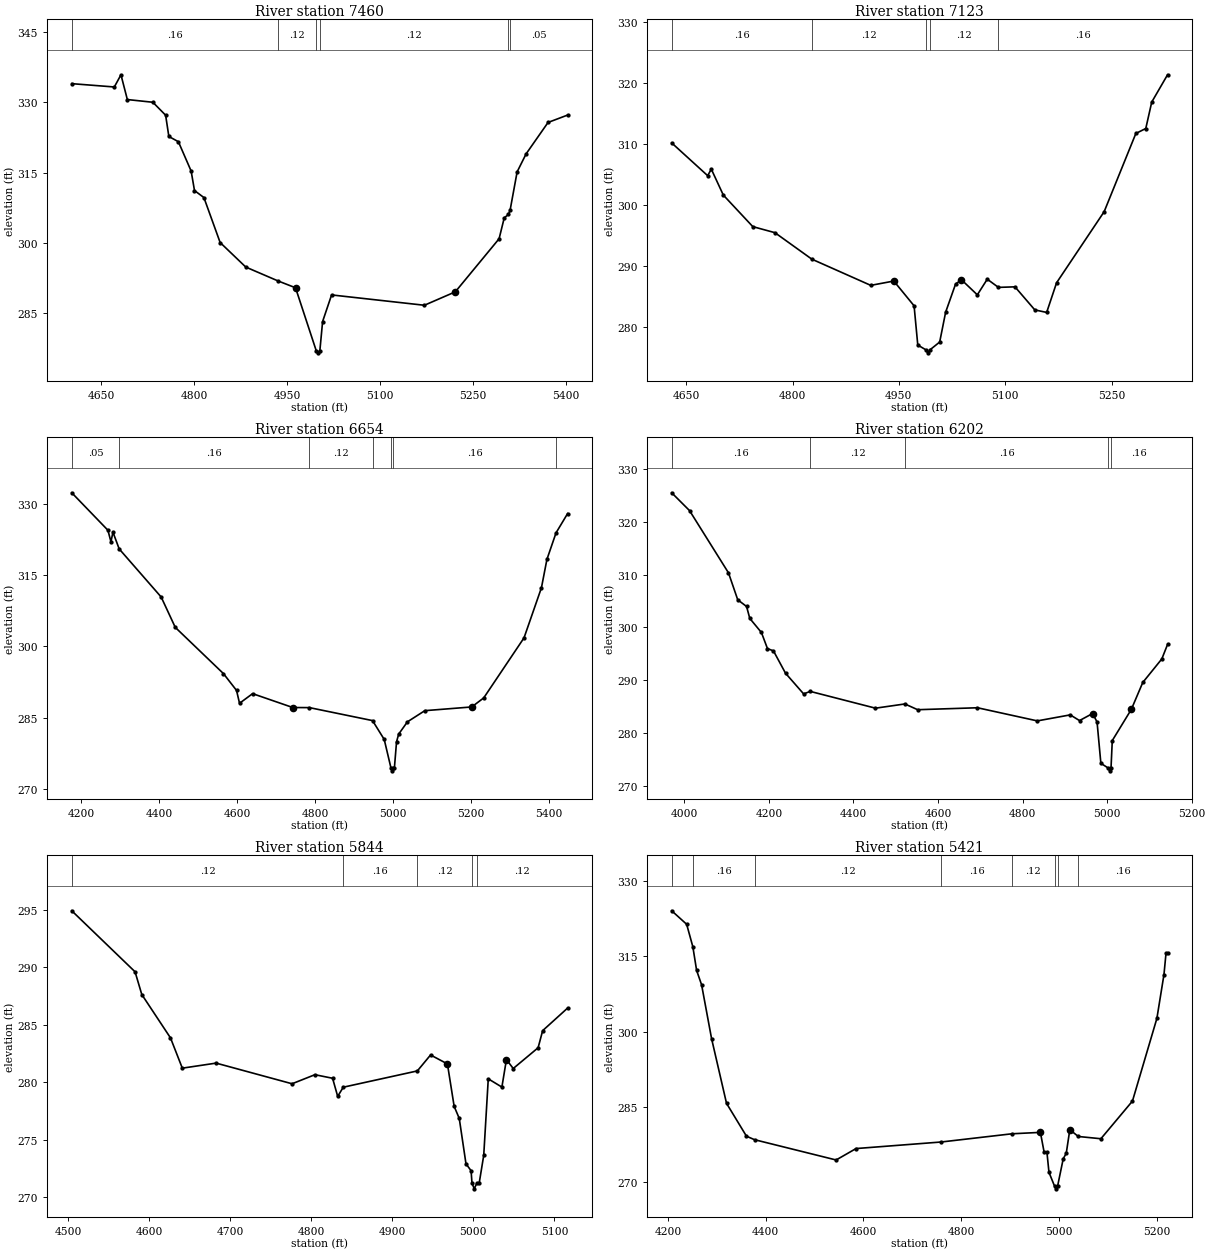
Type RM Length L Ch R = 1 ,7460    ,337,337,337
BEGIN DESCRIPTION:
UNT 126 IN CACR 14.0
END DESCRIPTION:
XS GIS Cut Line= 3
      3687726.66     10687782.82      3687389.87     10687699.49
      3687028.78     10687973.78
#Sta/Elev= 30
  4602.5  334.02  4671.2  333.31  4681.9  335.92  4692.2  330.62  4733.4  330.04
    4754  327.27  4759.2  322.72  4774.6   321.6  4795.2  315.32  4800.6  311.15
  4815.8  309.65    4842  300.03  4883.4  294.78  4935.5  291.81  4963.7  290.35
    4997  276.93  4999.8  276.43    5003  276.93  5007.4  283.13  5021.9  288.82
  5171.7  286.61  5221.6  289.48  5292.3  300.84  5300.6  305.32  5307.4  306.03
  5310.1  306.98  5321.4  315.15  5335.9     319  5371.3  325.72  5402.9   327.3
#Mann= 6 ,-1 , 0
  4602.5     .16       0  4935.5     .12       0    4997     .07       0
    5003     .12       0  5307.4     .16       0  5310.1     .05       0
Bank Sta=4963.7,5221.6
XS Rating Curve= 0 ,0
Exp/Cntr=0.3,0.1

Type RM Length L Ch R = 1 ,7123    ,469,469,469
BEGIN DESCRIPTION:
UNT 126 IN CACR 13.0
END DESCRIPTION:
XS GIS Cut Line= 3
      3687449.63     10687410.18      3687099.61     10687510.19
      3686949.62     10687810.16
#Sta/Elev= 30
  4629.6  310.17  4680.3  304.81  4685.5  305.87  4702.4  301.63    4744  296.46
  4775.2  295.47  4827.3  291.13  4910.4  286.84  4942.9  287.55  4971.5  283.49
  4976.7  277.07    4988  276.29  4990.8  275.79    4994  276.29  5007.6  277.56
    5016  282.45    5030  287.05  5038.3  287.76  5060.7  285.29  5074.7  287.85
  5090.5  286.51  5113.8   286.6  5141.8  282.82  5158.5  282.41  5172.5  287.27
  5239.6  298.91  5284.3  311.72  5298.3  312.53  5306.7  316.86    5329  321.33
#Mann= 5 ,-1 , 0
  4629.6     .16       0  4827.3     .12       0    4988     .07       0
    4994     .12       0  5090.5     .16       0
Bank Sta=4942.9,5038.3
XS Rating Curve= 0 ,0
Exp/Cntr=0.3,0.1

Type RM Length L Ch R = 1 ,6654    ,452,452,452
BEGIN DESCRIPTION:
UNT 126 IN CACR 12.0
END DESCRIPTION:
XS GIS Cut Line= 3
      3687599.56      10687110.2      3686799.61     10687310.19
       3686399.6     10687510.19
#Sta/Elev= 30
  4175.3  332.28    4268   324.4  4275.8  321.97  4280.9     324  4296.9  320.47
  4404.6  310.35  4440.7  303.97  4564.4  294.23  4597.9   290.7  4605.6  287.99
  4639.1  290.02  4742.2   287.1  4784.9  287.08  4946.7  284.35  4976.7  280.39
  4994.3  274.28    4997  273.78  5000.3  274.28  5002.7  274.28  5008.3  279.89
  5013.8  281.51  5036.2  284.09  5080.9  286.44  5201.1  287.22  5231.9  289.12
  5335.3  301.76    5380  312.31    5394  318.26  5417.4  323.85  5447.1  327.91
#Mann= 7 ,-1 , 0
  4175.3     .05       0  4296.9     .16       0  4784.9     .12       0
  4946.7     .16       0  4994.3     .07       0  5000.3     .16       0
  5417.4     .05       0
Bank Sta=4742.2,5201.1
XS Rating Curve= 0 ,0
Exp/Cntr=0.3,0.1

Type RM Length L Ch R = 1 ,6202    ,358,358,358
BEGIN DESCRIPTION:
UNT 126 IN CACR 11.0
END DESCRIPTION:
XS GIS Cut Line= 3
       3687099.6      10686310.2      3686449.61     10687060.19
      3686299.63     10687160.17
#Sta/Elev= 30
  3970.1  325.52  4012.3  322.14  4104.4  310.34  4126.3  305.23  4147.2  303.96
  4154.8   301.7  4182.3  299.03  4196.6  295.98  4210.8  295.54  4239.3  291.31
  4282.1  287.39  4297.8  287.86  4452.1  284.68  4521.6  285.48  4551.8  284.39
  4693.3  284.76  4834.8  282.27  4912.7  283.41  4934.6  282.33  4965.6  283.67
  4976.1  282.06  4985.1  274.23  5003.1   273.3  5005.9   272.8  5009.1   273.3
  5012.1  278.54  5057.2  284.46  5084.2  289.55  5129.3  294.02  5142.8  296.76
#Mann= 5 ,-1 , 0
  3970.1     .16       0  4297.8     .12       0  4521.6     .16       0
  5003.1     .07       0  5009.1     .16       0
Bank Sta=4965.6,5057.2
XS Rating Curve= 0 ,0
Exp/Cntr=0.3,0.1

Type RM Length L Ch R = 1 ,5844    ,423,423,423
BEGIN DESCRIPTION:
UNT 126 IN CACR 10.0
END DESCRIPTION:
XS GIS Cut Line= 3
      3686599.57     10686510.22      3686199.61     10686810.19
      3686149.59     10686910.23
#Sta/Elev= 30
  4504.5  294.94  4582.6  289.62  4590.9  287.64  4626.3  283.86  4640.9  281.22
  4682.6  281.66  4776.3  279.86  4804.5  280.65  4826.3  280.34  4832.6  278.76
  4839.5  279.56  4930.9  280.98  4947.2  282.37    4968  281.59  4976.3  277.89
  4982.6  276.84  4990.9  272.88  4997.2  272.28  4998.3   271.2  5001.1   270.7
  5004.3   271.2  5007.2   271.2  5012.8  273.62  5018.4  280.29  5035.2  279.57
  5040.8  281.97  5049.2  281.19  5079.9     283  5085.5  284.49  5116.3  286.46
#Mann= 5 ,-1 , 0
  4504.5     .12       0  4839.5     .16       0  4930.9     .12       0
  4998.3     .07       0  5004.3     .12       0
Bank Sta=4968,5040.8
XS Rating Curve= 0 ,0
Exp/Cntr=0.3,0.1

Type RM Length L Ch R = 1 ,5421    ,501,501,501
BEGIN DESCRIPTION:
UNT 126 IN CACR 9.0
END DESCRIPTION:
XS GIS Cut Line= 3
      3685699.61     10685860.21      3685849.61     10686610.19
      3685699.63     10686810.16
#Sta/Elev= 30
  4207.5  324.12  4238.1  321.43  4250.8  316.93  4258.5  312.22  4268.7  309.34
  4289.1  298.61  4319.7  285.69  4360.5  279.13    4377  278.43    4544  274.38
  4584.8  276.66  4759.1  277.97  4904.1  279.61  4962.1  279.89  4969.8  275.89
  4975.5  275.89  4979.6  271.93  4991.2  269.12    4994  268.62  4997.2  269.12
  5008.8  274.62    5015  275.72  5022.3  280.43  5039.6  279.07  5085.9  278.62
  5150.5  286.14  5200.5  302.64    5215   311.4  5219.2  315.68  5222.3  315.68
#Mann= 8 ,-1 , 0
  4207.5     .05       0  4250.8     .16       0    4377     .12       0
  4759.1     .16       0  4904.1     .12       0  4991.2     .07       0
  4997.2     .12       0  5039.6     .16       0
Bank Sta=4962.1,5022.3
XS Rating Curve= 0 ,0
Exp/Cntr=0.3,0.1