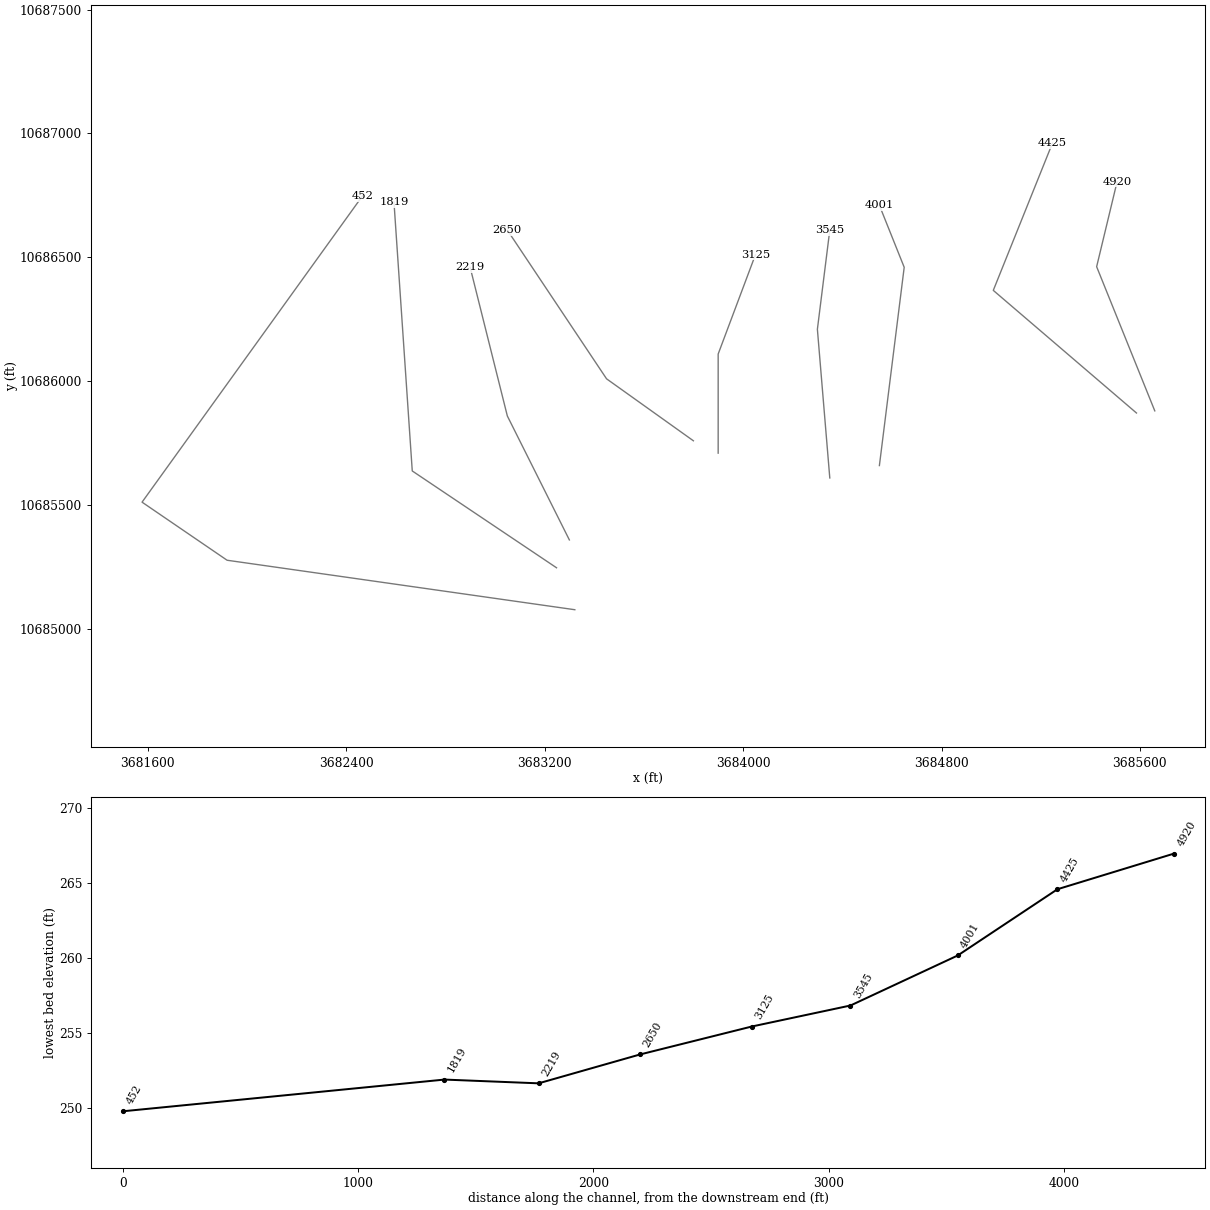
HEC-RAS study UNT 126 IN CACR.prj: UNT 126 IN CACR Base Level Engineering

--- UNT 126 IN CACR.g01 (geometry) --- (continued)

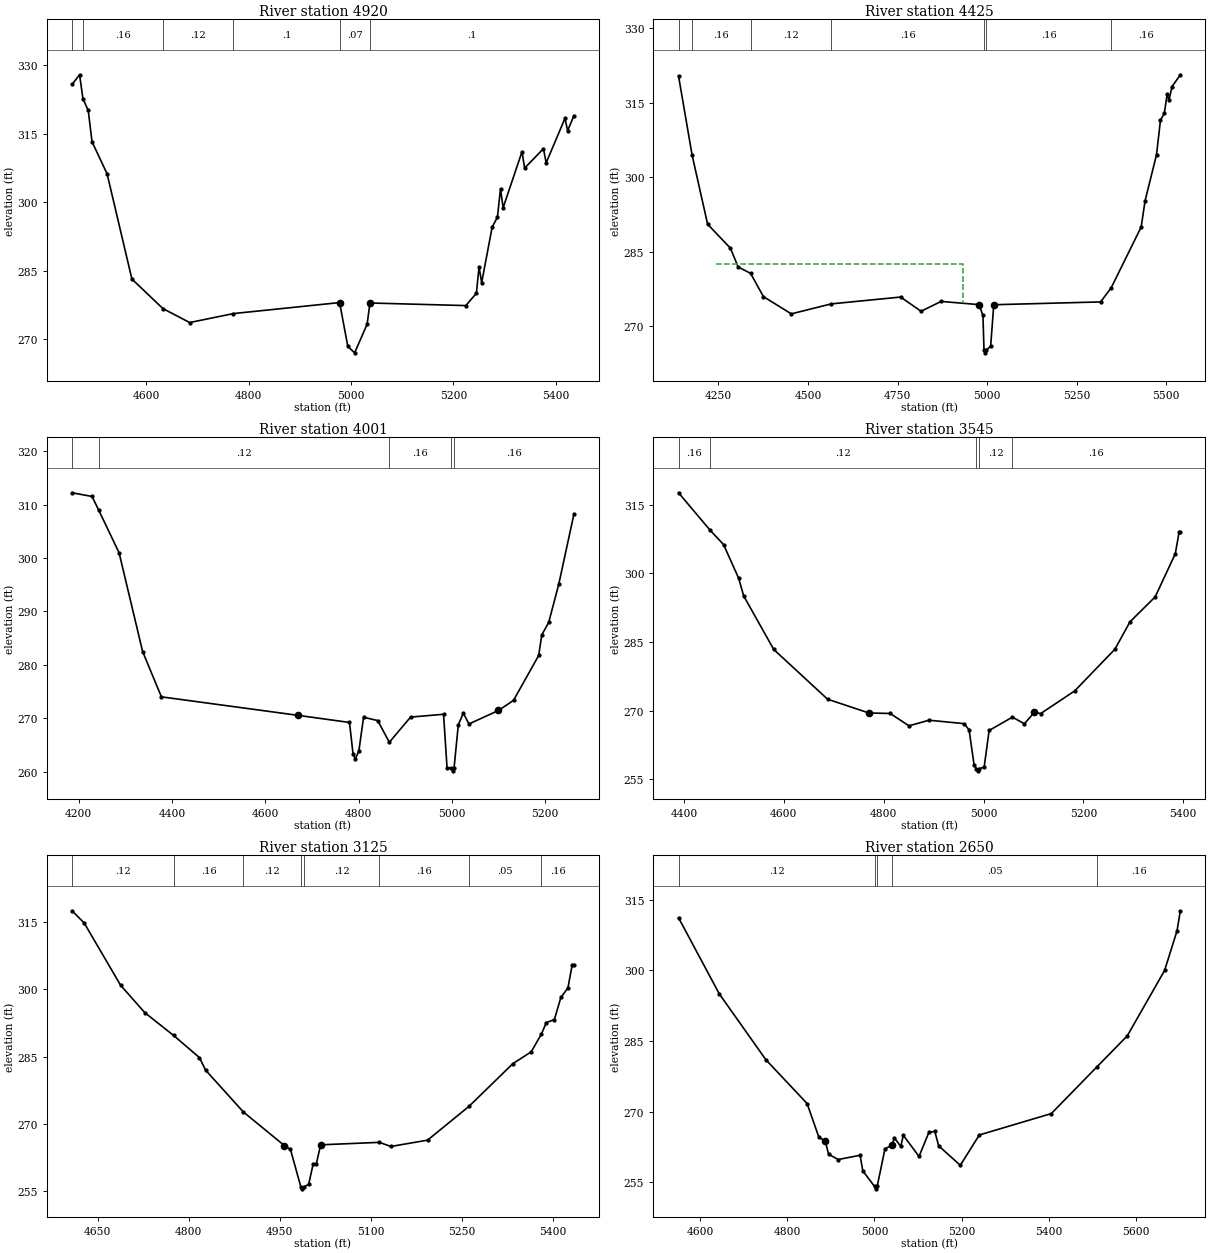
Type RM Length L Ch R = 1 ,4920    ,495,495,495
BEGIN DESCRIPTION:
UNT 126 IN CACR 8.0
END DESCRIPTION:
XS GIS Cut Line= 3
      3685659.86     10685880.87      3685425.46     10686462.51
      3685507.89     10686805.24
#Sta/Elev= 30
  4455.4  325.82  4470.1  327.93  4476.6  322.68    4487   320.1  4494.3  313.27
  4523.8   306.2  4572.2  283.14  4632.7  276.67    4685   273.6  4770.4  275.57
  4977.7  277.98  4993.7  268.37    5007  266.96  5031.4  273.23  5036.9  277.89
  5224.1  277.32  5244.7  280.02  5249.9   285.8    5255  282.35  5275.5  294.52
  5285.8  296.71  5291.8  302.91  5296.9  298.77  5333.8  311.08  5338.9  307.46
  5375.7  311.74  5380.9  308.62  5417.7  318.39  5422.8  315.66    5435  318.92
#Mann= 6 ,-1 , 0
  4455.4     .05       0  4476.6     .16       0  4632.7     .12       0
  4770.4      .1       0  4977.7     .07       0  5036.9      .1       0
Bank Sta=4977.7,5036.9
XS Rating Curve= 0 ,0
Exp/Cntr=0.3,0.1

Type RM Length L Ch R = 1 ,4425    ,424,424,424
BEGIN DESCRIPTION:
UNT 126 IN CACR 7.0
END DESCRIPTION:
XS GIS Cut Line= 3
      3685586.06     10685872.23       3685008.8     10686367.03
       3685247.5      10686961.6
#Sta/Elev= 30
  4138.6  320.41  4176.5  304.46  4219.8  290.52  4283.4   285.7  4305.1  281.91
  4339.8  280.61  4375.6  275.93  4453.5  272.45  4564.8  274.46  4758.7  275.84
  4815.7  272.97  4871.7  274.96  4977.7  274.31  4988.5  272.12  4991.5  265.09
  4994.2  264.59  4997.5  265.09  5010.1  265.95  5018.7  274.29  5317.1  274.86
  5346.7  277.72  5430.3  289.96  5441.1  295.23  5473.1  304.54  5484.2  311.51
    5495  312.89  5502.7  316.74  5508.1  315.56  5516.5  318.29  5539.6  320.66
#Mann= 7 ,-1 , 0
  4138.6     .12       0  4176.5     .16       0  4339.8     .12       0
  4564.8     .16       0  4991.5     .07       0  4997.5     .16       0
  5346.7     .16       0
#XS Ineff= 1 ,-1
 4242.73 4932.73   282.6
Permanent Ineff=
       F
Bank Sta=4977.7,5018.7
XS Rating Curve= 0 ,0
Exp/Cntr=0.3,0.1

Type RM Length L Ch R = 1 ,4001    ,456,456,456
BEGIN DESCRIPTION:
UNT 126 IN CACR 6.0
END DESCRIPTION:
XS GIS Cut Line= 3
      3684549.61     10685660.19      3684649.61     10686460.19
       3684549.6      10686710.2
#Sta/Elev= 30
    4186   312.2  4228.8  311.51  4242.9  308.99  4286.8  300.97  4337.2   282.5
  4377.5  274.02  4669.7  270.57  4780.6  269.23  4788.2  263.35  4793.2  262.39
  4800.8  263.97  4810.8  270.21  4841.1  269.58    4866  265.53  4911.6  270.24
  4982.2  270.76  4989.7  260.75  4998.7  260.68  5001.4  260.18  5004.7  260.68
  5013.8  268.76  5024.5  270.99  5036.7  268.95  5099.9  271.47  5132.2  273.37
  5186.1  281.76  5192.8  285.61  5207.6  287.95  5229.2  295.12  5261.5  308.15
#Mann= 5 ,-1 , 0
    4186     .16       0  4242.9     .12       0    4866     .16       0
  4998.7     .07       0  5004.7     .16       0
Bank Sta=4669.7,5099.9
XS Rating Curve= 0 ,0
Exp/Cntr=0.3,0.1

Type RM Length L Ch R = 1 ,3545    ,420,420,420
BEGIN DESCRIPTION:
UNT 126 IN CACR 5.0
END DESCRIPTION:
XS GIS Cut Line= 3
      3684349.61     10685610.18      3684299.61     10686210.19
      3684349.61     10686610.19
#Sta/Elev= 30
    4389  317.59  4452.6  309.37  4479.3  306.26  4509.4  298.92  4519.5  295.06
  4579.7  283.37  4687.5   272.5  4770.3  269.49    4813  269.38  4850.6  266.68
  4890.7  267.91    4961  267.16    4971   265.8  4981.1  258.13  4985.6  257.35
  4988.3  256.85  4991.6  257.35  5001.2  257.64  5011.2  265.67  5057.9  268.58
  5081.8  267.13  5101.9  269.65  5114.5  269.36  5182.6  274.31  5263.2  283.42
  5293.4  289.41  5343.8  294.85  5384.1  304.27  5391.7  308.96  5394.2  308.96
#Mann= 5 ,-1 , 0
    4389     .16       0  4452.6     .12       0  4985.6     .07       0
  4991.6     .12       0  5057.9     .16       0
Bank Sta=4770.3,5101.9
XS Rating Curve= 0 ,0
Exp/Cntr=0.3,0.1

Type RM Length L Ch R = 1 ,3125    ,475,475,475
BEGIN DESCRIPTION:
UNT 126 IN CACR 4.0
END DESCRIPTION:
XS GIS Cut Line= 3
      3683899.61     10685710.21      3683899.61     10686110.19
      3684049.62     10686510.21
#Sta/Elev= 30
  4607.6  317.54  4627.6  314.81  4687.6  300.91  4727.6  294.78  4774.9  289.71
  4817.6  284.75  4827.6  281.97  4890.1   272.6  4957.6  265.11  4967.6  264.26
  4984.6  255.95  4987.3  255.45  4990.6  255.95  4997.6  256.44  5005.1  261.04
  5010.2  261.04  5017.4  265.28  5114.2  265.83  5133.1  264.91  5193.6  266.32
  5262.1  273.89  5334.2   283.4  5364.5  286.04  5381.4  290.04  5389.4  292.57
  5402.7  293.25  5413.4   298.2    5425   300.3  5432.1  305.49  5434.8  305.49
#Mann= 8 ,-1 , 0
  4607.6     .12       0  4774.9     .16       0  4890.1     .12       0
  4984.6     .07       0  4990.6     .12       0  5114.2     .16       0
  5262.1     .05       0  5381.4     .16       0
Bank Sta=4957.6,5017.4
XS Rating Curve= 0 ,0
Exp/Cntr=0.3,0.1

Type RM Length L Ch R = 1 ,2650    ,431,431,431
BEGIN DESCRIPTION:
UNT 126 IN CACR 3.0
END DESCRIPTION:
XS GIS Cut Line= 3
      3683799.64     10685760.16      3683449.61     10686010.19
      3683049.59     10686610.21
#Sta/Elev= 30
  4550.6  311.19    4644  295.03    4751  281.02  4845.6  271.71  4872.6  264.55
  4887.4  263.74  4894.7  260.96  4916.9  259.82  4967.2  260.72  4973.4  257.41
  5000.3  254.09    5003  253.59  5006.3  254.09  5024.3  262.11  5041.3  262.88
  5045.4  264.48  5060.4   262.6  5066.4  264.96  5102.4  260.47    5125  265.59
  5138.5  265.81  5147.5  262.72  5197.1  258.59  5240.7  265.04  5405.9  269.58
  5511.3  279.58  5580.2   286.1  5665.8  299.99  5694.4  308.43  5701.9  312.67
#Mann= 5 ,-1 , 0
  4550.6     .12       0  5000.3     .07       0  5006.3     .12       0
  5041.3     .05       0  5511.3     .16       0
Bank Sta=4887.4,5041.3
XS Rating Curve= 0 ,0
Exp/Cntr=0.3,0.1

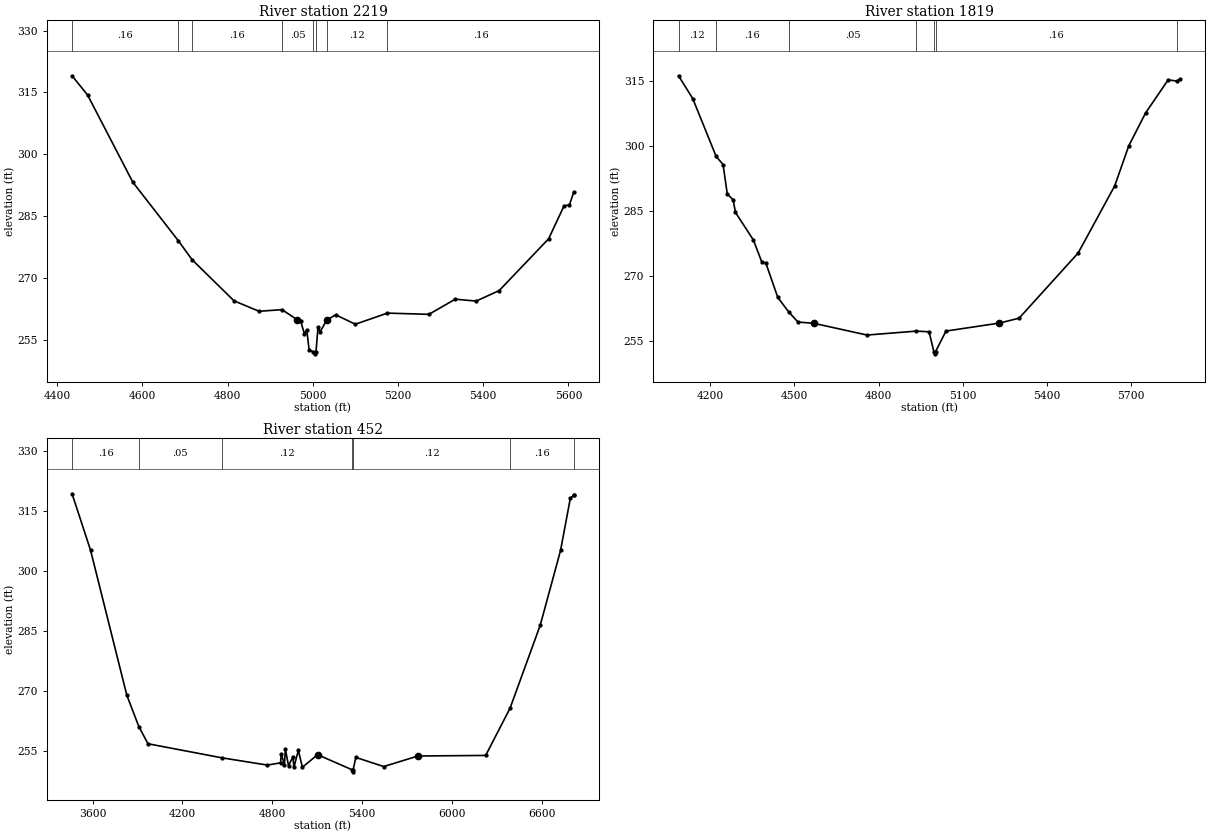
Type RM Length L Ch R = 1 ,2219    ,400,400,400
BEGIN DESCRIPTION:
UNT 126 IN CACR 2.0
END DESCRIPTION:
XS GIS Cut Line= 3
      3683299.63     10685360.15      3683049.61     10685860.19
      3682899.61     10686460.17
#Sta/Elev= 30
  4435.1  319.04  4471.5  314.38  4577.7  293.25  4684.8  279.03  4716.6  274.49
  4815.3   264.5    4874  261.98  4927.7  262.38  4963.4  259.93  4971.8  259.51
  4980.2  256.53  4985.8  257.47  4991.4  252.59  5001.5  252.17  5004.2  251.67
  5007.5  252.17  5012.2  258.06  5017.3  257.02  5032.4  259.79  5053.4  261.14
  5099.8  258.84    5175  261.54  5272.5  261.24  5334.3  264.91  5383.3  264.45
  5437.4     267  5553.4  279.55  5589.4  287.49  5602.3  287.79  5612.6  290.92
#Mann= 8 ,-1 , 0
  4435.1     .16       0  4684.8     .12       0  4716.6     .16       0
  4927.7     .05       0  5001.5     .04       0  5007.5     .05       0
  5032.4     .12       0    5175     .16       0
Bank Sta=4963.4,5032.4
XS Rating Curve= 0 ,0
Exp/Cntr=0.3,0.1

Type RM Length L Ch R = 1 ,1819    ,1367,1367,1367
BEGIN DESCRIPTION:
Mapping XS 81b7a548
END DESCRIPTION:
XS GIS Cut Line= 3
      3683247.89     10685247.76       3682666.3     10685638.38
      3682592.51     10686723.48
#Sta/Elev= 30
  4087.3  316.29    4138     311  4221.4  297.61    4246  295.75    4261  288.93
    4282  287.56    4290  284.68    4354  278.28    4384  273.18  4398.4  272.94
    4441  264.98  4479.8  261.63    4513  259.28    4570  258.98    4759  256.27
  4934.2  257.18  4980.1  257.03  4997.2  252.42  4999.9  251.92  5003.2  252.42
  5040.3  257.19  5230.7  259.04  5300.9  260.17  5511.4  275.26  5641.7  290.81
  5691.8  300.08  5751.9  307.71  5832.1  315.34  5863.6  315.06  5875.5  315.58
#Mann= 7 ,-1 , 0
  4087.3     .12       0  4221.4     .16       0  4479.8     .05       0
  4934.2     .16       0  4997.2     .07       0  5003.2     .16       0
  5863.6     .05       0
Bank Sta=4570,5230.7
XS Rating Curve= 0 ,0
Exp/Cntr=0.3,0.1

Type RM Length L Ch R = 1 ,452     ,0,0,0
BEGIN DESCRIPTION:
UNT 126 IN CACR 1.0
END DESCRIPTION:
XS GIS Cut Line= 4
      3683321.72     10685078.48      3681919.77     10685278.14
      3681576.89     10685512.51      3682465.62     10686748.06
#Sta/Elev= 30
  3462.4  319.32  3585.9  305.21  3828.2  268.97  3908.4  261.14  3969.6  256.83
  4461.5  253.33  4767.5   251.5  4855.5  252.06  4860.5  254.27  4881.6  251.64
  4887.9  255.47  4908.8  251.36  4938.7  253.55  4944.7  250.91  4974.6  255.17
  5001.6  250.95  5103.2   254.1  5334.7  250.31  5337.4  249.81  5340.7  250.31
  5358.6  253.42  5545.1  251.13  5773.5  253.77  6226.4  253.91  6389.1  265.69
    6591  286.45  6727.2   305.2  6792.3  318.22  6815.7  318.94  6815.8  318.93
#Mann= 7 ,-1 , 0
  3462.4     .16       0  3908.4     .05       0  4461.5     .12       0
  5334.7     .07       0  5340.7     .12       0  6389.1     .16       0
  6815.7     .05       0
Bank Sta=5103.2,5773.5
XS Rating Curve= 0 ,0
Exp/Cntr=0.3,0.1

Chan Stop Cuts=-1
Use User Specified Reach Order=0
Composite Channel Slope=5