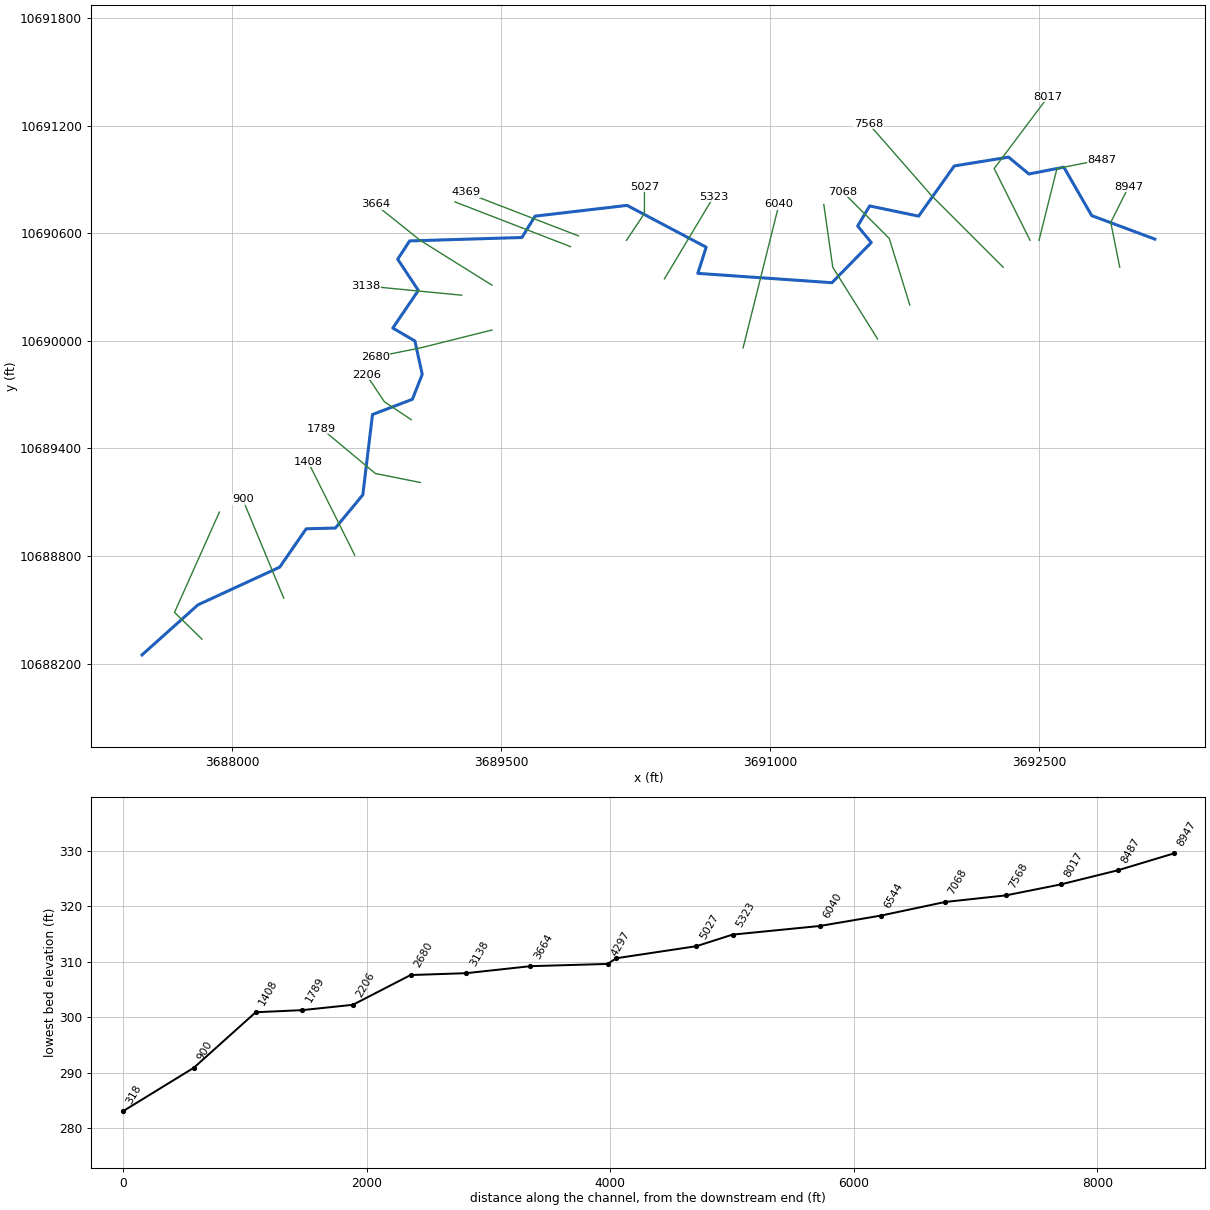
--- UNT 127 IN CACR.prj (project) ---

Proj Title=UNT 127 IN CACR Base Level Engineering
Current Plan=p01
Default Exp/Contr=0.3,0.1
English Units
Geom File=g01
Flow File=f01
Plan File=p01
BEGIN DESCRIPTION:
UNT 127 IN CACR
END DESCRIPTION:

--- UNT 127 IN CACR.p01 (plan) ---

Plan Title=Multiple Run
Short Identifier=Multiple
Geom File=g01
Flow File=f01
Subcritical Flow
K Sum by GR= 0
Std Step Tol= 0.01
Critical Tol= 0.01
Num of Std Step Trials= 20
Max Error Tol= 0.3
Flow Tol Ratio= 0.001
Split Flow NTrial= 30
Split Flow Tol= 0.02
Split Flow Ratio= 0.02
Log Output Level= 0
Friction Slope Method= 1
Unsteady Friction Slope Method= 2
Unsteady Bridges Friction Slope Method= 1
Parabolic Critical Depth
Global Vel Dist=  1 , 1 , 1
Global Log Level= 0
CheckData=True
Encroach Param= -1, 0, 0, 0
BEGIN DESCRIPTION:
Multiple Run
END DESCRIPTION:

--- UNT 127 IN CACR.f01 (steady flow) ---

Flow Title=Multiple
Number of Profiles=7
Profile Names=10-year,25-year,50-year,1pct_min,100-year,1pct_plu,500-year
River Rch & RM= UNT 127 IN CACR,Reach-1,8947
     551     750     916     822    1112    1503    1645
River Rch & RM= UNT 127 IN CACR,Reach-1,8487
     822    1136    1400    1267    1713    2317    2576
Boundary for River Rch & Prof#=UNT 127 IN CACR,Reach-1,1
Up Type=0
Dn Type=3
Dn Slope=0.005
Boundary for River Rch & Prof#=UNT 127 IN CACR,Reach-1,2
Up Type=0
Dn Type=3
Dn Slope=0.005
Boundary for River Rch & Prof#=UNT 127 IN CACR,Reach-1,3
Up Type=0
Dn Type=3
Dn Slope=0.005
Boundary for River Rch & Prof#=UNT 127 IN CACR,Reach-1,4
Up Type=0
Dn Type=3
Dn Slope=0.005
Boundary for River Rch & Prof#=UNT 127 IN CACR,Reach-1,5
Up Type=0
Dn Type=3
Dn Slope=0.005
Boundary for River Rch & Prof#=UNT 127 IN CACR,Reach-1,6
Up Type=0
Dn Type=3
Dn Slope=0.005
Boundary for River Rch & Prof#=UNT 127 IN CACR,Reach-1,7
Up Type=0
Dn Type=3
Dn Slope=0.005

--- UNT 127 IN CACR.g01 (geometry) ---

Geom Title=Existing Conditions

River Reach=UNT 127 IN CACR,Reach-1
Reach XY= 30
      3693144.96     10690567.09      3692793.25     10690698.00
      3692638.00     10690968.00      3692443.25     10690930.00
      3692330.00     10691024.00      3692027.25     10690975.00
      3691828.25     10690695.00      3691555.25     10690752.00
      3691488.50     10690640.00      3691564.50     10690548.00
      3691345.00     10690324.00      3690597.25     10690376.00
      3690644.00     10690522.00      3690202.75     10690755.00
      3689689.75     10690695.00      3689616.50     10690576.00
      3688990.75     10690557.00      3688924.00     10690455.00
      3689039.25     10690281.00      3688896.75     10690071.00
      3689020.00     10689999.00      3689060.75     10689813.00
      3689006.00     10689674.00      3688783.50     10689589.00
      3688729.50     10689141.00      3688576.50     10688956.00
      3688414.00     10688952.00      3688266.00     10688738.00
      3687810.50     10688528.00      3687498.75     10688249.00

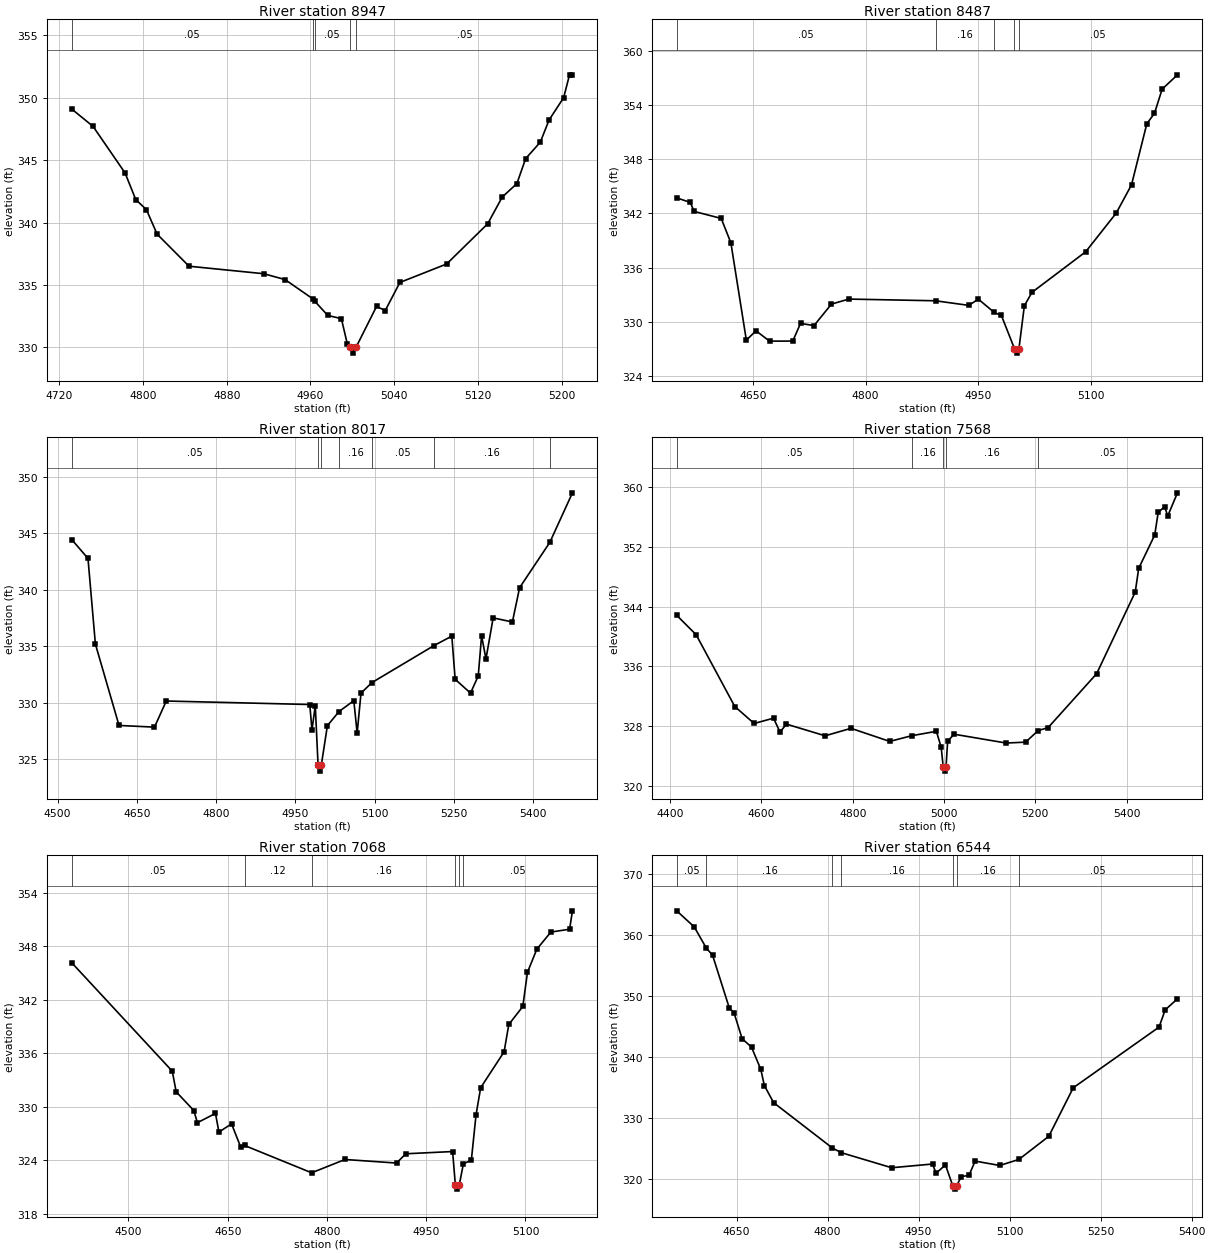
Type RM Length L Ch R = 1,8947,460,460,460
BEGIN DESCRIPTION:
UNT 127 IN CACR 18.0
END DESCRIPTION:
XS GIS Cut Line= 3
      3692949.60     10690410.22      3692899.61     10690660.19
      3692999.60     10690860.17
#Sta/Elev= 30
  4731.9  349.09  4752.3  347.70  4782.9  343.97  4793.1  341.84  4803.3  341.03
  4813.5  339.07  4844.0  336.50  4915.4  335.90  4935.8  335.43  4962.1  333.90
  4964.0  333.71  4976.6  332.56  4989.6  332.30  4995.2  330.30  4997.8  330.04
  5000.5  329.54  5003.8  330.04  5023.2  333.28  5031.5  332.95  5045.5  335.20
  5090.2  336.68  5129.4  339.90  5143.3  342.04  5157.3  343.12  5165.7  345.12
  5179.7  346.44  5188.1  348.22  5202.0  350.00  5207.6  351.83  5210.4  351.83
#Mann=5,-1,0
  4731.9    0.05       0  4962.1    0.12       0  4964.0    0.05       0
  4997.8    0.03       0  5003.8    0.05       0
Bank Sta=4997.8,5003.8
Exp/Cntr=0.3,0.1

Type RM Length L Ch R = 1,8487,470,470,470
BEGIN DESCRIPTION:
UNT 127 IN CACR 17.0
END DESCRIPTION:
XS GIS Cut Line= 3
      3692499.60     10690560.15      3692599.61     10690960.19
      3692849.60     10691010.19
#Sta/Elev= 30
  4548.4  343.73  4566.5  343.23  4571.6  342.23  4607.7  341.45  4620.6  338.74
  4641.2  327.94  4654.1  328.98  4672.1  327.83  4703.1  327.84  4713.4  329.80
  4731.4  329.56  4754.6  331.94  4777.8  332.50  4893.3  332.31  4937.6  331.80
  4950.4  332.49  4971.6  331.01  4981.1  330.68  4998.5  327.00  5001.3  326.50
  5004.5  327.00  5011.7  331.76  5021.9  333.25  5093.3  337.74  5134.1  342.04
  5154.5  345.18  5174.9  351.96  5185.1  353.12  5195.3  355.80  5215.7  357.39
#Mann=5,-1,0
  4548.4    0.05       0  4893.3    0.16       0  4971.6    0.05       0
  4998.5    0.03       0  5004.5    0.05       0
Bank Sta=4998.5,5004.5
Exp/Cntr=0.3,0.1

Type RM Length L Ch R = 1,8017,449,449,449
BEGIN DESCRIPTION:
UNT 127 IN CACR 16.0
END DESCRIPTION:
XS GIS Cut Line= 3
      3692449.63     10690560.15      3692249.61     10690960.19
      3692549.64     10691360.23
#Sta/Elev= 30
  4526.8  344.43  4557.6  342.76  4571.6  335.19  4616.3  327.99  4683.4  327.84
  4705.7  330.15  4977.2  329.84  4981.3  327.59  4987.6  329.73  4992.9  324.45
  4995.7  323.95  4998.9  324.45  5010.5  327.97  5032.5  329.22  5060.5  330.18
  5066.8  327.32  5074.1  330.85  5094.8  331.78  5212.1  335.05  5245.9  335.89
  5252.2  332.07  5281.3  330.85  5295.9  332.37  5302.2  335.91  5310.5  333.87
  5324.1  337.50  5360.5  337.14  5374.1  340.17  5431.2  344.17  5474.1  348.56
#Mann=7,-1,0
  4526.8    0.05       0  4992.9    0.03       0  4998.9    0.05       0
  5032.5    0.16       0  5094.8    0.05       0  5212.1    0.16       0
  5431.2    0.05       0
Bank Sta=4992.9,4998.9
Exp/Cntr=0.3,0.1

Type RM Length L Ch R = 1,7568,500,500,500
BEGIN DESCRIPTION:
UNT 127 IN CACR 15.0
END DESCRIPTION:
XS GIS Cut Line= 3
      3692299.63     10690410.16      3691899.61     10690810.19
      3691549.63     10691210.17
#Sta/Elev= 30
  4414.3  342.84  4456.8  340.25  4541.6  330.63  4584.0  328.36  4626.5  329.07
  4640.6  327.21  4654.8  328.27  4739.6  326.71  4796.2  327.71  4881.0  325.96
  4929.9  326.73  4983.3  327.31  4993.8  325.18  4998.4  322.48  5001.1  321.98
  5004.4  322.48  5008.0  326.01  5022.3  326.92  5136.2  325.74  5178.9  325.86
  5206.0  327.40  5228.2  327.81  5334.5  335.03  5419.0  345.95  5426.6  349.13
  5461.7  353.59  5469.3  356.61  5483.5  357.40  5490.2  356.13  5511.5  359.24
#Mann=5,-1,0
  4414.3    0.05       0  4929.9    0.16       0  4998.4    0.07       0
  5004.4    0.16       0  5206.0    0.05       0
Bank Sta=4998.4,5004.4
Exp/Cntr=0.3,0.1

Type RM Length L Ch R = 1,7068,524,524,524
BEGIN DESCRIPTION:
UNT 127 IN CACR 14.0
END DESCRIPTION:
XS GIS Cut Line= 3
      3691779.19     10690199.32      3691664.61     10690570.84
      3691404.39     10690831.07
#Sta/Elev= 30
  4414.2  346.15  4566.2  334.00  4572.1  331.69  4598.8  329.59  4604.1  328.23
  4631.5  329.27  4636.7  327.18  4655.8  328.10  4669.4  325.54  4675.4  325.68
  4776.8  322.62  4827.3  324.11  4905.1  323.71  4919.2  324.75  4989.9  325.00
  4994.0  321.29  4996.7  320.79  5000.0  321.29  5006.2  323.63  5018.2  324.03
  5025.3  329.12  5032.3  332.15  5067.7  336.17  5074.8  339.23  5096.0  341.25
  5103.0  345.07  5117.2  347.67  5138.4  349.58  5166.7  349.90  5171.0  351.96
#Mann=6,-1,0
  4414.2    0.05       0  4675.4    0.12       0  4776.8    0.16       0
  4994.0    0.07       0  5000.0    0.16       0  5006.2    0.05       0
Bank Sta=4994,5000
Exp/Cntr=0.3,0.1

Type RM Length L Ch R = 1,6544,504,504,504
BEGIN DESCRIPTION:
UNT 127 IN CACR 13.0
END DESCRIPTION:
XS GIS Cut Line= 3
      3691599.63     10690010.15      3691349.61     10690410.19
      3691299.61     10690760.19
#Sta/Elev= 30
  4551.3  363.90  4580.2  361.27  4600.4  357.75  4610.3  356.67  4638.0  348.00
  4645.7  347.23  4659.2  342.96  4674.6  341.59  4689.9  337.95  4695.8  335.29
  4711.1  332.50  4807.9  325.08  4822.4  324.32  4905.7  321.85  4972.9  322.46
  4978.8  320.94  4994.2  322.32  5006.5  318.85  5009.2  318.35  5012.5  318.85
  5020.1  320.37  5033.1  320.63  5043.2  322.94  5083.7  322.22  5115.3  323.21
  5164.5  326.99  5204.9  334.94  5346.3  344.87  5356.4  347.69  5376.6  349.50
#Mann=7,-1,0
  4551.3    0.05       0  4600.4    0.16       0  4807.9    0.05       0
  4822.4    0.16       0  5006.5    0.07       0  5012.5    0.16       0
  5115.3    0.05       0
Bank Sta=5006.5,5012.5
Exp/Cntr=0.3,0.1

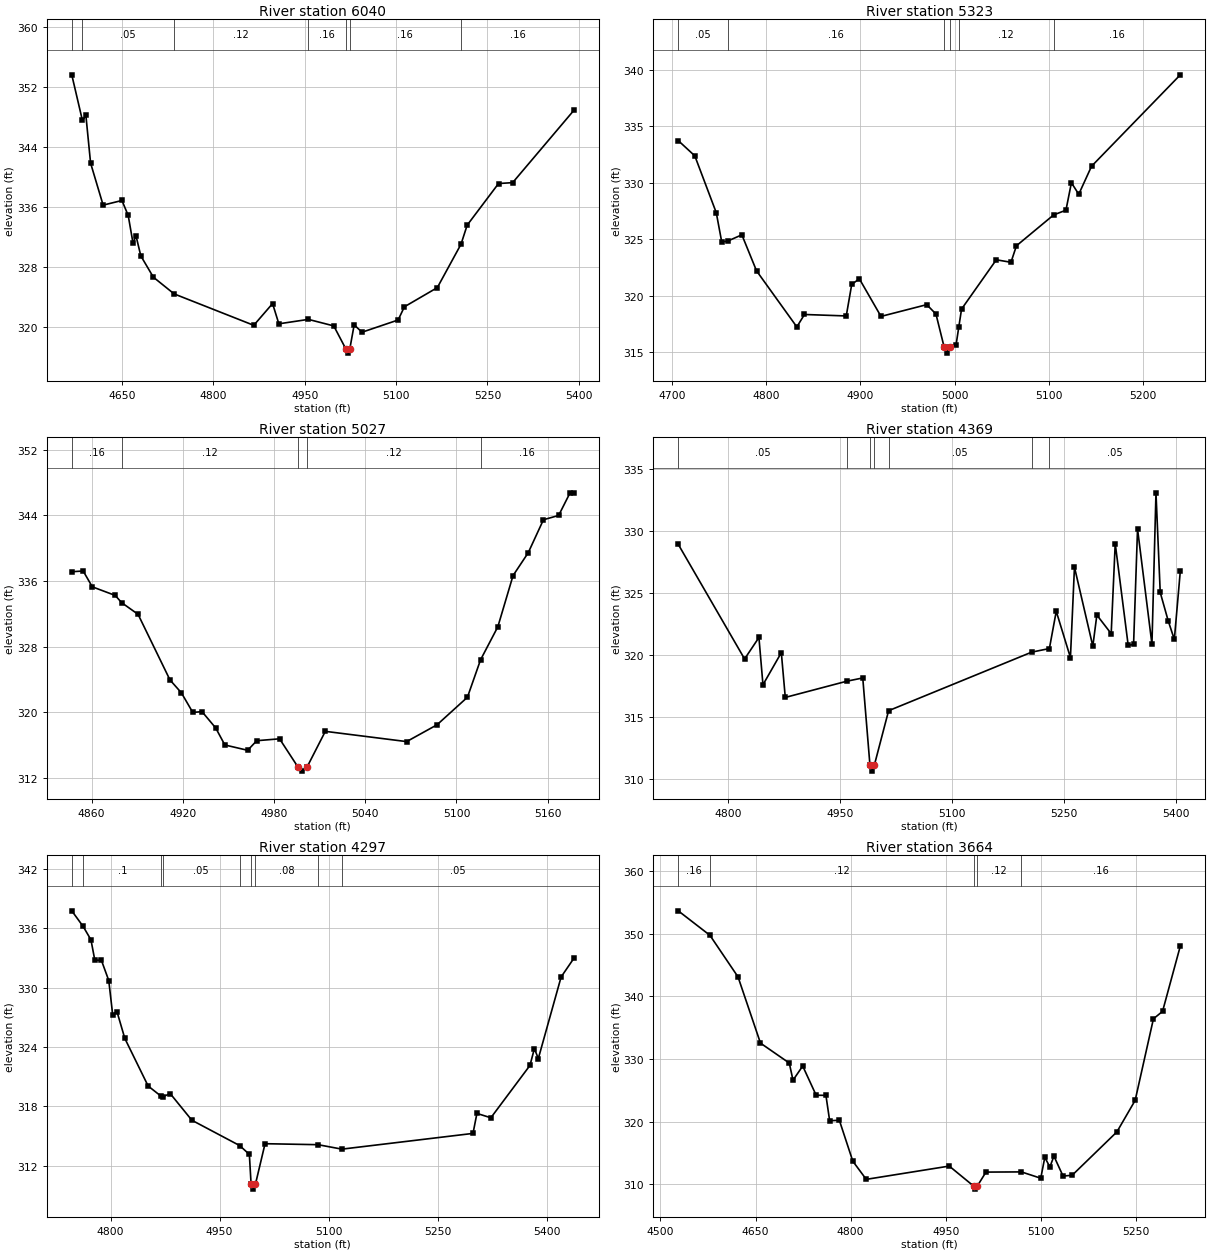
Type RM Length L Ch R = 1,6040,717,717,717
BEGIN DESCRIPTION:
UNT 127 IN CACR 12.0
END DESCRIPTION:
XS GIS Cut Line= 3
      3690849.62     10689960.22      3690949.61     10690360.19
      3691049.61     10690760.20
#Sta/Elev= 30
  4567.3  353.59  4584.8  347.50  4590.5  348.17  4598.2  341.82  4618.8  336.21
  4649.7  336.83  4660.0  334.83  4667.8  331.18  4672.9  332.08  4680.7  329.44
  4701.3  326.60  4735.4  324.37  4866.2  320.18  4897.1  323.08  4907.4  320.38
  4955.9  320.97  4997.6  320.10  5017.8  316.97  5020.6  316.47  5023.8  316.97
  5031.1  320.24  5044.0  319.26  5103.3  320.89  5113.6  322.65  5167.7  325.21
  5206.6  331.00  5216.7  333.54  5268.2  339.09  5291.4  339.21  5391.9  348.85
#Mann=7,-1,0
  4567.3    0.16       0  4584.8    0.05       0  4735.4    0.12       0
  4955.9    0.16       0  5017.8    0.07       0  5023.8    0.16       0
  5206.6    0.16       0
Bank Sta=5017.8,5023.8
Exp/Cntr=0.3,0.1

Type RM Length L Ch R = 1,5323,296,296,296
BEGIN DESCRIPTION:
UNT 127 IN CACR 11.0
END DESCRIPTION:
XS GIS Cut Line= 2
      3690411.12     10690345.11      3690685.04     10690802.81
#Sta/Elev= 30
  4706.5  333.72  4724.1  332.37  4746.9  327.34  4752.7  324.75  4759.1  324.83
  4774.1  325.38  4789.7  322.19  4832.5  317.23  4840.6  318.33  4885.0  318.20
  4890.8  320.99  4898.9  321.49  4921.9  318.16  4970.5  319.20  4980.3  318.37
  4989.1  315.41  4991.9  314.91  4995.1  315.41  5001.7  315.66  5004.6  317.24
  5007.5  318.81  5044.4  323.17  5060.0  322.95  5065.8  324.41  5105.3  327.14
  5118.4  327.56  5124.2  329.99  5132.0  328.97  5145.6  331.45  5239.9  339.54
#Mann=6,-1,0
  4706.5    0.05       0  4759.1    0.16       0  4989.1    0.07       0
  4995.1    0.16       0  5004.6    0.12       0  5105.3    0.16       0
Bank Sta=4989.1,4995.1
Exp/Cntr=0.3,0.1

Type RM Length L Ch R = 1,5027,658,658,658
BEGIN DESCRIPTION:
UNT 127 IN CACR 10.0
END DESCRIPTION:
XS GIS Cut Line= 3
      3690199.59     10690560.17      3690299.61     10690710.19
      3690299.61     10690860.19
#Sta/Elev= 30
  4846.9  337.14  4854.4  337.23  4860.4  335.30  4875.5  334.25  4879.7  333.37
  4890.5  331.95  4911.5  323.95  4919.0  322.38  4926.5  319.99  4932.6  320.08
  4941.6  318.09  4947.6  316.02  4962.6  315.37  4968.6  316.54  4983.6  316.77
  4995.7  313.33  4998.4  312.83  5001.7  313.33  5013.7  317.68  5067.2  316.43
  5087.2  318.48  5107.2  321.84  5115.8  326.39  5127.2  330.43  5137.2  336.67
  5147.2  339.46  5157.2  343.48  5167.2  344.00  5174.7  346.76  5177.2  346.76
#Mann=5,-1,0
  4846.9    0.16       0  4879.7    0.12       0  4995.7    0.07       0
  5001.7    0.12       0  5115.8    0.16       0
Bank Sta=4995.7,5001.7
Exp/Cntr=0.3,0.1

Type RM Length L Ch R = 1,4369,72,72,72
BEGIN DESCRIPTION:
UNT 127 IN CACR 9.0
END DESCRIPTION:
XS GIS Cut Line= 2
      3689932.02     10690584.93      3689304.52     10690827.08
#Sta/Elev= 30
  4733.5  328.94  4822.4  319.70  4841.6  321.43  4847.0  317.62  4871.6  320.21
  4876.9  316.60  4959.5  317.91  4980.7  318.17  4990.3  311.16  4993.1  310.66
  4996.3  311.16  5015.3  315.53  5207.0  320.25  5230.7  320.54  5239.9  323.54
  5258.9  319.81  5264.3  327.10  5288.9  320.73  5294.3  323.24  5313.5  321.74
  5318.9  329.00  5336.3  320.79  5343.5  320.88  5348.8  330.18  5368.1  320.89
  5373.5  333.09  5379.2  325.06  5389.9  322.77  5398.1  321.27  5406.1  326.79
#Mann=7,-1,0
  4733.5    0.05       0  4959.5    0.12       0  4990.3    0.07       0
  4996.3    0.12       0  5015.3    0.05       0  5207.0    0.12       0
  5230.7    0.05       0
Bank Sta=4990.3,4996.3
Exp/Cntr=0.3,0.1

Type RM Length L Ch R = 1,4297,633,633,633
BEGIN DESCRIPTION:
UNT 127 IN CACR 8.0
END DESCRIPTION:
XS GIS Cut Line= 2
      3689887.66     10690525.07      3689243.25     10690774.52
#Sta/Elev= 30
  4746.6  337.75  4762.3  336.17  4773.0  334.82  4778.3  332.77  4787.4  332.75
  4797.5  330.71  4802.9  327.26  4808.8  327.57  4819.6  324.86  4851.7  320.05
  4870.0  318.99  4871.6  318.94  4882.0  319.29  4911.9  316.59  4977.7  314.03
  4991.0  313.14  4993.4  310.13  4996.1  309.63  4999.4  310.13  5012.6  314.22
  5085.5  314.12  5118.4  313.67  5298.8  315.26  5304.2  317.28  5323.4  316.84
  5377.2  322.13  5383.3  323.83  5388.7  322.82  5420.1  331.07  5437.6  332.95
#Mann=9,-1,0
  4746.6    0.05       0  4762.3     0.1       0  4870.0    0.12       0
  4871.6    0.05       0  4977.7    0.08       0  4993.4    0.07       0
  4999.4    0.08       0  5085.5    0.12       0  5118.4    0.05       0
Bank Sta=4993.4,4999.4
Exp/Cntr=0.3,0.1

Type RM Length L Ch R = 1,3664,526,526,526
BEGIN DESCRIPTION:
UNT 127 IN CACR 7.0
END DESCRIPTION:
XS GIS Cut Line= 3
      3689449.57     10690310.21      3689049.61     10690560.19
      3688799.62     10690760.18
#Sta/Elev= 30
  4528.1  353.66  4578.1  349.75  4622.4  343.11  4657.8  332.54  4703.2  329.36
  4709.1  326.62  4724.4  328.88  4745.6  324.22  4761.0  324.20  4766.9  320.15
  4782.2  320.22  4803.4  313.69  4824.6  310.79  4955.5  312.91  4993.8  309.73
  4996.6  309.23  4999.8  309.73  5013.4  311.95  5069.3  311.98  5099.8  310.97
  5106.2  314.30  5114.2  312.77  5120.6  314.49  5135.0  311.31  5149.4  311.45
  5219.9  318.37  5248.7  323.40  5277.5  336.42  5291.9  337.61  5319.9  348.04
#Mann=5,-1,0
  4528.1    0.16       0  4578.1    0.12       0  4993.8    0.07       0
  4999.8    0.12       0  5069.3    0.16       0
Bank Sta=4993.8,4999.8
Exp/Cntr=0.3,0.1

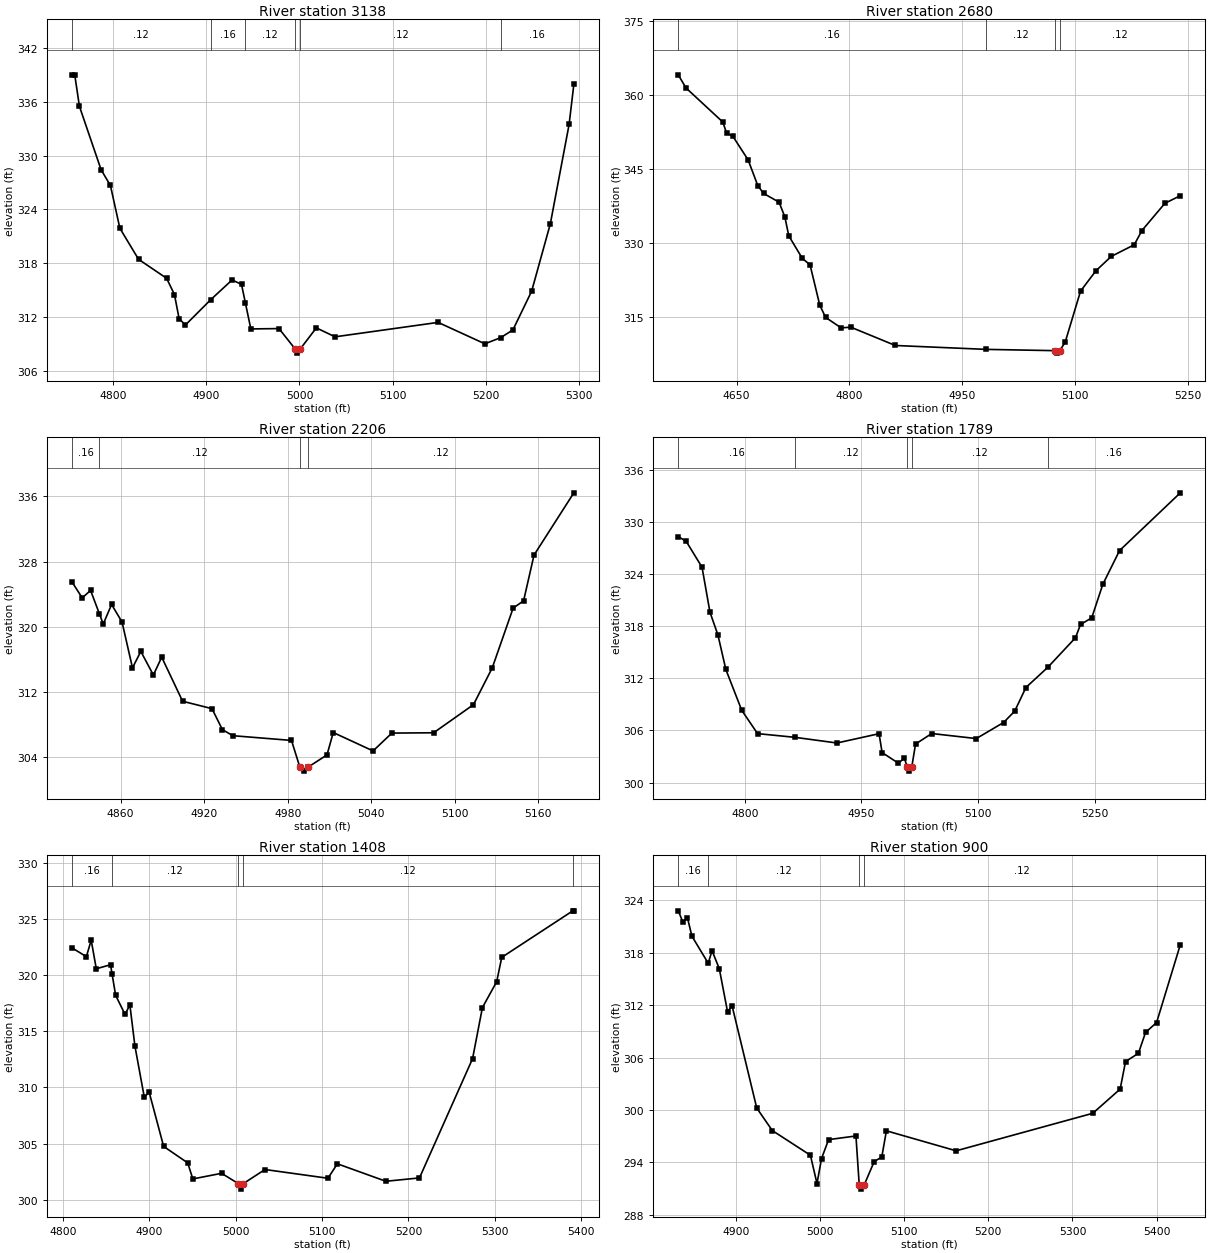
Type RM Length L Ch R = 1,3138,458,458,458
BEGIN DESCRIPTION:
UNT 127 IN CACR 6.0
END DESCRIPTION:
XS GIS Cut Line= 2
      3689280.93     10690254.22      3688744.55     10690306.30
#Sta/Elev= 30
  4755.6  339.03  4758.8  339.03  4763.8  335.52  4787.1  328.43  4797.1  326.68
  4807.2  321.91  4827.3  318.44  4857.4  316.32  4865.8  314.51  4870.8  311.83
  4877.5  311.10  4904.8  313.94  4927.7  316.14  4937.8  315.64  4942.0  313.55
  4947.8  310.67  4978.0  310.71  4995.1  308.47  4997.8  307.97  5001.1  308.47
  5018.1  310.79  5038.2  309.79  5148.8  311.40  5199.0  309.01  5216.0  309.70
  5229.1  310.56  5249.2  314.88  5269.3  322.42  5289.4  333.49  5294.5  337.96
#Mann=6,-1,0
  4755.6    0.12       0  4904.8    0.16       0  4942.0    0.12       0
  4995.1    0.07       0  5001.1    0.12       0  5216.0    0.16       0
Bank Sta=4995.1,5001.1
Exp/Cntr=0.3,0.1

Type RM Length L Ch R = 1,2680,474,474,474
BEGIN DESCRIPTION:
UNT 127 IN CACR 5.0
END DESCRIPTION:
XS GIS Cut Line= 3
      3689449.62     10690060.19      3689049.61     10689960.19
      3688799.59     10689910.18
#Sta/Elev= 30
  4572.4  364.15  4582.7  361.49  4631.7  354.55  4636.8  352.24  4644.6  351.76
  4665.2  346.90  4678.1  341.67  4685.8  340.06  4706.4  338.29  4714.1  335.30
  4719.3  331.46  4737.3  326.87  4747.6  325.56  4760.5  317.38  4768.3  314.88
  4788.9  312.76  4801.8  312.90  4861.0  309.18  4981.8  308.39  5073.5  308.13
  5076.3  307.63  5079.5  308.13  5086.7  309.87  5107.1  320.22  5127.5  324.35
  5147.9  327.27  5178.5  329.64  5188.7  332.53  5219.3  338.07  5239.7  339.60
#Mann=4,-1,0
  4572.4    0.16       0  4981.8    0.12       0  5073.5    0.07       0
  5079.5    0.12       0
Bank Sta=5073.5,5079.5
Exp/Cntr=0.3,0.1

Type RM Length L Ch R = 1,2206,417,417,417
BEGIN DESCRIPTION:
UNT 127 IN CACR 4.0
END DESCRIPTION:
XS GIS Cut Line= 3
      3688999.63     10689560.17      3688849.61     10689660.19
      3688749.60     10689810.21
#Sta/Elev= 30
  4824.9  325.54  4832.4  323.54  4838.4  324.46  4844.8  321.56  4847.5  320.33
  4853.5  322.73  4861.0  320.58  4868.5  314.95  4874.5  316.97  4883.5  314.07
  4889.5  316.26  4904.5  310.85  4925.6  309.94  4933.1  307.36  4940.6  306.62
  4982.7  306.04  4988.7  302.77  4991.4  302.27  4994.7  302.77  5008.2  304.26
  5012.7  307.01  5041.3  304.75  5054.8  306.94  5084.8  306.98  5113.4  310.43
  5126.9  314.95  5141.9  322.29  5149.4  323.18  5156.9  328.80  5185.5  336.44
#Mann=4,-1,0
  4824.9    0.16       0  4844.8    0.12       0  4988.7    0.07       0
  4994.7    0.12       0
Bank Sta=4988.7,4994.7
Exp/Cntr=0.3,0.1

Type RM Length L Ch R = 1,1789,381,381,381
BEGIN DESCRIPTION:
UNT 127 IN CACR 3.0
END DESCRIPTION:
XS GIS Cut Line= 3
      3689049.61     10689210.19      3688799.61     10689260.19
      3688499.58     10689510.21
#Sta/Elev= 30
  4714.5  328.32  4724.7  327.78  4745.1  324.79  4755.3  319.61  4765.5  317.00
  4775.7  313.02  4796.1  308.32  4816.5  305.63  4864.8  305.20  4918.5  304.55
  4972.7  305.62  4976.6  303.45  4997.4  302.23  5005.3  302.79  5008.8  301.81
  5011.5  301.31  5014.8  301.81  5019.6  304.43  5040.4  305.64  5097.7  305.06
  5132.8  306.91  5147.1  308.22  5161.5  310.94  5189.8  313.28  5225.2  316.67
  5231.7  318.20  5246.1  318.96  5260.4  322.83  5281.9  326.71  5360.0  333.36
#Mann=5,-1,0
  4714.5    0.16       0  4864.8    0.12       0  5008.8    0.07       0
  5014.8    0.12       0  5189.8    0.16       0
Bank Sta=5008.8,5014.8
Exp/Cntr=0.3,0.1

Type RM Length L Ch R = 1,1408,508,508,508
BEGIN DESCRIPTION:
Mapping XS 26fd64bd
END DESCRIPTION:
XS GIS Cut Line= 2
      3688684.56     10688804.78      3688424.50     10689324.89
#Sta/Elev= 30
  4810.1  322.47  4827.0  321.67  4832.6  323.14  4838.5  320.59  4855.0  320.95
  4856.8  320.12  4860.9  318.22  4871.8  316.52  4877.4  317.37  4883.2  313.71
  4894.1  309.13  4899.7  309.59  4916.5  304.74  4944.4  303.27  4950.3  301.84
  4983.6  302.34  5002.9  301.43  5005.7  300.93  5008.9  301.43  5033.9  302.68
  5106.8  301.90  5117.7  303.19  5173.9  301.63  5212.8  301.93  5274.3  312.57
  5285.7  317.13  5302.2  319.43  5308.1  321.61  5390.4  325.76  5391.6  325.76
#Mann=5,-1,0
  4810.1    0.16       0  4856.8    0.12       0  5002.9    0.07       0
  5008.9    0.12       0  5390.4    0.16       0
Bank Sta=5002.9,5008.9
Exp/Cntr=0.3,0.1

Type RM Length L Ch R = 1,900,582,582,582
BEGIN DESCRIPTION:
UNT 127 IN CACR 2.0
END DESCRIPTION:
XS GIS Cut Line= 2
      3688288.76     10688565.11      3688060.00     10689116.22
#Sta/Elev= 30
  4831.5  322.81  4837.0  321.53  4842.4  322.02  4847.8  319.90  4867.1  316.81
  4871.7  318.24  4880.3  316.18  4890.1  311.25  4895.5  311.93  4924.8  300.22
  4943.3  297.64  4988.6  294.81  4996.4  291.57  5001.8  294.43  5010.2  296.60
  5042.7  297.02  5046.6  291.43  5049.3  290.93  5052.6  291.43  5064.4  294.09
  5073.4  294.61  5078.9  297.61  5161.8  295.32  5324.2  299.62  5356.7  302.39
  5363.1  305.54  5378.4  306.49  5386.9  308.88  5400.0  310.01  5428.2  318.93
#Mann=4,-1,0
  4831.5    0.16       0  4867.1    0.12       0  5046.6    0.07       0
  5052.6    0.12       0
Bank Sta=5046.6,5052.6
Exp/Cntr=0.3,0.1

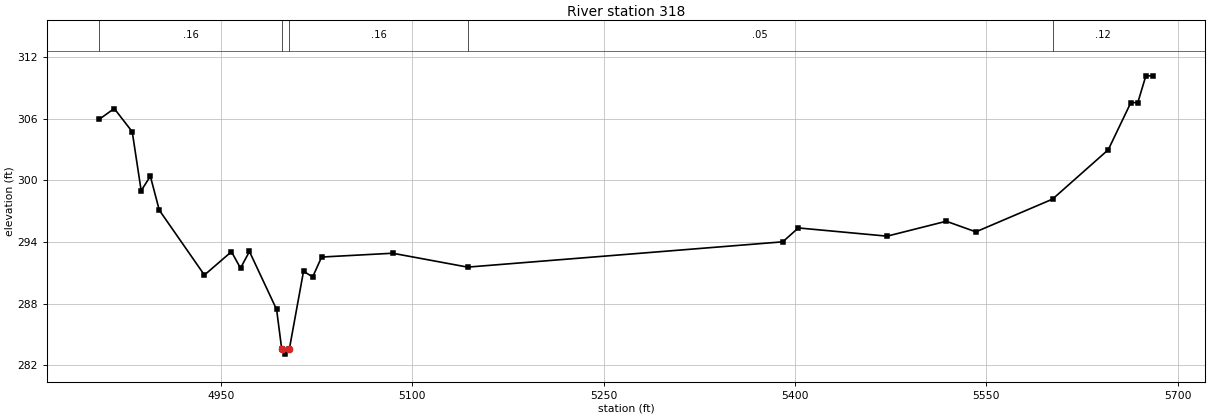
Type RM Length L Ch R = 1,318,0,0,0
BEGIN DESCRIPTION:
UNT 127 IN CACR 1.0
END DESCRIPTION:
XS GIS Cut Line= 3
      3687832.59     10688336.64      3687679.80     10688485.95
      3687929.80     10689044.97
#Sta/Elev= 30
  4854.5  305.94  4866.2  306.98  4880.3  304.72  4887.3  298.99  4894.5  300.40
  4901.5  297.10  4936.9  290.79  4958.1  293.06  4965.2  291.46  4972.2  293.08
  4993.5  287.44  4997.5  283.60  5000.2  283.10  5003.5  283.60  5014.6  291.15
  5021.8  290.61  5028.8  292.54  5084.5  292.91  5143.3  291.56  5390.4  294.02
  5402.6  295.37  5472.2  294.57  5518.6  296.02  5541.8  294.99  5601.9  298.17
  5645.6  302.97  5663.3  307.55  5668.8  307.56  5675.1  310.16  5680.5  310.16
#Mann=5,-1,0
  4854.5    0.16       0  4997.5    0.07       0  5003.5    0.16       0
  5143.3    0.05       0  5601.9    0.12       0
Bank Sta=4997.5,5003.5
Exp/Cntr=0.3,0.1

Chan Stop Cuts=-1