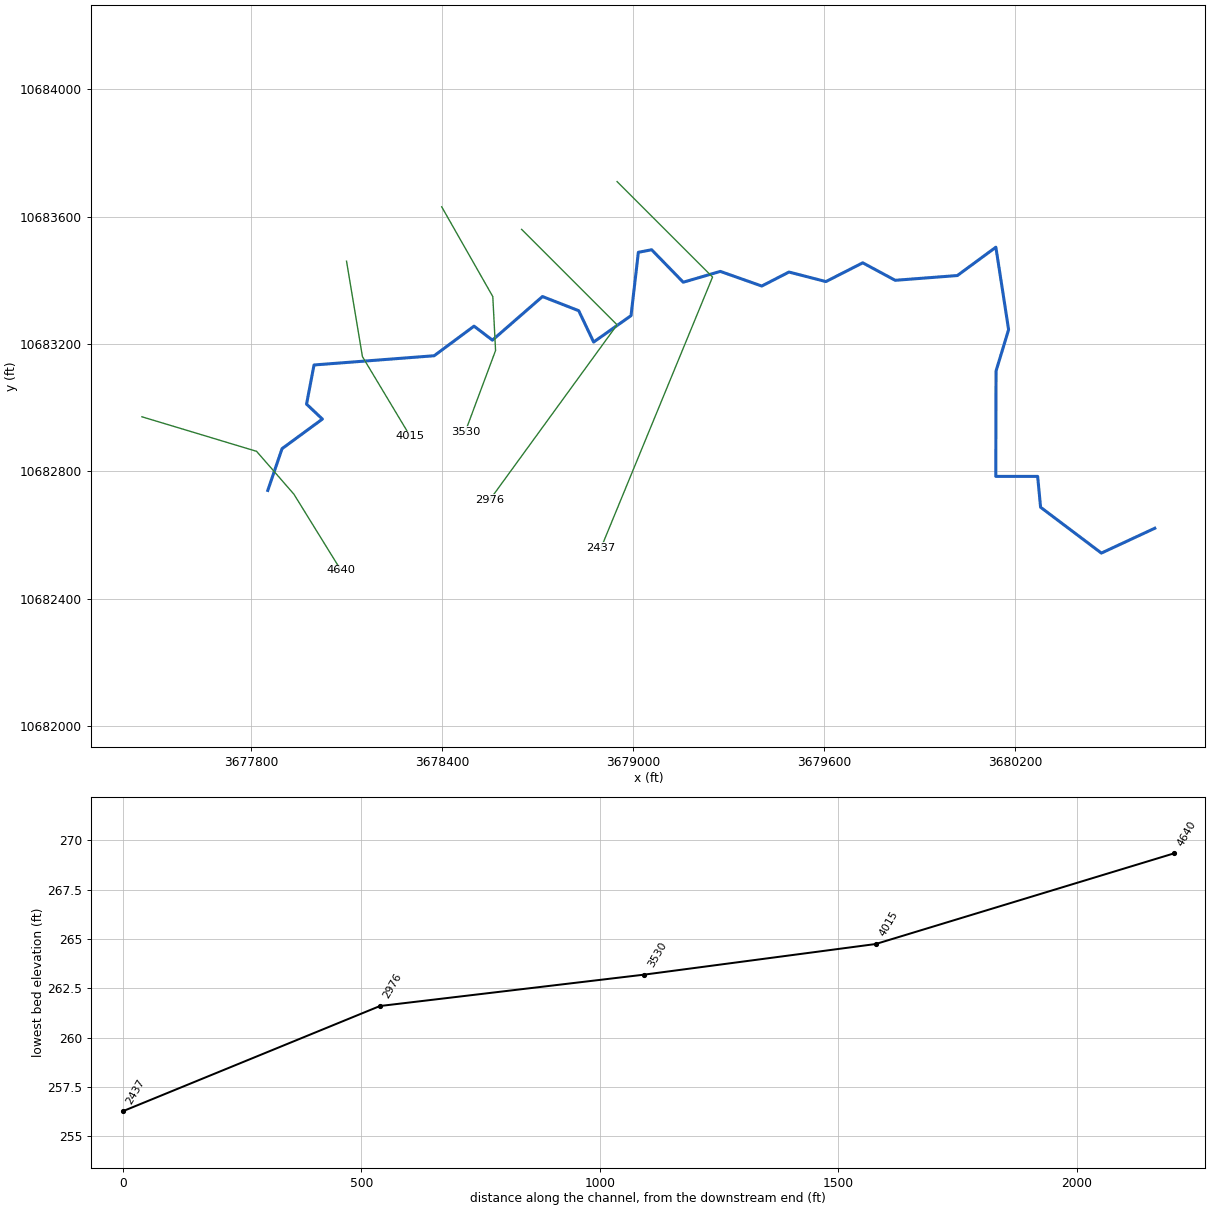
--- UNT 128 IN CACR.prj (project) ---

Proj Title=UNT 128 IN CACR Base Level Engineering
Current Plan=p01
Default Exp/Contr=0.3,0.1
English Units
Geom File=g01
Flow File=f01
Plan File=p01
BEGIN DESCRIPTION:
UNT 128 IN CACR
END DESCRIPTION:

--- UNT 128 IN CACR.p01 (plan) ---

Plan Title=Multiple Run
Short Identifier=Multiple
Geom File=g01
Flow File=f01
Subcritical Flow
K Sum by GR= 0
Std Step Tol= 0.01
Critical Tol= 0.01
Num of Std Step Trials= 20
Max Error Tol= 0.3
Flow Tol Ratio= 0.001
Split Flow NTrial= 30
Split Flow Tol= 0.02
Split Flow Ratio= 0.02
Log Output Level= 0
Friction Slope Method= 1
Unsteady Friction Slope Method= 2
Unsteady Bridges Friction Slope Method= 1
Parabolic Critical Depth
Global Vel Dist=  1 , 1 , 1
Global Log Level= 0
CheckData=True
Encroach Param= -1, 0, 0, 0
BEGIN DESCRIPTION:
Multiple Run
END DESCRIPTION:

--- UNT 128 IN CACR.f01 (steady flow) ---

Flow Title=Multiple
Number of Profiles=7
Profile Names=10-year,25-year,50-year,1pct_min,100-year,1pct_plu,500-year
River Rch & RM= UNT 128 IN CACR,Reach-1,4640
     438     582     699     617     835    1129    1194
Boundary for River Rch & Prof#=UNT 128 IN CACR,Reach-1,1
Up Type=0
Dn Type=3
Dn Slope=0.005
Boundary for River Rch & Prof#=UNT 128 IN CACR,Reach-1,2
Up Type=0
Dn Type=3
Dn Slope=0.005
Boundary for River Rch & Prof#=UNT 128 IN CACR,Reach-1,3
Up Type=0
Dn Type=3
Dn Slope=0.005
Boundary for River Rch & Prof#=UNT 128 IN CACR,Reach-1,4
Up Type=0
Dn Type=3
Dn Slope=0.005
Boundary for River Rch & Prof#=UNT 128 IN CACR,Reach-1,5
Up Type=0
Dn Type=3
Dn Slope=0.005
Boundary for River Rch & Prof#=UNT 128 IN CACR,Reach-1,6
Up Type=0
Dn Type=3
Dn Slope=0.005
Boundary for River Rch & Prof#=UNT 128 IN CACR,Reach-1,7
Up Type=0
Dn Type=3
Dn Slope=0.005

--- UNT 128 IN CACR.g01 (geometry) ---

Geom Title=Existing Conditions

River Reach=UNT 128 IN CACR,Reach-1
Reach XY= 30
      3677852.24     10682739.92      3677897.00     10682871.00
      3678023.75     10682964.00      3677974.00     10683011.00
      3677997.50     10683134.00      3678375.00     10683163.00
      3678500.25     10683256.00      3678558.00     10683212.00
      3678715.25     10683349.00      3678829.03     10683304.56
      3678876.00     10683206.00      3678993.50     10683289.00
      3679016.50     10683488.00      3679058.25     10683496.00
      3679157.50     10683394.00      3679274.00     10683428.00
      3679404.25     10683382.00      3679489.75     10683426.00
      3679605.75     10683396.00      3679721.50     10683455.00
      3679823.50     10683400.00      3680018.75     10683415.00
      3680139.75     10683504.00      3680179.75     10683245.00
      3680140.25     10683115.00      3680139.50     10682784.00
      3680271.00     10682784.00      3680280.25     10682687.00
      3680471.25     10682543.00      3680639.00     10682621.00

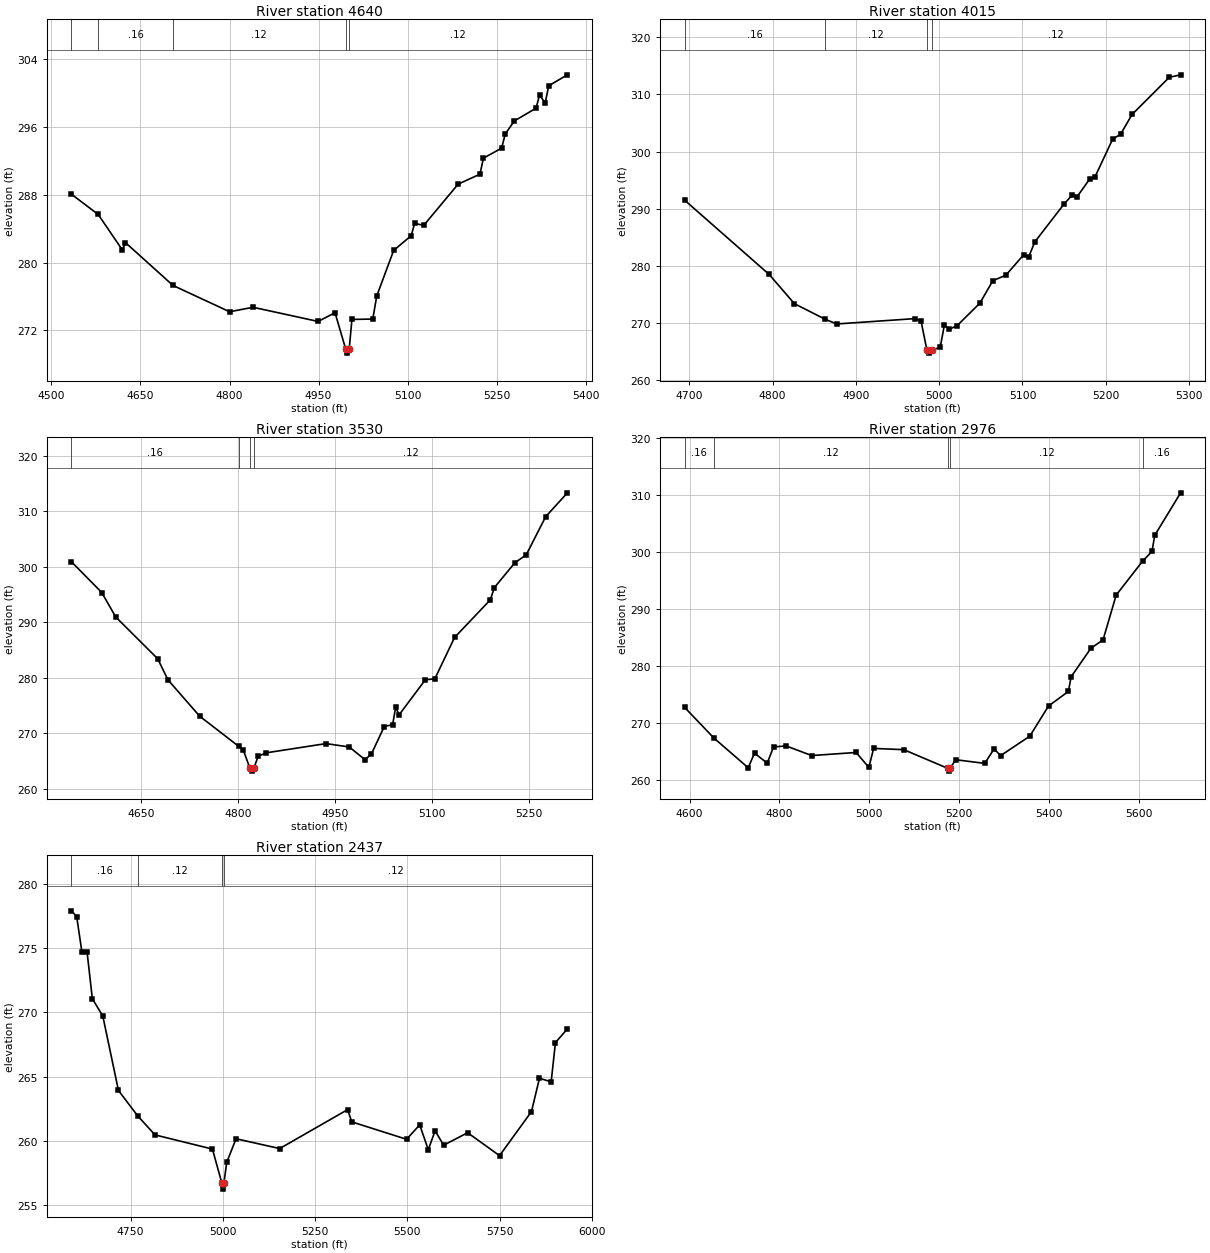
Type RM Length L Ch R = 1,4640,625,625,625
BEGIN DESCRIPTION:
UNT 128 IN CACR 5.0
END DESCRIPTION:
XS GIS Cut Line= 4
      3677456.81     10682971.21      3677817.01     10682862.71
      3677934.20     10682728.17      3678081.79     10682489.42
#Sta/Elev= 30
  4533.8  288.04  4578.8  285.66  4619.5  281.48  4624.8  282.34  4704.8  277.30
  4800.2  274.20  4839.6  274.73  4949.2  273.06  4977.7  274.09  4995.6  269.83
  4998.4  269.33  5001.6  269.83  5006.2  273.30  5041.3  273.34  5048.0  276.06
  5076.5  281.43  5105.9  283.15  5111.8  284.60  5127.2  284.38  5185.1  289.23
  5221.8  290.40  5227.7  292.29  5258.4  293.47  5264.3  295.12  5279.7  296.67
  5316.3  298.17  5322.2  299.73  5331.7  298.78  5337.6  300.81  5369.1  302.10
#Mann=5,-1,0
  4533.8    0.12       0  4578.8    0.16       0  4704.8    0.12       0
  4995.6    0.07       0  5001.6    0.12       0
Bank Sta=4995.6,5001.6
Exp/Cntr=0.3,0.1

Type RM Length L Ch R = 1,4015,485,485,485
BEGIN DESCRIPTION:
UNT 128 IN CACR 4.0
END DESCRIPTION:
XS GIS Cut Line= 3
      3678099.61     10683460.16      3678149.61     10683160.19
      3678299.63     10682910.16
#Sta/Elev= 30
  4694.3  291.48  4795.7  278.51  4826.1  273.39  4862.5  270.70  4876.8  269.84
  4970.5  270.77  4978.1  270.43  4985.3  265.24  4988.0  264.74  4991.3  265.24
  5001.3  265.79  5006.2  269.63  5012.0  268.90  5021.7  269.57  5048.9  273.48
  5064.5  277.42  5080.0  278.36  5101.4  281.92  5107.3  281.51  5115.0  284.22
  5150.0  290.82  5159.7  292.38  5165.6  292.08  5181.1  295.25  5186.9  295.48
  5208.3  302.14  5218.0  303.05  5231.7  306.48  5276.4  312.98  5290.0  313.41
#Mann=4,-1,0
  4694.3    0.16       0  4862.5    0.12       0  4985.3    0.07       0
  4991.3    0.12       0
Bank Sta=4985.3,4991.3
Exp/Cntr=0.3,0.1

Type RM Length L Ch R = 1,3530,554,554,554
BEGIN DESCRIPTION:
UNT 128 IN CACR 3.0
END DESCRIPTION:
XS GIS Cut Line= 4
      3678398.63     10683630.91      3678559.20     10683348.82
      3678567.88     10683179.55      3678472.70     10682924.30
#Sta/Elev= 30
  4542.7  300.93  4589.5  295.39  4611.1  290.98  4676.0  283.44  4691.8  279.65
  4740.8  273.10  4801.4  267.64  4808.2  267.03  4818.5  263.69  4821.3  263.19
  4824.5  263.69  4831.2  265.84  4843.1  266.48  4936.0  268.15  4972.0  267.55
  4996.1  265.28  5006.1  266.23  5026.1  271.22  5039.1  271.58  5043.8  274.71
  5049.1  273.34  5089.5  279.64  5104.4  279.85  5134.8  287.29  5190.1  294.07
  5196.2  296.26  5228.2  300.78  5245.4  302.15  5275.7  309.07  5309.2  313.36
#Mann=4,-1,0
  4542.7    0.16       0  4801.4    0.12       0  4818.5    0.07       0
  4824.5    0.12       0
Bank Sta=4818.5,4824.5
Exp/Cntr=0.3,0.1

Type RM Length L Ch R = 1,2976,539,539,539
BEGIN DESCRIPTION:
UNT 128 IN CACR 2.0
END DESCRIPTION:
XS GIS Cut Line= 3
      3678649.64     10683560.16      3678949.61     10683260.19
      3678549.61     10682710.18
#Sta/Elev= 30
  4588.9  272.76  4654.0  267.40  4730.3  262.19  4744.4  264.75  4772.7  263.00
  4786.8  265.85  4815.1  266.01  4871.7  264.33  4970.7  264.87  4999.0  262.25
  5009.6  265.58  5076.9  265.36  5174.3  262.10  5177.1  261.60  5180.3  262.10
  5192.0  263.60  5256.9  262.96  5277.8  265.48  5292.5  264.32  5357.4  267.73
  5399.1  273.02  5443.2  275.56  5449.4  278.14  5493.4  283.13  5520.5  284.61
  5549.8  292.47  5608.4  298.39  5629.4  300.11  5635.6  302.93  5693.2  310.38
#Mann=5,-1,0
  4588.9    0.16       0  4654.0    0.12       0  5174.3    0.07       0
  5180.3    0.12       0  5608.4    0.16       0
Bank Sta=5174.3,5180.3
Exp/Cntr=0.3,0.1

Type RM Length L Ch R = 1,2437,0,0,0
BEGIN DESCRIPTION:
UNT 128 IN CACR 1.0
END DESCRIPTION:
XS GIS Cut Line= 3
      3678949.60     10683710.20      3679249.61     10683410.19
      3678899.62     10682560.21
#Sta/Elev= 30
  4590.0  277.88  4604.2  277.43  4618.3  274.68  4632.4  274.65  4646.6  271.05
  4674.9  269.71  4717.3  263.93  4769.1  261.97  4816.3  260.48  4971.9  259.38
  4997.1  256.77  4999.9  256.27  5003.1  256.77  5010.7  258.36  5035.9  260.18
  5154.1  259.42  5337.9  262.44  5349.5  261.49  5497.8  260.14  5533.4  261.26
  5556.6  259.33  5575.1  260.80  5598.3  259.68  5663.2  260.65  5749.7  258.87
  5836.2  262.29  5857.8  264.88  5889.5  264.60  5901.1  267.65  5933.5  268.71
#Mann=4,-1,0
  4590.0    0.16       0  4769.1    0.12       0  4997.1    0.07       0
  5003.1    0.12       0
Bank Sta=4997.1,5003.1
Exp/Cntr=0.3,0.1

Chan Stop Cuts=-1