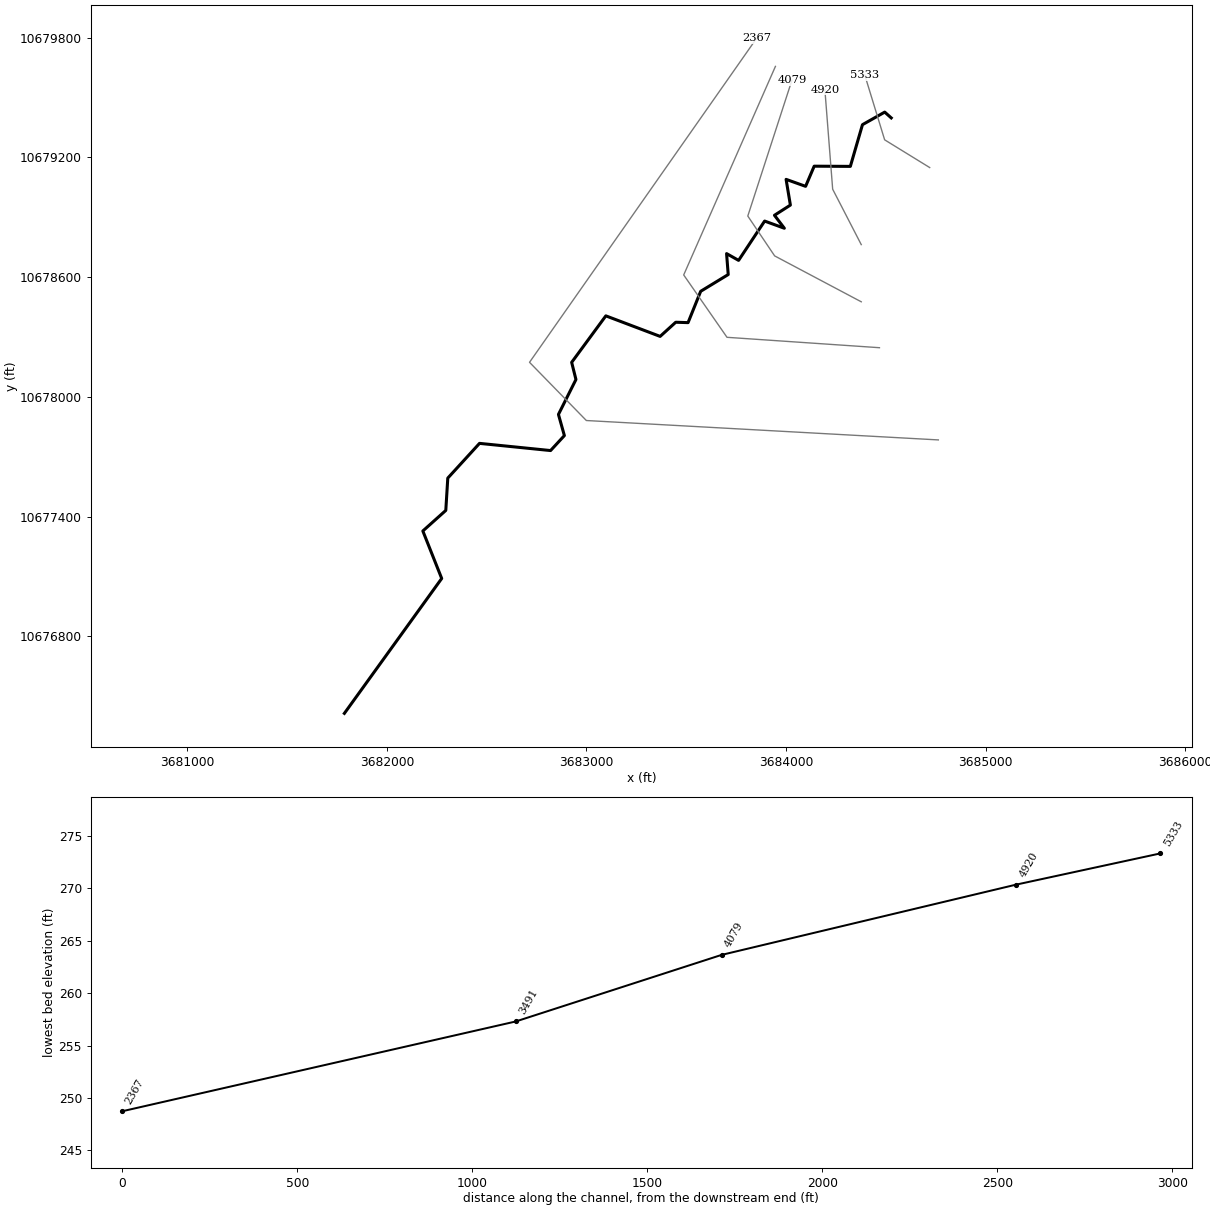
--- UNT 129 IN CACR.prj (project) ---

Proj Title=UNT 129 IN CACR Base Level Engineering
Current Plan=p01
Default Exp/Contr=0.3,0.1
English Units
Geom File=g01
Flow File=f01
Plan File=p01
BEGIN DESCRIPTION:
UNT 129 IN CACR
END DESCRIPTION:

--- UNT 129 IN CACR.p01 (plan) ---

Plan Title=Multiple Run
Short Identifier=Multiple
Geom File=g01
Flow File=f01
Subcritical Flow
K Sum by GR= 0
Std Step Tol= 0.01
Critical Tol= 0.01
Num of Std Step Trials= 20
Max Error Tol= 0.3
Flow Tol Ratio= 0.001
Split Flow NTrial= 30
Split Flow Tol= 0.02
Split Flow Ratio= 0.02
Log Output Level= 0
Friction Slope Method= 1
Unsteady Friction Slope Method= 2
Unsteady Bridges Friction Slope Method= 1
Parabolic Critical Depth
Global Vel Dist=  1 , 1 , 1
Global Log Level= 0
CheckData=True
Encroach Param= -1, 0, 0, 0
BEGIN DESCRIPTION:
Multiple Run
END DESCRIPTION:

--- UNT 129 IN CACR.f01 (steady flow) ---

Flow Title=Multiple
Number of Profiles=7
Profile Names=10-year,25-year,50-year,1pct_min,100-year,1pct_plu,500-year
River Rch & RM= UNT 129 IN CACR,Reach-1,5333
     457     616     748     668     903    1221    1321
Boundary for River Rch & Prof#=UNT 129 IN CACR,Reach-1,1
Up Type=0
Dn Type=3
Dn Slope=0.005
Boundary for River Rch & Prof#=UNT 129 IN CACR,Reach-1,2
Up Type=0
Dn Type=3
Dn Slope=0.005
Boundary for River Rch & Prof#=UNT 129 IN CACR,Reach-1,3
Up Type=0
Dn Type=3
Dn Slope=0.005
Boundary for River Rch & Prof#=UNT 129 IN CACR,Reach-1,4
Up Type=0
Dn Type=3
Dn Slope=0.005
Boundary for River Rch & Prof#=UNT 129 IN CACR,Reach-1,5
Up Type=0
Dn Type=3
Dn Slope=0.005
Boundary for River Rch & Prof#=UNT 129 IN CACR,Reach-1,6
Up Type=0
Dn Type=3
Dn Slope=0.005
Boundary for River Rch & Prof#=UNT 129 IN CACR,Reach-1,7
Up Type=0
Dn Type=3
Dn Slope=0.005

--- UNT 129 IN CACR.g01 (geometry) ---

Geom Title=Existing Conditions

River Reach=UNT 129 IN CACR,Reach-1
Reach XY= 30
      3684527.15     10679397.93      3684494.50     10679427.00
      3684383.00     10679364.00      3684322.25     10679155.00
      3684141.00     10679156.00      3684098.00     10679055.00
      3684000.25     10679090.00      3684021.75     10678961.00
      3683942.00     10678910.00      3683991.50     10678845.00
      3683892.75     10678881.00      3683762.25     10678684.00
      3683702.00     10678718.00      3683710.25     10678613.00
      3683572.25     10678529.00      3683509.00     10678372.00
      3683447.25     10678374.00      3683369.07     10678303.03
      3683097.00     10678406.00      3682925.75     10678173.00
      3682947.25     10678087.00      3682859.50     10677912.00
      3682889.25     10677806.00      3682820.00     10677731.00
      3682464.00     10677767.00      3682305.00     10677593.00
      3682295.00     10677431.00      3682180.00     10677328.00
      3682274.50     10677090.00      3681786.75     10676414.00

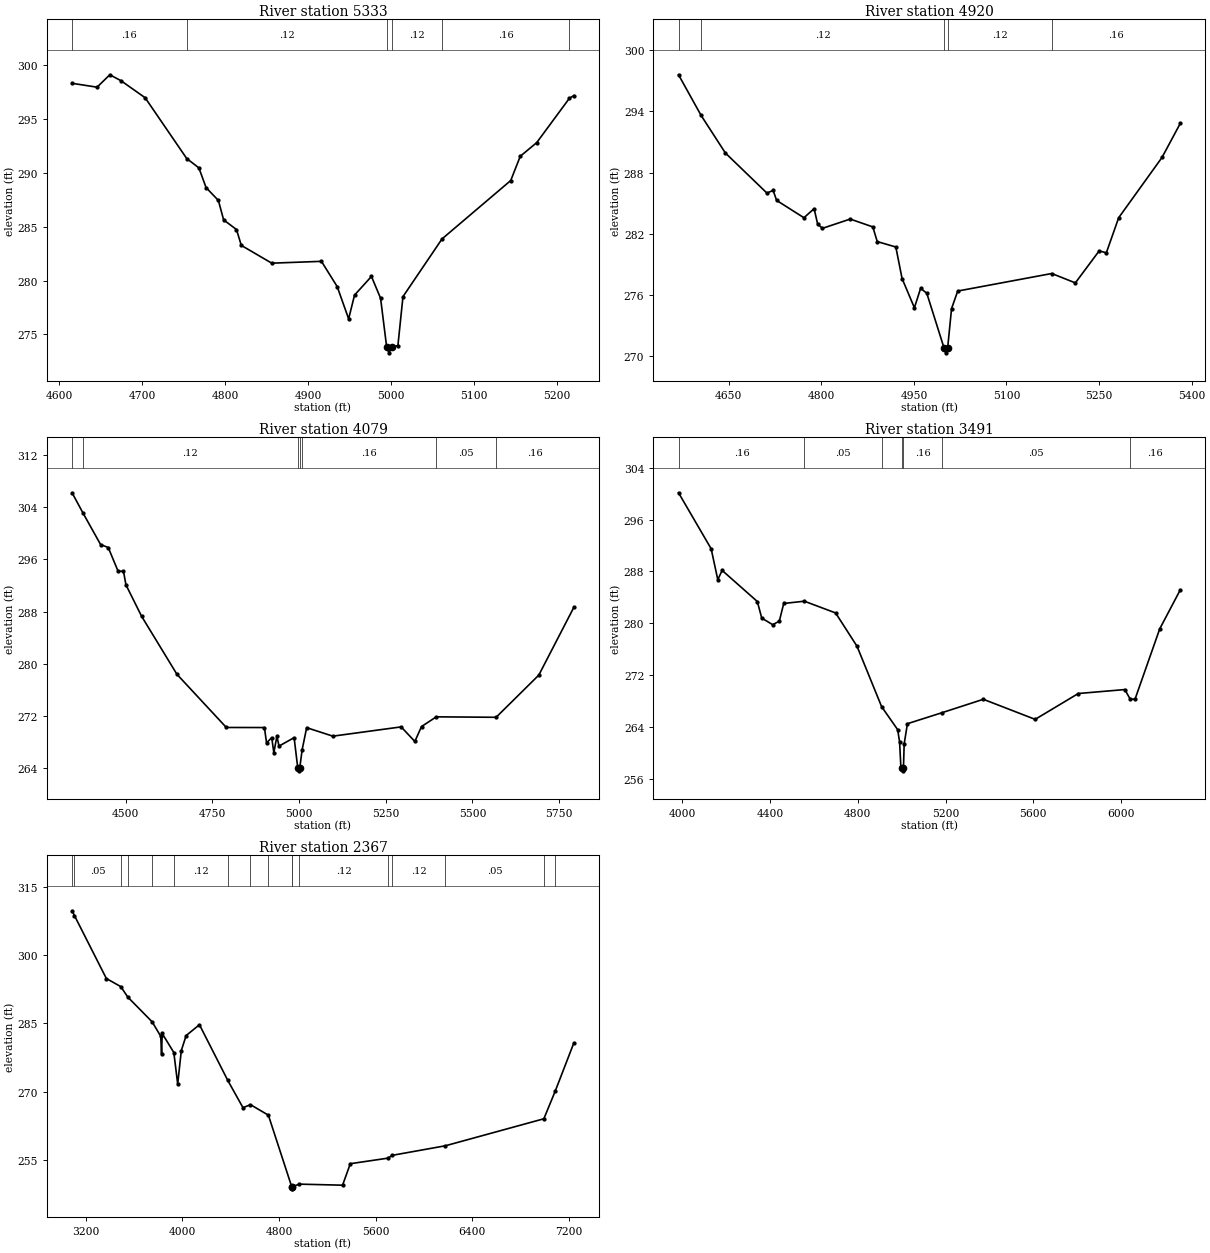
Type RM Length L Ch R = 1,5333,413,413,413
BEGIN DESCRIPTION:
UNT 129 IN CACR 4.0
END DESCRIPTION:
XS GIS Cut Line= 3
      3684719.82     10679149.15      3684494.10     10679288.06
      3684394.45     10679612.99
#Sta/Elev= 30
  4615.7  298.28  4645.8  297.92  4661.2  299.07  4674.7  298.52  4703.8  296.94
  4753.9  291.31  4768.6  290.44  4777.2  288.62  4792.1  287.42  4798.4  285.62
  4813.9  284.73  4819.7  283.26  4856.4  281.61  4916.3  281.78  4935.3  279.44
  4949.1  276.45  4956.2  278.65  4976.6  280.38  4987.6  278.36  4995.0  273.80
  4997.8  273.30  5001.0  273.80  5008.5  273.98  5014.6  278.51  5061.7  283.86
  5144.5  289.27  5156.0  291.52  5175.8  292.78  5215.3  296.90  5220.6  297.14
#Mann=6,-1,0
  4615.7    0.16       0  4753.9    0.12       0  4995.0    0.07       0
  5001.0    0.12       0  5061.7    0.16       0  5215.3    0.12       0
Bank Sta=4995,5001
Exp/Cntr=0.3,0.1

Type RM Length L Ch R = 1,4920,841,841,841
BEGIN DESCRIPTION:
UNT 129 IN CACR 3.0
END DESCRIPTION:
XS GIS Cut Line= 3
      3684376.89     10678762.93      3684233.68     10679040.67
      3684194.62     10679539.75
#Sta/Elev= 30
  4568.6  297.59  4605.2  293.60  4644.5  289.92  4711.8  285.99  4721.9  286.25
  4727.5  285.27  4771.8  283.57  4788.3  284.46  4794.0  282.95  4801.8  282.53
  4846.8  283.44  4883.4  282.67  4890.6  281.23  4920.7  280.70  4930.8  277.61
  4950.8  274.74  4960.9  276.65  4970.9  276.16  4998.7  270.82  5001.4  270.32
  5004.7  270.82  5011.0  274.66  5021.0  276.38  5173.4  278.10  5211.6  277.18
  5250.2  280.32  5261.8  280.13  5281.8  283.57  5352.0  289.48  5381.7  292.83
#Mann=5,-1,0
  4568.6    0.16       0  4605.2    0.12       0  4998.7    0.07       0
  5004.7    0.12       0  5173.4    0.16       0
Bank Sta=4998.7,5004.7
Exp/Cntr=0.3,0.1

Type RM Length L Ch R = 1,4079,588,588,588
BEGIN DESCRIPTION:
Mapping XS 5a43360d
END DESCRIPTION:
XS GIS Cut Line= 4
      3684376.90     10678476.44      3683942.88     10678706.46
      3683808.33     10678906.12      3684029.31     10679586.36
#Sta/Elev= 30
  4345.4  306.21  4376.8  303.12  4427.7  298.28  4449.7  297.83  4478.1  294.20
  4493.7  294.19  4500.8  292.11  4546.0  287.29  4647.9  278.41  4790.3  270.27
  4900.2  270.26  4906.3  267.90  4921.2  268.72  4927.3  266.42  4936.2  268.92
  4942.2  267.42  4985.8  268.71  4996.2  264.13  4999.0  263.63  5002.2  264.13
  5009.0  266.88  5022.0  270.24  5097.5  268.94  5294.5  270.36  5334.0  268.13
  5353.2  270.41  5395.9  271.90  5568.4  271.83  5691.5  278.29  5792.6  288.67
#Mann=7,-1,0
  4345.4    0.16       0  4376.8    0.12       0  4996.2    0.07       0
  5002.2    0.12       0  5009.0    0.16       0  5395.9    0.05       0
  5568.4    0.16       0
Bank Sta=4996.2,5002.2
Exp/Cntr=0.3,0.1

Type RM Length L Ch R = 1,3491,1124,1124,1124
BEGIN DESCRIPTION:
UNT 129 IN CACR 2.0
END DESCRIPTION:
XS GIS Cut Line= 4
      3684468.05     10678246.39      3683704.17     10678298.48
      3683487.15     10678610.98      3683946.81     10679656.04
#Sta/Elev= 30
  3982.4  300.12  4131.2  291.49  4161.3  286.74  4181.3  288.16  4341.7  283.37
  4361.7  280.82  4411.8  279.80  4441.9  280.35  4462.0  283.07  4556.0  283.42
  4698.6  281.61  4796.3  276.47  4908.4  267.17  4981.5  263.63  4990.1  261.78
  4996.2  257.84  5002.0  257.79  5004.7  257.29  5008.0  257.79  5011.1  261.42
  5025.9  264.55  5182.2  266.23  5372.0  268.31  5608.3  265.22  5805.0  269.20
  6017.2  269.81  6042.0  268.31  6063.9  268.35  6176.4  279.17  6270.2  285.18
#Mann=7,-1,0
  3982.4    0.16       0  4556.0    0.05       0  4908.4    0.16       0
  5002.0    0.07       0  5008.0    0.16       0  5182.2    0.05       0
  6042.0    0.16       0
Bank Sta=5002,5008
Exp/Cntr=0.3,0.1

Type RM Length L Ch R = 1,2367,0,0,0
BEGIN DESCRIPTION:
UNT 129 IN CACR 1.0
END DESCRIPTION:
XS GIS Cut Line= 4
      3684763.24     10677784.30      3682999.31     10677881.52
      3682714.58     10678173.19      3683852.40     10679796.65
#Sta/Elev= 30
  3085.7  309.70  3105.2  308.66  3369.8  294.85  3488.9  293.08  3547.3  290.78
  3748.5  285.37  3820.4  282.18  3827.1  278.33  3832.1  282.80  3928.6  278.63
  3960.7  271.71  3990.7  279.06  4030.8  282.35  4140.9  284.72  4375.4  272.52
  4501.5  266.53  4563.7  267.19  4711.9  264.89  4904.7  249.24  4907.4  248.74
  4910.7  249.24  4969.2  249.77  5326.5  249.54  5390.6  254.25  5702.8  255.47
  5738.7  256.09  6178.0  258.18  6993.8  264.10  7088.4  270.18  7242.4  280.73
#Mann=17,-1,0
  3085.7    0.16       0  3105.2    0.05       0  3488.9     0.1       0
  3547.3    0.05       0  3748.5    0.16       0  3928.6    0.12       0
  4375.4    0.16       0  4563.7    0.05       0  4711.9    0.16       0
  4904.7    0.07       0  4910.7    0.16       0  4969.2    0.12       0
  5702.8    0.16       0  5738.7    0.12       0  6178.0    0.05       0
  6993.8    0.16       0  7088.4    0.12       0
Bank Sta=4904.7,4910.7
Exp/Cntr=0.3,0.1

Chan Stop Cuts=-1