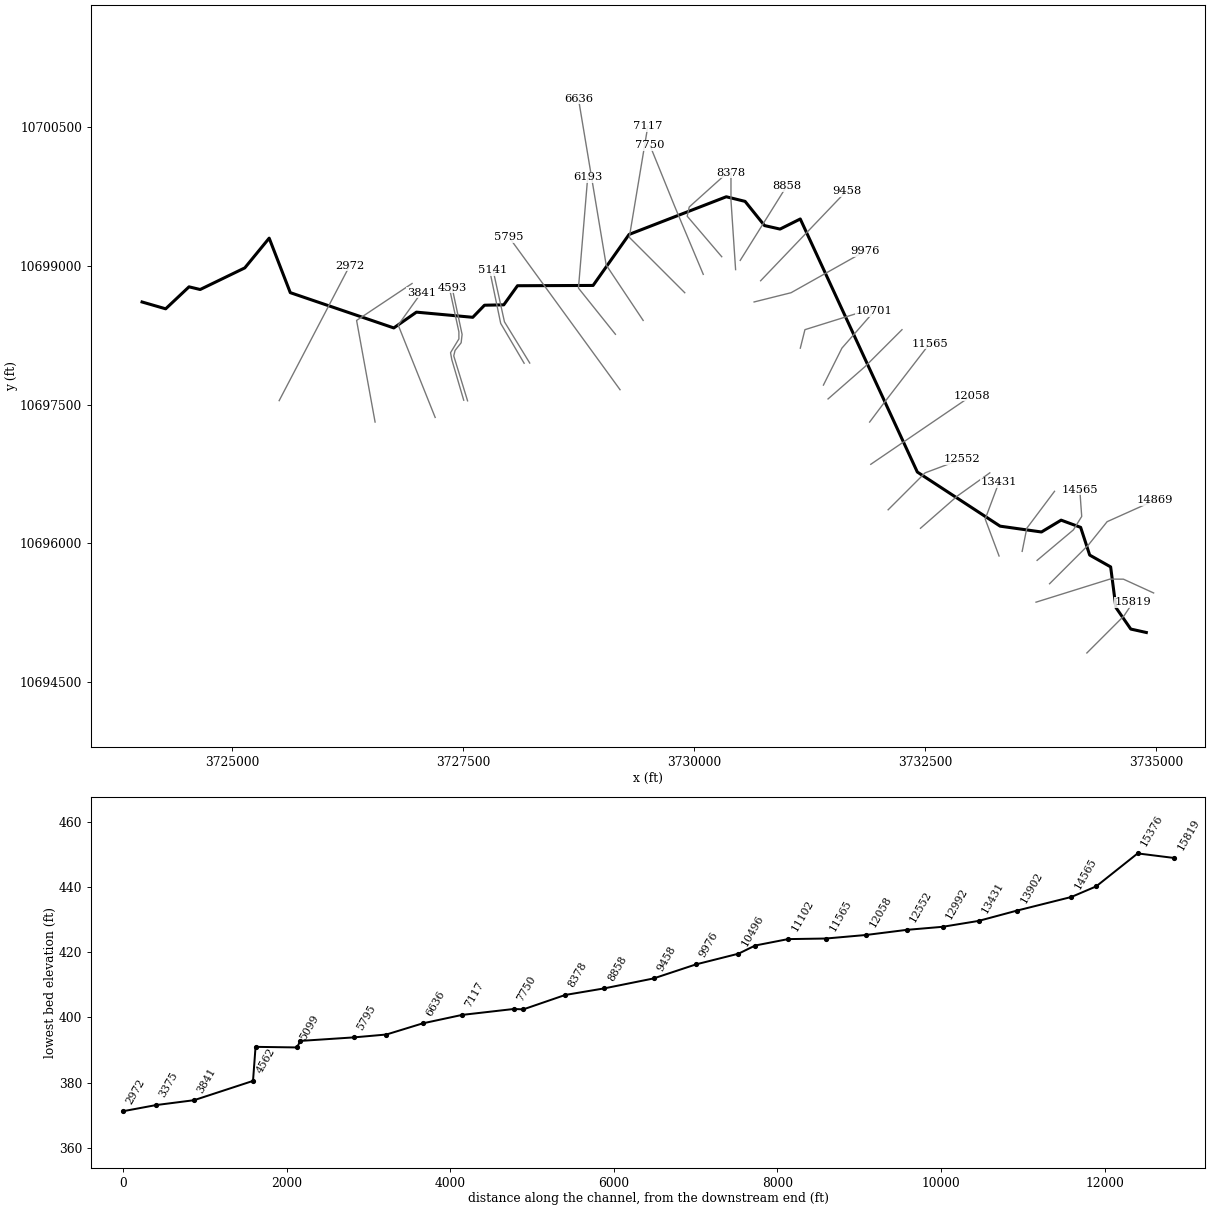
--- UNT 130 IN CACR.prj (project) ---

Proj Title=UNT 130 IN CACR Base Level Engineering
Current Plan=p01
Default Exp/Contr=0.3,0.1
English Units
Geom File=g01
Flow File=f01
Plan File=p01
Y Axis Title=Elevation
X Axis Title(PF)=Main Channel Distance
X Axis Title(XS)=Station
BEGIN DESCRIPTION:
UNT 130 IN CACR
END DESCRIPTION:
DSS Export Rating Curves= 0
DSS Export Rating Curve Sorted= 0
DSS Export Volume Flow Curves= 0
DXF OffsetX= 0
DXF OffsetY= 0
DXF ScaleX= 1
DXF ScaleY= 10

--- UNT 130 IN CACR.p01 (plan) ---

Plan Title=Multiple Run
Short Identifier=Multiple
Geom File=g01
Flow File=f01
Subcritical Flow
K Sum by GR= 0
Std Step Tol= 0.01
Critical Tol= 0.01
Num of Std Step Trials= 20
Max Error Tol= 0.3
Flow Tol Ratio= 0.001
Split Flow NTrial= 30
Split Flow Tol= 0.02
Split Flow Ratio= 0.02
Log Output Level= 0
Friction Slope Method= 1
Unsteady Friction Slope Method= 2
Unsteady Bridges Friction Slope Method= 1
Parabolic Critical Depth
Global Vel Dist=  1 , 1 , 1
Global Log Level= 0
CheckData=True
Encroach Param= -1, 0, 0, 0
BEGIN DESCRIPTION:
Multiple Run
END DESCRIPTION:

--- UNT 130 IN CACR.f01 (steady flow) ---

Flow Title=Multiple
Number of Profiles=7
Profile Names=10-year,25-year,50-year,1pct_min,100-year,1pct_plu,500-year
River Rch & RM= UNT 130 IN CACR,Reach-1,15819
    1432    2075    2642    2470    3341    4518    5367
River Rch & RM= UNT 130 IN CACR,Reach-1,13902
    1635    2371    3019    2821    3815    5159    6118
River Rch & RM= UNT 130 IN CACR,Reach-1,7750
    2326    3413    4383    4122    5575    7540    9067
River Rch & RM= UNT 130 IN CACR,Reach-1,1040
    2380    3492    4482    4214    5699    7708    9261
Boundary for River Rch & Prof#=UNT 130 IN CACR,Reach-1,1
Up Type=0
Dn Type=3
Dn Slope=0.005
Boundary for River Rch & Prof#=UNT 130 IN CACR,Reach-1,2
Up Type=0
Dn Type=3
Dn Slope=0.005
Boundary for River Rch & Prof#=UNT 130 IN CACR,Reach-1,3
Up Type=0
Dn Type=3
Dn Slope=0.005
Boundary for River Rch & Prof#=UNT 130 IN CACR,Reach-1,4
Up Type=0
Dn Type=3
Dn Slope=0.005
Boundary for River Rch & Prof#=UNT 130 IN CACR,Reach-1,5
Up Type=0
Dn Type=3
Dn Slope=0.005
Boundary for River Rch & Prof#=UNT 130 IN CACR,Reach-1,6
Up Type=0
Dn Type=3
Dn Slope=0.005
Boundary for River Rch & Prof#=UNT 130 IN CACR,Reach-1,7
Up Type=0
Dn Type=3
Dn Slope=0.005

--- UNT 130 IN CACR.g01 (geometry) ---

Geom Title=Existing Conditions
Program Version=4.10

River Reach=UNT 130 IN CACR ,Reach-1
Reach XY= 30
      3734892.68      10695031.8       3734724.5       10695069.
      3734563.75       10695302.      3734506.75       10695742.
        3734280.       10695870.      3734182.25       10696170.
        3733971.       10696248.      3733758.25       10696120.
        3733311.       10696183.       3732415.5       10696769.
      3731149.21     10699508.46      3730930.46     10699399.09
      3730762.44     10699437.15      3730552.25       10699699.
      3730348.75       10699749.      3729297.25       10699341.
        3728908.       10698789.      3728090.25       10698786.
      3727941.75       10698579.      3727733.25       10698575.
      3727606.25       10698444.        3726997.       10698500.
        3726752.       10698329.      3725632.25       10698711.
        3725404.       10699301.      3725140.25       10698979.
       3724657.5       10698745.      3724536.75       10698774.
      3724284.25       10698536.      3724028.75       10698610.

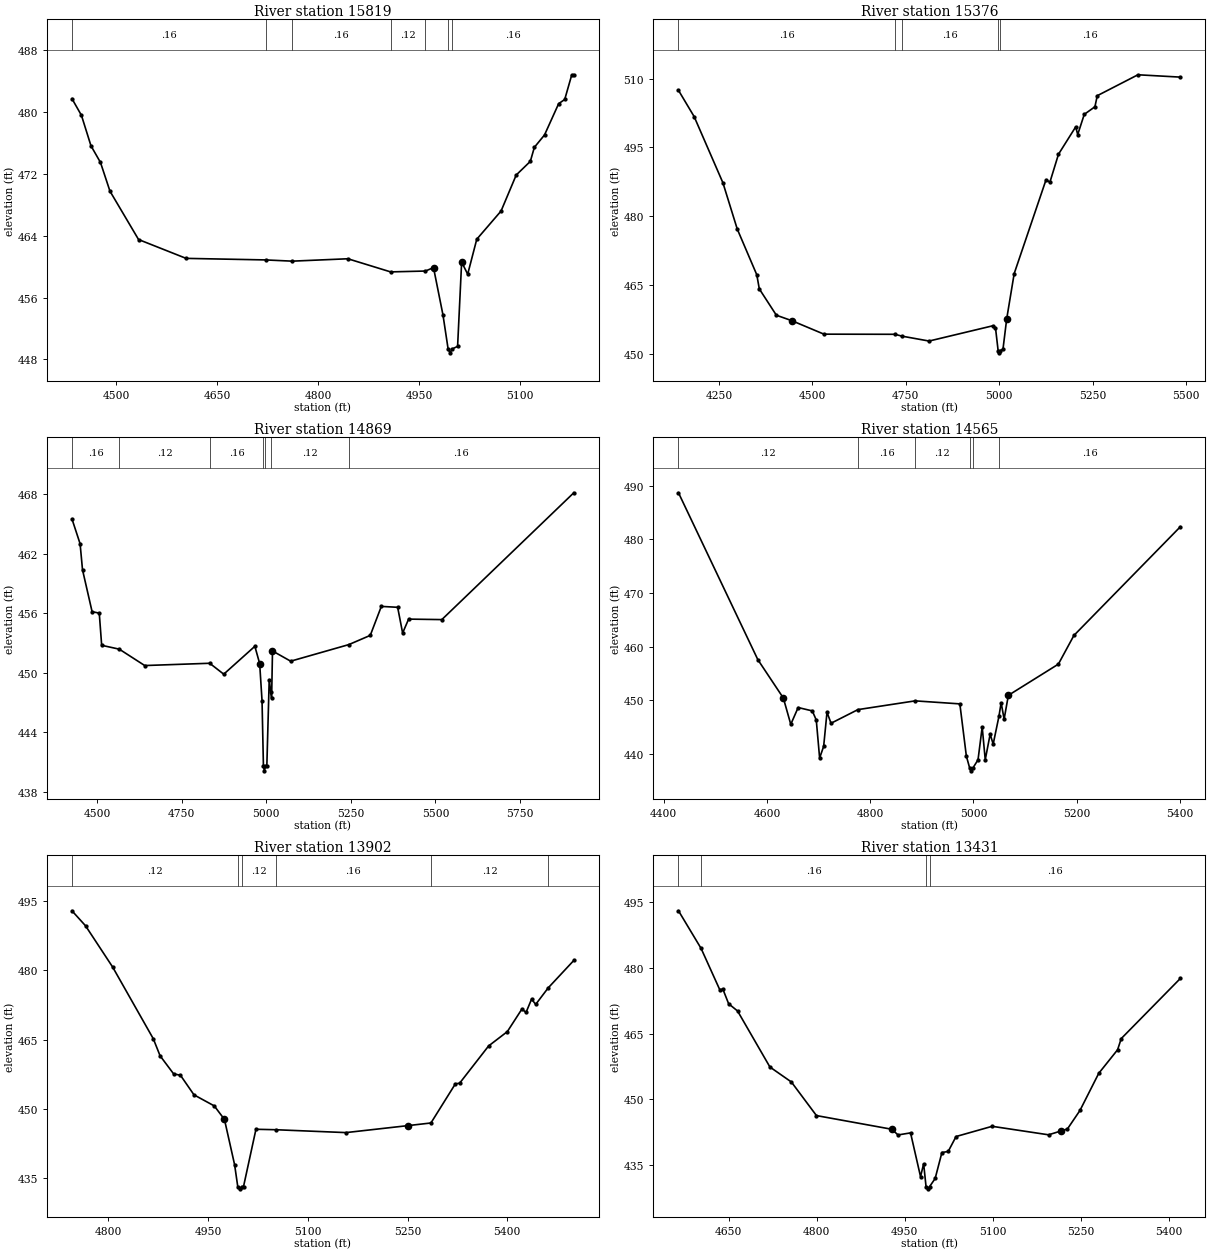
Type RM Length L Ch R = 1 ,15819   ,443,443,443
BEGIN DESCRIPTION:
UNT 130 IN CACR 32.0
END DESCRIPTION:
XS GIS Cut Line= 3
      3734249.63     10694810.21      3734649.61     10695210.19
      3734749.59     10695360.16
#Sta/Elev= 30
  4434.3  481.75  4448.4  479.59  4462.6  475.64  4476.7  473.49  4490.8  469.77
  4533.3  463.51    4604  461.07    4722  460.87  4761.7  460.71  4844.4  461.02
  4907.9  459.32  4959.6  459.43  4971.7  459.87  4985.8  453.73  4993.4  449.34
  4996.2  448.84  4999.4  449.34  5007.5  449.68  5013.5  460.59  5022.5  459.02
    5036  463.55  5072.1   467.2  5094.6  471.86  5115.6  473.63  5121.6  475.45
  5136.7  477.05  5157.7   481.1  5166.7  481.64  5177.2  484.84  5180.2  484.84
#Mann= 7 ,-1 , 0
  4434.3     .16       0    4722     .12       0  4761.7     .16       0
  4907.9     .12       0  4959.6     .16       0  4993.4     .07       0
  4999.4     .16       0
Bank Sta=4971.7,5013.5
XS Rating Curve= 0 ,0
Exp/Cntr=0.3,0.1

Type RM Length L Ch R = 1 ,15376   ,507,507,507
BEGIN DESCRIPTION:
UNT 130 IN CACR 31.0
END DESCRIPTION:
XS GIS Cut Line= 4
      3733699.61     10695360.19      3734499.61     10695610.19
      3734645.24     10695609.12      3734971.63     10695459.81
#Sta/Elev= 30
  4141.6  507.44  4183.5  501.72  4260.5  487.29  4298.8  477.22  4351.1  467.25
  4357.9  464.16  4403.5  458.43  4445.4  457.22  4530.8   454.3  4720.8  454.27
    4740  453.86  4812.1   452.8  4982.3  456.12  4989.8  455.68  4996.8  450.73
  4999.5  450.23  5002.8  450.73  5009.8  451.01  5019.8  457.65  5039.8   467.5
  5125.1  487.97  5135.3   487.4  5158.3  493.51  5204.3  499.47  5209.8  497.81
  5227.3   502.2  5255.8  503.86  5262.1  506.27  5370.9  510.83  5484.3  510.32
#Mann= 5 ,-1 , 0
  4141.6     .16       0  4720.8     .12       0    4740     .16       0
  4996.8     .07       0  5002.8     .16       0
Bank Sta=4445.4,5019.8
XS Rating Curve= 0 ,0
Exp/Cntr=0.3,0.1

Type RM Length L Ch R = 1 ,14869   ,304,304,304
BEGIN DESCRIPTION:
Mapping XS 62783c18
END DESCRIPTION:
XS GIS Cut Line= 4
      3733846.15     10695559.53      3734265.43     10695978.81
      3734468.55     10696231.41      3734984.17     10696463.17
#Sta/Elev= 30
  4426.3  465.52  4450.4  463.01  4457.5  460.39  4485.8  456.17    4507  456.02
  4514.1  452.78  4566.2  452.39  4641.3  450.74  4833.2  450.97  4874.7  449.87
  4966.6  452.68  4980.8  450.94  4987.8   447.2  4991.9  440.63  4994.7  440.13
  4997.9  440.63    5002  440.65    5009  449.32  5013.5  448.12  5016.1  447.43
  5018.7  452.21  5072.4  451.18  5244.1  452.85  5307.5  453.78  5340.2   456.7
  5388.4  456.61  5403.1  454.02  5420.8  455.42  5518.9  455.37  5908.7  468.15
#Mann= 7 ,-1 , 0
  4426.3     .16       0  4566.2     .12       0  4833.2     .16       0
  4991.9     .07       0  4997.9     .16       0  5013.5     .12       0
  5244.1     .16       0
Bank Sta=4980.8,5018.7
XS Rating Curve= 0 ,0
Exp/Cntr=0.3,0.1

Type RM Length L Ch R = 1 ,14565   ,663,663,663
BEGIN DESCRIPTION:
UNT 130 IN CACR 29.0
END DESCRIPTION:
XS GIS Cut Line= 4
      3733711.11     10695812.65       3734103.5     10696142.54
      3734193.78     10696288.37        3734173.     10696575.87
#Sta/Elev= 30
  4428.5  488.66  4582.3  457.58  4631.7  450.44  4646.1  445.54  4660.4  448.67
  4687.8  448.04  4695.5  446.34    4702  439.27  4709.8  441.43  4716.3   447.8
  4724.1  445.74  4776.2  448.28  4887.1  449.91  4973.7  449.35  4986.3  439.63
  4992.8  437.38  4995.5  436.88  4998.8  437.38  5008.9  438.93    5017  445.03
  5022.9  438.94  5032.4   443.7  5038.3  441.86  5049.4  447.01  5053.7  449.56
  5059.5  446.51  5067.7  450.94  5164.6  456.75  5194.7  462.09  5400.9  482.33
#Mann= 6 ,-1 , 0
  4428.5     .12       0  4776.2     .16       0  4887.1     .12       0
  4992.8     .07       0  4998.8     .12       0  5049.4     .16       0
Bank Sta=4631.7,5067.7
XS Rating Curve= 0 ,0
Exp/Cntr=0.3,0.1

Type RM Length L Ch R = 1 ,13902   ,471,471,471
BEGIN DESCRIPTION:
UNT 130 IN CACR 28.0
END DESCRIPTION:
XS GIS Cut Line= 3
      3733549.61      10695910.2      3733599.61     10696160.19
      3733899.58     10696560.16
#Sta/Elev= 30
  4745.2  492.84  4765.6   489.6  4806.4  480.68  4867.6  465.16  4877.8  461.48
  4898.2  457.57  4908.4  457.28  4928.8  453.04  4959.3  450.65  4974.6  447.73
  4989.9  437.92  4994.6  433.22  4997.3  432.72  5000.6  433.22  5003.3  433.22
    5022   445.6  5051.8   445.5  5157.4  444.88  5250.1  446.38  5285.2  446.96
    5322  455.43  5328.3  455.55    5372  463.62  5400.1  466.71    5422  471.58
  5428.3  470.87  5436.6  473.74  5442.8   472.6  5461.6  476.17  5500.1   482.1
#Mann= 6 ,-1 , 0
  4745.2     .12       0  4994.6     .07       0  5000.6     .12       0
  5051.8     .16       0  5285.2     .12       0  5461.6     .07       0
Bank Sta=4974.6,5250.1
XS Rating Curve= 0 ,0
Exp/Cntr=0.3,0.1

Type RM Length L Ch R = 1 ,13431   ,439,439,439
BEGIN DESCRIPTION:
UNT 130 IN CACR 27.0
END DESCRIPTION:
XS GIS Cut Line= 3
       3733299.6      10695860.2      3733149.61     10696260.19
      3733299.61      10696660.2
#Sta/Elev= 30
  4564.6  493.01  4603.1  484.42  4634.9  474.99  4640.2  475.12    4650  471.79
  4665.2  470.14  4720.3  457.35  4756.8  453.94  4799.5  446.27  4927.7  443.15
  4938.4  441.85  4959.7  442.32  4976.7  432.34    4982  435.27  4986.1  430.05
  4988.9  429.55  4992.1  430.05  5001.6  431.91  5013.1  437.84  5023.8  438.08
  5037.2  441.49  5098.6  443.82  5194.7  441.88  5216.1  442.77  5226.7   443.2
  5248.1  447.43  5280.1  455.91  5312.2  461.29  5318.4  463.84    5419  477.56
#Mann= 4 ,-1 , 0
  4564.6     .12       0  4603.1     .16       0  4986.1     .07       0
  4992.1     .16       0
Bank Sta=4927.7,5216.1
XS Rating Curve= 0 ,0
Exp/Cntr=0.3,0.1

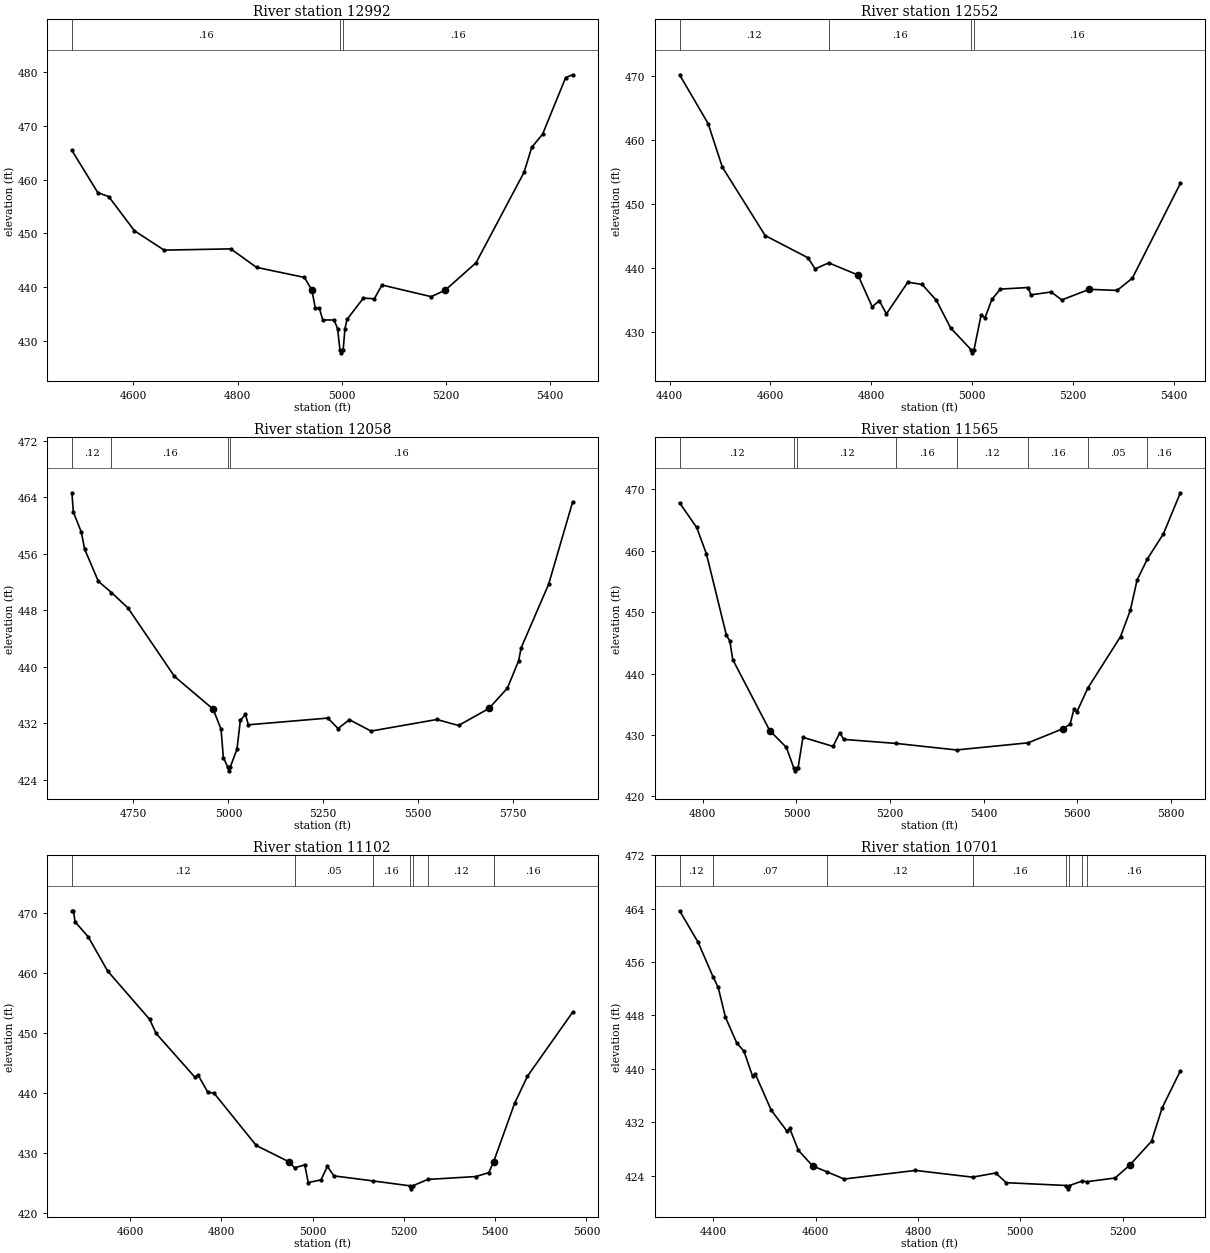
Type RM Length L Ch R = 1 ,12992   ,440,440,440
BEGIN DESCRIPTION:
UNT 130 IN CACR 26.0
END DESCRIPTION:
XS GIS Cut Line= 3
       3732449.6     10696160.18      3732849.61     10696510.19
      3733199.58     10696760.17
#Sta/Elev= 30
  4481.9  465.45  4531.7  457.58  4552.6  456.85    4602  450.48  4658.9  446.88
    4787  447.11  4836.4  443.67  4928.5  441.79  4942.7  439.44  4949.3  436.08
  4956.9   436.1  4963.6  433.87  4985.4  433.87  4992.1  432.24  4996.7  428.25
  4999.4  427.75  5002.7  428.25  5006.3  432.27  5010.1  433.96  5041.7  437.96
  5062.6  437.81  5077.3  440.38  5171.9  438.21    5199  439.43    5258  444.53
  5350.1  461.36  5364.9  466.02  5385.8  468.48    5430     479  5443.5  479.53
#Mann= 3 ,-1 , 0
  4481.9     .16       0  4996.7     .07       0  5002.7     .16       0
Bank Sta=4942.7,5199
XS Rating Curve= 0 ,0
Exp/Cntr=0.3,0.1

Type RM Length L Ch R = 1 ,12552   ,494,494,494
BEGIN DESCRIPTION:
UNT 130 IN CACR 25.0
END DESCRIPTION:
XS GIS Cut Line= 3
      3732099.61     10696360.19      3732499.61     10696760.19
      3732899.63      10696910.2
#Sta/Elev= 30
  4419.9   470.2  4476.5  462.57  4504.7  455.78  4589.6  445.11  4674.5  441.64
  4688.6  439.91  4715.6  440.85  4773.4  438.96  4801.7  434.01  4815.9  434.93
    4830  432.89  4872.4  437.84  4900.7  437.48    4929  435.01  4957.3  430.69
  4997.7  427.31  5000.5  426.81  5003.7  427.31  5017.6  432.67  5025.6  432.31
    5039  435.14  5055.9  436.76  5111.1     437  5116.4  435.86  5156.5   436.3
  5177.8  435.07  5232.1  436.72  5287.3  436.55  5317.5  438.45  5412.8  453.26
#Mann= 4 ,-1 , 0
  4419.9     .12       0  4715.6     .16       0  4997.7     .07       0
  5003.7     .16       0
Bank Sta=4773.4,5232.1
XS Rating Curve= 0 ,0
Exp/Cntr=0.3,0.1

Type RM Length L Ch R = 1 ,12058   ,493,493,493
BEGIN DESCRIPTION:
Mapping XS 2c452b02
END DESCRIPTION:
XS GIS Cut Line= 2
      3731911.86     10696852.62       3733001.8     10697595.45
#Sta/Elev= 30
  4587.8  464.62  4591.7  461.88  4612.7  459.04  4621.4  456.64  4657.5  452.08
  4691.9   450.5  4735.4  448.32    4858  438.62  4959.7  433.99  4980.7  431.14
  4986.7  427.13  4998.7  425.75  5001.4  425.25  5004.7  425.75  5022.6  428.31
  5031.5  432.39  5044.9  433.25  5052.5  431.77  5261.9  432.72  5288.9  431.24
  5318.8  432.49  5375.7  430.88  5549.2  432.52  5606.1  431.67  5686.3  434.08
  5734.8  436.96  5764.6  440.85    5771  442.65  5843.6  451.69  5906.8  463.34
#Mann= 4 ,-1 , 0
  4587.8     .12       0  4691.9     .16       0  4998.7     .07       0
  5004.7     .16       0
Bank Sta=4959.7,5686.3
XS Rating Curve= 0 ,0
Exp/Cntr=0.3,0.1

Type RM Length L Ch R = 1 ,11565   ,463,463,463
BEGIN DESCRIPTION:
UNT 130 IN CACR 23.0
END DESCRIPTION:
XS GIS Cut Line= 3
      3731899.61     10697310.19      3732049.61     10697510.19
      3732549.63     10698160.22
#Sta/Elev= 30
  4750.4   467.8  4786.9  463.79  4807.7   459.5  4850.4  446.24  4857.7  445.32
  4863.9  442.29  4943.1   430.7  4978.5  427.99  4994.3  424.66    4997  424.16
  5000.3  424.66  5003.6  424.66    5014  429.62  5078.3  428.14  5092.8  430.38
    5101  429.28  5213.6  428.62  5342.2  427.56    5495  428.72  5570.3  431.04
  5584.8  431.75  5593.1  434.19  5599.4  433.76  5622.4  437.59  5692.7  446.03
  5713.5   450.3    5728  455.23  5749.9  458.65  5784.2  462.75  5820.5  469.44
#Mann= 8 ,-1 , 0
  4750.4     .12       0  4994.3     .07       0  5000.3     .12       0
  5213.6     .16       0  5342.2     .12       0    5495     .16       0
  5622.4     .05       0  5749.9     .16       0
Bank Sta=4943.1,5570.3
XS Rating Curve= 0 ,0
Exp/Cntr=0.3,0.1

Type RM Length L Ch R = 1 ,11102   ,401,401,401
BEGIN DESCRIPTION:
UNT 130 IN CACR 22.0
END DESCRIPTION:
XS GIS Cut Line= 3
      3731449.59     10697560.17      3731849.61     10697910.19
       3732249.6     10698310.18
#Sta/Elev= 30
  4472.7  470.34    4476  470.34  4479.8  468.49  4508.3  466.02    4551   460.3
  4643.1  452.23  4657.3  449.88  4741.8  442.63  4749.4  442.92  4770.3  440.12
  4784.5   439.9  4876.6  431.21  4947.8  428.51  4960.8  427.48  4982.9  427.98
  4990.5  425.03  5018.4  425.47  5032.5  427.72  5046.7  426.14  5131.5  425.31
  5213.4  424.48  5216.1  423.98  5219.4  424.48  5252.5  425.55  5357.8  426.03
  5386.1  426.68  5396.7  428.49  5442.6  438.22  5470.9  442.76  5569.9  453.44
#Mann= 7 ,-1 , 0
  4472.7     .12       0  4960.8     .05       0  5131.5     .16       0
  5213.4     .03       0  5219.4     .16       0  5252.5     .12       0
  5396.7     .16       0
Bank Sta=4947.8,5396.7
XS Rating Curve= 0 ,0
Exp/Cntr=0.3,0.1

Type RM Length L Ch R = 1 ,10701   ,205,205,205
BEGIN DESCRIPTION:
UNT 130 IN CACR 21.0
END DESCRIPTION:
XS GIS Cut Line= 3
       3731399.6     10697710.16      3731599.61     10698110.19
      3731949.58     10698510.15
#Sta/Elev= 30
  4334.3  463.68  4370.7  458.93  4399.6   453.8  4409.8  452.19  4423.8  447.75
  4446.1  443.86  4460.1  442.65  4476.9  438.89  4482.5  439.19  4513.2  433.83
    4544  430.68  4549.5  431.07  4566.3  427.81  4594.3  425.45  4623.2  424.54
  4655.8  423.49  4795.3  424.78  4906.8  423.77  4951.9  424.39  4972.8  422.94
  5090.3  422.52  5093.1  422.02  5096.3  422.52  5121.7   423.2  5129.8  423.08
  5185.4  423.65  5213.9  425.56  5256.6  429.15  5277.5  434.17    5313   439.7
#Mann= 8 ,-1 , 0
  4334.3     .12       0  4399.6     .07       0  4623.2     .12       0
  4906.8     .16       0  5090.3     .07       0  5096.3     .16       0
  5121.7     .12       0  5129.8     .16       0
Bank Sta=4594.3,5213.9
XS Rating Curve= 0 ,0
Exp/Cntr=0.3,0.1

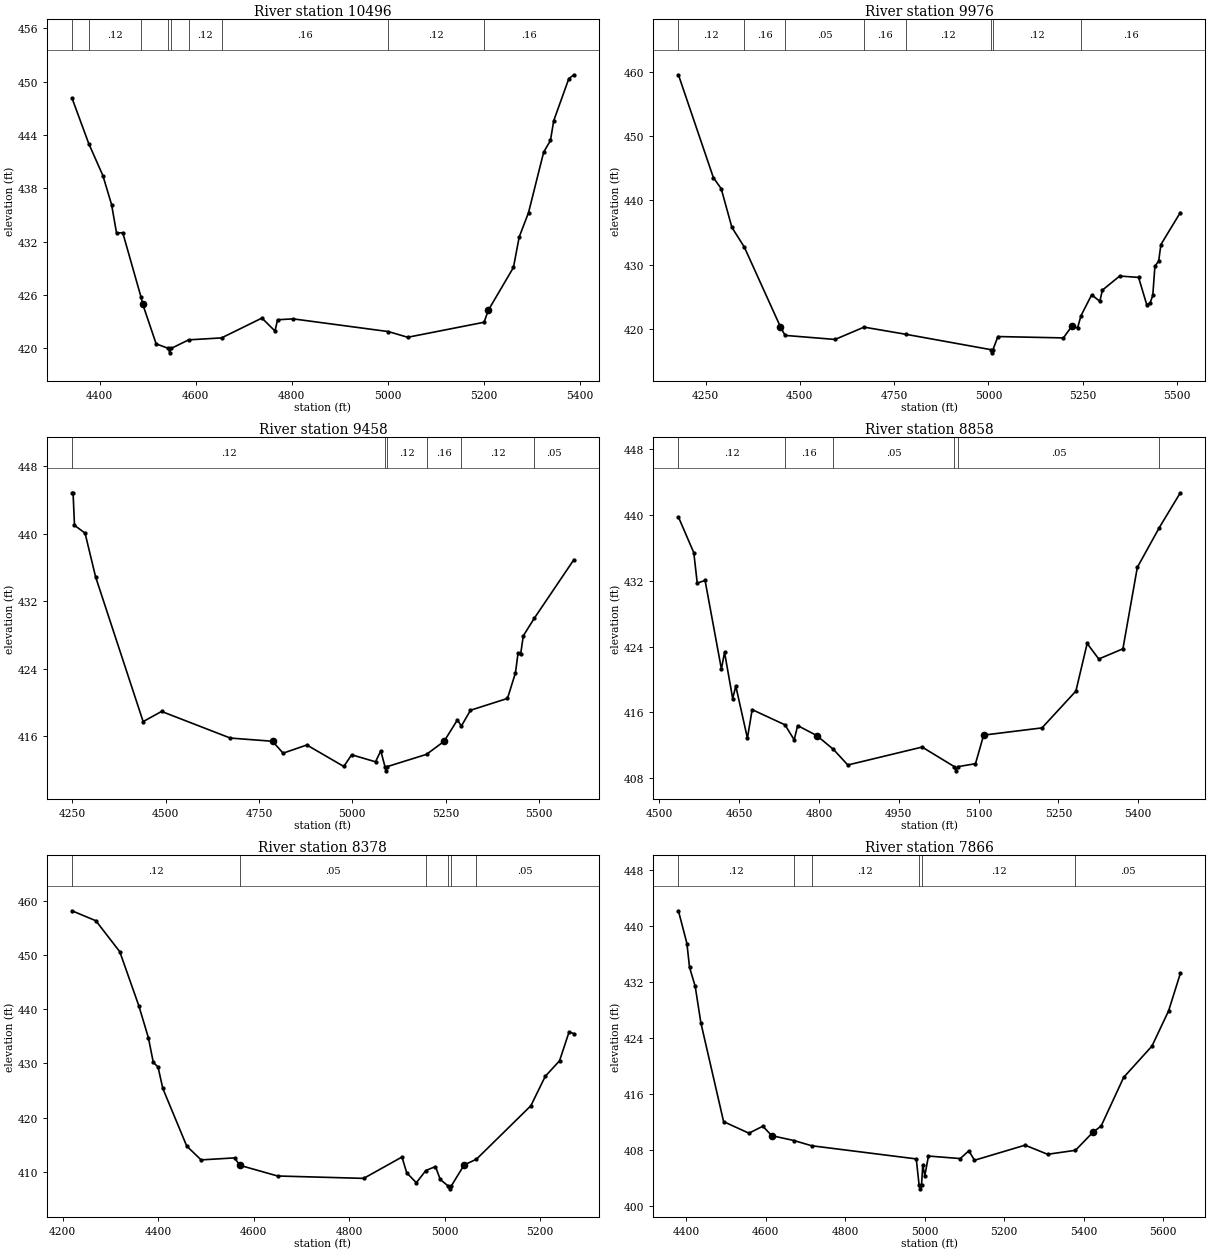
Type RM Length L Ch R = 1 ,10496   ,520,520,520
BEGIN DESCRIPTION:
UNT 130 IN CACR 20.0
END DESCRIPTION:
XS GIS Cut Line= 3
      3731149.61     10698110.17      3731199.61     10698310.19
      3731999.59     10698560.18
#Sta/Elev= 30
  4342.5  448.17  4377.6  443.02  4406.9  439.44    4425  436.17  4435.3  432.98
  4448.2  433.02    4486  425.82  4489.4  425.04  4517.7  420.52  4543.1  420.01
  4545.8  419.51  4549.1  420.01  4585.3  420.97  4653.8  421.19  4737.8  423.42
    4765  421.96  4770.3  423.23  4802.7  423.33    5001   421.9  5041.1  421.26
    5200  422.95  5208.7  424.29  5261.1  429.11  5273.1  432.54  5292.5  435.28
    5324  442.08  5338.1  443.39  5344.9  445.61  5376.3  450.34  5386.8  450.78
#Mann= 9 ,-1 , 0
  4342.5     .16       0  4377.6     .12       0    4486     .16       0
  4543.1     .07       0  4549.1     .16       0  4585.3     .12       0
  4653.8     .16       0    5001     .12       0    5200     .16       0
Bank Sta=4489.4,5208.7
XS Rating Curve= 0 ,0
Exp/Cntr=0.3,0.1

Type RM Length L Ch R = 1 ,9976    ,518,518,518
BEGIN DESCRIPTION:
UNT 130 IN CACR 19.0
END DESCRIPTION:
XS GIS Cut Line= 3
      3730649.64      10698610.2      3731049.61     10698710.19
      3731849.65     10699160.21
#Sta/Elev= 30
  4178.2  459.61  4270.9  443.56  4291.6  441.84  4319.9  435.81    4353  432.71
  4448.7  420.27  4460.9  418.95  4593.3  418.32  4670.2  420.24  4781.4  419.12
  5005.9  416.73  5008.7  416.23  5011.9  416.73  5024.9  418.77  5198.6  418.56
  5221.5  420.45  5235.9   420.1  5245.3  422.04  5273.5  425.29  5295.1  424.26
  5301.8  426.01  5347.7  428.21  5397.8     428  5419.4  423.74    5428  423.96
  5435.4  425.19  5441.1  429.75    5451  430.55    5457  433.13  5508.4  438.12
#Mann= 8 ,-1 , 0
  4178.2     .12       0    4353     .16       0  4460.9     .05       0
  4670.2     .16       0  4781.4     .12       0  5005.9     .07       0
  5011.9     .12       0  5245.3     .16       0
Bank Sta=4448.7,5221.5
XS Rating Curve= 0 ,0
Exp/Cntr=0.3,0.1

Type RM Length L Ch R = 1 ,9458    ,600,600,600
BEGIN DESCRIPTION:
UNT 130 IN CACR 18.0
END DESCRIPTION:
XS GIS Cut Line= 2
      3730720.49     10698839.73      3731649.25     10699811.89
#Sta/Elev= 30
  4248.8  444.84  4251.8  444.84  4255.6  440.99  4283.9  440.06  4312.2  434.88
  4439.5  417.76  4488.9  418.96  4672.9  415.81  4786.1  415.43  4814.4  414.02
    4878  414.99    4977  412.45  4998.1  413.83    5062     413  5076.1   414.3
  5087.3  412.43    5090  411.93  5093.3  412.43  5198.6  413.88  5245.6  415.42
  5281.2  417.94  5292.1  417.24  5316.4   419.1  5415.5   420.5  5436.9  423.53
  5443.8  425.88    5451  425.81  5457.9  427.91  5487.2  429.98  5593.3  436.92
#Mann= 6 ,-1 , 0
  4248.8     .12       0  5087.3     .07       0  5093.3     .12       0
  5198.6     .16       0  5292.1     .12       0  5487.2     .05       0
Bank Sta=4786.1,5245.6
XS Rating Curve= 0 ,0
Exp/Cntr=0.3,0.1

Type RM Length L Ch R = 1 ,8858    ,480,480,480
BEGIN DESCRIPTION:
UNT 130 IN CACR 17.0
END DESCRIPTION:
XS GIS Cut Line= 3
      3730499.61     10699060.19      3730749.61     10699460.19
      3730999.61     10699860.19
#Sta/Elev= 30
  4535.7  439.75  4564.6  435.41  4571.1  431.71  4585.8  432.04  4616.5  421.27
  4622.4   423.3  4637.7  417.69  4643.6  419.19  4665.4  412.87  4674.3  416.34
    4736  414.49  4753.3  412.67  4759.8   414.4  4795.7  413.19  4827.2   411.5
  4854.1  409.61  4993.8  411.79  5054.5   409.4  5057.3   408.9  5060.5   409.4
  5094.1  409.77  5109.4  413.24  5219.1  414.12  5282.8  418.59    5304  424.38
  5325.8  422.49  5371.2  423.73  5398.3  433.63  5439.6  438.46  5479.1  442.69
#Mann= 6 ,-1 , 0
  4535.7     .12       0    4736     .16       0  4827.2     .05       0
  5054.5     .03       0  5060.5     .05       0  5439.6     .16       0
Bank Sta=4795.7,5109.4
XS Rating Curve= 0 ,0
Exp/Cntr=0.3,0.1

Type RM Length L Ch R = 1 ,8378    ,512,512,512
BEGIN DESCRIPTION:
UNT 130 IN CACR 16.0
END DESCRIPTION:
XS GIS Cut Line= 3
      3730449.61      10698960.2      3730399.61     10699710.19
      3730399.61     10700010.24
#Sta/Elev= 30
  4219.3  458.17  4269.4  456.33  4319.5  450.62  4359.6   440.6  4379.6  434.71
  4389.7  430.21  4399.7  429.34  4409.7  425.39  4459.8  414.76  4489.9  412.21
    4560  412.58  4571.1  411.21  4650.2  409.24  4830.6   408.8  4910.8  412.74
  4920.8  409.83  4940.9  407.99  4960.8  410.25    4981  410.98    4991   408.6
    5008  407.37  5010.7  406.87    5014  407.37    5041  411.27  5066.9  412.34
    5181  422.21    5211  427.62    5241  430.49    5261  435.82    5271  435.51
#Mann= 6 ,-1 , 0
  4219.3     .12       0  4571.1     .05       0  4960.8     .16       0
    5008     .07       0    5014     .16       0  5066.9     .05       0
Bank Sta=4571.1,5041
XS Rating Curve= 0 ,0
Exp/Cntr=0.3,0.1

Type RM Length L Ch R = 1 ,7866    ,116,116,116
BEGIN DESCRIPTION:
UNT 130 IN CACR 15.0
END DESCRIPTION:
XS GIS Cut Line= 4
      3730299.48     10699100.09      3729926.19     10699538.49
      3729947.89     10699638.31      3730381.94     10700028.95
#Sta/Elev= 30
  4380.9  442.14  4402.3  437.47  4408.8  434.08  4423.1  431.35  4437.4  426.14
  4494.5  412.05  4558.2   410.4  4593.3   411.4  4615.3  410.05  4671.7  409.35
  4715.7  408.61  4978.9  406.73  4986.1  402.96  4988.9  402.46  4992.1  402.96
  4995.3  405.83  5000.4  404.36  5009.6  407.14  5089.4  406.78  5111.1  407.88
  5125.3  406.54  5252.4  408.69  5309.2  407.39  5379.2  407.96  5422.8  410.52
  5443.7  411.42  5500.5  418.38  5571.5  422.83  5613.4  427.87  5642.8  433.19
#Mann= 6 ,-1 , 0
  4380.9     .12       0  4671.7     .05       0  4715.7     .12       0
  4986.1     .07       0  4992.1     .12       0  5379.2     .05       0
Bank Sta=4615.3,5422.8
XS Rating Curve= 0 ,0
Exp/Cntr=0.3,0.1

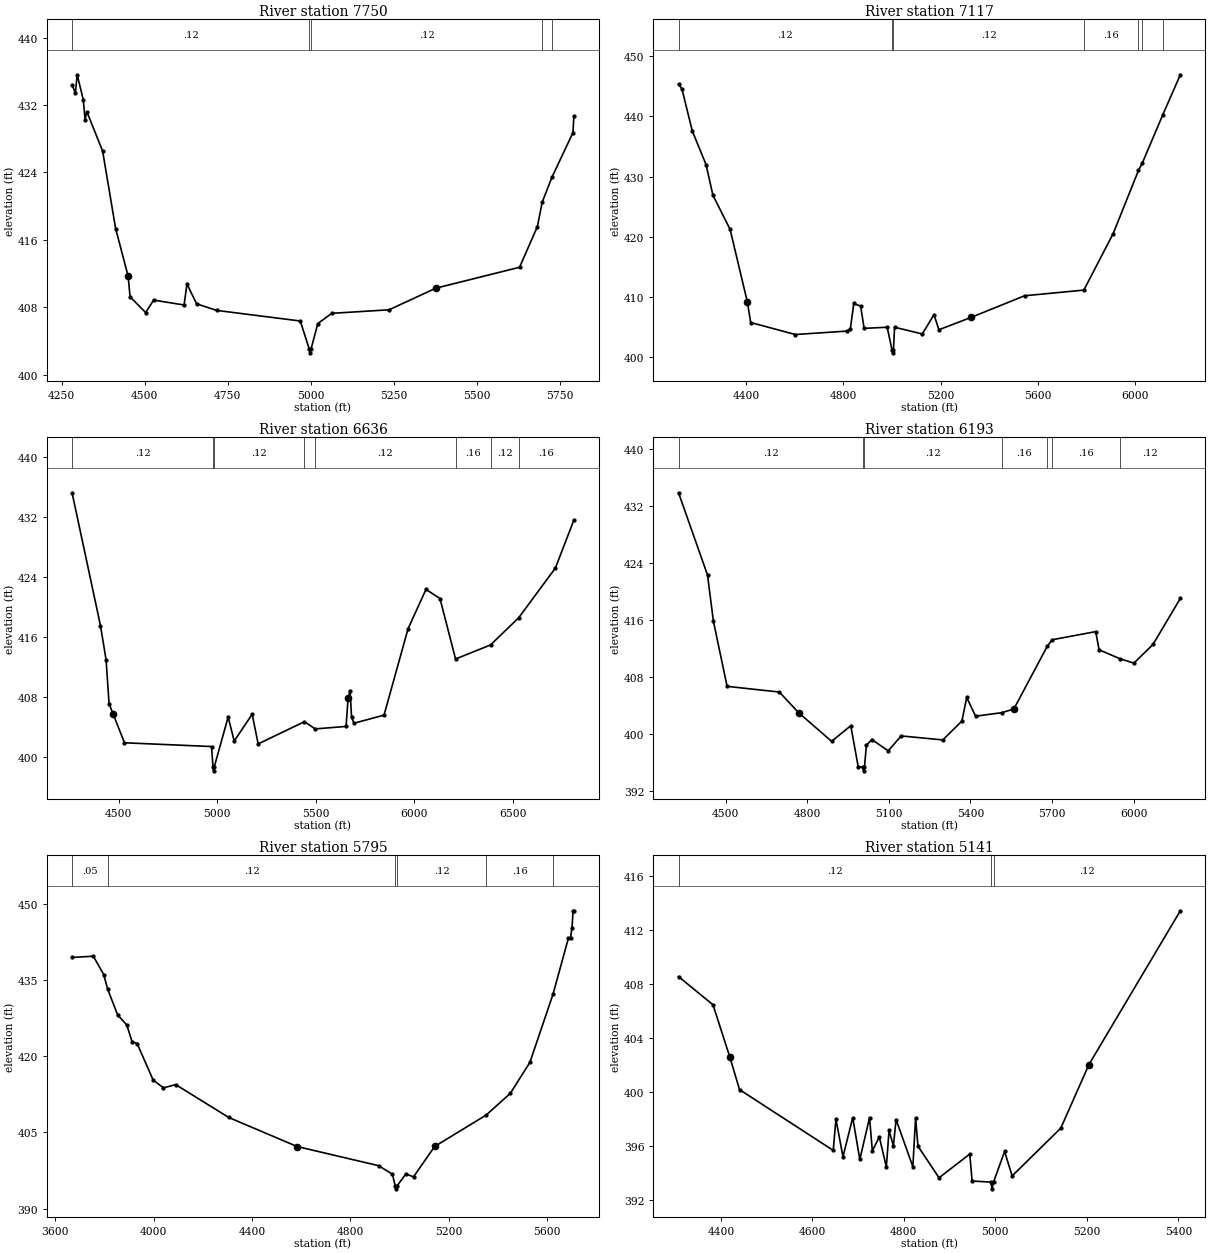
Type RM Length L Ch R = 1 ,7750    ,633,633,633
BEGIN DESCRIPTION:
UNT 130 IN CACR 14.0
END DESCRIPTION:
XS GIS Cut Line= 3
      3730099.81     10698909.12      3729791.64     10699642.65
      3729522.86     10700305.92
#Sta/Elev= 30
  4280.9  434.39  4290.9  433.44  4296.3  435.59  4314.6  432.64  4320.1  430.26
  4325.5  431.21    4373  426.52  4412.2  417.31  4449.7  411.69  4455.6  409.23
  4502.6  407.36  4526.4  408.84  4618.3  408.26  4626.9  410.75    4656   408.4
  4715.9  407.62  4968.2  406.36  4994.9  403.08  4997.7  402.58  5000.9  403.08
  5021.1  406.06    5063  407.27  5235.7  407.69    5376  410.25  5628.7  412.74
  5682.3  417.56  5696.9  420.47  5726.6  423.46  5789.5  428.72  5792.2  430.65
#Mann= 5 ,-1 , 0
  4280.9     .12       0  4994.9     .07       0  5000.9     .12       0
  5696.9     .16       0  5726.6     .05       0
Bank Sta=4449.7,5376
XS Rating Curve= 0 ,0
Exp/Cntr=0.3,0.1

Type RM Length L Ch R = 1 ,7117    ,481,481,481
BEGIN DESCRIPTION:
UNT 130 IN CACR 13.0
END DESCRIPTION:
XS GIS Cut Line= 3
      3729899.63     10698710.16      3729299.61     10699310.19
      3729499.61     10700510.17
#Sta/Elev= 30
  4121.1  445.33  4135.3  444.53  4177.7  437.58  4234.3     432  4262.6  426.91
  4333.3  421.25    4404  409.25  4418.1  405.79    4602   403.8  4814.1  404.37
  4828.2  404.74  4842.4  408.95  4870.7   408.5  4884.8  404.82  4979.8  405.01
  4999.6  401.26  5002.4  400.76  5005.6  401.26  5010.2  405.01  5124.3  403.89
  5172.4   407.1  5192.7  404.59  5324.5  406.63    5545  410.23  5789.1  411.17
    5910  420.56  6013.9  431.02  6029.6  432.24  6113.9  440.25  6186.2   446.9
#Mann= 7 ,-1 , 0
  4121.1     .12       0  4999.6     .07       0  5005.6     .12       0
  5789.1     .16       0  6013.9     .05       0  6029.6     .16       0
  6113.9     .12       0
Bank Sta=4404,5324.5
XS Rating Curve= 0 ,0
Exp/Cntr=0.3,0.1

Type RM Length L Ch R = 1 ,6636    ,443,443,443
BEGIN DESCRIPTION:
UNT 130 IN CACR 12.0
END DESCRIPTION:
XS GIS Cut Line= 3
      3729449.59     10698410.22      3729049.61     10699010.19
      3728749.61     10700810.18
#Sta/Elev= 30
  4264.3  435.24  4408.5  417.52    4437  412.95  4452.1  407.11  4473.1  405.71
  4530.2  401.91  4971.9  401.41  4979.4  398.67  4982.1  398.17  4985.4  398.67
  5056.3  405.35  5086.8  402.14    5178  405.71  5208.4  401.76  5443.2  404.72
  5498.1  403.76  5654.5  404.09  5664.6  407.82  5674.8  408.88  5682.4   405.3
    5695  404.52  5847.1   405.6  5968.8   417.1    6060  422.36    6131  421.14
    6210  413.08  6387.3  414.95  6530.4  418.58  6716.4   425.2  6810.2  431.59
#Mann= 8 ,-1 , 0
  4264.3     .12       0  4979.4     .07       0  4985.4     .12       0
  5443.2     .16       0  5498.1     .12       0    6210     .16       0
  6387.3     .12       0  6530.4     .16       0
Bank Sta=4473.1,5664.6
XS Rating Curve= 0 ,0
Exp/Cntr=0.3,0.1

Type RM Length L Ch R = 1 ,6193    ,398,398,398
BEGIN DESCRIPTION:
UNT 130 IN CACR 11.0
END DESCRIPTION:
XS GIS Cut Line= 3
      3729149.63     10698260.16      3728749.61     10698760.19
      3728849.61     10699960.18
#Sta/Elev= 30
  4327.1  433.79  4433.6  422.25  4455.2  415.78  4505.6  406.62  4697.7  405.82
  4768.2  402.93  4889.8   398.9  4960.2  401.09  4987.5  395.35  5004.6  395.26
  5007.3  394.76  5010.6  395.26  5017.6  398.35  5037.7  399.15  5097.9  397.57
  5145.6  399.66  5298.6   399.1  5368.8  401.75  5386.4  405.06    5419  402.43
  5514.4  402.92  5559.5  403.43  5682.7  412.26  5700.4  413.16  5860.5   414.3
  5873.1  411.75  5951.6  410.47    6001  409.88  6071.3  412.51  6171.6  418.96
#Mann= 7 ,-1 , 0
  4327.1     .12       0  5004.6     .07       0  5010.6     .12       0
  5514.4     .16       0  5682.7     .12       0  5700.4     .16       0
  5951.6     .12       0
Bank Sta=4768.2,5559.5
XS Rating Curve= 0 ,0
Exp/Cntr=0.3,0.1

Type RM Length L Ch R = 1 ,5795    ,654,654,654
BEGIN DESCRIPTION:
UNT 130 IN CACR 10.0
END DESCRIPTION:
XS GIS Cut Line= 3
      3729199.58     10697660.23      3728399.61     10698760.19
      3727999.59     10699310.21
#Sta/Elev= 30
  3668.3  439.51  3754.8  439.75  3796.9  436.14  3813.2  433.24  3853.7  428.16
  3890.8   426.2  3912.1  422.91  3932.9  422.53  3997.9  415.33  4039.6   413.8
  4089.8  414.43  4305.4  407.95  4583.6  402.22  4914.4  398.45  4970.8  396.76
  4982.5  394.38  4985.3  393.88  4988.5  394.38  5025.3  396.82  5056.6  396.25
  5142.4  402.23  5352.3  408.44    5450   412.7  5529.6   418.8  5623.7  432.25
  5686.4  443.33    5695  443.41  5701.1  445.41  5705.4  448.71  5708.5  448.71
#Mann= 6 ,-1 , 0
  3668.3     .05       0  3813.2     .12       0  4982.5     .07       0
  4988.5     .12       0  5352.3     .16       0  5623.7     .12       0
Bank Sta=4583.6,5142.4
XS Rating Curve= 0 ,0
Exp/Cntr=0.3,0.1

Type RM Length L Ch R = 1 ,5141    ,42,42,42
BEGIN DESCRIPTION:
Mapping XS 00f1b78a
END DESCRIPTION:
XS GIS Cut Line= 4
      3728222.67     10697948.96      3727949.05     10698395.43
      3727827.52     10698947.73      3727825.37     10698955.27
#Sta/Elev= 30
  4307.4  408.54  4382.7  406.45  4419.4  402.59  4440.7  400.16  4645.6  395.65
  4651.5  397.96  4666.9  395.18  4688.2  398.08  4703.7  394.98    4725  398.08
  4731.1  395.61  4746.3  396.65  4761.7  394.42  4767.6  397.13  4777.1  395.99
    4783  397.93  4819.7  394.44  4825.6  398.05  4830.9  395.96  4876.9  393.62
  4944.1  395.38  4949.2  393.38    4990   393.3  4992.7   392.8    4996   393.3
  5020.2  395.57  5036.7  393.76  5143.1   397.3  5204.5  402.01  5404.4  413.42
#Mann= 3 ,-1 , 0
  4307.4     .12       0    4990     .07       0    4996     .12       0
Bank Sta=4419.4,5204.5
XS Rating Curve= 0 ,0
Exp/Cntr=0.3,0.1

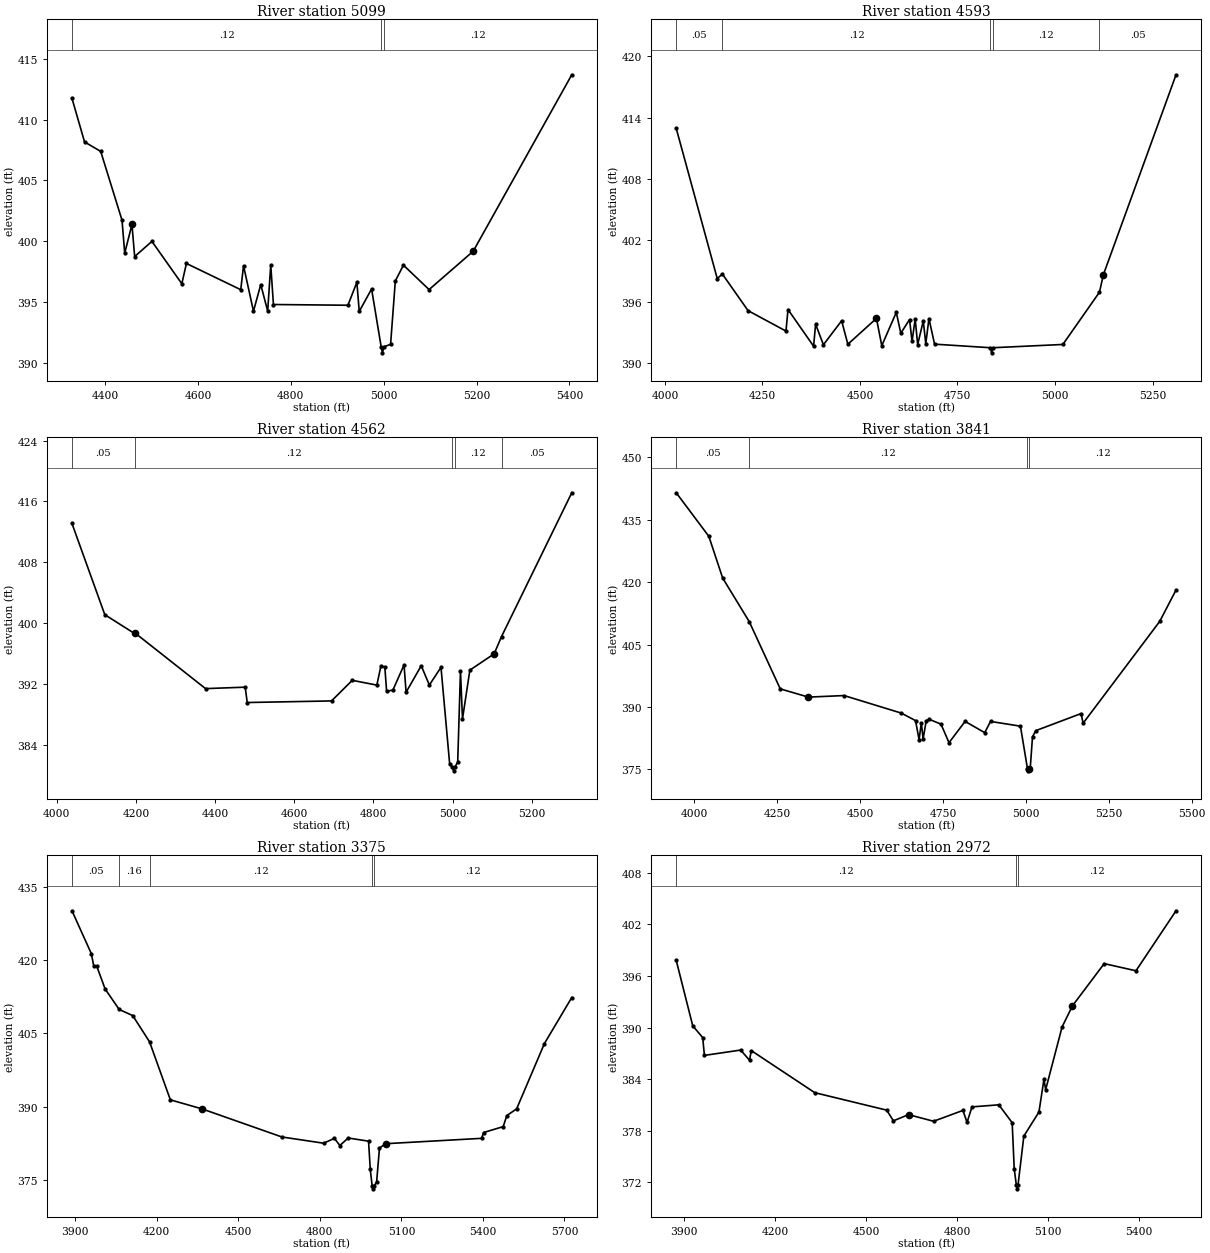
Type RM Length L Ch R = 1 ,5099    ,506,506,506
BEGIN DESCRIPTION:
UNT 130 IN CACR 8.0
END DESCRIPTION:
XS GIS Cut Line= 3
      3728161.89     10697946.82      3727908.51     10698378.04
      3727791.33     10698942.25
#Sta/Elev= 30
  4328.6  411.76  4355.7  408.17  4390.5  407.39  4436.4  401.72  4442.2  399.01
  4457.8  401.37  4463.6  398.73  4500.8  399.98  4565.2  396.49  4575.1  398.16
  4692.1     396  4698.1  397.97  4719.5  394.23  4735.2  396.42  4750.1  394.24
  4756.7  398.03  4762.5  394.78  4922.9  394.72  4942.2  396.61  4947.3  394.21
  4973.9  396.06  4994.5   391.3  4997.2   390.8  5000.5   391.3  5014.8   391.5
    5025  396.72  5042.5  398.02  5097.7  396.01  5192.8  399.17    5405   413.7
#Mann= 3 ,-1 , 0
  4328.6     .12       0  4994.5     .07       0  5000.5     .12       0
Bank Sta=4457.8,5192.8
XS Rating Curve= 0 ,0
Exp/Cntr=0.3,0.1

Type RM Length L Ch R = 1 ,4593    ,31,31,31
BEGIN DESCRIPTION:
UNT 130 IN CACR 7.0
END DESCRIPTION:
XS GIS Cut Line= 6
      3727549.99     10697539.98       3727400.7     10698026.04
      3727414.58     10698085.07      3727480.56      10698168.4
      3727490.97     10698258.68      3727383.33     10698762.18
#Sta/Elev= 30
    4029  412.94  4134.1  398.25  4147.3  398.69  4213.1  395.11  4310.3  393.11
  4315.5  395.22  4381.1  391.63  4386.3  393.78  4406.3  391.77    4453  394.12
  4468.9  391.82  4542.2  394.35  4555.9  391.68  4593.1  394.94  4604.7   392.9
  4627.1  394.24  4633.5   392.1  4641.5   394.3  4647.9  391.79  4662.3   394.1
  4668.7  391.87  4676.8  394.33  4691.2  391.83  4834.6  391.48  4837.4  390.98
  4840.6  391.48  5020.1   391.8    5114  396.92  5123.9  398.62  5310.2  418.19
#Mann= 5 ,-1 , 0
    4029     .05       0  4147.3     .12       0  4834.6     .07       0
  4840.6     .12       0    5114     .05       0
Bank Sta=4542.2,5123.9
XS Rating Curve= 0 ,0
Exp/Cntr=0.3,0.1

Type RM Length L Ch R = 1 ,4562    ,721,721,721
BEGIN DESCRIPTION:
Mapping XS d71d74c8
END DESCRIPTION:
XS GIS Cut Line= 6
      3727508.32     10697546.92      3727379.86     10697984.38
      3727365.97     10698060.77      3727456.25     10698210.07
      3727456.25     10698286.46      3727355.55     10698751.75
#Sta/Elev= 30
  4038.6   413.1  4121.5   401.1    4197  398.61  4198.6  398.66    4376  391.37
  4476.1  391.56  4481.3  389.54  4694.2  389.75  4746.6  392.46  4808.7  391.83
  4818.7  394.29  4828.8  394.25  4833.3  391.03  4849.2  391.17  4877.4  394.49
  4882.5  390.89  4920.8  394.38  4941.3  391.84  4970.7  394.17  4992.5  381.51
  4999.7  381.05  5002.4  380.55  5005.7  381.05  5012.9  381.68  5019.9  393.69
    5025  387.38  5043.6   393.8    5105  395.95  5123.6  398.22    5301  417.14
#Mann= 5 ,-1 , 0
  4038.6     .05       0    4197     .12       0  4999.7     .07       0
  5005.7     .12       0  5123.6     .05       0
Bank Sta=4198.6,5105
XS Rating Curve= 0 ,0
Exp/Cntr=0.3,0.1

Type RM Length L Ch R = 1 ,3841    ,466,466,466
BEGIN DESCRIPTION:
UNT 130 IN CACR 6.0
END DESCRIPTION:
XS GIS Cut Line= 3
      3727199.61     10697360.18      3726799.61     10698360.19
      3727049.63     10698710.22
#Sta/Elev= 30
  3945.7   441.5    4044  431.03  4085.7     421  4165.7  410.54  4259.4  394.35
  4344.2  392.37  4451.9  392.74  4624.2  388.53  4667.3  386.72  4678.1  382.12
  4684.8  386.21  4690.2  382.32  4699.6  386.68  4709.1  387.01  4744.1  385.87
  4768.3  381.41  4816.8  386.53    4876  383.82  4893.5  386.52  4983.7  385.38
  5004.9  375.14  5007.7  374.64  5010.9  375.14  5013.3  375.32  5020.1  382.84
  5030.1  384.31  5166.5  388.41  5172.7  386.09  5403.7  410.57  5452.9  418.12
#Mann= 4 ,-1 , 0
  3945.7     .05       0  4165.7     .12       0  5004.9     .07       0
  5010.9     .12       0
Bank Sta=4344.2,5010.9
XS Rating Curve= 0 ,0
Exp/Cntr=0.3,0.1

Type RM Length L Ch R = 1 ,3375    ,403,403,403
BEGIN DESCRIPTION:
UNT 130 IN CACR 5.0
END DESCRIPTION:
XS GIS Cut Line= 3
      3726549.61     10697310.17      3726349.61     10698410.19
      3726949.64     10698810.21
#Sta/Elev= 30
  3887.8  430.13    3959  421.35  3967.9  418.86  3979.3  418.73  4009.8   414.1
  4061.6   409.9  4111.4  408.65  4173.3  403.27  4249.9  391.38  4366.8  389.52
  4660.3  383.77    4814  382.49  4853.4  383.49  4873.7  382.02  4904.2  383.56
  4979.2  382.91  4985.5  377.14  4992.7  373.64  4995.4  373.14  4998.7  373.64
  5008.9  374.55  5019.4  381.49  5041.9  382.39    5395  383.49  5402.5  384.68
  5474.6  385.89  5488.1  388.16  5524.1  389.53  5626.3  402.91    5727  412.35
#Mann= 5 ,-1 , 0
  3887.8     .05       0  4061.6     .16       0  4173.3     .12       0
  4992.7     .07       0  4998.7     .12       0
Bank Sta=4366.8,5041.9
XS Rating Curve= 0 ,0
Exp/Cntr=0.3,0.1

Type RM Length L Ch R = 1 ,2972    ,605,605,605
BEGIN DESCRIPTION:
UNT 130 IN CACR 4.0
END DESCRIPTION:
XS GIS Cut Line= 2
      3725512.08     10697541.93       3726275.3     10699003.33
#Sta/Elev= 30
  3873.2  397.79  3927.6   390.2  3960.5  388.83  3966.1  386.76  4085.6  387.38
    4115   386.2  4120.7  387.32  4330.2  382.43  4567.5   380.4  4589.6  379.16
  4639.4  379.88  4722.1  379.11  4818.9  380.37  4832.5  378.98  4848.9  380.78
  4937.3  381.02  4981.4  378.94  4988.1  373.59  4994.9  371.76  4997.6  371.26
  5000.9  371.76  5019.9  377.39  5069.7  380.18  5086.2  383.98  5091.8  382.78
  5146.1  390.07  5180.2  392.52  5284.9  397.42  5389.7  396.59  5521.9  403.56
#Mann= 3 ,-1 , 0
  3873.2     .12       0  4994.9     .07       0  5000.9     .12       0
Bank Sta=4639.4,5180.2
XS Rating Curve= 0 ,0
Exp/Cntr=0.3,0.1