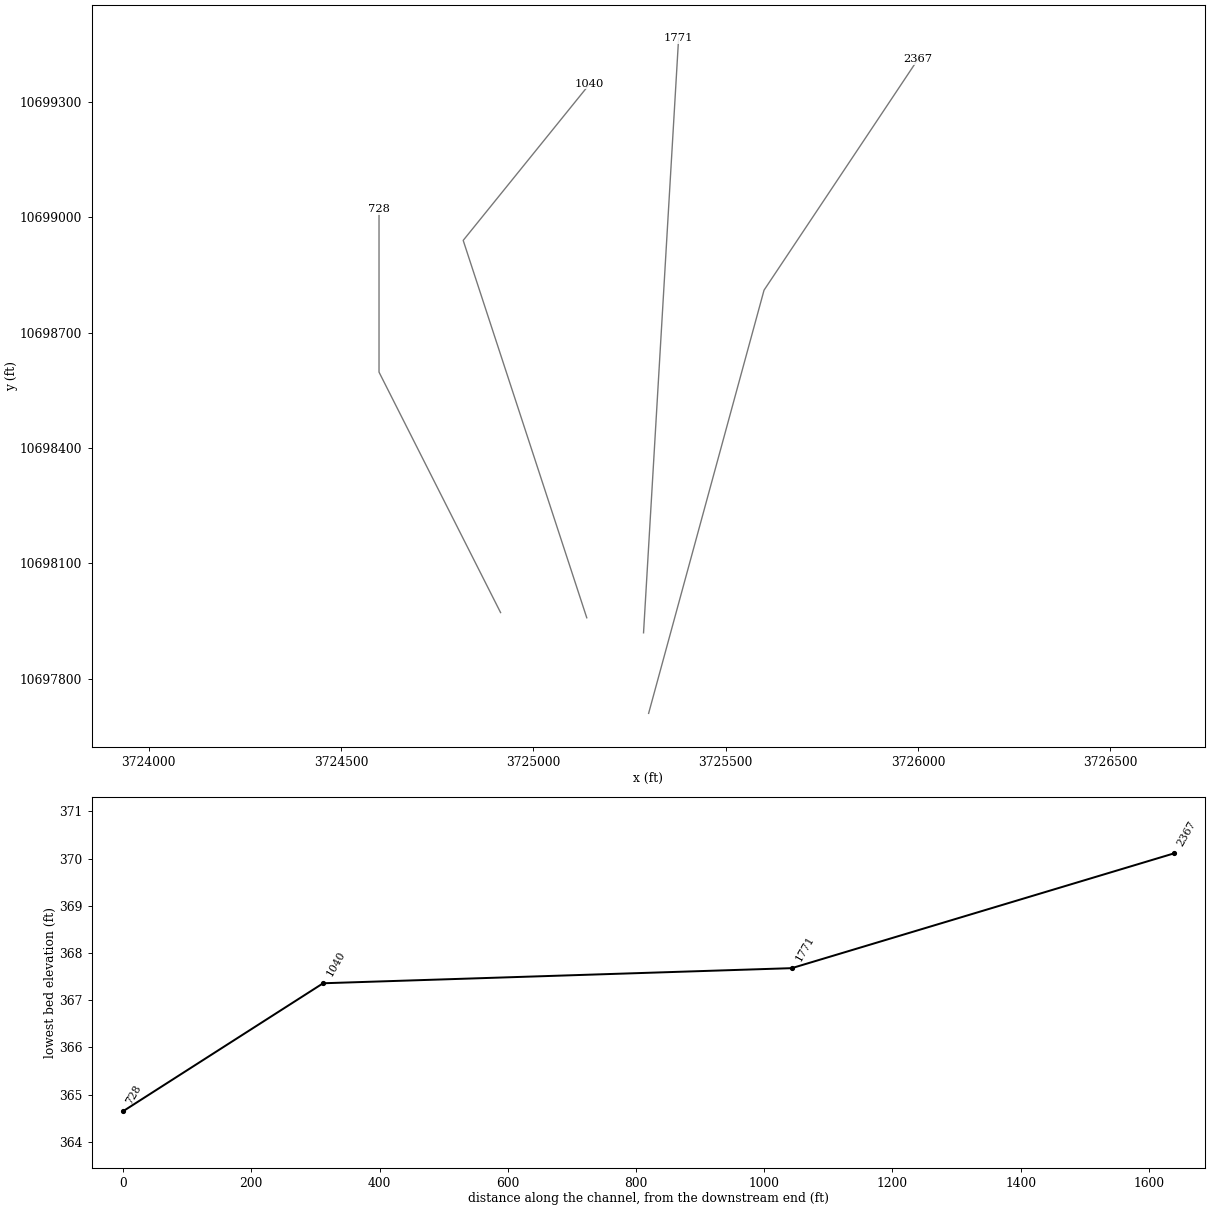
HEC-RAS study UNT 130 IN CACR.prj: UNT 130 IN CACR Base Level Engineering

--- UNT 130 IN CACR.g01 (geometry) --- (continued)

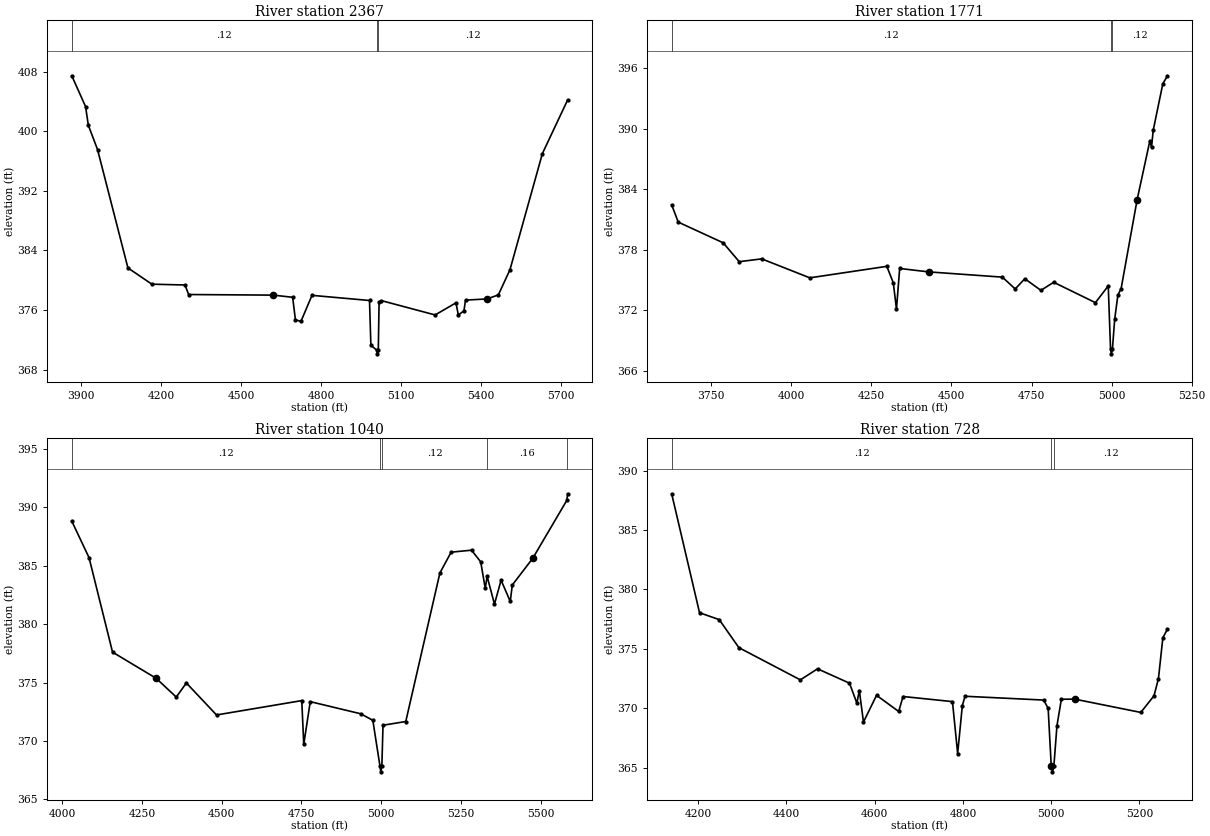
Type RM Length L Ch R = 1 ,2367    ,596,596,596
BEGIN DESCRIPTION:
UNT 130 IN CACR 3.0
END DESCRIPTION:
XS GIS Cut Line= 3
      3725299.61     10697710.17      3725599.61     10698810.19
      3725999.61     10699410.19
#Sta/Elev= 30
    3864  407.43  3915.8   403.3  3926.2  400.79  3960.8  397.52  4074.8  381.64
  4164.6  379.46    4289  379.35  4302.8  378.07  4620.7  377.99  4693.2   377.7
  4703.6  374.68  4724.3  374.46  4765.8  377.96  4981.7  377.27  4986.9  371.25
  5008.7  370.61  5011.5  370.11  5014.7  370.61  5017.7  377.08  5026.7  377.25
    5228  375.33  5306.2  376.95  5315.2  375.32  5336.2  375.88  5342.2  377.32
  5423.3  377.48  5465.4  378.02    5509   381.4  5630.7  396.99  5725.3  404.17
#Mann= 3 ,-1 , 0
    3864     .12       0  5008.7     .07       0  5014.7     .12       0
Bank Sta=4620.7,5423.3
XS Rating Curve= 0 ,0
Exp/Cntr=0.3,0.1

Type RM Length L Ch R = 1 ,1771    ,731,731,731
BEGIN DESCRIPTION:
UNT 130 IN CACR 2.0
END DESCRIPTION:
XS GIS Cut Line= 2
       3725286.4     10697919.61      3725377.55     10699464.73
#Sta/Elev= 30
  3626.5  382.44  3647.1  380.73  3787.4  378.68  3837.4  376.81  3907.6  377.09
  4057.8  375.21  4298.2  376.35  4318.3  374.72  4328.3  372.12  4338.3  376.14
  4428.5   375.8  4658.9  375.28  4698.9  374.11    4729  375.12  4779.1  373.97
  4819.1  374.77  4949.4  372.75  4989.4  374.41  4996.5  368.18  4999.2  367.68
  5002.5  368.18  5009.5   371.1  5019.5  373.51  5029.5  374.13  5079.6  382.96
  5119.5  388.81  5124.5  388.13  5129.7  389.82  5159.7  394.43  5174.3  395.23
#Mann= 3 ,-1 , 0
  3626.5     .12       0  4996.5     .07       0  5002.5     .12       0
Bank Sta=4428.5,5079.6
XS Rating Curve= 0 ,0
Exp/Cntr=0.3,0.1

Type RM Length L Ch R = 1 ,1040    ,312,312,312
BEGIN DESCRIPTION:
UNT 130 IN CACR 1.0
END DESCRIPTION:
XS GIS Cut Line= 3
      3725138.83     10697958.64      3724817.65     10698939.53
      3725146.58     10699346.36
#Sta/Elev= 30
  4029.4  388.83  4083.6   385.7  4157.3  377.61  4294.1  375.37  4357.2  373.76
  4388.8  374.97  4483.5  372.23  4750.9  373.46  4757.1  369.71  4777.5  373.37
    4936  372.33  4973.8  371.77  4996.1  367.86  4998.8  367.36  5002.1  367.86
  5005.7  371.35  5077.1  371.67  5184.2  384.39  5219.4  386.17  5283.4  386.34
  5312.2  385.34  5326.5  383.06  5332.3   384.1  5355.3  381.72  5376.1  383.77
  5404.9  381.95  5411.3  383.36  5475.3  385.64  5582.4  390.61  5584.7  391.17
#Mann= 5 ,-1 , 0
  4029.4     .12       0  4996.1     .07       0  5002.1     .12       0
  5332.3     .16       0  5582.4     .12       0
Bank Sta=4294.1,5475.3
XS Rating Curve= 0 ,0
Exp/Cntr=0.3,0.1

Type RM Length L Ch R = 1 ,728     ,0,0,0
BEGIN DESCRIPTION:
Mapping XS 8467b6b5
END DESCRIPTION:
XS GIS Cut Line= 3
      3724914.85     10697972.14      3724598.88     10698597.14
      3724598.88     10699020.71
#Sta/Elev= 30
  4139.8  388.05    4203  378.04  4247.6  377.46  4292.2   375.1  4431.5  372.39
  4470.5  373.32  4542.9  372.11  4559.6  370.43  4565.2  371.49  4574.6  368.84
  4604.2  371.09  4654.4  369.73  4664.3  370.99  4776.3  370.56  4788.1  366.19
  4798.7  370.23  4804.8  371.01  4983.2  370.69  4993.2  369.99  5000.2  365.15
  5002.9  364.65  5006.2  365.15  5013.2  368.54  5023.2  370.76  5053.2  370.77
  5203.2  369.65  5233.2  371.05  5243.2  372.49  5253.2  375.93  5263.7  376.66
#Mann= 3 ,-1 , 0
  4139.8     .12       0  5000.2     .07       0  5006.2     .12       0
Bank Sta=5000.2,5053.2
XS Rating Curve= 0 ,0
Exp/Cntr=0.3,0.1

Chan Stop Cuts=-1
Use User Specified Reach Order=0
Composite Channel Slope=5