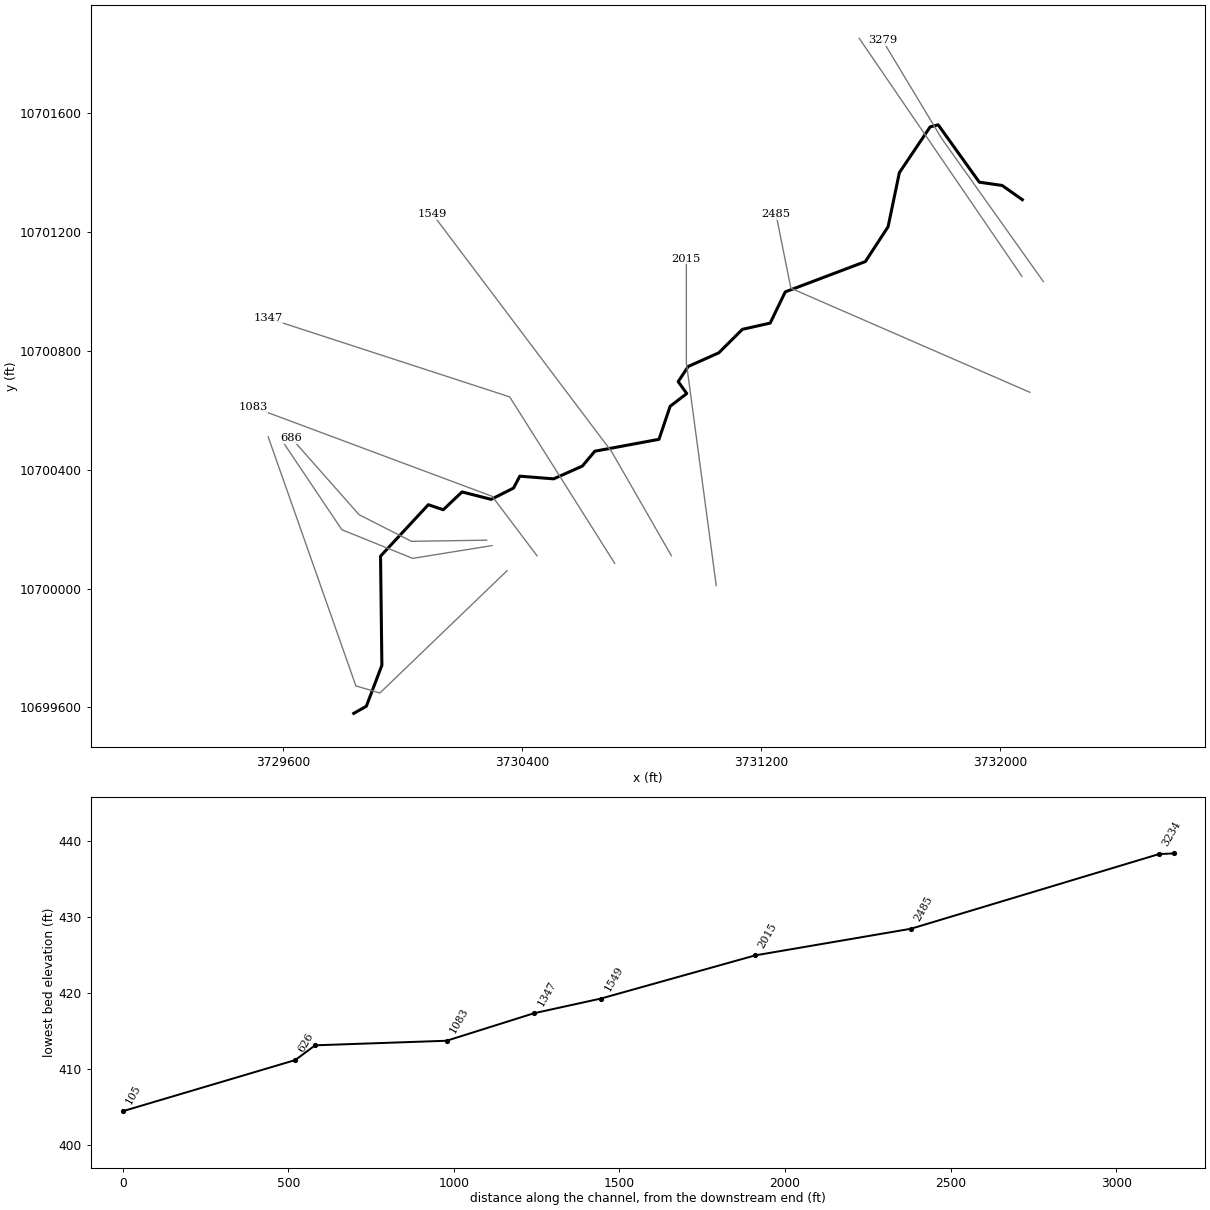
--- UNT 131 IN CACR.prj (project) ---

Proj Title=UNT 131 IN CACR Base Level Engineering
Current Plan=p01
Default Exp/Contr=0.3,0.1
English Units
Geom File=g01
Flow File=f01
Plan File=p01
Y Axis Title=Elevation
X Axis Title(PF)=Main Channel Distance
X Axis Title(XS)=Station
BEGIN DESCRIPTION:
UNT 131 IN CACR
END DESCRIPTION:
DSS Export Rating Curves= 0
DSS Export Rating Curve Sorted= 0
DSS Export Volume Flow Curves= 0
DXF OffsetX= 0
DXF OffsetY= 0
DXF ScaleX= 1
DXF ScaleY= 10

--- UNT 131 IN CACR.p01 (plan) ---

Plan Title=Multiple Run
Short Identifier=Multiple
Geom File=g01
Flow File=f01
Subcritical Flow
K Sum by GR= 0
Std Step Tol= 0.01
Critical Tol= 0.01
Num of Std Step Trials= 20
Max Error Tol= 0.3
Flow Tol Ratio= 0.001
Split Flow NTrial= 30
Split Flow Tol= 0.02
Split Flow Ratio= 0.02
Log Output Level= 0
Friction Slope Method= 1
Unsteady Friction Slope Method= 2
Unsteady Bridges Friction Slope Method= 1
Parabolic Critical Depth
Global Vel Dist=  1 , 1 , 1
Global Log Level= 0
CheckData=True
Encroach Param= -1, 0, 0, 0
BEGIN DESCRIPTION:
Multiple Run
END DESCRIPTION:

--- UNT 131 IN CACR.f01 (steady flow) ---

Flow Title=Multiple
Number of Profiles=7
Profile Names=10-year,25-year,50-year,1pct_min,100-year,1pct_plu,500-year
River Rch & RM= UNT 131 IN CACR,Reach-1,3279
     859    1214    1520    1401    1895    2562    2954
River Rch & RM= UNT 131 IN CACR,Reach-1,2485
    1033    1471    1852    1714    2318    3135    3648
Boundary for River Rch & Prof#=UNT 131 IN CACR,Reach-1,1
Up Type=0
Dn Type=3
Dn Slope=0.005
Boundary for River Rch & Prof#=UNT 131 IN CACR,Reach-1,2
Up Type=0
Dn Type=3
Dn Slope=0.005
Boundary for River Rch & Prof#=UNT 131 IN CACR,Reach-1,3
Up Type=0
Dn Type=3
Dn Slope=0.005
Boundary for River Rch & Prof#=UNT 131 IN CACR,Reach-1,4
Up Type=0
Dn Type=3
Dn Slope=0.005
Boundary for River Rch & Prof#=UNT 131 IN CACR,Reach-1,5
Up Type=0
Dn Type=3
Dn Slope=0.005
Boundary for River Rch & Prof#=UNT 131 IN CACR,Reach-1,6
Up Type=0
Dn Type=3
Dn Slope=0.005
Boundary for River Rch & Prof#=UNT 131 IN CACR,Reach-1,7
Up Type=0
Dn Type=3
Dn Slope=0.005

--- UNT 131 IN CACR.g01 (geometry) ---

Geom Title=Existing Conditions
Program Version=4.10

River Reach=UNT 131 IN CACR ,Reach-1
Reach XY= 30
      3732074.57     10701308.09        3732007.       10701356.
       3731930.5       10701367.      3731792.75       10701560.
      3731765.75       10701553.      3731662.75       10701399.
        3731625.       10701217.        3731549.       10701100.
      3731280.75       10700998.      3731230.25       10700893.
      3731137.25       10700872.      3731058.25       10700793.
      3730955.75       10700747.      3730922.25       10700696.
        3730951.       10700656.      3730895.25       10700613.
        3730858.       10700502.      3730643.25       10700462.
       3730601.5       10700412.      3730505.25       10700369.
        3730392.       10700378.        3730371.       10700338.
      3730296.25       10700300.       3730198.5       10700325.
      3730135.75       10700265.      3730085.75       10700282.
      3729925.75       10700109.      3729930.25       10699742.
      3729878.25       10699604.        3729836.       10699580.

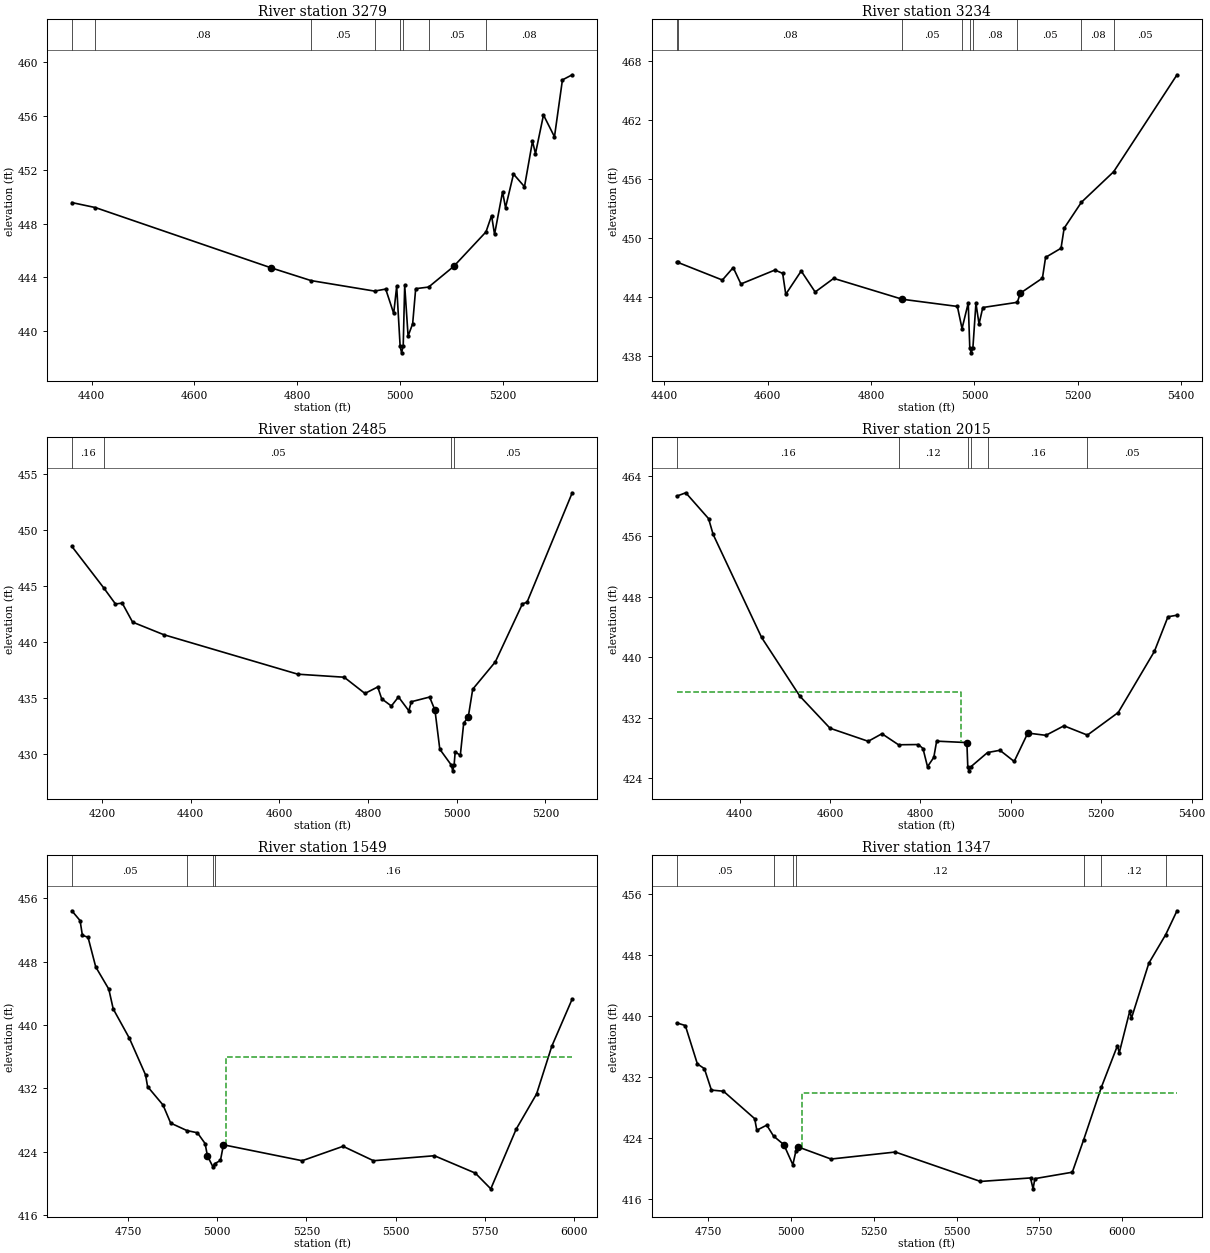
Type RM Length L Ch R = 1 ,3279    ,45,45,45
BEGIN DESCRIPTION:
UNT 131 IN CACR 6.0
END DESCRIPTION:
XS GIS Cut Line= 3
      3732144.74     10701032.86      3731804.02     10701514.64
      3731606.56     10701844.46
#Sta/Elev= 30
  4361.2  449.56  4406.9  449.19  4749.9   444.7  4827.1  443.76  4950.7  442.98
  4972.4  443.13    4988  441.32  4993.8  443.34  5000.5  438.89  5003.3  438.39
  5006.5  438.89  5009.4  443.41    5016  439.64  5024.9  440.55  5030.8  443.16
    5056  443.28  5104.7  444.81  5167.7  447.38  5178.6  448.59  5184.4   447.2
    5200  450.36  5205.8  449.18  5221.3  451.68  5242.7  450.74  5258.3  454.12
  5264.1   453.2  5279.7  456.07  5301.1  454.45  5316.6  458.68  5335.7  459.06
#Mann= 8 ,-1 , 0
  4361.2     .05       0  4406.9     .08       0  4827.1     .05       0
  4950.7     .08       0  5000.5     .07       0  5006.5     .08       0
    5056     .05       0  5167.7     .08       0
Bank Sta=4749.9,5104.7
XS Rating Curve= 0 ,0
Exp/Cntr=0.3,0.1

Type RM Length L Ch R = 1 ,3234    ,749,749,749
BEGIN DESCRIPTION:
Mapping XS 0da2236f
END DESCRIPTION:
XS GIS Cut Line= 2
      3732073.15     10701050.19      3731528.43     10701850.99
#Sta/Elev= 30
  4423.7  447.51  4426.4  447.51  4512.2  445.72  4533.2  446.99  4548.1  445.32
  4613.9  446.74  4628.9   446.4  4634.9  444.27  4664.8  446.64  4691.8   444.5
  4727.7  445.89  4860.6  443.76  4967.1  443.03  4976.1  440.77  4988.1  443.38
  4991.1   438.8  4993.9   438.3  4997.1   438.8    5003  443.36    5009  441.24
  5016.3  442.92  5083.1  443.45  5088.9  444.38  5131.7  445.91  5137.8  448.03
  5167.7  448.96  5173.7     451  5207.2  453.65  5269.6  456.76  5392.2  466.64
#Mann= 9 ,-1 , 0
  4423.7     .05       0  4426.4     .08       0  4860.6     .05       0
  4976.1     .08       0  4991.1     .07       0  4997.1     .08       0
  5083.1     .05       0  5207.2     .08       0  5269.6     .05       0
Bank Sta=4860.6,5088.9
XS Rating Curve= 0 ,0
Exp/Cntr=0.3,0.1

Type RM Length L Ch R = 1 ,2485    ,470,470,470
BEGIN DESCRIPTION:
UNT 131 IN CACR 5.0
END DESCRIPTION:
XS GIS Cut Line= 3
      3732099.65     10700660.17      3731299.61     10701010.19
      3731249.61     10701260.18
#Sta/Elev= 30
  4132.4  448.52    4204  444.83  4230.7  443.38  4245.9  443.46  4269.3  441.76
  4339.4  440.64  4641.9  437.11  4746.4  436.84  4793.2  435.39    4822  435.97
    4831  434.91  4852.8  434.27  4868.8  435.08  4892.2  433.84  4897.7  434.65
    4939  435.07  4951.1  433.89    4962  430.41  4988.2  428.98    4991  428.48
  4994.2  428.98  4996.7  430.18  5008.2  429.86  5015.9  432.75  5026.1  433.27
  5036.2  435.77  5087.2  438.21  5148.4   443.4  5158.6  443.53  5260.6  453.31
#Mann= 4 ,-1 , 0
  4132.4     .16       0    4204     .05       0  4988.2     .03       0
  4994.2     .05       0
Bank Sta=4951.1,5026.1
XS Rating Curve= 0 ,0
Exp/Cntr=0.3,0.1

Type RM Length L Ch R = 1 ,2015    ,466,466,466
BEGIN DESCRIPTION:
UNT 131 IN CACR 4.0
END DESCRIPTION:
XS GIS Cut Line= 3
      3731049.61     10700010.21      3730949.61     10700760.19
      3730949.61     10701110.17
#Sta/Elev= 30
  4260.9  461.33  4281.1  461.78  4331.5  458.36  4341.6  456.27  4448.8  442.63
  4533.3  434.87  4600.1  430.62  4684.6  428.89  4714.9  429.89  4751.6  428.43
  4795.6  428.46  4805.7  427.93  4815.7  425.53  4829.6  426.76  4835.9  428.91
  4902.8  428.72  4904.8  425.48  4907.6  424.98  4910.8  425.48  4948.4   427.4
  4975.9   427.7  5007.4  426.22  5037.5  429.98  5077.5  429.68  5117.5  430.94
  5169.3  429.71  5237.5   432.7  5317.5  440.79  5347.5  445.37  5367.5  445.58
#Mann= 6 ,-1 , 0
  4260.9     .16       0  4751.6     .12       0  4904.8     .07       0
  4910.8     .12       0  4948.4     .16       0  5169.3     .05       0
#XS Ineff= 2 , 0
         4890.68  435.43
Permanent Ineff=
       F       F
Bank Sta=4902.8,5037.5
XS Rating Curve= 0 ,0
Exp/Cntr=0.3,0.1

Type RM Length L Ch R = 1 ,1549    ,202,202,202
BEGIN DESCRIPTION:
UNT 131 IN CACR 3.0
END DESCRIPTION:
XS GIS Cut Line= 3
       3730899.6     10700110.21      3730699.61     10700460.19
       3730099.6      10701260.2
#Sta/Elev= 30
  4592.2  454.41  4615.2  453.17  4621.7  451.31  4637.5  451.07  4659.1  447.32
  4695.8  444.51  4708.1  442.02  4753.4  438.32  4798.8  433.69  4804.5  432.21
  4847.7  429.89  4869.3   427.6  4914.7  426.66  4944.2  426.38  4965.8  425.02
  4972.3  423.46  4987.4  422.11  4992.4  422.47  5008.8  422.88  5017.2  424.86
    5238  422.85  5352.6  424.67    5438  422.85  5608.8  423.48  5723.4  421.29
  5766.9   419.3    5838  426.83  5895.3  431.28    5938  437.31  5995.3  443.28
#Mann= 4 ,-1 , 0
  4592.2     .05       0  4914.7     .16       0  4987.4     .07       0
  4992.4     .16       0
#XS Ineff= 2 , 0
                         5024.59          435.94
Permanent Ineff=
       F       F
Bank Sta=4972.3,5017.2
XS Rating Curve= 0 ,0
Exp/Cntr=0.3,0.1

Type RM Length L Ch R = 1 ,1347    ,264,264,264
BEGIN DESCRIPTION:
Mapping XS 692a1f6d
END DESCRIPTION:
XS GIS Cut Line= 3
      3730709.69      10700084.9      3730358.13     10700644.79
      3729548.65     10700909.56
#Sta/Elev= 30
  4653.8  439.15    4680   438.8  4716.5  433.76  4737.7  433.14  4758.9  430.33
  4795.4  430.18  4889.7  426.58  4896.2  425.06  4926.2  425.73  4946.7   424.3
    4978  423.16  5005.1  420.53  5014.3  422.33  5020.4  422.88  5120.6  421.28
  5314.9   422.2  5572.3  418.34  5723.7   418.8  5731.4  417.37  5736.9  418.71
    5850  419.55  5884.6  423.84  5937.6  430.67  5986.6  436.17  5991.9  435.21
  6023.7  440.69    6029  439.78  6081.4  446.98  6132.4  450.73  6166.6  453.86
#Mann= 7 ,-1 , 0
  4653.8     .05       0  4946.7     .16       0  5005.1     .07       0
  5014.3     .12       0  5884.6     .16       0  5937.6     .12       0
  6132.4     .16       0
#XS Ineff= 2 , 0
                         5031.82          429.97
Permanent Ineff=
       F       F
Bank Sta=4978,5020.4
XS Rating Curve= 0 ,0
Exp/Cntr=0.3,0.1

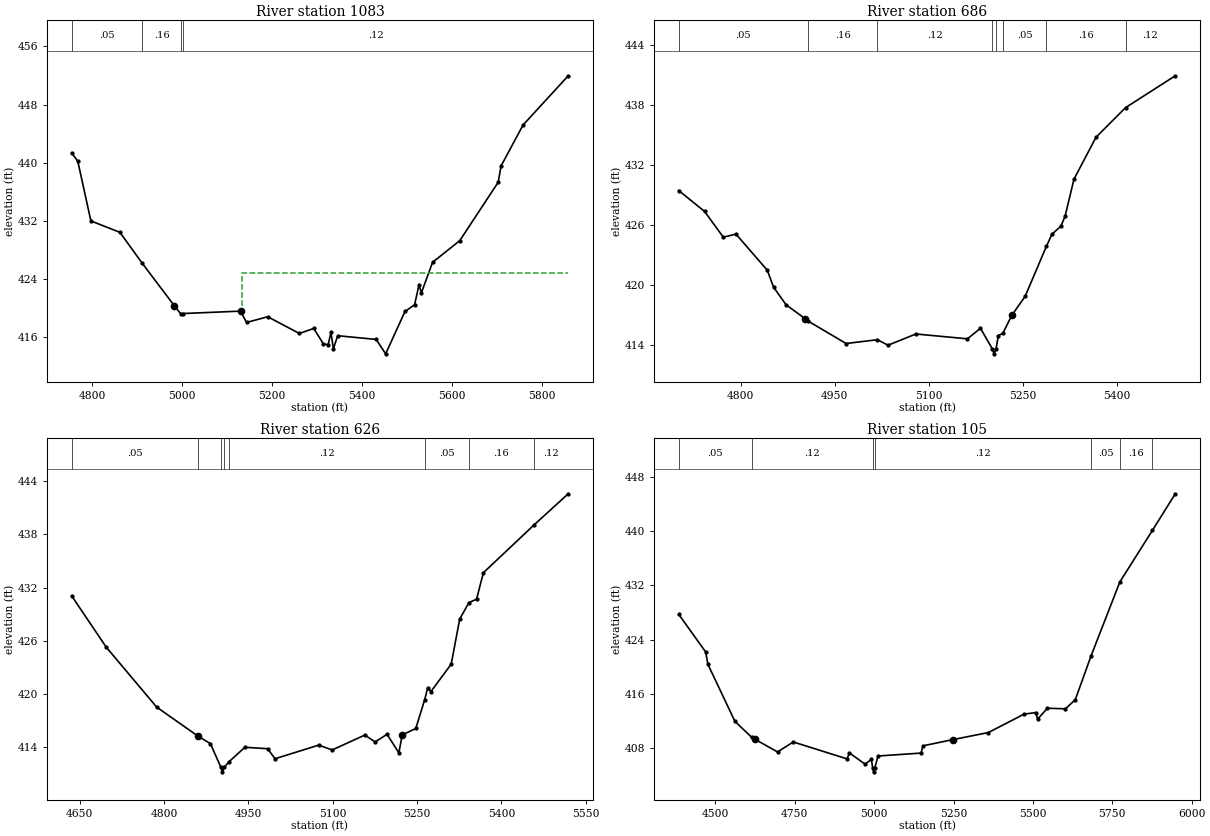
Type RM Length L Ch R = 1 ,1083    ,397,397,397
BEGIN DESCRIPTION:
UNT 131 IN CACR 2.0
END DESCRIPTION:
XS GIS Cut Line= 3
      3730449.63     10700110.16      3730299.61     10700310.19
      3729499.64     10700610.18
#Sta/Elev= 30
  4754.5  441.38  4768.1  440.22  4797.2  432.02  4861.8  430.45  4911.8  426.17
  4982.7  420.37  4997.2  419.23  5001.4  419.29    5130  419.62  5143.4  418.06
  5190.5  418.85  5260.9  416.55  5292.9  417.24  5314.3  415.12  5324.9  415.01
  5331.2  416.69  5336.5  414.46  5346.3  416.24  5431.7  415.73  5452.8  413.75
  5495.8  419.57  5517.2   420.5    5527  423.24  5532.3  422.13  5557.2  426.33
  5617.7  429.31  5703.2  437.34  5709.4  439.56  5758.4   445.2  5858.9  451.97
#Mann= 4 ,-1 , 0
  4754.5     .05       0  4911.8     .16       0  4997.2     .07       0
  5001.4     .12       0
#XS Ineff= 2 , 0
                         5132.95          424.89
Permanent Ineff=
       F       F
Bank Sta=4982.7,5130
XS Rating Curve= 0 ,0
Exp/Cntr=0.3,0.1

Type RM Length L Ch R = 1 ,686     ,60,60,60
BEGIN DESCRIPTION:
Mapping XS 9ed14b30
END DESCRIPTION:
XS GIS Cut Line= 4
      3730280.71     10700162.69      3730029.36     10700158.78
      3729853.58     10700248.62      3729627.55     10700505.83
#Sta/Elev= 30
  4701.4  429.44  4742.5  427.36  4772.5  424.78  4792.5   425.1  4842.5  421.49
  4852.5   419.8  4872.5  418.04  4902.5  416.67  4906.9  416.44  4968.1  414.18
    5018  414.56  5034.8  414.01  5079.2  415.13  5161.4  414.65  5182.2   415.7
    5201  413.65  5203.8  413.15    5207  413.65  5210.7  414.97  5217.8   415.2
  5232.1  416.99  5253.4  418.89  5287.1  423.86  5296.1  425.09  5310.3  425.88
    5317  426.88  5331.2  430.58  5366.3  434.76  5413.3  437.71  5492.6  440.89
#Mann= 8 ,-1 , 0
  4701.4     .05       0  4906.9     .16       0    5018     .12       0
    5201     .07       0    5207     .12       0  5217.8     .05       0
  5287.1     .16       0  5413.3     .12       0
Bank Sta=4902.5,5232.1
XS Rating Curve= 0 ,0
Exp/Cntr=0.3,0.1

Type RM Length L Ch R = 1 ,626     ,521,521,521
BEGIN DESCRIPTION:
Mapping XS d4367693
END DESCRIPTION:
XS GIS Cut Line= 4
      3730298.85     10700144.45      3730033.27     10700101.49
      3729796.29     10700197.84      3729597.32     10700495.64
#Sta/Elev= 30
  4635.8  431.06  4697.3  425.27    4787  418.51  4860.4  415.24  4882.4   414.4
  4901.2  411.71  4903.9  411.21  4907.2  411.71    4915  412.32  4943.9  413.98
  4984.3  413.82  4997.4  412.69    5075  414.22  5099.1  413.68  5157.1  415.36
  5175.5  414.58  5196.6  415.45  5217.6  413.35  5223.6  415.38  5247.7   416.1
  5263.6  419.36  5268.7  420.65  5274.7  420.27  5310.7  423.36  5325.8  428.44
  5342.2   430.3  5355.8  430.69  5367.9  433.67  5457.2  439.02  5518.8  442.58
#Mann= 8 ,-1 , 0
  4635.8     .05       0  4860.4     .16       0  4901.2     .07       0
  4907.2     .16       0    4915     .12       0  5263.6     .05       0
  5342.2     .16       0  5457.2     .12       0
Bank Sta=4860.4,5223.6
XS Rating Curve= 0 ,0
Exp/Cntr=0.3,0.1

Type RM Length L Ch R = 1 ,105     ,0,0,0
BEGIN DESCRIPTION:
UNT 131 IN CACR 1.0
END DESCRIPTION:
XS GIS Cut Line= 4
      3730349.59     10700060.17      3729923.57     10699648.58
      3729843.27     10699672.45      3729549.59     10700510.23
#Sta/Elev= 30
  4384.6  427.73  4469.3  422.19  4476.5  420.35  4561.4  411.95  4614.7  409.56
    4625  409.28  4695.7  407.42  4745.4  408.89  4914.9  406.39  4922.1  407.28
  4971.5  405.61  4991.5  406.32  4995.5  404.98  4998.2  404.48  5001.5  404.98
  5012.4  406.82  5147.9  407.25  5153.7  408.32  5249.1  409.25  5359.7  410.28
  5471.6  412.99  5509.4  413.24  5514.7  412.26  5545.8  413.87  5602.4  413.79
  5633.4  415.12  5683.4  421.62  5773.9  432.52  5876.4  440.13  5948.5  445.54
#Mann= 7 ,-1 , 0
  4384.6     .05       0  4614.7     .12       0  4995.5     .07       0
  5001.5     .12       0  5683.4     .05       0  5773.9     .16       0
  5876.4     .12       0
Bank Sta=4625,5249.1
XS Rating Curve= 0 ,0
Exp/Cntr=0.3,0.1

Chan Stop Cuts=-1
Use User Specified Reach Order=0
Composite Channel Slope=5