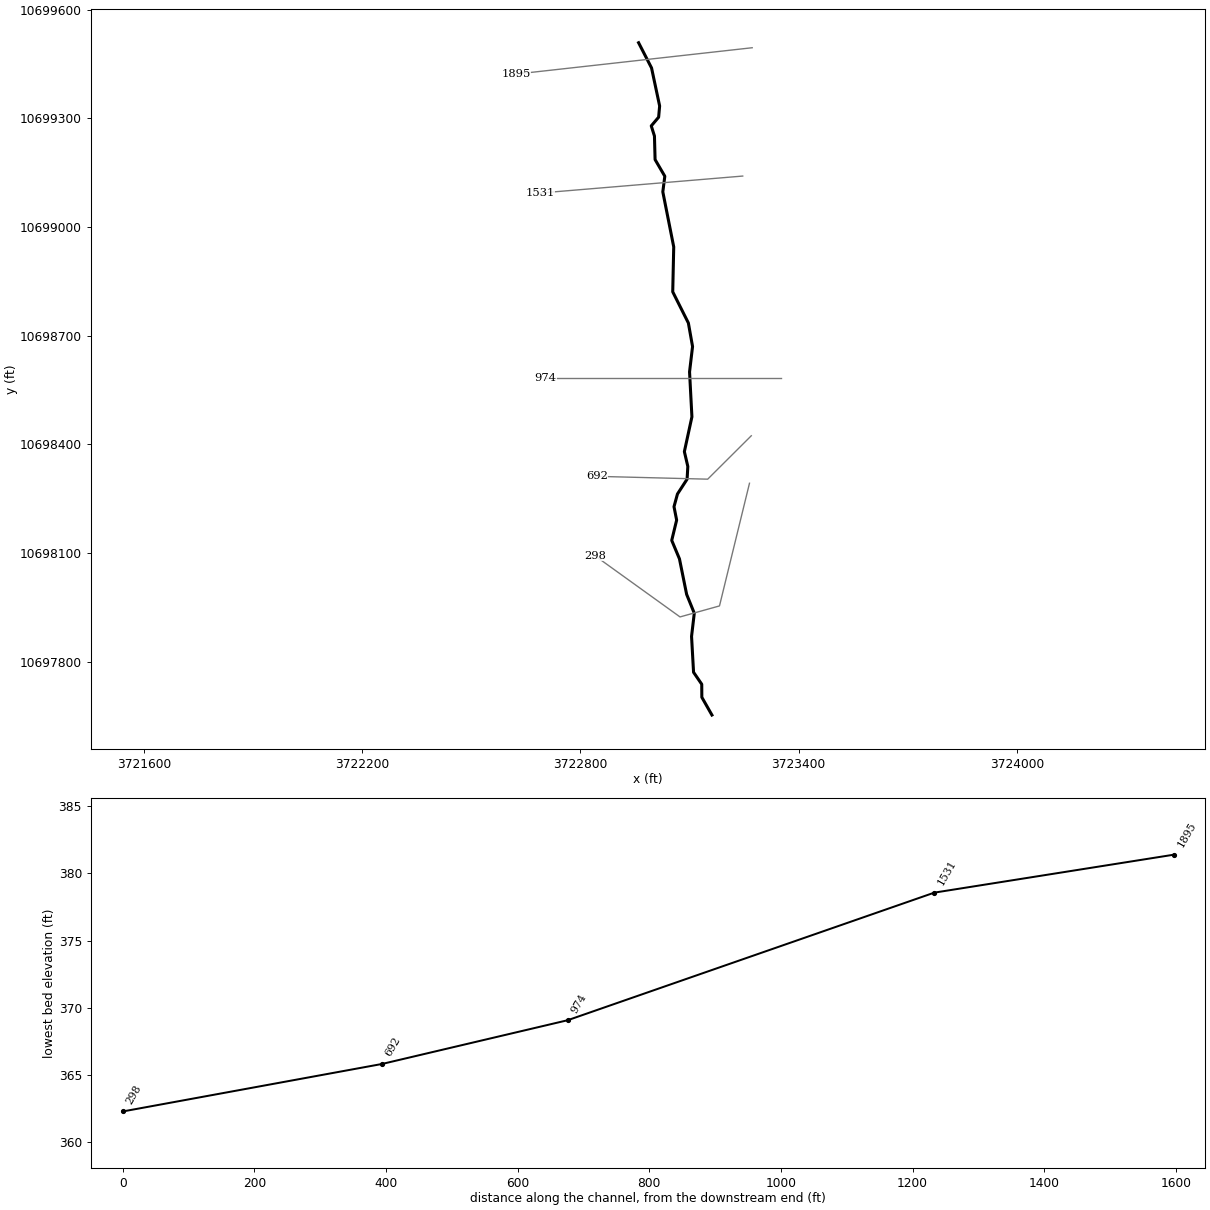
--- UNT 133 IN CACR.prj (project) ---

Proj Title=UNT 133 IN CACR Base Level Engineering
Current Plan=p01
Default Exp/Contr=0.3,0.1
English Units
Geom File=g01
Flow File=f01
Plan File=p01
BEGIN DESCRIPTION:
UNT 133 IN CACR
END DESCRIPTION:

--- UNT 133 IN CACR.p01 (plan) ---

Plan Title=Multiple Run
Short Identifier=Multiple
Geom File=g01
Flow File=f01
Subcritical Flow
K Sum by GR= 0
Std Step Tol= 0.01
Critical Tol= 0.01
Num of Std Step Trials= 20
Max Error Tol= 0.3
Flow Tol Ratio= 0.001
Split Flow NTrial= 30
Split Flow Tol= 0.02
Split Flow Ratio= 0.02
Log Output Level= 0
Friction Slope Method= 1
Unsteady Friction Slope Method= 2
Unsteady Bridges Friction Slope Method= 1
Parabolic Critical Depth
Global Vel Dist=  1 , 1 , 1
Global Log Level= 0
CheckData=True
Encroach Param= -1, 0, 0, 0
BEGIN DESCRIPTION:
Multiple Run
END DESCRIPTION:

--- UNT 133 IN CACR.f01 (steady flow) ---

Flow Title=Multiple
Number of Profiles=7
Profile Names=10-year,25-year,50-year,1pct_min,100-year,1pct_plu,500-year
River Rch & RM= UNT 133 IN CACR,Reach-1,1895
     421     563     680     604     817    1105    1185
Boundary for River Rch & Prof#=UNT 133 IN CACR,Reach-1,1
Up Type=0
Dn Type=3
Dn Slope=0.005
Boundary for River Rch & Prof#=UNT 133 IN CACR,Reach-1,2
Up Type=0
Dn Type=3
Dn Slope=0.005
Boundary for River Rch & Prof#=UNT 133 IN CACR,Reach-1,3
Up Type=0
Dn Type=3
Dn Slope=0.005
Boundary for River Rch & Prof#=UNT 133 IN CACR,Reach-1,4
Up Type=0
Dn Type=3
Dn Slope=0.005
Boundary for River Rch & Prof#=UNT 133 IN CACR,Reach-1,5
Up Type=0
Dn Type=3
Dn Slope=0.005
Boundary for River Rch & Prof#=UNT 133 IN CACR,Reach-1,6
Up Type=0
Dn Type=3
Dn Slope=0.005
Boundary for River Rch & Prof#=UNT 133 IN CACR,Reach-1,7
Up Type=0
Dn Type=3
Dn Slope=0.005

--- UNT 133 IN CACR.g01 (geometry) ---

Geom Title=Existing Conditions

River Reach=UNT 133 IN CACR,Reach-1
Reach XY= 30
      3722960.16     10699508.52      3722995.75     10699439.00
      3723018.00     10699334.00      3723015.25     10699303.00
      3722995.00     10699279.00      3723003.75     10699251.00
      3723005.50     10699186.00      3723032.25     10699140.00
      3723026.75     10699097.00      3723056.75     10698945.00
      3723054.00     10698821.00      3723097.00     10698735.00
      3723108.50     10698670.00      3723100.25     10698600.00
      3723106.75     10698476.00      3723086.00     10698380.00
      3723095.50     10698339.00      3723093.50     10698304.00
      3723067.00     10698263.00      3723057.50     10698228.00
      3723064.75     10698191.00      3723051.25     10698135.00
      3723072.50     10698084.00      3723092.25     10697986.00
      3723113.25     10697934.00      3723105.75     10697870.00
      3723111.25     10697771.00      3723133.75     10697738.00
      3723134.00     10697702.00      3723161.75     10697653.00

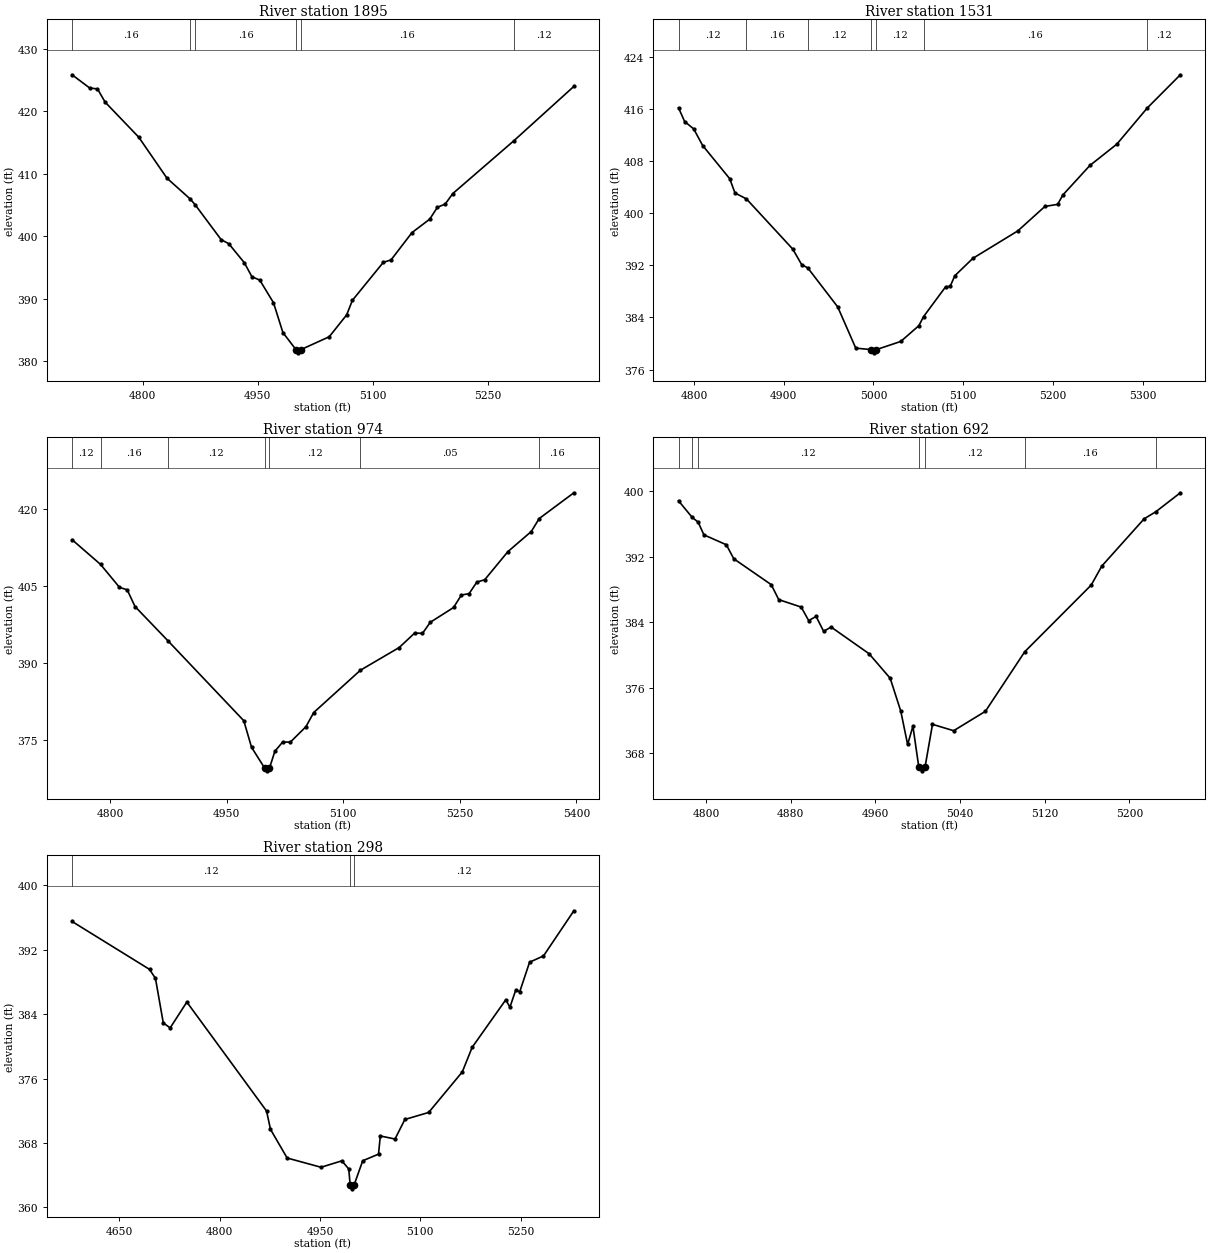
Type RM Length L Ch R = 1,1895,364,364,364
BEGIN DESCRIPTION:
Mapping XS eb641841
END DESCRIPTION:
XS GIS Cut Line= 2
      3723272.47     10699494.70      3722623.03     10699421.97
#Sta/Elev= 30
  4708.2  425.85  4731.2  423.73  4741.3  423.59  4751.3  421.47  4795.1  415.86
  4831.8  409.31  4862.0  405.99  4868.4  405.08  4902.3  399.49  4912.3  398.83
  4932.5  395.80  4942.5  393.54  4952.6  393.02  4970.5  389.40  4982.8  384.62
  4999.9  381.88  5002.6  381.38  5005.9  381.88  5043.1  383.95  5065.8  387.45
  5073.3  389.78  5113.6  395.86  5123.6  396.24  5150.9  400.61  5174.0  402.76
  5184.0  404.66  5194.1  405.17  5204.1  406.86  5283.3  415.27  5361.7  423.99
#Mann=6,-1,0
  4708.2    0.16       0  4862.0    0.05       0  4868.4    0.16       0
  4999.9    0.07       0  5005.9    0.16       0  5283.3    0.12       0
Bank Sta=4999.9,5005.9
Exp/Cntr=0.3,0.1

Type RM Length L Ch R = 1,1531,557,557,557
BEGIN DESCRIPTION:
Mapping XS 93d619f4
END DESCRIPTION:
XS GIS Cut Line= 2
      3723246.43     10699140.54      3722689.19     10699093.67
#Sta/Elev= 30
  4782.8  416.13  4789.6  414.03  4799.7  412.90  4809.7  410.35  4839.8  405.27
  4845.7  403.08  4858.5  402.16  4910.1  394.47  4920.1  392.07  4926.8  391.59
  4960.2  385.60  4980.3  379.28  4997.4  379.06  5000.1  378.56  5003.4  379.06
  5030.5  380.31  5050.6  382.72  5055.9  384.12  5080.4  388.68  5085.5  388.76
  5090.7  390.38  5110.8  393.05  5160.9  397.26  5191.1  401.01  5205.3  401.33
  5211.1  402.77  5241.2  407.29  5271.3  410.57  5305.1  416.10  5342.0  421.20
#Mann=7,-1,0
  4782.8    0.12       0  4858.5    0.16       0  4926.8    0.12       0
  4997.4    0.07       0  5003.4    0.12       0  5055.9    0.16       0
  5305.1    0.12       0
Bank Sta=4997.4,5003.4
Exp/Cntr=0.3,0.1

Type RM Length L Ch R = 1,974,282,282,282
BEGIN DESCRIPTION:
Mapping XS 15913d57
END DESCRIPTION:
XS GIS Cut Line= 2
      3723350.61     10698583.25      3722704.81     10698583.25
#Sta/Elev= 30
  4750.9  413.99  4787.5  409.20  4811.9  404.74  4821.9  404.24  4831.9  401.01
  4874.1  394.38  4971.9  378.82  4981.9  373.65  4998.9  369.58  5001.6  369.08
  5004.9  369.58  5011.9  372.88  5021.9  374.67  5031.9  374.67  5051.9  377.66
  5061.9  380.41  5122.0  388.63  5171.9  393.04  5191.9  395.86  5201.9  395.79
  5211.9  397.94  5241.9  400.82  5251.9  403.23  5261.9  403.52  5271.9  405.77
  5281.9  406.20  5311.9  411.69  5341.9  415.58  5352.1  418.10  5396.7  423.11
#Mann=7,-1,0
  4750.9    0.12       0  4787.5    0.16       0  4874.1    0.12       0
  4998.9    0.07       0  5004.9    0.12       0  5122.0    0.05       0
  5352.1    0.16       0
Bank Sta=4998.9,5004.9
Exp/Cntr=0.3,0.1

Type RM Length L Ch R = 1,692,394,394,394
BEGIN DESCRIPTION:
Mapping XS c40d7d7e
END DESCRIPTION:
XS GIS Cut Line= 3
      3723269.94     10698423.75      3723150.13     10698303.94
      3722845.46     10698311.76
#Sta/Elev= 30
  4774.0  398.81  4786.8  396.80  4792.5  396.21  4798.0  394.65  4819.2  393.44
  4826.2  391.73  4861.6  388.57  4868.7  386.74  4889.9  385.83  4897.0  384.18
  4904.0  384.69  4911.1  382.87  4918.2  383.39  4954.0  380.14  4974.0  377.14
  4984.0  373.13  4990.5  369.05  4995.5  371.28  5001.0  366.33  5003.7  365.83
  5007.0  366.33  5014.0  371.51  5034.0  370.73  5064.0  373.10  5101.2  380.38
  5164.0  388.52  5174.0  390.84  5214.0  396.61  5225.0  397.47  5248.2  399.79
#Mann=7,-1,0
  4774.0    0.12       0  4786.8    0.16       0  4792.5    0.12       0
  5001.0    0.07       0  5007.0    0.12       0  5101.2    0.16       0
  5225.0    0.12       0
Bank Sta=5001,5007
Exp/Cntr=0.3,0.1

Type RM Length L Ch R = 1,298,0,0,0
BEGIN DESCRIPTION:
UNT 133 IN CACR 1.0
END DESCRIPTION:
XS GIS Cut Line= 4
      3723265.01     10698292.69      3723182.54     10697954.12
      3723074.03     10697923.74      3722839.63     10698093.03
#Sta/Elev= 30
  4579.4  395.52  4695.2  389.57  4704.1  388.45  4715.8  382.91  4726.1  382.30
  4751.0  385.51  4870.2  371.97  4876.1  369.69  4901.0  366.13  4951.7  364.98
  4982.8  365.78  4993.1  364.77  4995.2  362.80  4998.0  362.30  5001.2  362.80
  5014.0  365.79  5037.6  366.61  5040.3  368.87  5062.3  368.49  5077.0  370.92
  5112.6  371.79  5162.9  376.83  5177.6  379.88  5227.9  385.79  5234.1  384.87
  5242.6  386.95  5248.8  386.80  5263.5  390.46  5284.3  391.24  5329.7  396.85
#Mann=3,-1,0
  4579.4    0.12       0  4995.2    0.07       0  5001.2    0.12       0
Bank Sta=4995.2,5001.2
Exp/Cntr=0.3,0.1

Chan Stop Cuts=-1