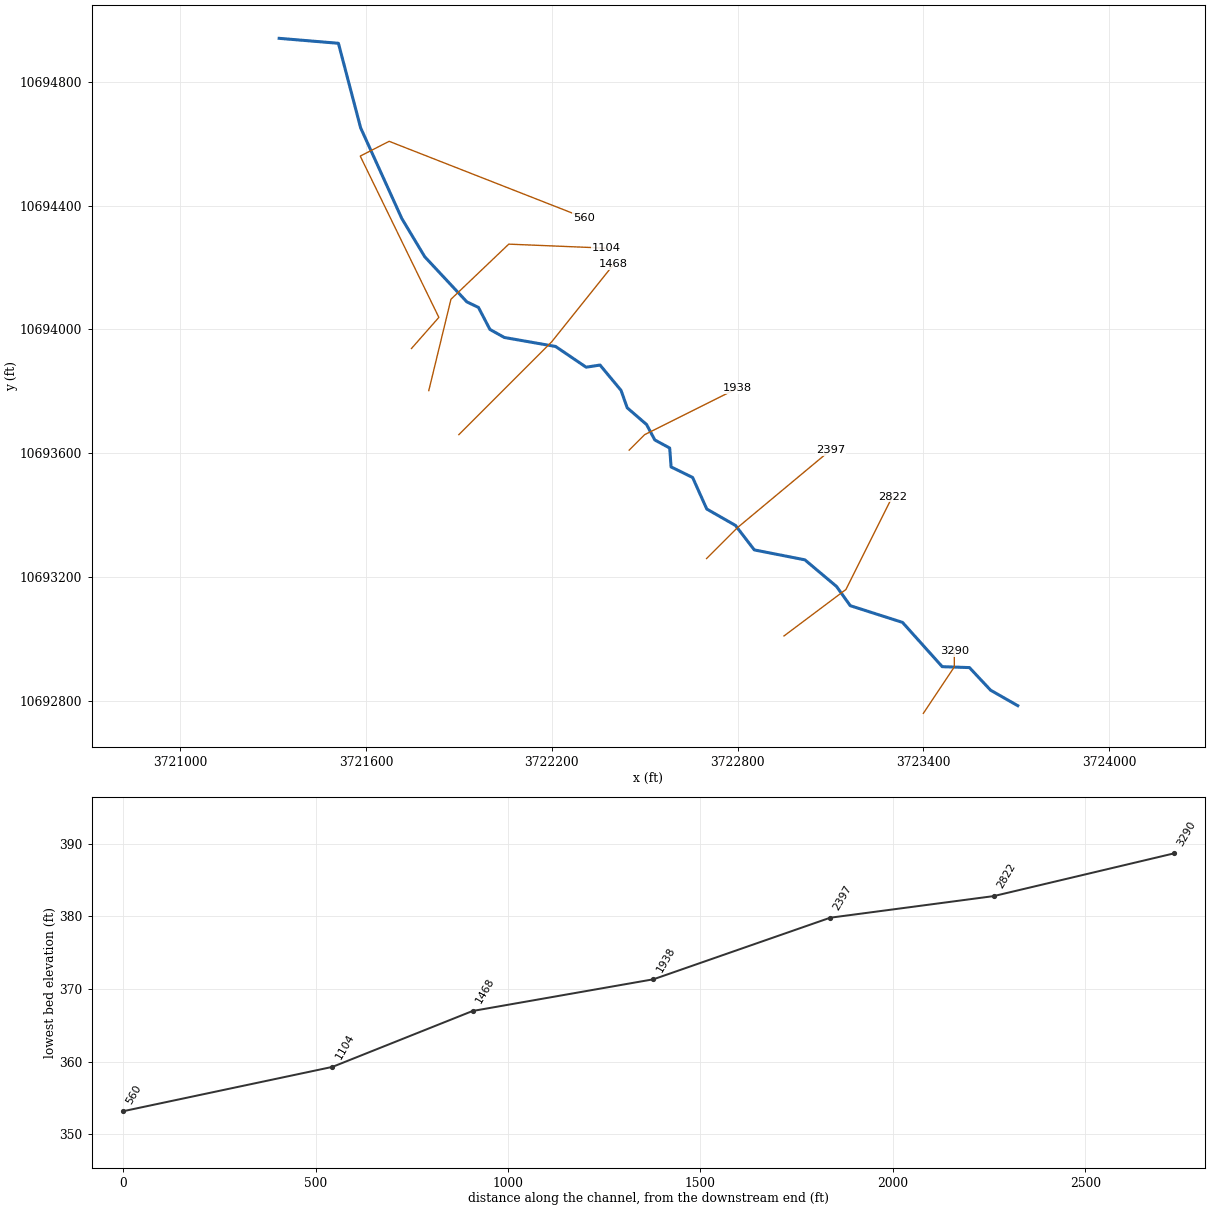
--- UNT 134 IN CACR.prj (project) ---

Proj Title=UNT 134 IN CACR Base Level Engineering
Current Plan=p01
Default Exp/Contr=0.3,0.1
English Units
Geom File=g01
Flow File=f01
Plan File=p01
BEGIN DESCRIPTION:
UNT 134 IN CACR
END DESCRIPTION:

--- UNT 134 IN CACR.p01 (plan) ---

Plan Title=Multiple Run
Short Identifier=Multiple
Geom File=g01
Flow File=f01
Subcritical Flow
K Sum by GR= 0
Std Step Tol= 0.01
Critical Tol= 0.01
Num of Std Step Trials= 20
Max Error Tol= 0.3
Flow Tol Ratio= 0.001
Split Flow NTrial= 30
Split Flow Tol= 0.02
Split Flow Ratio= 0.02
Log Output Level= 0
Friction Slope Method= 1
Unsteady Friction Slope Method= 2
Unsteady Bridges Friction Slope Method= 1
Parabolic Critical Depth
Global Vel Dist=  1 , 1 , 1
Global Log Level= 0
CheckData=True
Encroach Param= -1, 0, 0, 0
BEGIN DESCRIPTION:
Multiple Run
END DESCRIPTION:

--- UNT 134 IN CACR.f01 (steady flow) ---

Flow Title=Multiple
Number of Profiles=7
Profile Names=10-year,25-year,50-year,1pct_min,100-year,1pct_plu,500-year
River Rch & RM= UNT 134 IN CACR,Reach-1,3290
     258     334     395     345     467     631     652
Boundary for River Rch & Prof#=UNT 134 IN CACR,Reach-1,1
Up Type=0
Dn Type=3
Dn Slope=0.005
Boundary for River Rch & Prof#=UNT 134 IN CACR,Reach-1,2
Up Type=0
Dn Type=3
Dn Slope=0.005
Boundary for River Rch & Prof#=UNT 134 IN CACR,Reach-1,3
Up Type=0
Dn Type=3
Dn Slope=0.005
Boundary for River Rch & Prof#=UNT 134 IN CACR,Reach-1,4
Up Type=0
Dn Type=3
Dn Slope=0.005
Boundary for River Rch & Prof#=UNT 134 IN CACR,Reach-1,5
Up Type=0
Dn Type=3
Dn Slope=0.005
Boundary for River Rch & Prof#=UNT 134 IN CACR,Reach-1,6
Up Type=0
Dn Type=3
Dn Slope=0.005
Boundary for River Rch & Prof#=UNT 134 IN CACR,Reach-1,7
Up Type=0
Dn Type=3
Dn Slope=0.005

--- UNT 134 IN CACR.g01 (geometry) ---

Geom Title=Existing Conditions

River Reach=UNT 134 IN CACR,Reach-1
Reach XY= 30
      3723704.50     10692785.00      3723616.75     10692835.00
      3723548.50     10692908.00      3723460.50     10692911.00
      3723332.25     10693054.00      3723163.50     10693108.00
      3723119.25     10693170.00      3723017.00     10693256.00
      3722853.75     10693288.00      3722793.00     10693367.00
      3722700.25     10693420.00      3722654.50     10693522.00
      3722585.00     10693556.00      3722580.50     10693617.00
      3722532.50     10693643.00      3722505.75     10693693.00
      3722443.25     10693747.00      3722423.50     10693803.00
      3722355.50     10693885.00      3722310.75     10693878.00
      3722212.00     10693945.00      3722046.50     10693974.00
      3722000.00     10694000.00      3721963.00     10694071.00
      3721925.50     10694089.00      3721789.25     10694235.00
      3721715.50     10694358.00      3721582.50     10694651.00
      3721510.75     10694924.00      3721319.50     10694940.00

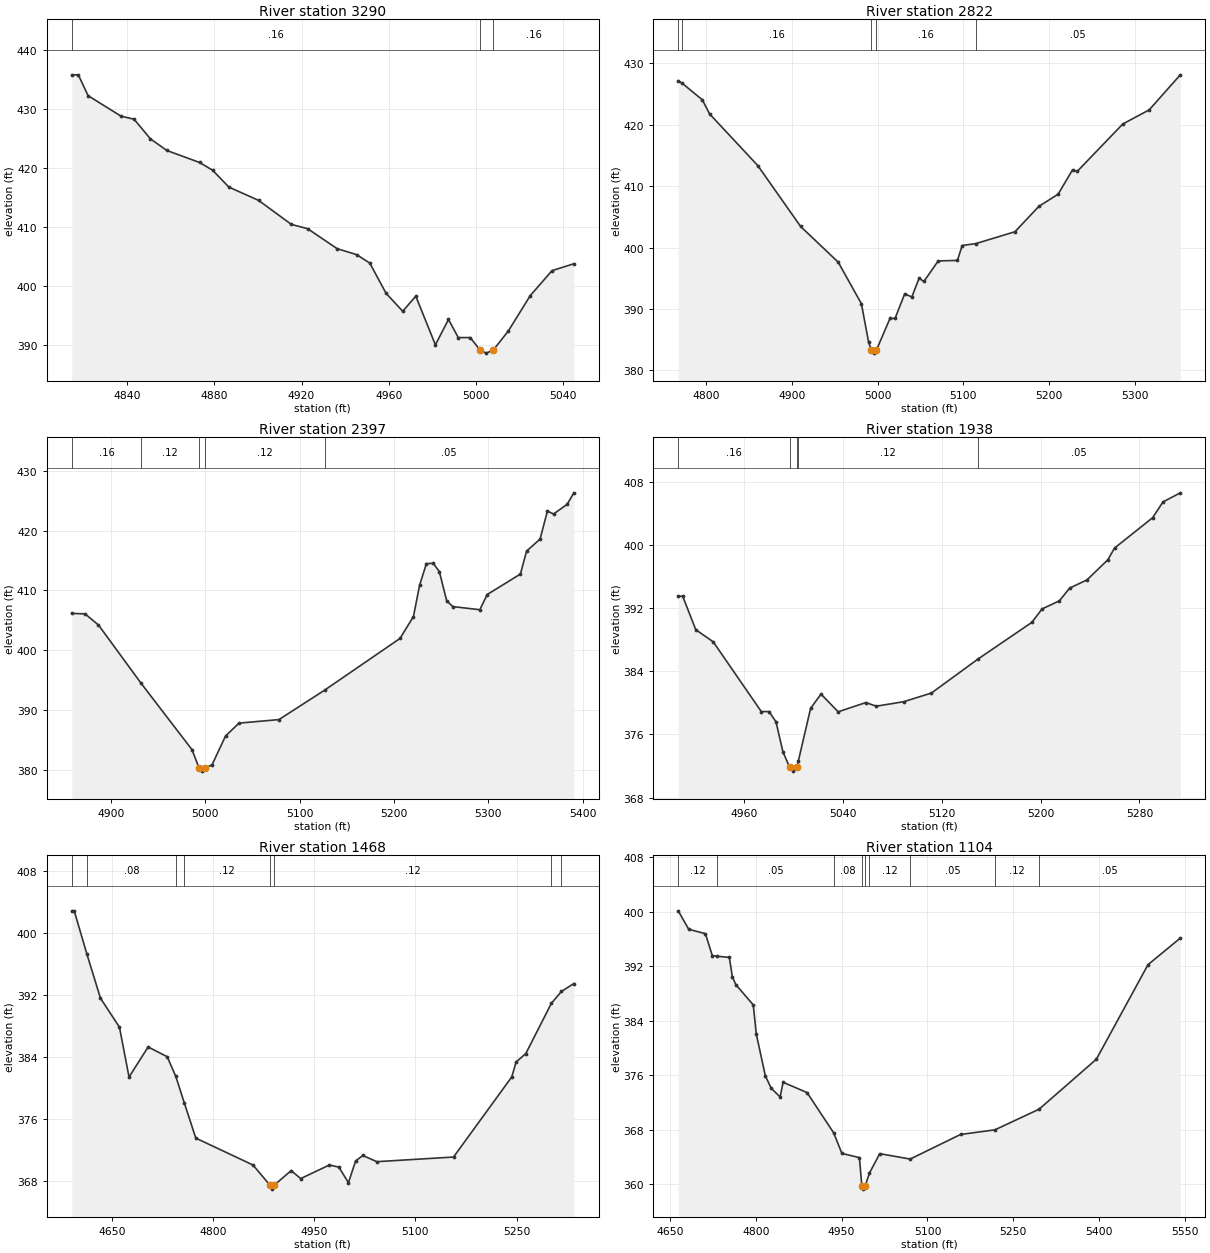
Type RM Length L Ch R = 1,3290,468,468,468
BEGIN DESCRIPTION:
UNT 134 IN CACR 6.0
END DESCRIPTION:
XS GIS Cut Line= 3
      3723399.59     10692760.17      3723499.61     10692910.19
      3723499.61     10692960.19
#Sta/Elev= 30
  4814.6  435.74  4817.6  435.74  4822.1  432.21  4837.2  428.75  4843.2  428.23
  4850.7  424.90  4858.2  422.95  4873.2  420.92  4879.2  419.61  4886.7  416.75
  4900.3  414.51  4915.3  410.45  4922.8  409.72  4936.3  406.35  4945.3  405.33
  4951.3  403.90  4958.8  398.78  4966.4  395.76  4972.4  398.31  4981.4  390.08
  4987.4  394.37  4991.9  391.31  4997.4  391.31  5001.9  389.18  5004.7  388.68
  5007.9  389.18  5014.9  392.45  5024.9  398.40  5034.9  402.63  5044.9  403.79
#Mann=3,-1,0
  4814.6    0.16       0  5001.9    0.07       0  5007.9    0.16       0
Bank Sta=5001.9,5007.9
Exp/Cntr=0.3,0.1

Type RM Length L Ch R = 1,2822,425,425,425
BEGIN DESCRIPTION:
UNT 134 IN CACR 5.0
END DESCRIPTION:
XS GIS Cut Line= 3
      3722949.59     10693010.17      3723149.61     10693160.19
      3723299.59     10693460.16
#Sta/Elev= 30
  4767.6  427.17  4772.1  426.77  4795.7  424.06  4804.1  421.77  4860.3  413.36
  4910.3  403.43  4954.1  397.62  4981.2  390.84  4989.5  384.62  4992.7  383.30
  4995.5  382.80  4998.7  383.30  5014.5  388.45  5020.4  388.45  5031.6  392.45
  5040.0  391.95  5048.4  395.00  5054.0  394.47  5070.7  397.82  5093.1  397.90
  5098.7  400.33  5114.6  400.64  5160.2  402.57  5188.1  406.71  5210.5  408.68
  5227.3  412.65  5232.8  412.40  5286.0  420.13  5316.7  422.42  5353.0  428.13
#Mann=5,-1,0
  4767.6    0.05       0  4772.1    0.16       0  4992.7    0.07       0
  4998.7    0.16       0  5114.6    0.05       0
Bank Sta=4992.7,4998.7
Exp/Cntr=0.3,0.1

Type RM Length L Ch R = 1,2397,459,459,459
BEGIN DESCRIPTION:
UNT 134 IN CACR 4.0
END DESCRIPTION:
XS GIS Cut Line= 3
      3722699.62     10693260.20      3722799.61     10693360.19
      3723099.60     10693610.18
#Sta/Elev= 30
  4858.7  406.17  4872.8  406.09  4887.0  404.23  4932.2  394.48  4986.0  383.42
  4993.6  380.32  4996.3  379.82  4999.6  380.32  5007.3  380.87  5021.6  385.69
  5035.9  387.84  5078.2  388.43  5126.6  393.35  5206.4  401.98  5220.7  405.65
  5227.2  410.88  5234.4  414.48  5241.6  414.54  5248.1  413.16  5255.9  408.26
  5262.4  407.31  5291.0  406.78  5298.8  409.32  5334.0  412.74  5340.5  416.57
  5354.8  418.58  5362.6  423.26  5369.1  422.77  5383.5  424.39  5390.6  426.31
#Mann=5,-1,0
  4858.7    0.16       0  4932.2    0.12       0  4993.6    0.07       0
  4999.6    0.12       0  5126.6    0.05       0
Bank Sta=4993.6,4999.6
Exp/Cntr=0.3,0.1

Type RM Length L Ch R = 1,1938,470,470,470
BEGIN DESCRIPTION:
UNT 134 IN CACR 3.0
END DESCRIPTION:
XS GIS Cut Line= 3
      3722449.58     10693610.16      3722499.61     10693660.19
      3722799.65     10693810.21
#Sta/Elev= 30
  4906.9  393.48  4910.5  393.48  4921.1  389.24  4935.2  387.71  4974.1  378.88
  4980.4  378.88  4986.0  377.57  4991.6  373.78  4997.0  371.84  4999.8  371.34
  5003.0  371.84  5004.1  372.64  5014.0  379.29  5022.4  381.09  5036.3  378.85
  5058.7  380.02  5067.1  379.56  5089.4  380.13  5111.8  381.23  5149.6  385.55
  5192.9  390.16  5201.3  391.88  5215.2  392.89  5223.6  394.51  5237.6  395.55
  5254.4  398.08  5259.9  399.58  5290.7  403.42  5299.1  405.42  5313.1  406.57
#Mann=5,-1,0
  4906.9    0.16       0  4997.0    0.07       0  5003.0    0.16       0
  5004.1    0.12       0  5149.6    0.05       0
Bank Sta=4997,5003
Exp/Cntr=0.3,0.1

Type RM Length L Ch R = 1,1468,364,364,364
BEGIN DESCRIPTION:
UNT 134 IN CACR 2.0
END DESCRIPTION:
XS GIS Cut Line= 3
      3721899.59     10693660.17      3722199.61     10693960.19
      3722399.58     10694210.15
#Sta/Elev= 30
  4590.6  402.87  4594.2  402.87  4613.1  397.27  4633.1  391.61  4661.3  387.86
  4675.5  381.43  4703.8  385.31  4732.1  384.05  4744.8  381.52  4757.3  378.13
  4774.5  373.55  4859.3  370.08  4884.6  367.47  4887.4  366.97  4890.6  367.47
  4915.9  369.36  4930.0  368.33  4972.5  370.08  4986.6  369.81  5000.8  367.80
  5011.4  370.60  5022.1  371.31  5042.9  370.51  5156.6  371.11  5243.0  381.45
  5249.4  383.37  5263.8  384.46  5301.7  390.94  5316.6  392.47  5335.0  393.49
#Mann=8,-1,0
  4590.6    0.12       0  4613.1    0.08       0  4744.8    0.05       0
  4757.3    0.12       0  4884.6    0.07       0  4890.6    0.12       0
  5301.7    0.05       0  5316.6    0.08       0
Bank Sta=4884.6,4890.6
Exp/Cntr=0.3,0.1

Type RM Length L Ch R = 1,1104,544,544,544
BEGIN DESCRIPTION:
Mapping XS cc303d3f
END DESCRIPTION:
XS GIS Cut Line= 4
      3721802.57     10693802.38      3721874.18     10694097.48
      3722060.81     10694275.43      3722376.11     10694262.47
#Sta/Elev= 30
  4664.6  400.16  4682.9  397.45  4712.1  396.80  4724.1  393.58  4732.6  393.49
  4753.9  393.32  4759.1  390.47  4765.2  389.32  4795.7  386.33  4800.9  382.08
  4816.7  375.94  4827.0  374.09  4842.6  372.82  4847.8  374.97  4889.6  373.46
  4936.2  367.53  4950.5  364.52  4981.1  363.90  4985.3  359.77  4988.0  359.27
  4991.3  359.77  4998.7  361.64  5016.6  364.48  5069.8  363.69  5157.8  367.30
  5217.8  367.98  5295.1  371.02  5395.1  378.36  5485.2  392.24  5541.7  396.16
#Mann=9,-1,0
  4664.6    0.12       0  4732.6    0.05       0  4936.2    0.08       0
  4985.3    0.07       0  4991.3    0.08       0  4998.7    0.12       0
  5069.8    0.05       0  5217.8    0.12       0  5295.1    0.05       0
Bank Sta=4985.3,4991.3
Exp/Cntr=0.3,0.1

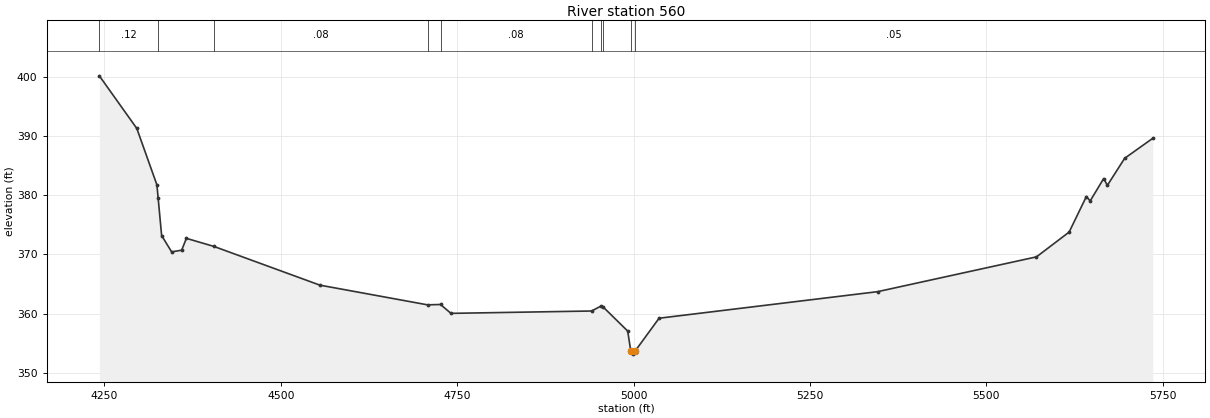
Type RM Length L Ch R = 1,560,0,0,0
BEGIN DESCRIPTION:
UNT 134 IN CACR 1.0
END DESCRIPTION:
XS GIS Cut Line= 5
      3721746.72     10693938.47      3721835.11     10694038.89
      3721581.21     10694559.72      3721674.52     10694607.46
      3722303.07     10694361.20
#Sta/Elev= 30
  4242.7  400.20  4295.8  391.31  4324.3  381.77  4326.1  379.47  4331.0  373.20
  4345.2  370.44  4359.4  370.73  4366.1  372.73  4405.2  371.36  4555.3  364.82
  4707.9  361.49  4726.3  361.55  4741.1  360.05  4940.4  360.45  4953.1  361.24
  4957.2  361.08  4991.6  357.06  4996.0  353.66  4998.8  353.16  5002.0  353.66
  5036.1  359.23  5345.9  363.72  5571.0  369.60  5617.3  373.79  5641.7  379.80
  5647.1  379.05  5666.2  382.83  5671.5  381.69  5696.0  386.26  5735.8  389.64
#Mann=10,-1,0
  4242.7    0.12       0  4326.1    0.05       0  4405.2    0.08       0
  4707.9    0.05       0  4726.3    0.08       0  4940.4    0.05       0
  4953.1    0.08       0  4957.2    0.05       0  4996.0    0.04       0
  5002.0    0.05       0
Bank Sta=4996,5002
Exp/Cntr=0.3,0.1

Chan Stop Cuts=-1