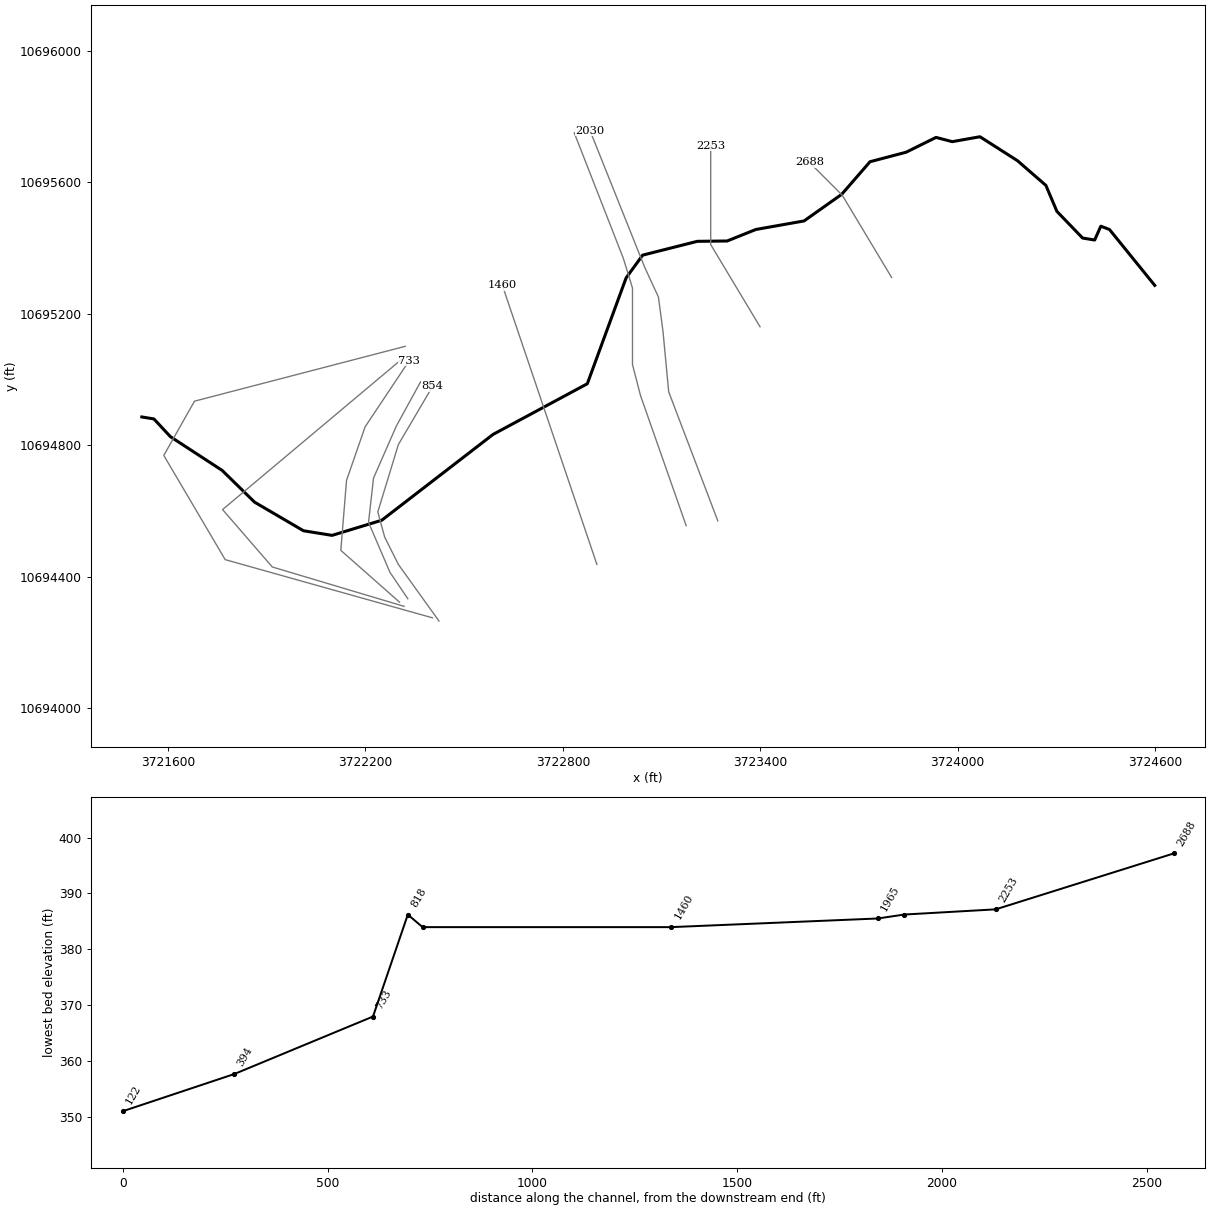
--- UNT 135 IN CACR.prj (project) ---

Proj Title=UNT 135 IN CACR Base Level Engineering
Current Plan=p01
Default Exp/Contr=0.3,0.1
English Units
Geom File=g01
Flow File=f01
Plan File=p01
Y Axis Title=Elevation
X Axis Title(PF)=Main Channel Distance
X Axis Title(XS)=Station
BEGIN DESCRIPTION:
UNT 135 IN CACR
END DESCRIPTION:
DSS Export Rating Curves= 0
DSS Export Rating Curve Sorted= 0
DSS Export Volume Flow Curves= 0
DXF OffsetX= 0
DXF OffsetY= 0
DXF ScaleX= 1
DXF ScaleY= 10

--- UNT 135 IN CACR.p01 (plan) ---

Plan Title=Multiple Run
Program Version=4.10
Short Identifier=Multiple
Geom File=g01
Flow File=f01
Subcritical Flow
K Sum by GR= 0
Std Step Tol= 0.01
Critical Tol= 0.01
Num of Std Step Trials= 20
Max Error Tol= 0.3
Flow Tol Ratio= 0.001
Split Flow NTrial= 30
Split Flow Tol= 0.02
Split Flow Ratio= 0.02
Log Output Level= 0
Friction Slope Method= 1
Unsteady Friction Slope Method= 2
Unsteady Bridges Friction Slope Method= 1
Parabolic Critical Depth
Global Vel Dist= 1 , 1 , 1
Global Log Level= 0
CheckData=True
Encroach Param=-1 ,0,0, 0
BEGIN DESCRIPTION:
Multiple Run
END DESCRIPTION:
Computation Interval=1HOUR
Output Interval=1HOUR
Run HTab= 0
Run UNet= 0
Run PostProcess= 0
Run WQNet= 0
UNET Theta= 1
UNET Theta Warmup= 1
UNET ZTol= 0.02
UNET ZSATol= 0.05
UNET MxIter= 20
UNET MaxInSteps= 0
UNET DtIC= 0
UNET DtMin= 0
UNET MaxCRTS= 20
UNET WFStab= 2
UNET SFStab= 1
UNET WFX= 1
UNET SFX= 1
UNET DSS MLevel= 4
UNET DZMax Abort= 100
UNET Convert EG Bridges= 0
UNET Use Existing IB Tables=-1
UNET Froude Reduction=False
UNET Froude Limit= 1
UNET Froude Power= 10
UNET Time Slicing=0,0, 5
UNET Junction Losses=0
Instantaneous Interval=1HOUR
Write IC File= 0
Write IC File at Sim End=0
Echo Input=False
Echo Parameters=False
Echo Output=False
Write Detailed= 0
WQ AD Non Conservative
WQ ULTIMATE=-1
WQ Max Comp Step=1HOUR
WQ Output Interval=15MIN
WQ Output Selected Increments= 0
WQ Output face flow=0
WQ Output face velocity=0
WQ Output face area=0
WQ Output face dispersion=0
WQ Output cell volume=0
WQ Output cell surface area=0
WQ Output cell continuity=0
WQ Output cumulative cell continuity=0
WQ Output face conc=0
WQ Output face dconc_dx=0
WQ Output face courant=0
WQ Output face peclet=0
WQ Output face adv mass=0
WQ Output face disp mass=0
WQ Output cell mass=0
WQ Output cell source sink temp=0
WQ Output cell source sink nsm=0
WQ Output MaxMinRange=-1
WQ Daily Max Min Mean=-1
WQ Daily Range=0
WQ Daily Time=0
WQ Create Restart=0
WQ Fixed Restart=0
WQ System Summary=0
WQ Use Fixed Temperature=0
Sorting and Armoring Iterations= 10
XS Update Threshold= 0.02
Hydraulics Update Threshold= 0.02
Energy Slope Method= 1
Volume Change Method= 0
XS Weighting Method= 0
Number of US Weighted Cross Sections= 1
Number of DS Weighted Cross Sections= 1
Upstream XS Weight=0.25
Main XS Weight=0.5
Downstream XS Weight=0.25
Number of DS XS's Weighted with US Boundary= 1
Upstream Boundary Weight= 1
Weight of XSs Associated with US Boundary= 0
Number of US XS's Weighted with DS Boundary= 1
Downstream Boundary Weight= 0.5
Weight of XSs Associated with DS Boundary= 0.5
Sediment Output Level= 4
Mass or Volume Output= 0
Output Increment Type= 1
Profile and TS Output Increment= 10
XS Output Flag= 0
XS Output Increment= 10
Disregard all LS=0
Disregard all Conn=0
Disregard all Breaches=0
Disregard all Pumps=0

--- UNT 135 IN CACR.f01 (steady flow) ---

Flow Title=Multiple
Program Version=4.10
Number of Profiles= 7
Profile Names=10-year,25-year,50-year,1pct_min,100-year,1pct_plu,500-year
River Rch & RM=UNT 135 IN CACR,Reach-1         ,2688
     347     465     562     503     680     919     993
Boundary for River Rch & Prof#=UNT 135 IN CACR,Reach-1         , 1
Up Type= 0
Dn Type= 3
Dn Slope=0.0243
Boundary for River Rch & Prof#=UNT 135 IN CACR,Reach-1         , 2
Up Type= 0
Dn Type= 3
Dn Slope=0.0243
Boundary for River Rch & Prof#=UNT 135 IN CACR,Reach-1         , 3
Up Type= 0
Dn Type= 3
Dn Slope=0.0243
Boundary for River Rch & Prof#=UNT 135 IN CACR,Reach-1         , 4
Up Type= 0
Dn Type= 3
Dn Slope=0.0243
Boundary for River Rch & Prof#=UNT 135 IN CACR,Reach-1         , 5
Up Type= 0
Dn Type= 3
Dn Slope=0.0243
Boundary for River Rch & Prof#=UNT 135 IN CACR,Reach-1         , 6
Up Type= 0
Dn Type= 3
Dn Slope=0.0243
Boundary for River Rch & Prof#=UNT 135 IN CACR,Reach-1         , 7
Up Type= 0
Dn Type= 3
Dn Slope=0.0243
DSS Import GetInterval= 0
DSS Import GetPeak= 0
DSS Import FillOption= 0

--- UNT 135 IN CACR.g01 (geometry) ---

Geom Title=Existing Conditions
Program Version=4.10

River Reach=UNT 135 IN CACR ,Reach-1
Reach XY= 30
      3724599.75       10695286.        3724462.       10695456.
      3724435.75       10695466.        3724417.       10695424.
      3724380.25       10695430.      3724302.25       10695511.
      3724268.75       10695590.       3724182.5       10695665.
      3724068.25       10695738.        3723984.       10695723.
      3723934.75       10695736.        3723844.       10695691.
        3723734.       10695662.        3723648.       10695563.
       3723533.5       10695482.        3723387.       10695456.
       3723299.5       10695421.        3723209.       10695420.
      3723042.75       10695378.       3722992.5       10695309.
       3722874.5       10694987.        3722588.       10694833.
       3722249.5       10694572.       3722098.5       10694526.
       3722011.5       10694540.       3721862.9     10694626.95
      3721764.29     10694723.48        3721607.       10694826.
      3721556.75       10694880.        3721520.       10694886.

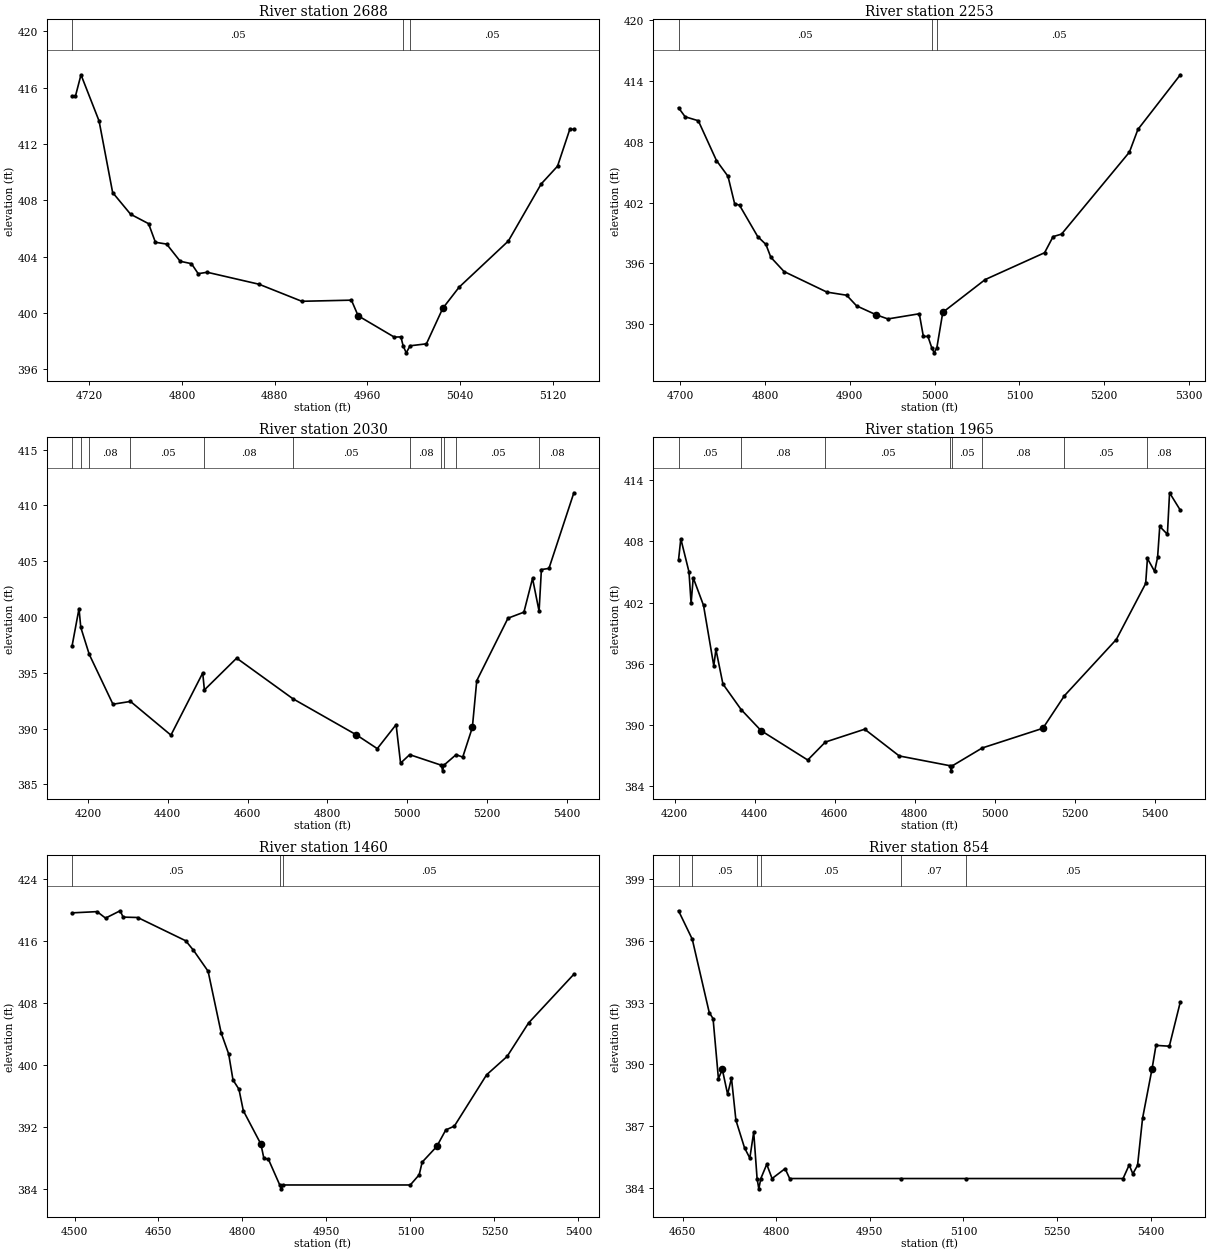
Type RM Length L Ch R = 1 ,2688    ,435,435,435
BEGIN DESCRIPTION:
UNT 135 IN CACR 4.0
END DESCRIPTION:
XS GIS Cut Line= 3
      3723799.59     10695310.22      3723649.61     10695560.19
      3723549.63     10695660.16
#Sta/Elev= 30
  4705.2   415.4  4708.1   415.4  4712.9  416.92  4728.5  413.64  4740.2  408.56
  4755.7  407.02  4771.2  406.35  4777.1  405.03  4786.8   404.9  4798.5  403.68
  4808.2  403.51    4814   402.8  4821.8   402.9  4866.5  402.05  4903.4  400.84
  4946.2  400.92    4952  399.81  4983.1   398.3  4988.9  398.31  4990.8  397.68
  4993.5  397.18  4996.8  397.68  5010.9  397.82    5025  400.34  5039.1  401.84
  5081.6  405.12  5109.9  409.17    5124  410.43  5134.6  413.05  5138.1  413.05
#Mann= 3 ,-1 , 0
  4705.2     .05       0  4990.8     .03       0  4996.8     .05       0
Bank Sta=4952,5025
XS Rating Curve= 0 ,0
Exp/Cntr=0.3,0.1

Type RM Length L Ch R = 1 ,2253    ,223,223,223
BEGIN DESCRIPTION:
UNT 135 IN CACR 3.0
END DESCRIPTION:
XS GIS Cut Line= 3
       3723399.6      10695160.2      3723249.61     10695410.19
      3723249.61     10695710.15
#Sta/Elev= 30
  4698.2  411.36    4706  410.47  4721.5  410.08  4742.9  406.15  4756.5  404.59
  4764.3  401.89  4770.1  401.73  4791.5  398.64  4801.2  397.86    4807  396.59
  4822.6  395.18  4873.1  393.15  4896.4  392.84  4908.1  391.79  4931.4   390.9
    4945   390.5    4982  391.01  4986.8  388.77  4992.2  388.77  4996.7  387.65
  4999.5  387.15  5002.7  387.65  5009.7  391.15  5059.7  394.39  5129.7  397.04
  5139.7  398.63  5149.7  398.88  5229.7  406.98  5239.7  409.22  5289.7  414.62
#Mann= 3 ,-1 , 0
  4698.2     .05       0  4996.7     .03       0  5002.7     .05       0
Bank Sta=4931.4,5009.7
XS Rating Curve= 0 ,0
Exp/Cntr=0.3,0.1

Type RM Length L Ch R = 1 ,2030    ,65,65,65
BEGIN DESCRIPTION:
Mapping XS 63bf4a57
END DESCRIPTION:
XS GIS Cut Line= 6
      3723271.23     10694570.04      3723121.92     10694962.44
      3723104.55     10695146.46      3723090.67     10695250.63
        3723049.     10695340.91       3722882.8     10695756.39
#Sta/Elev= 30
  4160.4  397.41  4177.8  400.76  4182.2  399.08  4203.4  396.66  4262.8  392.19
  4306.7  392.44    4408  389.42  4487.6  394.99  4491.8  393.47  4572.6  396.32
  4713.1  392.69  4872.7  389.44  4924.8  388.21  4971.9  390.36  4983.1  386.91
  5005.9  387.67  5085.5  386.72  5088.3  386.22  5091.5  386.72  5122.2  387.67
  5138.8  387.45  5162.9  390.11  5173.9   394.3  5252.1   399.9    5292  400.44
  5313.6  403.47    5330  400.53  5335.8  404.26  5354.7  404.36  5417.1  411.14
#Mann= 11 ,-1 , 0
  4160.4     .16       0  4182.2     .05       0  4203.4     .08       0
  4306.7     .05       0  4491.8     .08       0  4713.1     .05       0
  5005.9     .08       0  5085.5     .04       0  5091.5     .08       0
  5122.2     .05       0    5330     .08       0
Bank Sta=4872.7,5162.9
XS Rating Curve= 0 ,0
Exp/Cntr=0.3,0.1

Type RM Length L Ch R = 1 ,1965    ,505,505,505
BEGIN DESCRIPTION:
Mapping XS a8742968
END DESCRIPTION:
XS GIS Cut Line= 6
      3723175.02     10694555.58      3723036.12     10694951.44
      3723011.82     10695045.19      3723011.82     10695277.83
      3722984.04     10695368.11      3722834.73     10695750.06
#Sta/Elev= 30
  4209.8  406.18  4215.5  408.25  4235.9  405.01  4241.2  401.93  4246.5  404.43
  4272.2  401.73  4297.9   395.8  4303.2  397.41  4320.7  394.02  4366.1  391.52
    4416  389.45  4532.6  386.57  4576.6  388.33  4674.9  389.59  4761.2  386.97
  4888.2  386.01    4891  385.51  4894.2  386.01  4968.5  387.75  5120.1  389.68
  5173.9  392.87  5303.5  398.38  5376.9  403.87  5381.3  406.32  5399.2  405.06
  5406.7  406.43  5412.1  409.46  5431.2  408.69  5436.6  412.76  5463.5  411.05
#Mann= 8 ,-1 , 0
  4209.8     .05       0  4366.1     .08       0  4576.6     .05       0
  4888.2     .07       0  4894.2     .05       0  4968.5     .08       0
  5173.9     .05       0  5381.3     .08       0
Bank Sta=4416,5120.1
XS Rating Curve= 0 ,0
Exp/Cntr=0.3,0.1

Type RM Length L Ch R = 1 ,1460    ,606,606,606
BEGIN DESCRIPTION:
Mapping XS 66802935
END DESCRIPTION:
XS GIS Cut Line= 2
      3722903.55     10694437.89      3722615.93      10695286.9
#Sta/Elev= 30
  4495.6  419.66  4540.3  419.82  4555.4  418.98  4581.5  419.93  4586.8  419.11
  4612.9  419.06  4698.6  416.05  4712.5  414.82  4738.6  412.11    4762  404.12
  4775.3  401.42  4783.1  398.04  4793.7  396.85  4801.5  394.07  4832.9  389.75
  4838.2  387.92  4846.4  387.78  4866.6  384.46  4869.3  383.96  4872.6  384.46
  5099.8  384.46  5115.7  385.78    5121  387.41  5147.1  389.44  5163.2  391.58
  5178.5  392.07  5236.1  398.71  5272.8  401.09    5311  405.41    5392  411.72
#Mann= 3 ,-1 , 0
  4495.6     .05       0  4866.6    .033       0  4872.6     .05       0
Bank Sta=4832.9,5147.1
XS Rating Curve= 0 ,0
Exp/Cntr=0.3,0.1

Type RM Length L Ch R = 1 ,854     ,36,36,36
BEGIN DESCRIPTION:
Mapping XS ecc504ff
END DESCRIPTION:
XS GIS Cut Line= 6
      3722423.51     10694265.57      3722300.01     10694437.55
      3722258.35     10694520.89      3722237.51     10694597.27
      3722300.01     10694802.14      3722404.17      10694979.2
#Sta/Elev= 30
  4643.6  397.45  4665.6  396.07  4692.8  392.51  4698.9  392.22  4707.5   389.3
  4713.7  389.76  4722.2  388.55  4728.4  389.33  4735.5  387.29  4749.3  385.95
  4757.8  385.45    4764  386.71  4769.4  384.46  4772.2  383.96  4775.4  384.46
  4784.9  385.15  4793.4  384.46  4814.3  384.94  4821.6  384.46  5000.6  384.46
  5103.3  384.46  5355.6  384.46  5365.4  385.12  5371.2  384.69  5378.8   385.1
  5386.8  387.38    5402  389.78  5408.3  390.92  5429.7  390.88  5447.3  393.03
#Mann= 6 ,-1 , 0
  4643.6     .08       0  4665.6     .05       0  4769.4     .03       0
  4775.4     .05       0  5000.6     .07       0  5103.3     .05       0
Bank Sta=4713.7,5402
XS Rating Curve= 0 ,0
Exp/Cntr=0.3,0.1

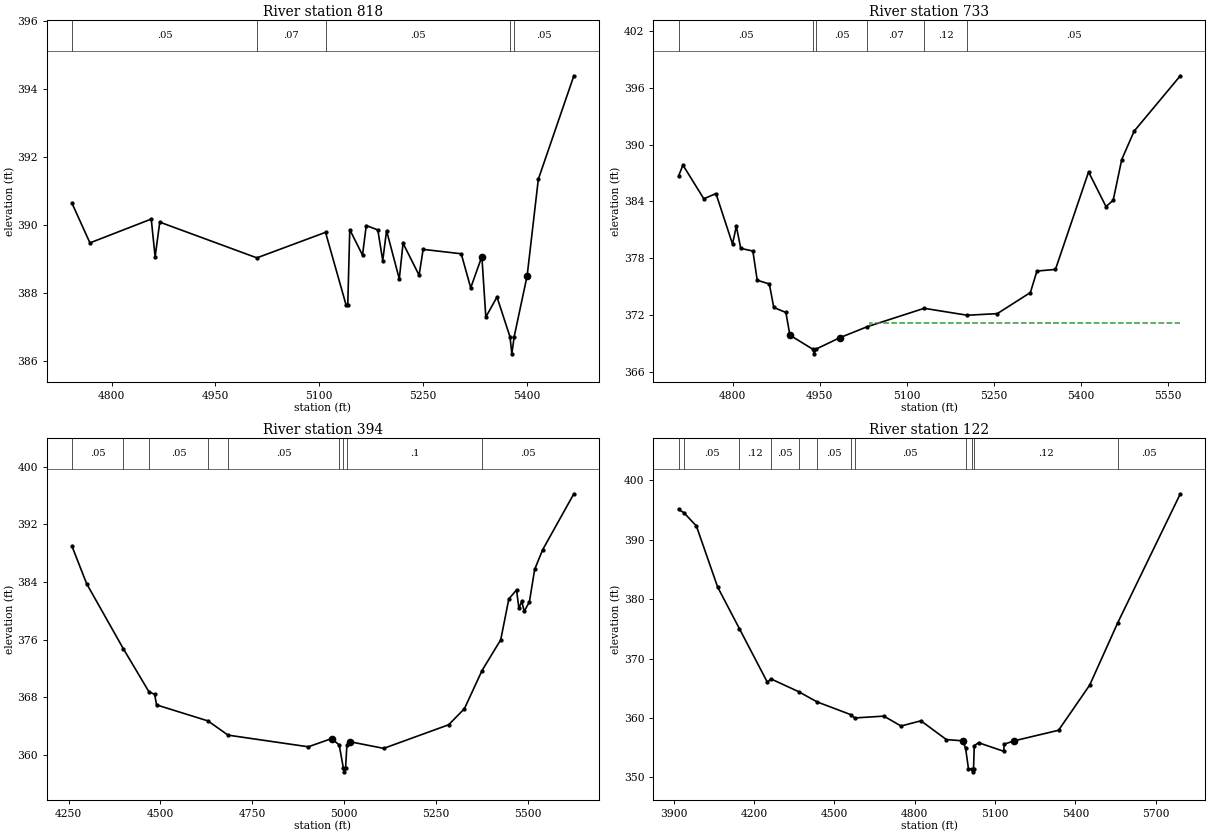
Type RM Length L Ch R = 1 ,818     ,85,85,85
BEGIN DESCRIPTION:
Mapping XS 95e5cb95
END DESCRIPTION:
XS GIS Cut Line= 6
      3722328.69     10694333.34       3722274.4     10694413.68
       3722209.3     10694565.59      3722224.49     10694700.14
      3722293.94     10694858.56       3722367.7     10694993.07
#Sta/Elev= 30
    4743  390.63  4768.8  389.47  4857.3  390.17  4862.9  389.06  4869.6  390.08
  5009.8  389.03  5108.9  389.78  5138.5  387.65    5141  387.65  5143.9  389.86
  5162.3  389.11  5167.7  389.98  5184.4  389.85  5191.5  388.95    5197  389.83
  5215.4  388.41  5220.8  389.46    5244  388.52  5249.8  389.28  5304.8  389.15
  5318.5  388.15  5334.6  389.07  5340.3  387.29  5356.4  387.88  5375.2  386.71
  5377.9  386.21  5381.2  386.71    5400  388.51  5416.1  391.34  5467.4  394.38
#Mann= 5 ,-1 , 0
    4743     .05       0  5009.8     .07       0  5108.9     .05       0
  5375.2     .03       0  5381.2     .05       0
Bank Sta=5334.6,5400
XS Rating Curve= 0 ,0
Exp/Cntr=0.3,0.1

Type RM Length L Ch R = 1 ,733     ,339,339,339
BEGIN DESCRIPTION:
UNT 135 IN CACR 2.0
END DESCRIPTION:
XS GIS Cut Line= 5
      3722303.49     10694322.96      3722125.04     10694480.44
      3722142.41     10694693.11      3722198.83     10694855.87
      3722332.54     10695056.44
#Sta/Elev= 30
  4706.8  386.67  4714.4  387.83  4750.4  384.28  4771.3  384.83  4799.8  379.51
  4806.4  381.38    4814  379.05  4834.9  378.77  4842.4  375.69  4863.3   375.3
  4870.9  372.82  4891.8  372.29  4898.7   369.9  4937.8  368.43  4940.6  367.93
  4943.8  368.43  4984.7  369.63  5031.5  370.78  5130.1  372.73  5204.3     372
  5256.1  372.17  5313.1  374.39  5324.4  376.66  5356.3  376.83  5413.4  387.11
  5443.4  383.46  5455.8  384.12  5470.5  388.41  5491.9  391.41  5571.5  397.25
#Mann= 6 ,-1 , 0
  4706.8     .05       0  4937.8     .03       0  4943.8     .05       0
  5031.5     .07       0  5130.1     .12       0  5204.3     .05       0
#XS Ineff= 2 , 0
                         5036.24          371.21
Permanent Ineff=
       F       F
Bank Sta=4898.7,4984.7
XS Rating Curve= 0 ,0
Exp/Cntr=0.3,0.1

Type RM Length L Ch R = 1 ,394     ,272,272,272
BEGIN DESCRIPTION:
Mapping XS 7391e900
END DESCRIPTION:
XS GIS Cut Line= 4
      3722317.63     10694310.16       3721916.6     10694429.94
      3721765.56     10694604.42      3722314.62     10695065.22
#Sta/Elev= 30
  4259.7  388.93  4299.4  383.75    4399  374.74  4469.3  368.71  4484.5  368.39
  4489.7  366.91  4629.5  364.69  4684.4  362.71  4902.9  361.09  4966.2  362.23
    4987  361.35  4998.3  358.11  5001.1  357.61  5004.3  358.11  5007.9  361.33
  5015.6   361.8    5108  360.87  5284.9  364.15  5327.9  366.39  5375.7  371.68
  5426.7  375.96  5448.8  381.64  5469.7  382.89  5476.2  380.34    5484  381.32
  5490.5  379.91  5504.8  381.24  5519.1  385.74  5540.9  388.48  5625.8  396.25
#Mann= 9 ,-1 , 0
  4259.7     .05       0    4399     .12       0  4469.3     .05       0
  4629.5     .07       0  4684.4     .05       0    4987     .05       0
  4998.3     .07       0  5007.9      .1       0  5375.7     .05       0
Bank Sta=4966.2,5015.6
XS Rating Curve= 0 ,0
Exp/Cntr=0.3,0.1

Type RM Length L Ch R = 1 ,122     ,0,0,0
BEGIN DESCRIPTION:
UNT 135 IN CACR 1.0
END DESCRIPTION:
XS GIS Cut Line= 5
      3722403.73     10694275.27      3721773.48     10694452.22
      3721586.85     10694769.07      3721680.17       10694934.
      3722320.88     10695100.76
#Sta/Elev= 30
  3917.8  395.08  3937.5  394.54  3984.4   392.3  4063.9  382.02  4145.3  375.01
  4249.8  365.99  4262.3  366.59  4366.4  364.43  4435.1  362.71  4560.9  360.57
  4575.5  360.01  4684.4  360.32  4748.7  358.66    4823  359.53  4918.2  356.37
  4978.9  356.17  4989.7  354.94  5000.6  351.45  5013.5  351.45  5016.2  350.95
  5019.5  351.45  5022.2  355.34  5038.1  355.85  5131.9  354.41  5134.3   355.6
  5169.7  356.15  5336.9  357.94  5453.3  365.54    5558  376.02  5791.7  397.71
#Mann= 12 ,-1 , 0
  3917.8     .08       0  3937.5     .05       0  4145.3     .12       0
  4262.3     .05       0  4366.4     .07       0  4435.1     .05       0
  4560.9     .12       0  4575.5     .05       0  4989.7     .12       0
  5013.5     .07       0  5019.5     .12       0    5558     .05       0
Bank Sta=4978.9,5169.7
XS Rating Curve= 0 ,0
Exp/Cntr=0.3,0.1

Chan Stop Cuts=-1
Use User Specified Reach Order=0
Composite Channel Slope=5