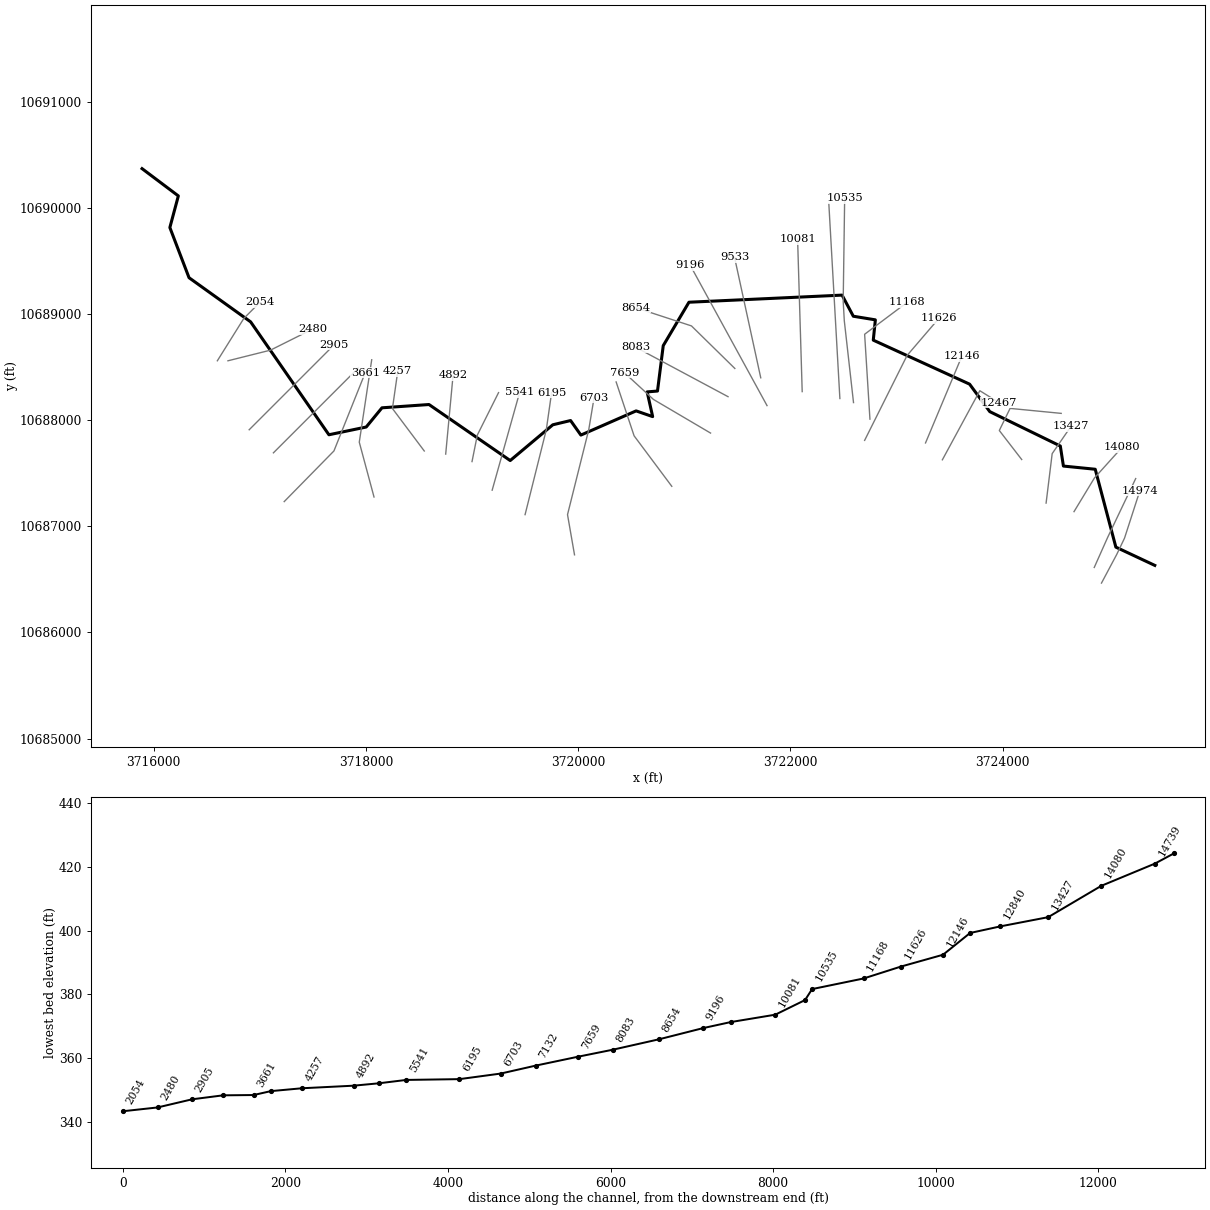
--- UNT 136 IN CACR.prj (project) ---

Proj Title=UNT 136 IN CACR Base Level Engineering
Current Plan=p01
Default Exp/Contr=0.3,0.1
English Units
Geom File=g01
Flow File=f01
Plan File=p01
Y Axis Title=Elevation
X Axis Title(PF)=Main Channel Distance
X Axis Title(XS)=Station
BEGIN DESCRIPTION:
UNT 136 IN CACR
END DESCRIPTION:
DSS Export Rating Curves= 0
DSS Export Rating Curve Sorted= 0
DSS Export Volume Flow Curves= 0
DXF OffsetX= 0
DXF OffsetY= 0
DXF ScaleX= 1
DXF ScaleY= 10

--- UNT 136 IN CACR.p01 (plan) ---

Plan Title=Multiple Run
Short Identifier=Multiple
Geom File=g01
Flow File=f01
Subcritical Flow
K Sum by GR= 0
Std Step Tol= 0.01
Critical Tol= 0.01
Num of Std Step Trials= 20
Max Error Tol= 0.3
Flow Tol Ratio= 0.001
Split Flow NTrial= 30
Split Flow Tol= 0.02
Split Flow Ratio= 0.02
Log Output Level= 0
Friction Slope Method= 1
Unsteady Friction Slope Method= 2
Unsteady Bridges Friction Slope Method= 1
Parabolic Critical Depth
Global Vel Dist=  1 , 1 , 1
Global Log Level= 0
CheckData=True
Encroach Param= -1, 0, 0, 0
BEGIN DESCRIPTION:
Multiple Run
END DESCRIPTION:

--- UNT 136 IN CACR.f01 (steady flow) ---

Flow Title=Multiple
Program Version=4.10
Number of Profiles= 7
Profile Names=10-year,25-year,50-year,1pct_min,100-year,1pct_plu,500-year
River Rch & RM=UNT 136 IN CACR,Reach-1         ,14974
     699     973    1205    1099    1486    2010    2269
River Rch & RM=UNT 136 IN CACR,Reach-1         ,12146
    1336    1924    2440    2272    3073    4156    4896
River Rch & RM=UNT 136 IN CACR,Reach-1         ,10448
    1452    2094    2657    2475    3347    4527    5337
River Rch & RM=UNT 136 IN CACR,Reach-1         ,5541
    1616    2334    2965    2762    3735    5051    5957
Boundary for River Rch & Prof#=UNT 136 IN CACR,Reach-1         , 1
Up Type= 0
Dn Type= 3
Dn Slope=0.00773
Boundary for River Rch & Prof#=UNT 136 IN CACR,Reach-1         , 2
Up Type= 0
Dn Type= 3
Dn Slope=0.00773
Boundary for River Rch & Prof#=UNT 136 IN CACR,Reach-1         , 3
Up Type= 0
Dn Type= 3
Dn Slope=0.00773
Boundary for River Rch & Prof#=UNT 136 IN CACR,Reach-1         , 4
Up Type= 0
Dn Type= 3
Dn Slope=0.00773
Boundary for River Rch & Prof#=UNT 136 IN CACR,Reach-1         , 5
Up Type= 0
Dn Type= 3
Dn Slope=0.00773
Boundary for River Rch & Prof#=UNT 136 IN CACR,Reach-1         , 6
Up Type= 0
Dn Type= 3
Dn Slope=0.00773
Boundary for River Rch & Prof#=UNT 136 IN CACR,Reach-1         , 7
Up Type= 0
Dn Type= 3
Dn Slope=0.00773
DSS Import GetInterval= 0
DSS Import GetPeak= 0
DSS Import FillOption= 0

--- UNT 136 IN CACR.g01 (geometry) ---

Geom Title=Existing Conditions
Program Version=4.10

River Reach=UNT 136 IN CACR ,Reach-1
Reach XY= 30
        3725434.       10686632.      3725067.25       10686804.
      3724872.75       10687538.        3724573.       10687568.
      3724543.75       10687757.        3723879.       10688081.
      3723688.75       10688340.      3722781.12     10688754.67
      3722800.75       10688946.        3722593.       10688980.
        3722487.       10689179.        3721044.       10689112.
      3720801.75       10688703.       3720747.5       10688275.
        3720650.       10688267.        3720702.       10688034.
        3720546.       10688088.       3720025.5       10687860.
       3719928.5       10687997.        3719761.       10687957.
       3719359.5       10687620.      3718594.25       10688148.
        3718151.       10688117.       3718002.5       10687936.
        3717651.       10687863.      3716913.25       10688927.
      3716332.75       10689343.        3716152.       10689816.
        3716232.       10690114.        3715890.       10690371.

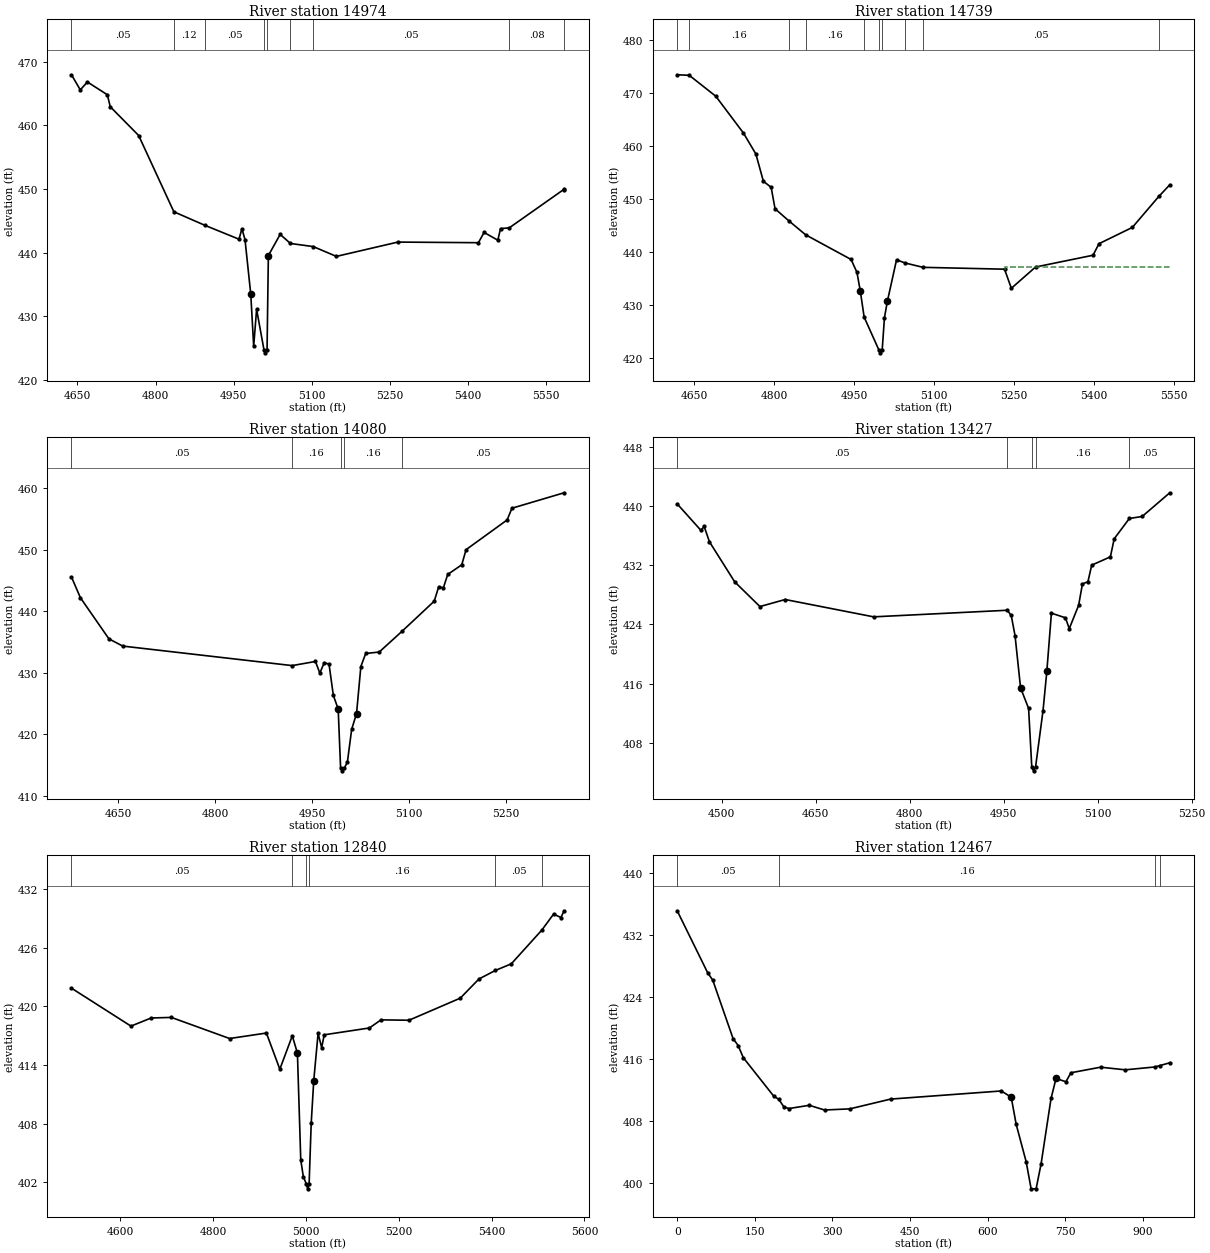
Type RM Length L Ch R = 1 ,14974   ,235,235,235
BEGIN DESCRIPTION:
UNT 136 IN CACR 29.0
END DESCRIPTION:
XS GIS Cut Line= 4
      3724931.78     10686465.31      3725074.99     10686734.38
      3725148.78     10686888.46      3725293.77     10687336.43
#Sta/Elev= 30
  4638.5  467.94  4655.4  465.57  4669.1  466.81  4707.4   464.8    4713  462.92
  4767.6   458.4  4835.2  446.42  4894.9  444.29  4960.4  442.11    4966  443.75
  4971.9  442.06    4983  433.47  4988.6  425.29  4994.2  431.09  5008.3  424.76
  5011.1  424.26  5014.3  424.76  5016.8  439.54  5039.5  442.87  5059.2  441.44
  5103.1  440.95  5147.5  439.41  5265.7  441.66  5420.4  441.56  5431.3  443.17
  5457.7  441.96  5462.9  443.77  5479.8   443.9  5584.2  449.91    5585  449.96
#Mann= 9 ,-1 , 0
  4638.5     .05       0  4835.2     .12       0  4894.9     .05       0
  5008.3     .04       0  5014.3     .05       0  5059.2     .12       0
  5103.1     .05       0  5479.8     .08       0  5584.2     .05       0
Bank Sta=4983,5016.8
XS Rating Curve= 0 ,0
Exp/Cntr=0.3,0.1

Type RM Length L Ch R = 1 ,14739   ,659,659,659
BEGIN DESCRIPTION:
Mapping XS 6f6dcaef
END DESCRIPTION:
XS GIS Cut Line= 3
      3724863.57     10686612.49      3724989.43     10686894.59
      3725254.18     10687450.13
#Sta/Elev= 30
  4618.3  473.43  4640.9  473.33  4690.7  469.39  4742.6  462.45  4765.9  458.51
    4780  453.37  4794.6  452.22  4801.9  448.18  4827.8  445.91  4859.3  443.28
  4944.6  438.63  4955.6  436.19  4961.8  432.73  4969.1  427.77  4996.9  421.54
  4999.6  421.04  5002.9  421.54  5007.2  427.67  5012.7  430.77  5029.9  438.58
  5045.4  437.98  5079.7  437.15  5232.5   436.8  5245.3   433.2  5290.7  437.21
  5398.6  439.43  5409.7   441.6  5472.3  444.67  5522.3  450.54  5542.6   452.7
#Mann= 10 ,-1 , 0
  4618.3     .12       0  4640.9     .16       0  4827.8     .12       0
  4859.3     .16       0  4969.1     .12       0  4996.9     .07       0
  5002.9     .12       0  5045.4     .16       0  5079.7     .05       0
  5522.3     .16       0
#XS Ineff= 2 , 0
                         5233.31          437.18
Permanent Ineff=
       F       F
Bank Sta=4961.8,5012.7
XS Rating Curve= 0 ,0
Exp/Cntr=0.3,0.1

Type RM Length L Ch R = 1 ,14080   ,653,653,653
BEGIN DESCRIPTION:
UNT 136 IN CACR 28.0
END DESCRIPTION:
XS GIS Cut Line= 3
      3724672.81      10687138.4       3724865.5     10687456.09
      3725127.38     10687746.48
#Sta/Elev= 30
  4577.3  445.55  4591.1  442.19  4635.3   435.5  4656.7  434.33  4918.9  431.16
    4955  431.83  4961.8  429.93  4968.5  431.62    4976  431.41  4982.7  426.32
  4990.2   424.1  4993.9  414.56  4996.7  414.06  4999.9  414.56  5004.4  415.44
  5011.1  420.82  5018.6  423.36  5025.3  431.01  5032.8  433.13  5053.7  433.36
  5089.1  436.74  5138.9  441.63  5145.6   443.9  5153.1  443.82  5159.8  445.97
  5181.5  447.54  5188.2     450  5251.8  454.83  5259.2  456.73  5339.9  459.24
#Mann= 5 ,-1 , 0
  4577.3     .05       0  4918.9     .16       0  4993.9     .07       0
  4999.9     .16       0  5089.1     .05       0
Bank Sta=4990.2,5018.6
XS Rating Curve= 0 ,0
Exp/Cntr=0.3,0.1

Type RM Length L Ch R = 1 ,13427   ,588,588,588
BEGIN DESCRIPTION:
UNT 136 IN CACR 27.0
END DESCRIPTION:
XS GIS Cut Line= 3
      3724409.78     10687219.15      3724467.07     10687685.25
      3724646.75     10687945.67
#Sta/Elev= 30
    4429  440.26  4466.9  436.68    4472  437.22  4480.4  435.15  4520.7  429.74
    4561   426.4  4601.3  427.35  4742.4  425.01  4955.7   425.9    4962   425.2
  4968.1  422.46  4976.9  415.42  4989.7  412.65  4994.8  404.72  4997.6  404.22
  5000.8  404.72  5012.7  412.33  5018.8  417.65  5026.1  425.51  5048.5  424.88
  5054.6  423.42  5069.5  426.56  5075.6  429.45  5084.4  429.76  5090.4  431.99
  5120.2  433.11  5126.3  435.55  5150.5  438.29  5170.9  438.56    5215  441.76
#Mann= 5 ,-1 , 0
    4429     .05       0  4955.7     .16       0  4994.8     .07       0
  5000.8     .16       0  5150.5     .05       0
Bank Sta=4976.9,5018.8
XS Rating Curve= 0 ,0
Exp/Cntr=0.3,0.1

Type RM Length L Ch R = 1 ,12840   ,373,373,373
BEGIN DESCRIPTION:
UNT 136 IN CACR 26.0
END DESCRIPTION:
XS GIS Cut Line= 4
      3724179.72     10687629.72       3723968.8     10687903.13
      3724070.36     10688111.47      3724552.11     10688064.59
#Sta/Elev= 30
    4495  421.86  4623.1  417.98  4666.6  418.81  4710.1  418.87  4835.6  416.71
  4914.9  417.27  4943.8  413.57  4970.7  416.99  4981.7  415.21  4988.9  404.29
  4994.4  402.58  5000.9  401.83  5003.7  401.33  5006.9  401.83  5011.4  408.04
  5016.9  412.41  5026.2  417.23  5033.9  415.79  5039.5  417.09  5136.8  417.79
  5161.7  418.62    5222  418.58  5332.5  420.84  5372.7   422.8  5408.3  423.68
  5442.4  424.35  5508.1   427.8  5533.5  429.44  5549.3  429.09  5556.1  429.78
#Mann= 6 ,-1 , 0
    4495     .05       0  4970.7     .16       0  5000.9     .07       0
  5006.9     .16       0  5408.3     .05       0  5508.1     .16       0
Bank Sta=4981.7,5016.9
XS Rating Curve= 0 ,0
Exp/Cntr=0.3,0.1

Type RM Length L Ch R = 1 ,12467   ,333,333,333
BEGIN DESCRIPTION:
UNT 136 IN CACR 25.0
END DESCRIPTION:
XS GIS Cut Line= 3
      3723432.33     10687627.07     3723785.164    10688278.071
     3723966.278    10688165.862
#Sta/Elev= 30
       0  435.16    58.9  427.15   68.72   426.2  107.99  418.65  117.81  417.76
  127.62   416.2  186.53  411.22  196.35  410.81  206.16  409.83  215.98  409.62
  255.25  410.04   284.7  409.43  333.79  409.58  412.33  410.84  626.18  411.89
  645.43  411.09  655.05  407.58   674.3  402.76  683.93  399.25  693.55  399.25
  703.17  402.47  722.42  410.92  732.05   413.5  751.22  413.08  760.78  414.24
  818.11  414.96  865.89  414.62  923.22  414.99  932.78  415.17  951.89  415.53
#Mann= 4 ,-1 , 0
       0     .05       0  196.35     .16       0  923.22     .07       0
  932.78     .16       0
Bank Sta=645.43,732.05
XS Rating Curve= 0 ,0
Exp/Cntr=0.3,0.1

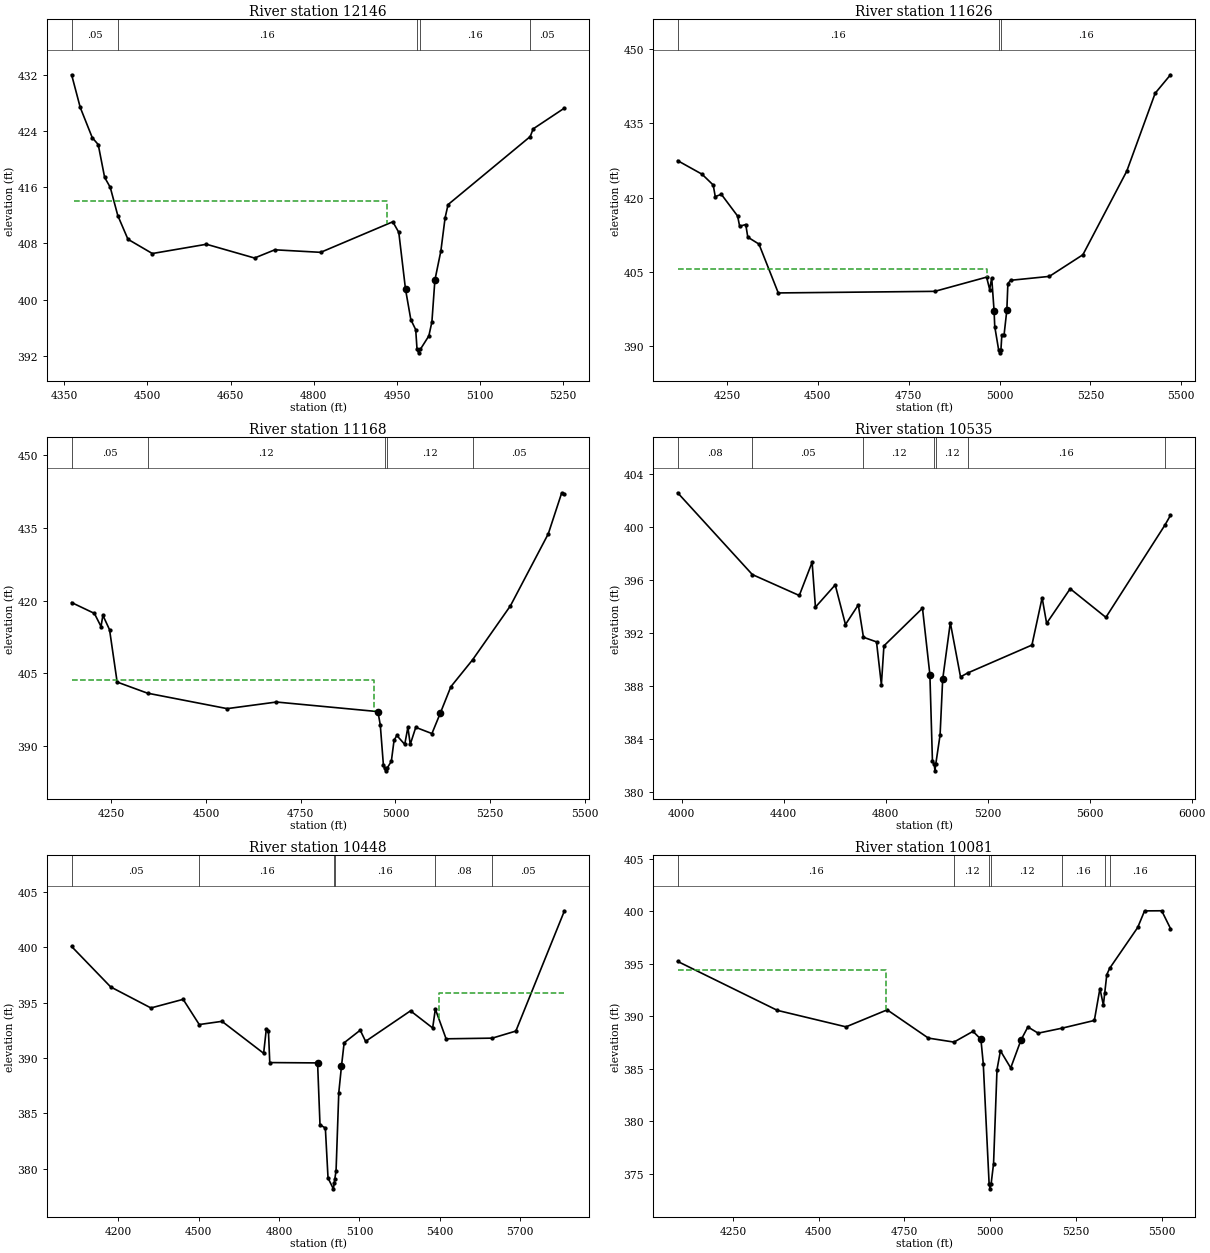
Type RM Length L Ch R = 1 ,12146   ,520,520,520
BEGIN DESCRIPTION:
UNT 136 IN CACR 24.0
END DESCRIPTION:
XS GIS Cut Line= 2
      3723273.47     10687785.91      3723617.02     10688605.74
#Sta/Elev= 30
  4363.3     432  4378.8  427.36  4400.5  423.05  4411.3  422.06  4422.8   417.4
    4433  415.97  4446.6  411.95  4464.9  408.58  4508.9  406.55  4606.5  407.87
  4693.2  405.91  4729.8  407.08  4812.5  406.72  4942.6  411.07  4953.4  409.56
  4965.5  401.47  4975.1  397.14  4983.9  395.71  4986.3  392.91  4989.1  392.41
  4992.3  392.91  5007.6  394.82  5013.1  396.81  5018.5  402.76  5029.3  406.92
  5036.9  411.64  5042.3  413.52  5190.4   423.2  5195.8   424.3  5252.2  427.26
#Mann= 5 ,-1 , 0
  4363.3     .05       0  4446.6     .16       0  4986.3     .07       0
  4992.3     .16       0  5190.4     .05       0
#XS Ineff= 1 ,-1
 4367.73 4932.95  414.09
Permanent Ineff=
       F
Bank Sta=4965.5,5018.5
XS Rating Curve= 0 ,0
Exp/Cntr=0.3,0.1

Type RM Length L Ch R = 1 ,11626   ,458,458,458
BEGIN DESCRIPTION:
UNT 136 IN CACR 23.0
END DESCRIPTION:
XS GIS Cut Line= 3
      3722699.61     10687810.18      3723099.61     10688610.19
       3723399.6     10688960.18
#Sta/Elev= 30
  4114.8  427.47  4181.9  424.73  4212.6  422.55  4218.2  420.22    4235  420.67
  4279.7  416.29  4285.3  414.22  4302.1  414.58  4307.7  412.03  4338.4  410.63
  4391.5  400.77    4822  401.09  4964.5  403.96  4972.9  401.46  4978.5  403.83
 4984.99  397.21  4986.9  393.97  4997.8  389.18  5000.6  388.68  5003.8  389.18
  5006.4  392.31  5012.5  392.31 5020.13   397.3    5023  402.67  5030.6  403.32
  5137.1  404.11  5229.3  408.48    5350  425.36    5428  441.07  5470.2   444.8
#Mann= 3 ,-1 , 0
  4114.8     .16       0  4997.8     .07       0  5003.8     .16       0
#XS Ineff= 2 , 0
         4964.55  405.58
Permanent Ineff=
       F       F
Bank Sta=4984.99,5020.13
XS Rating Curve= 0 ,0
Exp/Cntr=0.3,0.1

Type RM Length L Ch R = 1 ,11168   ,633,633,633
BEGIN DESCRIPTION:
UNT 136 IN CACR 22.0
END DESCRIPTION:
XS GIS Cut Line= 3
      3722749.61      10688010.2      3722699.61     10688810.19
      3723099.57     10689110.16
#Sta/Elev= 30
  4144.9  419.58    4205  417.35  4222.5  414.65  4227.5  416.95  4245.1  413.98
  4265.1  403.22  4345.3  400.93  4555.7  397.75  4685.9  399.11  4953.7  397.14
    4960  394.43  4968.3  386.09  4971.6  385.45  4974.3  384.95  4977.6  385.45
  4989.2   386.9  4996.4  391.23  5003.7  392.23  5024.6  390.39  5032.9  393.91
  5039.2   390.4  5053.7   393.9  5096.4  392.62  5118.3  396.78  5146.4  402.26
  5203.7  407.79  5303.7  418.91  5403.7  433.73  5439.2  442.17  5446.4  441.83
#Mann= 5 ,-1 , 0
  4144.9     .05       0  4345.3     .12       0  4971.6     .07       0
  4977.6     .12       0  5203.7     .05       0
#XS Ineff= 2 , 0
         4943.64  403.74
Permanent Ineff=
       F       F
Bank Sta=4953.7,5118.3
XS Rating Curve= 0 ,0
Exp/Cntr=0.3,0.1

Type RM Length L Ch R = 1 ,10535   ,87,87,87
BEGIN DESCRIPTION:
Mapping XS b3a12d77
END DESCRIPTION:
XS GIS Cut Line= 4
      3722594.85     10688166.31      3722508.04     10688937.16
      3722497.62     10689121.19      3722511.51     10690093.45
#Sta/Elev= 30
  3984.6   402.6  4277.4  396.43  4461.5  394.85  4511.8  397.36  4524.9  393.97
  4602.4  395.65  4642.6  392.66  4692.9  394.14  4713.1   391.7  4764.3  391.35
  4783.4  388.12  4793.4  391.05  4944.6  393.89  4973.6  388.88  4983.6  382.37
  4990.6  382.12  4993.4  381.62  4996.6  382.12  5013.6  384.33  5023.7  388.52
  5053.7   392.8  5093.7  388.71  5121.4     389  5373.7  391.11  5413.7  394.68
  5431.3  392.75  5523.7  395.36  5663.7   393.2  5895.1  400.16    5917   400.9
#Mann= 7 ,-1 , 0
  3984.6     .08       0  4277.4     .05       0  4713.1     .12       0
  4990.6     .07       0  4996.6     .12       0  5121.4     .16       0
  5895.1     .05       0
Bank Sta=4973.6,5023.7
XS Rating Curve= 0 ,0
Exp/Cntr=0.3,0.1

Type RM Length L Ch R = 1 ,10448   ,367,367,367
BEGIN DESCRIPTION:
UNT 136 IN CACR 21.0
END DESCRIPTION:
XS GIS Cut Line= 2
      3722466.37     10688204.52       3722362.2     10690041.37
#Sta/Elev= 30
  4025.6  400.09  4171.5  396.43  4321.7  394.53  4441.9  395.31    4502  393.03
  4586.9  393.32  4742.4  390.43  4752.4  392.62  4760.3  392.48  4765.3  389.59
  4943.8  389.56  4952.8  383.97  4972.8  383.67  4982.8  379.15  5002.6  378.17
  5005.8  378.67  5007.9  379.02  5012.8  379.82  5022.9  386.86  5032.9  389.24
  5042.9  391.38    5103  392.52    5123  391.51  5290.7  394.27  5373.4  392.72
  5383.4  394.43  5423.5  391.74  5595.8   391.8  5683.9  392.44  5865.4  403.32
#Mann= 6 ,-1 , 0
  4025.6     .05       0    4502     .16       0  5005.8     .08       0
  5007.9     .16       0  5383.4     .08       0  5595.8     .05       0
#XS Ineff= 2 , 0
                         5396.59          395.88
Permanent Ineff=
       F       F
Bank Sta=4943.8,5032.9
XS Rating Curve= 0 ,0
Exp/Cntr=0.3,0.1

Type RM Length L Ch R = 1 ,10081   ,548,548,548
BEGIN DESCRIPTION:
Mapping XS 61dcbb12
END DESCRIPTION:
XS GIS Cut Line= 2
      3722111.25     10688269.62      3722067.86     10689705.76
#Sta/Elev= 30
    4089  395.22  4379.7  390.56  4579.8  388.99  4699.8  390.61  4819.9  387.92
  4894.5  387.54    4950  388.56  4973.1  387.81    4980  385.47    4997  374.07
  4999.7  373.57    5003  374.07    5010  375.98    5020  384.92    5030  386.71
    5060  385.08    5090  387.74    5110  388.98    5140  388.39  5208.9  388.86
  5303.8   389.6  5320.1  392.64  5330.1  391.06    5334  392.19  5340.1  393.96
  5348.4  394.56  5430.2  398.45  5450.2  400.03  5500.2  400.04  5525.8  398.35
#Mann= 7 ,-1 , 0
    4089     .16       0  4894.5     .12       0    4997     .07       0
    5003     .12       0  5208.9     .16       0    5334     .12       0
  5348.4     .16       0
#XS Ineff= 2 , 0
         4696.36   394.4
Permanent Ineff=
       F       F
Bank Sta=4973.1,5090
XS Rating Curve= 0 ,0
Exp/Cntr=0.3,0.1

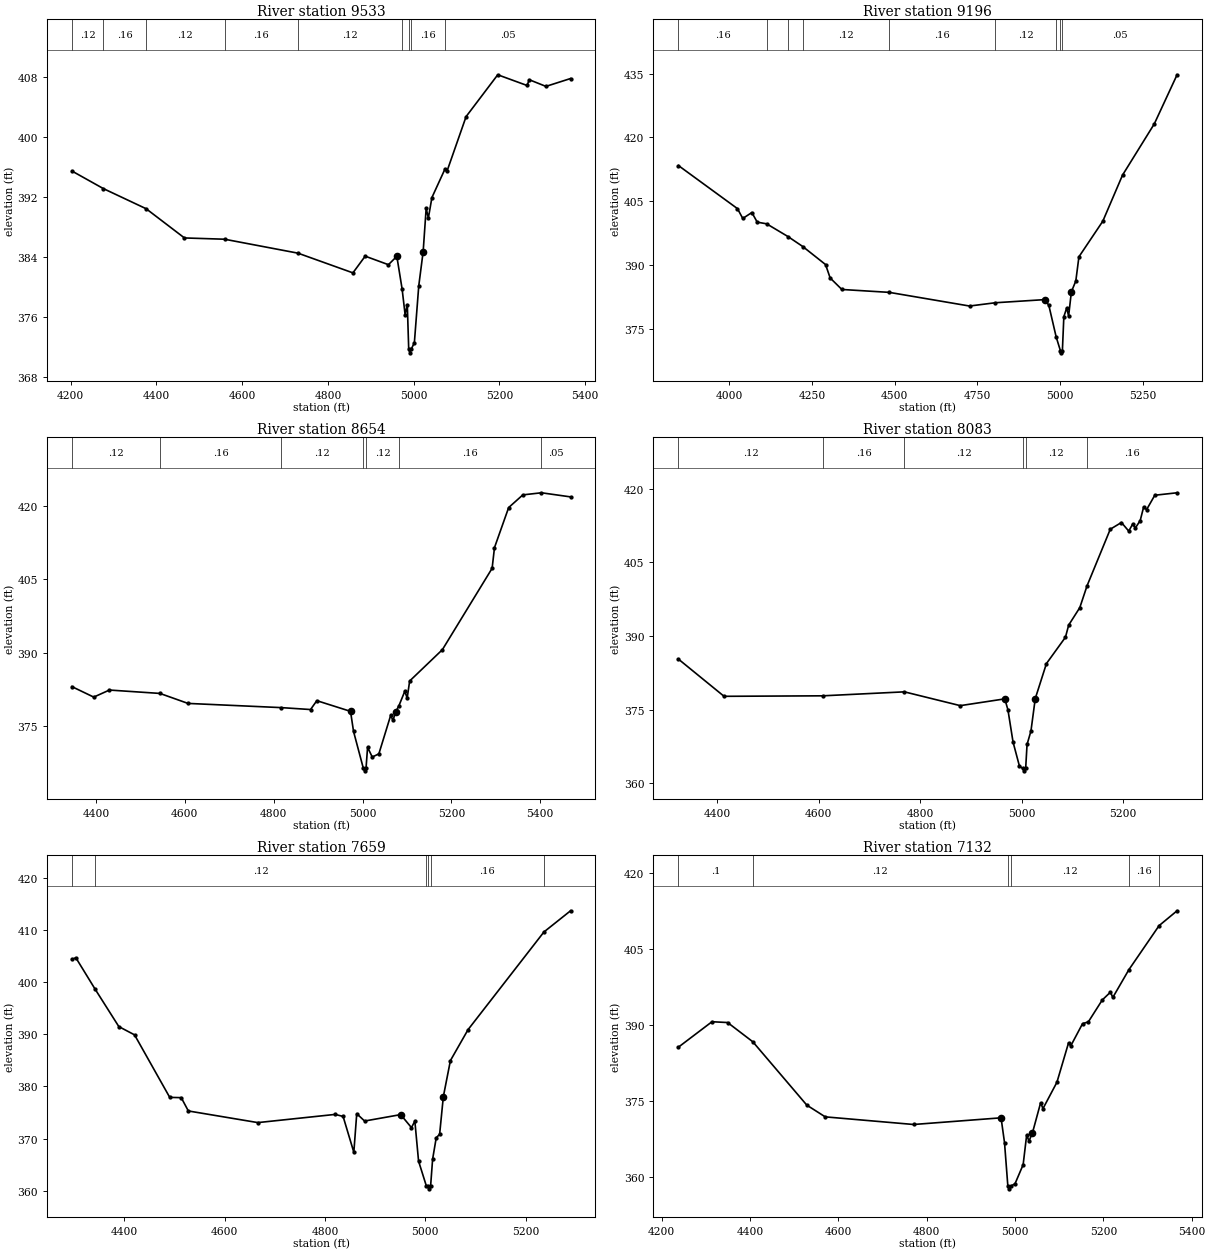
Type RM Length L Ch R = 1 ,9533    ,337,337,337
BEGIN DESCRIPTION:
Mapping XS 35e74279
END DESCRIPTION:
XS GIS Cut Line= 2
      3721720.62     10688399.86      3721473.43     10689536.08
#Sta/Elev= 30
  4202.9  395.51  4276.4  393.16  4375.9  390.48  4465.3  386.58  4558.8  386.41
    4730  384.55  4858.2  381.92  4886.8  384.15    4941  383.01  4960.6  384.13
  4972.9  379.77  4979.9  376.35    4985  377.69  4988.3  371.75    4991  371.25
  4994.3  371.75  5001.5  372.61  5011.7  380.18    5022  384.77    5029  390.54
  5034.1  389.23  5042.4  391.97  5072.4  395.72  5078.1  395.57  5122.1  402.77
  5195.9  408.35  5264.3  406.92  5269.4  407.69  5308.3   406.8  5365.7  407.85
#Mann= 9 ,-1 , 0
  4202.9     .12       0  4276.4     .16       0  4375.9     .12       0
  4558.8     .16       0    4730     .12       0  4972.9     .16       0
  4988.3     .07       0  4994.3     .16       0  5072.4     .05       0
Bank Sta=4960.6,5022
XS Rating Curve= 0 ,0
Exp/Cntr=0.3,0.1

Type RM Length L Ch R = 1 ,9196    ,542,542,542
BEGIN DESCRIPTION:
Mapping XS b9a1c071
END DESCRIPTION:
XS GIS Cut Line= 2
      3721779.79     10688137.66      3721055.86     10689460.53
#Sta/Elev= 30
  3845.8  413.38  4024.3  403.26  4040.4  400.95  4067.9  402.34  4084.1  400.08
  4112.5  399.69    4177   396.7  4221.9  394.35  4290.8  390.11  4304.7  386.96
  4340.1  384.26  4483.4  383.58  4726.1  380.37  4804.1  381.14  4954.4  381.88
  4966.1   380.5  4988.1  373.13    5001  369.87  5003.8  369.37    5007  369.87
  5011.4  377.88  5020.1  379.92  5025.8  378.01  5034.2  383.72  5047.6  386.26
    5057  391.94  5129.2   400.3  5188.9  411.14    5285  423.18  5353.8  434.71
#Mann= 9 ,-1 , 0
  3845.8     .16       0  4112.5     .12       0    4177     .16       0
  4221.9     .12       0  4483.4     .16       0  4804.1     .12       0
  4988.1     .05       0    5001     .03       0    5007     .05       0
Bank Sta=4954.4,5034.2
XS Rating Curve= 0 ,0
Exp/Cntr=0.3,0.1

Type RM Length L Ch R = 1 ,8654    ,571,571,571
BEGIN DESCRIPTION:
UNT 136 IN CACR 18.0
END DESCRIPTION:
XS GIS Cut Line= 3
      3721476.55     10688487.75      3721067.67     10688888.81
      3720545.41     10689059.53
#Sta/Elev= 30
    4346  383.06  4395.1  380.92  4430.4  382.36  4544.1  381.67  4607.3  379.63
  4817.6  378.77    4883  378.38  4897.2  380.19    4973  378.01  4979.8  373.91
  5001.9  366.36  5004.6  365.86  5007.9  366.36  5011.4  370.67  5021.9  368.68
  5036.8  369.33  5063.4  377.19  5068.6  376.15  5074.5   377.9  5081.9  379.15
  5095.2  382.12  5100.5  380.72  5106.1  384.21  5179.7   390.6  5291.7  407.23
    5297  411.45  5328.9  419.63  5360.8  422.22  5402.7  422.65  5468.2  421.81
#Mann= 7 ,-1 , 0
    4346     .12       0  4544.1     .16       0  4817.6     .12       0
  5001.9     .07       0  5007.9     .12       0  5081.9     .16       0
  5402.7     .05       0
Bank Sta=4973,5074.5
XS Rating Curve= 0 ,0
Exp/Cntr=0.3,0.1

Type RM Length L Ch R = 1 ,8083    ,424,424,424
BEGIN DESCRIPTION:
Mapping XS 5dd759d8
END DESCRIPTION:
XS GIS Cut Line= 2
      3721412.47     10688221.89      3720545.54      10688685.7
#Sta/Elev= 30
  4323.4  385.31  4413.4  377.74  4607.8  377.84  4768.9  378.65  4879.1  375.84
  4966.9  377.22  4973.1     375  4983.2  368.43  4995.8  363.53  5002.1  363.07
  5004.8  362.57  5008.1  363.07  5010.8  367.94  5018.5  370.68    5027  377.28
    5049   384.4  5086.5  389.76  5092.9  392.24  5114.8  395.79  5129.1  400.23
  5174.9  411.75  5196.9  413.12  5211.3  411.37  5218.8  412.74  5224.5  412.03
  5233.9  413.51  5240.8  416.32  5246.4  415.72  5262.7  418.67  5306.6  419.17
#Mann= 6 ,-1 , 0
  4323.4     .12       0  4607.8     .16       0  4768.9     .12       0
  5002.1     .07       0  5008.1     .12       0  5129.1     .16       0
Bank Sta=4966.9,5027
XS Rating Curve= 0 ,0
Exp/Cntr=0.3,0.1

Type RM Length L Ch R = 1 ,7659    ,527,527,527
BEGIN DESCRIPTION:
Mapping XS 6c057b9e
END DESCRIPTION:
XS GIS Cut Line= 3
      3721247.51     10687879.03      3720709.34     10688195.86
      3720437.21     10688446.39
#Sta/Elev= 30
  4295.4  404.33  4303.2  404.67  4341.5  398.67    4389  391.47  4420.3  389.89
  4490.5  377.91  4513.4  377.86  4527.6  375.31  4666.2  373.08  4820.5  374.65
  4836.2  374.26  4857.6   367.4  4863.4  374.79  4879.1  373.38    4951  374.61
  4972.5  372.12  4979.3  373.36  4986.7   365.7  5002.3  360.92  5004.7  360.89
  5007.4  360.39  5010.7  360.89  5014.7  366.06  5021.9  370.16  5028.7  370.85
  5036.1  378.05  5050.2  384.96  5085.4  390.89  5236.7   409.6  5289.8  413.66
#Mann= 6 ,-1 , 0
  4295.4     .16       0  4341.5     .12       0  5002.3     .16       0
  5004.7     .07       0  5010.7     .16       0  5236.7     .05       0
#XS Ineff= 2 , 0
         4863.33  374.66
Permanent Ineff=
       F       F
Bank Sta=4951,5036.1
XS Rating Curve= 0 ,0
Exp/Cntr=0.3,0.1

Type RM Length L Ch R = 1 ,7132    ,429,429,429
BEGIN DESCRIPTION:
Mapping XS f0e5d251
END DESCRIPTION:
XS GIS Cut Line= 3
      3720882.23     10687377.23      3720527.05     10687852.97
      3720357.77      10688360.8
#Sta/Elev= 30
  4237.9  385.59  4313.9  390.62  4349.3  390.46  4406.4  386.65  4528.6  374.12
  4570.3   371.8  4770.4  370.29  4968.4  371.61  4976.2  366.72  4983.8  358.06
  4986.5  357.56  4989.8  358.06    5000  358.57  5018.4  362.34  5026.4  368.23
  5031.6     367  5039.5  368.64    5058  374.59  5063.3  373.43  5094.9  378.65
  5121.2  386.44  5126.5  385.89  5152.9  390.24    5166  390.59  5197.6  394.93
  5216.1  396.47  5221.4  395.42  5257.7   400.9  5326.2  409.63  5366.9  412.57
#Mann= 6 ,-1 , 0
  4237.9      .1       0  4406.4     .12       0  4983.8     .07       0
  4989.8     .12       0  5257.7     .16       0  5326.2     .05       0
Bank Sta=4968.4,5039.5
XS Rating Curve= 0 ,0
Exp/Cntr=0.3,0.1

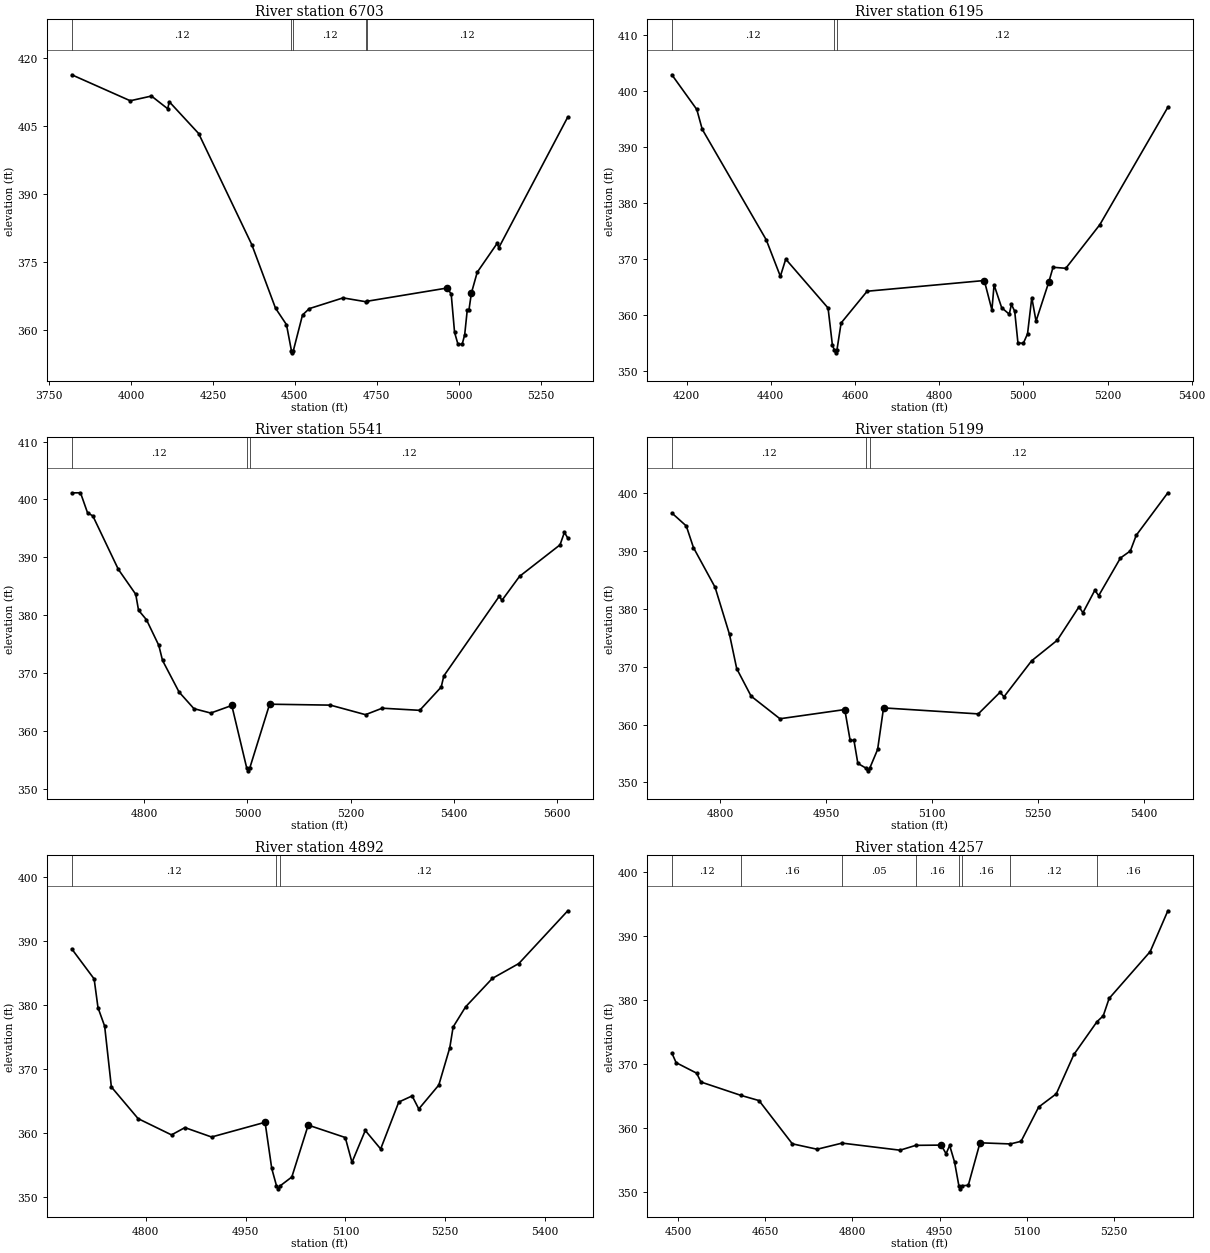
Type RM Length L Ch R = 1 ,6703    ,508,508,508
BEGIN DESCRIPTION:
UNT 136 IN CACR 14.0
END DESCRIPTION:
XS GIS Cut Line= 4
      3719965.56     10686731.39      3719899.61     10687110.19
      3720099.61     10687910.19      3720149.62     10688210.24
#Sta/Elev= 30
  3819.6   416.4    3998  410.67  4062.7  411.71  4112.2  408.91  4117.2  410.44
  4206.7  403.44    4369  378.91  4441.2  364.92  4474.7  361.28  4489.7  355.57
  4492.5  355.07  4495.7  355.57  4523.6  363.42  4544.2  364.82  4647.3  367.19
    4717  366.34  4719.9  366.44  4964.3  369.36  4977.2  368.07  4987.5  359.59
  4997.8  356.98  5010.7  356.96  5018.4  359.06  5026.1  364.43  5031.2  364.43
  5038.9  368.26  5056.6  372.84  5117.4  379.21  5122.5  378.26  5332.9  407.08
#Mann= 5 ,-1 , 0
  3819.6     .12       0  4489.7     .07       0  4495.7     .12       0
    4717     .16       0  4719.9     .12       0
Bank Sta=4964.3,5038.9
XS Rating Curve= 0 ,0
Exp/Cntr=0.3,0.1

Type RM Length L Ch R = 1 ,6195    ,654,654,654
BEGIN DESCRIPTION:
UNT 136 IN CACR 13.0
END DESCRIPTION:
XS GIS Cut Line= 3
      3719499.62     10687110.22      3719699.61     10687910.19
       3719749.6     10688260.15
#Sta/Elev= 30
  4165.2  402.88  4224.4   396.7  4237.3  393.17  4389.4  373.46  4422.9  366.96
  4435.7  370.02  4536.2  361.31  4546.6  354.64  4551.3  353.82    4554  353.32
  4557.3  353.82  4567.2  358.64    4629   364.3  4907.3  366.21  4925.4  360.95
  4930.5  365.43  4948.6  361.36  4966.6  360.21  4971.7  361.95  4979.5  360.74
  4987.2  355.11  4999.9     355    5010  356.71  5020.1  363.16  5030.2  358.97
  5060.5  365.94  5070.6  368.57  5100.9  368.39  5181.7  376.16  5343.3   397.1
#Mann= 3 ,-1 , 0
  4165.2     .12       0  4551.3     .07       0  4557.3     .12       0
Bank Sta=4907.3,5060.5
XS Rating Curve= 0 ,0
Exp/Cntr=0.3,0.1

Type RM Length L Ch R = 1 ,5541    ,342,342,342
BEGIN DESCRIPTION:
Mapping XS 772c6bb8
END DESCRIPTION:
XS GIS Cut Line= 2
      3719189.53     10687340.81      3719449.55     10688266.49
#Sta/Elev= 30
  4659.6  401.12  4676.5  401.14  4690.1  397.69  4700.5  397.13  4749.8  387.91
  4783.6  383.59    4789  380.84  4804.4  379.19  4828.3  374.76  4835.5  372.16
  4867.6  366.69  4896.4  363.82    4929  363.06  4969.8  364.37  4998.7  353.57
  5001.5  353.07  5004.7  353.57  5043.1  364.59  5160.9  364.43    5229  362.78
  5261.4   363.9  5334.1  363.53  5375.7  367.55  5380.9  369.49  5488.3  383.25
  5493.5  382.54  5527.6  386.69  5606.1  392.14  5614.6   394.3  5621.1  393.31
#Mann= 3 ,-1 , 0
  4659.6     .12       0  4998.7     .07       0  5004.7     .12       0
Bank Sta=4969.8,5043.1
XS Rating Curve= 0 ,0
Exp/Cntr=0.3,0.1

Type RM Length L Ch R = 1 ,5199    ,307,307,307
BEGIN DESCRIPTION:
UNT 136 IN CACR 11.0
END DESCRIPTION:
XS GIS Cut Line= 3
      3718999.61     10687610.18      3719049.61     10687860.19
      3719249.62     10688260.22
#Sta/Elev= 30
  4731.3   396.6  4751.7  394.36  4761.9  390.61  4792.5  383.75  4812.9   375.6
  4823.1  369.68  4843.5  364.92  4884.3  361.01  4976.1   362.6  4983.7  357.27
  4989.1  357.27  4994.6  353.29  5005.6   352.5  5008.4     352  5011.6   352.5
  5022.6   355.7    5031  362.89  5165.1  361.85  5195.9  365.59  5201.5  364.81
  5240.6  371.03  5276.9  374.59  5307.7  380.37  5313.3  379.35  5330.1  383.23
  5335.6  382.31  5366.4  388.82  5380.4  390.04  5388.7  392.74  5433.5   400.1
#Mann= 3 ,-1 , 0
  4731.3     .12       0  5005.6     .07       0  5011.6     .12       0
Bank Sta=4976.1,5031
XS Rating Curve= 0 ,0
Exp/Cntr=0.3,0.1

Type RM Length L Ch R = 1 ,4892    ,635,635,635
BEGIN DESCRIPTION:
UNT 136 IN CACR 10.0
END DESCRIPTION:
XS GIS Cut Line= 2
      3718751.56     10687680.96        3718821.     10688423.12
#Sta/Elev= 30
  4688.7  388.75  4722.3  384.06  4728.1  379.57  4738.1  376.68  4748.2  367.18
  4788.4  362.23  4838.6  359.69  4858.7  360.83  4898.8  359.36  4979.2  361.66
  4989.2  354.45  4996.3  351.76    4999  351.26  5002.3  351.76  5019.4  353.11
    5044  361.22  5099.7  359.28  5109.8   355.4  5129.8  360.38  5152.9  357.49
  5180.1  364.82  5200.2  365.78  5210.2  363.74  5240.3  367.48  5256.8  373.32
  5261.8  376.55  5280.5  379.69  5320.7  384.14  5360.6  386.47  5434.1  394.71
#Mann= 3 ,-1 , 0
  4688.7     .12       0  4996.3     .07       0  5002.3     .12       0
Bank Sta=4979.2,5044
XS Rating Curve= 0 ,0
Exp/Cntr=0.3,0.1

Type RM Length L Ch R = 1 ,4257    ,383,383,383
BEGIN DESCRIPTION:
UNT 136 IN CACR 9.0
END DESCRIPTION:
XS GIS Cut Line= 3
      3718549.61     10687710.19      3718249.61     10688110.19
      3718299.62     10688460.23
#Sta/Elev= 30
  4489.3  371.72  4496.6  370.21    4532  368.56  4539.3  367.18  4608.3  365.08
  4639.3  364.27  4696.6   357.5  4739.3  356.65  4782.2  357.61    4882   356.5
  4909.1  357.26  4952.8   357.3  4961.2  355.95  4967.4  357.24  4975.8  354.65
  4983.2  350.95  4985.9  350.45  4989.2  350.95  4999.4  350.99  5019.6  357.66
  5071.8  357.48  5090.3  357.89  5120.6  363.26  5150.9  365.33  5181.2  371.49
    5221  376.63  5231.7  377.54  5241.8  380.26  5312.5   387.6  5342.9  393.99
#Mann= 8 ,-1 , 0
  4489.3     .12       0  4608.3     .16       0  4782.2     .05       0
  4909.1     .16       0  4983.2     .07       0  4989.2     .16       0
  5071.8     .12       0    5221     .16       0
Bank Sta=4952.8,5019.6
XS Rating Curve= 0 ,0
Exp/Cntr=0.3,0.1

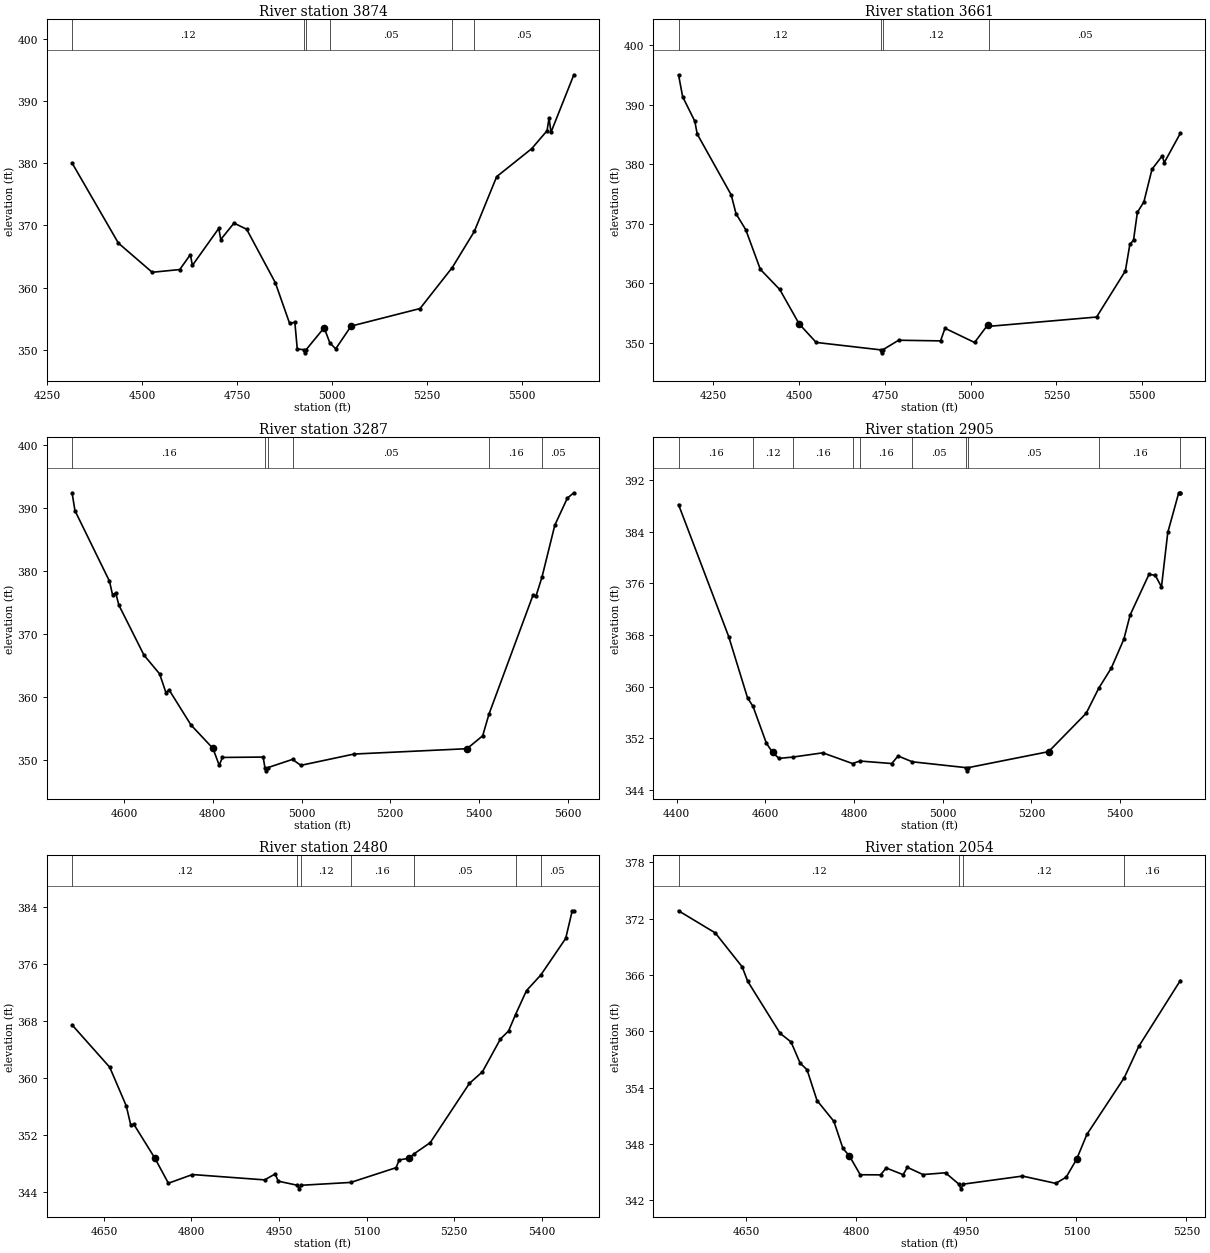
Type RM Length L Ch R = 1 ,3874    ,213,213,213
BEGIN DESCRIPTION:
Mapping XS 3d024836
END DESCRIPTION:
XS GIS Cut Line= 3
      3718076.02     10687276.54      3717937.13     10687793.03
      3718054.31      10688569.9
#Sta/Elev= 30
  4315.9  380.02  4437.8  367.16  4526.8  362.48  4599.3  362.92  4627.3  365.32
  4632.5  363.58    4702  369.53  4707.2  367.74    4742  370.37  4775.3  369.39
  4850.7  360.82  4888.3  354.29  4902.2  354.44  4908.5  350.17  4925.8  350.05
  4928.5  349.55  4931.8  350.05  4979.3  353.58  4994.2  351.15  5009.7  350.19
  5050.1  353.84  5231.6  356.66  5316.4  363.24  5374.4  369.03  5433.3  377.83
  5525.4  382.32  5565.9   385.2  5571.1  387.24  5576.2  384.95  5636.4  394.18
#Mann= 6 ,-1 , 0
  4315.9     .12       0  4925.8     .03       0  4931.8     .12       0
  4994.2     .05       0  5316.4     .16       0  5374.4     .05       0
Bank Sta=4979.3,5050.1
XS Rating Curve= 0 ,0
Exp/Cntr=0.3,0.1

Type RM Length L Ch R = 1 ,3661    ,374,374,374
BEGIN DESCRIPTION:
Mapping XS 6dc5a06c
END DESCRIPTION:
XS GIS Cut Line= 3
      3717229.66     10687233.12      3717698.42     10687710.56
       3717992.9     10688446.76
#Sta/Elev= 30
  4148.8  395.07  4160.8  391.38  4196.2  387.26  4203.2  385.11  4302.2  374.88
  4316.4  371.69  4344.7  369.02  4387.1  362.36  4443.7  358.97  4500.2  353.19
  4549.8  350.07  4737.7  348.82  4740.4  348.32  4743.7  348.82  4790.1  350.44
  4912.2  350.33  4925.2  352.45  5011.4  350.06  5049.5  353.01  5052.3  352.77
  5366.8  354.34  5450.7   362.1  5463.7  366.54  5474.5  367.29  5485.7  371.95
  5504.6  373.69  5528.3  379.19  5558.4  381.46  5563.8  380.28  5610.8  385.23
#Mann= 4 ,-1 , 0
  4148.8     .12       0  4737.7     .07       0  4743.7     .12       0
  5052.3     .05       0
Bank Sta=4500.2,5049.5
XS Rating Curve= 0 ,0
Exp/Cntr=0.3,0.1

Type RM Length L Ch R = 1 ,3287    ,382,382,382
BEGIN DESCRIPTION:
UNT 136 IN CACR 7.0
END DESCRIPTION:
XS GIS Cut Line= 3
      3717127.94     10687692.68      3717527.91     10688092.65
      3717927.89     10688492.63
#Sta/Elev= 30
  4482.7  392.44  4489.2   389.6    4567  378.39    4574  376.21  4581.1  376.52
  4588.2  374.58  4644.8  366.63  4680.1  363.64  4694.3  360.67  4701.3  361.12
  4750.8  355.52  4800.3   351.8  4814.5   349.1  4821.5  350.36  4913.5  350.42
  4917.5  348.73  4920.3  348.23  4923.5  348.73  4979.8  350.05  4998.3   349.1
  5118.5   350.9  5373.1  351.75  5408.4   353.8  5422.6  357.24  5521.6  376.11
  5528.6  376.01  5542.1  379.02  5571.1   387.3  5599.3  391.59    5614  392.44
#Mann= 6 ,-1 , 0
  4482.7     .16       0  4917.5     .03       0  4923.5     .16       0
  4979.8     .05       0  5422.6     .16       0  5542.1     .05       0
Bank Sta=4800.3,5373.1
XS Rating Curve= 0 ,0
Exp/Cntr=0.3,0.1

Type RM Length L Ch R = 1 ,2905    ,425,425,425
BEGIN DESCRIPTION:
UNT 136 IN CACR 6.0
END DESCRIPTION:
XS GIS Cut Line= 3
      3716899.61     10687910.18      3717299.61     10688310.19
      3717699.63     10688710.21
#Sta/Elev= 30
  4404.2  388.21  4517.3  367.77  4559.8  358.28  4572.2  356.95  4602.2  351.27
  4616.3  349.83  4630.5  348.91  4661.8  349.11  4729.5  349.77  4796.5  348.11
  4813.1   348.5    4885  348.11  4899.2  349.28  4931.3  348.38  5051.7  347.48
  5054.5  346.98  5057.7  347.48  5238.6  349.95  5323.4   355.9  5351.4  359.74
    5380   362.9  5408.3  367.37  5422.4  371.11  5464.9   377.4    5479  377.27
  5493.1  375.46  5507.3  383.89    5532  390.04  5535.5  390.04  5535.6  390.04
#Mann= 10 ,-1 , 0
  4404.2     .16       0  4572.2     .12       0  4661.8     .16       0
  4796.5     .12       0  4813.1     .16       0  4931.3     .05       0
  5051.7     .03       0  5057.7     .05       0  5351.4     .16       0
  5535.5     .05       0
Bank Sta=4616.3,5238.6
XS Rating Curve= 0 ,0
Exp/Cntr=0.3,0.1

Type RM Length L Ch R = 1 ,2480    ,426,426,426
BEGIN DESCRIPTION:
UNT 136 IN CACR 5.0
END DESCRIPTION:
XS GIS Cut Line= 3
      3716699.58     10688560.18      3717099.61     10688660.19
      3717499.65     10688860.21
#Sta/Elev= 30
  4595.5  367.47    4660  361.52  4688.3  356.09    4696   353.4  4701.2  353.51
  4737.3  348.74  4760.5  345.21  4801.7  346.43  4925.4  345.68  4943.4  346.51
  4948.6   345.5  4981.6  344.92  4984.4  344.42  4987.6  344.92  5072.8  345.32
  5150.4  347.39    5156  348.49  5172.7  348.72  5181.3  349.34  5209.1  350.92
  5276.2  359.25  5298.5  360.88  5329.3  365.49  5343.2  366.61  5355.2  368.93
    5374   372.3  5398.4  374.48  5441.1  379.63  5452.3  383.52  5455.1  383.52
#Mann= 7 ,-1 , 0
  4595.5     .12       0  4981.6     .07       0  4987.6     .12       0
  5072.8     .16       0  5181.3     .05       0  5355.2     .16       0
  5398.4     .05       0
Bank Sta=4737.3,5172.7
XS Rating Curve= 0 ,0
Exp/Cntr=0.3,0.1

Type RM Length L Ch R = 1 ,2054    ,534,534,534
BEGIN DESCRIPTION:
UNT 136 IN CACR 4.0
END DESCRIPTION:
XS GIS Cut Line= 3
      3716599.62      10688560.2      3716849.61     10688960.19
       3716999.6     10689110.18
#Sta/Elev= 30
  4557.8  372.85  4607.9  370.49  4644.5  366.88  4652.1  365.33  4696.3  359.79
  4711.1  358.88  4723.5  356.62  4732.9  355.92  4746.5  352.64  4769.5  350.42
  4781.8  347.54  4790.7  346.73  4805.4  344.73  4833.1  344.72  4840.8  345.45
  4863.8  344.74  4869.7  345.52  4890.9  344.75  4921.6  344.94  4939.8  343.73
  4942.6  343.23  4945.8  343.73  5026.5  344.59  5071.9  343.81  5086.1  344.48
  5100.2  346.37  5114.3  349.03  5165.2  355.07    5185  358.41  5241.6  365.42
#Mann= 4 ,-1 , 0
  4557.8     .12       0  4939.8     .07       0  4945.8     .12       0
  5165.2     .16       0
Bank Sta=4790.7,5100.2
XS Rating Curve= 0 ,0
Exp/Cntr=0.3,0.1