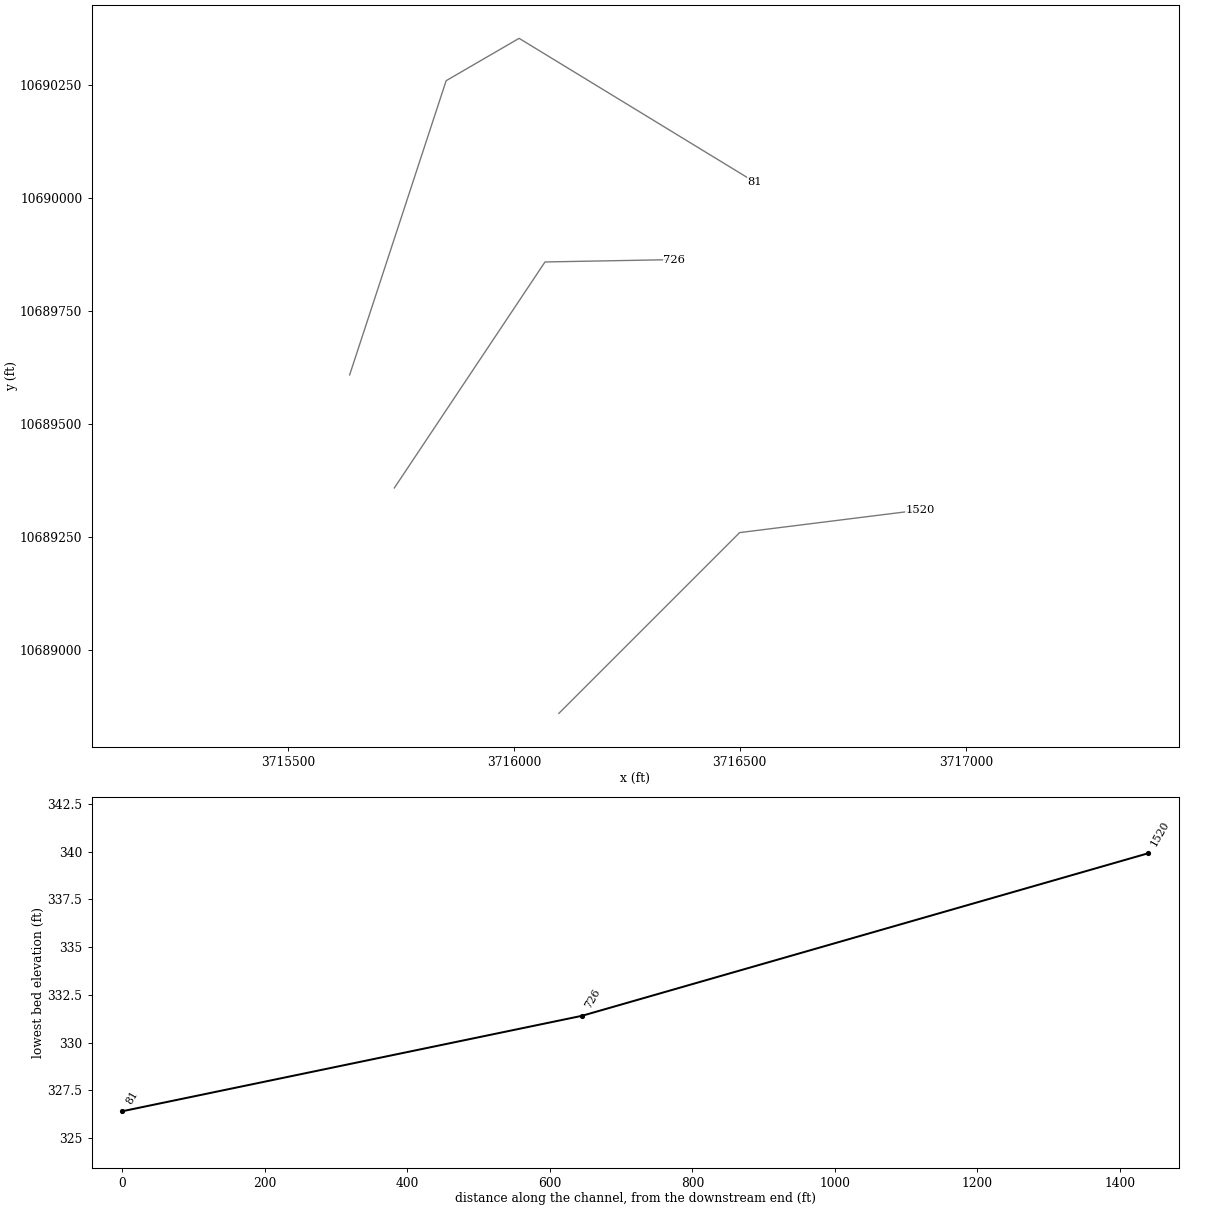
HEC-RAS study UNT 136 IN CACR.prj: UNT 136 IN CACR Base Level Engineering

--- UNT 136 IN CACR.g01 (geometry) --- (continued)

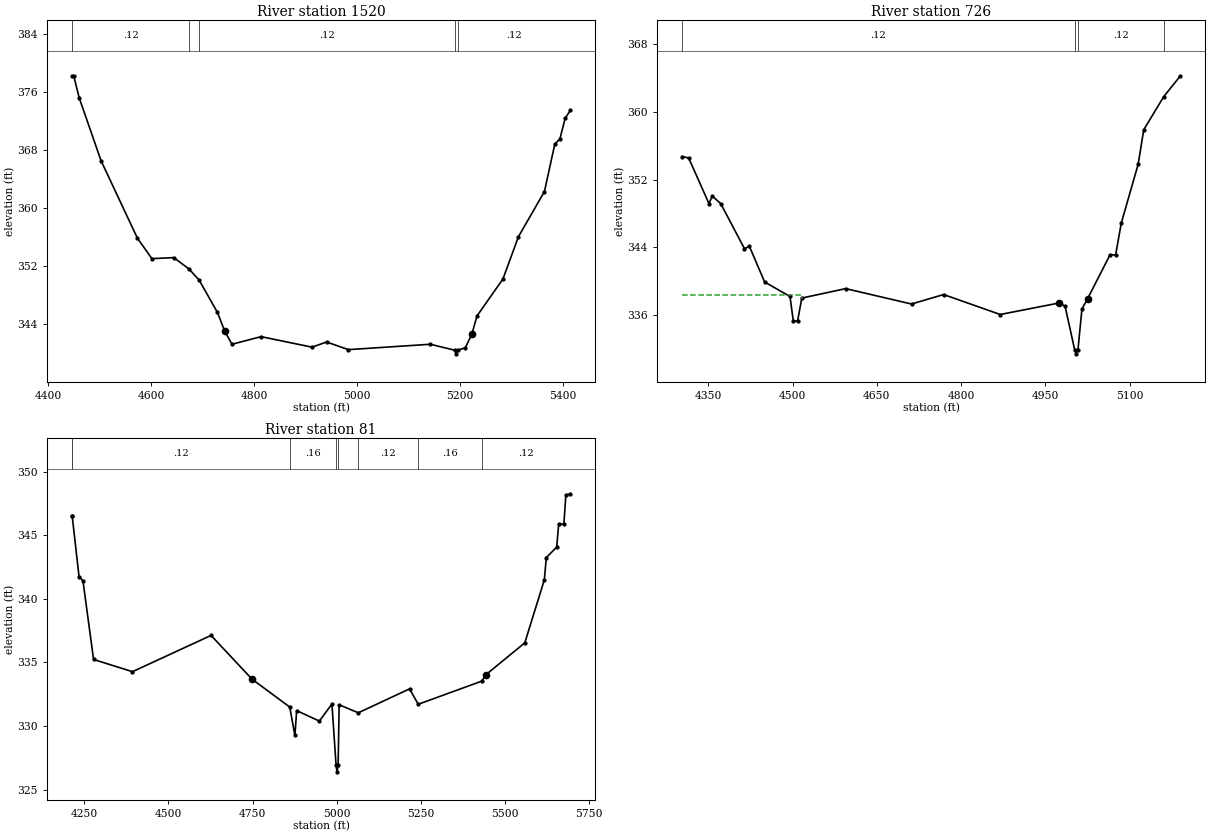
Type RM Length L Ch R = 1 ,1520    ,794,794,794
BEGIN DESCRIPTION:
UNT 136 IN CACR 3.0
END DESCRIPTION:
XS GIS Cut Line= 3
      3716099.62      10688860.2      3716499.61     10689260.19
      3716899.63     10689310.19
#Sta/Elev= 30
  4445.8  378.23  4449.3  378.23  4459.9  375.21  4502.4  366.53  4573.1  355.85
  4601.3  353.03  4643.8  353.17  4673.5   351.6  4693.2  350.06  4728.6  345.63
  4742.8  343.04  4756.9  341.23  4813.5  342.28  4912.5  340.83  4940.8  341.54
  4983.2  340.49  5142.5  341.23  5189.9  340.41  5192.6  339.91  5195.9  340.41
  5210.5  340.76  5223.1  342.61  5233.2  345.14  5283.6  350.23  5313.8  356.07
  5364.2  362.27  5384.3  368.79  5394.4  369.56  5404.5  372.37  5414.6  373.46
#Mann= 5 ,-1 , 0
  4445.8     .12       0  4673.5     .16       0  4693.2     .12       0
  5189.9     .07       0  5195.9     .12       0
Bank Sta=4742.8,5223.1
XS Rating Curve= 0 ,0
Exp/Cntr=0.3,0.1

Type RM Length L Ch R = 1 ,726     ,645,645,645
BEGIN DESCRIPTION:
UNT 136 IN CACR 2.0
END DESCRIPTION:
XS GIS Cut Line= 3
      3715735.64     10689358.99        3716069.     10689859.02
      3716354.99     10689864.22
#Sta/Elev= 30
  4303.4  354.72  4315.2  354.56  4351.3  349.16  4357.3  350.06  4372.3  349.15
  4414.4  343.84  4423.4  344.09  4450.4  339.89  4495.5  338.18  4501.5  335.23
  4509.2  335.33  4516.5  337.99  4594.6  339.11  4711.8  337.29  4768.9  338.41
  4869.7  336.05    4975  337.42    4985  337.03    5002   331.9  5004.7   331.4
    5008   331.9    5015   336.7    5025  337.91    5065  343.11    5075   343.1
    5085  346.85    5115  353.79    5125  357.89  5160.7  361.82  5190.4  364.27
#Mann= 4 ,-1 , 0
  4303.4     .12       0    5002     .07       0    5008     .12       0
  5160.7     .16       0
#XS Ineff= 2 , 0
         4516.05  338.36
Permanent Ineff=
       F       F
Bank Sta=4975,5025
XS Rating Curve= 0 ,0
Exp/Cntr=0.3,0.1

Type RM Length L Ch R = 1 ,81      ,0,0,0
BEGIN DESCRIPTION:
UNT 136 IN CACR 1.0
END DESCRIPTION:
XS GIS Cut Line= 4
      3715636.71     10689609.02      3715850.25     10690260.06
       3716011.7     10690353.81      3716532.58     10690036.08
#Sta/Elev= 30
    4213  346.48    4214  346.48  4234.2  341.74  4245.8  341.43  4277.4  335.23
  4393.1  334.27  4626.7  337.12  4748.7  333.68  4860.7  331.49    4876  329.26
  4881.3  331.21  4948.8  330.39  4986.1  331.73  4998.5   326.9  5001.3   326.4
  5004.5   326.9  5007.6  331.67  5064.5  331.04  5216.9  332.92  5242.7  331.71
  5431.9  333.53  5443.4  334.02  5559.6  336.54  5617.6  341.49  5623.5  343.24
  5654.4  344.06  5660.3  345.88  5675.7  345.86  5681.6  348.14    5695  348.25
#Mann= 8 ,-1 , 0
    4213     .16       0    4214     .12       0  4860.7     .16       0
  4998.5     .07       0  5004.5     .16       0  5064.5     .12       0
  5242.7     .16       0  5431.9     .12       0
Bank Sta=4748.7,5443.4
XS Rating Curve= 0 ,0
Exp/Cntr=0.3,0.1
Stream Node=UNT 136 IN CACR ,Reach-1         , 0 , 0 ,Upstream end
Stream Node=UNT 136 IN CACR ,Reach-1         , 0 , 1 ,Downstream end

Chan Stop Cuts=-1
Use User Specified Reach Order=0
Composite Channel Slope=5