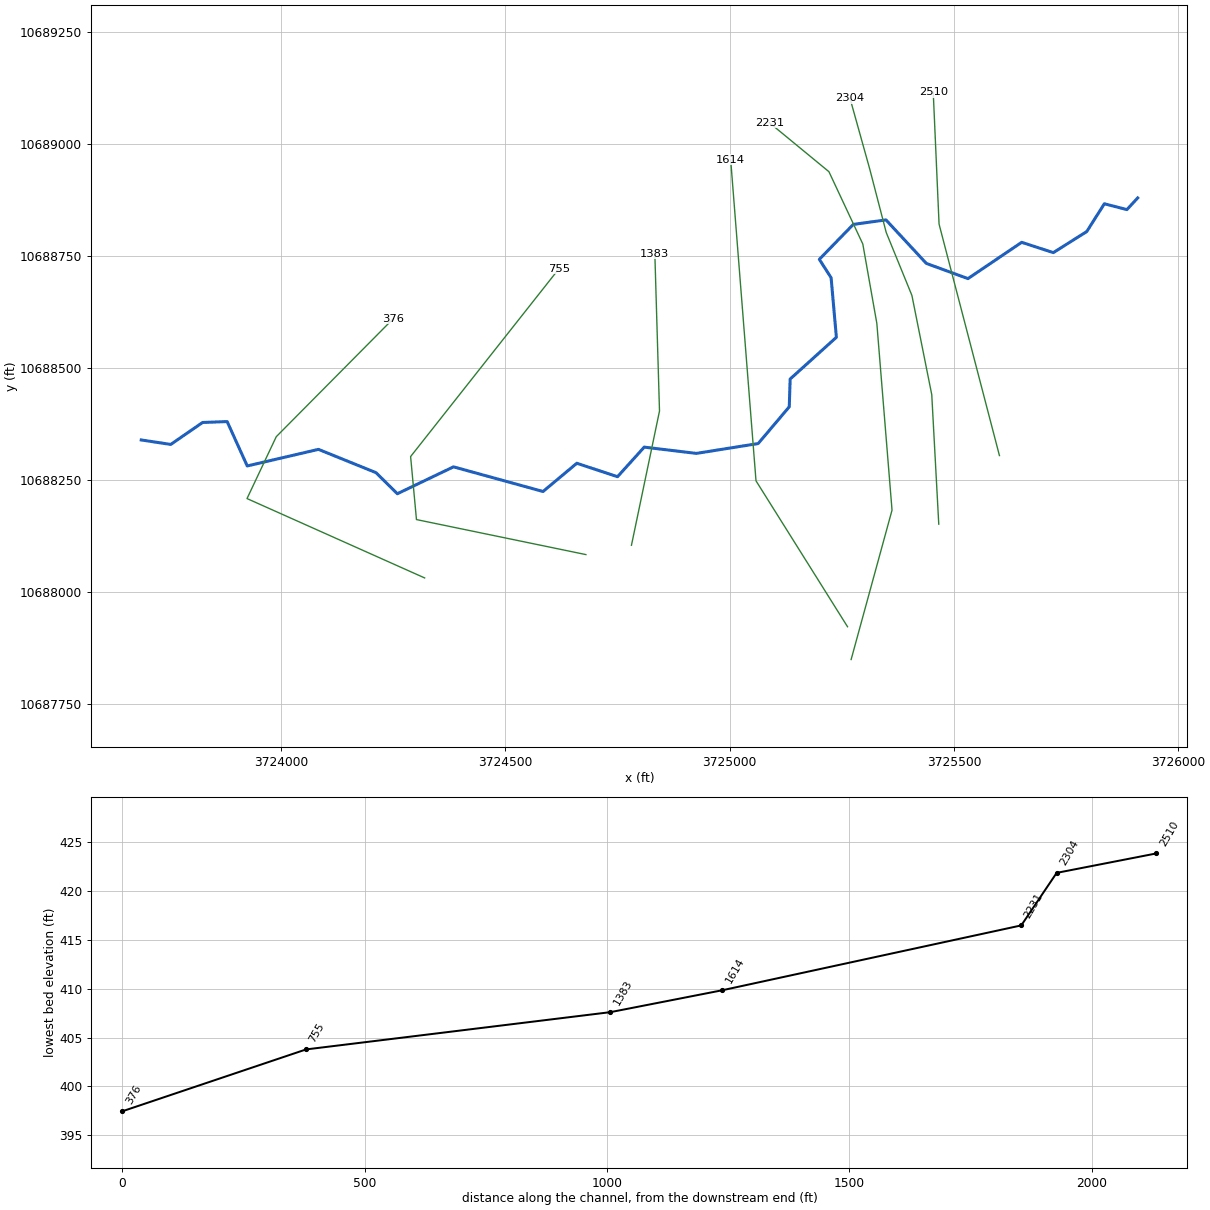
--- UNT 137 IN CACR.prj (project) ---

Proj Title=UNT 137 IN CACR Base Level Engineering
Current Plan=p01
Default Exp/Contr=0.3,0.1
English Units
Geom File=g01
Flow File=f01
Plan File=p01
Y Axis Title=Elevation
X Axis Title(PF)=Main Channel Distance
X Axis Title(XS)=Station
BEGIN DESCRIPTION:
UNT 137 IN CACR
END DESCRIPTION:
DSS Export Rating Curves= 0
DSS Export Rating Curve Sorted= 0
DSS Export Volume Flow Curves= 0
DXF OffsetX= 0
DXF OffsetY= 0
DXF ScaleX= 1
DXF ScaleY= 10

--- UNT 137 IN CACR.p01 (plan) ---

Plan Title=Multiple Run
Short Identifier=Multiple
Geom File=g01
Flow File=f01
Subcritical Flow
K Sum by GR= 0
Std Step Tol= 0.01
Critical Tol= 0.01
Num of Std Step Trials= 20
Max Error Tol= 0.3
Flow Tol Ratio= 0.001
Split Flow NTrial= 30
Split Flow Tol= 0.02
Split Flow Ratio= 0.02
Log Output Level= 0
Friction Slope Method= 1
Unsteady Friction Slope Method= 2
Unsteady Bridges Friction Slope Method= 1
Parabolic Critical Depth
Global Vel Dist=  1 , 1 , 1
Global Log Level= 0
CheckData=True
Encroach Param= -1, 0, 0, 0
BEGIN DESCRIPTION:
Multiple Run
END DESCRIPTION:

--- UNT 137 IN CACR.f01 (steady flow) ---

Flow Title=Multiple
Program Version=4.10
Number of Profiles= 7
Profile Names=10-year,25-year,50-year,1pct_min,100-year,1pct_plu,500-year
River Rch & RM=UNT 137 IN CACR,Reach-1         ,2510
   609.6   857.6  1071.2   985.6  1333.6  1803.2  2071.2
River Rch & RM=UNT 137 IN CACR,Reach-1         ,2231
     447  718.24  897.13  825.44 1116.89 1510.18 1734.63
Boundary for River Rch & Prof#=UNT 137 IN CACR,Reach-1         , 1
Up Type= 0
Dn Type= 3
Dn Slope=0.01664
Boundary for River Rch & Prof#=UNT 137 IN CACR,Reach-1         , 2
Up Type= 0
Dn Type= 3
Dn Slope=0.01664
Boundary for River Rch & Prof#=UNT 137 IN CACR,Reach-1         , 3
Up Type= 0
Dn Type= 3
Dn Slope=0.01664
Boundary for River Rch & Prof#=UNT 137 IN CACR,Reach-1         , 4
Up Type= 0
Dn Type= 3
Dn Slope=0.01664
Boundary for River Rch & Prof#=UNT 137 IN CACR,Reach-1         , 5
Up Type= 0
Dn Type= 3
Dn Slope=0.01664
Boundary for River Rch & Prof#=UNT 137 IN CACR,Reach-1         , 6
Up Type= 0
Dn Type= 3
Dn Slope=0.01664
Boundary for River Rch & Prof#=UNT 137 IN CACR,Reach-1         , 7
Up Type= 0
Dn Type= 3
Dn Slope=0.01664
DSS Import GetInterval= 0
DSS Import GetPeak= 0
DSS Import FillOption= 0

--- UNT 137 IN CACR.g01 (geometry) ---

Geom Title=Existing Conditions
Program Version=4.10

River Reach=UNT 137 IN CACR ,Reach-1
Reach XY= 30
       3725909.5       10688880.       3725885.5       10688854.
      3725835.25       10688867.        3725796.       10688805.
       3725721.5       10688758.        3725651.       10688781.
      3725531.25       10688700.      3725438.46     10688733.98
       3725348.5       10688831.      3725275.75       10688821.
        3725200.       10688743.      3725226.25       10688702.
        3725238.       10688569.        3725135.       10688476.
        3725133.       10688414.      3725063.75       10688332.
        3724926.       10688310.      3724809.75       10688324.
      3724750.25       10688258.       3724659.5       10688288.
      3724584.25       10688225.      3724384.75       10688280.
       3724259.5       10688220.        3724212.       10688267.
      3724083.75       10688319.        3723925.       10688282.
      3723880.25       10688381.       3723825.5       10688379.
       3723754.5       10688330.      3723688.75       10688340.

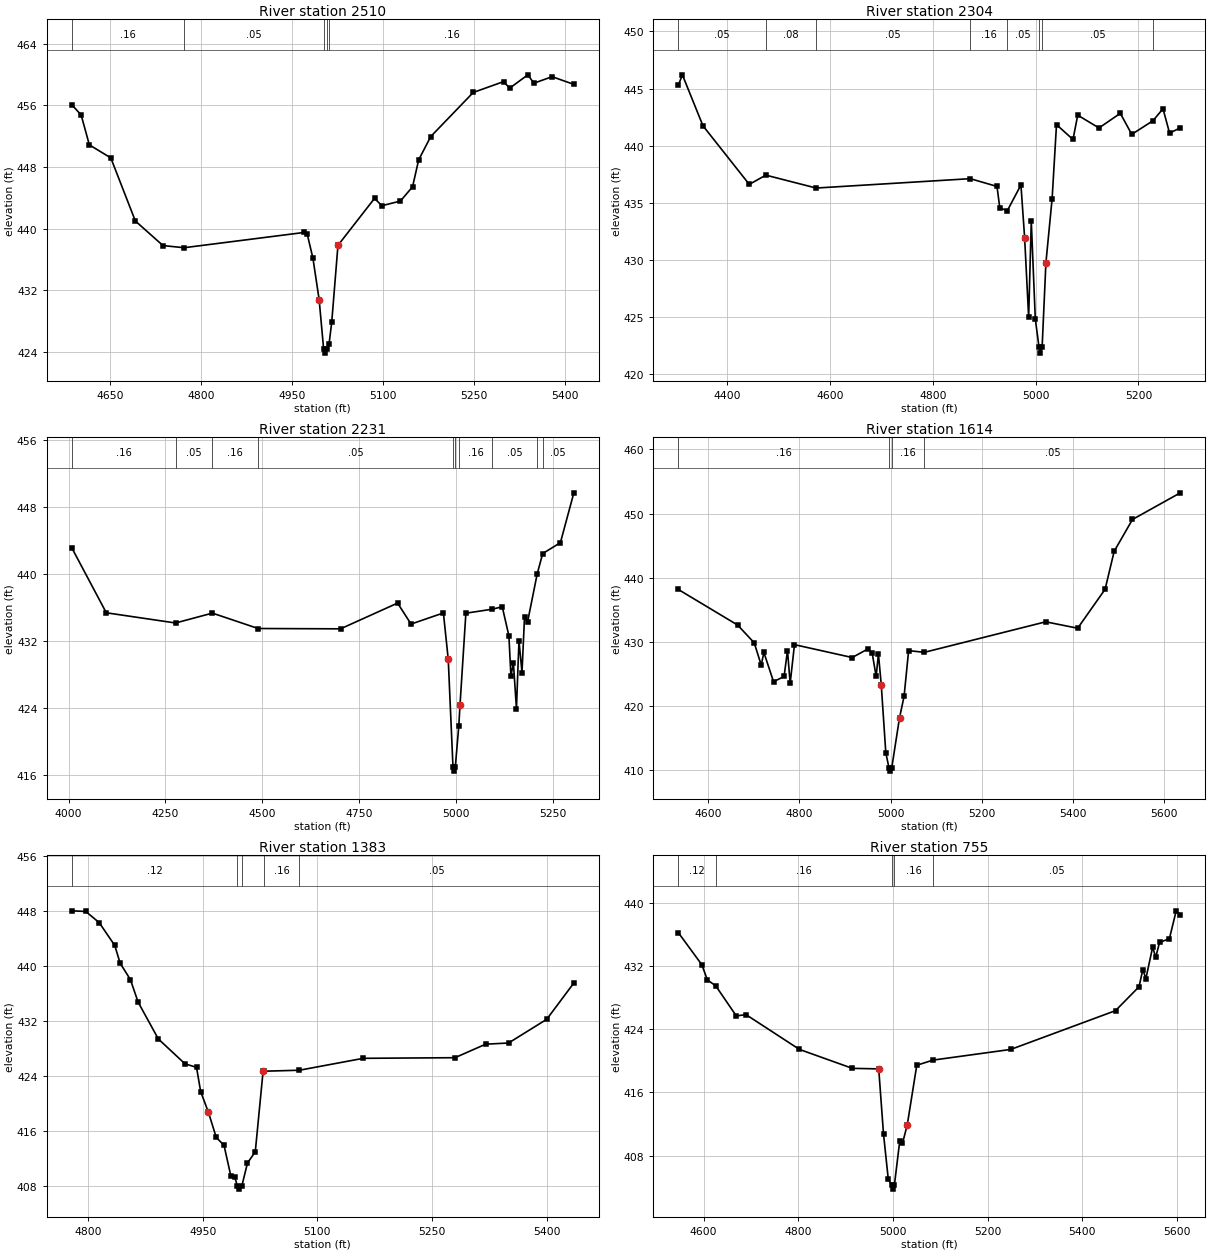
Type RM Length L Ch R = 1 ,2510    ,206,206,206
BEGIN DESCRIPTION:
Mapping XS 1caf1a8e
END DESCRIPTION:
XS GIS Cut Line= 3
      3725601.42     10688305.14      3725466.86     10688821.67
      3725453.88     10689116.02
#Sta/Elev= 30
  4586.5  456.08    4602  454.73  4615.5  450.86  4650.9  449.17  4691.4  440.98
    4737  437.79  4771.8  437.51  4969.7  439.49  4974.9   439.3  4984.4  436.15
  4994.7  430.74  5002.1  424.33  5004.8  423.83  5008.1  424.33  5011.1  425.07
  5015.4  427.83  5025.7  437.82  5086.1  443.92  5098.1  442.96  5128.8  443.57
  5148.8  445.42  5158.8   448.9  5178.8  451.94  5248.9  457.66    5299  459.07
    5309  458.22    5339  459.95    5349  458.86    5379  459.71  5414.9  458.71
#Mann= 5 ,-1 , 0
  4586.5     .16       0  4771.8     .05       0  5002.1     .03       0
  5008.1     .05       0  5011.1     .16       0
Bank Sta=4994.7,5025.7
XS Rating Curve= 0 ,0
Exp/Cntr=0.3,0.1

Type RM Length L Ch R = 1 ,2304    ,73,73,73
BEGIN DESCRIPTION:
UNT 137 IN CACR 4.0
END DESCRIPTION:
XS GIS Cut Line= 6
       3725466.2     10688152.12      3725450.57      10688441.2
       3725406.3     10688662.55      3725349.01     10688803.18
      3725312.55      10688943.8      3725268.27     10689102.69
#Sta/Elev= 30
  4304.2  445.27  4312.3   446.2  4352.3  441.74  4442.5  436.61  4474.7  437.42
  4572.7  436.29  4872.6  437.11  4924.7  436.43  4930.1  434.55  4944.8  434.31
  4971.3  436.56  4978.5  431.91  4986.3  424.97  4991.4   433.4  4999.2  424.85
  5006.5  422.34  5009.3  421.84  5012.5  422.34  5019.9  429.76    5032  435.37
  5040.5  441.84  5072.6  440.54  5081.8  442.67  5123.2  441.55  5164.7  442.83
    5187  440.99  5228.2  442.18  5247.8  443.23  5260.6   441.1  5281.5  441.56
#Mann= 8 ,-1 , 0
  4304.2     .05       0  4474.7     .08       0  4572.7     .05       0
  4872.6     .16       0  4944.8     .05       0  5006.5     .04       0
  5012.5     .05       0  5228.2     .16       0
Bank Sta=4978.5,5019.9
XS Rating Curve= 0 ,0
Exp/Cntr=0.3,0.1

Type RM Length L Ch R = 1 ,2231    ,617,617,617
BEGIN DESCRIPTION:
UNT 137 IN CACR 3.0
END DESCRIPTION:
XS GIS Cut Line= 6
      3725270.88     10687850.04      3725362.03     10688183.39
      3725328.18     10688600.05      3725296.93     10688777.14
      3725221.41     10688938.59      3725088.61     10689047.95
#Sta/Elev= 30
  4008.4  443.17  4097.5   435.4  4276.2  434.18  4371.2  435.36  4489.3  433.52
  4701.9  433.48  4849.2  436.56  4883.9  434.05  4967.4  435.38  4979.9  429.82
  4992.1  416.97  4994.8  416.47  4998.1  416.97  5007.1  421.87  5010.2  424.35
  5025.4  435.35  5093.8  435.83  5119.2  436.12  5136.4  432.65  5141.6  427.85
    5148  429.41  5155.9  423.95  5162.4  432.07  5170.2  428.26  5176.7  434.88
  5184.6  434.31  5209.4  440.04  5223.6  442.48  5269.3  443.78    5304  449.74
#Mann= 10 ,-1 , 0
  4008.4     .16       0  4276.2     .05       0  4371.2     .16       0
  4489.3     .05       0  4992.1     .04       0  4998.1     .05       0
  5007.1     .16       0  5093.8     .05       0  5209.4     .16       0
  5223.6     .05       0
Bank Sta=4979.9,5010.2
XS Rating Curve= 0 ,0
Exp/Cntr=0.3,0.1

Type RM Length L Ch R = 1 ,1614    ,231,231,231
BEGIN DESCRIPTION:
Mapping XS d7fe7814
END DESCRIPTION:
XS GIS Cut Line= 3
      3725262.86     10687923.25      3725058.88     10688248.76
      3725002.45      10688964.9
#Sta/Elev= 30
  4533.8  438.17  4664.1  432.62  4700.6  429.85    4716  426.38  4721.9  428.34
  4743.1  423.78  4766.2   424.6  4773.7  428.62  4779.6  423.52    4789  429.56
  4915.8  427.55  4949.5  428.86  4959.5  428.32  4968.4   424.6  4973.4  428.13
  4979.6  423.29  4989.6  412.71  4996.6  410.34  4999.4  409.84  5002.6  410.34
  5019.7  418.15  5029.7  421.49  5039.7  428.63  5074.2  428.36  5340.7  433.12
  5410.9  432.12  5471.1  438.19  5491.1  444.12  5531.3  449.08  5636.3  453.23
#Mann= 4 ,-1 , 0
  4533.8     .16       0  4996.6     .07       0  5002.6     .16       0
  5074.2     .05       0
Bank Sta=4979.6,5019.7
XS Rating Curve= 0 ,0
Exp/Cntr=0.3,0.1

Type RM Length L Ch R = 1 ,1383    ,628,628,628
BEGIN DESCRIPTION:
Mapping XS acb4276a
END DESCRIPTION:
XS GIS Cut Line= 3
      3724781.31     10688105.08       3724843.8     10688404.52
       3724833.4     10688755.67
#Sta/Elev= 30
  4778.5  447.98  4796.8  447.89  4814.4  446.27  4834.8  442.95  4841.8  440.38
  4855.2  438.01  4865.4  434.72  4891.8  429.39  4926.7  425.78  4941.8  425.27
  4947.2  421.76  4957.4  418.74  4967.6  415.11  4977.8  413.95  4986.7  409.52
  4991.8  409.35  4995.2   408.1    4998   407.6  5001.2   408.1  5008.5  411.39
  5018.7  413.02  5028.9  424.67  5029.8  424.71  5076.4  424.85  5160.1  426.58
  5280.1  426.67  5320.2  428.63  5350.2   428.8  5400.2  432.24  5435.7  437.51
#Mann= 5 ,-1 , 0
  4778.5     .12       0  4995.2     .07       0  5001.2     .12       0
  5029.8     .16       0  5076.4     .05       0
Bank Sta=4957.4,5028.9
XS Rating Curve= 0 ,0
Exp/Cntr=0.3,0.1

Type RM Length L Ch R = 1 ,755     ,379,379,379
BEGIN DESCRIPTION:
UNT 137 IN CACR 2.0
END DESCRIPTION:
XS GIS Cut Line= 4
      3724679.74     10688084.21      3724302.14     10688162.34
      3724289.11     10688302.96      3724619.82      10688722.2
#Sta/Elev= 30
  4546.5  436.21  4596.6  432.12  4607.9  430.23  4625.8  429.47  4669.2  425.67
  4689.6  425.84  4802.6  421.44  4914.3  419.05  4970.1  418.98  4980.2  410.76
  4990.2  405.09  4997.2  404.29    5000  403.79  5003.2  404.29  5014.5  409.87
  5020.3  409.58  5030.4  411.91  5050.5  419.44  5084.7  420.09  5249.1  421.44
  5470.4  426.34  5520.1  429.36  5528.1  431.53  5534.5  430.38  5548.9  434.37
  5555.3  433.07  5563.4  434.96  5584.2  435.42  5598.6  438.95  5607.3  438.48
#Mann= 5 ,-1 , 0
  4546.5     .12       0  4625.8     .16       0  4997.2     .07       0
  5003.2     .16       0  5084.7     .05       0
Bank Sta=4970.1,5030.4
XS Rating Curve= 0 ,0
Exp/Cntr=0.3,0.1

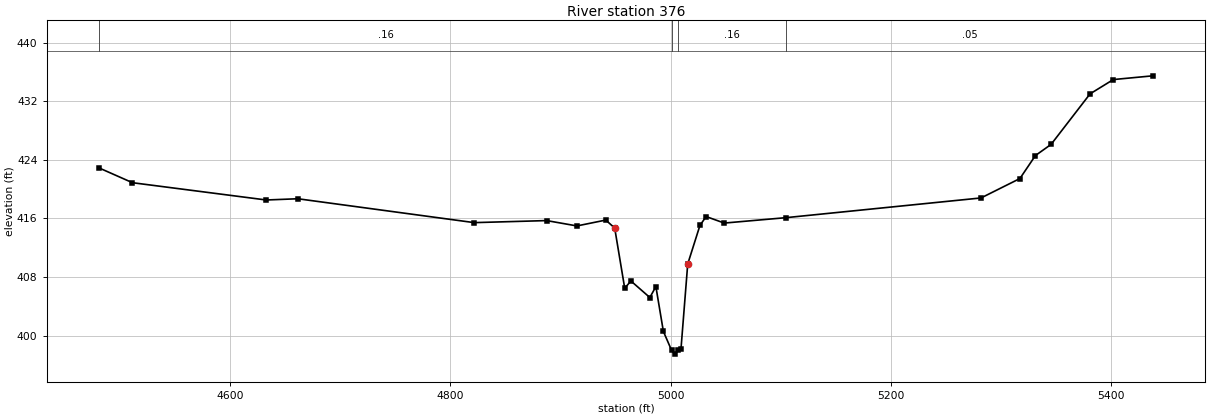
Type RM Length L Ch R = 1 ,376     ,0,0,0
BEGIN DESCRIPTION:
UNT 137 IN CACR 1.0
END DESCRIPTION:
XS GIS Cut Line= 4
      3724320.35     10688032.13      3723924.53     10688209.21
      3723989.64     10688347.23      3724250.08     10688610.28
#Sta/Elev= 30
  4481.4  422.87  4511.5  420.87    4633  418.51  4661.6  418.68  4821.8  415.42
  4887.5   415.7    4915  414.97  4941.2  415.77  4949.3  414.68  4958.4  406.46
    4964  407.46  4981.2   405.2  4986.7  406.69  4993.5  400.57    5001  397.97
  5003.7  397.47    5007  397.97  5009.5  398.21  5015.6  409.77  5026.7  415.04
  5032.3  416.25  5048.8  415.36  5104.9   416.1  5281.9  418.79  5317.2  421.44
  5331.3  424.58  5345.5   426.1  5380.9     433    5402  434.95  5437.8  435.46
#Mann= 4 ,-1 , 0
  4481.4     .16       0    5001     .07       0    5007     .16       0
  5104.9     .05       0
Bank Sta=4949.3,5015.6
XS Rating Curve= 0 ,0
Exp/Cntr=0.3,0.1

Chan Stop Cuts=-1
Use User Specified Reach Order=0
Composite Channel Slope=5