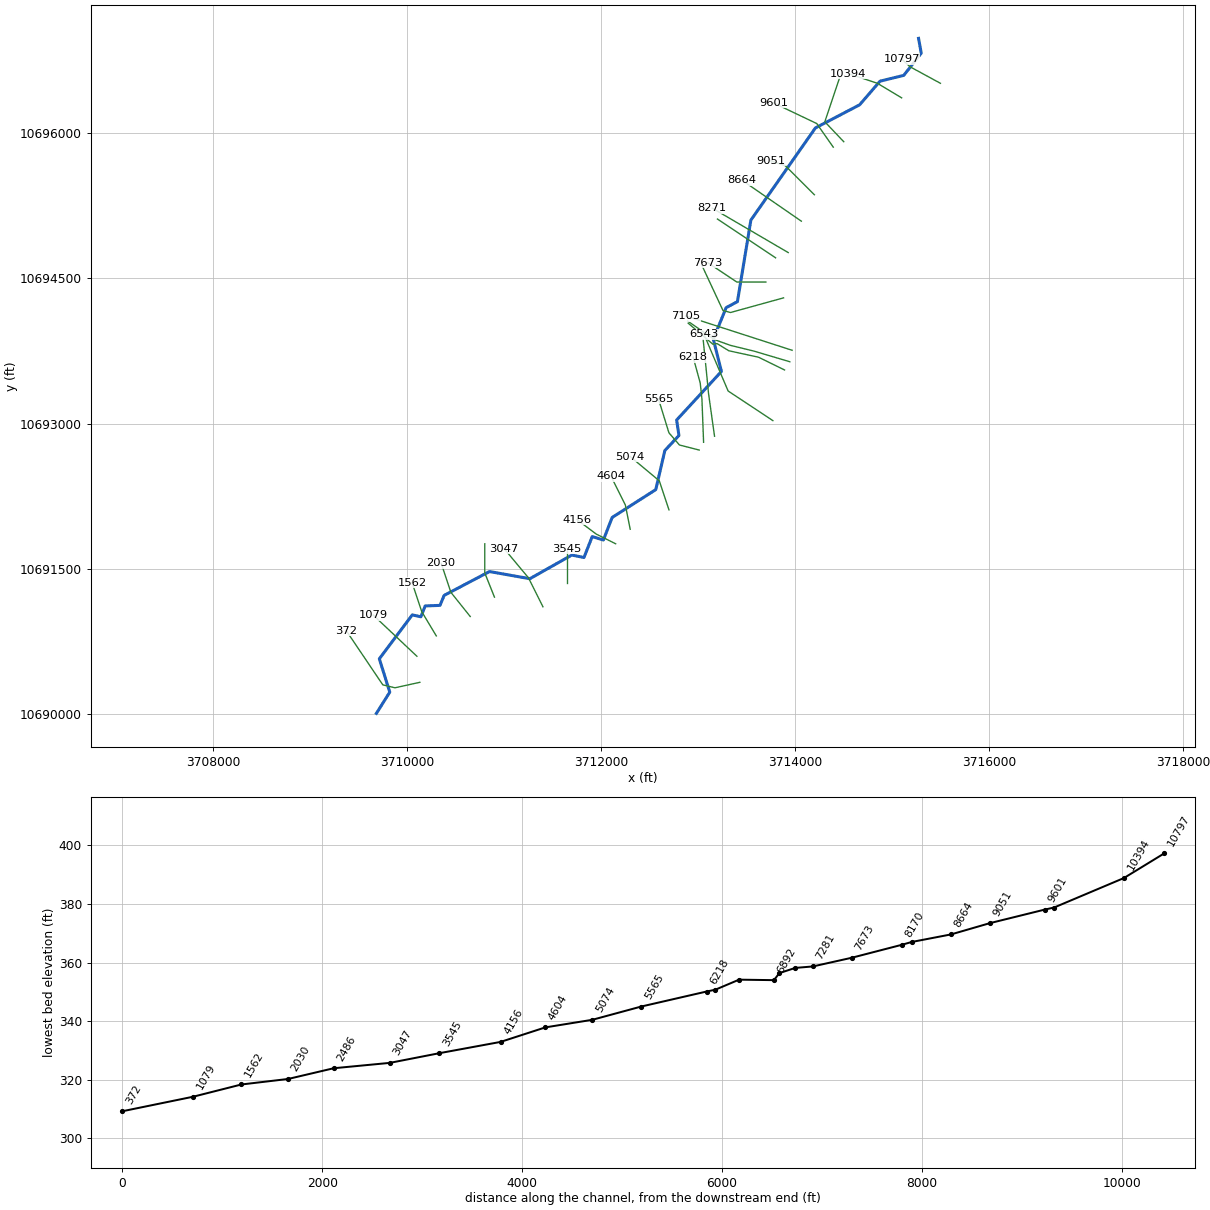
--- UNT 138 IN CACR.prj (project) ---

Proj Title=UNT 138 IN CACR Base Level Engineering
Current Plan=p01
Default Exp/Contr=0.3,0.1
English Units
Geom File=g01
Flow File=f01
Plan File=p01
Y Axis Title=Elevation
X Axis Title(PF)=Main Channel Distance
X Axis Title(XS)=Station
BEGIN DESCRIPTION:
UNT 138 IN CACR
END DESCRIPTION:
DSS Export Rating Curves= 0
DSS Export Rating Curve Sorted= 0
DSS Export Volume Flow Curves= 0
DXF OffsetX= 0
DXF OffsetY= 0
DXF ScaleX= 1
DXF ScaleY= 10

--- UNT 138 IN CACR.p01 (plan) ---

Plan Title=Multiple Run
Short Identifier=Multiple
Geom File=g01
Flow File=f01
Subcritical Flow
K Sum by GR= 0
Std Step Tol= 0.01
Critical Tol= 0.01
Num of Std Step Trials= 20
Max Error Tol= 0.3
Flow Tol Ratio= 0.001
Split Flow NTrial= 30
Split Flow Tol= 0.02
Split Flow Ratio= 0.02
Log Output Level= 0
Friction Slope Method= 1
Unsteady Friction Slope Method= 2
Unsteady Bridges Friction Slope Method= 1
Parabolic Critical Depth
Global Vel Dist=  1 , 1 , 1
Global Log Level= 0
CheckData=True
Encroach Param= -1, 0, 0, 0
BEGIN DESCRIPTION:
Multiple Run
END DESCRIPTION:

--- UNT 138 IN CACR.f01 (steady flow) ---

Flow Title=Multiple
Number of Profiles=7
Profile Names=10-year,25-year,50-year,1pct_min,100-year,1pct_plu,500-year
River Rch & RM= UNT 138 IN CACR,Reach-1,10797
     185     235     275     238     322     435     440
River Rch & RM= UNT 138 IN CACR,Reach-1,9601
     424     568     687     613     829    1121    1207
River Rch & RM= UNT 138 IN CACR,Reach-1,5565
     534     724     881     788    1066    1442    1568
Boundary for River Rch & Prof#=UNT 138 IN CACR,Reach-1,1
Up Type=0
Dn Type=3
Dn Slope=0.005
Boundary for River Rch & Prof#=UNT 138 IN CACR,Reach-1,2
Up Type=0
Dn Type=3
Dn Slope=0.005
Boundary for River Rch & Prof#=UNT 138 IN CACR,Reach-1,3
Up Type=0
Dn Type=3
Dn Slope=0.005
Boundary for River Rch & Prof#=UNT 138 IN CACR,Reach-1,4
Up Type=0
Dn Type=3
Dn Slope=0.005
Boundary for River Rch & Prof#=UNT 138 IN CACR,Reach-1,5
Up Type=0
Dn Type=3
Dn Slope=0.005
Boundary for River Rch & Prof#=UNT 138 IN CACR,Reach-1,6
Up Type=0
Dn Type=3
Dn Slope=0.005
Boundary for River Rch & Prof#=UNT 138 IN CACR,Reach-1,7
Up Type=0
Dn Type=3
Dn Slope=0.005

--- UNT 138 IN CACR.g01 (geometry) ---

Geom Title=Existing Conditions
Program Version=4.10

River Reach=UNT 138 IN CACR ,Reach-1
Reach XY= 30
      3715273.97     10696973.92      3715301.75     10696821.14
      3715121.19     10696591.97       3714876.5       10696532.
        3714666.       10696288.       3714210.5       10696050.
       3713544.5       10695099.      3713405.75       10694258.
      3713289.25       10694196.        3713157.       10693870.
      3713240.75       10693538.        3712779.       10693037.
      3712802.25       10692877.        3712657.       10692722.
       3712563.5       10692319.      3712113.75       10692032.
        3712023.       10691799.        3711908.       10691835.
        3711823.       10691619.        3711697.       10691644.
       3711264.5       10691400.      3710848.25       10691474.
      3710380.75       10691228.      3710337.75       10691125.
      3710184.75       10691119.      3710140.75       10691007.
        3710052.       10691027.        3709712.       10690574.
      3709819.75       10690230.      3709681.75       10690011.

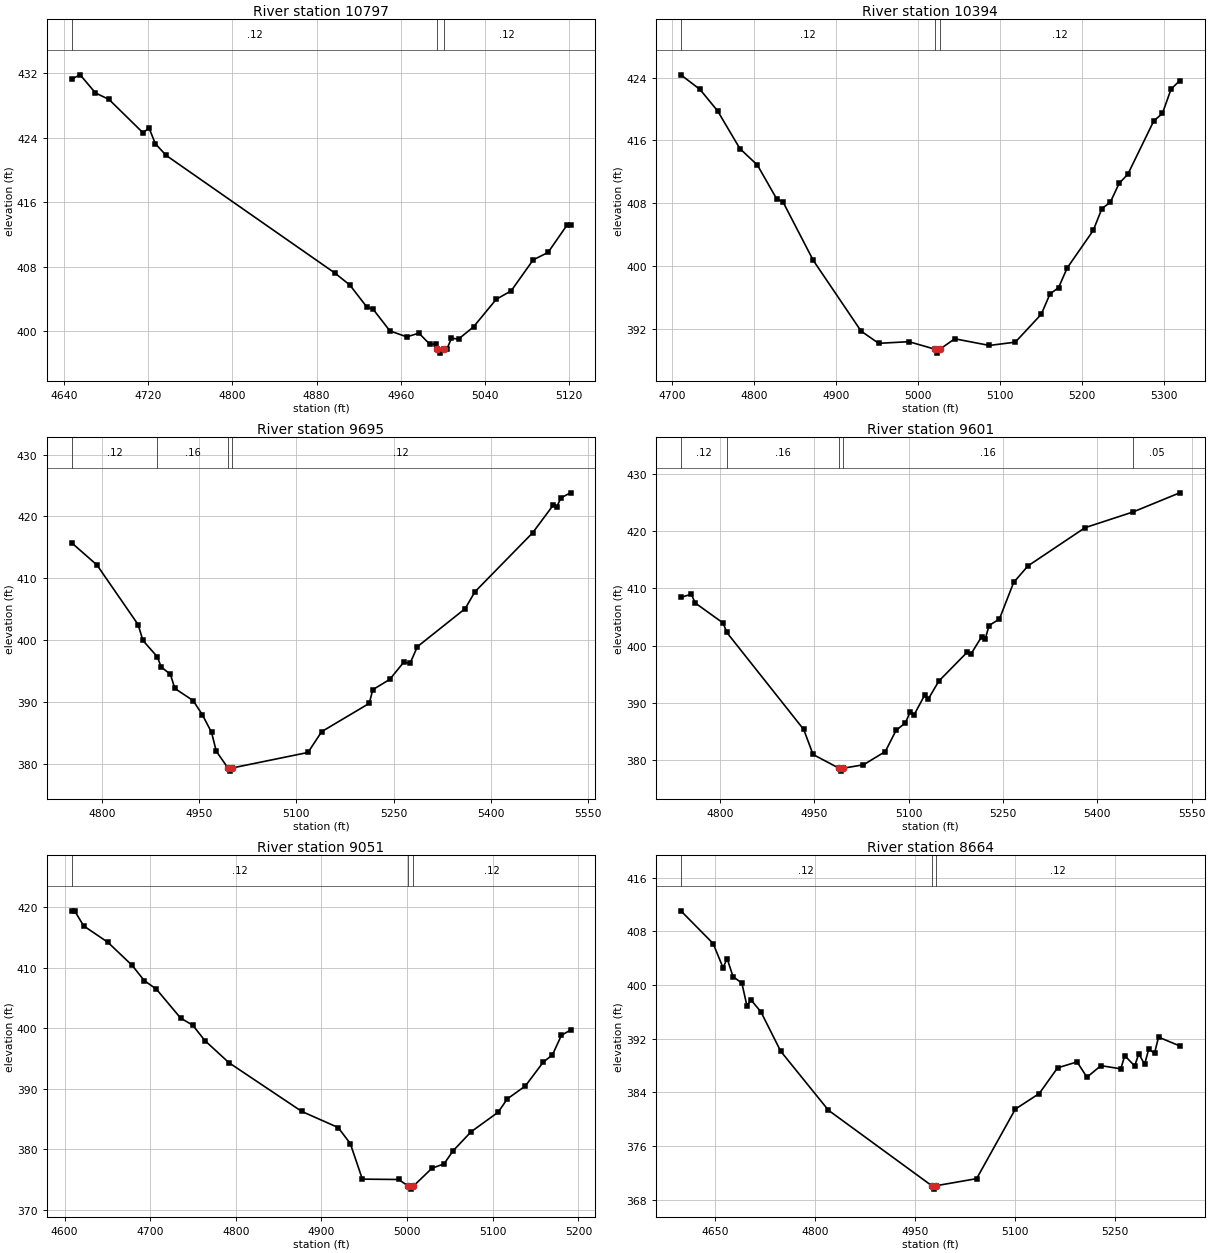
Type RM Length L Ch R = 1 ,10797   ,403,403,403
BEGIN DESCRIPTION:
UNT 138 IN CACR 23.0
END DESCRIPTION:
XS GIS Cut Line= 3
      3715499.59      10696510.2      3715188.24     10696679.36
       3715099.6      10696760.2
#Sta/Elev= 30
  4647.1  431.28  4655.2  431.81  4669.8  429.56  4682.7  428.75    4715  424.61
  4720.7  425.22  4726.7  423.26  4736.9  421.82  4897.4  407.21  4911.7  405.71
  4927.9  402.97  4933.6  402.74  4949.7  400.03  4965.7  399.29  4977.3  399.75
  4987.8  398.35  4993.4   398.4  4994.8  397.77  4997.6  397.27  5000.8  397.77
  5003.9  397.77  5008.2  399.11    5015  399.02  5029.2  400.53  5050.8  403.95
    5065     405  5085.9  408.84  5100.1  409.77    5118  413.14  5121.4  413.14
#Mann= 3 ,-1 , 0
  4647.1     .12       0  4994.8     .07       0  5000.8     .12       0
Bank Sta=4994.8,5000.8
XS Rating Curve= 0 ,0
Exp/Cntr=0.3,0.1

Type RM Length L Ch R = 1 ,10394   ,699,699,699
BEGIN DESCRIPTION:
UNT 138 IN CACR 22.0
END DESCRIPTION:
XS GIS Cut Line= 3
      3715099.61     10696360.19      3714849.61     10696510.19
      3714549.58      10696610.2
#Sta/Elev= 30
  4711.1  424.37  4734.4  422.51  4755.8  419.78    4783  414.96  4804.4  412.85
  4827.7  408.57  4835.5  408.16  4872.4   400.7  4930.7  391.67  4952.1  390.11
    4989  390.32  5020.7  389.36  5023.5  388.86  5026.7  389.36  5044.8  390.69
    5087  389.84  5118.6  390.26  5150.2  393.82  5160.8   396.4  5171.3  397.22
  5181.8  399.73  5213.5  404.51    5224  407.28  5234.5  408.14  5245.1  410.53
  5255.6  411.67  5287.3  418.49  5297.8  419.44  5308.3  422.54  5318.9  423.63
#Mann= 3 ,-1 , 0
  4711.1     .12       0  5020.7     .07       0  5026.7     .12       0
Bank Sta=5020.7,5026.7
XS Rating Curve= 0 ,0
Exp/Cntr=0.3,0.1

Type RM Length L Ch R = 1 ,9695    ,94,94,94
BEGIN DESCRIPTION:
Mapping XS 88ffeacd
END DESCRIPTION:
XS GIS Cut Line= 3
      3714502.34     10695907.57      3714307.04     10696113.29
      3714461.97     10696574.19
#Sta/Elev= 30
  4753.2  415.75  4792.4  412.14  4855.9  402.49  4863.2  399.94  4885.4   397.3
  4891.5  395.63  4905.6  394.47  4912.5  392.17  4940.8   390.2    4955  387.91
  4969.2  385.05  4976.4  382.02  4994.5  379.29  4997.2  378.79  5000.5  379.29
    5118  381.81  5139.1  385.18  5212.6  389.76  5217.9  391.97  5244.1  393.63
  5265.7  396.41  5275.6  396.26  5286.8  398.93  5360.6  405.09  5375.5   407.8
  5464.7  417.36  5496.3  421.82  5501.5  421.46  5508.3  423.02  5523.1  423.83
#Mann= 4 ,-1 , 0
  4753.2     .12       0  4885.4     .16       0  4994.5     .07       0
  5000.5     .12       0
Bank Sta=4994.5,5000.5
XS Rating Curve= 0 ,0
Exp/Cntr=0.3,0.1

Type RM Length L Ch R = 1 ,9601    ,550,550,550
BEGIN DESCRIPTION:
Mapping XS ced4fe2a
END DESCRIPTION:
XS GIS Cut Line= 3
      3714394.28     10695851.58      3714223.71     10696095.06
      3713775.79     10696308.61
#Sta/Elev= 30
  4737.6  408.45  4754.3  408.99  4760.4  407.47  4804.9  403.95  4810.7  402.31
    4933  385.36  4947.9  380.99  4989.3  378.58  4992.1  378.08  4995.3  378.58
  5028.1  379.19  5062.8   381.5  5079.9   385.2  5094.8  386.52  5102.6  388.49
  5108.2  387.84  5125.3  391.33  5130.9  390.63    5148  393.82  5193.4   398.9
  5198.9  398.51  5216.1  401.58  5221.6   401.1  5227.8  403.52  5244.3  404.66
    5267  411.06  5289.7  413.94  5380.5  420.62  5456.7  423.36  5531.1  426.71
#Mann= 5 ,-1 , 0
  4737.6     .12       0  4810.7     .16       0  4989.3     .07       0
  4995.3     .16       0  5456.7     .05       0
Bank Sta=4989.3,4995.3
XS Rating Curve= 0 ,0
Exp/Cntr=0.3,0.1

Type RM Length L Ch R = 1 ,9051    ,387,387,387
BEGIN DESCRIPTION:
UNT 138 IN CACR 19.0
END DESCRIPTION:
XS GIS Cut Line= 3
       3714199.6      10695360.2      3713899.61     10695660.19
      3713749.58      10695710.2
#Sta/Elev= 30
  4608.3  419.37  4611.8  419.37  4622.4  416.88  4650.7  414.17    4679  410.36
  4693.1  407.86  4707.3  406.44  4735.6  401.66  4749.7   400.5  4763.9  397.95
  4792.1  394.29    4877  386.26  4919.4  383.61  4933.6  380.97  4947.7  375.09
  4990.1  375.03  5001.3  373.94    5004  373.44  5007.3  373.94    5029  376.89
  5043.1  377.61  5053.6  379.76  5074.7  382.91  5106.3  386.14  5116.9  388.33
    5138  390.46    5159  394.42  5169.6  395.59  5180.1  398.83  5190.7  399.69
#Mann= 3 ,-1 , 0
  4608.3     .12       0  5001.3     .07       0  5007.3     .12       0
Bank Sta=5001.3,5007.3
XS Rating Curve= 0 ,0
Exp/Cntr=0.3,0.1

Type RM Length L Ch R = 1 ,8664    ,393,393,393
BEGIN DESCRIPTION:
Mapping XS 0508fa38
END DESCRIPTION:
XS GIS Cut Line= 2
      3714065.04     10695087.99      3713448.68     10695513.37
#Sta/Elev= 30
  4598.9  411.04  4647.4  406.17  4662.3  402.56  4668.4  403.94  4677.2  401.25
  4690.5  400.28  4698.1  396.91  4704.2  397.78  4719.1     396  4748.8  390.14
  4820.5  381.35  4975.7  370.11  4978.4  369.61  4981.7  370.11  5042.9  371.17
  5101.1  381.53  5136.9  383.84  5164.4  387.66  5193.7  388.55  5208.5  386.27
  5229.5  387.99  5259.3  387.52  5265.3  389.48  5280.2  387.94  5286.3  389.76
  5295.1  388.19  5301.2  390.42    5310  389.85    5316  392.24  5347.8  390.93
#Mann= 3 ,-1 , 0
  4598.9     .12       0  4975.7     .07       0  4981.7     .12       0
Bank Sta=4975.7,4981.7
XS Rating Curve= 0 ,0
Exp/Cntr=0.3,0.1

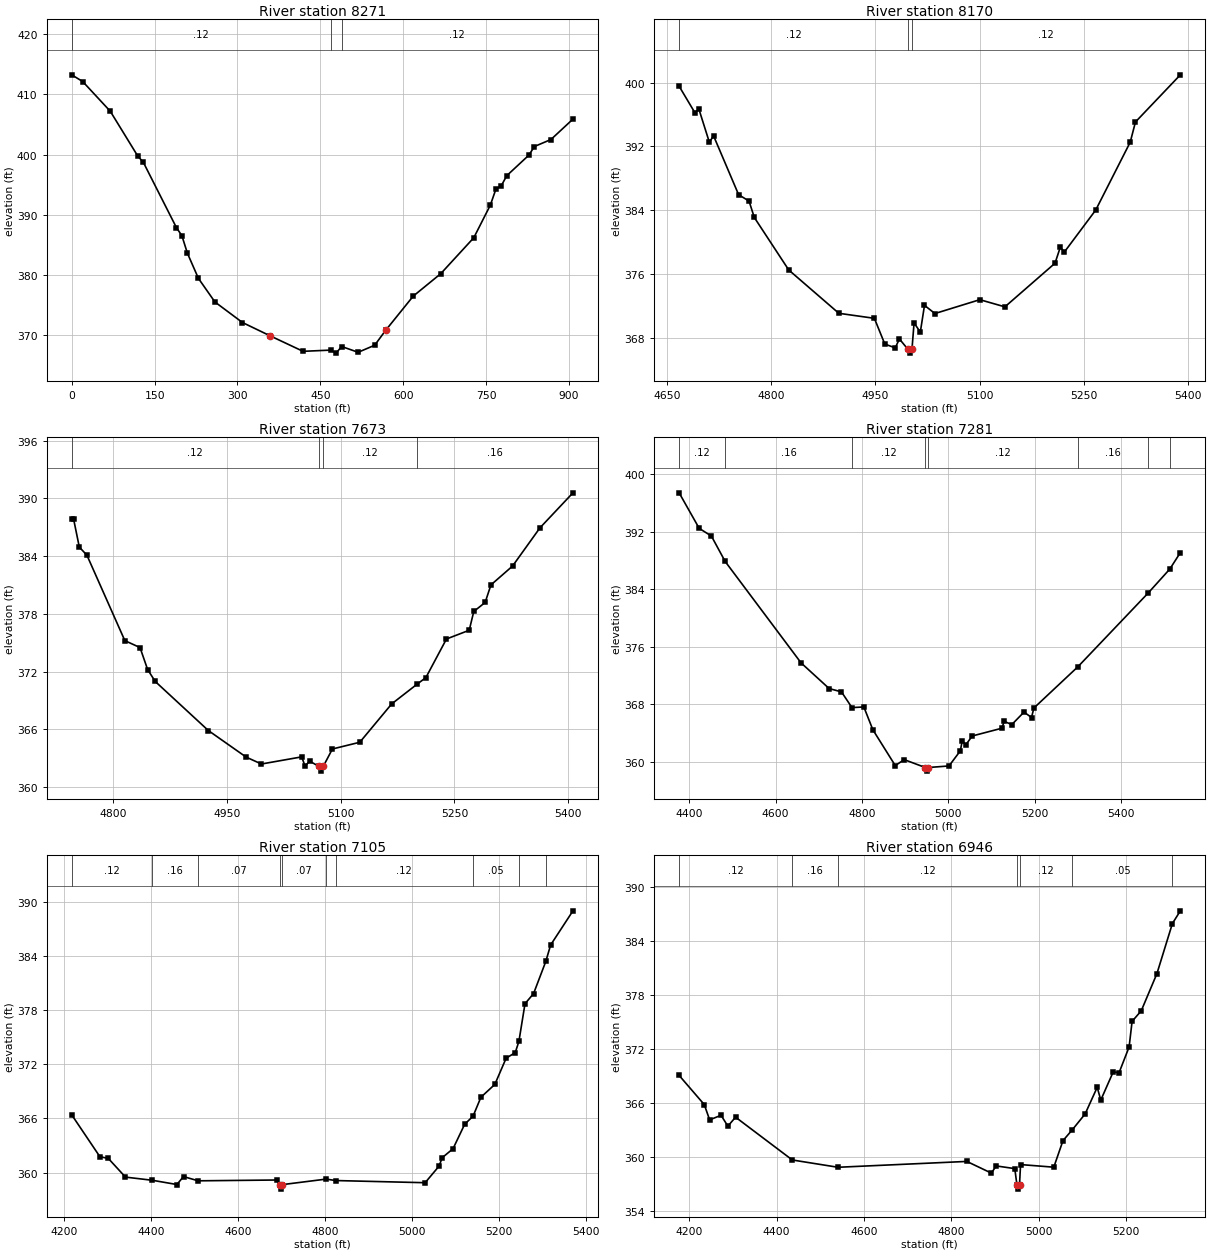
Type RM Length L Ch R = 1 ,8271    ,101,101,101
XS GIS Cut Line= 2
     3713929.619    10694764.152     3713145.765    10695222.485
#Sta/Elev= 30
       0  413.23   19.94  412.11    69.8  407.18  119.65  399.73  129.62  398.71
  189.45  387.88  199.42  386.52  209.39  383.62  229.33  379.44  259.25  375.52
   309.1  372.11  358.96  369.91  418.78  367.33  468.64  367.53  478.61  367.03
  488.58  368.13  518.49  367.17  548.41  368.34  568.35  370.82   618.2  376.49
  668.06  380.22  727.88  386.19   757.8   391.6  767.77  394.23  777.74  394.85
  787.71   396.5  827.59   399.9  837.56  401.33  867.48  402.49  907.36  405.88
#Mann= 3 ,-1 , 0
       0     .12       0  468.64     .07       0  488.58     .12       0
Bank Sta=358.96,568.35
XS Rating Curve= 0 ,0
Exp/Cntr=0.3,0.1

Type RM Length L Ch R = 1 ,8170    ,497,497,497
BEGIN DESCRIPTION:
UNT 138 IN CACR 17.0
END DESCRIPTION:
XS GIS Cut Line= 3
      3713799.57     10694710.21      3713499.61     10694910.19
      3713199.58     10695110.21
#Sta/Elev= 30
  4667.5  399.56    4690  396.26    4696  396.67    4711  392.52    4717  393.34
  4753.1  385.94  4768.1  385.14  4775.6  383.09  4825.2  376.49  4897.3  371.05
  4948.4  370.42  4963.4  367.19  4978.4  366.71  4984.4  367.83  4996.5  366.55
  4999.2  366.05  5002.5  366.55  5005.5  369.84  5014.5  368.69  5020.5  372.05
  5035.5  371.02  5100.1  372.76  5136.2  371.86  5208.3  377.34  5215.8  379.33
  5221.8  378.75  5266.9  384.02  5316.5  392.54    5324  395.07  5388.6  400.99
#Mann= 3 ,-1 , 0
  4667.5     .12       0  4996.5     .07       0  5002.5     .12       0
Bank Sta=4996.5,5002.5
XS Rating Curve= 0 ,0
Exp/Cntr=0.3,0.1

Type RM Length L Ch R = 1 ,7673    ,392,392,392
BEGIN DESCRIPTION:
UNT 138 IN CACR 16.0
END DESCRIPTION:
XS GIS Cut Line= 3
      3713699.58     10694460.19      3713399.61     10694460.19
      3713099.63     10694660.18
#Sta/Elev= 30
  4745.6  387.84  4748.1  387.84  4755.6  384.94  4765.6   384.1  4815.6  375.22
  4835.6   374.5  4845.6  372.22  4855.6  370.98  4925.6  365.88  4975.6  363.11
  4995.6   362.4  5048.6  363.14  5053.1  362.18  5059.1   362.7  5071.1  362.16
  5073.9  361.66  5077.1  362.16  5089.1  363.96  5125.2  364.66  5167.3  368.65
  5201.1  370.72  5212.3  371.38  5239.4  375.39  5269.4   376.3  5275.4  378.25
  5290.4  379.19    5298  381.01  5326.5  382.97  5362.6  386.94  5406.1  390.58
#Mann= 4 ,-1 , 0
  4745.6     .12       0  5071.1     .07       0  5077.1     .12       0
  5201.1     .16       0
Bank Sta=5071.1,5077.1
XS Rating Curve= 0 ,0
Exp/Cntr=0.3,0.1

Type RM Length L Ch R = 1 ,7281    ,176,176,176
BEGIN DESCRIPTION:
UNT 138 IN CACR 15.0
END DESCRIPTION:
XS GIS Cut Line= 4
      3713881.61     10694296.93      3713334.72     10694145.89
      3713256.59     10694166.72      3713040.44     10694630.27
#Sta/Elev= 30
    4377   397.4  4423.4  392.46  4451.7  391.38  4483.5  387.85  4659.2  373.73
  4724.1  370.16  4752.6   369.7  4776.9  367.51  4804.4   367.6  4825.2  364.43
  4877.1  359.44  4897.8  360.27  4946.7  359.17  4949.4  358.67  4952.7  359.17
  5001.4  359.39  5027.6  361.49  5032.2  362.93  5040.1  362.31  5055.1  363.56
  5123.7  364.64  5129.2   365.6  5146.6  365.14    5175  366.89  5192.3  366.13
  5197.8  367.45  5299.9  373.21  5462.9   383.5  5512.4   386.8  5536.7  389.08
#Mann= 8 ,-1 , 0
    4377     .12       0  4483.5     .16       0  4776.9     .12       0
  4946.7     .07       0  4952.7     .12       0  5299.9     .16       0
  5462.9     .08       0  5512.4     .05       0
Bank Sta=4946.7,4952.7
XS Rating Curve= 0 ,0
Exp/Cntr=0.3,0.1

Type RM Length L Ch R = 1 ,7105    ,159,159,159
BEGIN DESCRIPTION:
Mapping XS c38ee71a
END DESCRIPTION:
XS GIS Cut Line= 2
      3713969.55      10693756.4      3712873.44     10694110.21
#Sta/Elev= 30
    4218  366.39  4282.7  361.76    4302  361.57  4341.5   359.5  4403.2  359.15
  4459.6  358.68  4474.9  359.56  4508.5  359.09  4690.8  359.18  4696.2  358.67
    4699  358.17  4702.2  358.67  4802.7  359.28  4824.4  359.12  5030.1  358.88
  5062.2  360.72  5069.1  361.64  5094.2  362.64    5121  365.35  5140.3  366.25
  5158.3  368.34  5190.3  369.76  5216.2  372.66  5237.2  373.28  5245.6  374.52
  5259.6  378.69  5279.3  379.81  5307.4  383.37  5318.5  385.19  5369.8  388.97
#Mann= 10 ,-1 , 0
    4218     .12       0  4403.2     .16       0  4508.5     .07       0
  4696.2     .07       0  4702.2     .07       0  4802.7     .16       0
  4824.4     .12       0  5140.3     .05       0  5245.6     .12       0
  5307.4     .05       0
Bank Sta=4696.2,4702.2
XS Rating Curve= 0 ,0
Exp/Cntr=0.3,0.1

Type RM Length L Ch R = 1 ,6946    ,54,54,54
BEGIN DESCRIPTION:
Mapping XS b2fc5a03
END DESCRIPTION:
XS GIS Cut Line= 5
      3713946.51     10693637.88      3713578.07     10693747.25
      3713333.27     10693807.14      3713170.51     10693865.73
       3712893.2     10694057.52
#Sta/Elev= 30
  4177.2  369.04  4234.7   365.8    4247   364.1  4273.1  364.61  4288.7   363.4
  4306.3   364.4  4436.1  359.64  4540.6  358.83  4835.3  359.48  4891.4  358.18
  4902.5  358.98    4945  358.68  4949.8   356.9  4952.6   356.4  4955.8   356.9
  4958.2  359.13  5034.2  358.84  5055.2  361.79  5076.4  362.99  5105.9  364.76
  5133.5  367.72  5141.7   366.3    5170  369.42  5183.6  369.35  5206.5  372.21
  5213.3  375.05  5234.3  376.23  5270.1  380.36  5305.5  385.93  5323.7  387.34
#Mann= 7 ,-1 , 0
  4177.2     .12       0  4436.1     .16       0  4540.6     .12       0
  4949.8     .07       0  4955.8     .12       0  5076.4     .05       0
  5305.5     .12       0
Bank Sta=4949.8,4955.8
XS Rating Curve= 0 ,0
Exp/Cntr=0.3,0.1

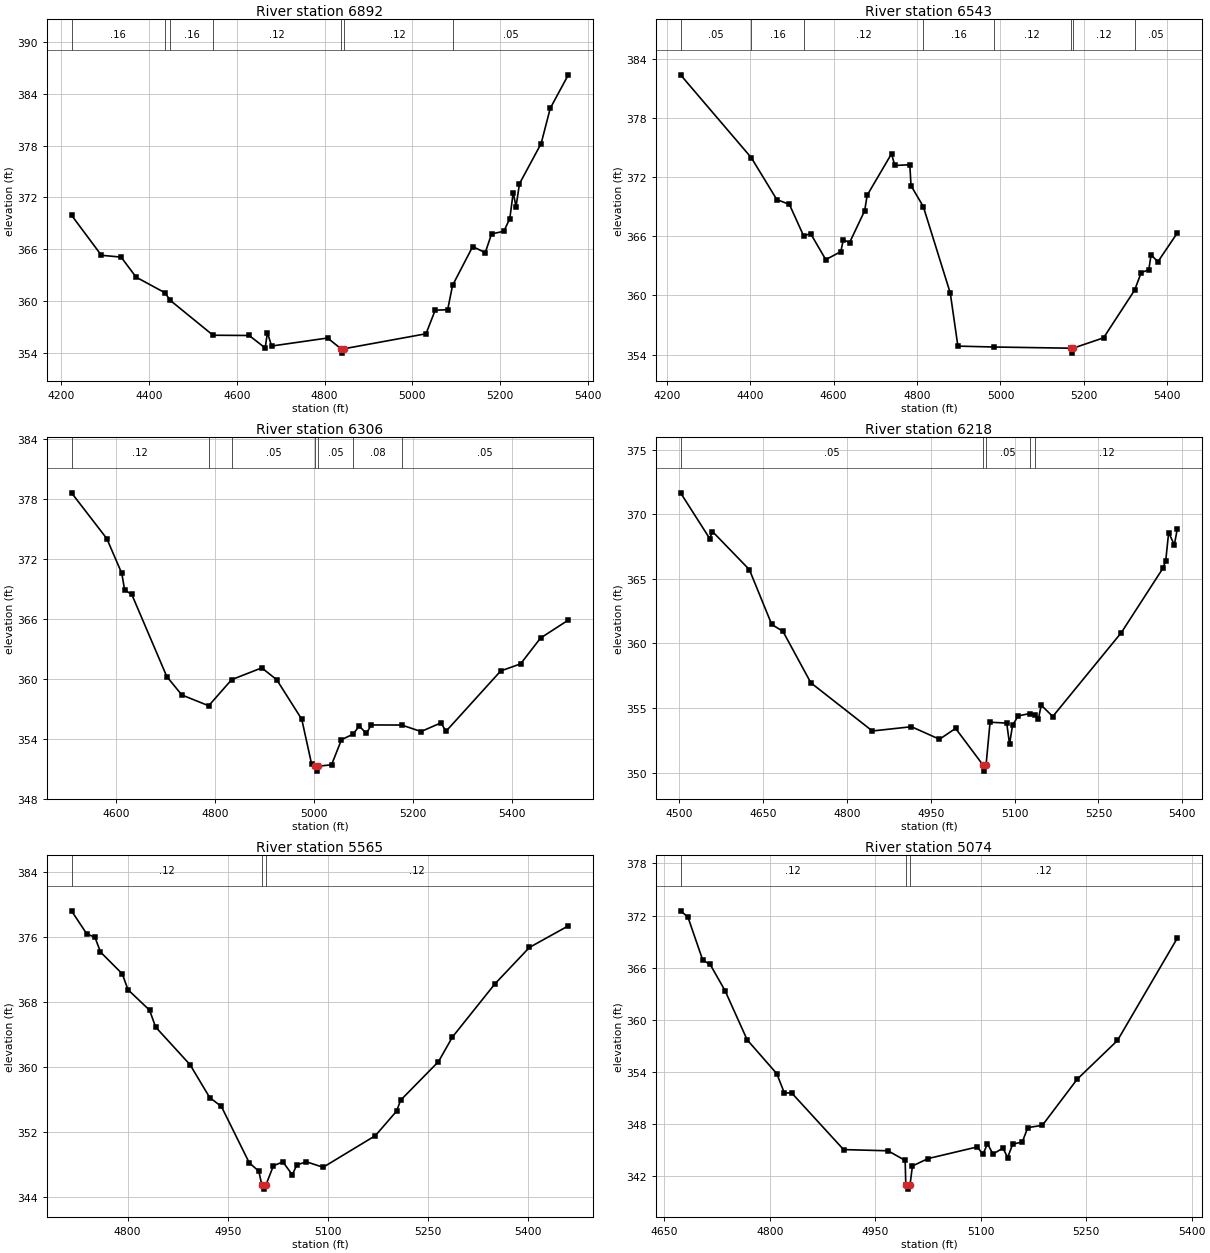
Type RM Length L Ch R = 1 ,6892    ,349,349,349
BEGIN DESCRIPTION:
Mapping XS 0250bb45
END DESCRIPTION:
XS GIS Cut Line= 6
      3713891.83     10693553.25      3713623.64     10693684.75
      3713317.65     10693751.15      3713195.25     10693825.37
      3713152.29     10693818.86      3712897.75     10694035.73
#Sta/Elev= 30
  4222.9  369.95    4291  365.31    4336   365.1  4370.2  362.78  4435.7  360.98
  4448.4  360.08  4545.6  356.06    4628  356.03  4664.5  354.59  4669.6  356.35
  4679.2  354.81  4806.9  355.74  4837.4  354.49  4840.1  353.99  4843.4  354.49
  5031.2  356.23  5052.1  358.95  5080.6  359.02  5091.8  361.84  5137.7  366.32
  5166.3  365.61  5180.6  367.78  5208.7  368.09  5222.3  369.56    5230  372.57
  5236.5  370.94  5244.3  373.59  5293.7  378.24  5314.5  382.32  5355.7  386.19
#Mann= 7 ,-1 , 0
  4222.9     .16       0  4435.7     .12       0  4448.4     .16       0
  4545.6     .12       0  4837.4     .07       0  4843.4     .12       0
  5091.8     .05       0
Bank Sta=4837.4,4843.4
XS Rating Curve= 0 ,0
Exp/Cntr=0.3,0.1

Type RM Length L Ch R = 1 ,6543    ,237,237,237
BEGIN DESCRIPTION:
Mapping XS 3eeb4cdb
END DESCRIPTION:
XS GIS Cut Line= 3
      3713771.64      10693030.7      3713309.82     10693336.26
      3713059.82     10693923.07
#Sta/Elev= 30
  4232.7  382.35  4402.5  373.95  4463.6  369.71  4493.7  369.23  4527.8  366.05
  4544.9  366.25    4581  363.63  4617.1  364.44  4623.1  365.64  4638.2  365.36
  4674.3  368.58  4680.3  370.15  4738.8  374.36  4746.5  373.17  4782.6  373.24
  4785.5  371.12    4815     369  4879.7  360.23  4897.9  354.87  4984.1  354.78
  5168.2  354.66  5170.9  354.16  5174.2  354.66  5247.3  355.71  5321.8  360.54
  5337.6  362.32  5355.8   362.6  5361.2  364.11  5377.7  363.42  5424.3  366.34
#Mann= 8 ,-1 , 0
  4232.7     .05       0  4402.5     .16       0  4527.8     .12       0
    4815     .16       0  4984.1     .12       0  5168.2     .07       0
  5174.2     .12       0  5321.8     .05       0
Bank Sta=5168.2,5174.2
XS Rating Curve= 0 ,0
Exp/Cntr=0.3,0.1

Type RM Length L Ch R = 1 ,6306    ,88,88,88
BEGIN DESCRIPTION:
UNT 138 IN CACR 13.0
END DESCRIPTION:
XS GIS Cut Line= 4
      3713169.61     10692869.56      3713107.11      10693314.9
      3713091.49     10693478.96      3713052.51      10693866.1
#Sta/Elev= 30
    4510  378.58  4581.3     374  4611.6  370.52  4617.3  368.87  4631.8  368.41
  4702.5   360.2  4732.8  358.36  4787.1  357.28  4833.5  359.89  4894.4  361.07
  4924.6  359.88  4975.1  355.93  4995.1  351.43  5002.2  351.24  5004.9  350.74
  5008.2  351.24  5035.3  351.37  5055.4  353.89  5078.9  354.44  5091.1  355.25
  5105.6  354.52  5115.7  355.36    5177  355.35  5216.2   354.7  5256.4  355.57
  5266.4  354.72    5377  360.76  5417.2  361.47  5457.4  364.05  5513.6  365.85
#Mann= 7 ,-1 , 0
    4510     .12       0  4787.1     .16       0  4833.5     .05       0
  5002.2     .04       0  5008.2     .05       0  5078.9     .08       0
    5177     .05       0
Bank Sta=5002.2,5008.2
XS Rating Curve= 0 ,0
Exp/Cntr=0.3,0.1

Type RM Length L Ch R = 1 ,6218    ,653,653,653
BEGIN DESCRIPTION:
UNT 138 IN CACR 12.0
END DESCRIPTION:
XS GIS Cut Line= 4
      3713056.77     10692807.05       3713039.4     10693258.47
      3713022.04     10693418.19      3712949.16     10693685.41
#Sta/Elev= 30
  4501.9  371.67  4554.1  368.13  4559.1  368.67  4625.1  365.72  4665.2  361.47
  4685.2  360.94  4735.2  356.95  4845.3  353.22  4915.3  353.55  4965.4  352.58
  4994.3  353.42  5042.9  350.61  5045.7  350.11  5048.9  350.61    5056   353.9
  5085.8  353.83  5090.9   352.2  5096.2  353.65  5106.3  354.39  5127.1  354.57
  5137.2  354.49  5142.4  354.13  5147.6  355.22  5168.2  354.34    5291  360.84
  5365.2  365.81  5370.5  366.42  5375.7  368.59  5385.9  367.64  5391.3   368.9
#Mann= 5 ,-1 , 0
  4501.9     .05       0  5042.9     .04       0  5048.9     .05       0
  5127.1     .08       0  5137.2     .12       0
Bank Sta=5042.9,5048.9
XS Rating Curve= 0 ,0
Exp/Cntr=0.3,0.1

Type RM Length L Ch R = 1 ,5565    ,491,491,491
BEGIN DESCRIPTION:
UNT 138 IN CACR 11.0
END DESCRIPTION:
XS GIS Cut Line= 4
      3713011.62     10692727.22      3712807.63     10692779.31
      3712699.13     10692905.17      3712590.87     10693255.93
#Sta/Elev= 30
    4716  379.24  4738.7  376.42  4751.2  375.97  4759.4  374.17    4792  371.48
  4800.6  369.53  4832.9  367.01  4841.9  364.94  4893.5   360.3  4922.9  356.26
  4940.4  355.16  4982.1  348.23  4996.4   347.2    5001  345.49  5003.8  344.99
    5007  345.49  5018.3  347.87  5032.5  348.34  5046.5  346.76  5053.4  347.97
  5067.7  348.35  5092.7  347.68  5170.9  351.57  5202.6  354.58  5208.8  355.94
  5265.4  360.68  5286.3  363.71  5349.9  370.25  5401.5  374.73  5459.8  377.39
#Mann= 3 ,-1 , 0
    4716     .12       0    5001     .07       0    5007     .12       0
Bank Sta=5001,5007
XS Rating Curve= 0 ,0
Exp/Cntr=0.3,0.1

Type RM Length L Ch R = 1 ,5074    ,470,470,470
BEGIN DESCRIPTION:
UNT 138 IN CACR 10.0
END DESCRIPTION:
XS GIS Cut Line= 3
       3712699.6     10692110.21      3712599.61     10692410.19
      3712299.62     10692660.18
#Sta/Elev= 30
    4673  372.54  4683.5  371.82  4704.6  366.85  4715.1  366.36  4736.2  363.35
  4767.8  357.66    4810  353.75  4820.6  351.54  4831.1  351.54  4904.9  345.01
  4968.1  344.87  4992.5  343.76  4993.4  340.95  4996.1  340.45  4999.4  340.95
  5002.9  343.12    5025  343.97  5095.3  345.32  5103.1  344.45  5109.6  345.68
  5117.4   344.5  5131.7  345.18  5138.3  344.08  5145.4  345.64  5159.1  345.88
  5166.9  347.54  5187.7  347.81  5237.2  353.12  5294.5  357.59  5379.7   369.4
#Mann= 3 ,-1 , 0
    4673     .12       0  4993.4     .07       0  4999.4     .12       0
Bank Sta=4993.4,4999.4
XS Rating Curve= 0 ,0
Exp/Cntr=0.3,0.1

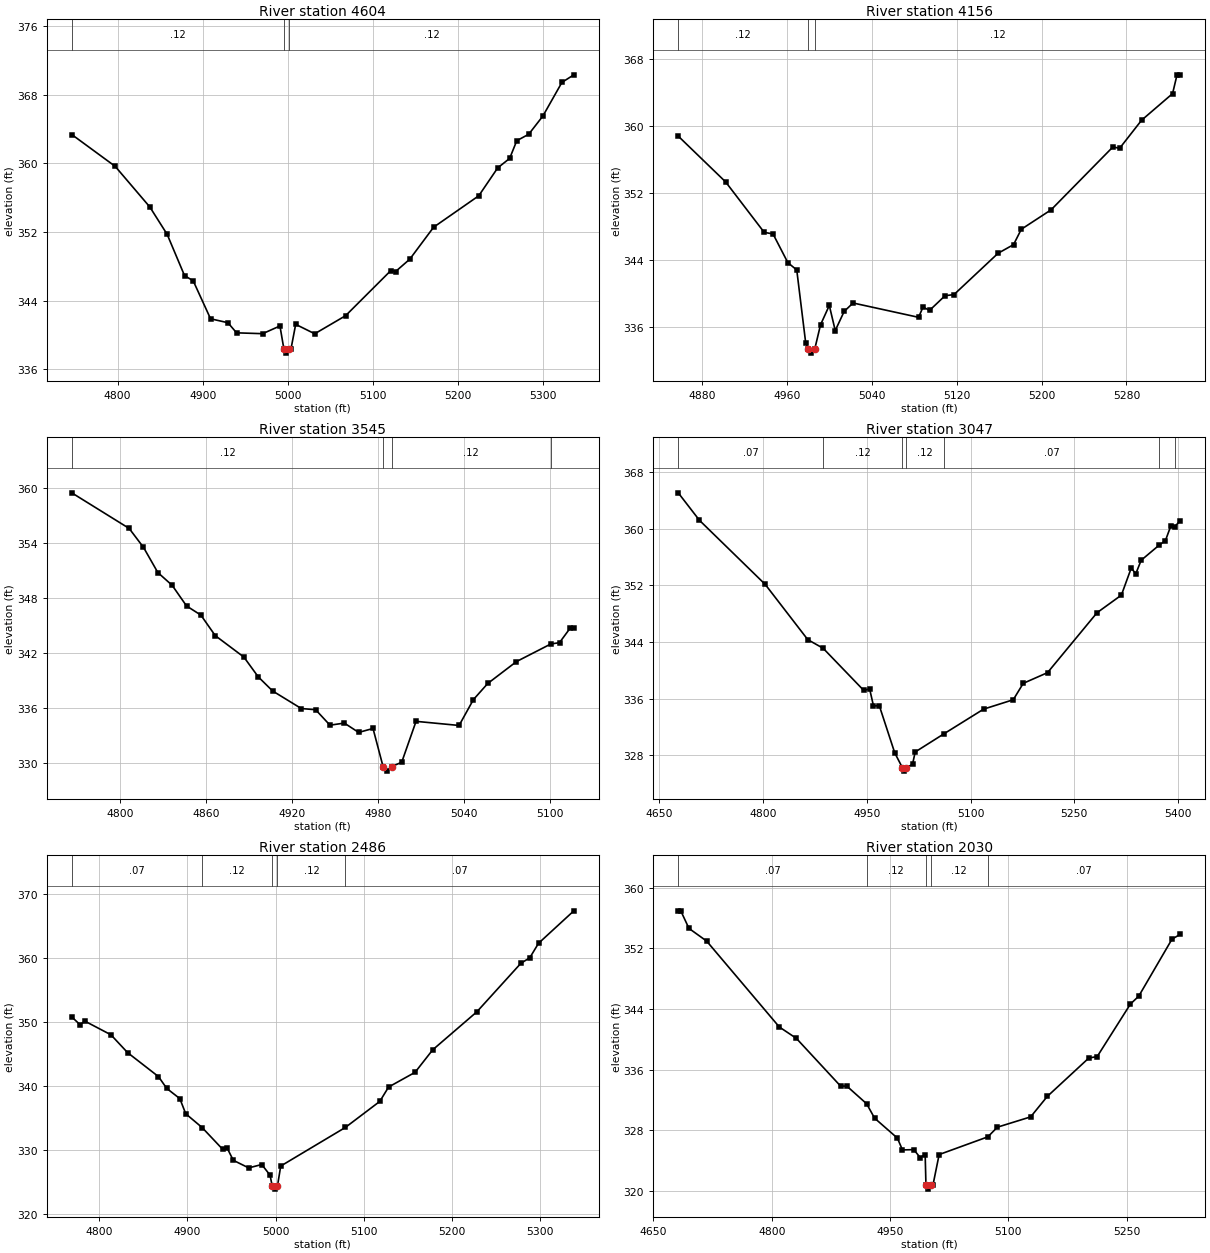
Type RM Length L Ch R = 1 ,4604    ,448,448,448
BEGIN DESCRIPTION:
UNT 138 IN CACR 9.0
END DESCRIPTION:
XS GIS Cut Line= 3
      3712299.61     10691910.18      3712249.61     10692160.19
       3712099.6     10692460.21
#Sta/Elev= 30
  4746.1  363.38  4797.1  359.67  4837.9  354.92  4858.3  351.72  4878.7  346.91
  4888.9   346.3  4909.3  341.87  4929.7  341.41  4939.9  340.23  4970.5  340.13
  4990.9  341.03  4995.5  338.36  4998.3  337.86  5001.5  338.36  5003.9  338.36
  5009.4  341.22  5031.8  340.12  5068.1  342.23  5121.2  347.49  5126.8  347.38
  5143.6  348.83  5171.6  352.56  5224.7  356.23    5247  359.49    5261  360.59
  5269.4  362.66  5283.4  363.41  5300.1  365.54  5322.5  369.47  5336.5  370.35
#Mann= 3 ,-1 , 0
  4746.1     .12       0  4995.5     .07       0  5001.5     .12       0
Bank Sta=4995.5,5001.5
XS Rating Curve= 0 ,0
Exp/Cntr=0.3,0.1

Type RM Length L Ch R = 1 ,4156    ,611,611,611
BEGIN DESCRIPTION:
UNT 138 IN CACR 8.0
END DESCRIPTION:
XS GIS Cut Line= 3
       3712149.6     10691760.19      3711949.61     10691860.19
      3711749.61     10692010.19
#Sta/Elev= 30
  4857.2  358.78  4901.9  353.32  4938.3   347.3  4946.6  347.12  4960.6  343.69
    4969  342.82  4977.4  334.15    4980   333.4  4982.7   332.9    4986   333.4
  4991.4  336.27  4999.7  338.59  5005.3  335.59  5013.7  337.87  5022.1  338.88
  5083.9  337.17  5088.1  338.39  5094.3     338  5108.9  339.75  5117.3  339.88
  5158.9  344.81  5173.5  345.84  5180.8  347.67  5208.9  349.99  5267.3   357.5
  5273.5  357.32  5294.3  360.68  5323.5  363.85  5327.7  366.09  5330.8  366.09
#Mann= 3 ,-1 , 0
  4857.2     .12       0    4980     .07       0    4986     .12       0
Bank Sta=4980,4986
XS Rating Curve= 0 ,0
Exp/Cntr=0.3,0.1

Type RM Length L Ch R = 1 ,3545    ,498,498,498
BEGIN DESCRIPTION:
UNT 138 IN CACR 7.0
END DESCRIPTION:
XS GIS Cut Line= 3
      3711649.61     10691360.19      3711649.61     10691610.19
      3711649.61     10691710.19
#Sta/Elev= 30
  4766.4  359.47  4806.4  355.58  4816.4  353.51  4826.4  350.76  4836.4  349.36
  4846.4  347.11  4856.4  346.11  4866.4  343.87  4886.4  341.52  4896.4  339.36
  4906.4  337.82  4926.4   335.9  4936.4  335.77  4946.4  334.08  4956.4  334.31
  4966.4  333.29  4976.4  333.72  4983.4  329.56  4986.2  329.06  4989.4  329.56
  4996.4  330.03  5006.4   334.5  5036.4  334.05  5046.4  336.88  5056.4  338.64
  5076.4  341.03  5100.3  342.95  5106.4   343.1  5113.9   344.7  5116.4   344.7
#Mann= 4 ,-1 , 0
  4766.4     .12       0  4983.4     .07       0  4989.4     .12       0
  5100.3     .07       0
Bank Sta=4983.4,4989.4
XS Rating Curve= 0 ,0
Exp/Cntr=0.3,0.1

Type RM Length L Ch R = 1 ,3047    ,561,561,561
BEGIN DESCRIPTION:
UNT 138 IN CACR 6.0
END DESCRIPTION:
XS GIS Cut Line= 3
      3711399.61      10691110.2      3711249.61     10691410.19
      3710999.62     10691710.18
#Sta/Elev= 30
  4677.3  365.11    4708  361.22  4803.1  352.15  4864.6  344.34  4886.8  343.12
  4945.6  337.15    4954  337.38  4959.6  334.96    4968     335  4990.3  328.33
  5001.3  326.24  5004.1  325.74  5007.3  326.24    5016  326.69  5019.9  328.45
  5061.8  331.04  5118.8  334.51  5161.7  335.84  5176.1  338.16  5211.2  339.67
  5282.8  348.15    5318  350.64  5332.3  354.48  5338.8  353.65  5346.6  355.57
  5372.5   357.7  5381.7  358.36  5389.5  360.43  5394.9   360.3  5403.2  361.18
#Mann= 7 ,-1 , 0
  4677.3     .07       0  4886.8     .12       0  5001.3     .07       0
  5007.3     .12       0  5061.8     .07       0  5372.5     .16       0
  5394.9     .05       0
Bank Sta=5001.3,5007.3
XS Rating Curve= 0 ,0
Exp/Cntr=0.3,0.1

Type RM Length L Ch R = 1 ,2486    ,456,456,456
BEGIN DESCRIPTION:
UNT 138 IN CACR 5.0
END DESCRIPTION:
XS GIS Cut Line= 3
       3710899.6      10691210.2      3710799.61     10691460.19
      3710799.61     10691760.15
#Sta/Elev= 30
  4768.9  350.84  4778.3  349.63  4783.7  350.19  4813.3  348.05  4832.2  345.26
  4867.2  341.51  4876.6  339.66  4891.4  338.07  4898.1   335.7  4916.7  333.54
  4939.9  330.15  4945.2   330.3    4952  328.42  4969.5  327.23  4984.3  327.76
  4993.7  326.09  4996.1  324.41  4998.8  323.91  5002.1  324.41  5005.8  327.52
  5079.1  333.56  5118.1  337.63  5128.1  339.88  5158.1  342.18  5178.1   345.7
  5228.1  351.64  5278.1  359.24  5288.1  360.09  5298.1  362.37  5338.1  367.44
#Mann= 5 ,-1 , 0
  4768.9     .07       0  4916.7     .12       0  4996.1     .07       0
  5002.1     .12       0  5079.1     .07       0
Bank Sta=4996.1,5002.1
XS Rating Curve= 0 ,0
Exp/Cntr=0.3,0.1

Type RM Length L Ch R = 1 ,2030    ,468,468,468
BEGIN DESCRIPTION:
UNT 138 IN CACR 4.0
END DESCRIPTION:
XS GIS Cut Line= 3
      3710649.63     10691010.17      3710449.61     10691260.19
      3710349.61     10691560.18
#Sta/Elev= 30
  4681.5  356.96  4684.7  356.96  4695.1  354.64  4717.5  352.97  4809.6  341.64
  4831.2  340.14  4887.2  333.85  4895.2  333.84  4920.3  331.51  4930.4  329.61
  4959.3  326.98  4965.7  325.42  4980.1  325.46  4988.1  324.42  4994.5  324.79
  4995.5  320.75  4998.2  320.25  5001.5  320.75  5004.3  320.75  5012.2  324.81
    5074  327.15    5086  328.42  5128.2  329.78  5149.3  332.48    5202  337.55
  5212.5  337.73  5254.7  344.67  5265.2   345.7  5307.4  353.23  5317.9  353.86
#Mann= 5 ,-1 , 0
  4681.5     .07       0  4920.3     .12       0  4995.5     .07       0
  5001.5     .12       0    5074     .07       0
Bank Sta=4995.5,5001.5
XS Rating Curve= 0 ,0
Exp/Cntr=0.3,0.1

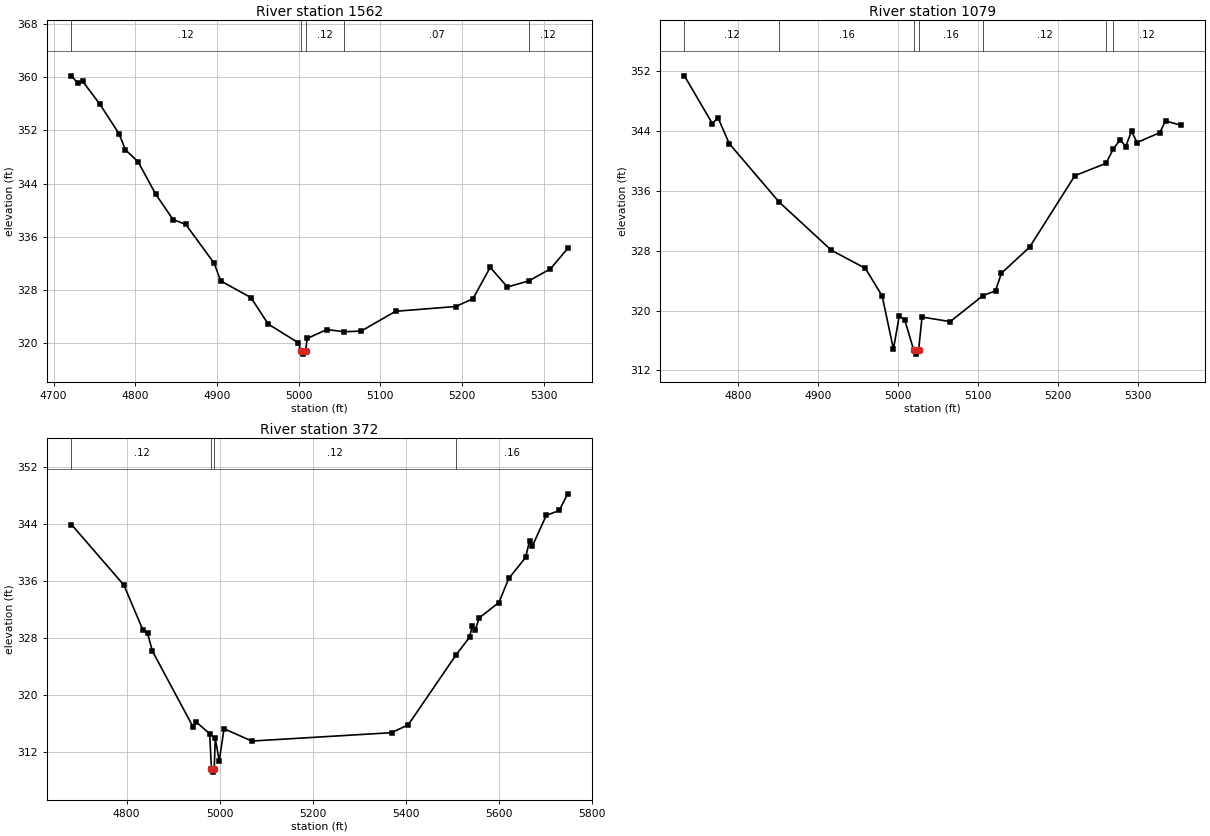
Type RM Length L Ch R = 1 ,1562    ,483,483,483
BEGIN DESCRIPTION:
UNT 138 IN CACR 3.0
END DESCRIPTION:
XS GIS Cut Line= 3
      3710299.62     10690810.17      3710149.61     10691060.19
      3710049.61     10691360.19
#Sta/Elev= 30
  4721.8   360.2  4729.6  359.06  4735.4  359.39  4756.8   355.9  4780.1  351.48
  4787.9  349.08  4803.5  347.26  4824.8  342.44  4846.2   338.6  4861.8  337.86
  4896.7     332  4904.5  329.37  4941.5  326.87  4962.8  322.88  4999.8  320.06
  5002.6  318.86  5005.3  318.36  5008.6  318.86  5010.5  320.71  5034.4  322.05
  5055.9  321.73  5076.6  321.82  5118.8   324.8  5192.6  325.52  5213.6  326.69
  5234.7   331.4  5255.8  328.46    5282  329.37  5308.5  331.18  5329.6  334.25
#Mann= 5 ,-1 , 0
  4721.8     .12       0  5002.6     .07       0  5008.6     .12       0
  5055.9     .07       0    5282     .12       0
Bank Sta=5002.6,5008.6
XS Rating Curve= 0 ,0
Exp/Cntr=0.3,0.1

Type RM Length L Ch R = 1 ,1079    ,707,707,707
BEGIN DESCRIPTION:
UNT 138 IN CACR 2.0
END DESCRIPTION:
XS GIS Cut Line= 2
      3710099.32     10690600.47      3709648.23     10691025.53
#Sta/Elev= 30
  4732.9  351.41  4767.9     345  4774.8  345.82  4788.9  342.34  4851.2  334.53
  4916.4  328.08  4958.9  325.66  4979.9  321.96    4994  314.86  5001.3   319.3
  5008.2  318.74  5019.4  314.68  5022.1  314.18  5025.4  314.68  5029.7  319.14
  5064.9  318.53  5105.8  322.01  5121.5  322.65  5128.8     325    5164  328.48
  5220.6  338.05  5259.6  339.71  5268.4  341.59  5277.3  342.87  5284.1  341.95
  5291.4     344  5298.3  342.49  5326.6   343.8  5333.9  345.38  5352.7  344.81
#Mann= 7 ,-1 , 0
  4732.9     .12       0  4851.2     .16       0  5019.4     .07       0
  5025.4     .16       0  5105.8     .12       0  5259.6     .16       0
  5268.4     .12       0
Bank Sta=5019.4,5025.4
XS Rating Curve= 0 ,0
Exp/Cntr=0.3,0.1

Type RM Length L Ch R = 1 ,372     ,0,0,0
BEGIN DESCRIPTION:
UNT 138 IN CACR 1.0
END DESCRIPTION:
XS GIS Cut Line= 4
      3710129.66     10690331.39       3709873.6     10690274.97
      3709747.74     10690305.35      3709370.14     10690865.23
#Sta/Elev= 30
  4681.4  343.88  4794.1  335.41  4835.1  329.11  4844.9  328.68  4855.5  326.16
  4943.1  315.53  4948.7   316.3  4978.6   314.6  4982.4  309.73  4985.2  309.23
  4988.4  309.73  4990.6     314  4999.1  310.77  5009.4   315.3  5069.2  313.58
  5369.6  314.75  5405.6  315.85  5508.4  325.64  5537.3  328.09  5543.5  329.74
  5549.5  329.14  5558.5  330.83  5600.5  332.97  5621.7  336.33  5657.9  339.27
  5666.4   341.6  5672.4  340.86  5702.4  345.16  5730.3  345.85  5748.4  348.18
#Mann= 4 ,-1 , 0
  4681.4     .12       0  4982.4     .07       0  4988.4     .12       0
  5508.4     .16       0
Bank Sta=4982.4,4988.4
XS Rating Curve= 0 ,0
Exp/Cntr=0.3,0.1

Chan Stop Cuts=-1
Use User Specified Reach Order=0
Composite Channel Slope=5