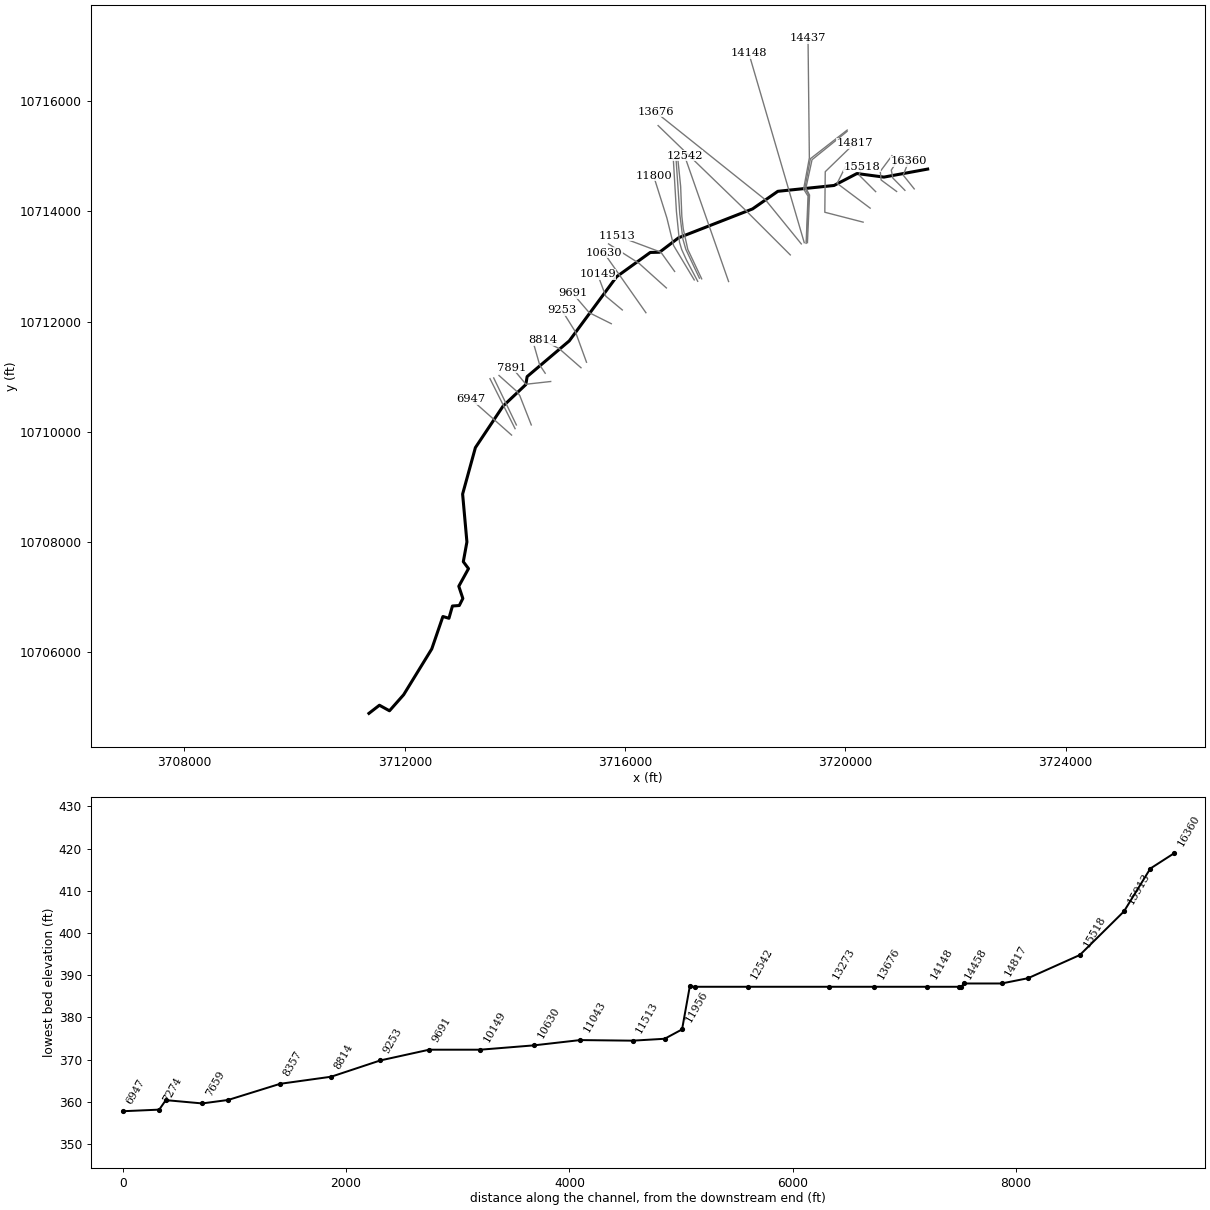
--- UNT 139 IN CACR.prj (project) ---

Proj Title=UNT 139 IN CACR Base Level Engineering
Current Plan=p01
Default Exp/Contr=0.3,0.1
English Units
Geom File=g01
Flow File=f01
Plan File=p01
Y Axis Title=Elevation
X Axis Title(PF)=Main Channel Distance
X Axis Title(XS)=Station
BEGIN DESCRIPTION:
UNT 139 IN CACR
END DESCRIPTION:
DSS Export Rating Curves= 0
DSS Export Rating Curve Sorted= 0
DSS Export Volume Flow Curves= 0
DXF OffsetX= 0
DXF OffsetY= 0
DXF ScaleX= 1
DXF ScaleY= 10

--- UNT 139 IN CACR.p01 (plan) ---

Plan Title=Multiple Run
Short Identifier=Multiple
Geom File=g01
Flow File=f01
Subcritical Flow
K Sum by GR= 0
Std Step Tol= 0.01
Critical Tol= 0.01
Num of Std Step Trials= 20
Max Error Tol= 0.3
Flow Tol Ratio= 0.001
Split Flow NTrial= 30
Split Flow Tol= 0.02
Split Flow Ratio= 0.02
Log Output Level= 0
Friction Slope Method= 1
Unsteady Friction Slope Method= 2
Unsteady Bridges Friction Slope Method= 1
Parabolic Critical Depth
Global Vel Dist=  1 , 1 , 1
Global Log Level= 0
CheckData=True
Encroach Param= -1, 0, 0, 0
BEGIN DESCRIPTION:
Multiple Run
END DESCRIPTION:

--- UNT 139 IN CACR.f01 (steady flow) ---

Flow Title=Multiple
Program Version=4.10
Number of Profiles= 7
Profile Names=10-year,25-year,50-year,1pct_min,100-year,1pct_plu,500-year
River Rch & RM=UNT 139 IN CACR,Reach-1         ,16360
     691     959    1187    1080    1460    1975    2220
River Rch & RM=UNT 139 IN CACR,Reach-1         ,13676
    1001    1407    1755    1606    2173    2938    3346
River Rch & RM=UNT 139 IN CACR,Reach-1         ,7659
    1662    2378    3000    2772    3749    5070    5886
Boundary for River Rch & Prof#=UNT 139 IN CACR,Reach-1         , 1
Up Type= 0
Dn Type= 3
Dn Slope=0.01409
Boundary for River Rch & Prof#=UNT 139 IN CACR,Reach-1         , 2
Up Type= 0
Dn Type= 3
Dn Slope=0.01409
Boundary for River Rch & Prof#=UNT 139 IN CACR,Reach-1         , 3
Up Type= 0
Dn Type= 3
Dn Slope=0.01409
Boundary for River Rch & Prof#=UNT 139 IN CACR,Reach-1         , 4
Up Type= 0
Dn Type= 3
Dn Slope=0.01409
Boundary for River Rch & Prof#=UNT 139 IN CACR,Reach-1         , 5
Up Type= 0
Dn Type= 3
Dn Slope=0.01409
Boundary for River Rch & Prof#=UNT 139 IN CACR,Reach-1         , 6
Up Type= 0
Dn Type= 3
Dn Slope=0.01409
Boundary for River Rch & Prof#=UNT 139 IN CACR,Reach-1         , 7
Up Type= 0
Dn Type= 3
Dn Slope=0.01409
DSS Import GetInterval= 0
DSS Import GetPeak= 0
DSS Import FillOption= 0

--- UNT 139 IN CACR.g01 (geometry) ---

Geom Title=Existing Conditions
Program Version=4.10

River Reach=UNT 139 IN CACR ,Reach-1
Reach XY= 30
      3721493.75       10714770.      3720699.25       10714624.
      3720209.75       10714689.      3719793.75       10714472.
       3718773.5       10714366.      3718314.25       10714046.
       3716970.5       10713521.      3716625.25       10713259.
        3716457.       10713255.        3715845.       10712813.
       3714986.5       10711648.      3714221.25       10710999.
        3714198.       10710855.      3713784.25       10710463.
      3713282.25       10709709.      3713050.25       10708865.
      3713128.25       10707995.      3713062.75       10707636.
        3713157.       10707510.      3712980.75       10707190.
      3713054.25       10706968.      3712989.75       10706840.
       3712865.5       10706831.        3712802.       10706608.
        3712692.       10706640.        3712490.       10706051.
      3711979.75       10705219.      3711722.25       10704927.
       3711539.5       10705028.        3711349.       10704880.

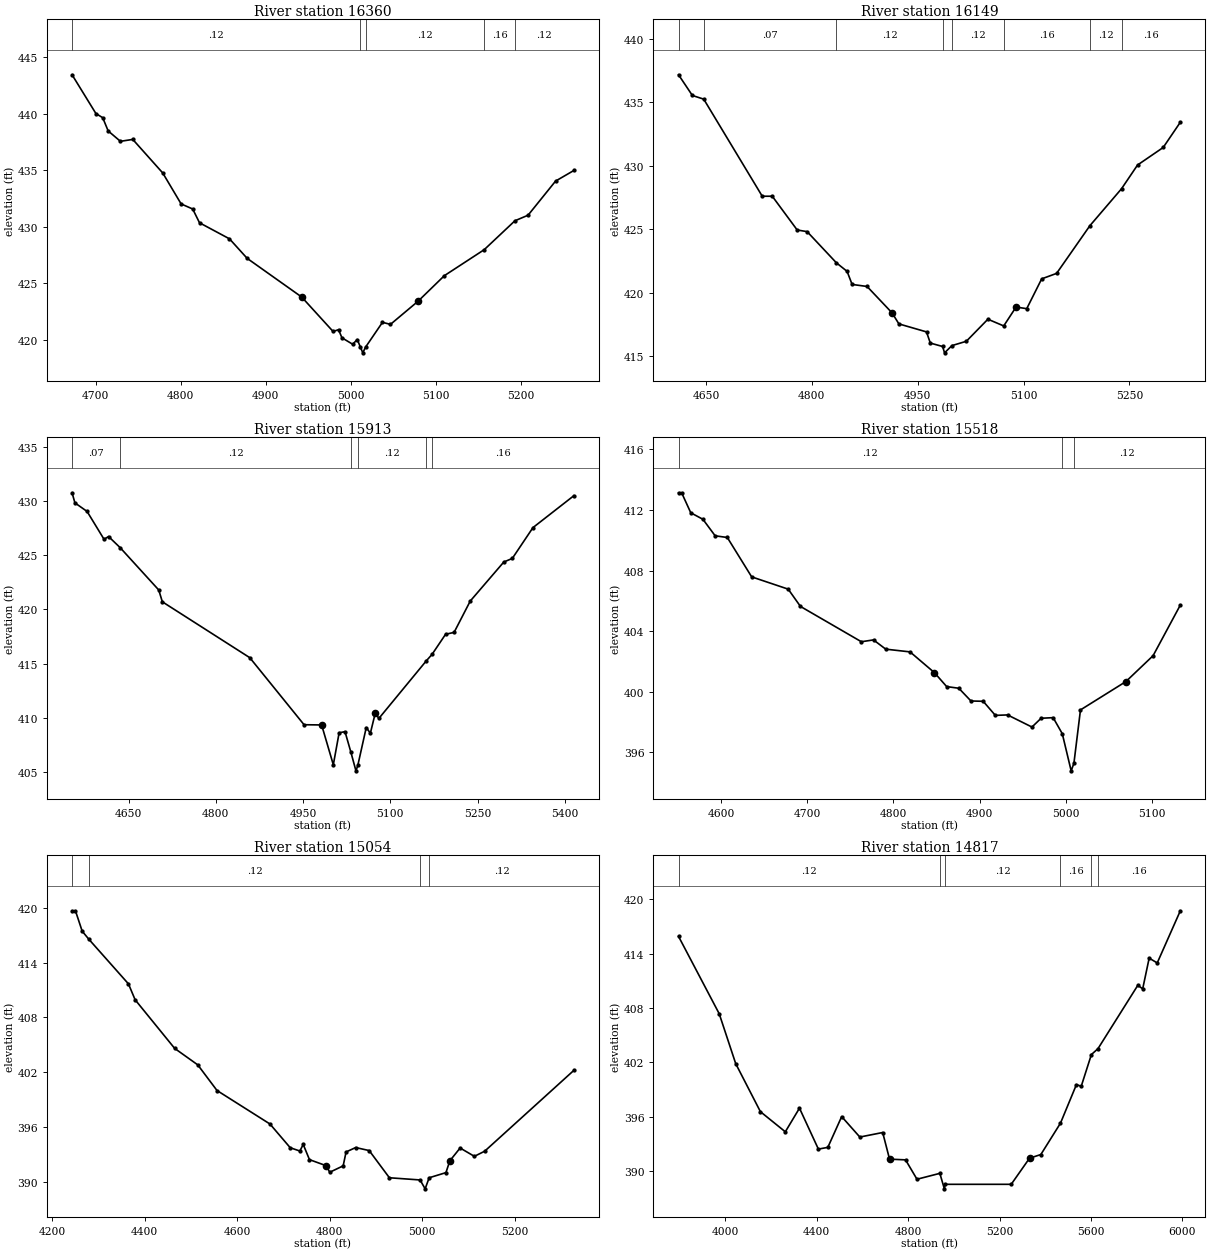
Type RM Length L Ch R = 1 ,16360   ,211,211,211
BEGIN DESCRIPTION:
UNT 139 IN CACR 36.0
END DESCRIPTION:
XS GIS Cut Line= 3
      3721249.62     10714410.18      3721049.61     10714660.19
       3721149.6     10714910.16
#Sta/Elev= 30
  4672.4  443.46  4700.4  440.03  4708.4  439.66  4714.8  438.49  4729.2  437.57
  4743.7  437.74  4778.9  434.77  4800.5  432.03  4814.1  431.58  4822.1  430.36
  4857.3  428.94  4878.1  427.21  4942.1  423.79    4979  420.74  4985.4   420.9
  4989.4  420.18    5002  419.61  5007.4  420.03  5011.1  419.35  5013.9  418.85
  5017.1  419.35    5037  421.55  5046.4  421.37  5078.7  423.41  5109.7  425.68
  5156.5  427.98  5192.6  430.54    5208  431.03  5240.3  434.05  5261.8  434.99
#Mann= 5 ,-1 , 0
  4672.4     .12       0  5011.1     .07       0  5017.1     .12       0
  5156.5     .16       0  5192.6     .12       0
Bank Sta=4942.1,5078.7
XS Rating Curve= 0 ,0
Exp/Cntr=0.3,0.1

Type RM Length L Ch R = 1 ,16149   ,236,236,236
BEGIN DESCRIPTION:
Mapping XS 20726c73
END DESCRIPTION:
XS GIS Cut Line= 4
      3721080.91     10714383.79      3720862.13     10714606.48
      3720833.49     10714751.01      3720970.21     10714961.96
#Sta/Elev= 30
  4611.2  437.17  4630.8  435.54  4646.9  435.25  4729.8   427.6    4744   427.6
  4779.3  424.94  4793.4  424.81  4834.9  422.35    4850  421.68  4857.1  420.65
  4878.3  420.49  4913.7  418.41  4923.4  417.54  4962.5  416.91  4967.9  416.03
  4985.3  415.76  4988.1  415.26  4998.5  415.83  5018.9  416.17  5049.5  417.91
  5071.9  417.38  5089.4  418.87  5104.5  418.74  5125.7  421.09  5146.8  421.52
    5194  425.28  5238.8  428.19  5261.5  430.06  5297.8  431.44  5322.1  433.43
#Mann= 8 ,-1 , 0
  4611.2     .12       0  4646.9     .07       0  4834.9     .12       0
  4985.3     .07       0  4998.5     .12       0  5071.9     .16       0
    5194     .12       0  5238.8     .16       0
Bank Sta=4913.7,5089.4
XS Rating Curve= 0 ,0
Exp/Cntr=0.3,0.1

Type RM Length L Ch R = 1 ,15913   ,395,395,395
BEGIN DESCRIPTION:
UNT 139 IN CACR 35.0
END DESCRIPTION:
XS GIS Cut Line= 4
      3720930.02      10714363.3      3720648.76     10714571.65
      3720633.13      10714727.9      3720845.63     10715012.96
#Sta/Elev= 30
  4552.9  430.74  4557.8  429.81  4578.7  429.02  4607.9  426.45  4615.6  426.71
  4635.6  425.68  4701.9  421.78  4708.1  420.69  4858.4  415.54  4951.7  409.36
  4981.9  409.34    5002  405.67    5012  408.62  5022.1  408.72  5032.1  406.85
  5040.9  405.11  5044.1  405.61  5058.6   409.1  5065.7  408.58  5074.1  410.43
  5080.3  409.94  5161.7  415.24  5171.8  415.85    5195   417.7  5209.6  417.87
  5237.4  420.76  5295.1  424.36  5309.7  424.69  5345.2  427.53  5415.5  430.47
#Mann= 6 ,-1 , 0
  4552.9     .07       0  4635.6     .12       0  5032.1     .07       0
  5044.1     .12       0  5161.7     .05       0  5171.8     .16       0
Bank Sta=4981.9,5074.1
XS Rating Curve= 0 ,0
Exp/Cntr=0.3,0.1

Type RM Length L Ch R = 1 ,15518   ,464,464,464
BEGIN DESCRIPTION:
UNT 139 IN CACR 34.0
END DESCRIPTION:
XS GIS Cut Line= 3
      3720549.63     10714360.16      3720249.61     10714660.19
       3720299.6     10714810.17
#Sta/Elev= 30
  4550.6  413.13  4554.2  413.13  4564.8  411.81  4578.9  411.38  4593.1  410.29
  4607.2  410.18  4635.5  407.58  4677.9  406.77  4692.1  405.63  4762.8   403.3
  4776.9  403.42  4791.1  402.81  4819.3  402.63  4847.6  401.26  4861.8  400.34
  4875.9  400.23    4890  399.39  4904.2  399.37  4918.3  398.44  4932.5  398.47
  4960.8  397.67  4971.4  398.25  4985.4  398.29    4996  397.23  5006.3  394.78
  5009.5  395.28  5017.1   398.8  5069.8  400.67  5101.4  402.38    5133  405.72
#Mann= 3 ,-1 , 0
  4550.6     .12       0    4996     .07       0  5009.5     .12       0
Bank Sta=4847.6,5069.8
XS Rating Curve= 0 ,0
Exp/Cntr=0.3,0.1

Type RM Length L Ch R = 1 ,15054   ,237,237,237
BEGIN DESCRIPTION:
UNT 139 IN CACR 33.0
END DESCRIPTION:
XS GIS Cut Line= 3
       3720449.6     10714060.19      3719849.61     10714510.19
      3719999.61     10714810.19
#Sta/Elev= 30
  4242.9  419.61  4250.2  419.65  4264.8  417.42  4279.2  416.54  4364.8  411.67
  4379.3  409.93  4464.8  404.62  4514.8  402.82  4556.4  400.02    4671  396.36
  4714.8  393.77  4735.6  393.41  4742.9  394.13  4756.4  392.47  4792.9   391.8
  4800.2  391.09  4829.3  391.79  4835.6  393.31  4856.4  393.79  4885.6  393.46
  4929.3  390.49  4995.7  390.25  5006.6  389.28  5015.3  390.49  5051.6  391.05
    5060  392.34  5082.3  393.74  5113.1  392.83  5135.4  393.39  5328.3  402.22
#Mann= 4 ,-1 , 0
  4242.9     .16       0  4279.2     .12       0  4995.7     .07       0
  5015.3     .12       0
Bank Sta=4792.9,5060
XS Rating Curve= 0 ,0
Exp/Cntr=0.3,0.1

Type RM Length L Ch R = 1 ,14817   ,338,338,338
BEGIN DESCRIPTION:
Mapping XS ea1581ba
END DESCRIPTION:
XS GIS Cut Line= 4
      3720321.81     10713805.68      3719626.46     10713985.38
      3719634.27     10714722.36      3720165.05     10715237.53
#Sta/Elev= 30
  3795.8  415.91  3973.7  407.37    4046  401.85    4154  396.55  4262.9  394.33
  4324.8  396.94  4407.5  392.42  4448.8  392.61  4509.4  396.01  4588.8  393.75
  4688.8  394.25  4718.8  391.31  4788.8  391.23  4838.8  389.09  4938.8  389.74
  4958.6  388.03  4961.8  388.53    5251  388.53    5331  391.41  5380.6  391.82
  5466.4  395.28  5536.2  399.54  5557.3  399.36  5601.7  402.86  5630.5  403.51
  5804.8  410.51  5826.1  410.12  5854.4  413.51  5889.7  412.98  5990.7  418.74
#Mann= 6 ,-1 , 0
  3795.8     .12       0  4938.8     .07       0  4961.8     .12       0
  5466.4     .16       0  5601.7     .12       0  5630.5     .16       0
Bank Sta=4718.8,5331
XS Rating Curve= 0 ,0
Exp/Cntr=0.3,0.1

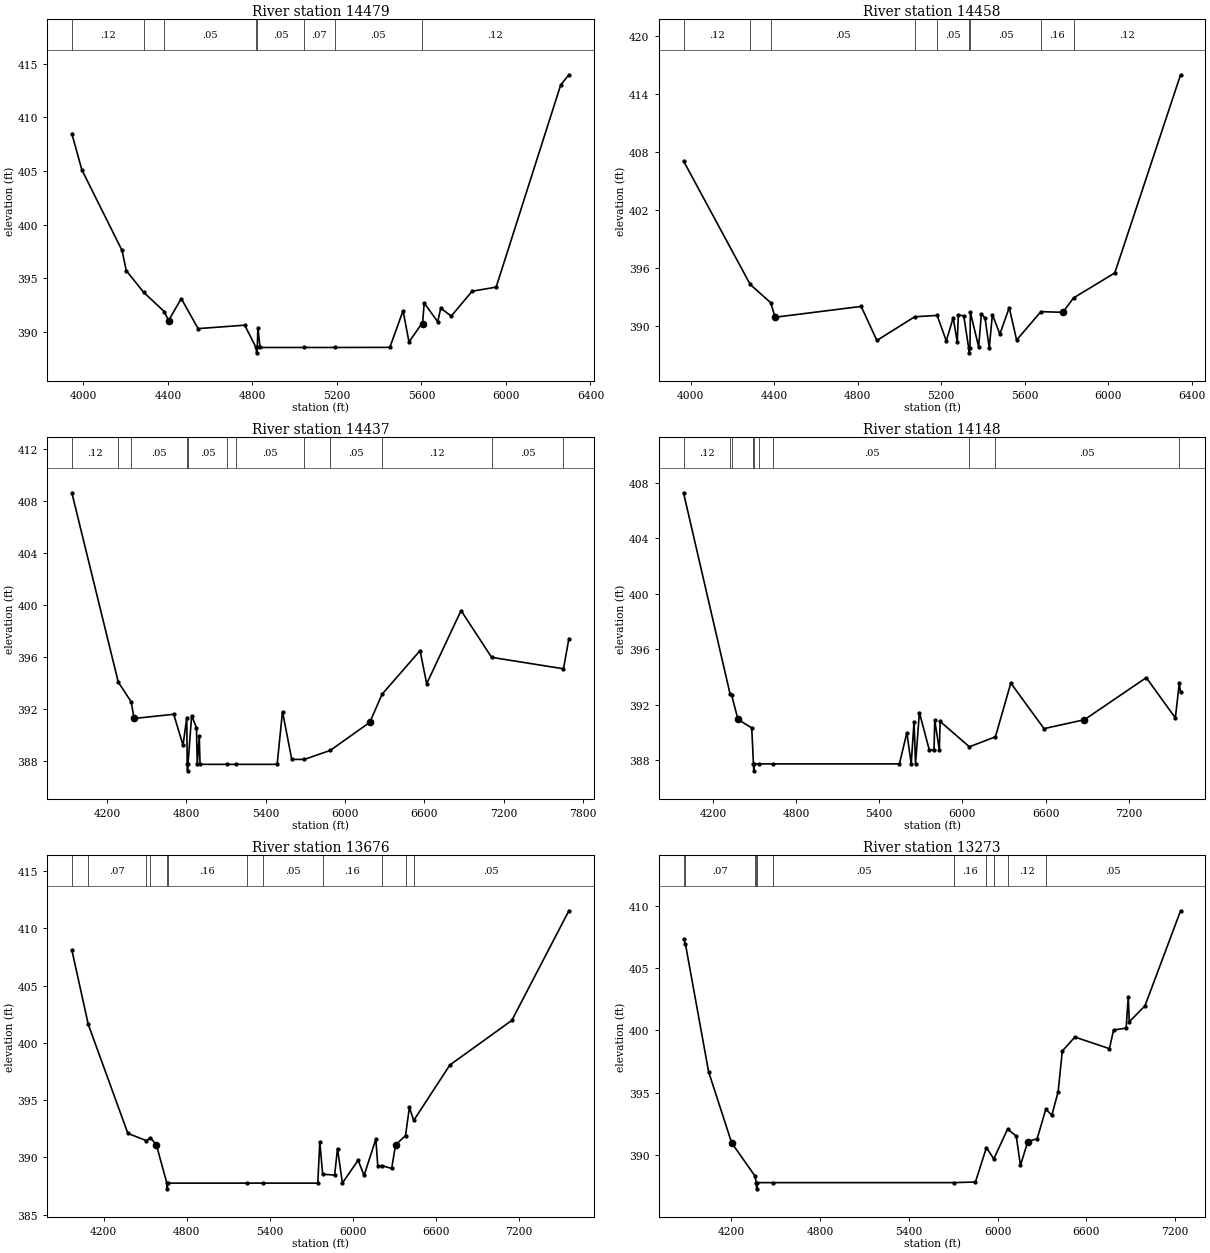
Type RM Length L Ch R = 1 ,14479   ,21,21,21
BEGIN DESCRIPTION:
UNT 139 IN CACR 32.0
END DESCRIPTION:
XS GIS Cut Line= 5
      3719311.08     10713432.73      3719349.28     10714297.34
       3719283.3     10714425.81      3719394.42      10714939.7
      3720029.87     10715453.62
#Sta/Elev= 30
  3944.9  408.48  3992.4   405.1  4182.6  397.58  4202.6   395.7  4284.4  393.69
  4382.7  391.87  4402.8  391.04  4462.9  393.09  4542.9  390.29  4763.2  390.61
  4816.9  388.53  4819.6  388.03  4822.9  388.53  4825.5  390.39    4836  388.53
  5041.9  388.53  5188.7  388.53  5450.3  388.54  5512.9  391.96    5541  389.04
  5601.8  390.77    5605  390.73  5612.9  392.68  5676.9  390.93  5691.3   392.2
  5740.9  391.46    5840  393.78  5953.5  394.16    6259  413.02  6297.8  413.97
#Mann= 8 ,-1 , 0
  3944.9     .12       0  4284.4     .16       0  4382.7     .05       0
  4816.9    .033       0  4822.9     .05       0  5041.9     .07       0
  5188.7     .05       0  5601.8     .12       0
Bank Sta=4402.8,5605
XS Rating Curve= 0 ,0
Exp/Cntr=0.3,0.1

Type RM Length L Ch R = 1 ,14458   ,21,21,21
BEGIN DESCRIPTION:
Mapping XS ed4e5562
END DESCRIPTION:
XS GIS Cut Line= 5
      3719295.24     10713452.05       3719334.3     10714298.42
      3719264.86     10714424.29      3719364.68     10714958.15
      3720033.08     10715478.98
#Sta/Elev= 30
  3965.9  407.09  4285.5  394.32  4383.8  392.43  4404.5  390.93    4817  392.05
  4892.4  388.53  5073.6  390.98  5181.1  391.12    5225  388.48    5258  390.88
  5277.6  388.35  5282.7  391.21  5308.8  391.04  5332.3  387.75  5335.1  387.25
  5338.3  387.75  5340.4  391.43    5380  387.87  5393.1  391.29  5410.6  390.83
  5430.9  387.75  5445.7  391.21  5481.8  389.19  5526.5  391.93  5561.8  388.57
  5678.2  391.51  5783.5  391.44  5834.7  392.93  6032.3  395.51  6347.4     416
#Mann= 9 ,-1 , 0
  3965.9     .12       0  4285.5     .16       0  4383.8     .05       0
  5073.6     .07       0  5181.1     .05       0  5332.3    .033       0
  5338.3     .05       0  5678.2     .16       0  5834.7     .12       0
Bank Sta=4404.5,5783.5
XS Rating Curve= 0 ,0
Exp/Cntr=0.3,0.1

Type RM Length L Ch R = 1 ,14437   ,289,289,289
BEGIN DESCRIPTION:
Mapping XS 7a2de26a
END DESCRIPTION:
XS GIS Cut Line= 5
      3719286.85     10713420.19      3719321.57     10714277.84
      3719241.71     10714406.32      3719345.88     10714972.29
      3719321.58     10717145.55
#Sta/Elev= 30
  3933.3  408.64  4284.3  394.08  4382.6  392.55  4403.7  391.28  4703.9   391.6
    4774  389.22  4802.6  391.35  4805.5  387.75  4808.2  387.25  4811.5  387.75
  4839.2  391.49  4875.8  390.57  4881.7  387.75    4897  389.91  4902.9  387.75
  5105.7  387.75  5172.5  387.75  5485.8  387.75  5526.3  391.81  5596.3  388.13
  5691.2  388.13  5887.2  388.82  6186.3  390.98  6279.2  393.14  6566.4   396.5
  6616.4  393.95  6876.4  399.58  7107.6  395.98  7651.1   395.1  7691.8  397.42
#Mann= 12 ,-1 , 0
  3933.3     .12       0  4284.3     .16       0  4382.6     .05       0
  4805.5    .033       0  4811.5     .05       0  5105.7     .07       0
  5172.5     .05       0  5691.2     .16       0  5887.2     .05       0
  6279.2     .12       0  7107.6     .05       0  7651.1      .1       0
Bank Sta=4403.7,6186.3
XS Rating Curve= 0 ,0
Exp/Cntr=0.3,0.1

Type RM Length L Ch R = 1 ,14148   ,472,472,472
BEGIN DESCRIPTION:
Mapping XS ca49080d
END DESCRIPTION:
XS GIS Cut Line= 2
      3719252.85     10713432.82      3718246.19     10716876.29
#Sta/Elev= 30
  3986.8  407.27  4323.7  392.75  4333.2  392.74    4380  390.95  4479.2  390.34
  4491.6  387.75  4494.3  387.25  4497.6  387.75  4535.2  387.75  4636.2  387.75
  5545.1  387.75  5598.9     390  5630.2  387.75  5650.7  390.78  5661.4  387.75
  5689.3  391.45  5761.4  388.73  5794.9  388.78  5800.1  390.89  5833.5  388.74
  5838.8  390.81  6050.2  388.98  6238.1   389.7  6349.1  393.57  6588.7  390.29
  6880.4  390.93  7326.9  393.96  7536.8  391.06  7565.1  393.56  7574.4  392.93
#Mann= 10 ,-1 , 0
  3986.8     .12       0  4323.7     .07       0  4333.2     .05       0
  4491.6    .033       0  4497.6     .05       0  4535.2     .16       0
  4636.2     .05       0  6050.2     .16       0  6238.1     .05       0
  7565.1     .08       0
Bank Sta=4380,6880.4
XS Rating Curve= 0 ,0
Exp/Cntr=0.3,0.1

Type RM Length L Ch R = 1 ,13676   ,403,403,403
BEGIN DESCRIPTION:
UNT 139 IN CACR 30.0
END DESCRIPTION:
XS GIS Cut Line= 3
       3719199.6      10713410.2      3718549.61     10714210.19
      3716549.62     10715810.18
#Sta/Elev= 30
  3969.4  408.11  4088.1  401.61  4374.5  392.09  4507.6  391.46  4537.6  391.71
  4580.7  391.08    4656  387.75  4658.7  387.25    4662  387.75  5234.5  387.75
  5352.4  387.75  5746.9  387.75  5761.3  391.35  5782.1  388.53  5868.6  388.45
  5889.4  390.77  5924.6  387.75  6038.3  389.75  6081.5  388.42  6166.3  391.59
  6180.7  389.22    6209  389.28  6280.8  389.03  6308.8  391.08    6381   391.9
  6408.8  394.36  6440.1  393.22    6701  398.06  7149.2  401.96  7561.4  411.53
#Mann= 12 ,-1 , 0
  3969.4     .12       0  4088.1     .07       0  4507.6     .12       0
  4537.6     .16       0    4656    .033       0    4662     .16       0
  5234.5     .07       0  5352.4     .05       0  5782.1     .16       0
    6209     .12       0    6381     .16       0  6440.1     .05       0
Bank Sta=4580.7,6308.8
XS Rating Curve= 0 ,0
Exp/Cntr=0.3,0.1

Type RM Length L Ch R = 1 ,13273   ,731,731,731
BEGIN DESCRIPTION:
UNT 139 IN CACR 29.0
END DESCRIPTION:
XS GIS Cut Line= 3
      3718999.58     10713210.22      3718199.61     10714010.19
      3716599.61     10715560.19
#Sta/Elev= 30
  3877.8  407.35  3890.5  406.98  4047.5  396.67    4203  390.96  4358.5  388.32
  4369.7  387.75  4372.5  387.25  4375.7  387.75  4484.5  387.75  5703.6  387.75
  5850.7   387.8  5924.7  390.57  5974.6  389.66  6067.9  392.06  6126.4   391.5
  6154.7  389.14  6204.4  391.05  6267.9  391.29    6326  393.66    6367  393.18
  6409.4  395.06  6437.7  398.35  6522.6  399.47  6755.9  398.54  6784.2  400.04
  6869.1  400.19  6883.2  402.72  6890.2   400.7  6996.4  401.99  7236.8  409.64
#Mann= 11 ,-1 , 0
  3877.8     .12       0  3890.5     .07       0  4358.5     .16       0
  4369.7    .033       0  4375.7     .16       0  4484.5     .05       0
  5703.6     .16       0  5924.7     .12       0  5974.6     .16       0
  6067.9     .12       0    6326     .05       0
Bank Sta=4203,6204.4
XS Rating Curve= 0 ,0
Exp/Cntr=0.3,0.1

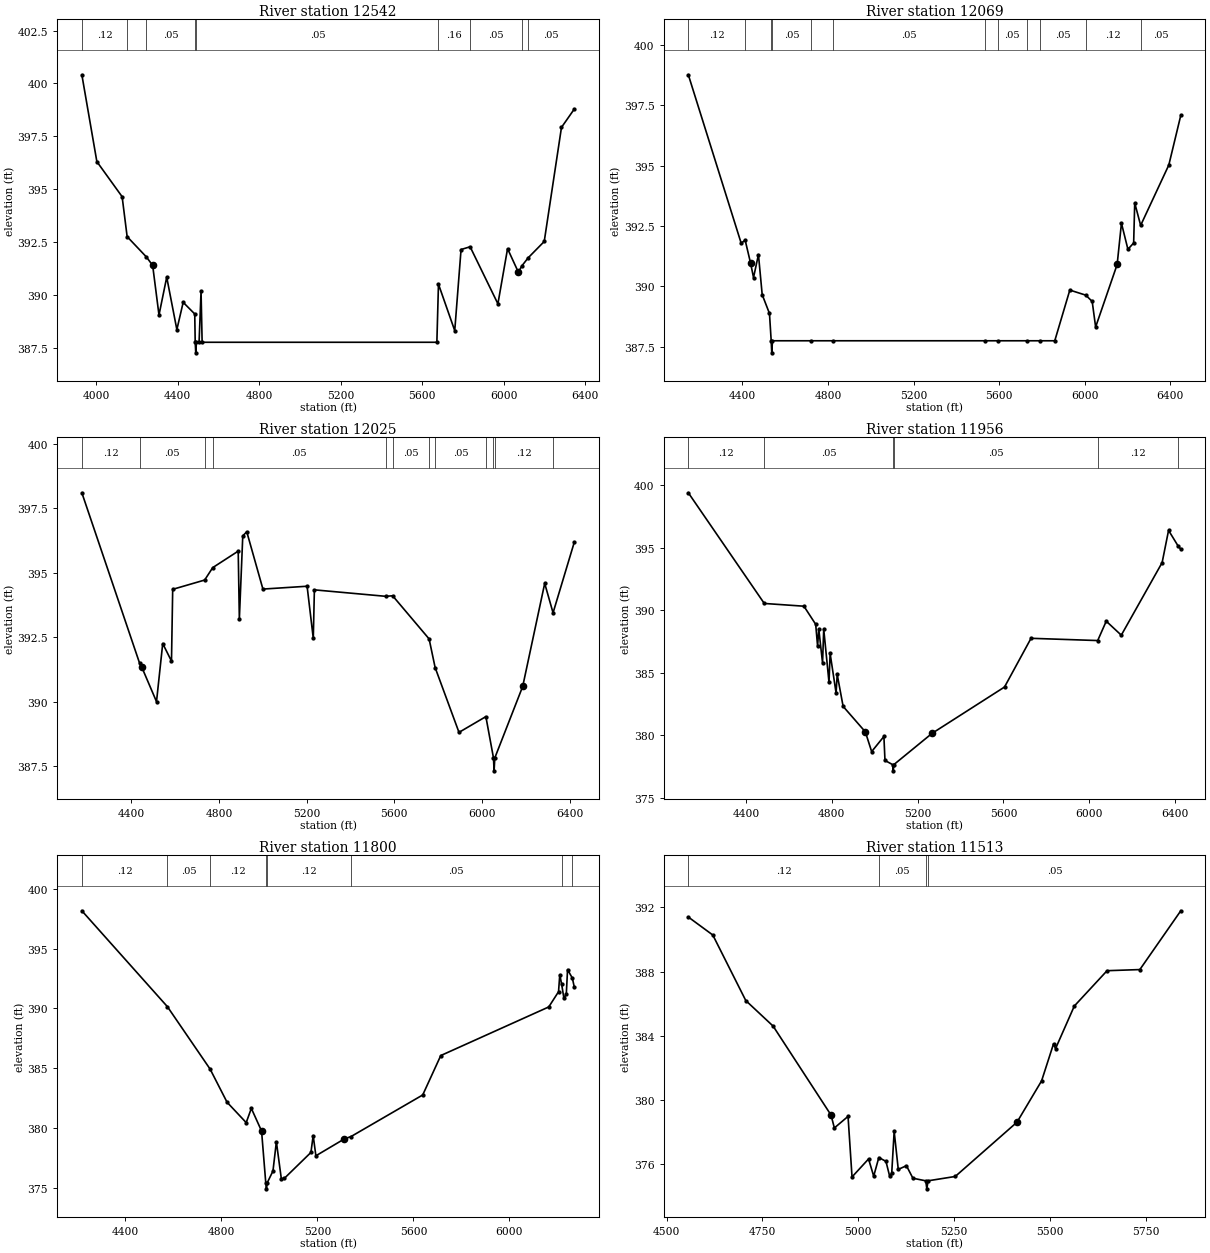
Type RM Length L Ch R = 1 ,12542   ,473,473,473
BEGIN DESCRIPTION:
UNT 139 IN CACR 28.0
END DESCRIPTION:
XS GIS Cut Line= 2
      3717879.36     10712726.78      3717080.76     10715009.73
#Sta/Elev= 30
  3928.8  400.41  4002.5   396.3  4126.6  394.64  4151.2  392.75  4245.6  391.79
  4276.5  391.39  4307.6  389.04  4345.6  390.83  4395.4  388.35  4426.4  389.64
  4483.2  389.09  4485.5  387.75  4488.2  387.25  4491.5  387.75  4504.5  387.75
  4514.2  390.16  4519.5  387.75  5672.3  387.75  5680.2   390.5  5760.1   388.3
  5791.1  392.14  5835.6  392.27  5972.1  389.57  6019.5  392.18  6072.4  391.07
  6090.1  391.37    6121  391.75  6199.6  392.52  6284.3  397.92  6347.4  398.79
#Mann= 9 ,-1 , 0
  3928.8     .12       0  4151.2      .1       0  4245.6     .05       0
  4485.5    .033       0  4491.5     .05       0  5680.2     .16       0
  5835.6     .05       0  6090.1     .12       0    6121     .05       0
Bank Sta=4276.5,6072.4
XS Rating Curve= 0 ,0
Exp/Cntr=0.3,0.1

Type RM Length L Ch R = 1 ,12069   ,44,44,44
BEGIN DESCRIPTION:
UNT 139 IN CACR 27.0
END DESCRIPTION:
XS GIS Cut Line= 6
      3717390.66     10712775.77      3717138.92     10713309.64
      3717056.45      10713682.9      3717030.41     10713912.94
      3717008.71     10714455.47      3716952.36     10715005.94
#Sta/Elev= 30
  4147.9  398.77  4394.9  391.79  4413.4  391.92  4438.9  390.96  4452.5  390.37
  4475.5  391.32    4493  389.66    4527  388.88    4535  387.75  4537.7  387.25
    4541  387.75  4722.5  387.75  4822.9  387.75  5531.9  387.75  5594.8  387.75
    5728  387.75  5790.7  387.75  5859.7  387.75    5930  389.85  6004.5  389.64
  6034.5  389.38  6050.6  388.32  6151.1  390.91  6171.2  392.62  6201.4  391.54
  6228.2   391.8  6233.2  393.46  6260.9  392.53  6392.4  395.03  6448.4  397.09
#Mann= 12 ,-1 , 0
  4147.9     .12       0  4413.4     .05       0    4535     .03       0
    4541     .05       0  4722.5      .1       0  4822.9     .05       0
  5531.9      .1       0  5594.8     .05       0    5728      .1       0
  5790.7     .05       0  6004.5     .12       0  6260.9     .05       0
Bank Sta=4438.9,6151.1
XS Rating Curve= 0 ,0
Exp/Cntr=0.3,0.1

Type RM Length L Ch R = 1 ,12025   ,69,69,69
BEGIN DESCRIPTION:
Mapping XS f0de02d5
END DESCRIPTION:
XS GIS Cut Line= 6
      3717349.85     10712787.51      3717102.46     10713312.68
      3717050.38     10713494.97      3717028.67     10713668.58
      3716993.95     10713946.36       3716924.6       10714965.
#Sta/Elev= 30
  4174.9   398.1  4438.6  391.49    4447  391.37  4515.4  390.01  4543.7  392.26
  4583.7  391.58  4589.2  394.36    4735  394.72  4771.6   395.2    4888  395.84
  4893.2  393.21  4908.8  396.43    4927  396.59  5000.7  394.37  5202.2  394.48
  5230.4  392.46  5235.4  394.34  5560.3  394.09  5592.3  394.11  5758.6  392.44
  5786.1  391.33  5894.9  388.82  6017.5  389.43  6052.2  387.83    6055  387.33
  6058.2  387.83  6185.5   390.6  6285.8  394.59  6323.9  393.45  6420.9  396.19
#Mann= 12 ,-1 , 0
  4174.9     .12       0  4438.6     .05       0    4735      .1       0
  4771.6     .05       0  5560.3      .1       0  5592.3     .05       0
  5758.6      .1       0  5786.1     .05       0  6017.5     .12       0
  6052.2     .03       0  6058.2     .12       0  6323.9     .05       0
Bank Sta=4447,6185.5
XS Rating Curve= 0 ,0
Exp/Cntr=0.3,0.1

Type RM Length L Ch R = 1 ,11956   ,156,156,156
BEGIN DESCRIPTION:
UNT 139 IN CACR 26.0
END DESCRIPTION:
XS GIS Cut Line= 6
      3717318.61     10712731.08      3717114.61     10713117.36
      3717027.81     10713308.34      3716988.74     10713438.54
      3716932.32     10713998.44      3716876.01     10714947.07
#Sta/Elev= 30
    4131  399.41  4485.1  390.55  4669.9  390.33  4724.7  388.88  4733.6  387.13
  4739.1  388.51  4756.7  385.79  4762.2  388.49  4786.8  384.23    4792  386.55
  4819.8  383.38    4825  384.87  4852.6  382.31  4956.2  380.27  4985.6  378.69
  5042.7   379.9  5047.7  377.98  5083.2  377.65    5086  377.15  5089.2  377.65
  5267.1  380.15  5604.9  383.86  5728.5  387.76  6039.3  387.58  6079.1  389.13
  6149.2  388.01  6339.6  393.82  6369.6   396.4  6413.7  395.16  6426.6  394.89
#Mann= 6 ,-1 , 0
    4131     .12       0  4485.1     .05       0  5083.2     .03       0
  5089.2     .05       0  6039.3     .12       0  6413.7     .05       0
Bank Sta=4956.2,5267.1
XS Rating Curve= 0 ,0
Exp/Cntr=0.3,0.1

Type RM Length L Ch R = 1 ,11800   ,287,287,287
BEGIN DESCRIPTION:
Mapping XS 891aae02
END DESCRIPTION:
XS GIS Cut Line= 5
      3717255.61     10712755.93      3716880.62     10713380.91
      3716838.96     10713554.52      3716759.09     10713880.91
      3716516.03     10714651.79
#Sta/Elev= 30
  4218.4  398.15  4574.9  390.14  4752.7  384.93  4823.4  382.16  4903.1  380.46
  4924.5  381.65  4967.1  379.76  4984.6  375.43  4987.4  374.93  4990.6  375.43
  5014.6  376.42  5028.8  378.86  5049.3  375.79  5061.7   375.8  5172.8  377.97
  5182.1  379.38  5193.4  377.69  5312.1   379.1  5340.1   379.3  5638.5  382.77
  5713.7  386.06  6163.6  390.12  6204.3  391.39  6209.5  392.81    6217  392.05
  6226.5  390.87  6236.6  391.16  6241.9  393.24  6261.8  392.53  6270.1  391.77
#Mann= 8 ,-1 , 0
  4218.4     .12       0  4574.9     .05       0  4752.7     .12       0
  4984.6     .07       0  4990.6     .12       0  5340.1     .05       0
    6217     .16       0  6261.8     .12       0
Bank Sta=4967.1,5312.1
XS Rating Curve= 0 ,0
Exp/Cntr=0.3,0.1

Type RM Length L Ch R = 1 ,11513   ,470,470,470
BEGIN DESCRIPTION:
UNT 139 IN CACR 25.0
END DESCRIPTION:
XS GIS Cut Line= 3
      3716899.59     10712910.22      3716649.61     10713260.19
      3715849.59      10713560.2
#Sta/Elev= 30
  4556.6   391.4  4620.5  390.28  4706.5   386.2  4777.8  384.61  4928.9  379.07
  4937.5  378.27  4973.2  378.99  4983.6  375.22  5026.7  376.34  5040.1  375.27
  5053.5  376.43  5072.1  376.19  5081.9  375.25  5087.2  375.48  5093.5  378.06
  5104.2  375.69  5125.5  375.92  5142.4  375.14  5175.9  374.98  5178.7  374.48
  5181.9  374.98  5252.8  375.25  5413.9  378.63    5478   381.2  5509.1   383.5
  5514.4  383.21  5563.4  385.86  5648.8  388.06  5734.3  388.13  5841.1  391.79
#Mann= 4 ,-1 , 0
  4556.6     .12       0  5053.5     .05       0  5175.9     .07       0
  5181.9     .05       0
Bank Sta=4928.9,5413.9
XS Rating Curve= 0 ,0
Exp/Cntr=0.3,0.1

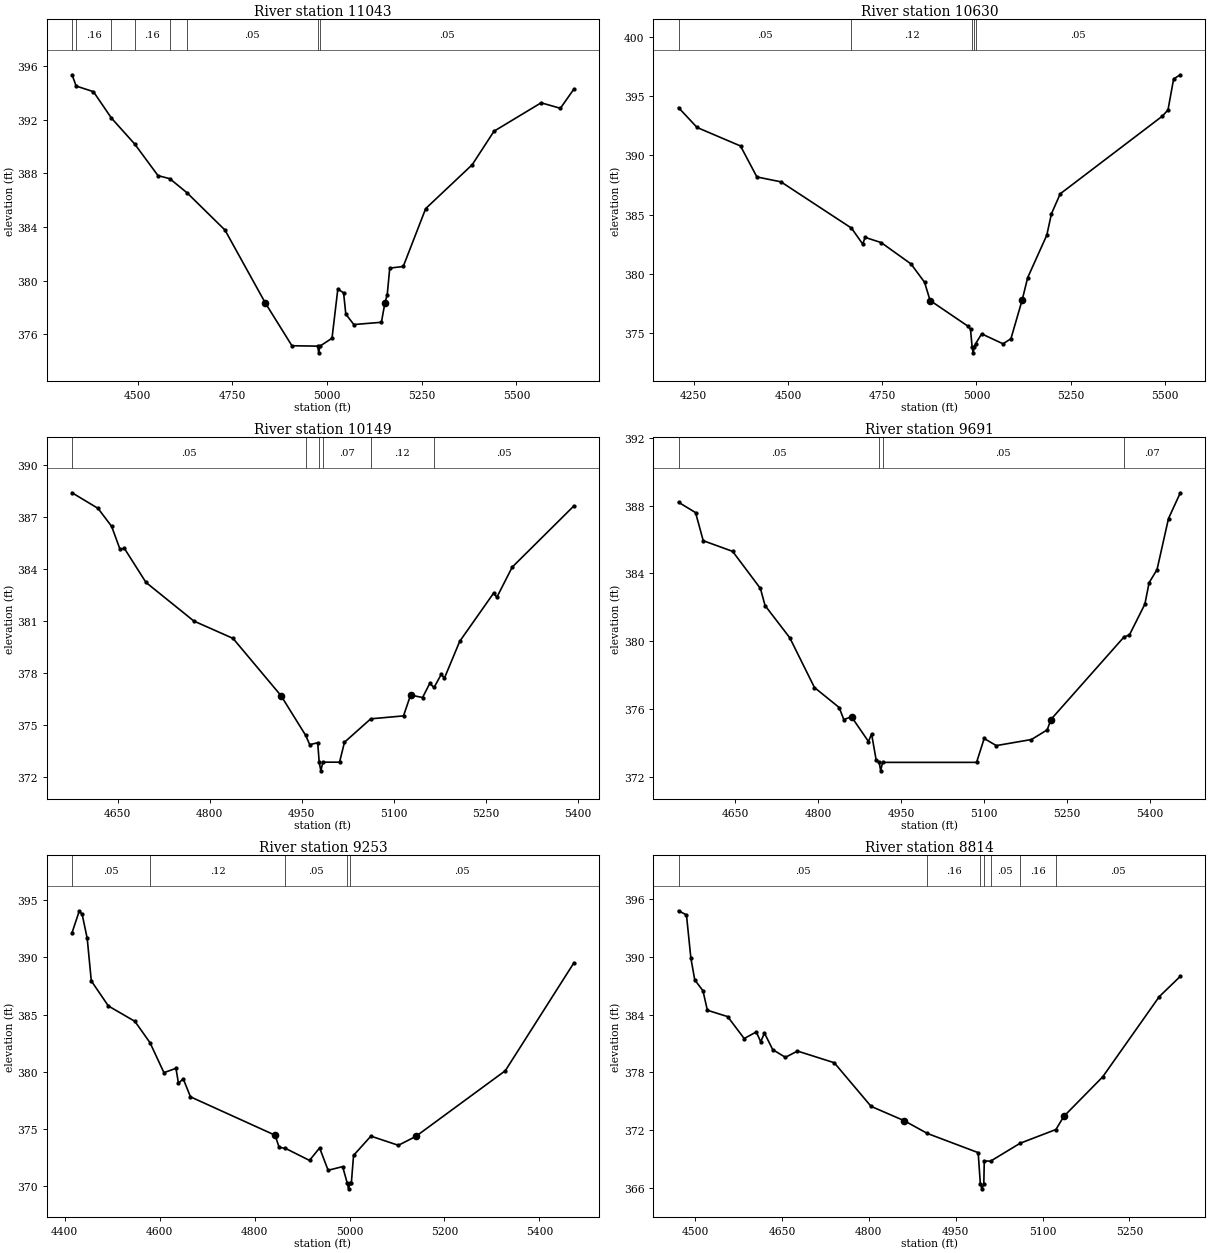
Type RM Length L Ch R = 1 ,11043   ,413,413,413
BEGIN DESCRIPTION:
UNT 139 IN CACR 24.0
END DESCRIPTION:
XS GIS Cut Line= 3
      3716749.61     10712610.19      3716249.61     10713060.19
      3715699.61     10713410.19
#Sta/Elev= 30
  4326.9  395.36  4337.7  394.52  4383.3   394.1  4430.8  392.13  4492.4  390.19
  4553.7  387.84  4584.8  387.61  4630.3  386.56  4730.5  383.78    4837  378.34
  4907.3  375.15  4975.3  375.12    4978  374.62  4981.3  375.12  5013.1  375.71
  5028.4  379.37  5043.6   379.1  5049.5  377.51  5070.7  376.73  5143.5   376.9
  5152.8  378.36  5158.8  378.94  5165.5  380.94  5201.1  381.06  5260.4  385.38
  5383.1  388.65  5440.7  391.15  5565.1  393.27  5615.9  392.86  5651.5  394.29
#Mann= 8 ,-1 , 0
  4326.9     .12       0  4337.7     .16       0  4430.8     .12       0
  4492.4     .16       0  4584.8     .12       0  4630.3     .05       0
  4975.3    .035       0  4981.3     .05       0
Bank Sta=4837,5152.8
XS Rating Curve= 0 ,0
Exp/Cntr=0.3,0.1

Type RM Length L Ch R = 1 ,10630   ,481,481,481
BEGIN DESCRIPTION:
UNT 139 IN CACR 23.0
END DESCRIPTION:
XS GIS Cut Line= 2
      3716378.48     10712159.93      3715614.62     10713250.16
#Sta/Elev= 30
  4209.8  394.03    4259  392.36  4374.2   390.8  4417.7  388.19  4481.4  387.78
  4668.6  383.88  4698.5  382.53  4704.6   383.1  4747.4  382.66  4826.6  380.86
  4862.4  379.32  4877.2  377.78  4978.3   375.6  4984.4  375.35  4988.6  373.87
  4991.3  373.37  4994.6  373.87  4997.8  374.13    5014  374.97  5070.7  374.13
  5091.6  374.56  5121.3  377.81  5136.1  379.71  5186.7  383.28  5199.1  385.09
  5222.4  386.77  5493.5  393.32  5508.3  393.84  5523.2  396.45    5541   396.8
#Mann= 5 ,-1 , 0
  4209.8     .05       0  4668.6     .12       0  4988.6     .03       0
  4994.6     .12       0  4997.8     .05       0
Bank Sta=4877.2,5121.3
XS Rating Curve= 0 ,0
Exp/Cntr=0.3,0.1

Type RM Length L Ch R = 1 ,10149   ,458,458,458
BEGIN DESCRIPTION:
UNT 139 IN CACR 22.0
END DESCRIPTION:
XS GIS Cut Line= 3
      3715949.62     10712210.18      3715649.61     10712460.19
      3715499.62     10712860.16
#Sta/Elev= 30
  4575.7  388.38    4618  387.48  4640.2  386.44  4653.8  385.12    4661  385.17
  4696.1  383.21  4774.2  380.98    4838  379.98  4916.1  376.68  4956.3  374.39
    4963  373.85    4976  373.96  4978.4  372.84  4981.1  372.34  4984.4  372.84
  5011.6  372.84  5019.6  373.99  5062.4  375.34  5115.8  375.51  5127.3  376.71
  5146.9  376.57  5158.5  377.38  5165.6  377.15  5177.2   377.9  5182.5  377.69
  5207.4  379.81  5262.6  382.59  5267.9  382.35  5292.9  384.09  5393.4  387.62
#Mann= 6 ,-1 , 0
  4575.7     .05       0  4956.3     .07       0  4978.4     .07       0
  4984.4     .07       0  5062.4     .12       0  5165.6     .05       0
Bank Sta=4916.1,5127.3
XS Rating Curve= 0 ,0
Exp/Cntr=0.3,0.1

Type RM Length L Ch R = 1 ,9691    ,438,438,438
BEGIN DESCRIPTION:
UNT 139 IN CACR 21.0
END DESCRIPTION:
XS GIS Cut Line= 3
      3715749.63     10711960.18      3715349.61     10712160.19
      3715049.62     10712510.17
#Sta/Elev= 30
  4547.5   388.2  4578.3  387.59  4592.2  385.93  4645.4   385.3  4695.7  383.11
  4704.1   382.1  4748.8   380.2  4793.5  377.26  4838.2  376.08  4846.6  375.37
  4860.6  375.53  4891.3  374.07  4896.9  374.52  4905.3  372.96  4910.7  372.84
  4913.4  372.34  4916.7  372.84  5086.9  372.84  5100.7  374.25  5122.6  373.83
  5186.3  374.19  5214.8  374.76  5221.4  375.37  5353.9  380.25  5363.5  380.36
  5391.5  382.18  5399.2  383.45  5413.5  384.22  5434.3  387.24  5455.7  388.76
#Mann= 4 ,-1 , 0
  4547.5     .05       0  4910.7    .033       0  4916.7     .05       0
  5353.9     .07       0
Bank Sta=4860.6,5221.4
XS Rating Curve= 0 ,0
Exp/Cntr=0.3,0.1

Type RM Length L Ch R = 1 ,9253    ,439,439,439
BEGIN DESCRIPTION:
UNT 139 IN CACR 20.0
END DESCRIPTION:
XS GIS Cut Line= 3
       3715299.6     10711260.21      3715099.61     10711810.19
      3714849.62     10712210.18
#Sta/Elev= 30
  4415.6  392.15  4430.9  394.06  4436.9  393.74  4447.5  391.65  4456.1  387.94
  4492.1  385.75  4547.9  384.41  4579.7  382.55  4609.1  379.93  4634.4  380.31
  4639.7     379  4649.7   379.4    4665  377.82  4843.2  374.47  4851.8   373.4
  4864.7  373.33  4915.7  372.27    4937  373.36  4954.9  371.41  4985.5  371.73
  4995.2  370.29  4997.9  369.79  5001.2  370.29  5003.8  370.29  5008.5  372.71
    5045  374.39  5102.8  373.59  5139.4  374.36  5328.1   380.1  5472.5  389.51
#Mann= 5 ,-1 , 0
  4415.6     .05       0  4579.7     .12       0  4864.7     .05       0
  4995.2     .03       0  5001.2     .05       0
Bank Sta=4843.2,5139.4
XS Rating Curve= 0 ,0
Exp/Cntr=0.3,0.1

Type RM Length L Ch R = 1 ,8814    ,457,457,457
BEGIN DESCRIPTION:
UNT 139 IN CACR 19.0
END DESCRIPTION:
XS GIS Cut Line= 3
      3715199.59     10711160.21      3714799.61     10711510.19
       3714499.6     10711660.19
#Sta/Elev= 30
  4471.2  394.76  4484.9  394.33  4492.5  389.86  4499.2   387.6  4513.4  386.47
    4521  384.45  4556.1  383.79  4584.6  381.52  4605.5   382.2  4613.1  381.19
  4619.7  382.08  4633.9  380.37  4655.8  379.57  4676.7  380.22  4740.2  379.01
  4803.8  374.49  4860.8  373.01  4901.1  371.68  4988.9  369.69  4992.6  366.44
  4995.3  365.94  4998.6  366.44  4999.4  368.83  5010.3  368.81  5061.2  370.66
  5123.2  372.09  5136.8  373.45  5203.9  377.54  5301.7  385.86  5338.1  387.97
#Mann= 7 ,-1 , 0
  4471.2     .05       0  4901.1     .16       0  4992.6     .07       0
  4998.6     .16       0  5010.3     .05       0  5061.2     .16       0
  5123.2     .05       0
Bank Sta=4860.8,5136.8
XS Rating Curve= 0 ,0
Exp/Cntr=0.3,0.1

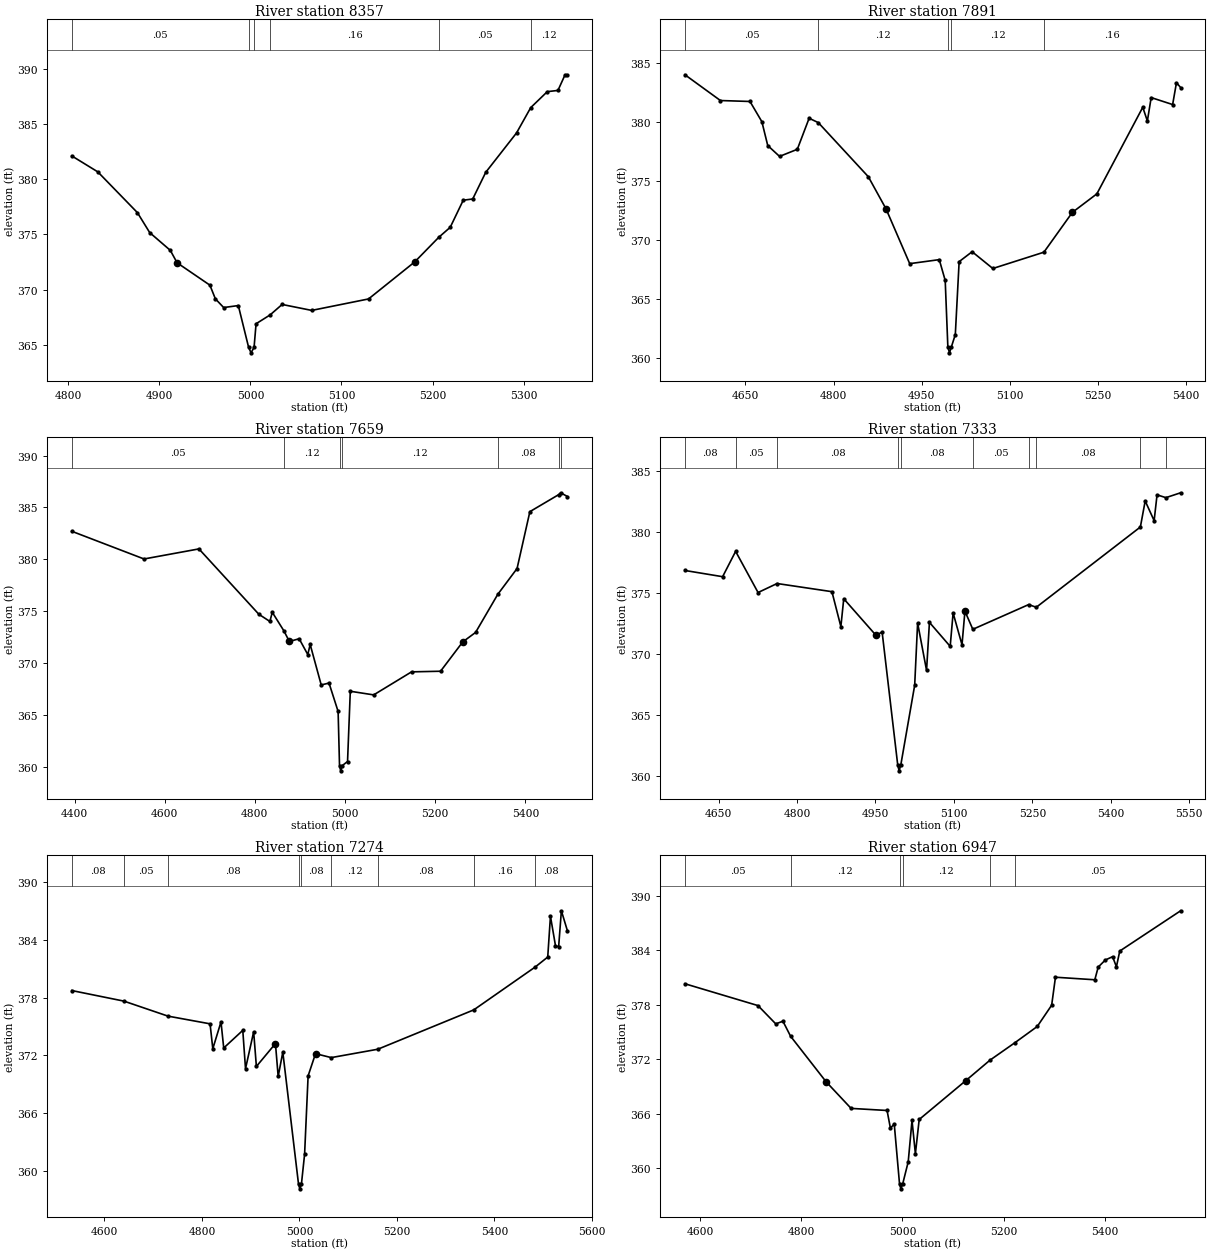
Type RM Length L Ch R = 1 ,8357    ,466,466,466
BEGIN DESCRIPTION:
UNT 139 IN CACR 18.0
END DESCRIPTION:
XS GIS Cut Line= 3
      3714549.61     10711060.18      3714449.61     10711210.19
      3714349.61      10711560.2
#Sta/Elev= 30
  4803.8  382.13  4832.4  380.68  4875.9  376.98  4889.4  375.17    4912  373.56
  4919.5  372.43  4955.5   370.4  4961.5  369.16  4970.6  368.37  4986.7  368.55
    4998  364.76  5000.7  364.26    5004  364.76  5006.2   366.9  5021.6   367.7
  5034.8  368.65  5067.3  368.11  5129.7  369.15  5180.4  372.51  5206.9  374.75
  5219.4  375.65  5233.7  378.11  5244.1  378.22  5258.4  380.64  5292.2  384.21
  5307.8  386.51    5326  387.96  5337.7  388.07  5345.5  389.49  5348.1  389.49
#Mann= 6 ,-1 , 0
  4803.8     .05       0    4998     .03       0    5004     .05       0
  5021.6     .16       0  5206.9     .05       0  5307.8     .12       0
Bank Sta=4919.5,5180.4
XS Rating Curve= 0 ,0
Exp/Cntr=0.3,0.1

Type RM Length L Ch R = 1 ,7891    ,232,232,232
BEGIN DESCRIPTION:
UNT 139 IN CACR 17.0
END DESCRIPTION:
XS GIS Cut Line= 3
      3714649.56     10710910.18      3714199.61     10710860.19
      3713949.63     10711160.16
#Sta/Elev= 30
  4547.3  383.97  4607.6  381.79  4657.9  381.71  4678.1     380  4688.1  377.98
  4708.2  377.06  4738.4  377.66  4758.5  380.29  4774.1  379.92  4859.2  375.34
  4889.3  372.62  4929.6  367.98  4979.9  368.32    4990  366.56  4994.5  360.93
  4997.3  360.43  5000.5  360.93  5007.2  361.98  5013.7  368.15  5035.8  368.99
    5071  367.57  5157.9  368.95  5206.3  372.32    5248  373.89  5326.1  381.22
  5333.9  380.06  5340.4  382.04  5376.9  381.45  5383.4   383.3  5390.5  382.89
#Mann= 5 ,-1 , 0
  4547.3     .05       0  4774.1     .12       0  4994.5     .07       0
  5000.5     .12       0  5157.9     .16       0
Bank Sta=4889.3,5206.3
XS Rating Curve= 0 ,0
Exp/Cntr=0.3,0.1

Type RM Length L Ch R = 1 ,7659    ,326,326,326
BEGIN DESCRIPTION:
Mapping XS c0a2acc9
END DESCRIPTION:
XS GIS Cut Line= 4
      3714296.92     10710120.92       3714088.6     10710652.15
      3714033.91     10710730.28      3713710.98     10711019.35
#Sta/Elev= 30
  4393.9   382.7  4554.2  380.03    4676     381  4808.9   374.7  4833.3  374.01
  4838.7  374.89  4864.6  373.09  4876.5  372.08  4898.3  372.34  4917.4  370.82
  4922.7  371.79  4947.2  367.89  4964.5  368.07  4984.7  365.33  4987.8  360.11
  4990.5  359.61  4993.8  360.11  5005.6  360.51  5011.7  367.28  5063.6  366.93
  5147.6  369.15  5211.9  369.21  5261.2  372.04  5289.6  372.95  5338.8  376.62
  5381.6  379.11    5410  384.59  5474.3  386.24  5478.3  386.41  5493.3  386.05
#Mann= 7 ,-1 , 0
  4393.9     .05       0  4864.6     .12       0  4987.8     .07       0
  4993.8     .12       0  5338.8     .08       0  5474.3     .16       0
  5478.3     .08       0
Bank Sta=4876.5,5261.2
XS Rating Curve= 0 ,0
Exp/Cntr=0.3,0.1

Type RM Length L Ch R = 1 ,7333    ,59,59,59
BEGIN DESCRIPTION:
UNT 139 IN CACR 16.0
END DESCRIPTION:
XS GIS Cut Line= 2
       3714026.1     10710120.91      3713614.64     10710975.07
#Sta/Elev= 30
  4585.6  376.84  4657.6  376.33  4682.5  378.41  4725.4  375.03  4761.8  375.77
  4866.7   375.1  4883.8  372.23  4889.3  374.52  4951.1  371.51  4962.7  371.79
  4992.5  360.89  4995.2  360.39  4998.5  360.89    5025  367.42  5030.6  372.53
  5047.7  368.64  5053.2  372.58  5092.9  370.61  5098.5  373.35  5115.5  370.74
  5121.1   373.5  5136.2  372.01    5243  374.04  5257.6  373.82  5456.7  380.41
  5465.9  382.55    5483  380.93  5488.6  383.05  5505.5  382.82  5533.7  383.22
#Mann= 10 ,-1 , 0
  4585.6     .08       0  4682.5     .05       0  4761.8     .08       0
  4992.5     .07       0  4998.5     .08       0  5136.2     .05       0
    5243     .12       0  5257.6     .08       0  5456.7      .1       0
  5505.5     .08       0
Bank Sta=4951.1,5121.1
XS Rating Curve= 0 ,0
Exp/Cntr=0.3,0.1

Type RM Length L Ch R = 1 ,7274    ,327,327,327
BEGIN DESCRIPTION:
UNT 139 IN CACR 15.0
END DESCRIPTION:
XS GIS Cut Line= 2
      3714002.64     10710053.23      3713546.92     10710962.08
#Sta/Elev= 30
    4533  378.75    4640  377.65  4730.4  376.09  4816.7  375.29  4822.3   372.7
  4839.1  375.49  4844.7  372.78  4883.8  374.61  4889.4  370.63  4906.1  374.46
  4911.7  370.86  4950.8  373.24  4956.4  369.82  4965.9  372.35  4998.1  358.64
  5000.8  358.14  5004.1  358.64  5010.6  361.74  5017.8  369.88    5033  372.19
  5065.3  371.78  5160.8  372.65  5357.6  376.74  5483.5  381.19  5509.3  382.23
  5514.9  386.47  5525.2  383.41  5531.7   383.3  5537.3  387.04  5549.7  384.96
#Mann= 9 ,-1 , 0
    4533     .08       0    4640     .05       0  4730.4     .08       0
  4998.1     .07       0  5004.1     .08       0  5065.3     .12       0
  5160.8     .08       0  5357.6     .16       0  5483.5     .08       0
Bank Sta=4950.8,5033
XS Rating Curve= 0 ,0
Exp/Cntr=0.3,0.1

Type RM Length L Ch R = 1 ,6947    ,428,428,428
BEGIN DESCRIPTION:
Mapping XS 54da49e0
END DESCRIPTION:
XS GIS Cut Line= 2
      3713939.18      10709936.5      3713206.16     10710586.34
#Sta/Elev= 30
  4570.3  380.32  4714.6  377.92  4749.7  375.91  4763.9   376.2    4779  374.55
  4849.2  369.54  4898.6  366.61  4969.7  366.38  4976.3  364.44  4983.9  364.89
  4994.4  358.26  4997.1  357.76  5000.4  358.26  5011.5  360.73    5019  365.28
  5025.7  361.62  5033.2  365.39  5125.2  369.66  5173.2  371.92  5222.2  373.83
  5266.5  375.62    5295  377.96  5302.5  381.04  5380.3  380.76    5387  382.16
  5401.2  382.94  5415.4   383.3    5423  382.19  5429.6  383.92  5549.9  388.35
#Mann= 6 ,-1 , 0
  4570.3     .05       0    4779     .12       0  4994.4     .07       0
  5000.4     .12       0  5173.2     .16       0  5222.2     .05       0
Bank Sta=4849.2,5125.2
XS Rating Curve= 0 ,0
Exp/Cntr=0.3,0.1