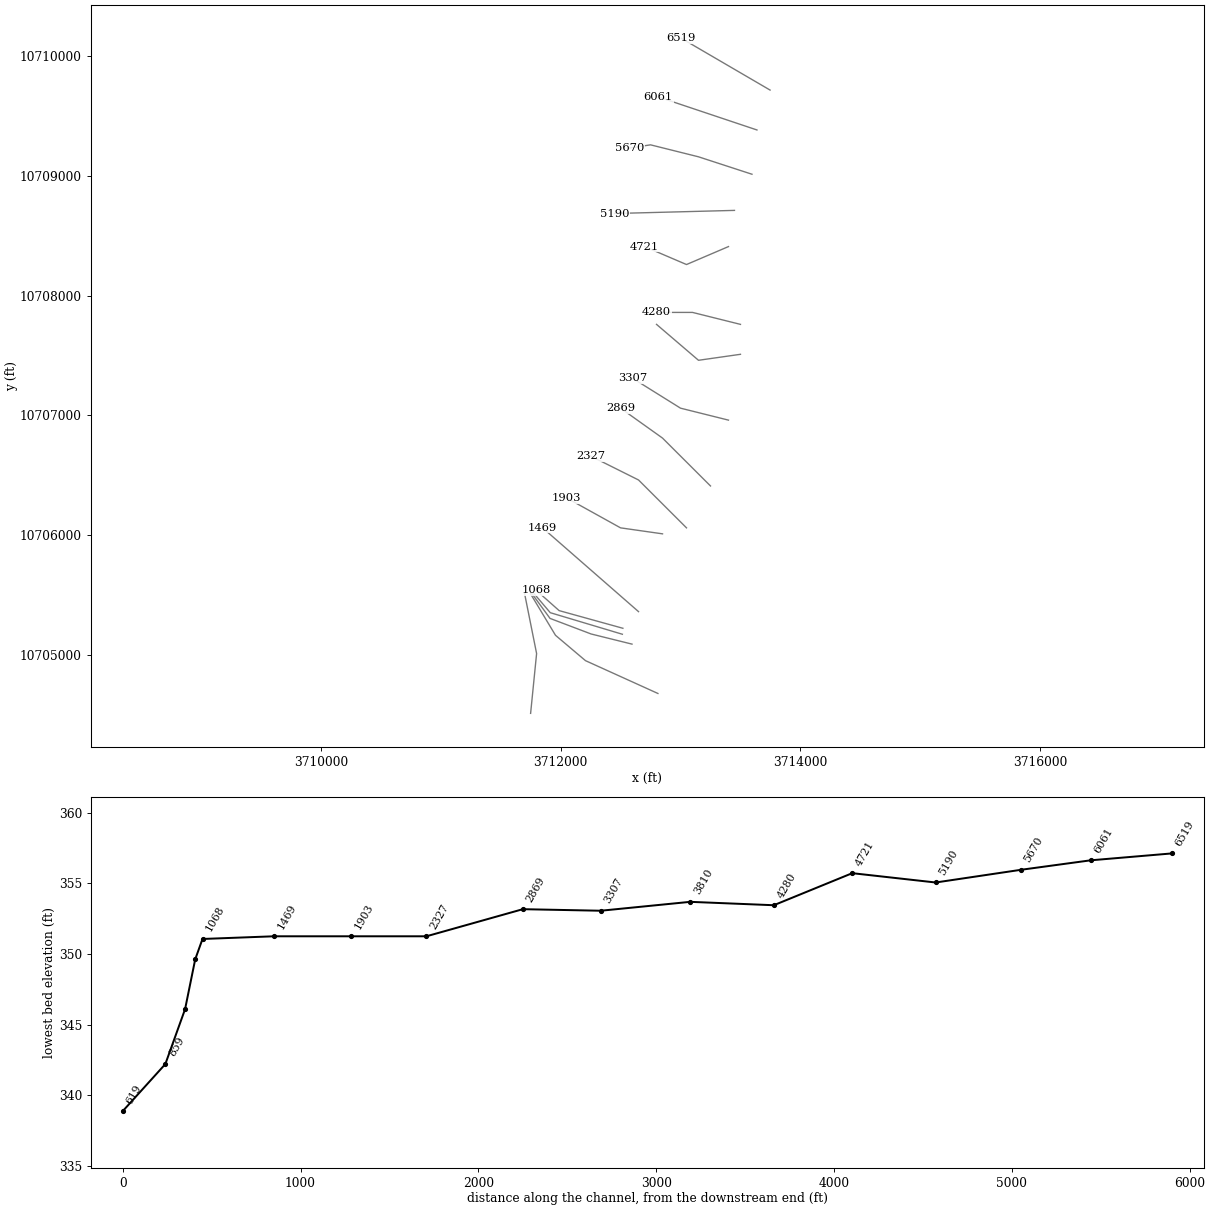
HEC-RAS study UNT 139 IN CACR.prj: UNT 139 IN CACR Base Level Engineering

--- UNT 139 IN CACR.g01 (geometry) --- (continued)

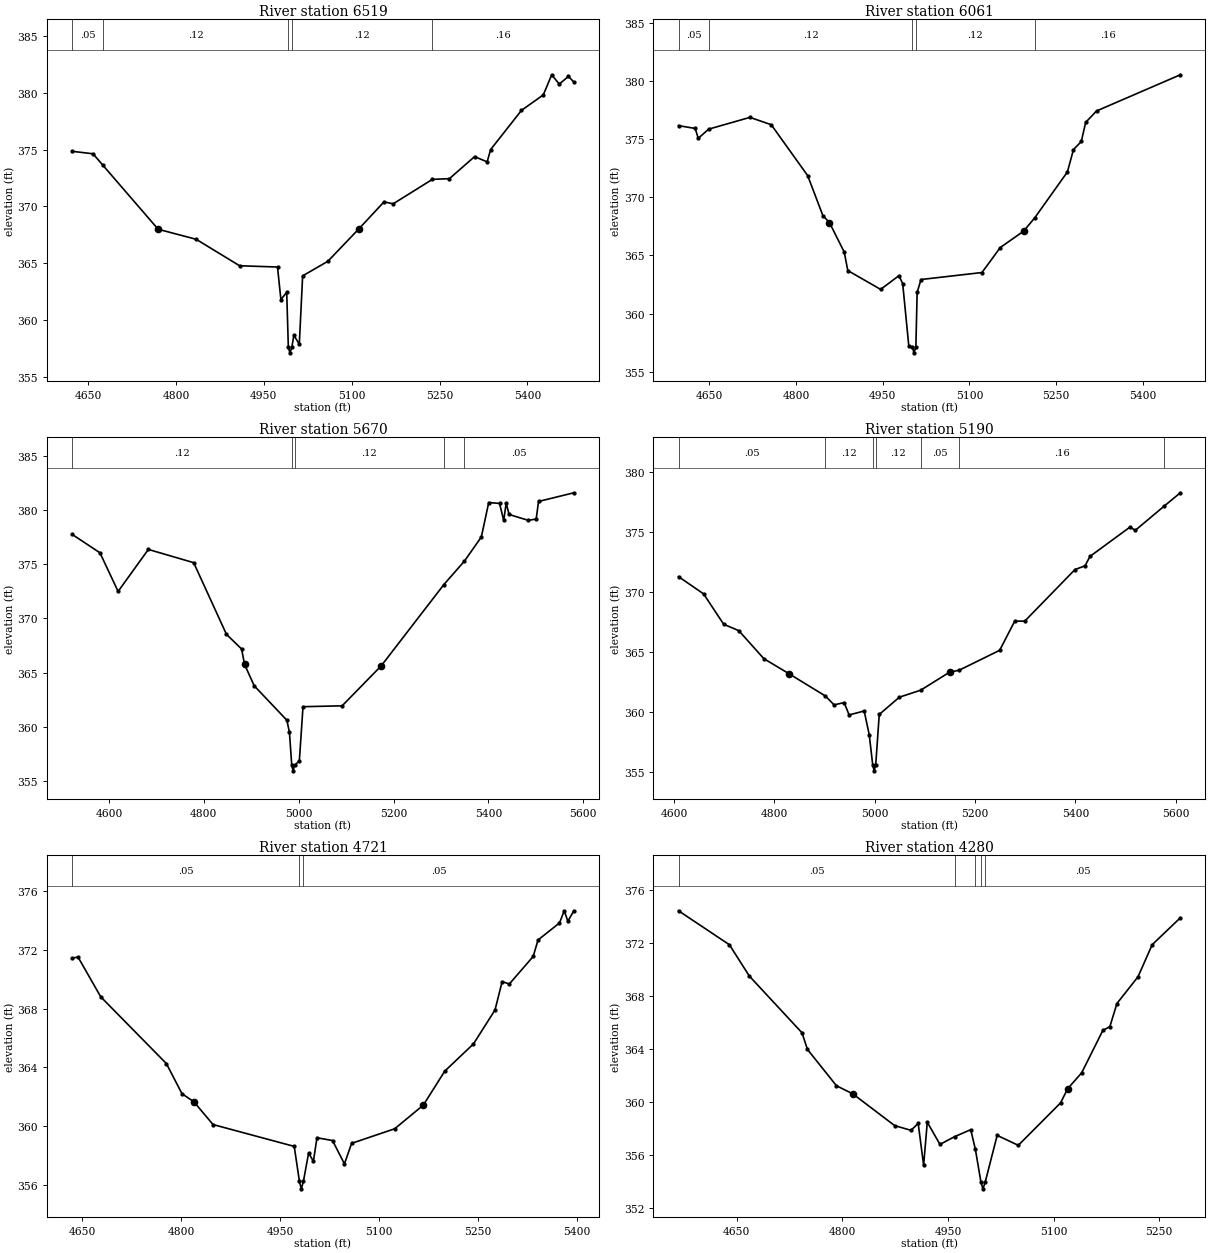
Type RM Length L Ch R = 1 ,6519    ,458,458,458
BEGIN DESCRIPTION:
Mapping XS 86b3b8c5
END DESCRIPTION:
XS GIS Cut Line= 2
      3713746.49     10709717.73      3713006.95     10710149.99
#Sta/Elev= 30
  4622.7  374.85  4658.5  374.63  4675.5  373.61  4769.7  367.99  4834.5  367.11
  4908.7  364.78  4973.4  364.67  4979.2   361.8  4989.1  362.45  4991.9  357.62
  4994.6  357.12  4997.9  357.62  5001.3  358.67  5010.6  357.88  5016.3  363.89
  5059.3  365.17  5112.2  368.02  5155.2   370.4  5170.9  370.23  5237.8  372.38
  5266.8  372.44  5309.8  374.38  5331.3  373.92  5337.2     375  5389.9  378.45
  5427.1  379.81  5441.5  381.58  5454.4  380.76  5470.1  381.44  5479.3  380.94
#Mann= 5 ,-1 , 0
  4622.7     .05       0  4675.5     .12       0  4991.9     .07       0
  4997.9     .12       0  5237.8     .16       0
Bank Sta=4769.7,5112.2
XS Rating Curve= 0 ,0
Exp/Cntr=0.3,0.1

Type RM Length L Ch R = 1 ,6061    ,391,391,391
BEGIN DESCRIPTION:
Mapping XS e2f4f850
END DESCRIPTION:
XS GIS Cut Line= 2
       3713637.1     10709384.39      3712814.45     10709660.35
#Sta/Elev= 30
  4596.9  376.15  4625.7  375.91    4631  375.06    4649  375.85  4720.4  376.86
  4757.2  376.23  4820.3  371.85  4846.5  368.42  4857.9  367.82  4883.4  365.29
  4889.6   363.7  4946.4  362.08    4978  363.26  4984.5  362.58  4995.1  357.21
  5001.3  357.13    5004  356.63  5007.3  357.13  5009.5  361.82  5016.2  362.93
  5121.6  363.53  5153.3  365.68  5193.5  367.08  5212.7  368.22  5269.3  372.17
  5279.8  374.09  5293.4  374.79  5300.9  376.43  5319.7  377.41  5464.6  380.52
#Mann= 5 ,-1 , 0
  4596.9     .05       0    4649     .12       0  5001.3     .07       0
  5007.3     .12       0  5212.7     .16       0
Bank Sta=4857.9,5193.5
XS Rating Curve= 0 ,0
Exp/Cntr=0.3,0.1

Type RM Length L Ch R = 1 ,5670    ,480,480,480
BEGIN DESCRIPTION:
UNT 139 IN CACR 12.0
END DESCRIPTION:
XS GIS Cut Line= 4
       3713595.5     10709014.58      3713149.61     10709160.19
      3712749.61     10709260.19      3712574.63     10709233.34
#Sta/Elev= 30
    4522  377.75  4580.8  376.05  4619.1  372.49  4682.9  376.36  4778.5  375.14
  4847.6  368.54  4879.5  367.19  4885.9  365.76  4906.1   363.8  4975.1  360.62
  4980.5   359.5  4985.4  356.46  4988.2  355.96  4991.4  356.46  5001.4  356.89
  5009.1  361.87  5091.6  361.95    5174  365.63    5306  373.11  5349.5  375.28
  5385.3  377.51  5400.8  380.68  5423.6   380.6  5432.5  379.03  5437.6  380.63
  5443.8  379.58  5484.3  379.04  5500.9  379.16  5505.9  380.78  5580.4  381.58
#Mann= 5 ,-1 , 0
    4522     .12       0  4985.4     .07       0  4991.4     .12       0
    5306     .16       0  5349.5     .05       0
Bank Sta=4885.9,5174
XS Rating Curve= 0 ,0
Exp/Cntr=0.3,0.1

Type RM Length L Ch R = 1 ,5190    ,469,469,469
BEGIN DESCRIPTION:
Mapping XS 2040682e
END DESCRIPTION:
XS GIS Cut Line= 2
      3713449.61     10708712.51      3712449.65     10708686.47
#Sta/Elev= 30
  4608.8  371.25  4658.8  369.81  4698.8  367.28  4728.8  366.75  4778.9  364.41
  4828.9  363.16  4901.5   361.3  4918.9  360.56  4938.9  360.75  4948.9  359.72
  4978.9  360.05  4988.9  358.08  4995.9  355.56  4998.7  355.06  5001.9  355.56
  5008.9  359.76    5049   361.2  5091.4  361.78    5149  363.28  5168.3  363.45
    5249  365.11    5279  367.54    5299  367.54  5399.1  371.84  5419.1  372.15
  5429.1  372.94  5509.1  375.39  5519.1   375.1  5576.1   377.1  5609.1  378.24
#Mann= 7 ,-1 , 0
  4608.8     .05       0  4901.5     .12       0  4995.9     .07       0
  5001.9     .12       0  5091.4     .05       0  5168.3     .16       0
  5576.1     .05       0
Bank Sta=4828.9,5149
XS Rating Curve= 0 ,0
Exp/Cntr=0.3,0.1

Type RM Length L Ch R = 1 ,4721    ,441,441,441
BEGIN DESCRIPTION:
UNT 139 IN CACR 10.0
END DESCRIPTION:
XS GIS Cut Line= 3
      3713399.59     10708410.18      3713049.61     10708260.19
      3712699.57     10708410.21
#Sta/Elev= 30
  4634.3  371.43  4643.3  371.51  4677.8   368.8  4777.5  364.25  4801.1   362.2
  4819.2  361.65  4848.2   360.1  4971.5  358.61  4979.4  356.22  4982.2  355.72
  4985.4  356.22  4993.3  358.16  5000.6   357.6    5006   359.2  5029.6  359.01
  5047.7  357.42  5058.6  358.82  5123.9  359.81  5167.4  361.42    5200  363.74
  5243.5  365.59  5276.2   367.9  5287.1  369.84  5297.9  369.67  5334.2  371.55
  5341.5  372.67  5374.1  373.83  5381.3  374.66  5386.8  373.95  5395.9  374.66
#Mann= 3 ,-1 , 0
  4634.3     .05       0  4979.4     .03       0  4985.4     .05       0
Bank Sta=4819.2,5167.4
XS Rating Curve= 0 ,0
Exp/Cntr=0.3,0.1

Type RM Length L Ch R = 1 ,4280    ,470,470,470
BEGIN DESCRIPTION:
UNT 139 IN CACR 9.0
END DESCRIPTION:
XS GIS Cut Line= 3
      3713499.63     10707760.18      3713099.61     10707860.19
      3712799.64     10707860.19
#Sta/Elev= 30
  4567.6  374.41  4639.8  371.85  4668.1  369.49  4742.9  365.21  4750.6  363.96
  4791.8  361.22    4815  360.61  4874.3  358.22  4897.5  357.86  4907.8  358.38
  4915.5  355.23  4920.7  358.47  4938.7   356.8  4959.4  357.38  4982.4  357.91
    4989  356.42  4996.9  353.95  4999.7  353.45  5002.9  353.95  5019.9  357.48
  5049.9  356.73  5109.9  359.93  5119.9  360.99  5139.9   362.2  5169.9  365.39
  5179.9  365.68  5189.9  367.42  5219.9  369.44  5239.9  371.85  5279.9  373.88
#Mann= 5 ,-1 , 0
  4567.6     .05       0  4959.4     .16       0    4989     .05       0
  4996.9     .03       0  5002.9     .05       0
Bank Sta=4815,5119.9
XS Rating Curve= 0 ,0
Exp/Cntr=0.3,0.1

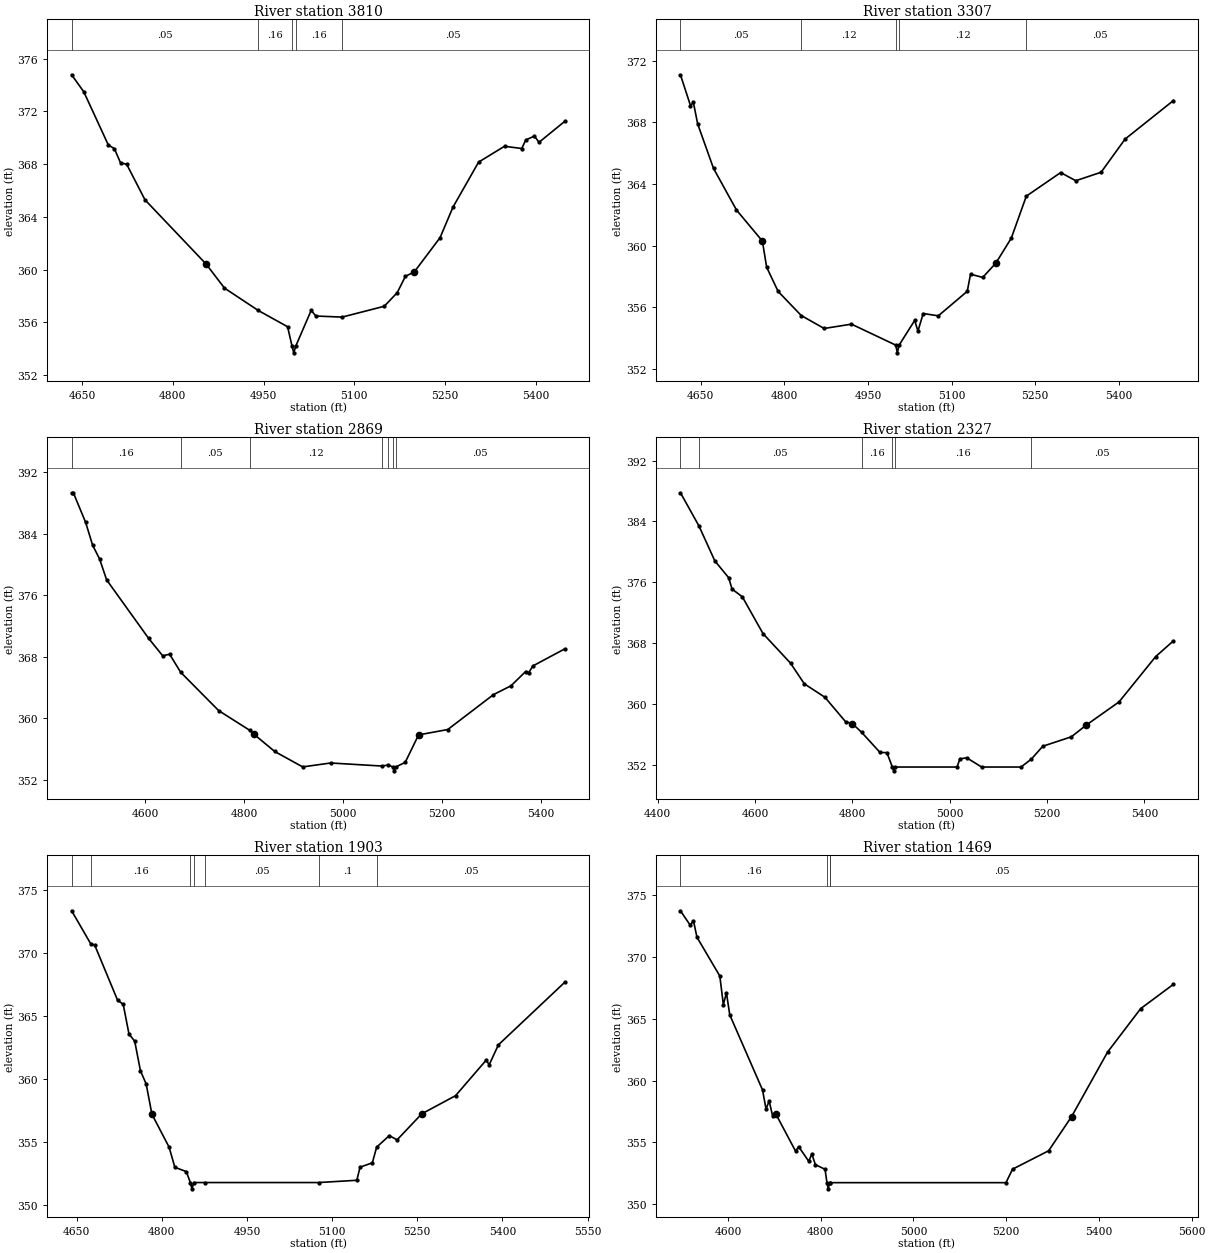
Type RM Length L Ch R = 1 ,3810    ,503,503,503
BEGIN DESCRIPTION:
UNT 139 IN CACR 8.0
END DESCRIPTION:
XS GIS Cut Line= 3
      3713499.58     10707510.18      3713149.61     10707460.19
      3712799.61     10707760.19
#Sta/Elev= 30
  4632.9  374.77  4653.1  373.47  4693.5  369.45  4703.6  369.17  4713.7  368.09
  4723.8  367.99  4754.1  365.29  4855.1  360.42  4885.4   358.6  4941.3   356.9
  4989.7  355.67  4997.1  354.19  4999.9  353.69  5003.1  354.19  5028.7  356.91
  5036.4  356.48  5079.8   356.4  5149.4  357.22  5170.8  358.25  5184.5   359.5
  5198.8  359.81  5241.6  362.42    5263  364.74  5305.3  368.15  5348.1  369.35
  5376.6  369.18  5383.2  369.83  5397.5  370.12  5405.1  369.65  5447.4  371.23
#Mann= 5 ,-1 , 0
  4632.9     .05       0  4941.3     .16       0  4997.1     .07       0
  5003.1     .16       0  5079.8     .05       0
Bank Sta=4855.1,5198.8
XS Rating Curve= 0 ,0
Exp/Cntr=0.3,0.1

Type RM Length L Ch R = 1 ,3307    ,438,438,438
BEGIN DESCRIPTION:
UNT 139 IN CACR 7.0
END DESCRIPTION:
XS GIS Cut Line= 3
       3713399.6     10706960.19      3712999.61     10707060.19
      3712599.61     10707310.19
#Sta/Elev= 30
  4613.8  371.09  4631.8  369.09    4637   369.3  4644.7   367.9  4673.1  365.02
  4714.3  362.32  4760.7  360.31  4768.4  358.61    4789  357.04  4830.4  355.48
  4871.5  354.64  4920.5  354.92  4999.9  353.56  5002.7  353.06  5005.9  353.56
  5033.8  355.16  5039.7  354.47  5049.1  355.61  5076.2  355.46  5128.1  357.05
    5134  358.16  5155.8  357.95  5179.4  358.88  5207.1   360.5    5234  363.22
  5295.6  364.75  5322.7  364.22  5368.1  364.77  5411.1  366.92  5497.8  369.42
#Mann= 5 ,-1 , 0
  4613.8     .05       0  4830.4     .12       0  4999.9     .07       0
  5005.9     .12       0    5234     .05       0
Bank Sta=4760.7,5179.4
XS Rating Curve= 0 ,0
Exp/Cntr=0.3,0.1

Type RM Length L Ch R = 1 ,2869    ,542,542,542
BEGIN DESCRIPTION:
UNT 139 IN CACR 6.0
END DESCRIPTION:
XS GIS Cut Line= 3
      3713249.59      10706410.2      3712849.61     10706810.19
      3712499.59      10707060.2
#Sta/Elev= 30
  4451.5  389.31    4455  389.31  4479.8  385.46  4493.9   382.5    4508   380.7
  4522.2  377.99    4607  370.39  4635.3  368.13  4649.5  368.32  4671.9  365.97
  4748.5     361  4811.7  358.42  4819.2  357.96  4861.6  355.69  4918.2  353.68
  4974.7  354.19  5079.1  353.79  5090.9  353.94  5100.2  353.67  5102.9  353.17
  5106.2  353.67  5125.3  354.27  5152.3  357.84  5211.3  358.54  5303.5  363.07
  5339.1  364.23  5368.6  366.08  5374.8  365.94  5383.4  366.81  5447.3  369.01
#Mann= 7 ,-1 , 0
  4451.5     .16       0  4671.9     .05       0  4811.7     .12       0
  5079.1     .16       0  5090.9     .05       0  5100.2     .07       0
  5106.2     .05       0
Bank Sta=4819.2,5152.3
XS Rating Curve= 0 ,0
Exp/Cntr=0.3,0.1

Type RM Length L Ch R = 1 ,2327    ,424,424,424
BEGIN DESCRIPTION:
UNT 139 IN CACR 5.0
END DESCRIPTION:
XS GIS Cut Line= 3
      3713049.58     10706060.21      3712649.61     10706460.19
      3712249.58     10706660.21
#Sta/Elev= 30
  4446.7  387.77  4484.6  383.43  4517.4  378.82  4545.7  376.62  4552.7  375.13
  4573.9   374.1  4616.4  369.27  4672.9  365.39  4701.2  362.68  4743.6  360.91
  4786.1  357.69  4800.2  357.44  4818.8  356.32  4856.8  353.66  4870.9  353.64
  4882.1  351.75  4884.8  351.25  4888.1  351.75  5015.1  351.75  5020.7  352.81
  5034.7  352.97  5065.5  351.75  5146.5  351.75  5167.5  352.78  5191.2  354.48
  5249.9  355.72  5280.7  357.27  5347.8   360.3  5423.2  366.26  5459.6  368.32
#Mann= 6 ,-1 , 0
  4446.7      .1       0  4484.6     .05       0  4818.8     .16       0
  4882.1     .07       0  4888.1     .16       0  5167.5     .05       0
Bank Sta=4800.2,5280.7
XS Rating Curve= 0 ,0
Exp/Cntr=0.3,0.1

Type RM Length L Ch R = 1 ,1903    ,434,434,434
BEGIN DESCRIPTION:
UNT 139 IN CACR 4.0
END DESCRIPTION:
XS GIS Cut Line= 3
      3712849.62     10706010.19      3712499.61     10706060.19
      3712049.65     10706310.17
#Sta/Elev= 30
  4641.3  373.34  4675.4  370.68  4681.7  370.64  4722.1  366.25  4732.2   365.9
  4742.3  363.55  4752.4  362.98  4762.5  360.63  4772.6  359.58  4782.7  357.18
    4813  354.56  4823.1  352.96  4843.3  352.62  4850.4  351.75  4853.2  351.25
  4856.4  351.75  4875.8  351.75  5076.2  351.75  5143.6  351.93  5149.3  352.97
    5171  353.32  5178.5  354.56  5200.8  355.48  5214.5  355.14    5258  357.21
  5317.5  358.65  5371.2  361.46  5376.9  361.12    5393  362.69  5509.6  367.65
#Mann= 7 ,-1 , 0
  4641.3     .05       0  4675.4     .16       0  4850.4    .033       0
  4856.4     .16       0  4875.8     .05       0  5076.2      .1       0
  5178.5     .05       0
Bank Sta=4782.7,5258
XS Rating Curve= 0 ,0
Exp/Cntr=0.3,0.1

Type RM Length L Ch R = 1 ,1469    ,401,401,401
BEGIN DESCRIPTION:
UNT 139 IN CACR 3.0
END DESCRIPTION:
XS GIS Cut Line= 3
      3712649.59      10705360.2      3712249.61     10705710.19
      3711849.61     10706060.19
#Sta/Elev= 30
  4497.7  373.75    4519  372.57  4525.7  372.96  4533.3  371.61  4582.6  368.47
  4590.2  366.16  4596.9  367.11    4604  365.33  4674.7  359.25  4682.3   357.7
  4688.9  358.37  4696.5  357.14  4703.2  357.32  4745.9   354.3  4752.5  354.67
  4774.3  353.48    4781  354.07  4788.6  353.21  4809.5  352.83  4813.6  351.75
  4816.3  351.25  4819.6  351.75  4820.6  351.75  5199.6  351.75  5213.8  352.84
  5291.6  354.33    5341  357.09  5418.8  362.32    5490  365.83  5560.7   367.8
#Mann= 4 ,-1 , 0
  4497.7     .16       0  4813.6    .033       0  4819.6     .16       0
  4820.6     .05       0
Bank Sta=4703.2,5341
XS Rating Curve= 0 ,0
Exp/Cntr=0.3,0.1

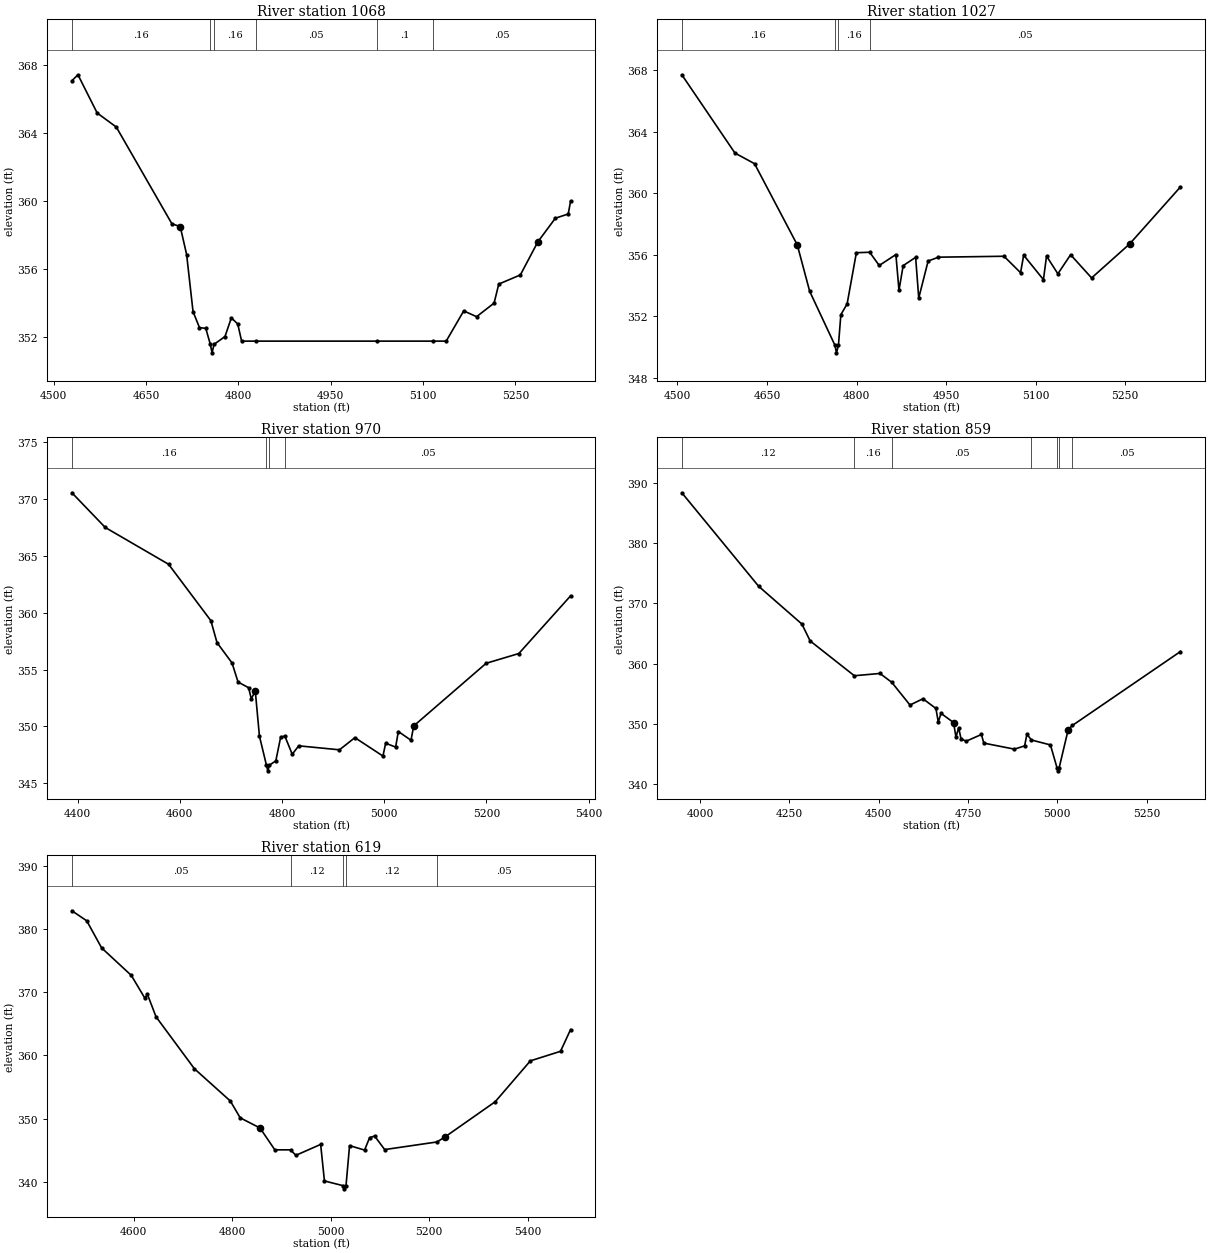
Type RM Length L Ch R = 1 ,1068    ,41,41,41
BEGIN DESCRIPTION:
Mapping XS 387234d2
END DESCRIPTION:
XS GIS Cut Line= 3
      3712519.13      10705221.2      3711987.48     10705368.76
      3711794.49     10705540.07
#Sta/Elev= 30
  4529.7  367.09  4539.5  367.44  4570.7  365.19  4601.8  364.36  4692.1  358.66
  4705.6   358.5    4716  356.85  4726.4  353.49  4736.8  352.55  4747.1   352.5
  4754.5  351.56  4757.3  351.06  4760.5  351.56  4778.3  352.02  4788.6  353.12
    4799  352.76  4805.3  351.75  4828.3  351.75  5024.8  351.75  5116.9  351.75
  5137.5  351.75    5166  353.53  5186.9  353.19  5215.3  353.99  5222.9  355.11
    5258  355.65  5286.4   357.6  5314.8  358.99  5335.7  359.24  5339.5  359.99
#Mann= 6 ,-1 , 0
  4529.7     .16       0  4754.5    .035       0  4760.5     .16       0
  4828.3     .05       0  5024.8      .1       0  5116.9     .05       0
Bank Sta=4705.6,5286.4
XS Rating Curve= 0 ,0
Exp/Cntr=0.3,0.1

Type RM Length L Ch R = 1 ,1027    ,57,57,57
BEGIN DESCRIPTION:
Mapping XS f3638500
END DESCRIPTION:
XS GIS Cut Line= 3
      3712514.83     10705171.27       3711913.7      10705351.4
      3711779.14     10705509.83
#Sta/Elev= 30
  4507.3   367.7  4596.3  362.61  4629.1  361.92  4700.7  356.64  4721.5  353.62
  4763.7  350.12  4766.4  349.62  4769.7  350.12  4773.7   352.1  4784.2   352.8
  4799.7  356.13    4822  356.16    4838   355.3  4865.9  356.01  4871.1  353.69
  4878.1  355.29    4899  355.83  4904.2  353.18  4919.9  355.59  4937.3  355.84
    5047   355.9  5074.8  354.83    5080  355.97  5113.1  354.38  5118.3  355.91
  5137.3  354.76  5158.6     356  5193.8  354.49  5257.5   356.7  5342.7  360.41
#Mann= 4 ,-1 , 0
  4507.3     .16       0  4763.7    .035       0  4769.7     .16       0
    4822     .05       0
Bank Sta=4700.7,5257.5
XS Rating Curve= 0 ,0
Exp/Cntr=0.3,0.1

Type RM Length L Ch R = 1 ,970     ,111,111,111
BEGIN DESCRIPTION:
Mapping XS 42c6dfbf
END DESCRIPTION:
XS GIS Cut Line= 4
      3712595.16      10705088.8      3712254.41     10705173.44
      3711911.53     10705303.65      3711759.63     10705511.97
#Sta/Elev= 30
  4388.8  370.55    4454   367.5    4578  364.26  4660.7   359.3  4672.7  357.37
  4702.1  355.58  4713.9   353.9  4734.6   353.4  4739.8  352.42  4747.6  353.11
  4755.7  349.15  4769.4  346.59  4772.1  346.09  4775.4  346.59  4787.8  346.97
  4797.2  349.05  4805.4  349.15  4819.9  347.55  4832.6  348.29  4912.3  347.94
  4942.5  349.01  4997.4  347.39  5002.7  348.52  5022.2  348.18  5027.5  349.55
  5052.3  348.78  5057.6  350.04  5199.3  355.55  5263.3  356.41  5364.5  361.48
#Mann= 4 ,-1 , 0
  4388.8     .16       0  4769.4    .035       0  4775.4     .16       0
  4805.4     .05       0
Bank Sta=4747.6,5057.6
XS Rating Curve= 0 ,0
Exp/Cntr=0.3,0.1

Type RM Length L Ch R = 1 ,859     ,240,240,240
BEGIN DESCRIPTION:
Mapping XS 66832fd2
END DESCRIPTION:
XS GIS Cut Line= 4
      3712811.25     10704676.49       3712207.1     10704950.79
       3711957.1     10705162.59      3711748.76     10705509.82
#Sta/Elev= 30
    3949  388.34  4164.3  372.81  4285.1  366.56  4308.2  363.76    4432  357.98
  4503.8  358.36  4536.7  356.89  4587.8  353.12  4624.1  354.16  4660.4  352.55
    4667  350.29  4674.7  351.74  4709.8  350.21  4716.4  347.81  4724.1  349.32
  4730.7  347.51    4745  347.12  4787.8  348.23  4794.4   346.8  4880.1   345.8
  4908.7  346.34  4915.2  348.28  4927.8  347.32    4981   346.5  4999.4   342.7
  5002.2   342.2  5005.4   342.7  5030.7  349.03  5042.4  349.73  5345.1     362
#Mann= 7 ,-1 , 0
    3949     .12       0    4432     .16       0  4536.7     .05       0
  4927.8      .1       0  4999.4     .07       0  5005.4      .1       0
  5042.4     .05       0
Bank Sta=4709.8,5030.7
XS Rating Curve= 0 ,0
Exp/Cntr=0.3,0.1

Type RM Length L Ch R = 1 ,619     ,0,0,0
BEGIN DESCRIPTION:
UNT 139 IN CACR 1.0
END DESCRIPTION:
XS GIS Cut Line= 3
      3711749.61     10704510.22      3711799.61     10705010.19
       3711699.6     10705510.22
#Sta/Elev= 30
  4474.8  382.92  4504.9  381.33  4535.1  377.04  4595.4  372.68    4623  369.06
    4628   369.7  4645.6  366.12  4723.5  357.89  4796.4  352.78  4816.5  350.11
  4856.7   348.5  4886.8  345.04  4918.6  345.04  4929.5  344.17  4979.8   345.9
  4987.5  340.11  5025.3  339.36    5028  338.86  5031.3  339.36  5038.5  345.71
    5069     345  5079.2  346.97  5089.4  347.23  5109.8  345.08  5216.1  346.29
  5232.2  347.08  5334.2  352.66  5405.6  359.14  5466.8  360.65  5487.2  364.09
#Mann= 5 ,-1 , 0
  4474.8     .05       0  4918.6     .12       0  5025.3     .07       0
  5031.3     .12       0  5216.1     .05       0
Bank Sta=4856.7,5232.2
XS Rating Curve= 0 ,0
Exp/Cntr=0.3,0.1

Chan Stop Cuts=-1
Use User Specified Reach Order=0
Composite Channel Slope=5