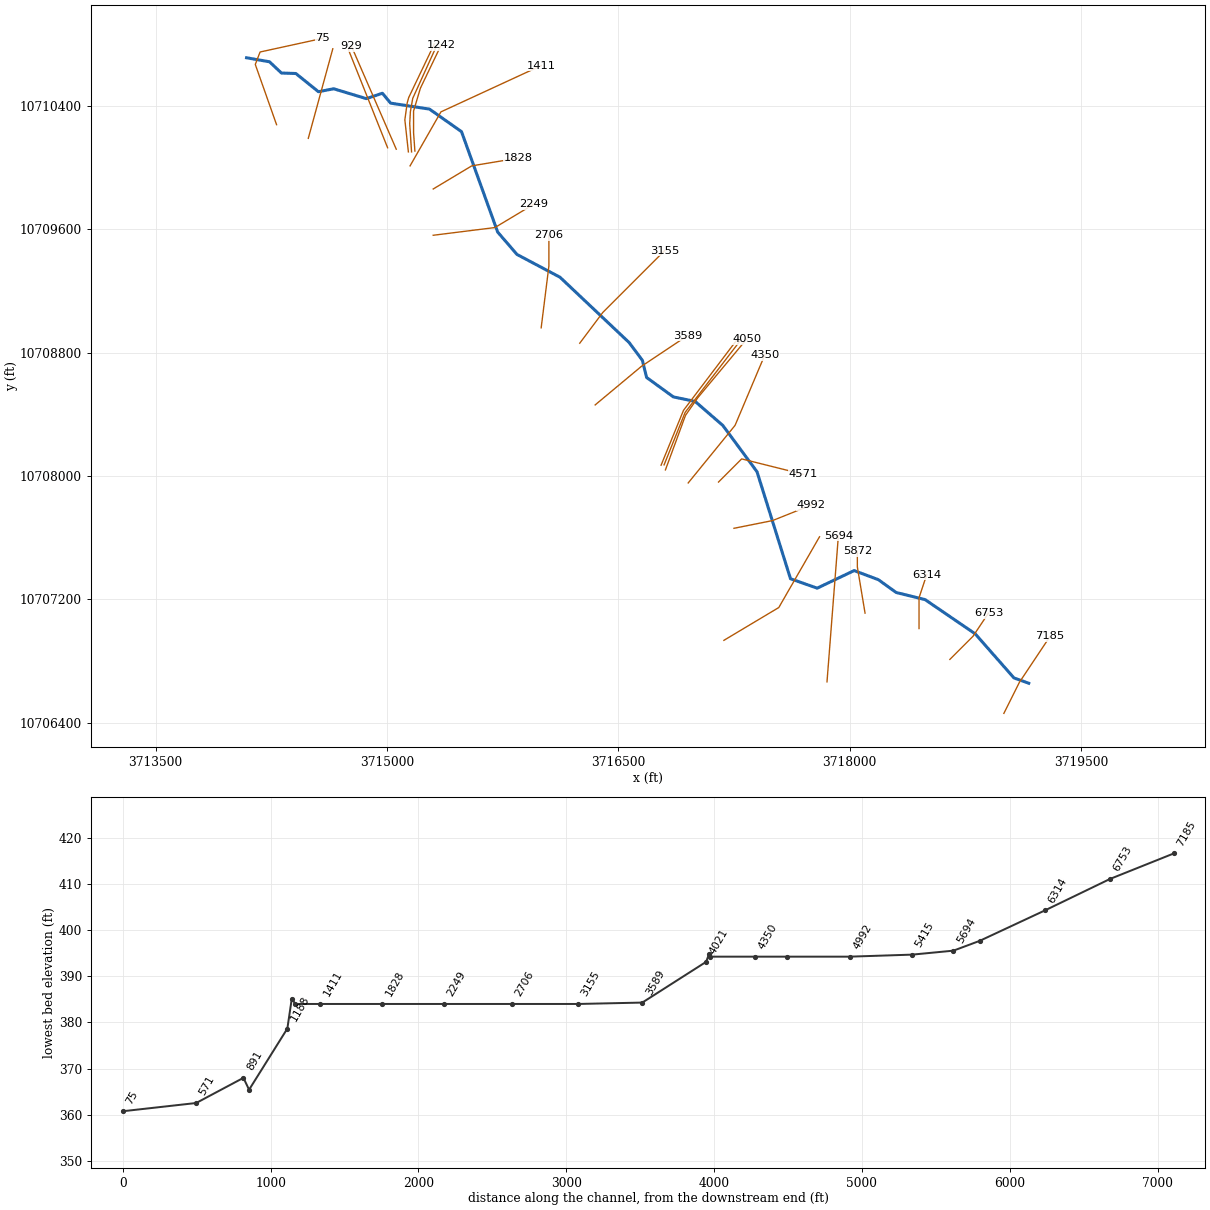
--- UNT 141 IN CACR.prj (project) ---

Proj Title=UNT 141 IN CACR Base Level Engineering
Current Plan=p01
Default Exp/Contr=0.3,0.1
English Units
Geom File=g01
Flow File=f01
Plan File=p01
BEGIN DESCRIPTION:
UNT 141 IN CACR
END DESCRIPTION:

--- UNT 141 IN CACR.p01 (plan) ---

Plan Title=Multiple Run
Short Identifier=Multiple
Geom File=g01
Flow File=f01
Subcritical Flow
K Sum by GR= 0
Std Step Tol= 0.01
Critical Tol= 0.01
Num of Std Step Trials= 20
Max Error Tol= 0.3
Flow Tol Ratio= 0.001
Split Flow NTrial= 30
Split Flow Tol= 0.02
Split Flow Ratio= 0.02
Log Output Level= 0
Friction Slope Method= 1
Unsteady Friction Slope Method= 2
Unsteady Bridges Friction Slope Method= 1
Parabolic Critical Depth
Global Vel Dist=  1 , 1 , 1
Global Log Level= 0
CheckData=True
Encroach Param= -1, 0, 0, 0
BEGIN DESCRIPTION:
Multiple Run
END DESCRIPTION:

--- UNT 141 IN CACR.f01 (steady flow) ---

Flow Title=Multiple
Number of Profiles=7
Profile Names=10-year,25-year,50-year,1pct_min,100-year,1pct_plu,500-year
River Rch & RM= UNT 141 IN CACR,Reach-1,7185
     557     757     923     828    1120    1515    1654
River Rch & RM= UNT 141 IN CACR,Reach-1,5694
     724     997    1227    1110    1501    2030    2254
River Rch & RM= UNT 141 IN CACR,Reach-1,4021
     908    1266    1570    1429    1933    2614    2942
Boundary for River Rch & Prof#=UNT 141 IN CACR,Reach-1,1
Up Type=0
Dn Type=3
Dn Slope=0.005
Boundary for River Rch & Prof#=UNT 141 IN CACR,Reach-1,2
Up Type=0
Dn Type=3
Dn Slope=0.005
Boundary for River Rch & Prof#=UNT 141 IN CACR,Reach-1,3
Up Type=0
Dn Type=3
Dn Slope=0.005
Boundary for River Rch & Prof#=UNT 141 IN CACR,Reach-1,4
Up Type=0
Dn Type=3
Dn Slope=0.005
Boundary for River Rch & Prof#=UNT 141 IN CACR,Reach-1,5
Up Type=0
Dn Type=3
Dn Slope=0.005
Boundary for River Rch & Prof#=UNT 141 IN CACR,Reach-1,6
Up Type=0
Dn Type=3
Dn Slope=0.005
Boundary for River Rch & Prof#=UNT 141 IN CACR,Reach-1,7
Up Type=0
Dn Type=3
Dn Slope=0.005

--- UNT 141 IN CACR.g01 (geometry) ---

Geom Title=Existing Conditions

River Reach=UNT 141 IN CACR,Reach-1
Reach XY= 30
      3719160.93     10706655.69      3719065.00     10706690.00
      3718813.75     10706976.00      3718488.50     10707198.00
      3718301.25     10707244.00      3718186.00     10707327.00
      3718028.75     10707386.00      3717789.25     10707272.00
      3717616.25     10707333.00      3717399.00     10708027.00
      3717177.50     10708327.00      3716997.50     10708483.00
      3716857.00     10708512.00      3716683.25     10708638.00
      3716656.00     10708749.00      3716570.50     10708864.00
      3716121.75     10709288.00      3715842.50     10709436.00
      3715717.50     10709581.00      3715483.00     10710232.00
      3715275.75     10710378.00      3715023.25     10710417.00
      3714970.25     10710481.00      3714866.00     10710446.00
      3714654.25     10710510.00      3714555.25     10710491.00
      3714409.00     10710609.00      3714315.50     10710612.00
      3714238.25     10710685.00      3714089.50     10710711.00

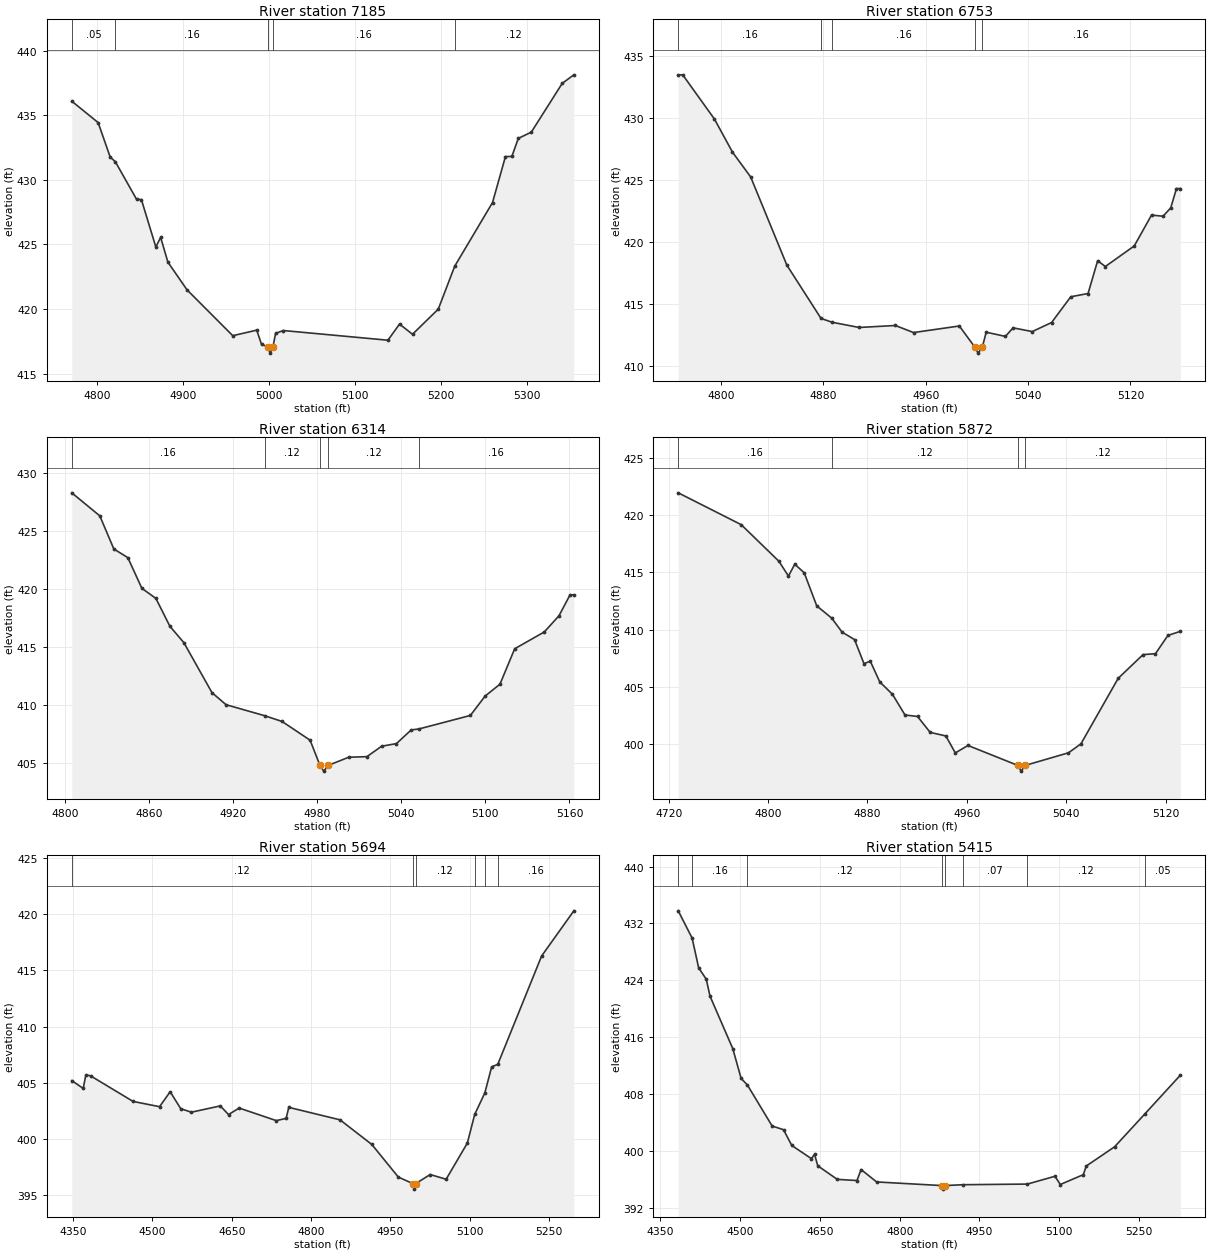
Type RM Length L Ch R = 1,7185,432,432,432
BEGIN DESCRIPTION:
UNT 141 IN CACR 16.0
END DESCRIPTION:
XS GIS Cut Line= 3
      3718999.62     10706460.20      3719099.61     10706660.19
      3719299.58     10706960.15
#Sta/Elev= 30
  4770.5  436.09  4801.2  434.43  4815.2  431.76  4821.2  431.40  4845.9  428.49
  4851.5  428.47  4868.3  424.80  4873.9  425.54  4882.3  423.63  4904.6  421.48
  4957.8  417.93  4985.7  418.36  4991.3  417.25  4998.6  417.08  5001.3  416.58
  5004.6  417.08  5007.6  418.11  5016.6  418.33  5138.3  417.58  5151.8  418.83
  5166.9  418.04  5196.9  419.99  5216.0  423.31  5260.0  428.24  5275.0  431.80
  5282.5  431.81  5290.0  433.21  5305.1  433.69  5341.1  437.47  5354.6  438.13
#Mann=5,-1,0
  4770.5    0.05       0  4821.2    0.16       0  4998.6    0.07       0
  5004.6    0.16       0  5216.0    0.12       0
Bank Sta=4998.6,5004.6
Exp/Cntr=0.3,0.1

Type RM Length L Ch R = 1,6753,439,439,439
BEGIN DESCRIPTION:
UNT 141 IN CACR 15.0
END DESCRIPTION:
XS GIS Cut Line= 3
      3718649.60     10706810.18      3718799.61     10706960.19
      3718899.60     10707110.17
#Sta/Elev= 30
  4766.6  433.51  4770.1  433.51  4794.9  429.94  4809.0  427.27  4823.2  425.27
  4851.5  418.15  4878.2  413.85  4886.9  413.54  4908.0  413.12  4936.3  413.28
  4950.5  412.71  4986.3  413.24  4998.3  411.55  5001.0  411.05  5004.3  411.55
  5007.3  412.74  5022.3  412.40  5028.3  413.09  5043.3  412.79  5058.4  413.52
  5073.4  415.60  5086.9  415.86  5094.4  418.51  5100.4  418.04  5123.0  419.70
  5136.5  422.19  5145.5  422.10  5151.5  422.77  5156.0  424.33  5159.0  424.33
#Mann=5,-1,0
  4766.6    0.16       0  4878.2    0.12       0  4886.9    0.16       0
  4998.3    0.07       0  5004.3    0.16       0
Bank Sta=4998.3,5004.3
Exp/Cntr=0.3,0.1

Type RM Length L Ch R = 1,6314,442,442,442
BEGIN DESCRIPTION:
UNT 141 IN CACR 14.0
END DESCRIPTION:
XS GIS Cut Line= 3
      3718449.61     10707010.23      3718449.61     10707210.19
      3718499.62     10707360.22
#Sta/Elev= 30
  4805.0  428.30  4825.0  426.31  4835.0  423.45  4845.0  422.70  4855.0  420.05
  4865.0  419.18  4875.0  416.77  4885.0  415.35  4905.0  411.04  4915.0  410.00
  4942.5  409.05  4955.0  408.55  4975.0  406.93  4982.0  404.76  4984.7  404.26
  4988.0  404.76  5002.5  405.46  5015.5  405.51  5026.0  406.41  5036.6  406.64
  5047.1  407.82  5052.5  407.90  5089.3  409.07  5099.8  410.74  5110.4  411.77
  5120.9  414.83  5142.0  416.28  5152.5  417.68  5160.4  419.49  5163.1  419.49
#Mann=5,-1,0
  4805.0    0.16       0  4942.5    0.12       0  4982.0    0.07       0
  4988.0    0.12       0  5052.5    0.16       0
Bank Sta=4982,4988
Exp/Cntr=0.3,0.1

Type RM Length L Ch R = 1,5872,178,178,178
BEGIN DESCRIPTION:
UNT 141 IN CACR 13.0
END DESCRIPTION:
XS GIS Cut Line= 3
      3718099.61     10707110.18      3718049.61     10707410.19
      3718049.61     10707510.14
#Sta/Elev= 30
  4727.7  421.95  4778.4  419.17  4808.8  415.97  4816.4  414.68  4821.5  415.72
  4829.1  414.97  4839.2  412.08  4851.2  411.02  4859.5  409.80  4869.6  409.14
  4877.2  407.04  4882.3  407.25  4889.9  405.45  4900.1  404.37  4910.2  402.56
  4920.3  402.43  4930.5  401.04  4943.1  400.73  4950.7  399.25  4960.9  399.90
  5001.0  398.16  5003.7  397.66  5007.0  398.16  5041.8  399.26  5051.8  400.04
  5081.8  405.76  5101.8  407.83  5111.8  407.91  5121.8  409.50  5131.8  409.86
#Mann=4,-1,0
  4727.7    0.16       0  4851.2    0.12       0  5001.0    0.07       0
  5007.0    0.12       0
Bank Sta=5001,5007
Exp/Cntr=0.3,0.1

Type RM Length L Ch R = 1,5694,279,279,279
BEGIN DESCRIPTION:
Mapping XS 6ff06dfd
END DESCRIPTION:
XS GIS Cut Line= 2
      3717852.84     10706664.77      3717926.62     10707610.90
#Sta/Elev= 30
  4347.7  405.19  4369.3  404.50  4374.4  405.70  4383.2  405.62  4463.5  403.34
  4513.6  402.87  4533.7  404.20  4553.7  402.69  4573.8  402.38  4628.4  402.94
  4644.0  402.17  4664.1  402.75  4734.3  401.63  4752.9  401.83  4757.9  402.81
  4854.7  401.70  4914.8  399.51  4965.0  396.60  4992.1  396.03  4994.8  395.53
  4998.1  396.03  5025.2  396.83  5055.3  396.41  5095.4  399.63  5109.3  402.18
  5128.4  404.09  5141.4  406.42  5152.9  406.64  5235.8  416.29  5296.7  420.31
#Mann=6,-1,0
  4347.7    0.12       0  4992.1    0.07       0  4998.1    0.12       0
  5109.3    0.16       0  5128.4    0.05       0  5152.9    0.16       0
Bank Sta=4992.1,4998.1
Exp/Cntr=0.3,0.1

Type RM Length L Ch R = 1,5415,423,423,423
BEGIN DESCRIPTION:
Mapping XS 688dbfac
END DESCRIPTION:
XS GIS Cut Line= 3
      3717184.39     10706933.81      3717540.33     10707146.50
      3717804.46     10707605.48
#Sta/Elev= 30
  4383.5  433.78  4409.6  429.95  4421.9  425.77  4436.2  424.17  4443.3  421.78
  4486.1  414.41  4501.7  410.24  4513.6  409.30  4560.1  403.54  4581.5  403.02
  4597.0  400.81  4634.0  398.95  4639.8  399.57  4645.9  397.95  4682.6  396.04
  4719.6  395.88  4727.4  397.42  4756.6  395.68  4879.2  395.17  4881.9  394.67
  4885.2  395.17  4919.1  395.29  5040.1  395.38  5092.0  396.48  5102.0  395.32
  5145.2  396.70  5150.9  397.92  5204.1  400.62  5260.8  405.22  5327.7  410.68
#Mann=8,-1,0
  4383.5    0.05       0  4409.6    0.16       0  4513.6    0.12       0
  4879.2    0.07       0  4885.2    0.12       0  4919.1    0.07       0
  5040.1    0.12       0  5260.8    0.05       0
Bank Sta=4879.2,4885.2
Exp/Cntr=0.3,0.1

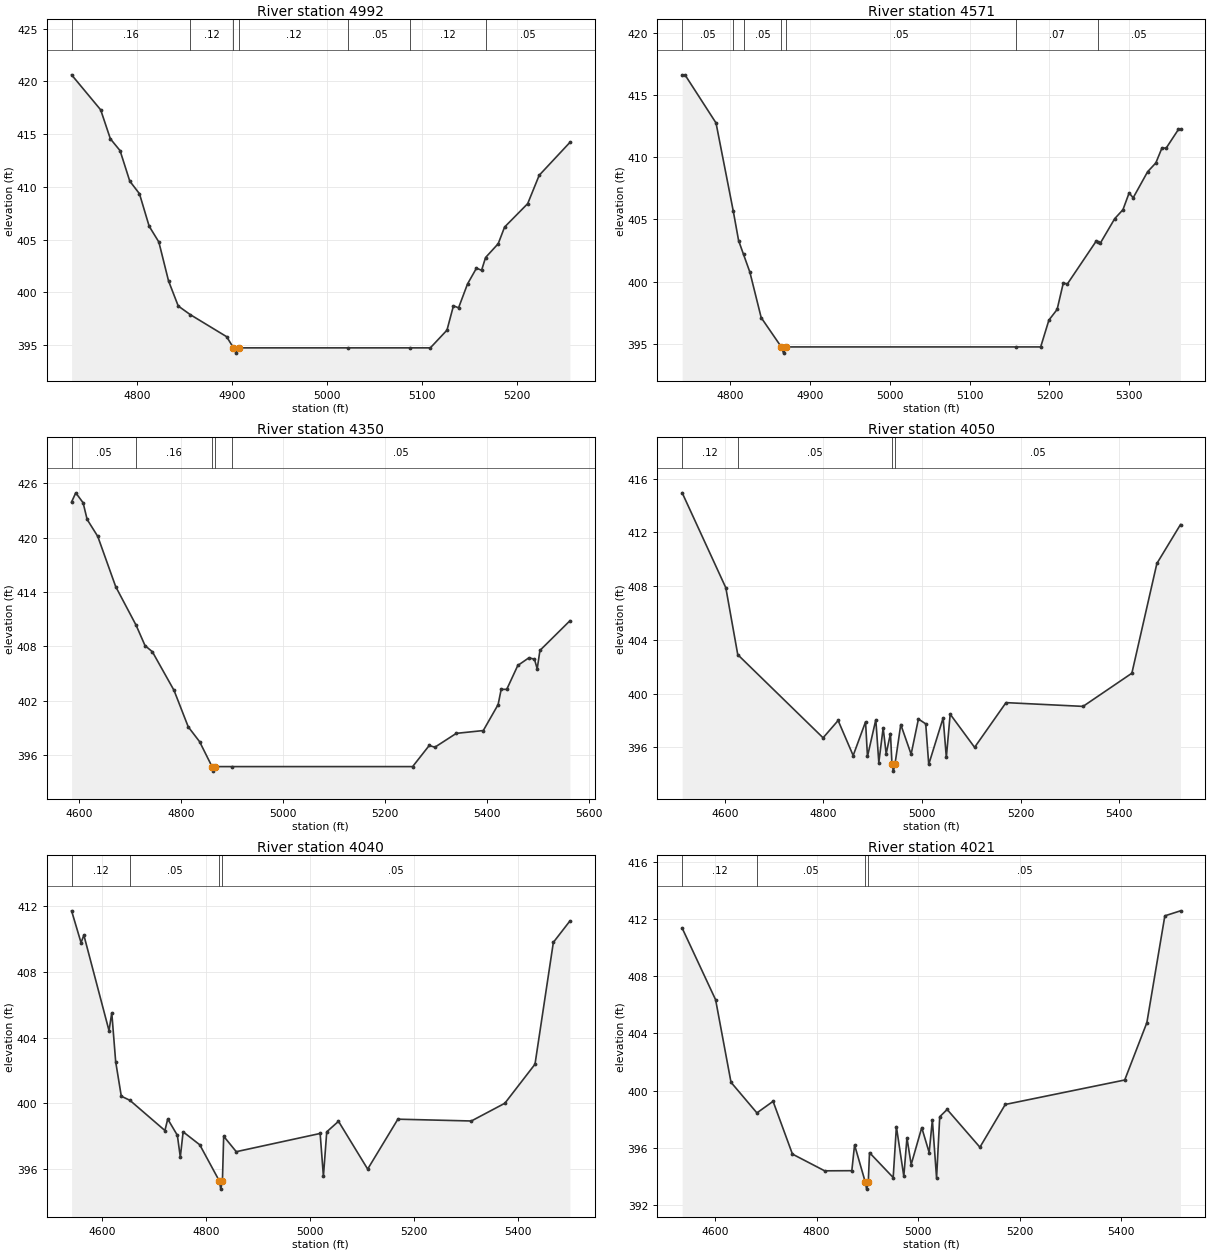
Type RM Length L Ch R = 1,4992,421,421,421
BEGIN DESCRIPTION:
UNT 141 IN CACR 11.0
END DESCRIPTION:
XS GIS Cut Line= 3
      3717249.63     10707660.19      3717499.61     10707710.19
      3717749.62     10707810.19
#Sta/Elev= 30
  4731.1  420.63  4761.7  417.31  4771.9  414.56  4782.1  413.44  4792.3  410.55
  4802.5  409.35  4812.7  406.27  4822.9  404.77  4833.1  401.08  4843.3  398.70
  4856.0  397.88  4894.2  395.79  4901.4  394.73  4904.2  394.23  4907.4  394.73
  5022.2  394.73  5087.5  394.73  5108.5  394.73  5126.0  396.41  5132.8  398.72
  5138.2  398.53  5147.6  400.79  5157.0  402.29  5162.4  402.09  5166.6  403.30
  5179.9  404.61  5186.6  406.19  5210.9  408.41  5223.0  411.10  5255.3  414.22
#Mann=7,-1,0
  4731.1    0.16       0  4856.0    0.12       0  4901.4    0.07       0
  4907.4    0.12       0  5022.2    0.05       0  5087.5    0.12       0
  5166.6    0.05       0
Bank Sta=4901.4,4907.4
Exp/Cntr=0.3,0.1

Type RM Length L Ch R = 1,4571,221,221,221
BEGIN DESCRIPTION:
UNT 141 IN CACR 10.0
END DESCRIPTION:
XS GIS Cut Line= 3
      3717149.63     10707960.21      3717299.61     10708110.19
      3717699.60     10708010.19
#Sta/Elev= 30
  4739.9  416.66  4743.4  416.66  4782.3  412.78  4803.9  405.68  4810.6  403.30
  4816.8  402.18  4824.7  400.76  4838.9  397.09  4864.1  394.73  4866.9  394.23
  4870.1  394.73  5157.7  394.73  5189.1  394.73  5199.4  396.89  5209.7  397.75
  5217.4  399.87  5222.6  399.81  5258.7  403.26  5260.7  403.19  5263.8  403.09
  5281.9  405.07  5292.2  405.79  5299.9  407.14  5305.0  406.75  5323.1  408.85
  5333.4  409.56  5341.1  410.77  5346.3  410.75  5361.7  412.26  5364.3  412.26
#Mann=7,-1,0
  4739.9    0.05       0  4803.9    0.16       0  4816.8    0.05       0
  4864.1   0.033       0  4870.1    0.05       0  5157.7    0.07       0
  5260.7    0.05       0
Bank Sta=4864.1,4870.1
Exp/Cntr=0.3,0.1

Type RM Length L Ch R = 1,4350,300,300,300
BEGIN DESCRIPTION:
UNT 141 IN CACR 9.0
END DESCRIPTION:
XS GIS Cut Line= 3
      3716952.99     10707954.39      3717256.83     10708327.68
      3717449.54     10708784.26
#Sta/Elev= 30
  4585.0  423.95  4593.2  424.96  4607.6  423.86  4615.5  422.02  4636.3  420.15
  4671.5  414.60  4711.5  410.34  4729.0  408.09  4743.4  407.41  4785.9  403.14
  4813.7  399.12  4836.0  397.48  4860.3  394.73  4863.0  394.23  4866.3  394.73
  4899.1  394.73  5253.6  394.73  5286.1  397.06  5297.2  396.87  5339.2  398.40
  5392.1  398.71  5421.2  401.58  5427.2  403.26  5438.1  403.26  5459.8  405.90
  5481.5  406.74  5492.4  406.59  5497.8  405.53  5503.2  407.56  5561.9  410.83
#Mann=5,-1,0
  4585.0    0.05       0  4711.5    0.16       0  4860.3   0.033       0
  4866.3    0.16       0  4899.1    0.05       0
Bank Sta=4860.3,4866.3
Exp/Cntr=0.3,0.1

Type RM Length L Ch R = 1,4050,10,10,10
BEGIN DESCRIPTION:
Mapping XS 78a5fc6c
END DESCRIPTION:
XS GIS Cut Line= 4
      3716805.24     10708038.83      3716935.46     10708392.59
      3717015.76     10708507.61      3717331.68     10708886.29
#Sta/Elev= 30
  4513.5  414.95  4602.0  407.88  4626.2  402.90  4799.2  396.71  4829.7  398.00
  4860.2  395.39  4885.3  397.90  4889.2  395.32  4906.1  398.06  4912.2  394.87
  4921.0  397.45  4927.1  395.52  4935.8  397.03  4938.9  394.73  4941.7  394.23
  4944.9  394.73  4956.7  397.70  4977.7  395.49  4992.5  398.11  5007.3  397.75
  5013.4  394.73  5042.6  398.19  5049.1  395.25  5056.9  398.47  5106.4  396.00
  5170.1  399.33  5326.3  399.05  5425.3  401.52  5476.0  409.69  5523.9  412.59
#Mann=4,-1,0
  4513.5    0.12       0  4626.2    0.05       0  4938.9   0.033       0
  4944.9    0.05       0
Bank Sta=4938.9,4944.9
Exp/Cntr=0.3,0.1

Type RM Length L Ch R = 1,4040,19,19,19
BEGIN DESCRIPTION:
Mapping XS c0a5f129
END DESCRIPTION:
XS GIS Cut Line= 3
      3716796.59     10708071.46      3716933.29     10708412.13
      3717293.56     10708880.91
#Sta/Elev= 30
  4541.2  411.73  4559.4  409.79  4564.8  410.25  4613.2  404.43  4618.5  405.52
  4626.0  402.54  4636.8  400.44  4653.3  400.19  4720.7  398.35  4726.1  399.05
  4744.6  398.06  4750.3  396.73  4755.7  398.27  4787.7  397.48  4825.3  395.28
  4828.1  394.78  4831.3  395.28  4833.7  398.00  4857.9  397.06  5019.2  398.17
  5025.5  395.56  5031.9  398.27  5054.5  398.91  5110.6  396.00  5168.7  399.04
  5310.0  398.93  5374.4  400.01  5432.4  402.39  5467.7  409.81  5499.5  411.11
#Mann=4,-1,0
  4541.2    0.12       0  4653.3    0.05       0  4825.3   0.033       0
  4831.3    0.05       0
Bank Sta=4825.3,4831.3
Exp/Cntr=0.3,0.1

Type RM Length L Ch R = 1,4021,432,432,432
BEGIN DESCRIPTION:
Mapping XS bd839d59
END DESCRIPTION:
XS GIS Cut Line= 3
      3716777.05     10708069.28      3716922.44     10708425.15
      3717282.69     10708900.42
#Sta/Elev= 30
  4535.5  411.36  4601.3  406.35  4631.6  400.58  4682.6  398.44  4714.4  399.25
  4752.5  395.56  4815.9  394.39  4869.4  394.40  4874.8  396.20  4895.8  393.61
  4898.5  393.11  4901.8  393.61  4904.2  395.66  4950.8  393.92  4957.1  397.48
  4971.7  394.01  4977.9  396.69  4986.2  394.83  5007.0  397.41  5021.6  395.67
  5027.9  397.94  5036.2  393.88  5042.4  398.17  5057.0  398.68  5121.5  396.04
  5171.4  399.03  5406.5  400.74  5450.1  404.75  5485.5  412.22  5516.3  412.57
#Mann=4,-1,0
  4535.5    0.12       0  4682.6    0.05       0  4895.8    0.03       0
  4901.8    0.05       0
Bank Sta=4895.8,4901.8
Exp/Cntr=0.3,0.1

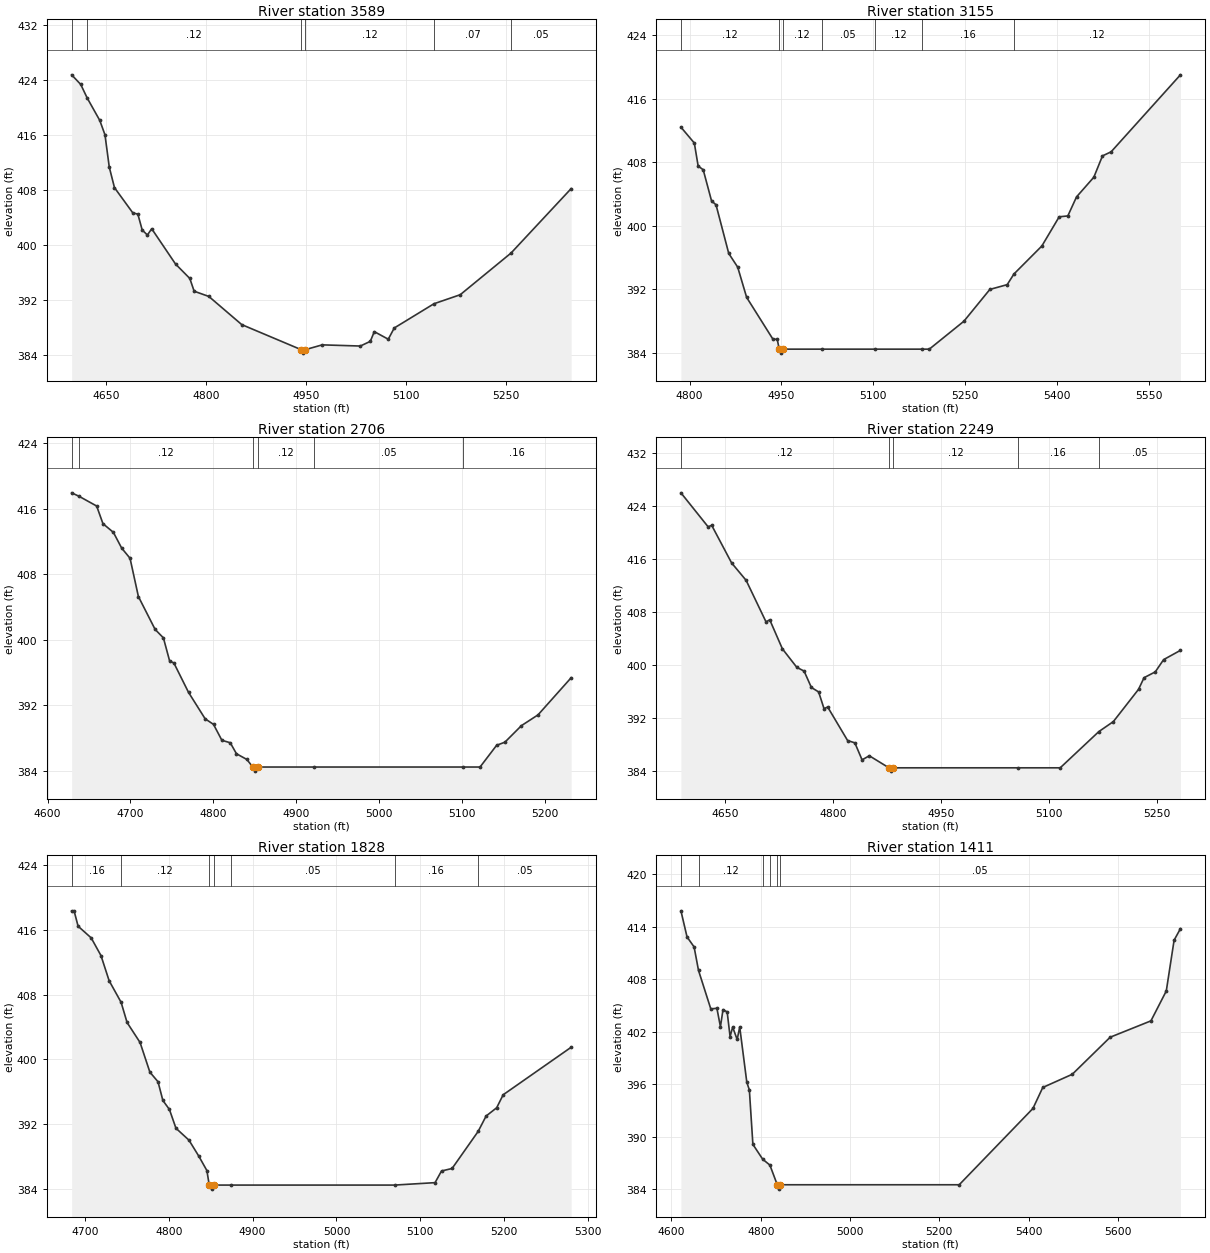
Type RM Length L Ch R = 1,3589,434,434,434
BEGIN DESCRIPTION:
UNT 141 IN CACR 8.0
END DESCRIPTION:
XS GIS Cut Line= 3
      3716349.62     10708460.20      3716649.61     10708710.19
      3716949.65     10708910.21
#Sta/Elev= 30
  4597.6  424.70  4611.3  423.30  4620.8  421.37  4639.9  418.08  4647.7  416.00
  4654.2  411.29  4662.0  408.32  4689.4  404.68  4697.2  404.46  4703.7  402.17
  4711.5  401.44  4718.0  402.35  4753.8  397.23  4775.3  395.13  4781.8  393.28
  4803.9  392.52  4853.4  388.43  4942.8  384.79  4945.5  384.29  4948.8  384.79
  4974.4  385.49  5031.7  385.32  5046.7  386.00  5052.7  387.41  5073.7  386.31
  5082.7  387.94  5142.4  391.46  5181.9  392.77  5258.4  398.83  5348.7  408.18
#Mann=6,-1,0
  4597.6    0.05       0  4620.8    0.12       0  4942.8    0.07       0
  4948.8    0.12       0  5142.4    0.07       0  5258.4    0.05       0
Bank Sta=4942.8,4948.8
Exp/Cntr=0.3,0.1

Type RM Length L Ch R = 1,3155,449,449,449
BEGIN DESCRIPTION:
UNT 141 IN CACR 7.0
END DESCRIPTION:
XS GIS Cut Line= 3
      3716249.62     10708860.20      3716399.61     10709060.19
      3716799.63     10709460.21
#Sta/Elev= 30
  4786.0  412.40  4807.9  410.40  4814.1  407.52  4822.4  407.04  4836.0  403.13
  4843.3  402.64  4864.1  396.52  4878.7  394.80  4893.3  391.00  4936.0  385.77
  4943.3  385.71  4946.5  384.49  4949.3  383.99  4952.5  384.49  5015.8  384.49
  5102.5  384.49  5179.9  384.49  5191.6  384.49  5248.1  388.00  5290.5  392.00
  5318.8  392.60  5329.8  393.94  5375.4  397.46  5403.7  401.13  5417.8  401.24
  5432.0  403.63  5460.3  406.11  5474.4  408.79  5488.5  409.30  5601.7  418.98
#Mann=7,-1,0
  4786.0    0.12       0  4946.5    0.07       0  4952.5    0.12       0
  5015.8    0.05       0  5102.5    0.12       0  5179.9    0.16       0
  5329.8    0.12       0
Bank Sta=4946.5,4952.5
Exp/Cntr=0.3,0.1

Type RM Length L Ch R = 1,2706,457,457,457
BEGIN DESCRIPTION:
UNT 141 IN CACR 6.0
END DESCRIPTION:
XS GIS Cut Line= 3
      3715999.61     10708960.21      3716049.61     10709360.19
      3716049.61     10709560.20
#Sta/Elev= 30
  4629.0  417.93  4638.1  417.50  4659.2  416.32  4666.8  414.17  4679.4  413.11
  4689.4  411.19  4699.5  409.95  4709.6  405.28  4729.8  401.27  4739.8  400.24
  4747.4  397.39  4752.4  397.19  4770.1  393.60  4790.2  390.37  4800.3  389.69
  4810.4  387.75  4820.5  387.45  4828.0  386.11  4840.6  385.41  4847.7  384.49
  4850.4  383.99  4853.7  384.49  4921.4  384.49  5101.8  384.49  5122.1  384.49
  5142.1  387.14  5152.1  387.52  5172.1  389.54  5192.1  390.85  5232.1  395.38
#Mann=6,-1,0
  4629.0    0.05       0  4638.1    0.12       0  4847.7   0.033       0
  4853.7    0.12       0  4921.4    0.05       0  5101.8    0.16       0
Bank Sta=4847.7,4853.7
Exp/Cntr=0.3,0.1

Type RM Length L Ch R = 1,2249,421,421,421
BEGIN DESCRIPTION:
UNT 141 IN CACR 5.0
END DESCRIPTION:
XS GIS Cut Line= 3
      3715299.61     10709560.19      3715699.61     10709610.19
      3715949.64     10709760.21
#Sta/Elev= 30
  4588.5  426.02  4626.3  420.89  4631.3  421.11  4659.0  415.43  4679.2  412.80
  4706.9  406.52  4712.0  406.85  4729.6  402.46  4749.7  399.66  4759.8  399.10
  4769.9  396.63  4780.0  395.95  4787.5  393.43  4792.6  393.67  4820.3  388.61
  4830.4  388.26  4840.4  385.69  4850.5  386.31  4877.8  384.49  4880.5  383.99
  4883.8  384.49  5056.9  384.49  5116.0  384.49  5169.7  389.96  5189.9  391.47
  5224.9  396.34  5232.6  398.10  5248.2  398.98  5259.8  400.83  5283.2  402.23
#Mann=5,-1,0
  4588.5    0.12       0  4877.8   0.033       0  4883.8    0.12       0
  5056.9    0.16       0  5169.7    0.05       0
Bank Sta=4877.8,4883.8
Exp/Cntr=0.3,0.1

Type RM Length L Ch R = 1,1828,417,417,417
BEGIN DESCRIPTION:
UNT 141 IN CACR 4.0
END DESCRIPTION:
XS GIS Cut Line= 3
      3715299.63     10709860.20      3715549.61     10710010.19
      3715849.65     10710060.20
#Sta/Elev= 30
  4684.2  418.36  4687.1  418.36  4691.9  416.46  4707.5  415.02  4719.2  412.83
  4728.9  409.73  4743.2  407.06  4750.3  404.57  4765.8  402.10  4777.5  398.44
  4787.2  397.25  4793.0  394.94  4800.8  393.83  4808.6  391.51  4824.1  390.04
  4835.8  388.07  4845.5  386.28  4848.3  384.49  4851.1  383.99  4854.3  384.49
  4874.1  384.49  5069.3  384.49  5117.6  384.79  5125.3  386.23  5137.9  386.54
  5169.0  391.12  5178.5  393.02  5191.1  394.04  5198.8  395.64  5279.9  401.51
#Mann=7,-1,0
  4684.2    0.16       0  4743.2    0.12       0  4848.3   0.033       0
  4854.3    0.12       0  4874.1    0.05       0  5069.3    0.16       0
  5169.0    0.05       0
Bank Sta=4848.3,4854.3
Exp/Cntr=0.3,0.1

Type RM Length L Ch R = 1,1411,169,169,169
BEGIN DESCRIPTION:
UNT 141 IN CACR 3.0
END DESCRIPTION:
XS GIS Cut Line= 3
      3715149.62     10710010.20      3715349.61     10710360.19
      3715999.62     10710660.19
#Sta/Elev= 30
  4621.3  415.83  4635.0  412.84  4650.8  411.70  4660.7  409.01  4688.2  404.61
  4701.9  404.68  4709.8  402.57  4715.6  404.53  4724.9  404.26  4731.4  401.44
  4737.2  402.52  4747.3  401.11  4753.0  402.54  4768.9  396.21  4774.6  395.34
  4782.5  389.11  4804.5  387.41  4820.6  386.74  4837.1  384.49  4839.9  383.99
  4843.1  384.49  5244.7  384.49  5409.9  393.22  5431.9  395.62  5498.0  397.13
  5582.9  401.37  5674.2  403.24  5708.6  406.66  5726.1  412.47  5740.3  413.79
#Mann=6,-1,0
  4621.3    0.16       0  4660.7    0.12       0  4804.5    0.16       0
  4820.6    0.05       0  4837.1   0.033       0  4843.1    0.05       0
Bank Sta=4837.1,4843.1
Exp/Cntr=0.3,0.1

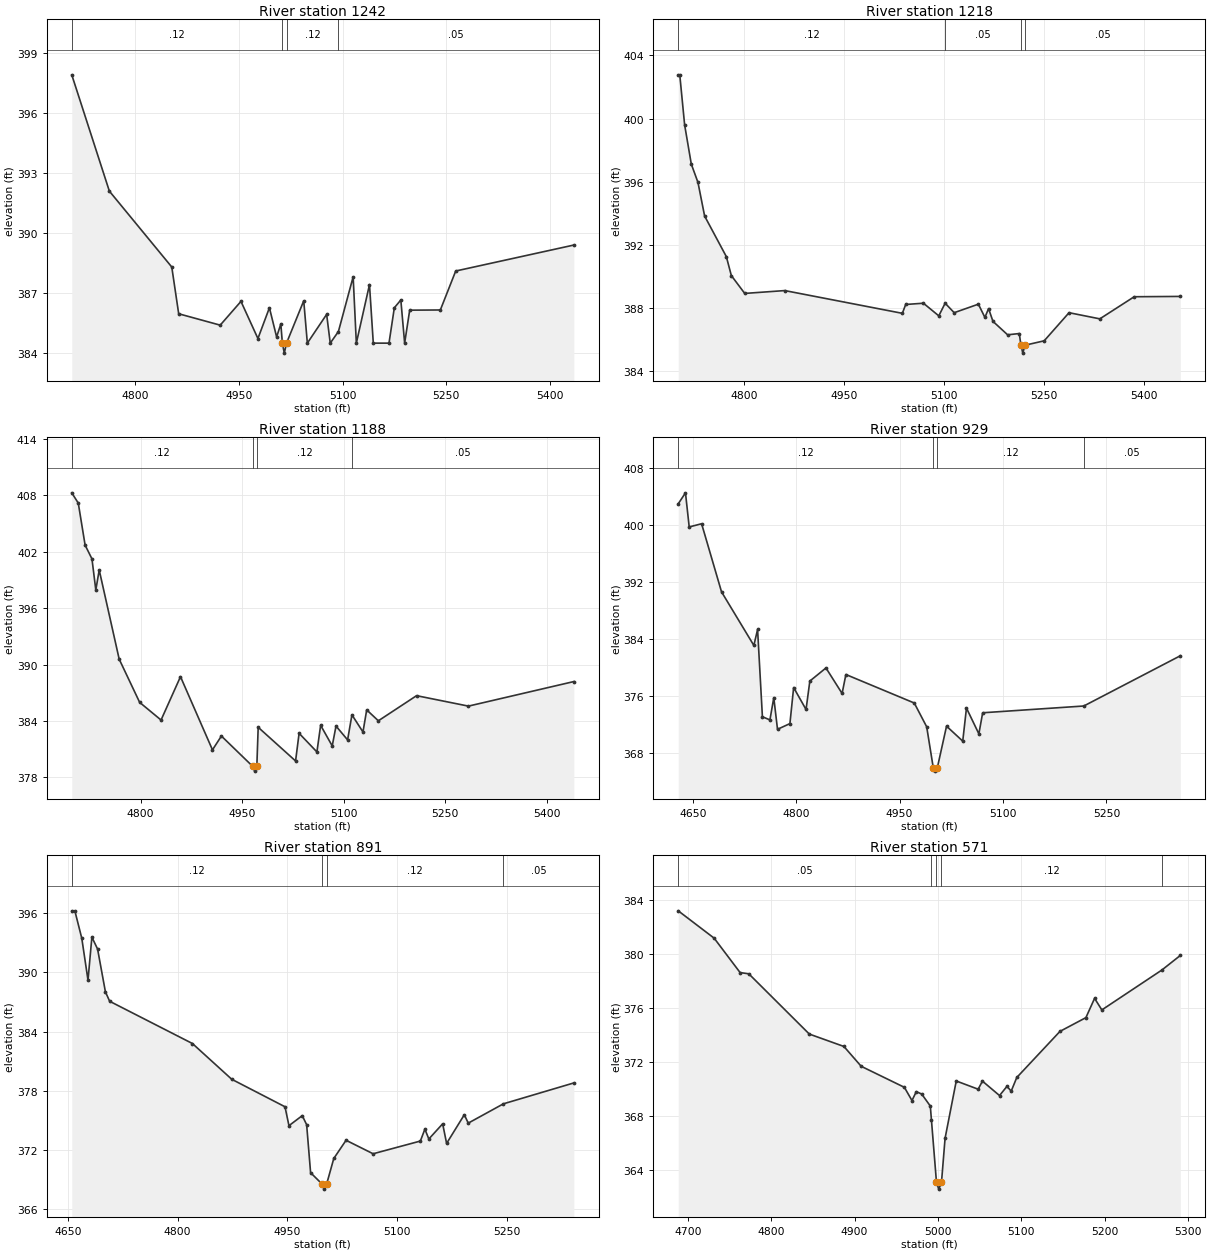
Type RM Length L Ch R = 1,1242,24,24,24
BEGIN DESCRIPTION:
Mapping XS 1402acae
END DESCRIPTION:
XS GIS Cut Line= 5
      3715180.87     10710106.01      3715172.18     10710225.40
      3715172.18     10710365.37      3715216.67     10710514.03
      3715351.24     10710794.02
#Sta/Elev= 30
  4708.7  397.92  4763.0  392.10  4853.2  388.30  4863.2  385.96  4923.2  385.39
  4953.2  386.58  4977.7  384.72  4994.3  386.26  5004.7  384.80  5010.8  385.45
  5013.0  384.49  5015.8  383.99  5019.0  384.49  5043.9  386.61  5049.1  384.49
  5077.0  385.93  5082.2  384.49  5094.0  385.07  5115.3  387.81  5119.9  384.49
  5138.9  387.42  5144.4  384.49  5167.1  384.49  5174.8  386.26  5184.2  386.65
  5189.7  384.49  5197.0  386.14  5241.3  386.15  5263.5  388.10  5434.2  389.40
#Mann=4,-1,0
  4708.7    0.12       0  5013.0    0.07       0  5019.0    0.12       0
  5094.0    0.05       0
Bank Sta=5013,5019
Exp/Cntr=0.3,0.1

Type RM Length L Ch R = 1,1218,30,30,30
BEGIN DESCRIPTION:
Mapping XS bfb4deb1
END DESCRIPTION:
XS GIS Cut Line= 5
      3715159.16     10710100.65      3715147.23     10710282.91
      3715151.57     10710361.03      3715166.76     10710447.84
      3715334.18     10710816.16
#Sta/Elev= 30
  4701.1  402.77  4703.4  402.77  4710.7  399.60  4720.7  397.12  4730.7  395.96
  4740.7  393.83  4773.3  391.26  4780.8  390.06  4800.9  388.93  4861.0  389.11
  5037.5  387.67  5042.5  388.23  5069.1  388.31  5092.2  387.51  5101.7  388.31
  5115.3  387.71  5151.6  388.25  5161.4  387.41  5166.9  387.97  5173.5  387.16
  5195.5  386.31  5213.0  386.39  5215.5  385.65  5218.3  385.15  5221.5  385.65
  5250.4  385.93  5287.7  387.71  5333.9  387.32  5385.5  388.72  5454.7  388.74
#Mann=4,-1,0
  4701.1    0.12       0  5101.7    0.05       0  5215.5    0.07       0
  5221.5    0.05       0
Bank Sta=5215.5,5221.5
Exp/Cntr=0.3,0.1

Type RM Length L Ch R = 1,1188,259,259,259
BEGIN DESCRIPTION:
Mapping XS f6f16c3d
END DESCRIPTION:
XS GIS Cut Line= 5
      3715138.55     10710100.61      3715115.76     10710308.95
      3715130.95     10710418.54      3715140.72     10710453.26
      3715306.75     10710800.52
#Sta/Elev= 30
  4698.5  408.25  4708.1  407.16  4718.2  402.69  4728.3  401.23  4734.0  397.92
  4739.0  400.05  4768.5  390.57  4798.7  385.98  4830.3  384.10  4859.0  388.71
  4906.2  380.93  4919.4  382.40  4965.7  379.17  4968.4  378.67  4971.7  379.17
  4973.7  383.33  5028.9  379.75  5034.1  382.69  5060.4  380.71  5065.9  383.54
  5083.0  381.35  5088.6  383.46  5105.7  381.99  5112.1  384.65  5128.4  382.83
  5133.9  385.18  5151.1  384.02  5207.5  386.69  5284.1  385.58  5439.7  388.19
#Mann=4,-1,0
  4698.5    0.12       0  4965.7    0.07       0  4971.7    0.12       0
  5112.1    0.05       0
Bank Sta=4965.7,4971.7
Exp/Cntr=0.3,0.1

Type RM Length L Ch R = 1,929,38,38,38
BEGIN DESCRIPTION:
UNT 141 IN CACR 2.0
END DESCRIPTION:
XS GIS Cut Line= 2
      3715059.96     10710118.27      3714769.27     10710786.04
#Sta/Elev= 30
  4628.9  402.94  4639.4  404.48  4644.8  399.69  4662.8  400.14  4691.7  390.58
  4738.6  383.06  4744.0  385.30  4751.0  373.05  4761.9  372.61  4767.5  375.73
  4772.9  371.29  4790.9  372.09  4796.3  377.15  4814.3  374.07  4819.8  378.06
  4843.2  379.90  4866.6  376.32  4872.1  378.98  4971.3  374.98  4989.3  371.64
  4998.8  365.92  5001.6  365.42  5004.8  365.92  5018.1  371.73  5041.6  369.63
  5047.0  374.27  5065.0  370.65  5070.5  373.61  5217.2  374.56  5357.2  381.61
#Mann=4,-1,0
  4628.9    0.12       0  4998.8    0.07       0  5004.8    0.12       0
  5217.2    0.05       0
Bank Sta=4998.8,5004.8
Exp/Cntr=0.3,0.1

Type RM Length L Ch R = 1,891,320,320,320
BEGIN DESCRIPTION:
Mapping XS d8e5349c
END DESCRIPTION:
XS GIS Cut Line= 2
      3715003.95     10710127.44      3714749.40     10710765.11
#Sta/Elev= 30
  4655.4  396.25  4659.6  396.25  4669.1  393.46  4677.6  389.21  4682.9  393.58
  4690.7  392.37  4701.4  388.03  4707.2  387.07  4820.4  382.78  4874.2  379.15
  4947.0  376.36  4952.4  374.44  4970.6  375.46  4976.6  374.54  4982.0  369.67
  4997.9  368.50  5000.7  368.00  5003.9  368.50  5013.7  371.11  5030.5  372.96
  5067.5  371.59  5132.1  372.88  5138.3  374.09  5143.7  373.09  5162.6  374.63
  5168.0  372.64  5192.2  375.55  5197.6  374.70  5245.7  376.66  5342.0  378.78
#Mann=4,-1,0
  4655.4    0.12       0  4997.9    0.07       0  5003.9    0.12       0
  5245.7    0.05       0
Bank Sta=4997.9,5003.9
Exp/Cntr=0.3,0.1

Type RM Length L Ch R = 1,571,496,496,496
BEGIN DESCRIPTION:
Mapping XS 8b6795e2
END DESCRIPTION:
XS GIS Cut Line= 2
      3714489.63     10710188.57      3714648.50     10710769.34
#Sta/Elev= 30
  4688.5  383.19  4731.6  381.16  4762.7  378.61  4773.1  378.52  4845.7  374.05
  4887.2  373.13  4907.9  371.66  4959.7  370.10  4968.8  369.12  4974.0  369.78
  4980.5  369.60  4990.8  368.71  4992.2  367.64  4998.2  363.05  5000.9  362.55
  5004.2  363.05  5008.5  366.32  5021.9  370.57  5048.2  369.96  5053.3  370.56
  5073.8  369.49  5082.7  370.17  5087.8  369.82  5094.5  370.83  5146.3  374.25
  5177.4  375.27  5187.8  376.70  5196.5  375.84  5268.5  378.80  5290.6  379.88
#Mann=5,-1,0
  4688.5    0.05       0  4992.2    0.12       0  4998.2    0.07       0
  5004.2    0.12       0  5268.5    0.05       0
Bank Sta=4998.2,5004.2
Exp/Cntr=0.3,0.1

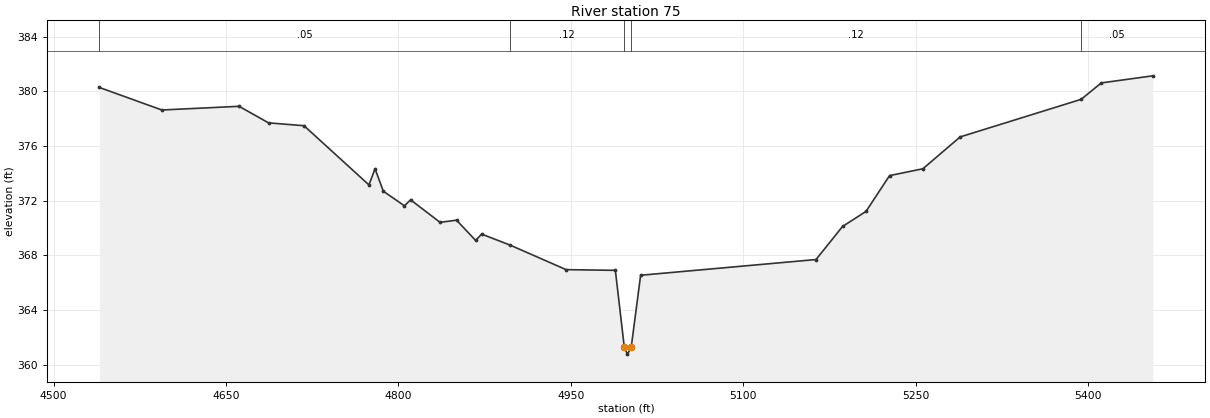
Type RM Length L Ch R = 1,75,0,0,0
BEGIN DESCRIPTION:
UNT 141 IN CACR 1.0
END DESCRIPTION:
XS GIS Cut Line= 4
      3714283.91     10710277.17      3714145.89     10710667.78
      3714177.14     10710748.50      3714583.37     10710837.04
#Sta/Elev= 30
  4539.8  380.28  4594.2  378.63  4661.4  378.90  4687.0  377.69  4717.9  377.48
  4774.4  373.15  4779.7  374.33  4786.9  372.69  4805.3  371.62  4810.6  372.06
  4836.3  370.41  4850.6  370.57  4867.2  369.09  4872.5  369.55  4897.1  368.75
  4946.0  366.95  4988.8  366.90  4996.6  361.27  4999.3  360.77  5002.6  361.27
  5010.8  366.54  5163.4  367.69  5186.5  370.11  5206.9  371.21  5227.4  373.83
  5256.4  374.33  5288.8  376.66  5394.1  379.41  5411.6  380.61  5456.4  381.13
#Mann=5,-1,0
  4539.8    0.05       0  4897.1    0.12       0  4996.6    0.07       0
  5002.6    0.12       0  5394.1    0.05       0
Bank Sta=4996.6,5002.6
Exp/Cntr=0.3,0.1

Chan Stop Cuts=-1