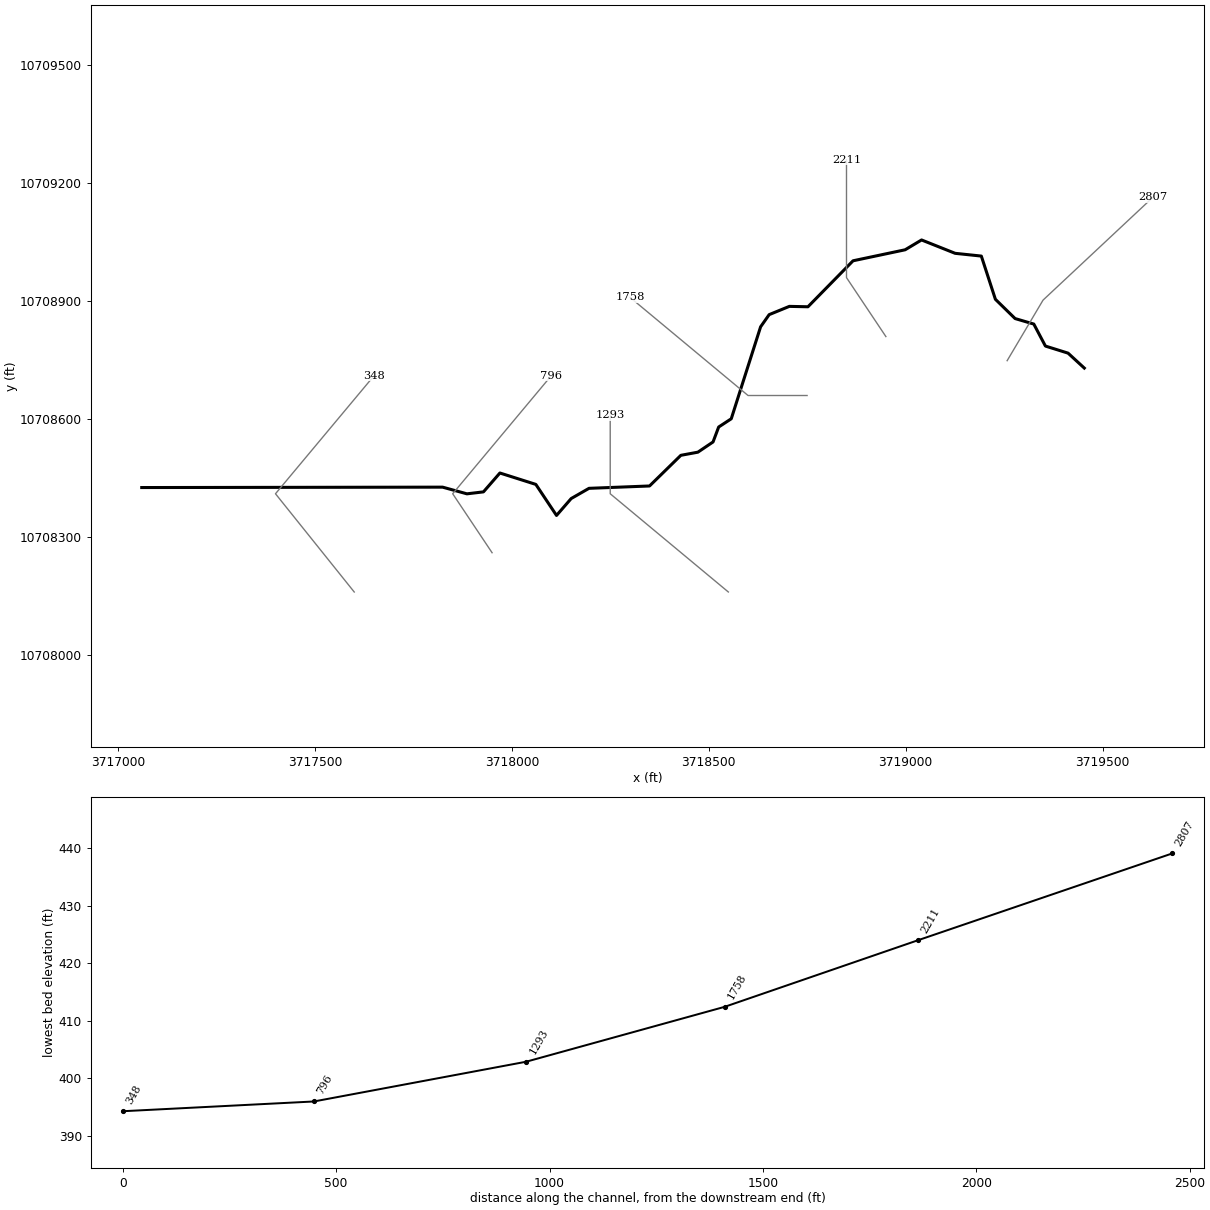
--- UNT 142 IN CACR.prj (project) ---

Proj Title=UNT 142 IN CACR Base Level Engineering
Current Plan=p01
Default Exp/Contr=0.3,0.1
English Units
Geom File=g01
Flow File=f01
Plan File=p01
BEGIN DESCRIPTION:
UNT 142 IN CACR
END DESCRIPTION:

--- UNT 142 IN CACR.p01 (plan) ---

Plan Title=Multiple Run
Short Identifier=Multiple
Geom File=g01
Flow File=f01
Subcritical Flow
K Sum by GR= 0
Std Step Tol= 0.01
Critical Tol= 0.01
Num of Std Step Trials= 20
Max Error Tol= 0.3
Flow Tol Ratio= 0.001
Split Flow NTrial= 30
Split Flow Tol= 0.02
Split Flow Ratio= 0.02
Log Output Level= 0
Friction Slope Method= 1
Unsteady Friction Slope Method= 2
Unsteady Bridges Friction Slope Method= 1
Parabolic Critical Depth
Global Vel Dist=  1 , 1 , 1
Global Log Level= 0
CheckData=True
Encroach Param= -1, 0, 0, 0
BEGIN DESCRIPTION:
Multiple Run
END DESCRIPTION:

--- UNT 142 IN CACR.f01 (steady flow) ---

Flow Title=Multiple
Number of Profiles=7
Profile Names=10-year,25-year,50-year,1pct_min,100-year,1pct_plu,500-year
River Rch & RM= UNT 142 IN CACR,Reach-1,2807
     258     336     399     350     473     639     665
Boundary for River Rch & Prof#=UNT 142 IN CACR,Reach-1,1
Up Type=0
Dn Type=3
Dn Slope=0.005
Boundary for River Rch & Prof#=UNT 142 IN CACR,Reach-1,2
Up Type=0
Dn Type=3
Dn Slope=0.005
Boundary for River Rch & Prof#=UNT 142 IN CACR,Reach-1,3
Up Type=0
Dn Type=3
Dn Slope=0.005
Boundary for River Rch & Prof#=UNT 142 IN CACR,Reach-1,4
Up Type=0
Dn Type=3
Dn Slope=0.005
Boundary for River Rch & Prof#=UNT 142 IN CACR,Reach-1,5
Up Type=0
Dn Type=3
Dn Slope=0.005
Boundary for River Rch & Prof#=UNT 142 IN CACR,Reach-1,6
Up Type=0
Dn Type=3
Dn Slope=0.005
Boundary for River Rch & Prof#=UNT 142 IN CACR,Reach-1,7
Up Type=0
Dn Type=3
Dn Slope=0.005

--- UNT 142 IN CACR.g01 (geometry) ---

Geom Title=Existing Conditions

River Reach=UNT 142 IN CACR,Reach-1
Reach XY= 30
      3719453.50     10708730.00      3719412.25     10708768.00
      3719354.75     10708786.00      3719325.25     10708842.00
      3719277.75     10708856.00      3719227.75     10708905.00
      3719192.00     10709015.00      3719125.50     10709022.00
      3719040.25     10709056.00      3718998.50     10709031.00
      3718866.25     10709003.00      3718751.75     10708886.00
      3718704.50     10708887.00      3718653.25     10708866.00
      3718631.50     10708835.00      3718557.00     10708601.00
      3718525.00     10708580.00      3718510.75     10708542.00
      3718472.25     10708516.00      3718429.00     10708508.00
      3718349.50     10708430.00      3718195.75     10708424.00
      3718150.50     10708398.00      3718113.25     10708355.00
      3718060.75     10708434.00      3717969.50     10708463.00
      3717927.75     10708415.00      3717885.75     10708410.00
      3717824.00     10708427.00      3717060.00     10708426.00

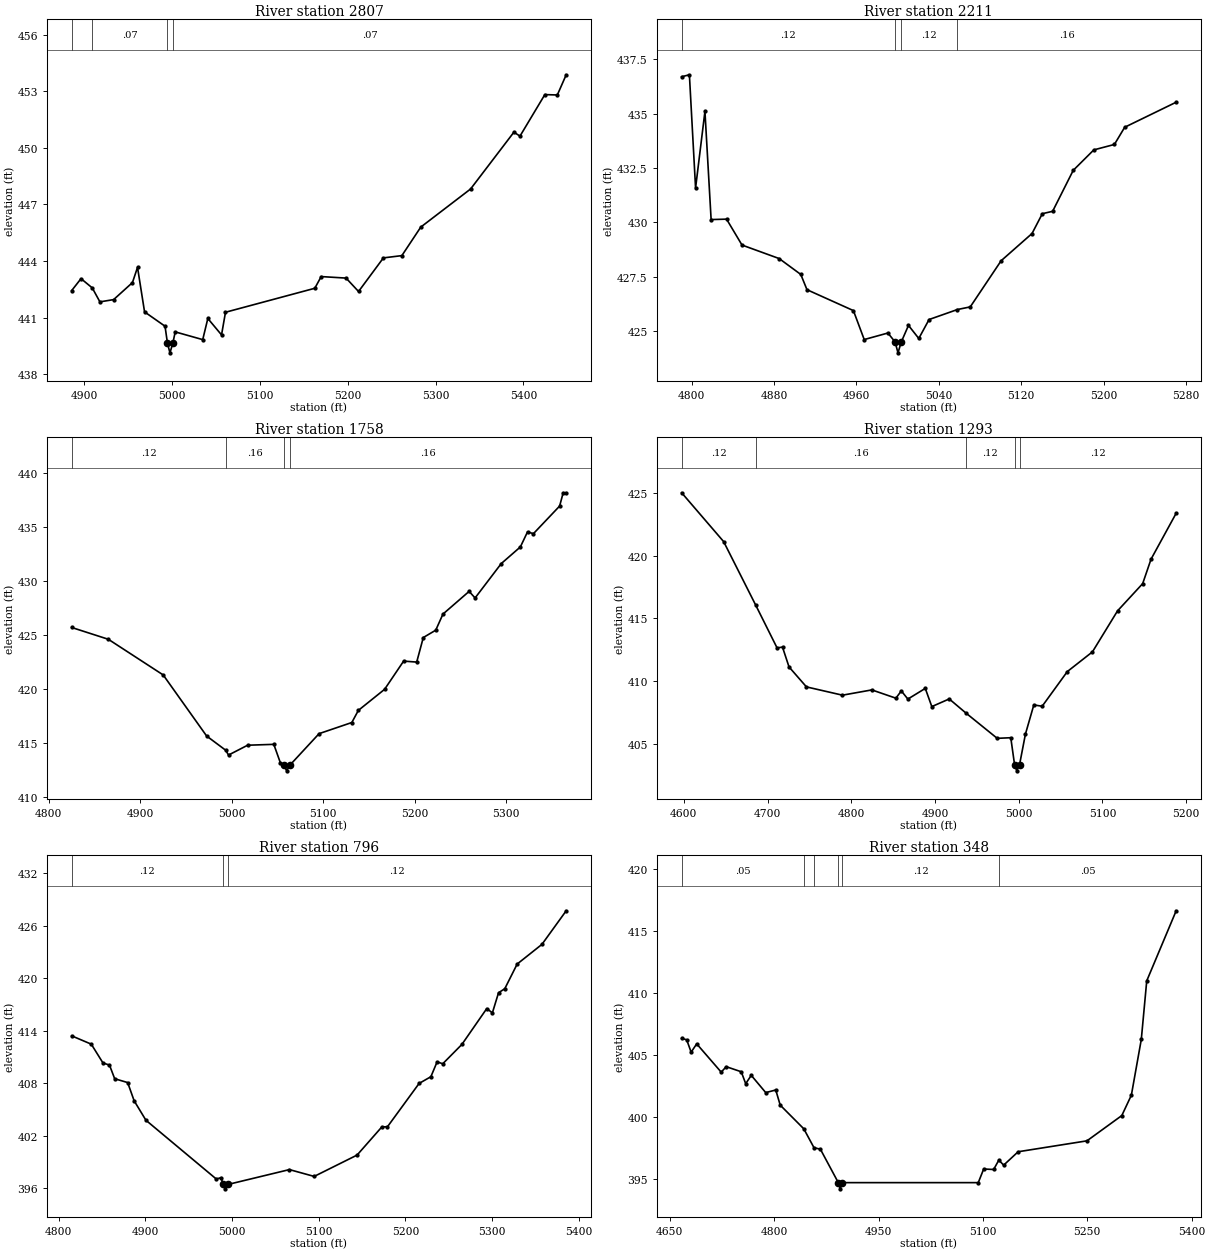
Type RM Length L Ch R = 1,2807,596,596,596
BEGIN DESCRIPTION:
Mapping XS 6300d674
END DESCRIPTION:
XS GIS Cut Line= 3
      3719257.57     10708748.81      3719348.73     10708902.92
      3719628.54     10709165.38
#Sta/Elev= 30
  4886.0  442.44  4896.6  443.07  4909.4  442.58  4918.1  441.84  4933.7  441.96
  4955.1  442.86  4960.9  443.67  4968.9  441.31  4992.2  440.55  4995.0  439.64
  4997.8  439.14  5001.0  439.64  5003.8  440.25  5035.1  439.84  5040.9  440.96
  5056.5  440.09  5061.0  441.29  5162.6  442.56  5169.9  443.18  5198.2  443.10
  5212.4  442.39  5240.7  444.17  5261.7  444.29  5283.2  445.80  5339.9  447.82
  5389.2  450.83  5396.1  450.62  5424.4  452.82  5438.6  452.80  5448.7  453.87
#Mann=4,-1,0
  4886.0    0.12       0  4909.4    0.07       0  4995.0    0.07       0
  5001.0    0.07       0
Bank Sta=4995,5001
Exp/Cntr=0.3,0.1

Type RM Length L Ch R = 1,2211,453,453,453
BEGIN DESCRIPTION:
UNT 142 IN CACR 5.0
END DESCRIPTION:
XS GIS Cut Line= 3
      3718949.62     10708810.17      3718849.61     10708960.19
      3718849.61     10709260.19
#Sta/Elev= 30
  4790.2  436.69  4797.7  436.78  4803.7  431.58  4812.8  435.10  4818.8  430.13
  4833.8  430.15  4848.8  428.96  4884.9  428.34  4905.9  427.61  4911.9  426.91
  4957.0  425.95  4967.5  424.62  4990.5  424.92  4997.5  424.51  5000.3  424.01
  5003.5  424.51  5010.5  425.27  5020.5  424.67  5030.5  425.54  5058.1  426.00
  5070.5  426.12  5100.5  428.24  5130.5  429.49  5140.5  430.40  5150.5  430.51
  5170.5  432.39  5190.5  433.33  5210.5  433.58  5220.5  434.37  5270.5  435.52
#Mann=4,-1,0
  4790.2    0.12       0  4997.5    0.07       0  5003.5    0.12       0
  5058.1    0.16       0
Bank Sta=4997.5,5003.5
Exp/Cntr=0.3,0.1

Type RM Length L Ch R = 1,1758,465,465,465
BEGIN DESCRIPTION:
UNT 142 IN CACR 4.0
END DESCRIPTION:
XS GIS Cut Line= 3
      3718749.58     10708660.19      3718599.61     10708660.19
      3718299.59     10708910.20
#Sta/Elev= 30
  4825.0  425.67  4865.0  424.58  4925.0  421.28  4972.5  415.63  4993.4  414.31
  4996.4  413.87  5017.3  414.78  5045.9  414.86  5053.1  413.15  5057.2  412.91
  5060.0  412.41  5063.2  412.91  5095.4  415.85  5131.2  416.88  5138.3  418.00
  5167.0  419.95  5187.8  422.56  5202.1  422.47  5209.3  424.74  5222.9  425.42
  5230.8  426.91  5259.4  429.01  5265.9  428.40  5294.5  431.58  5315.4  433.12
  5323.2  434.51  5329.7  434.35  5358.3  436.90  5362.2  438.13  5365.5  438.13
#Mann=4,-1,0
  4825.0    0.12       0  4993.4    0.16       0  5057.2    0.07       0
  5063.2    0.16       0
Bank Sta=5057.2,5063.2
Exp/Cntr=0.3,0.1

Type RM Length L Ch R = 1,1293,497,497,497
BEGIN DESCRIPTION:
UNT 142 IN CACR 3.0
END DESCRIPTION:
XS GIS Cut Line= 3
      3718549.59     10708160.21      3718249.61     10708410.19
      3718249.61     10708610.21
#Sta/Elev= 30
  4597.5  425.01  4647.6  421.12  4685.8  416.07  4711.4  412.65  4717.9  412.71
  4725.7  411.13  4746.5  409.54  4789.5  408.88  4824.6  409.30  4853.3  408.64
  4859.8  409.22  4867.6  408.57  4888.4  409.42  4896.2  407.97  4917.0  408.58
  4936.7  407.47  4974.3  405.44  4990.5  405.49  4995.0  403.35  4997.7  402.85
  5001.0  403.35  5008.0  405.78  5018.0  408.10  5028.0  408.00  5058.0  410.76
  5088.0  412.33  5118.0  415.60  5148.0  417.77  5158.0  419.72  5188.0  423.38
#Mann=5,-1,0
  4597.5    0.12       0  4685.8    0.16       0  4936.7    0.12       0
  4995.0    0.07       0  5001.0    0.12       0
Bank Sta=4995,5001
Exp/Cntr=0.3,0.1

Type RM Length L Ch R = 1,796,448,448,448
BEGIN DESCRIPTION:
UNT 142 IN CACR 2.0
END DESCRIPTION:
XS GIS Cut Line= 3
      3717949.63     10708260.16      3717849.61     10708410.19
      3718099.59     10708710.17
#Sta/Elev= 30
  4814.9  413.42  4837.5  412.47  4851.0  410.32  4858.5  410.08  4864.5  408.52
  4879.5  408.08  4887.0  405.99  4900.6  403.77  4981.7  397.06  4987.7  397.21
  4989.2  396.43  4992.0  395.93  4995.2  396.43  5066.2  398.13  5094.8  397.35
  5144.3  399.79  5172.9  403.01  5179.4  403.03  5215.9  407.98  5229.5  408.75
  5236.7  410.45  5243.2  410.23  5265.3  412.44  5294.0  416.54  5300.5  416.05
  5307.6  418.35  5314.8  418.81  5329.1  421.63  5357.7  423.88  5385.7  427.72
#Mann=3,-1,0
  4814.9    0.12       0  4989.2    0.07       0  4995.2    0.12       0
Bank Sta=4989.2,4995.2
Exp/Cntr=0.3,0.1

Type RM Length L Ch R = 1,348,0,0,0
BEGIN DESCRIPTION:
UNT 142 IN CACR 1.0
END DESCRIPTION:
XS GIS Cut Line= 3
      3717599.59     10708160.21      3717399.61     10708410.19
      3717649.58     10708710.16
#Sta/Elev= 30
  4667.1  406.36  4674.3  406.25  4680.7  405.25  4688.7  405.92  4723.9  403.64
  4731.1  404.08  4752.7  403.67  4759.1  402.71  4767.1  403.38  4787.9  401.99
  4802.3  402.20  4808.7  400.98  4842.6  399.07  4857.3  397.54  4866.4  397.43
  4892.2  394.73  4894.9  394.23  4898.2  394.73  5093.3  394.73  5101.1  395.83
  5115.4  395.79  5122.9  396.55  5129.8  396.14  5150.6  397.22  5249.5  398.10
  5299.6  400.14  5313.3  401.78  5327.6  406.28  5335.4  411.00  5377.7  416.65
#Mann=6,-1,0
  4667.1    0.05       0  4842.6    0.07       0  4857.3    0.12       0
  4892.2    0.07       0  4898.2    0.12       0  5122.9    0.05       0
Bank Sta=4892.2,4898.2
Exp/Cntr=0.3,0.1

Chan Stop Cuts=-1