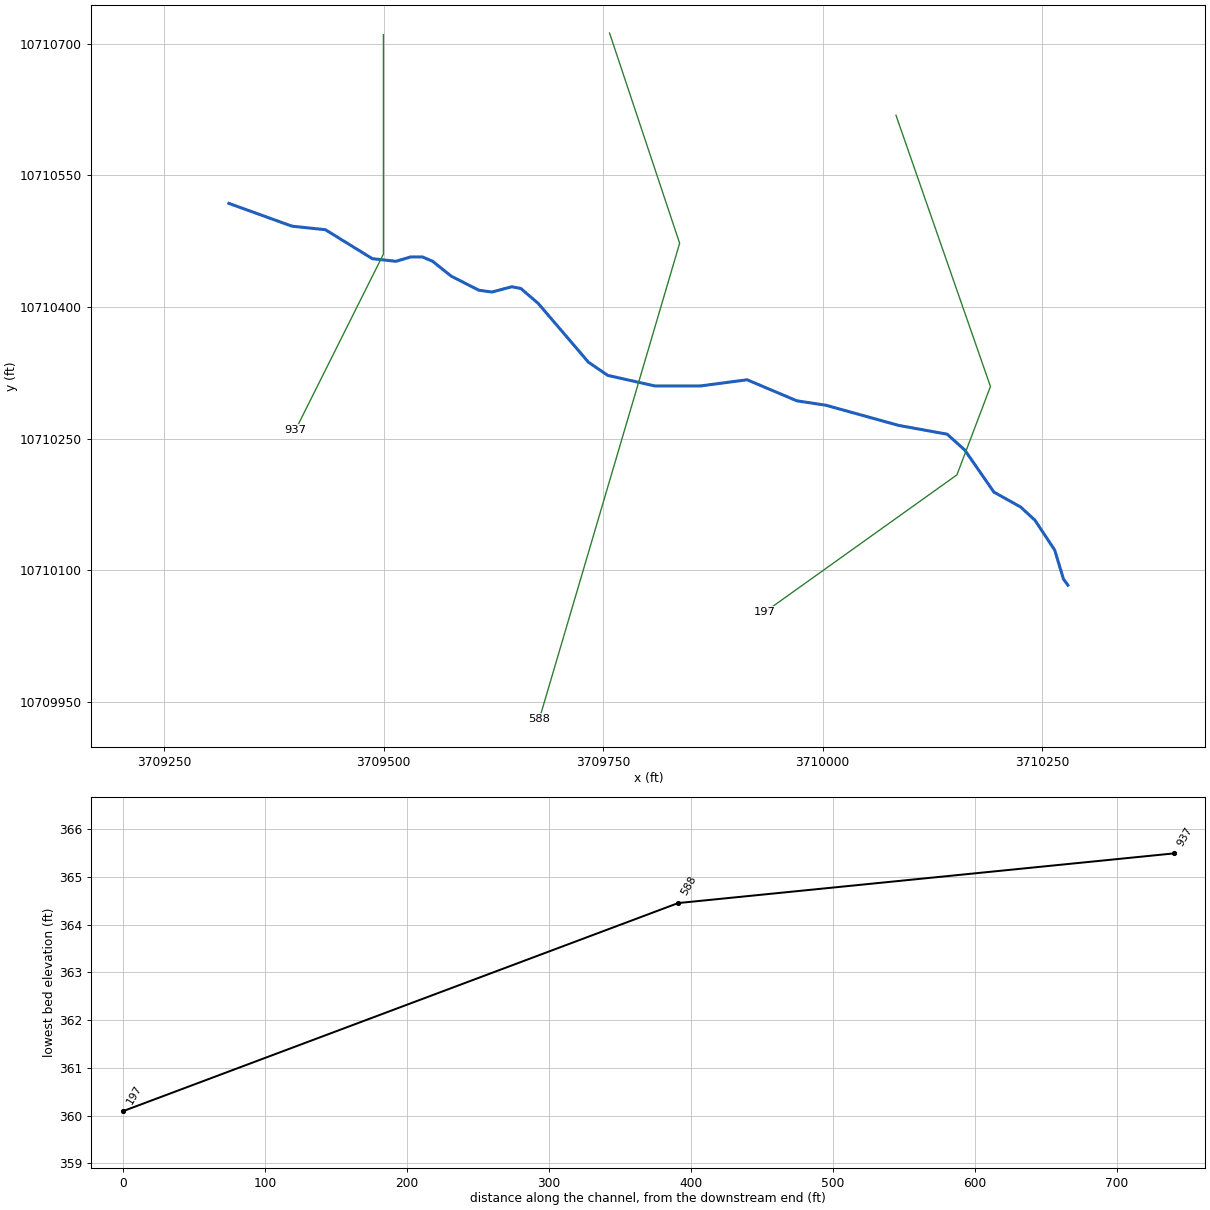
--- UNT 144 IN CACR.prj (project) ---

Proj Title=UNT 144 IN CACR Base Level Engineering
Current Plan=p01
Default Exp/Contr=0.3,0.1
English Units
Geom File=g01
Flow File=f01
Plan File=p01
BEGIN DESCRIPTION:
UNT 144 IN CACR
END DESCRIPTION:

--- UNT 144 IN CACR.p01 (plan) ---

Plan Title=Multiple Run
Short Identifier=Multiple
Geom File=g01
Flow File=f01
Subcritical Flow
K Sum by GR= 0
Std Step Tol= 0.01
Critical Tol= 0.01
Num of Std Step Trials= 20
Max Error Tol= 0.3
Flow Tol Ratio= 0.001
Split Flow NTrial= 30
Split Flow Tol= 0.02
Split Flow Ratio= 0.02
Log Output Level= 0
Friction Slope Method= 1
Unsteady Friction Slope Method= 2
Unsteady Bridges Friction Slope Method= 1
Parabolic Critical Depth
Global Vel Dist=  1 , 1 , 1
Global Log Level= 0
CheckData=True
Encroach Param= -1, 0, 0, 0
BEGIN DESCRIPTION:
Multiple Run
END DESCRIPTION:

--- UNT 144 IN CACR.f01 (steady flow) ---

Flow Title=Multiple
Number of Profiles=7
Profile Names=10-year,25-year,50-year,1pct_min,100-year,1pct_plu,500-year
River Rch & RM= UNT 144 IN CACR,Reach-1,937
     349     463     555     490     663     896     949
Boundary for River Rch & Prof#=UNT 144 IN CACR,Reach-1,1
Up Type=0
Dn Type=3
Dn Slope=0.005
Boundary for River Rch & Prof#=UNT 144 IN CACR,Reach-1,2
Up Type=0
Dn Type=3
Dn Slope=0.005
Boundary for River Rch & Prof#=UNT 144 IN CACR,Reach-1,3
Up Type=0
Dn Type=3
Dn Slope=0.005
Boundary for River Rch & Prof#=UNT 144 IN CACR,Reach-1,4
Up Type=0
Dn Type=3
Dn Slope=0.005
Boundary for River Rch & Prof#=UNT 144 IN CACR,Reach-1,5
Up Type=0
Dn Type=3
Dn Slope=0.005
Boundary for River Rch & Prof#=UNT 144 IN CACR,Reach-1,6
Up Type=0
Dn Type=3
Dn Slope=0.005
Boundary for River Rch & Prof#=UNT 144 IN CACR,Reach-1,7
Up Type=0
Dn Type=3
Dn Slope=0.005

--- UNT 144 IN CACR.g01 (geometry) ---

Geom Title=Existing Conditions

River Reach=UNT 144 IN CACR,Reach-1
Reach XY= 30
      3709323.50     10710518.00      3709395.50     10710492.00
      3709433.50     10710488.00      3709487.00     10710455.00
      3709514.00     10710452.00      3709530.75     10710457.00
      3709544.00     10710457.00      3709555.75     10710452.00
      3709577.00     10710435.00      3709608.50     10710419.00
      3709623.25     10710417.00      3709646.00     10710423.00
      3709656.25     10710421.00      3709676.00     10710404.00
      3709733.25     10710337.00      3709755.25     10710322.00
      3709808.75     10710310.00      3709861.00     10710310.00
      3709914.00     10710317.00      3709970.75     10710293.00
      3710003.75     10710288.00      3710086.75     10710265.00
      3710142.00     10710255.00      3710162.00     10710237.00
      3710195.25     10710189.00      3710225.75     10710172.00
      3710242.00     10710157.00      3710264.50     10710123.00
      3710274.50     10710090.00      3710279.50     10710083.00

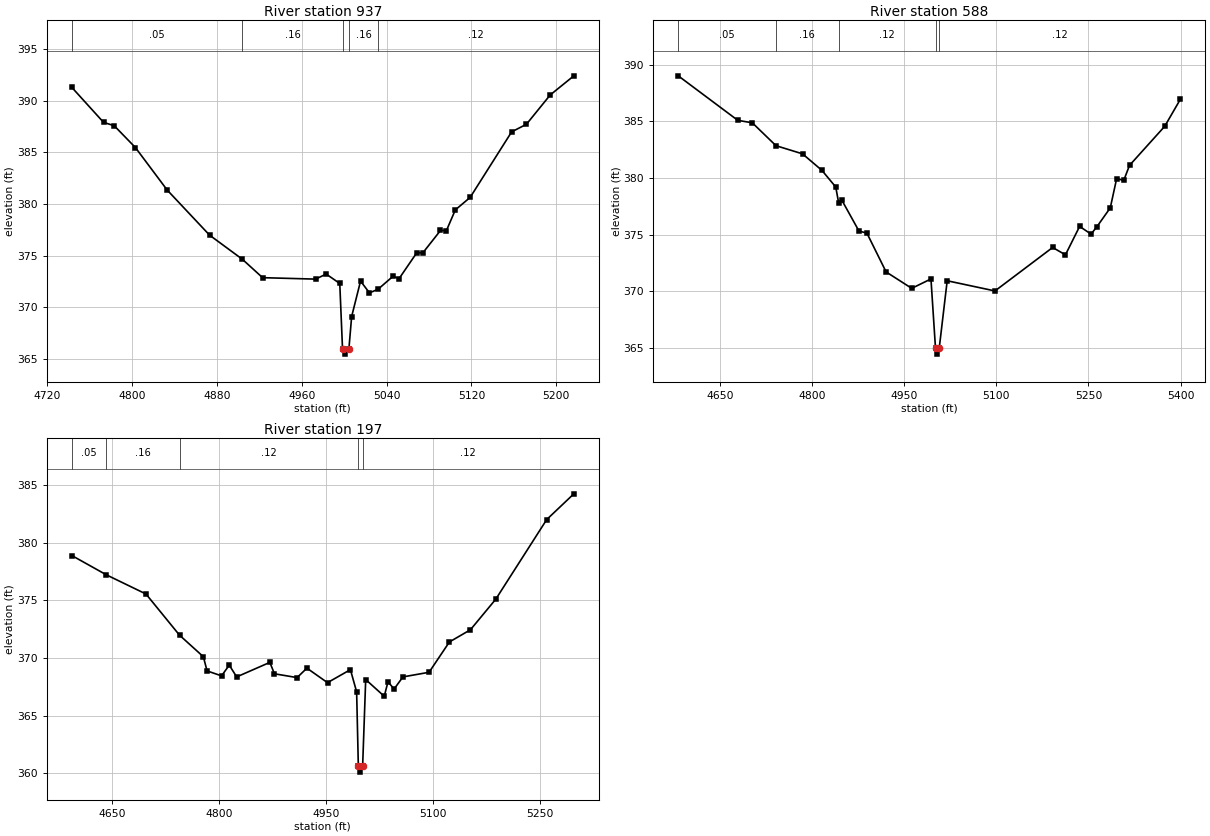
Type RM Length L Ch R = 1,937,349,349,349
BEGIN DESCRIPTION:
UNT 144 IN CACR 2.0
END DESCRIPTION:
XS GIS Cut Line= 3
      3709499.61     10710710.21      3709499.61     10710460.19
      3709399.62     10710260.21
#Sta/Elev= 30
  4743.0  391.28  4773.0  387.89  4783.0  387.57  4803.0  385.46  4833.0  381.35
  4873.0  376.99  4903.9  374.66  4923.0  372.88  4973.0  372.74  4983.0  373.23
  4995.8  372.32  4998.4  365.99  5001.2  365.49  5004.4  365.99  5007.0  369.12
  5015.4  372.55  5023.8  371.41  5031.9  371.76  5046.1  373.02  5051.7  372.78
  5068.5  375.30  5074.1  375.27  5090.8  377.44  5096.4  377.43  5104.8  379.43
  5118.8  380.64  5157.9  386.97  5171.9  387.71  5194.3  390.54  5216.6  392.39
#Mann=5,-1,0
  4743.0    0.05       0  4903.9    0.16       0  4998.4    0.07       0
  5004.4    0.16       0  5031.9    0.12       0
Bank Sta=4998.4,5004.4
Exp/Cntr=0.3,0.1

Type RM Length L Ch R = 1,588,391,391,391
BEGIN DESCRIPTION:
Mapping XS 6a7d42d9
END DESCRIPTION:
XS GIS Cut Line= 3
      3709757.29     10710712.11      3709837.14     10710472.54
      3709677.40     10709930.83
#Sta/Elev= 30
  4582.3  389.03  4679.2  385.10  4702.9  384.88  4741.4  382.86  4784.6  382.14
  4816.2  380.68  4838.7  379.21  4843.5  377.79  4848.3  378.08  4876.5  375.32
  4889.4  375.14  4920.7  371.71  4962.4  370.26  4993.7  371.09  5001.1  364.95
  5003.8  364.45  5007.1  364.95  5020.1  370.93  5097.9  370.03  5191.8  373.87
  5212.6  373.22  5235.7  375.73  5254.3  375.05  5263.8  375.70  5285.6  377.37
  5296.0  379.96  5307.5  379.79  5316.9  381.12  5374.2  384.57  5399.6  386.95
#Mann=5,-1,0
  4582.3    0.05       0  4741.4    0.16       0  4843.5    0.12       0
  5001.1    0.07       0  5007.1    0.12       0
Bank Sta=5001.1,5007.1
Exp/Cntr=0.3,0.1

Type RM Length L Ch R = 1,197,0,0,0
BEGIN DESCRIPTION:
UNT 144 IN CACR 1.0
END DESCRIPTION:
XS GIS Cut Line= 4
      3710083.66     10710618.40      3710191.31     10710309.35
      3710153.11     10710208.65      3709934.51     10710052.51
#Sta/Elev= 30
  4593.5  378.88  4642.1  377.20  4697.5  375.54  4744.5  371.97  4777.9  370.10
  4783.1  368.87  4803.4  368.44  4814.2  369.37  4824.6  368.35  4871.1  369.61
  4877.5  368.62  4909.3  368.29  4923.0  369.11  4951.9  367.85  4984.0  368.98
  4992.7  367.05  4995.1  360.59  4997.8  360.09  5001.1  360.59  5005.4  368.12
  5031.4  366.67  5036.7  367.94  5045.1  367.29  5057.6  368.35  5094.2  368.75
  5122.7  371.38  5152.2  372.44  5187.8  375.10  5259.1  382.00  5297.1  384.23
#Mann=5,-1,0
  4593.5    0.05       0  4642.1    0.16       0  4744.5    0.12       0
  4995.1    0.07       0  5001.1    0.12       0
Bank Sta=4995.1,5001.1
Exp/Cntr=0.3,0.1

Chan Stop Cuts=-1