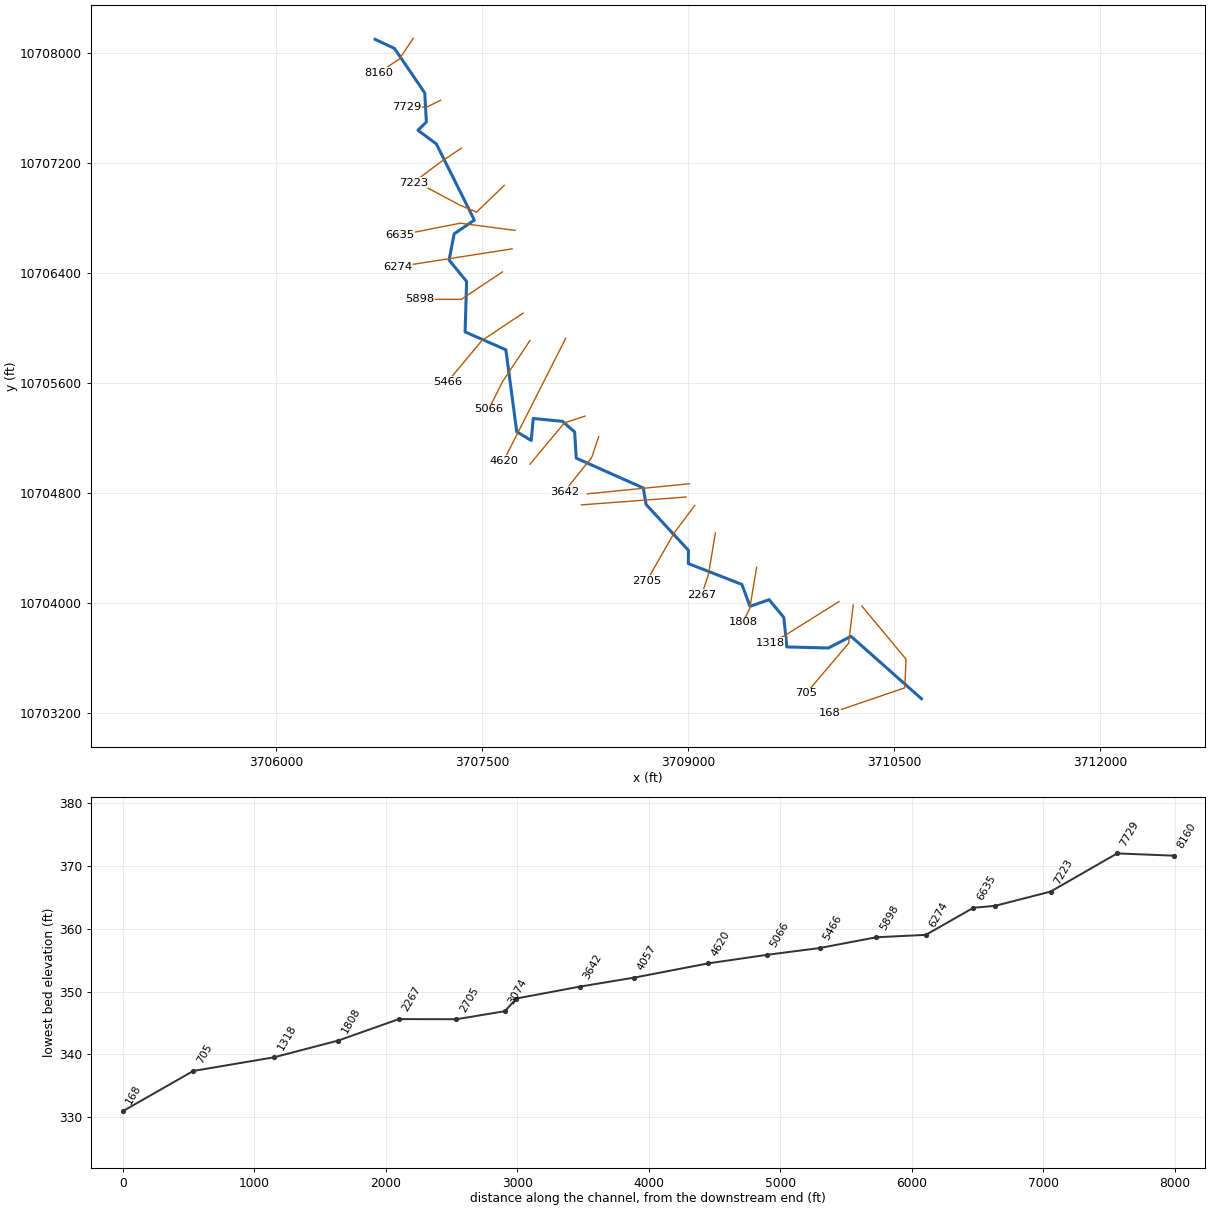
--- UNT 145 IN CACR.prj (project) ---

Proj Title=UNT 145 IN CACR Base Level Engineering
Current Plan=p01
Default Exp/Contr=0.3,0.1
English Units
Geom File=g01
Flow File=f01
Plan File=p01
BEGIN DESCRIPTION:
UNT 145 IN CACR
END DESCRIPTION:

--- UNT 145 IN CACR.p01 (plan) ---

Plan Title=Multiple Run
Short Identifier=Multiple
Geom File=g01
Flow File=f01
Subcritical Flow
K Sum by GR= 0
Std Step Tol= 0.01
Critical Tol= 0.01
Num of Std Step Trials= 20
Max Error Tol= 0.3
Flow Tol Ratio= 0.001
Split Flow NTrial= 30
Split Flow Tol= 0.02
Split Flow Ratio= 0.02
Log Output Level= 0
Friction Slope Method= 1
Unsteady Friction Slope Method= 2
Unsteady Bridges Friction Slope Method= 1
Parabolic Critical Depth
Global Vel Dist=  1 , 1 , 1
Global Log Level= 0
CheckData=True
Encroach Param= -1, 0, 0, 0
BEGIN DESCRIPTION:
Multiple Run
END DESCRIPTION:

--- UNT 145 IN CACR.f01 (steady flow) ---

Flow Title=Multiple
Number of Profiles=7
Profile Names=10-year,25-year,50-year,1pct_min,100-year,1pct_plu,500-year
River Rch & RM= UNT 145 IN CACR,Reach-1,8160
     377     502     605     536     725     981    1047
River Rch & RM= UNT 145 IN CACR,Reach-1,6635
     543     738     900     806    1091    1475    1610
River Rch & RM= UNT 145 IN CACR,Reach-1,2705
     571     777     946     848    1147    1551    1691
Boundary for River Rch & Prof#=UNT 145 IN CACR,Reach-1,1
Up Type=0
Dn Type=3
Dn Slope=0.005
Boundary for River Rch & Prof#=UNT 145 IN CACR,Reach-1,2
Up Type=0
Dn Type=3
Dn Slope=0.005
Boundary for River Rch & Prof#=UNT 145 IN CACR,Reach-1,3
Up Type=0
Dn Type=3
Dn Slope=0.005
Boundary for River Rch & Prof#=UNT 145 IN CACR,Reach-1,4
Up Type=0
Dn Type=3
Dn Slope=0.005
Boundary for River Rch & Prof#=UNT 145 IN CACR,Reach-1,5
Up Type=0
Dn Type=3
Dn Slope=0.005
Boundary for River Rch & Prof#=UNT 145 IN CACR,Reach-1,6
Up Type=0
Dn Type=3
Dn Slope=0.005
Boundary for River Rch & Prof#=UNT 145 IN CACR,Reach-1,7
Up Type=0
Dn Type=3
Dn Slope=0.005

--- UNT 145 IN CACR.g01 (geometry) ---

Geom Title=Existing Conditions

River Reach=UNT 145 IN CACR,Reach-1
Reach XY= 30
      3706722.49     10708102.86      3706863.00     10708037.00
      3707083.75     10707713.00      3707095.50     10707501.00
      3707034.25     10707441.00      3707168.46     10707341.47
      3707444.75     10706787.00      3707297.75     10706687.00
      3707261.25     10706496.00      3707388.50     10706340.00
      3707377.50     10705973.00      3707674.25     10705843.00
      3707753.50     10705246.00      3707859.00     10705183.00
      3707873.25     10705343.00      3708086.25     10705322.00
      3708174.75     10705245.00      3708186.75     10705054.00
      3708674.75     10704837.00      3708694.75     10704717.00
      3709003.50     10704383.00      3709002.25     10704287.00
      3709392.25     10704135.00      3709451.50     10703975.00
      3709590.75     10704024.00      3709697.50     10703894.00
      3709719.75     10703680.00      3710021.50     10703672.00
      3710186.75     10703757.00      3710699.50     10703303.00

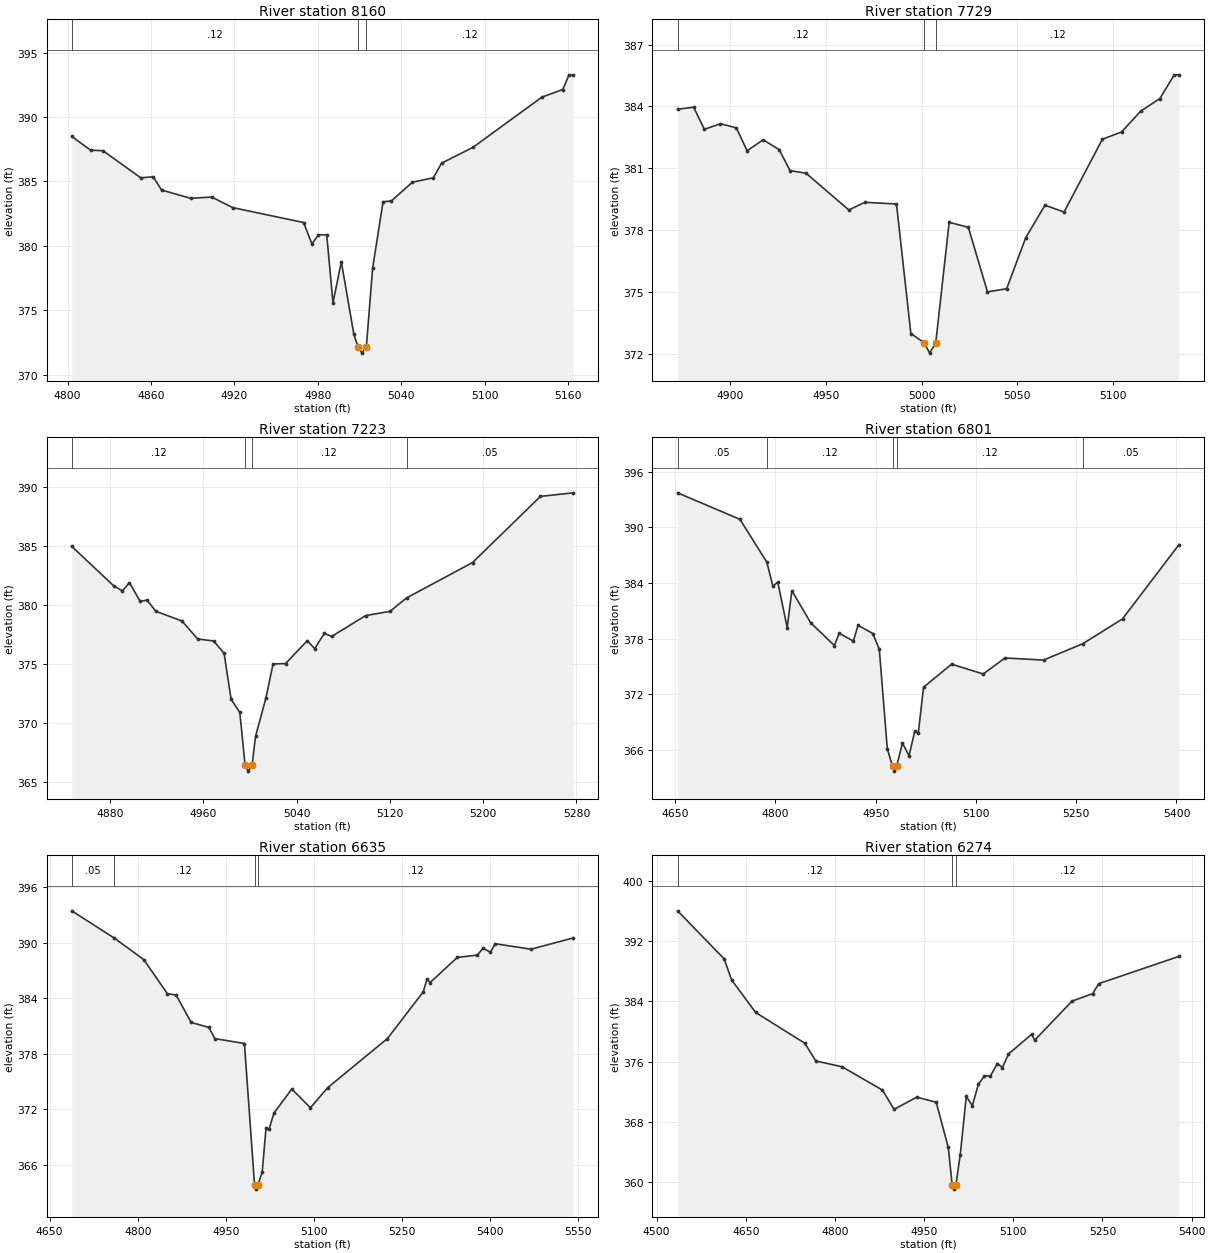
Type RM Length L Ch R = 1,8160,431,431,431
BEGIN DESCRIPTION:
UNT 145 IN CACR 18.0
END DESCRIPTION:
XS GIS Cut Line= 3
      3706999.60     10708110.17      3706899.61     10707960.19
      3706749.64     10707860.21
#Sta/Elev= 30
  4803.0  388.49  4816.5  387.43  4825.5  387.38  4852.6  385.28  4861.6  385.36
  4867.6  384.33  4888.6  383.69  4903.6  383.79  4918.7  382.97  4969.7  381.81
  4975.7  380.14  4980.3  380.86  4986.3  380.86  4990.8  375.58  4996.8  378.77
  5005.8  373.14  5008.8  372.18  5011.6  371.68  5014.8  372.18  5019.3  378.27
  5026.8  383.42  5032.8  383.49  5047.9  384.94  5062.9  385.28  5068.9  386.42
  5091.4  387.64  5141.0  391.54  5156.0  392.13  5160.5  393.27  5163.5  393.27
#Mann=3,-1,0
  4803.0    0.12       0  5008.8    0.07       0  5014.8    0.12       0
Bank Sta=5008.8,5014.8
Exp/Cntr=0.3,0.1

Type RM Length L Ch R = 1,7729,506,506,506
BEGIN DESCRIPTION:
UNT 145 IN CACR 17.0
END DESCRIPTION:
XS GIS Cut Line= 3
      3707199.61     10707660.19      3707099.61     10707610.19
      3706949.61     10707610.19
#Sta/Elev= 30
  4872.6  383.86  4881.0  383.96  4886.6  382.89  4895.0  383.16  4903.3  382.96
  4908.9  381.85  4917.3  382.38  4925.7  381.90  4931.3  380.89  4939.7  380.76
  4962.0  378.98  4970.4  379.35  4986.9  379.27  4994.4  372.99  5001.4  372.54
  5004.2  372.04  5007.4  372.54  5014.4  378.38  5024.4  378.14  5034.4  375.01
  5044.4  375.16  5054.4  377.64  5064.4  379.21  5074.4  378.88  5094.4  382.41
  5104.4  382.76  5114.4  383.77  5124.4  384.38  5131.9  385.53  5134.4  385.53
#Mann=3,-1,0
  4872.6    0.12       0  5001.4    0.07       0  5007.4    0.12       0
Bank Sta=5001.4,5007.4
Exp/Cntr=0.3,0.1

Type RM Length L Ch R = 1,7223,422,422,422
BEGIN DESCRIPTION:
UNT 145 IN CACR 16.0
END DESCRIPTION:
XS GIS Cut Line= 3
      3707349.58     10707310.17      3707199.61     10707210.19
      3706999.64     10707060.21
#Sta/Elev= 30
  4847.0  384.98  4883.0  381.64  4890.5  381.21  4896.5  381.92  4905.6  380.33
  4911.6  380.43  4919.1  379.49  4941.6  378.66  4955.1  377.14  4968.7  376.98
  4977.7  375.93  4983.7  372.04  4991.2  370.93  4995.7  366.46  4998.4  365.96
  5001.7  366.46  5004.7  368.91  5013.7  372.19  5019.7  375.03  5030.4  375.06
  5049.1  377.00  5055.4  376.32  5063.7  377.62  5070.0  377.36  5099.1  379.12
  5120.0  379.48  5134.3  380.62  5190.8  383.61  5249.1  389.21  5277.2  389.51
#Mann=4,-1,0
  4847.0    0.12       0  4995.7    0.07       0  5001.7    0.12       0
  5134.3    0.05       0
Bank Sta=4995.7,5001.7
Exp/Cntr=0.3,0.1

Type RM Length L Ch R = 1,6801,166,166,166
BEGIN DESCRIPTION:
UNT 145 IN CACR 15.0
END DESCRIPTION:
XS GIS Cut Line= 4
      3707662.16     10707039.51      3707460.76     10706845.06
      3707340.97     10706895.40      3707040.60     10707055.14
#Sta/Elev= 30
  4653.7  393.74  4747.0  390.88  4787.3  386.25  4796.4  383.64  4803.6  384.11
  4817.7  379.18  4824.7  383.18  4852.9  379.70  4888.4  377.25  4895.4  378.57
  4916.7  377.74  4923.7  379.43  4945.8  378.55  4955.5  376.84  4967.4  366.12
  4975.3  364.19  4978.0  363.69  4981.3  364.19  4990.1  366.71  5000.0  365.35
  5008.4  367.98  5013.8  367.80  5021.7  372.75  5063.6  375.24  5110.9  374.18
  5143.5  375.91  5201.1  375.68  5259.8  377.45  5319.3  380.13  5403.8  388.16
#Mann=5,-1,0
  4653.7    0.05       0  4787.3    0.12       0  4975.3    0.07       0
  4981.3    0.12       0  5259.8    0.05       0
Bank Sta=4975.3,4981.3
Exp/Cntr=0.3,0.1

Type RM Length L Ch R = 1,6635,361,361,361
BEGIN DESCRIPTION:
Mapping XS 10208d7d
END DESCRIPTION:
XS GIS Cut Line= 3
      3707741.16     10706712.24      3707341.84     10706764.33
      3706899.17     10706677.53
#Sta/Elev= 30
  4687.6  393.47  4759.9  390.53  4810.2  388.20  4850.5  384.50  4865.3  384.37
  4890.9  381.40  4921.1  380.86  4931.2  379.65  4981.6  379.12  4998.8  363.87
  5001.5  363.37  5004.8  363.87  5011.9  365.22  5018.3  369.93  5023.3  369.82
  5032.0  371.61  5062.3  374.20  5094.0  372.17  5123.1  374.33  5225.1  379.66
  5286.2  384.72  5292.5  386.11  5297.6  385.70  5344.0  388.43  5377.9  388.68
  5388.1  389.42  5400.5  388.99  5408.5  389.91  5469.6  389.32  5541.4  390.54
#Mann=4,-1,0
  4687.6    0.05       0  4759.9    0.12       0  4998.8    0.07       0
  5004.8    0.12       0
Bank Sta=4998.8,5004.8
Exp/Cntr=0.3,0.1

Type RM Length L Ch R = 1,6274,376,376,376
BEGIN DESCRIPTION:
UNT 145 IN CACR 14.0
END DESCRIPTION:
XS GIS Cut Line= 2
      3707719.42     10706577.69      3706886.13     10706447.49
#Sta/Elev= 30
  4535.4  396.04  4613.8  389.66  4626.3  386.86  4666.8  382.53  4749.4  378.45
  4768.0  376.09  4812.1  375.32  4880.0  372.22  4899.6  369.66  4937.6  371.28
  4970.4  370.61  4990.7  364.60  4997.4  359.56  5000.1  359.06  5003.4  359.56
  5010.9  363.66  5021.0  371.39  5031.2  370.14  5041.3  372.98  5051.4  374.10
  5061.5  374.09  5073.3  375.73  5081.8  375.22  5091.9  377.01  5131.0  379.63
  5136.0  378.85  5198.8  384.04  5233.6  385.04  5243.7  386.36  5378.8  389.99
#Mann=3,-1,0
  4535.4    0.12       0  4997.4    0.07       0  5003.4    0.12       0
Bank Sta=4997.4,5003.4
Exp/Cntr=0.3,0.1

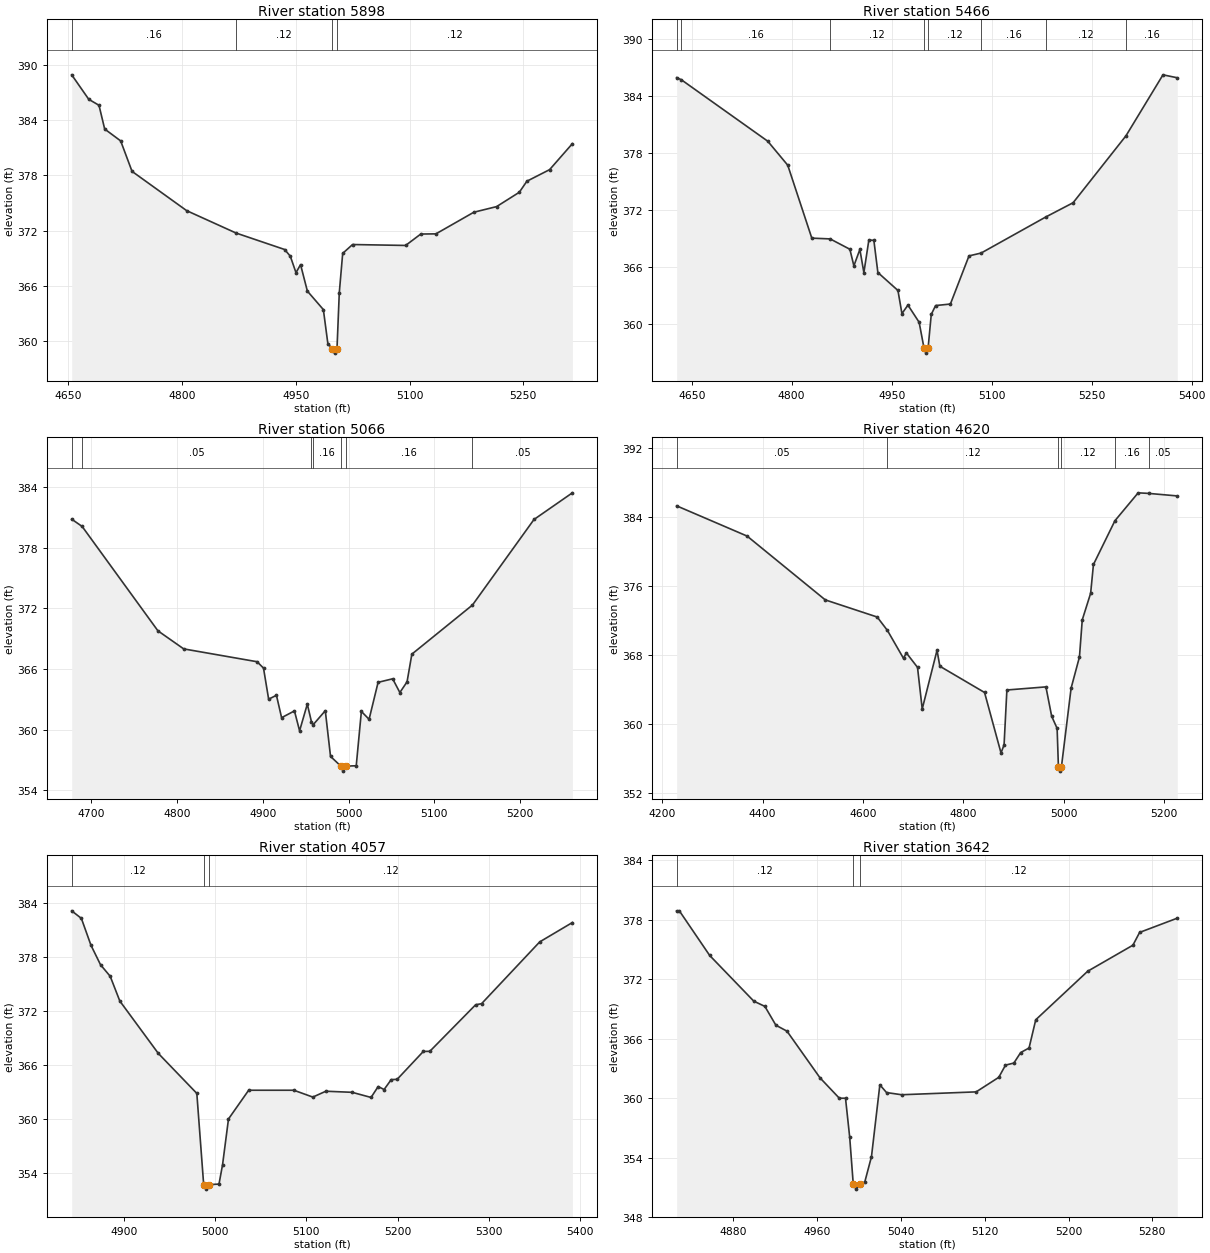
Type RM Length L Ch R = 1,5898,432,432,432
BEGIN DESCRIPTION:
UNT 145 IN CACR 13.0
END DESCRIPTION:
XS GIS Cut Line= 3
      3707649.58     10706410.17      3707349.61     10706210.19
      3707049.63     10706210.19
#Sta/Elev= 30
  4654.3  388.92  4676.8  386.26  4690.3  385.61  4697.8  383.03  4718.9  381.74
  4733.9  378.43  4806.0  374.16  4871.1  371.73  4935.2  369.94  4942.7  369.21
  4950.2  367.42  4956.2  368.30  4965.2  365.42  4986.3  363.41  4992.3  359.67
  4998.3  359.18  5001.0  358.68  5004.3  359.18  5007.3  365.24  5011.8  369.52
  5024.8  370.48  5094.8  370.38  5114.8  371.62  5134.8  371.64  5184.8  373.99
  5214.8  374.60  5244.8  376.16  5254.8  377.36  5284.8  378.62  5314.8  381.44
#Mann=4,-1,0
  4654.3    0.16       0  4871.1    0.12       0  4998.3    0.07       0
  5004.3    0.12       0
Bank Sta=4998.3,5004.3
Exp/Cntr=0.3,0.1

Type RM Length L Ch R = 1,5466,400,400,400
BEGIN DESCRIPTION:
UNT 145 IN CACR 12.0
END DESCRIPTION:
XS GIS Cut Line= 3
      3707799.60     10706110.18      3707499.61     10705910.19
      3707249.58     10705610.15
#Sta/Elev= 30
  4627.4  385.98  4634.5  385.75  4764.1  379.28  4794.1  376.75  4830.2  369.07
  4857.7  368.99  4887.3  367.90  4893.3  366.15  4902.3  367.88  4908.3  365.44
  4915.8  368.88  4923.3  368.83  4929.3  365.45  4959.4  363.56  4965.4  361.12
  4974.4  362.02  4991.2  360.21  4998.6  357.46  5001.4  356.96  5004.6  357.46
  5009.4  361.04  5015.9  361.97  5038.1  362.13  5066.0  367.20  5084.2  367.50
  5181.5  371.31  5222.2  372.80  5301.5  379.85  5357.0  386.27  5378.5  385.96
#Mann=8,-1,0
  4627.4    0.05       0  4634.5    0.16       0  4857.7    0.12       0
  4998.6    0.07       0  5004.6    0.12       0  5084.2    0.16       0
  5181.5    0.12       0  5301.5    0.16       0
Bank Sta=4998.6,5004.6
Exp/Cntr=0.3,0.1

Type RM Length L Ch R = 1,5066,446,446,446
BEGIN DESCRIPTION:
UNT 145 IN CACR 11.0
END DESCRIPTION:
XS GIS Cut Line= 3
      3707849.60     10705910.18      3707649.61     10705610.19
      3707549.59     10705410.15
#Sta/Elev= 30
  4677.0  380.82  4689.2  380.10  4777.6  369.77  4807.7  367.98  4893.3  366.71
  4900.8  366.08  4906.8  363.00  4915.9  363.39  4921.9  361.17  4936.9  361.84
  4942.9  359.87  4951.9  362.51  4956.8  360.75  4958.8  360.48  4972.9  361.86
  4979.0  357.34  4991.0  356.38  4993.7  355.88  4997.0  356.38  5009.0  356.41
  5015.0  361.79  5024.0  361.01  5034.5  364.67  5051.5  365.02  5059.9  363.66
  5068.3  364.72  5073.9  367.46  5144.6  372.32  5216.4  380.79  5261.2  383.43
#Mann=7,-1,0
  4677.0    0.16       0  4689.2    0.05       0  4956.8    0.12       0
  4958.8    0.16       0  4991.0    0.07       0  4997.0    0.16       0
  5144.6    0.05       0
Bank Sta=4991,4997
Exp/Cntr=0.3,0.1

Type RM Length L Ch R = 1,4620,563,563,563
BEGIN DESCRIPTION:
UNT 145 IN CACR 10.0
END DESCRIPTION:
XS GIS Cut Line= 2
      3708110.05     10705926.61      3707658.66     10705036.86
#Sta/Elev= 30
  4228.7  385.32  4369.1  381.81  4524.9  374.40  4628.4  372.41  4648.8  370.85
  4680.8  367.61  4686.4  368.25  4708.7  366.57  4718.1  361.74  4747.6  368.55
  4753.2  366.70  4842.3  363.65  4875.1  356.63  4881.2  357.57  4886.8  363.94
  4964.6  364.30  4976.0  360.90  4986.9  359.48  4989.5  355.02  4992.3  354.52
  4995.5  355.02  5014.8  364.16  5031.4  367.77  5037.0  372.08  5053.7  375.17
  5059.3  378.51  5102.1  383.59  5148.4  386.83  5170.0  386.76  5226.4  386.47
#Mann=6,-1,0
  4228.7    0.05       0  4648.8    0.12       0  4989.5    0.07       0
  4995.5    0.12       0  5102.1    0.16       0  5170.0    0.05       0
Bank Sta=4989.5,4995.5
Exp/Cntr=0.3,0.1

Type RM Length L Ch R = 1,4057,415,415,415
BEGIN DESCRIPTION:
UNT 145 IN CACR 9.0
END DESCRIPTION:
XS GIS Cut Line= 3
      3708249.63     10705360.19      3708099.61     10705310.19
      3707849.64     10705010.22
#Sta/Elev= 30
  4842.8  383.15  4853.4  382.31  4863.9  379.33  4874.4  377.16  4885.0  375.88
  4895.5  373.14  4937.7  367.32  4979.9  362.88  4987.4  352.75  4990.1  352.25
  4993.4  352.75  5004.2  352.81  5008.1  354.96  5014.6  360.04  5036.7  363.23
  5086.2  363.23  5107.0  362.47  5121.3  363.12  5150.0  363.00  5170.8  362.43
  5178.6  363.64  5185.1  363.31  5192.9  364.41  5199.4  364.44  5228.1  367.54
  5235.2  367.55  5285.4  372.72  5291.9  372.84  5355.6  379.70  5391.4  381.85
#Mann=3,-1,0
  4842.8    0.12       0  4987.4    0.07       0  4993.4    0.12       0
Bank Sta=4987.4,4993.4
Exp/Cntr=0.3,0.1

Type RM Length L Ch R = 1,3642,481,481,481
BEGIN DESCRIPTION:
UNT 145 IN CACR 8.0
END DESCRIPTION:
XS GIS Cut Line= 3
      3708349.59     10705210.14      3708299.61     10705060.19
      3708099.62     10704810.21
#Sta/Elev= 30
  4825.7  378.91  4828.3  378.91  4857.3  374.40  4899.4  369.79  4910.0  369.26
  4920.5  367.36  4931.1  366.76  4962.7  362.04  4981.1  359.99  4987.0  359.99
  4991.0  356.05  4994.4  351.31  4997.1  350.81  5000.4  351.31  5005.4  351.53
  5011.8  354.09  5019.8  361.34  5026.2  360.56  5040.6  360.34  5111.8  360.63
  5133.4  362.10  5139.8  363.33  5147.8  363.54  5154.3  364.60  5162.3  365.06
  5168.7  367.91  5218.3  372.81  5261.5  375.44  5267.9  376.73  5303.9  378.17
#Mann=3,-1,0
  4825.7    0.12       0  4994.4    0.07       0  5000.4    0.12       0
Bank Sta=4994.4,5000.4
Exp/Cntr=0.3,0.1

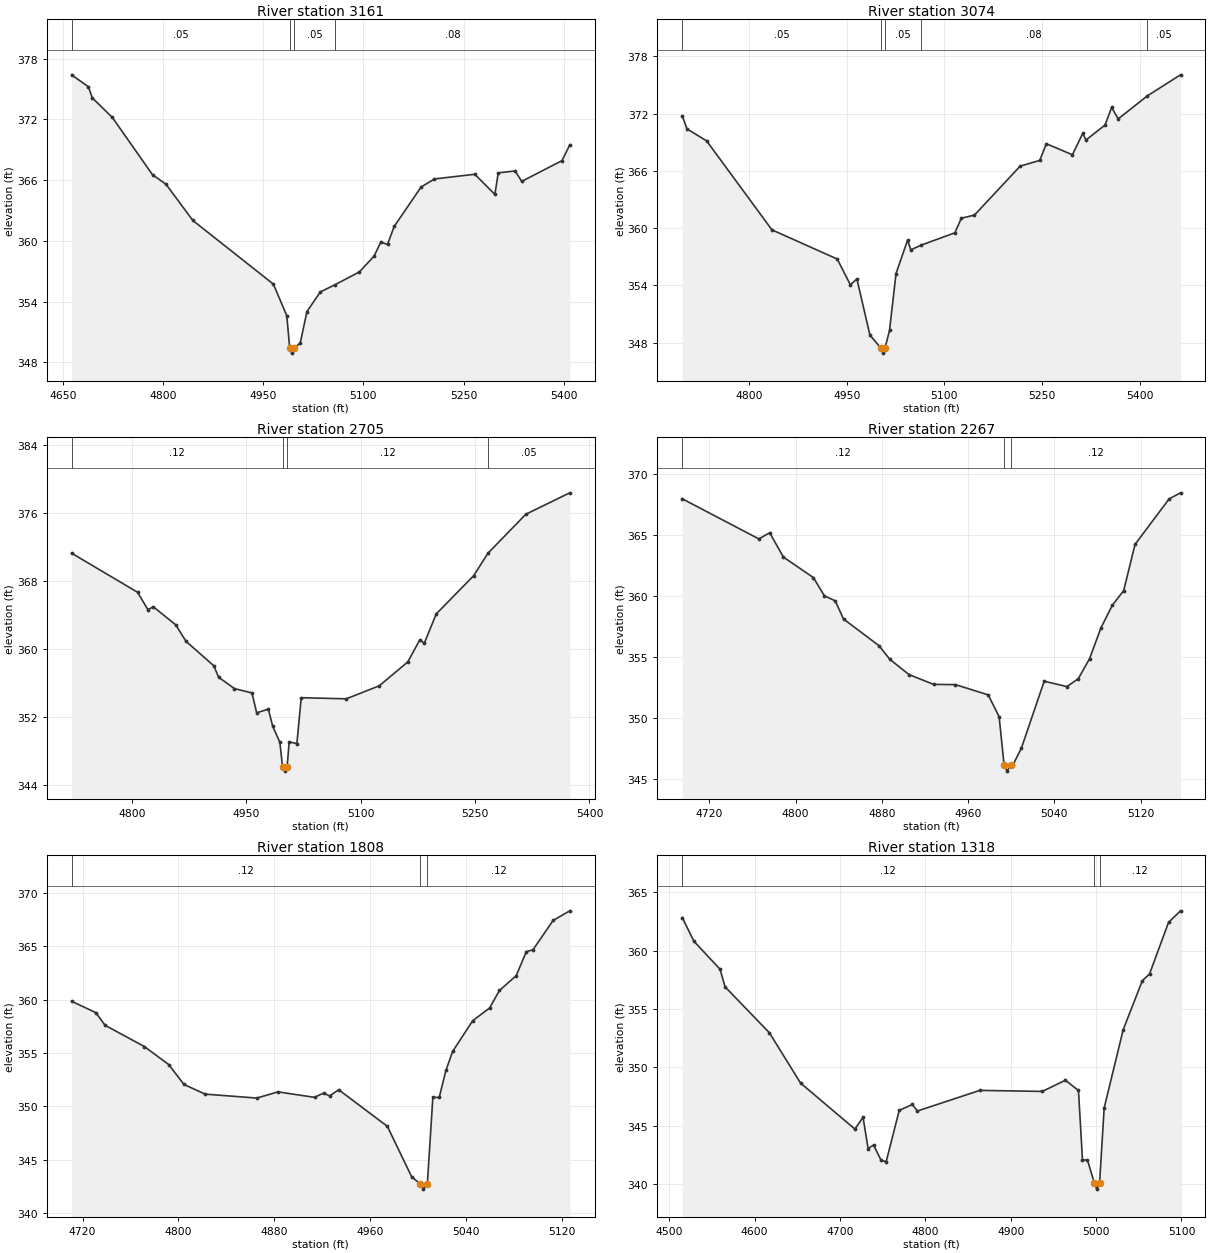
Type RM Length L Ch R = 1,3161,87,87,87
BEGIN DESCRIPTION:
Mapping XS 51127090
END DESCRIPTION:
XS GIS Cut Line= 2
      3709010.21     10704867.62      3708268.09     10704794.71
#Sta/Elev= 30
  4663.2  376.40  4688.5  375.21  4694.0  374.14  4724.1  372.20  4784.4  366.53
  4804.5  365.60  4844.7  362.02  4965.3  355.73  4985.3  352.62  4989.7  349.42
  4992.4  348.92  4995.7  349.42  5005.4  349.90  5015.5  353.02  5035.6  354.97
  5057.4  355.67  5094.0  356.94  5116.0  358.50  5126.0  359.88  5136.1  359.66
  5146.1  361.43  5186.3  365.32  5206.4  366.12  5266.7  366.58  5296.8  364.59
  5301.8  366.72  5327.0  366.91  5337.0  365.88  5397.3  367.93  5408.9  369.49
#Mann=4,-1,0
  4663.2    0.05       0  4989.7    0.03       0  4995.7    0.05       0
  5057.4    0.08       0
Bank Sta=4989.7,4995.7
Exp/Cntr=0.3,0.1

Type RM Length L Ch R = 1,3074,369,369,369
BEGIN DESCRIPTION:
UNT 145 IN CACR 7.0
END DESCRIPTION:
XS GIS Cut Line= 2
      3708986.84     10704771.28      3708224.18     10704714.01
#Sta/Elev= 30
  4697.7  371.76  4704.9  370.40  4735.0  369.15  4835.3  359.82  4935.6  356.76
  4955.7  354.06  4965.7  354.68  4985.7  348.80  5002.8  347.40  5005.5  346.90
  5008.8  347.40  5015.8  349.28  5025.8  355.24  5043.5  358.74  5048.5  357.72
  5064.4  358.22  5116.1  359.51  5126.1  361.04  5146.2  361.37  5216.4  366.50
  5246.5  367.10  5256.5  368.85  5296.6  367.69  5312.4  369.93  5317.4  369.24
  5346.7  370.81  5356.8  372.66  5366.8  371.45  5411.7  373.87  5462.5  376.07
#Mann=5,-1,0
  4697.7    0.05       0  5002.8    0.04       0  5008.8    0.05       0
  5064.4    0.08       0  5411.7    0.05       0
Bank Sta=5002.8,5008.8
Exp/Cntr=0.3,0.1

Type RM Length L Ch R = 1,2705,438,438,438
BEGIN DESCRIPTION:
UNT 145 IN CACR 6.0
END DESCRIPTION:
XS GIS Cut Line= 3
      3709049.63     10704710.22      3708899.61     10704510.19
      3708699.58     10704160.15
#Sta/Elev= 30
  4721.0  371.27  4807.5  366.67  4821.0  364.63  4828.3  364.95  4857.5  362.84
  4871.0  360.90  4907.5  358.02  4913.7  356.68  4934.6  355.33  4957.5  354.82
  4963.7  352.48  4979.0  352.92  4984.7  350.90  4994.1  349.01  4997.6  346.12
  5000.3  345.62  5003.6  346.12  5006.3  349.06  5016.4  348.86  5022.1  354.26
  5081.2  354.13  5124.4  355.66  5161.8  358.47  5177.6  361.08  5183.4  360.66
  5199.2  364.13  5248.2  368.62  5267.0  371.27  5316.6  375.85  5374.2  378.37
#Mann=4,-1,0
  4721.0    0.12       0  4997.6    0.07       0  5003.6    0.12       0
  5267.0    0.05       0
Bank Sta=4997.6,5003.6
Exp/Cntr=0.3,0.1

Type RM Length L Ch R = 1,2267,459,459,459
BEGIN DESCRIPTION:
UNT 145 IN CACR 5.0
END DESCRIPTION:
XS GIS Cut Line= 3
      3709199.61     10704510.21      3709149.61     10704210.19
      3709099.60     10704060.16
#Sta/Elev= 30
  4694.8  367.93  4765.8  364.65  4775.9  365.15  4788.6  363.16  4816.5  361.48
  4826.6  359.99  4836.7  359.58  4844.4  358.09  4877.3  355.91  4887.4  354.79
  4905.2  353.54  4928.0  352.74  4948.3  352.72  4978.7  351.88  4988.8  350.09
  4993.4  346.14  4996.2  345.64  4999.4  346.14  5001.6  346.14  5009.5  347.53
  5030.6  353.00  5051.7  352.56  5062.2  353.20  5072.7  354.84  5083.3  357.37
  5093.8  359.21  5104.4  360.42  5114.9  364.20  5146.5  367.92  5157.1  368.42
#Mann=3,-1,0
  4694.8    0.12       0  4993.4    0.07       0  4999.4    0.12       0
Bank Sta=4993.4,4999.4
Exp/Cntr=0.3,0.1

Type RM Length L Ch R = 1,1808,490,490,490
BEGIN DESCRIPTION:
UNT 145 IN CACR 4.0
END DESCRIPTION:
XS GIS Cut Line= 3
      3709499.61     10704260.19      3709449.61     10703960.19
      3709399.63     10703860.22
#Sta/Elev= 30
  4710.8  359.85  4731.1  358.78  4738.7  357.60  4771.6  355.60  4791.9  353.91
  4804.6  352.05  4822.3  351.14  4865.4  350.77  4883.1  351.35  4913.6  350.84
  4921.2  351.24  4926.2  350.97  4933.8  351.55  4974.4  348.12  4994.7  343.39
  5001.8  342.73  5004.5  342.23  5007.8  342.73  5012.4  350.83  5017.7  350.83
  5023.3  353.36  5028.9  355.14  5045.7  358.03  5059.7  359.21  5068.0  360.86
  5082.0  362.25  5090.4  364.50  5096.0  364.68  5112.8  367.43  5126.7  368.33
#Mann=3,-1,0
  4710.8    0.12       0  5001.8    0.07       0  5007.8    0.12       0
Bank Sta=5001.8,5007.8
Exp/Cntr=0.3,0.1

Type RM Length L Ch R = 1,1318,613,613,613
BEGIN DESCRIPTION:
UNT 145 IN CACR 3.0
END DESCRIPTION:
XS GIS Cut Line= 3
      3710099.60     10704010.18      3709699.61     10703760.19
      3709599.60     10703710.19
#Sta/Elev= 30
  4515.4  362.84  4529.0  360.81  4559.6  358.41  4565.5  356.90  4617.4  352.96
  4654.0  348.64  4717.6  344.70  4727.1  345.72  4733.0  343.03  4739.4  343.33
  4748.3  342.01  4754.2  341.91  4769.5  346.31  4784.9  346.81  4790.7  346.25
  4863.9  348.02  4937.0  347.93  4964.1  348.89  4979.4  348.01  4984.1  342.05
  4989.9  342.05  4998.1  340.05  5000.8  339.55  5004.1  340.05  5009.5  346.51
  5031.8  353.23  5054.2  357.43  5062.6  358.00  5084.9  362.43  5098.9  363.42
#Mann=3,-1,0
  4515.4    0.12       0  4998.1    0.07       0  5004.1    0.12       0
Bank Sta=4998.1,5004.1
Exp/Cntr=0.3,0.1

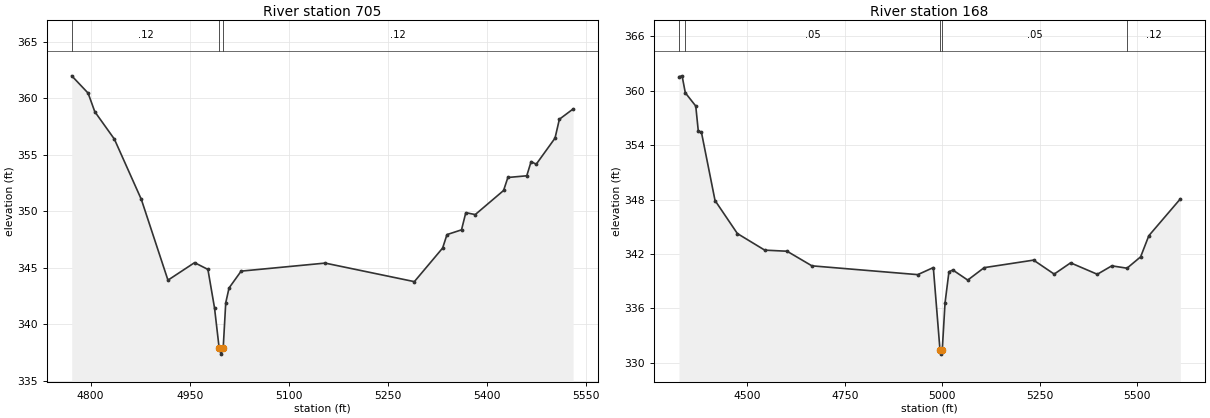
Type RM Length L Ch R = 1,705,537,537,537
BEGIN DESCRIPTION:
UNT 145 IN CACR 2.0
END DESCRIPTION:
XS GIS Cut Line= 3
      3710202.95     10703984.85      3710169.09     10703706.17
      3709859.21     10703341.60
#Sta/Elev= 30
  4771.4  361.99  4796.2  360.46  4806.3  358.82  4836.0  356.39  4876.8  351.06
  4917.1  343.92  4957.4  345.47  4977.6  344.87  4987.6  341.47  4994.7  337.88
  4997.5  337.38  5000.7  337.88  5004.6  341.92  5009.6  343.23  5027.9  344.72
  5155.1  345.43  5290.2  343.79  5333.0  346.76  5339.6  347.95  5361.6  348.37
  5368.1  349.89  5382.4  349.72  5425.3  351.85  5431.8  353.00  5460.4  353.15
  5467.0  354.41  5474.7  354.17  5503.2  356.48  5509.8  358.15  5530.6  359.06
#Mann=3,-1,0
  4771.4    0.12       0  4994.7    0.07       0  5000.7    0.12       0
Bank Sta=4994.7,5000.7
Exp/Cntr=0.3,0.1

Type RM Length L Ch R = 1,168,0,0,0
BEGIN DESCRIPTION:
UNT 145 IN CACR 1.0
END DESCRIPTION:
XS GIS Cut Line= 4
      3710265.89     10703977.00      3710587.06     10703590.72
      3710578.38     10703382.38      3710033.04     10703196.28
#Sta/Elev= 30
  4324.3  361.54  4332.3  361.63  4340.6  359.76  4367.4  358.30  4374.0  355.51
  4381.8  355.45  4416.9  347.89  4474.2  344.25  4544.5  342.42  4601.8  342.30
  4665.6  340.69  4937.3  339.72  4977.3  340.50  4994.3  331.46  4997.1  330.96
  5000.3  331.46  5007.3  336.59  5017.4  340.04  5027.4  340.23  5065.6  339.12
  5107.8  340.49  5234.6  341.32  5287.5  339.78  5329.7  341.02  5398.2  339.76
  5435.4  340.69  5474.5  340.43  5509.4  341.68  5530.5  344.01  5611.4  348.07
#Mann=5,-1,0
  4324.3    0.12       0  4340.6    0.05       0  4994.3    0.03       0
  5000.3    0.05       0  5474.5    0.12       0
Bank Sta=4994.3,5000.3
Exp/Cntr=0.3,0.1

Chan Stop Cuts=-1