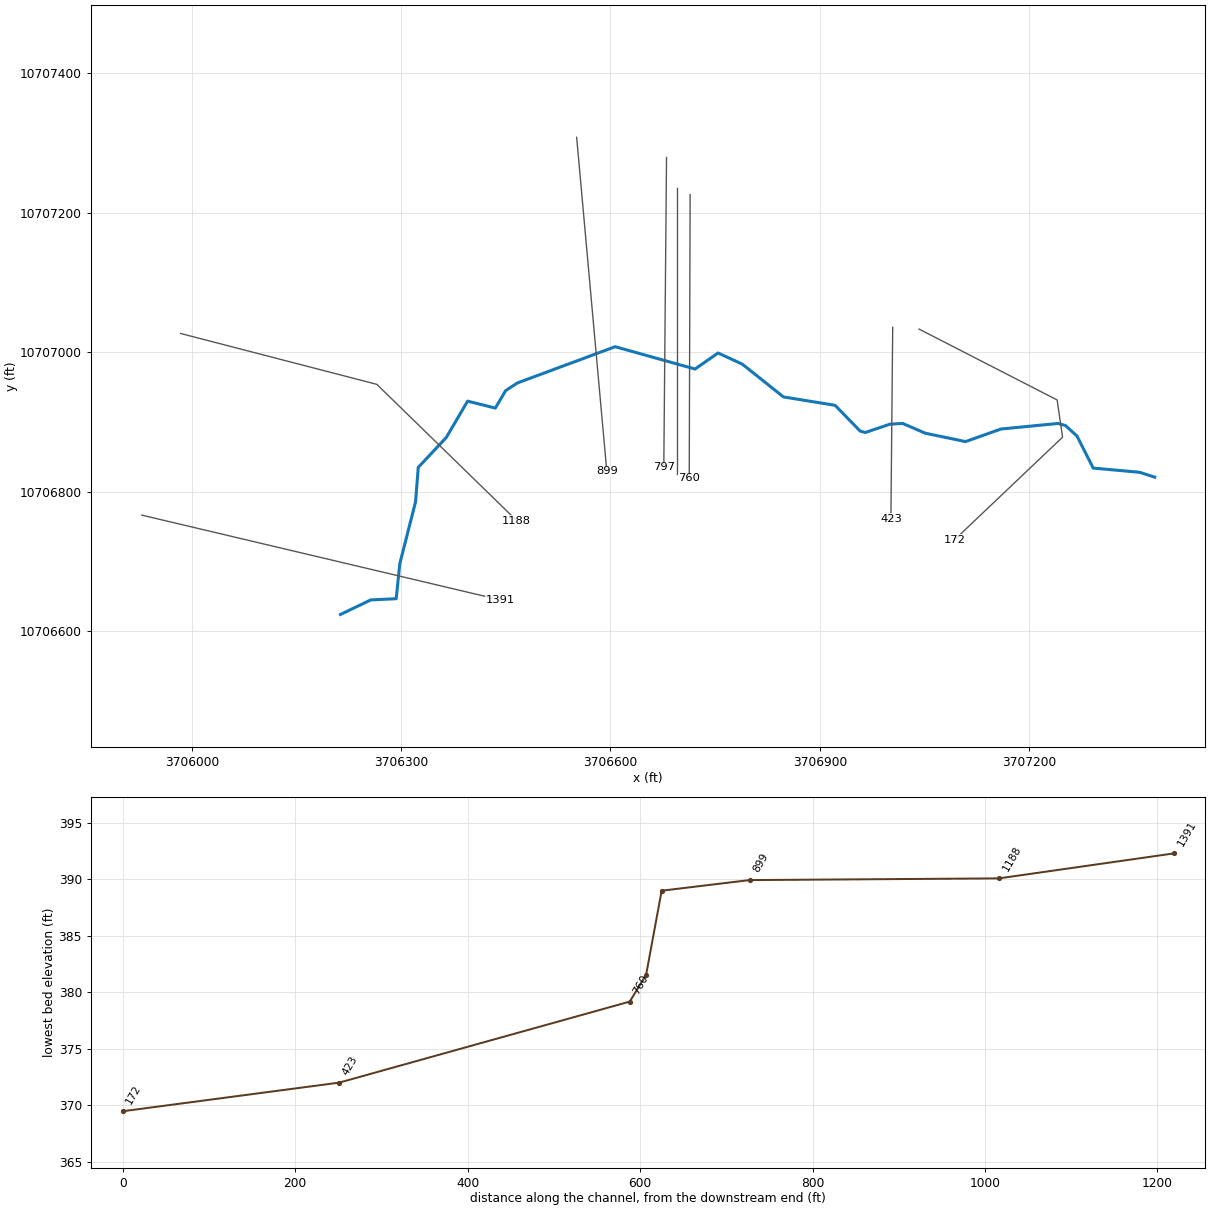
--- UNT 146 IN CACR.prj (project) ---

Proj Title=UNT 146 IN CACR Base Level Engineering
Current Plan=p01
Default Exp/Contr=0.3,0.1
English Units
Geom File=g01
Flow File=f01
Plan File=p01
BEGIN DESCRIPTION:
UNT 146 IN CACR
END DESCRIPTION:

--- UNT 146 IN CACR.p01 (plan) ---

Plan Title=Multiple Run
Short Identifier=Multiple
Geom File=g01
Flow File=f01
Subcritical Flow
K Sum by GR= 0
Std Step Tol= 0.01
Critical Tol= 0.01
Num of Std Step Trials= 20
Max Error Tol= 0.3
Flow Tol Ratio= 0.001
Split Flow NTrial= 30
Split Flow Tol= 0.02
Split Flow Ratio= 0.02
Log Output Level= 0
Friction Slope Method= 1
Unsteady Friction Slope Method= 2
Unsteady Bridges Friction Slope Method= 1
Parabolic Critical Depth
Global Vel Dist=  1 , 1 , 1
Global Log Level= 0
CheckData=True
Encroach Param= -1, 0, 0, 0
BEGIN DESCRIPTION:
Multiple Run
END DESCRIPTION:

--- UNT 146 IN CACR.f01 (steady flow) ---

Flow Title=Multiple
Number of Profiles=7
Profile Names=10-year,25-year,50-year,1pct_min,100-year,1pct_plu,500-year
River Rch & RM= UNT 146 IN CACR,Reach-1,1391
     158     198     229     197     266     360     357
River Rch & RM= UNT 146 IN CACR,Reach-1,172
     377     502     605     536     725     981    1047
Boundary for River Rch & Prof#=UNT 146 IN CACR,Reach-1,1
Up Type=0
Dn Type=3
Dn Slope=0.005
Boundary for River Rch & Prof#=UNT 146 IN CACR,Reach-1,2
Up Type=0
Dn Type=3
Dn Slope=0.005
Boundary for River Rch & Prof#=UNT 146 IN CACR,Reach-1,3
Up Type=0
Dn Type=3
Dn Slope=0.005
Boundary for River Rch & Prof#=UNT 146 IN CACR,Reach-1,4
Up Type=0
Dn Type=3
Dn Slope=0.005
Boundary for River Rch & Prof#=UNT 146 IN CACR,Reach-1,5
Up Type=0
Dn Type=3
Dn Slope=0.005
Boundary for River Rch & Prof#=UNT 146 IN CACR,Reach-1,6
Up Type=0
Dn Type=3
Dn Slope=0.005
Boundary for River Rch & Prof#=UNT 146 IN CACR,Reach-1,7
Up Type=0
Dn Type=3
Dn Slope=0.005

--- UNT 146 IN CACR.g01 (geometry) ---

Geom Title=Existing Conditions

River Reach=UNT 146 IN CACR,Reach-1
Reach XY= 30
      3706213.01     10706624.19      3706256.41     10706645.03
      3706292.87     10706646.76      3706298.08     10706697.11
      3706320.65     10706785.65      3706324.50     10706835.00
      3706364.75     10706878.00      3706395.25     10706930.00
      3706435.00     10706920.00      3706449.75     10706945.00
      3706466.50     10706956.00      3706606.75     10707008.00
      3706721.25     10706976.00      3706754.25     10706999.00
      3706789.00     10706983.00      3706848.00     10706936.00
      3706922.00     10706924.00      3706958.00     10706887.00
      3706965.25     10706885.00      3707000.75     10706897.00
      3707019.00     10706898.00      3707051.25     10706884.00
      3707109.00     10706872.00      3707159.75     10706890.00
      3707241.75     10706898.00      3707252.25     10706895.00
      3707268.75     10706880.00      3707292.00     10706834.00
      3707358.50     10706828.00      3707380.25     10706821.00

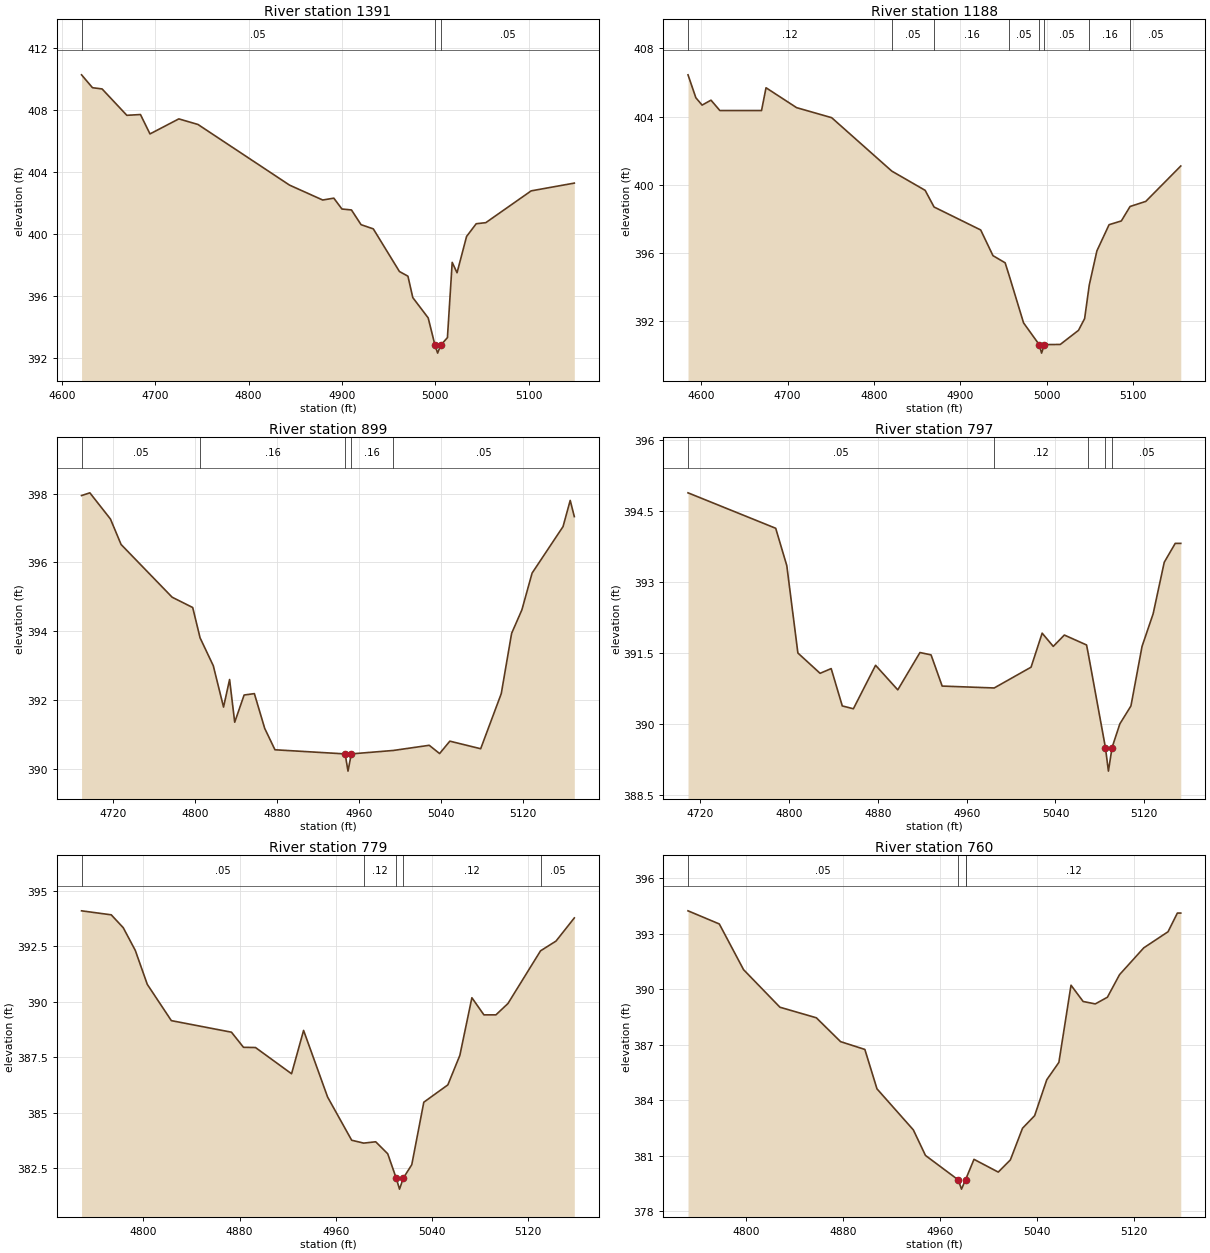
Type RM Length L Ch R = 1,1391,203,203,203
BEGIN DESCRIPTION:
UNT 146 IN CACR 2.0
END DESCRIPTION:
XS GIS Cut Line= 2
      3705928.24     10706766.56      3706441.87     10706645.10
#Sta/Elev= 30
  4621.1  410.24  4632.8  409.41  4643.1  409.33  4669.6  407.63  4684.2  407.68
  4694.4  406.43  4725.3  407.40  4745.8  407.04  4843.9  403.13  4879.4  402.17
  4891.3  402.29  4900.0  401.59  4910.2  401.53  4920.5  400.58  4933.6  400.31
  4961.6  397.56  4970.7  397.26  4975.9  395.88  4992.4  394.57  4999.7  392.80
  5002.5  392.30  5005.7  392.80  5013.0  393.30  5018.1  398.15  5023.3  397.48
  5033.5  399.82  5043.8  400.64  5054.1  400.71  5102.7  402.76  5148.9  403.26
#Mann=3,-1,0
  4621.1    0.05       0  4999.7    0.03       0  5005.7    0.05       0
Bank Sta=4999.7,5005.7
Exp/Cntr=0.3,0.1

Type RM Length L Ch R = 1,1188,289,289,289
BEGIN DESCRIPTION:
Mapping XS 8f449383
END DESCRIPTION:
XS GIS Cut Line= 3
      3705983.85     10707026.97      3706265.09     10706954.05
      3706465.56     10706758.78
#Sta/Elev= 30
  4584.7  406.45  4593.8  405.10  4601.0  404.67  4611.3  404.96  4621.6  404.35
  4669.8  404.35  4675.0  405.69  4710.4  404.52  4751.0  403.93  4820.6  400.79
  4859.2  399.66  4869.5  398.68  4923.5  397.33  4937.7  395.82  4951.8  395.40
  4956.7  394.61  4973.1  391.87  4991.2  390.59  4994.0  390.09  4997.2  390.59
  5015.6  390.60  5036.7  391.43  5043.8  392.12  5049.2  394.10  5058.0  396.10
  5072.1  397.64  5086.3  397.86  5096.4  398.71  5114.6  399.01  5155.1  401.09
#Mann=8,-1,0
  4584.7    0.12       0  4820.6    0.05       0  4869.5    0.16       0
  4956.7    0.05       0  4991.2    0.03       0  4997.2    0.05       0
  5049.2    0.16       0  5096.4    0.05       0
Bank Sta=4991.2,4997.2
Exp/Cntr=0.3,0.1

Type RM Length L Ch R = 1,899,102,102,102
BEGIN DESCRIPTION:
Mapping XS 28c4a3e0
END DESCRIPTION:
XS GIS Cut Line= 2
      3706551.55     10707308.24      3706594.79     10706829.19
#Sta/Elev= 30
  4689.3  397.94  4697.4  398.02  4717.5  397.26  4727.9  396.52  4777.7  394.99
  4797.8  394.69  4805.0  393.81  4817.9  393.00  4827.9  391.80  4833.8  392.60
  4838.8  391.36  4848.0  392.15  4858.0  392.19  4868.1  391.18  4878.1  390.56
  4946.6  390.44  4949.4  389.94  4952.6  390.44  4993.6  390.54  5028.7  390.69
  5038.8  390.45  5048.8  390.81  5078.9  390.59  5099.0  392.19  5109.1  393.94
  5119.1  394.62  5129.1  395.69  5159.3  397.04  5166.3  397.80  5170.3  397.33
#Mann=5,-1,0
  4689.3    0.05       0  4805.0    0.16       0  4946.6    0.03       0
  4952.6    0.16       0  4993.6    0.05       0
Bank Sta=4946.6,4952.6
Exp/Cntr=0.3,0.1

Type RM Length L Ch R = 1,797,18,18,18
BEGIN DESCRIPTION:
Mapping XS 913a063f
END DESCRIPTION:
XS GIS Cut Line= 2
      3706680.38     10707279.23      3706676.47     10706835.24
#Sta/Elev= 30
  4708.9  394.89  4787.9  394.14  4797.9  393.35  4807.9  391.50  4827.9  391.07
  4837.9  391.17  4847.9  390.38  4857.9  390.32  4877.9  391.24  4897.9  390.72
  4917.9  391.51  4927.9  391.46  4937.9  390.80  4984.8  390.76  5018.0  391.20
  5028.0  391.92  5038.0  391.64  5048.0  391.88  5068.0  391.67  5069.5  391.49
  5085.0  389.50  5087.7  389.00  5091.0  389.50  5098.0  390.00  5108.0  390.38
  5118.0  391.64  5128.0  392.33  5138.0  393.42  5147.9  393.82  5152.9  393.82
#Mann=5,-1,0
  4708.9    0.05       0  4984.8    0.12       0  5069.5    0.05       0
  5085.0    0.07       0  5091.0    0.05       0
Bank Sta=5085,5091
Exp/Cntr=0.3,0.1

Type RM Length L Ch R = 1,779,19,19,19
BEGIN DESCRIPTION:
Mapping XS 8f3ce192
END DESCRIPTION:
XS GIS Cut Line= 2
      3706694.70     10707234.92      3706694.70     10706825.02
#Sta/Elev= 30
  4748.5  394.09  4773.2  393.91  4783.2  393.33  4793.2  392.31  4803.2  390.78
  4823.2  389.15  4873.2  388.63  4883.2  387.95  4893.2  387.94  4923.2  386.76
  4933.2  388.71  4953.2  385.71  4973.2  383.77  4983.2  383.64  4993.2  383.70
  5003.2  383.16  5010.2  382.07  5013.0  381.57  5016.2  382.07  5023.2  382.67
  5033.2  385.48  5053.2  386.26  5063.2  387.59  5073.2  390.18  5083.2  389.41
  5093.2  389.41  5103.2  389.92  5130.3  392.29  5143.2  392.73  5158.4  393.77
#Mann=5,-1,0
  4748.5    0.05       0  4983.2    0.12       0  5010.2    0.07       0
  5016.2    0.12       0  5130.3    0.05       0
Bank Sta=5010.2,5016.2
Exp/Cntr=0.3,0.1

Type RM Length L Ch R = 1,760,337,337,337
BEGIN DESCRIPTION:
Mapping XS ffc95281
END DESCRIPTION:
XS GIS Cut Line= 2
      3706714.23     10707225.98      3706712.93     10706819.68
#Sta/Elev= 30
  4752.2  394.23  4778.0  393.52  4798.0  391.05  4828.0  389.02  4858.0  388.45
  4878.0  387.16  4898.0  386.74  4908.0  384.61  4938.0  382.39  4948.0  381.01
  4975.0  379.69  4977.7  379.19  4981.0  379.69  4981.5  379.77  4988.0  380.80
  5008.0  380.11  5018.0  380.77  5028.0  382.48  5038.0  383.16  5048.0  385.10
  5058.0  386.04  5068.0  390.21  5078.0  389.33  5088.0  389.20  5098.0  389.56
  5108.0  390.78  5128.0  392.23  5148.0  393.10  5155.7  394.11  5158.5  394.11
#Mann=4,-1,0
  4752.2    0.05       0  4975.0    0.07       0  4981.0    0.05       0
  4981.5    0.12       0
Bank Sta=4975,4981
Exp/Cntr=0.3,0.1

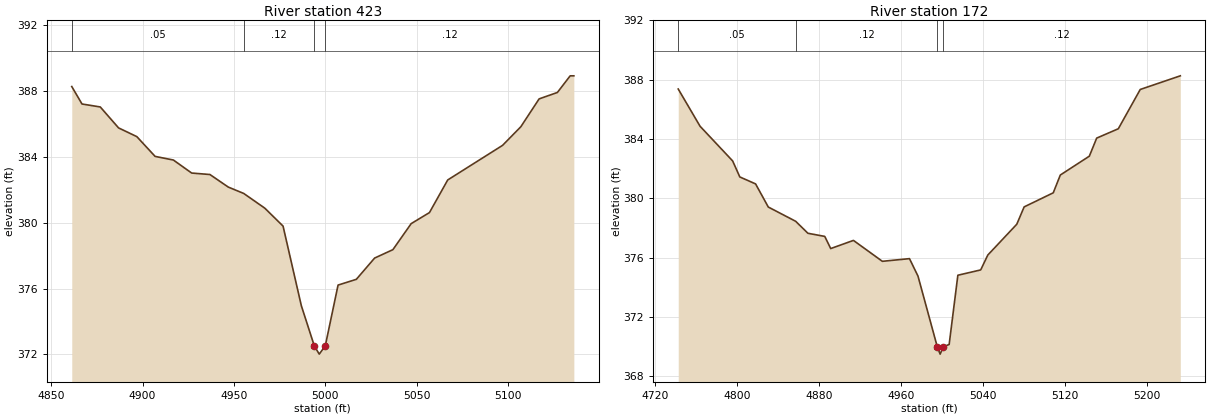
Type RM Length L Ch R = 1,423,251,251,251
BEGIN DESCRIPTION:
Mapping XS c1c2e62c
END DESCRIPTION:
XS GIS Cut Line= 2
      3707004.60     10707035.83      3707001.99     10706761.15
#Sta/Elev= 30
  4861.3  388.26  4866.9  387.20  4876.9  387.02  4886.9  385.75  4896.9  385.22
  4906.9  384.02  4916.9  383.80  4926.9  383.01  4936.9  382.92  4946.9  382.16
  4955.4  381.77  4966.9  380.88  4976.9  379.79  4986.9  374.96  4994.0  372.52
  4996.7  372.02  5000.0  372.52  5007.0  376.21  5017.0  376.56  5027.0  377.85
  5037.0  378.36  5047.0  379.94  5057.0  380.61  5067.0  382.59  5097.0  384.69
  5107.0  385.82  5117.0  387.51  5127.0  387.90  5134.0  388.91  5136.0  388.91
#Mann=4,-1,0
  4861.3    0.05       0  4955.4    0.12       0  4994.0    0.07       0
  5000.0    0.12       0
Bank Sta=4994,5000
Exp/Cntr=0.3,0.1

Type RM Length L Ch R = 1,172,0,0,0
BEGIN DESCRIPTION:
UNT 146 IN CACR 1.0
END DESCRIPTION:
XS GIS Cut Line= 4
      3707042.40     10707033.23      3707240.28     10706931.69
      3707248.09     10706878.30      3707093.20     10706731.16
#Sta/Elev= 30
  4742.5  387.37  4763.8  384.86  4795.6  382.52  4802.6  381.44  4818.0  380.97
  4830.4  379.41  4857.1  378.45  4869.1  377.64  4885.5  377.43  4891.3  376.61
  4913.5  377.16  4941.7  375.75  4968.2  375.93  4976.5  374.75  4995.3  369.99
  4998.1  369.49  5001.3  369.99  5006.9  370.14  5015.4  374.81  5037.7  375.17
  5044.6  376.17  5072.9  378.25  5080.1  379.42  5108.5  380.37  5115.4  381.57
  5143.7  382.84  5150.9  384.06  5172.0  384.69  5193.4  387.34  5232.5  388.26
#Mann=4,-1,0
  4742.5    0.05       0  4857.1    0.12       0  4995.3    0.07       0
  5001.3    0.12       0
Bank Sta=4995.3,5001.3
Exp/Cntr=0.3,0.1

Chan Stop Cuts=-1