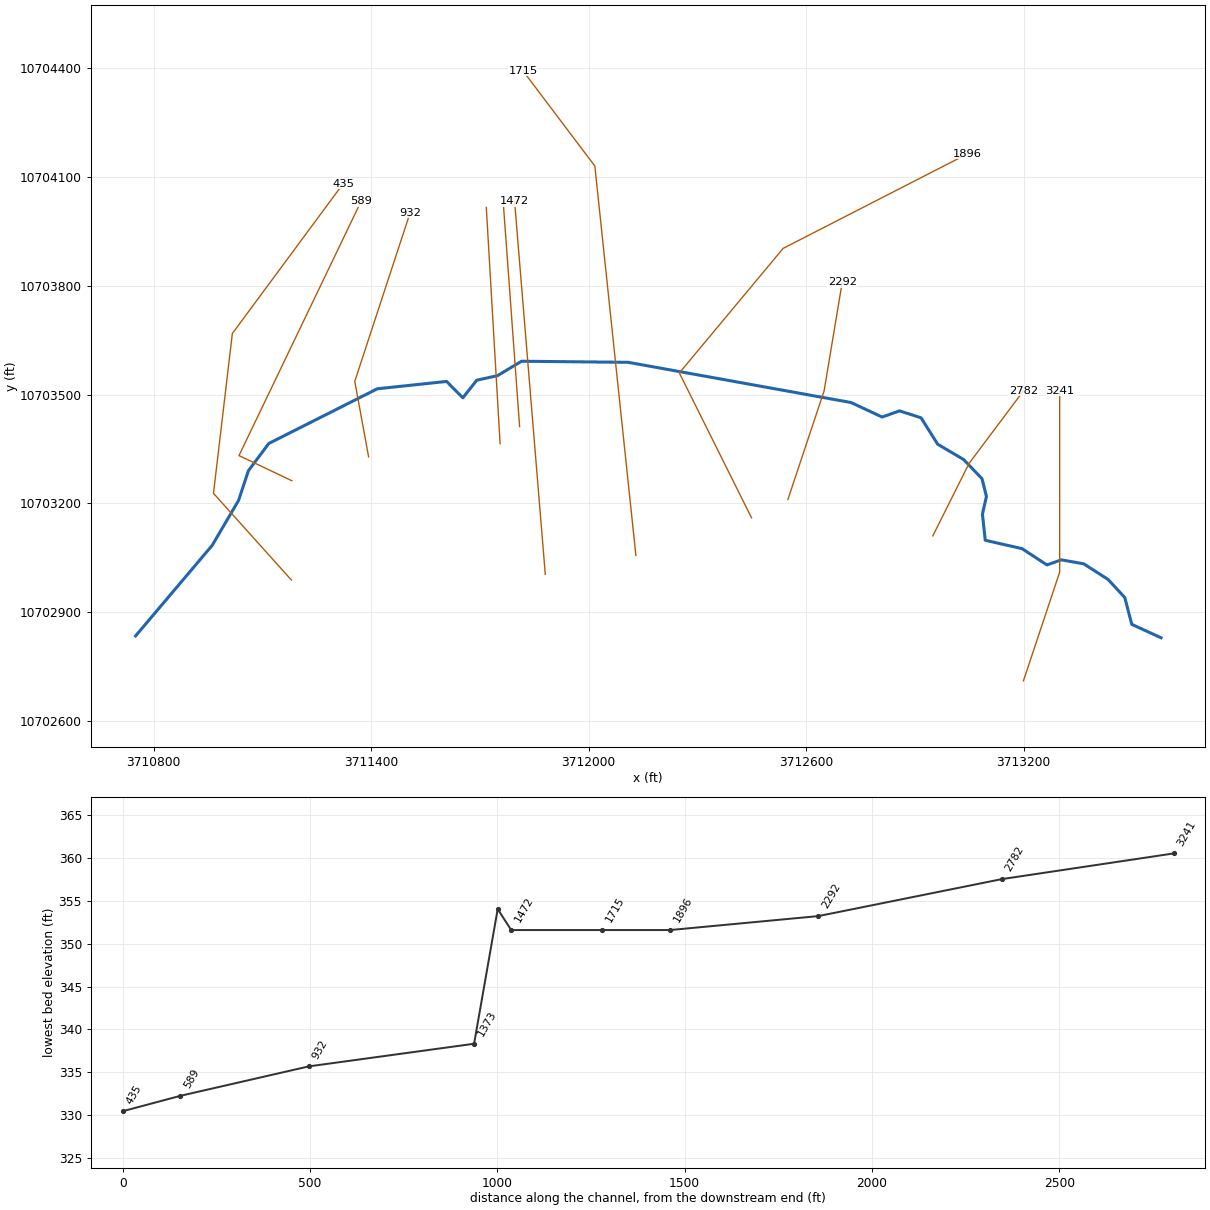
--- UNT 147 IN CACR.prj (project) ---

Proj Title=UNT 147 IN CACR Base Level Engineering
Current Plan=p01
Default Exp/Contr=0.3,0.1
English Units
Geom File=g01
Flow File=f01
Plan File=p01
BEGIN DESCRIPTION:
UNT 147 IN CACR
END DESCRIPTION:

--- UNT 147 IN CACR.p01 (plan) ---

Plan Title=Multiple Run
Short Identifier=Multiple
Geom File=g01
Flow File=f01
Subcritical Flow
K Sum by GR= 0
Std Step Tol= 0.01
Critical Tol= 0.01
Num of Std Step Trials= 20
Max Error Tol= 0.3
Flow Tol Ratio= 0.001
Split Flow NTrial= 30
Split Flow Tol= 0.02
Split Flow Ratio= 0.02
Log Output Level= 0
Friction Slope Method= 1
Unsteady Friction Slope Method= 2
Unsteady Bridges Friction Slope Method= 1
Parabolic Critical Depth
Global Vel Dist=  1 , 1 , 1
Global Log Level= 0
CheckData=True
Encroach Param= -1, 0, 0, 0
BEGIN DESCRIPTION:
Multiple Run
END DESCRIPTION:

--- UNT 147 IN CACR.f01 (steady flow) ---

Flow Title=Multiple
Number of Profiles=7
Profile Names=10-year,25-year,50-year,1pct_min,100-year,1pct_plu,500-year
River Rch & RM= UNT 147 IN CACR,Reach-1,3241
     592     805     981     880    1190    1609    1755
River Rch & RM= UNT 147 IN CACR,Reach-1,2782
     629     858    1047     940    1271    1719    1881
Boundary for River Rch & Prof#=UNT 147 IN CACR,Reach-1,1
Up Type=0
Dn Type=3
Dn Slope=0.005
Boundary for River Rch & Prof#=UNT 147 IN CACR,Reach-1,2
Up Type=0
Dn Type=3
Dn Slope=0.005
Boundary for River Rch & Prof#=UNT 147 IN CACR,Reach-1,3
Up Type=0
Dn Type=3
Dn Slope=0.005
Boundary for River Rch & Prof#=UNT 147 IN CACR,Reach-1,4
Up Type=0
Dn Type=3
Dn Slope=0.005
Boundary for River Rch & Prof#=UNT 147 IN CACR,Reach-1,5
Up Type=0
Dn Type=3
Dn Slope=0.005
Boundary for River Rch & Prof#=UNT 147 IN CACR,Reach-1,6
Up Type=0
Dn Type=3
Dn Slope=0.005
Boundary for River Rch & Prof#=UNT 147 IN CACR,Reach-1,7
Up Type=0
Dn Type=3
Dn Slope=0.005

--- UNT 147 IN CACR.g01 (geometry) ---

Geom Title=Existing Conditions

River Reach=UNT 147 IN CACR,Reach-1
Reach XY= 30
      3713579.25     10702829.00      3713498.50     10702866.00
      3713479.25     10702940.00      3713433.00     10702990.00
      3713366.00     10703033.00      3713304.25     10703044.00
      3713264.50     10703030.00      3713195.50     10703075.00
      3713094.25     10703098.00      3713086.50     10703170.00
      3713097.50     10703219.00      3713085.25     10703268.00
      3713034.25     10703321.00      3712963.00     10703363.00
      3712917.00     10703436.00      3712857.75     10703455.00
      3712809.75     10703438.00      3712724.25     10703478.00
      3712109.00     10703589.00      3711814.75     10703592.00
      3711748.28     10703552.20      3711691.34     10703539.70
      3711652.80     10703491.09      3711608.00     10703536.23
      3711416.75     10703516.00      3711117.25     10703365.00
      3711061.25     10703290.00      3711034.00     10703208.00
      3710961.25     10703084.00      3710749.75     10702834.00

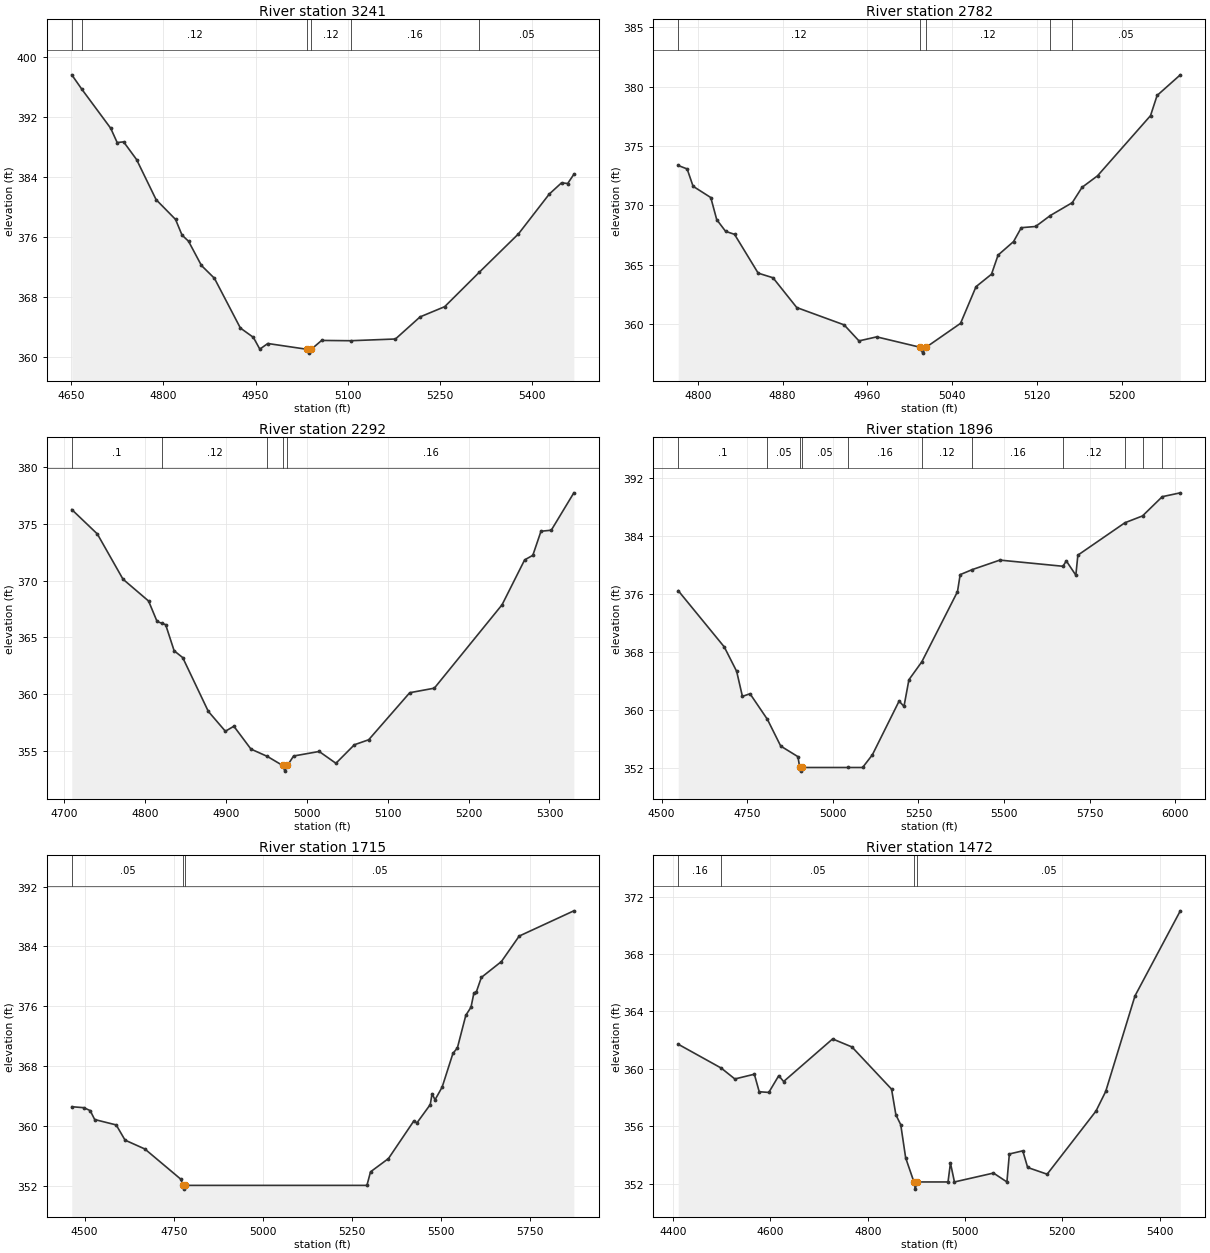
Type RM Length L Ch R = 1,3241,459,459,459
BEGIN DESCRIPTION:
UNT 147 IN CACR 6.0
END DESCRIPTION:
XS GIS Cut Line= 3
      3713199.60     10702710.17      3713299.61     10703010.19
      3713299.61     10703510.14
#Sta/Elev= 30
  4651.2  397.59  4667.7  395.66  4714.5  390.48  4725.0  388.58  4735.5  388.67
  4756.6  386.31  4788.3  380.98  4819.9  378.35  4830.4  376.27  4841.0  375.45
  4862.0  372.22  4883.1  370.52  4925.3  363.90  4946.4  362.66  4956.9  361.09
  4969.9  361.84  5034.4  361.06  5037.2  360.56  5040.4  361.06  5057.4  362.25
  5104.6  362.21  5177.4  362.44  5217.4  365.38  5257.4  366.74  5313.8  371.33
  5377.4  376.43  5427.4  381.72  5447.4  383.22  5457.4  383.13  5467.4  384.35
#Mann=6,-1,0
  4651.2    0.05       0  4667.7    0.12       0  5034.4    0.07       0
  5040.4    0.12       0  5104.6    0.16       0  5313.8    0.05       0
Bank Sta=5034.4,5040.4
Exp/Cntr=0.3,0.1

Type RM Length L Ch R = 1,2782,490,490,490
BEGIN DESCRIPTION:
UNT 147 IN CACR 5.0
END DESCRIPTION:
XS GIS Cut Line= 3
      3712949.62     10703110.21      3713049.61     10703310.19
      3713199.62     10703510.20
#Sta/Elev= 30
  4781.5  373.37  4789.9  373.08  4795.5  371.62  4812.2  370.67  4817.8  368.81
  4826.2  367.82  4834.6  367.57  4856.9  364.30  4870.9  363.91  4893.3  361.40
  4938.0  359.94  4952.0  358.59  4968.7  358.93  5009.4  358.06  5012.1  357.56
  5015.4  358.06  5047.8  360.07  5062.4  363.16  5077.0  364.21  5083.2  365.82
  5097.8  366.96  5105.1  368.13  5118.6  368.23  5132.4  369.15  5153.2  370.24
  5162.4  371.53  5177.0  372.50  5227.0  377.57  5233.2  379.27  5255.1  381.01
#Mann=5,-1,0
  4781.5    0.12       0  5009.4    0.07       0  5015.4    0.12       0
  5132.4    0.16       0  5153.2    0.05       0
Bank Sta=5009.4,5015.4
Exp/Cntr=0.3,0.1

Type RM Length L Ch R = 1,2292,396,396,396
BEGIN DESCRIPTION:
UNT 147 IN CACR 4.0
END DESCRIPTION:
XS GIS Cut Line= 3
      3712549.60     10703210.17      3712649.61     10703510.19
      3712699.61     10703810.20
#Sta/Elev= 30
  4709.7  376.26  4741.3  374.11  4773.0  370.13  4804.6  368.21  4815.1  366.41
  4821.0  366.25  4825.7  366.13  4836.2  363.83  4846.8  363.23  4878.4  358.50
  4899.5  356.75  4910.0  357.19  4931.1  355.18  4951.5  354.53  4970.2  353.74
  4973.0  353.24  4976.2  353.74  4983.8  354.57  5015.4  354.97  5036.1  353.93
  5058.9  355.56  5076.6  356.00  5127.3  360.14  5157.7  360.54  5241.4  367.88
  5269.3  371.83  5279.4  372.23  5289.5  374.35  5302.2  374.44  5330.1  377.73
#Mann=5,-1,0
  4709.7     0.1       0  4821.0    0.12       0  4951.5    0.16       0
  4970.2    0.07       0  4976.2    0.16       0
Bank Sta=4970.2,4976.2
Exp/Cntr=0.3,0.1

Type RM Length L Ch R = 1,1896,181,181,181
BEGIN DESCRIPTION:
Mapping XS 212fed1e
END DESCRIPTION:
XS GIS Cut Line= 4
      3712449.40     10703159.93      3712250.18     10703559.66
      3712536.64     10703903.41      3713045.83     10704164.49
#Sta/Elev= 30
  4548.5  376.45  4682.9  368.71  4719.1  365.35  4735.9  361.90  4758.2  362.26
  4809.0  358.73  4847.8  355.06  4898.1  353.60  4903.3  352.11  4906.1  351.61
  4909.3  352.11  5045.3  352.11  5086.9  352.11  5115.4  353.85  5193.5  361.25
  5207.8  360.52  5222.2  364.19  5259.9  366.66  5364.0  376.31  5371.9  378.66
  5407.7  379.36  5487.8  380.66  5672.0  379.81  5681.9  380.55  5709.7  378.58
  5715.6  381.34  5853.0  385.80  5904.4  386.74  5962.1  389.39  6014.8  389.92
#Mann=11,-1,0
  4548.5     0.1       0  4809.0    0.05       0  4903.3   0.033       0
  4909.3    0.05       0  5045.3    0.16       0  5259.9    0.12       0
  5407.7    0.16       0  5672.0    0.12       0  5853.0    0.16       0
  5904.4    0.05       0  5962.1    0.16       0
Bank Sta=4903.3,4909.3
Exp/Cntr=0.3,0.1

Type RM Length L Ch R = 1,1715,243,243,243
BEGIN DESCRIPTION:
Mapping XS 7d4ffa3c
END DESCRIPTION:
XS GIS Cut Line= 3
      3712130.28     10703056.21      3712017.02     10704130.61
      3711818.83     10704393.15
#Sta/Elev= 30
  4463.9  362.61  4498.1  362.48  4515.6  362.09  4528.2  360.90  4588.6  360.18
  4613.5  358.15  4669.0  356.97  4769.6  352.95  4776.6  352.11  4779.4  351.61
  4782.6  352.11  5292.4  352.11  5302.5  353.92  5352.8  355.69  5423.2  360.65
  5433.2  360.48  5470.2  362.90  5475.2  364.35  5483.5  363.53  5503.6  365.24
  5533.8  369.73  5546.3  370.46  5570.0  374.82  5584.5  375.89  5592.8  377.82
  5599.1  377.88  5613.6  379.87  5669.9  381.99  5719.8  385.39  5873.2  388.76
#Mann=3,-1,0
  4463.9    0.05       0  4776.6   0.033       0  4782.6    0.05       0
Bank Sta=4776.6,4782.6
Exp/Cntr=0.3,0.1

Type RM Length L Ch R = 1,1472,36,36,36
BEGIN DESCRIPTION:
Mapping XS 55660a16
END DESCRIPTION:
XS GIS Cut Line= 2
      3711880.27     10703004.21      3711795.57     10704033.03
#Sta/Elev= 30
  4410.4  361.71  4498.7  360.05  4526.8  359.29  4566.9  359.62  4576.9  358.40
  4596.6  358.35  4617.1  359.52  4627.1  359.11  4727.8  362.08  4767.6  361.52
  4849.0  358.58  4857.9  356.79  4867.9  356.10  4878.0  353.79  4895.0  352.11
  4897.8  351.61  4901.0  352.11  4965.1  352.11  4970.1  353.43  4978.3  352.11
  5058.6  352.73  5086.2  352.11  5091.2  354.06  5118.8  354.28  5128.8  353.12
  5168.9  352.65  5269.3  357.05  5289.3  358.42  5349.5  365.08  5442.7  371.01
#Mann=4,-1,0
  4410.4    0.16       0  4498.7    0.05       0  4895.0    0.03       0
  4901.0    0.05       0
Bank Sta=4895,4901
Exp/Cntr=0.3,0.1

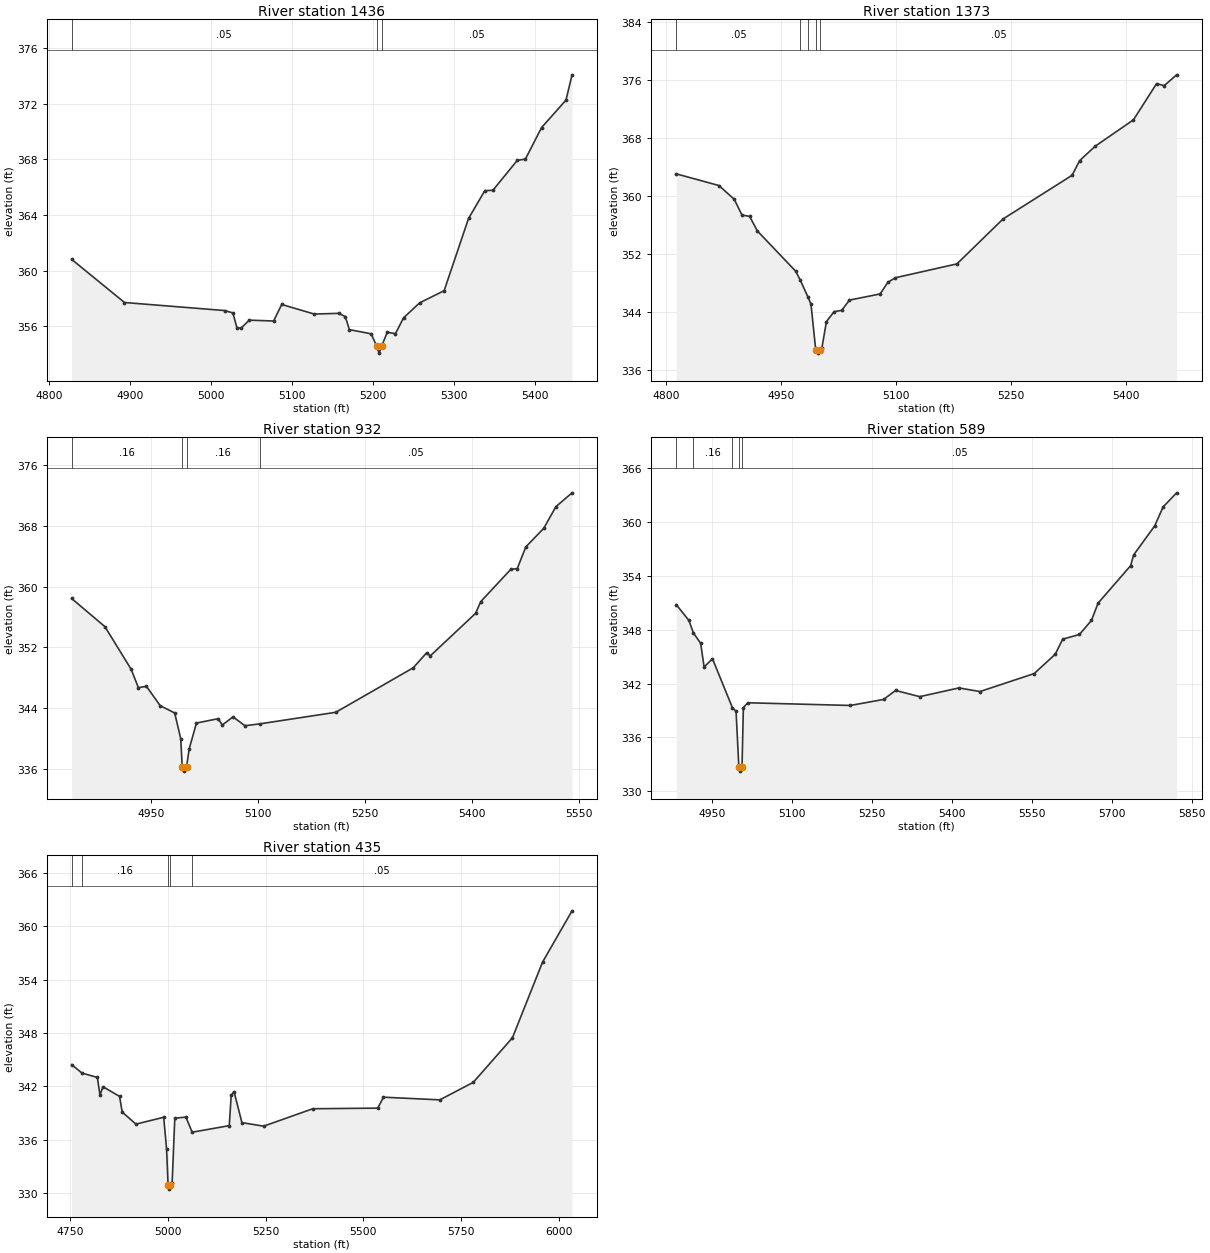
Type RM Length L Ch R = 1,1436,63,63,63
BEGIN DESCRIPTION:
Mapping XS 0a03b461
END DESCRIPTION:
XS GIS Cut Line= 2
      3711809.46     10703411.58      3711764.46     10704027.64
#Sta/Elev= 30
  4827.6  360.80  4892.8  357.70  5016.7  357.12  5026.6  356.95  5031.6  355.88
  5036.8  355.86  5046.8  356.43  5076.9  356.37  5086.9  357.56  5127.0  356.87
  5157.1  356.92  5165.4  356.69  5170.4  355.75  5197.2  355.45  5204.2  354.56
  5207.0  354.06  5210.2  354.56  5217.2  355.56  5227.3  355.46  5237.3  356.60
  5257.3  357.68  5287.4  358.55  5317.5  363.74  5337.6  365.74  5347.6  365.77
  5377.7  367.92  5387.7  368.01  5407.7  370.28  5437.8  372.25  5445.3  374.07
#Mann=3,-1,0
  4827.6    0.05       0  5204.2    0.03       0  5210.2    0.05       0
Bank Sta=5204.2,5210.2
Exp/Cntr=0.3,0.1

Type RM Length L Ch R = 1,1373,441,441,441
BEGIN DESCRIPTION:
Mapping XS 65dadb0e
END DESCRIPTION:
XS GIS Cut Line= 2
      3711755.64     10703364.66      3711717.51     10704016.34
#Sta/Elev= 30
  4812.8  363.08  4868.4  361.47  4888.5  359.56  4898.5  357.39  4908.5  357.21
  4918.5  355.21  4968.6  349.64  4974.8  348.36  4984.5  346.10  4988.6  345.07
  4994.7  338.83  4997.4  338.33  5000.7  338.83  5002.7  338.99  5008.7  342.68
  5018.7  344.05  5028.7  344.24  5038.7  345.65  5078.8  346.50  5088.8  348.10
  5098.8  348.74  5179.0  350.65  5239.1  356.85  5329.2  362.88  5339.1  364.91
  5359.3  366.89  5409.3  370.54  5439.4  375.53  5449.4  375.26  5465.6  376.75
#Mann=5,-1,0
  4812.8    0.05       0  4974.8    0.16       0  4984.5    0.05       0
  4994.7    0.03       0  5000.7    0.05       0
Bank Sta=4994.7,5000.7
Exp/Cntr=0.3,0.1

Type RM Length L Ch R = 1,932,343,343,343
BEGIN DESCRIPTION:
UNT 147 IN CACR 2.0
END DESCRIPTION:
XS GIS Cut Line= 3
      3711392.79     10703328.20      3711354.60     10703536.55
      3711507.36     10704001.79
#Sta/Elev= 30
  4839.3  358.43  4885.9  354.72  4922.7  349.10  4932.8  346.69  4944.1  346.86
  4963.3  344.32  4983.7  343.35  4992.2  339.97  4994.3  336.19  4997.0  335.69
  5000.3  336.19  5004.0  338.61  5014.2  342.02  5044.7  342.60  5050.4  341.76
  5065.5  342.84  5082.2  341.67  5103.3  341.92  5209.5  343.44  5318.1  349.30
  5336.8  351.26  5342.0  350.87  5405.6  356.48  5412.8  358.02  5454.9  362.27
  5464.0  362.37  5476.0  365.23  5501.1  367.67  5518.1  370.52  5540.8  372.35
#Mann=4,-1,0
  4839.3    0.16       0  4994.3    0.07       0  5000.3    0.16       0
  5103.3    0.05       0
Bank Sta=4994.3,5000.3
Exp/Cntr=0.3,0.1

Type RM Length L Ch R = 1,589,154,154,154
BEGIN DESCRIPTION:
UNT 147 IN CACR 1.0
END DESCRIPTION:
XS GIS Cut Line= 3
      3711180.97     10703262.26      3711035.15     10703331.69
      3711371.97     10704033.11
#Sta/Elev= 30
  4882.2  350.78  4905.9  349.03  4914.3  347.64  4928.0  346.48  4934.5  343.84
  4950.2  344.76  4987.5  339.33  4994.5  338.89  4999.7  332.75  5002.4  332.25
  5005.7  332.75  5008.2  339.33  5016.6  339.86  5209.1  339.56  5271.5  340.23
  5294.1  341.23  5339.4  340.54  5412.9  341.51  5452.5  341.11  5554.3  343.11
  5594.0  345.27  5607.8  346.94  5639.3  347.46  5661.9  349.03  5674.3  350.95
  5735.4  355.12  5741.0  356.31  5780.7  359.56  5796.4  361.66  5821.8  363.23
#Mann=5,-1,0
  4882.2    0.12       0  4914.3    0.16       0  4987.5    0.05       0
  4999.7    0.03       0  5005.7    0.05       0
Bank Sta=4999.7,5005.7
Exp/Cntr=0.3,0.1

Type RM Length L Ch R = 1,435,0,0,0
BEGIN DESCRIPTION:
Mapping XS 41f9c917
END DESCRIPTION:
XS GIS Cut Line= 4
      3711180.01     10702988.00      3710964.77     10703227.55
      3711016.85     10703668.53      3711322.41     10704081.73
#Sta/Elev= 30
  4753.9  344.45  4780.4  343.50  4819.6  343.01  4826.3  341.02  4833.8  341.97
  4876.4  340.88  4883.1  339.12  4918.2  337.76  4989.3  338.53  4996.7  334.94
  5000.5  330.95  5003.2  330.45  5006.5  330.95  5010.9  331.18  5017.7  338.43
  5046.1  338.55  5062.1  336.85  5157.0  337.59  5162.0  341.00  5169.2  341.42
  5189.4  337.93  5244.9  337.53  5370.6  339.49  5536.9  339.56  5551.5  340.79
  5695.6  340.49  5781.2  342.46  5881.4  347.47  5958.5  355.99  6033.9  361.75
#Mann=5,-1,0
  4753.9    0.12       0  4780.4    0.16       0  5000.5    0.07       0
  5006.5    0.16       0  5062.1    0.05       0
Bank Sta=5000.5,5006.5
Exp/Cntr=0.3,0.1

Chan Stop Cuts=-1