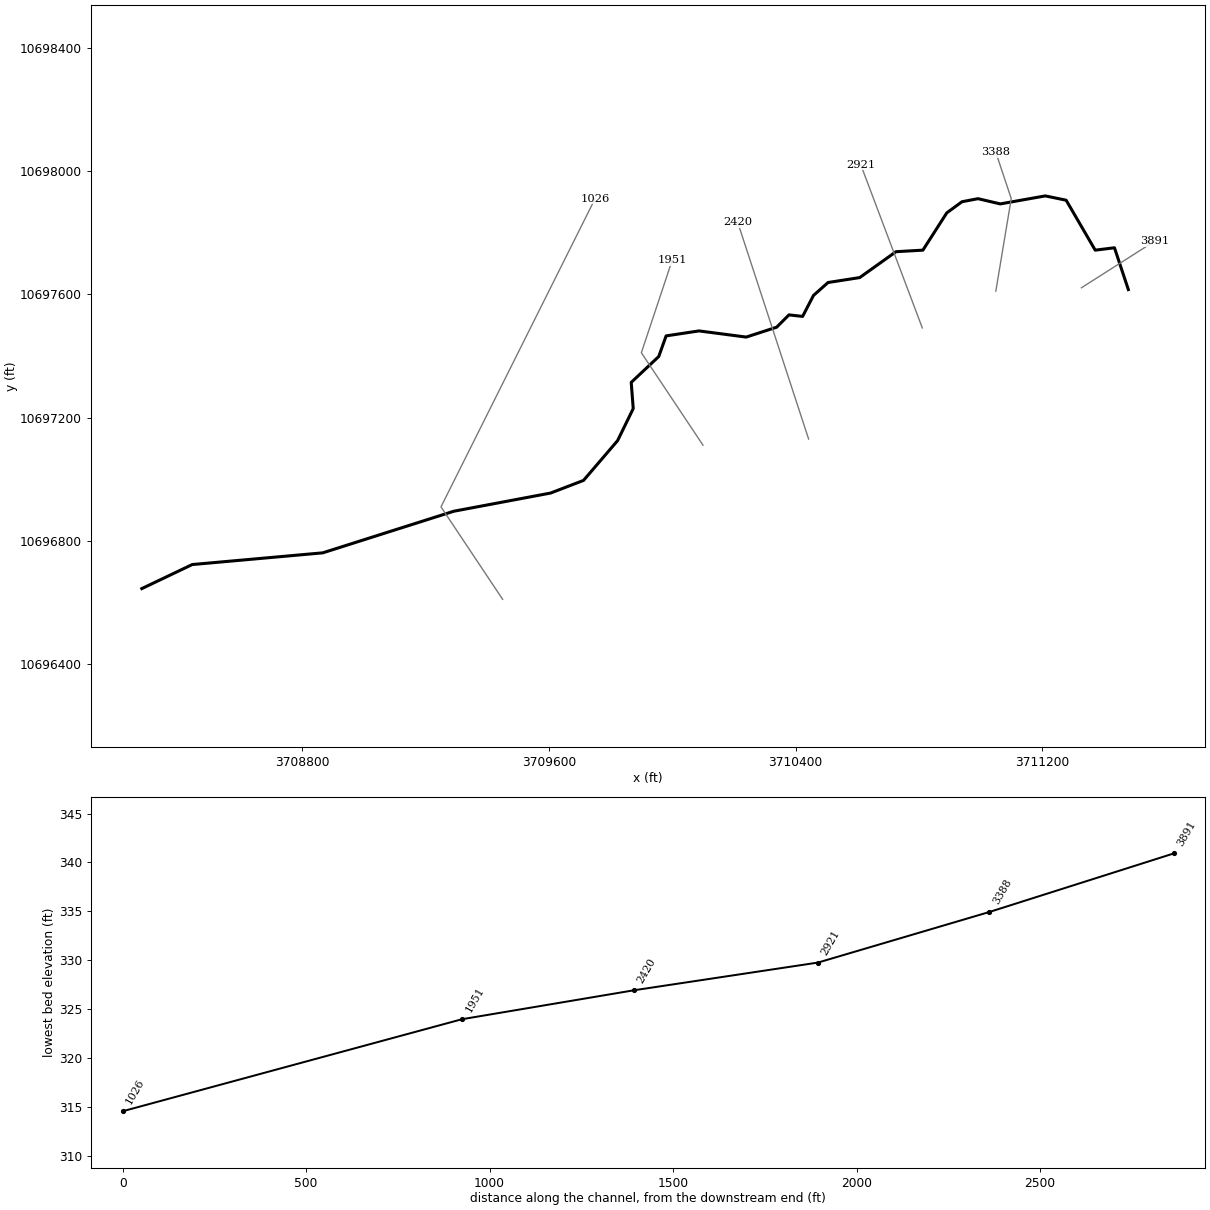
--- UNT 148 IN CACR.prj (project) ---

Proj Title=UNT 148 IN CACR Base Level Engineering
Current Plan=p01
Default Exp/Contr=0.3,0.1
English Units
Geom File=g01
Flow File=f01
Plan File=p01
Y Axis Title=Elevation
X Axis Title(PF)=Main Channel Distance
X Axis Title(XS)=Station
BEGIN DESCRIPTION:
UNT 148 IN CACR
END DESCRIPTION:
DSS Export Rating Curves= 0
DSS Export Rating Curve Sorted= 0
DSS Export Volume Flow Curves= 0
DXF OffsetX= 0
DXF OffsetY= 0
DXF ScaleX= 1
DXF ScaleY= 10

--- UNT 148 IN CACR.p01 (plan) ---

Plan Title=Multiple Run
Short Identifier=Multiple
Geom File=g01
Flow File=f01
Subcritical Flow
K Sum by GR= 0
Std Step Tol= 0.01
Critical Tol= 0.01
Num of Std Step Trials= 20
Max Error Tol= 0.3
Flow Tol Ratio= 0.001
Split Flow NTrial= 30
Split Flow Tol= 0.02
Split Flow Ratio= 0.02
Log Output Level= 0
Friction Slope Method= 1
Unsteady Friction Slope Method= 2
Unsteady Bridges Friction Slope Method= 1
Parabolic Critical Depth
Global Vel Dist=  1 , 1 , 1
Global Log Level= 0
CheckData=True
Encroach Param= -1, 0, 0, 0
BEGIN DESCRIPTION:
Multiple Run
END DESCRIPTION:

--- UNT 148 IN CACR.f01 (steady flow) ---

Flow Title=Multiple
Number of Profiles=7
Profile Names=10-year,25-year,50-year,1pct_min,100-year,1pct_plu,500-year
River Rch & RM= UNT 148 IN CACR,Reach-1,3891
     322     425     508     448     606     820     865
Boundary for River Rch & Prof#=UNT 148 IN CACR,Reach-1,1
Up Type=0
Dn Type=3
Dn Slope=0.005
Boundary for River Rch & Prof#=UNT 148 IN CACR,Reach-1,2
Up Type=0
Dn Type=3
Dn Slope=0.005
Boundary for River Rch & Prof#=UNT 148 IN CACR,Reach-1,3
Up Type=0
Dn Type=3
Dn Slope=0.005
Boundary for River Rch & Prof#=UNT 148 IN CACR,Reach-1,4
Up Type=0
Dn Type=3
Dn Slope=0.005
Boundary for River Rch & Prof#=UNT 148 IN CACR,Reach-1,5
Up Type=0
Dn Type=3
Dn Slope=0.005
Boundary for River Rch & Prof#=UNT 148 IN CACR,Reach-1,6
Up Type=0
Dn Type=3
Dn Slope=0.005
Boundary for River Rch & Prof#=UNT 148 IN CACR,Reach-1,7
Up Type=0
Dn Type=3
Dn Slope=0.005

--- UNT 148 IN CACR.g01 (geometry) ---

Geom Title=Existing Conditions
Program Version=4.10

River Reach=UNT 148 IN CACR ,Reach-1
Reach XY= 30
       3711479.5       10697615.      3711434.49      10697750.7
        3711372.       10697743.      3711277.75       10697905.
        3711210.       10697919.        3711064.       10697893.
      3710991.75       10697910.      3710939.75       10697900.
       3710890.5       10697864.        3710813.       10697743.
      3710725.75       10697738.        3710608.       10697654.
      3710505.25       10697638.        3710458.       10697596.
      3710422.75       10697528.       3710378.5       10697533.
       3710338.5       10697493.      3710239.75       10697461.
       3710086.5       10697481.      3709979.99     10697464.85
      3709956.03     10697397.92      3709866.75       10697314.
      3709873.25       10697229.       3709822.5       10697125.
        3709712.       10696996.      3709605.25       10696955.
      3709291.25       10696896.        3708866.       10696761.
       3708442.5       10696723.        3708279.       10696645.

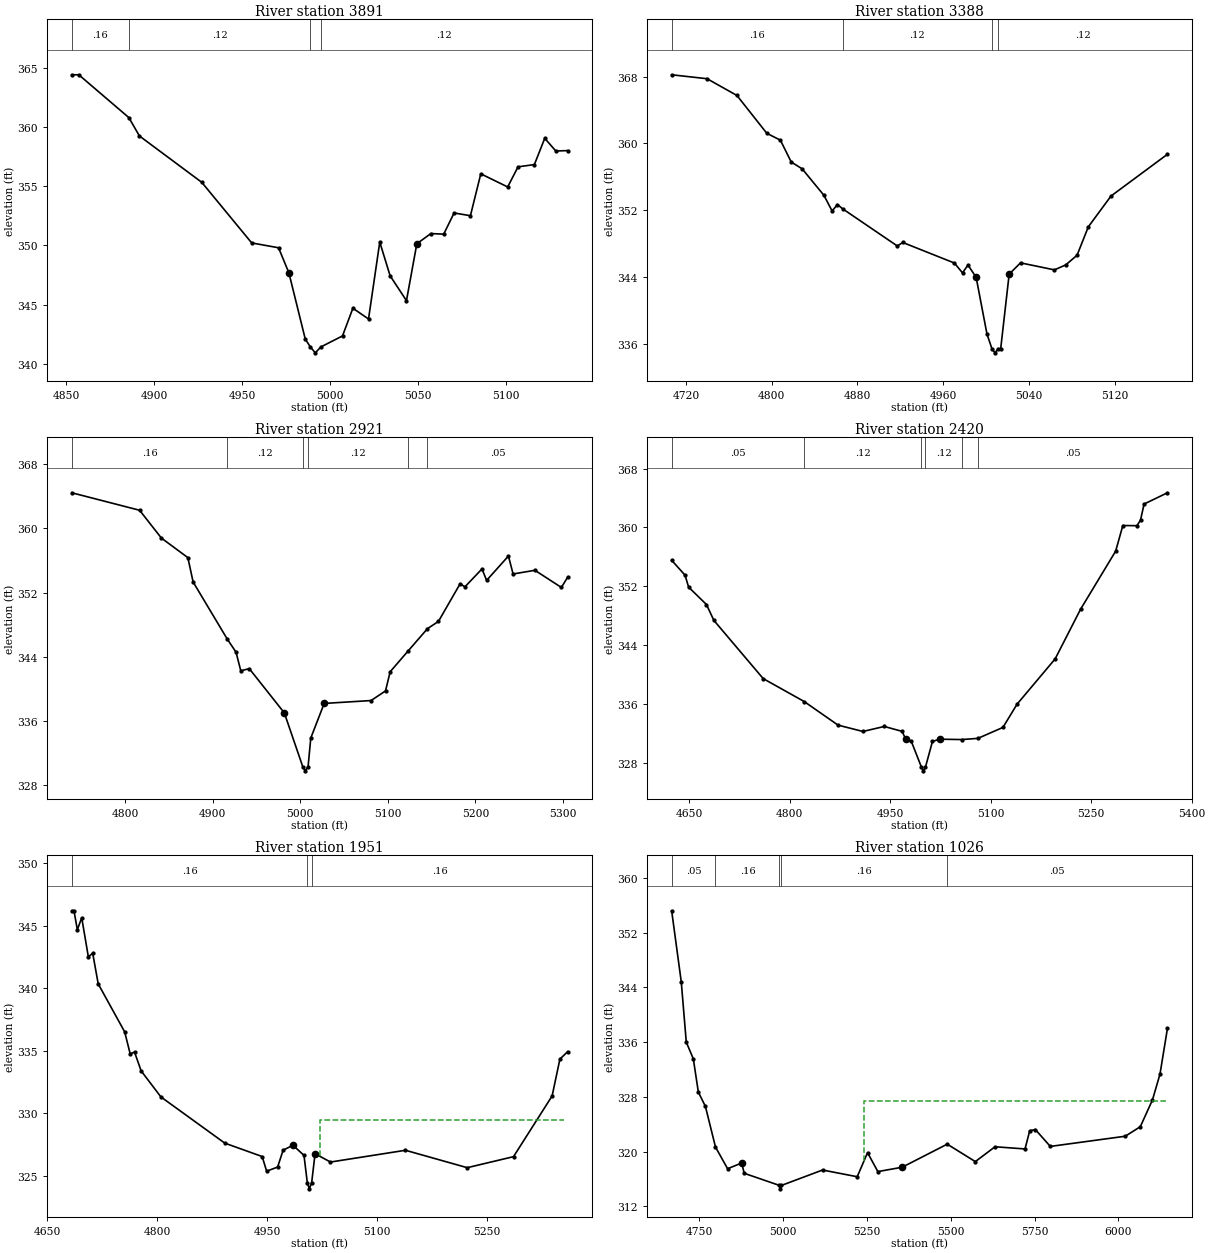
Type RM Length L Ch R = 1 ,3891    ,503,503,503
BEGIN DESCRIPTION:
UNT 148 IN CACR 6.0
END DESCRIPTION:
XS GIS Cut Line= 2
      3711327.15     10697620.85      3711565.23     10697772.36
#Sta/Elev= 30
    4853  364.42    4857  364.42  4885.5   360.8  4891.5  359.25    4927  355.33
  4955.4  350.21  4970.7   349.8  4976.6  347.67  4985.9  342.08  4988.8  341.42
  4991.6  340.92  4994.8  341.42  5007.1  342.35    5013  344.69  5021.9  343.78
  5028.3  350.28  5034.2  347.43  5043.5  345.33  5049.4  350.14  5057.4     351
  5064.7  350.95  5070.6  352.74  5079.9  352.51  5085.8  356.05  5101.1  354.94
    5107  356.64  5116.3  356.83  5122.2  359.05  5128.5  357.98  5135.2  358.01
#Mann= 4 ,-1 , 0
    4853     .16       0  4885.5     .12       0  4988.8     .07       0
  4994.8     .12       0
Bank Sta=4976.6,5049.4
XS Rating Curve= 0 ,0
Exp/Cntr=0.3,0.1

Type RM Length L Ch R = 1 ,3388    ,467,467,467
BEGIN DESCRIPTION:
UNT 148 IN CACR 5.0
END DESCRIPTION:
XS GIS Cut Line= 3
       3711049.6     10697610.16      3711099.61     10697910.19
       3711049.6      10698060.2
#Sta/Elev= 30
  4706.8  368.21  4739.8  367.74  4767.7  365.73  4795.5  361.21  4808.2  360.38
  4818.3  357.77  4828.5  356.95  4848.8  353.78  4856.4  351.91  4861.4  352.68
  4866.1  352.18  4917.2  347.72  4922.3  348.14  4970.4  345.68    4978   344.5
  4983.1  345.44  4990.7  343.97  5000.8  337.18  5005.4  335.43  5008.2  334.93
  5011.4  335.43  5013.6  335.43  5021.5  344.35  5032.1   345.7  5063.7  344.86
  5074.2  345.45  5084.8  346.61  5095.3  350.01  5116.4  353.69  5169.1   358.7
#Mann= 4 ,-1 , 0
  4706.8     .16       0  4866.1     .12       0  5005.4     .07       0
  5011.4     .12       0
Bank Sta=4990.7,5021.5
XS Rating Curve= 0 ,0
Exp/Cntr=0.3,0.1

Type RM Length L Ch R = 1 ,2921    ,501,501,501
BEGIN DESCRIPTION:
Mapping XS e56a2b59
END DESCRIPTION:
XS GIS Cut Line= 2
      3710811.11     10697490.59      3710611.46      10698020.1
#Sta/Elev= 30
  4739.2  364.45  4816.6  362.27  4841.5   358.8  4871.7  356.36  4877.7  353.32
  4916.6  346.21  4926.7  344.56  4932.1  342.24  4941.8  342.51  4981.8  336.99
  5002.9  330.26  5005.7  329.76  5008.9  330.26    5012  333.85  5027.3  338.17
  5080.8  338.53  5097.3  339.73  5102.6  342.12  5123.2  344.73  5145.2   347.5
  5157.7   348.4  5182.5  353.11  5187.9  352.71  5207.4  354.95  5212.7  353.52
  5237.6  356.56  5242.9  354.32  5267.8  354.78    5298  352.64  5305.1   353.9
#Mann= 6 ,-1 , 0
  4739.2     .16       0  4916.6     .12       0  5002.9     .07       0
  5008.9     .12       0  5123.2     .16       0  5145.2     .05       0
Bank Sta=4981.8,5027.3
XS Rating Curve= 0 ,0
Exp/Cntr=0.3,0.1

Type RM Length L Ch R = 1 ,2420    ,469,469,469
BEGIN DESCRIPTION:
Mapping XS 7b0596e2
END DESCRIPTION:
XS GIS Cut Line= 2
      3710442.19     10697130.35      3710212.16     10697833.48
#Sta/Elev= 30
    4624  355.54    4644  353.51  4649.3  351.89  4675.9  349.53    4687  347.37
  4760.6  339.46  4821.7  336.35  4872.3  333.14  4909.4  332.28  4941.3  332.96
  4967.9  332.29  4973.1  331.25  4981.6  330.94  4996.7  327.43  4999.5  326.93
  5002.7  327.43  5013.1  330.92  5023.7  331.23  5056.6  331.18  5080.9  331.34
  5118.3  332.83  5139.4  335.99  5196.2  342.14  5234.1  348.88  5286.5  356.78
  5297.2  360.26  5318.3  360.24  5323.6     361  5328.9  363.18  5363.8  364.71
#Mann= 6 ,-1 , 0
    4624     .05       0  4821.7     .12       0  4996.7     .07       0
  5002.7     .12       0  5056.6     .16       0  5080.9     .05       0
Bank Sta=4973.1,5023.7
XS Rating Curve= 0 ,0
Exp/Cntr=0.3,0.1

Type RM Length L Ch R = 1 ,1951    ,925,925,925
BEGIN DESCRIPTION:
UNT 148 IN CACR 2.0
END DESCRIPTION:
XS GIS Cut Line= 3
      3710099.63     10697110.15      3709899.61     10697410.19
       3709999.6     10697710.16
#Sta/Elev= 30
  4683.4  346.18  4686.4  346.18    4691  344.67    4697  345.62    4706  342.51
    4712  342.78  4719.5  340.34  4755.6  336.51  4763.1  334.76  4769.1  334.89
  4778.1  333.39  4805.1  331.31  4892.3  327.62  4943.3  326.55  4949.4  325.38
  4964.4  325.71  4971.9  327.06  4985.4  327.45  5000.4  326.64  5004.9  324.47
  5007.7  323.97  5010.9  324.47  5015.5  326.78  5036.5  326.11  5138.9  327.05
  5223.2  325.66  5286.4  326.54  5339.1  331.39  5349.7  334.33  5360.2  334.92
#Mann= 3 ,-1 , 0
  4683.4     .16       0  5004.9     .03       0  5010.9     .16       0
#XS Ineff= 1 ,-1
 5021.82 5355.91  329.46
Permanent Ineff=
       F
Bank Sta=4985.4,5015.5
XS Rating Curve= 0 ,0
Exp/Cntr=0.3,0.1

Type RM Length L Ch R = 1 ,1026    ,0,0,0
BEGIN DESCRIPTION:
UNT 148 IN CACR 1.0
END DESCRIPTION:
XS GIS Cut Line= 3
      3709449.62     10696610.17      3709249.61     10696910.19
       3709749.6     10697910.17
#Sta/Elev= 30
  4667.9   355.2  4696.5  344.84  4711.5     336  4732.5  333.56  4747.5   328.7
  4768.6   326.6  4798.6  320.67  4834.7   317.5  4876.7  318.33  4884.3  316.83
  4989.4  315.06  4992.2  314.56  4995.4  315.06  5117.9  317.31  5221.3  316.33
  5252.1  319.85  5282.8  317.08  5355.5  317.72  5489.7  321.09  5573.5  318.54
  5632.2  320.71  5721.7  320.39  5735.6  323.04  5752.4  323.23  5797.1  320.76
  6020.7  322.25  6065.5  323.64  6101.8  327.56  6124.2  331.33  6146.5  338.03
#Mann= 5 ,-1 , 0
  4667.9     .05       0  4798.6     .16       0  4989.4     .07       0
  4995.4     .16       0  5489.7     .05       0
#XS Ineff= 1 ,-1
 5241.82 6176.36  327.46
Permanent Ineff=
       F
Bank Sta=4876.7,5355.5
XS Rating Curve= 0 ,0
Exp/Cntr=0.3,0.1

Chan Stop Cuts=-1
Use User Specified Reach Order=0
Composite Channel Slope=5