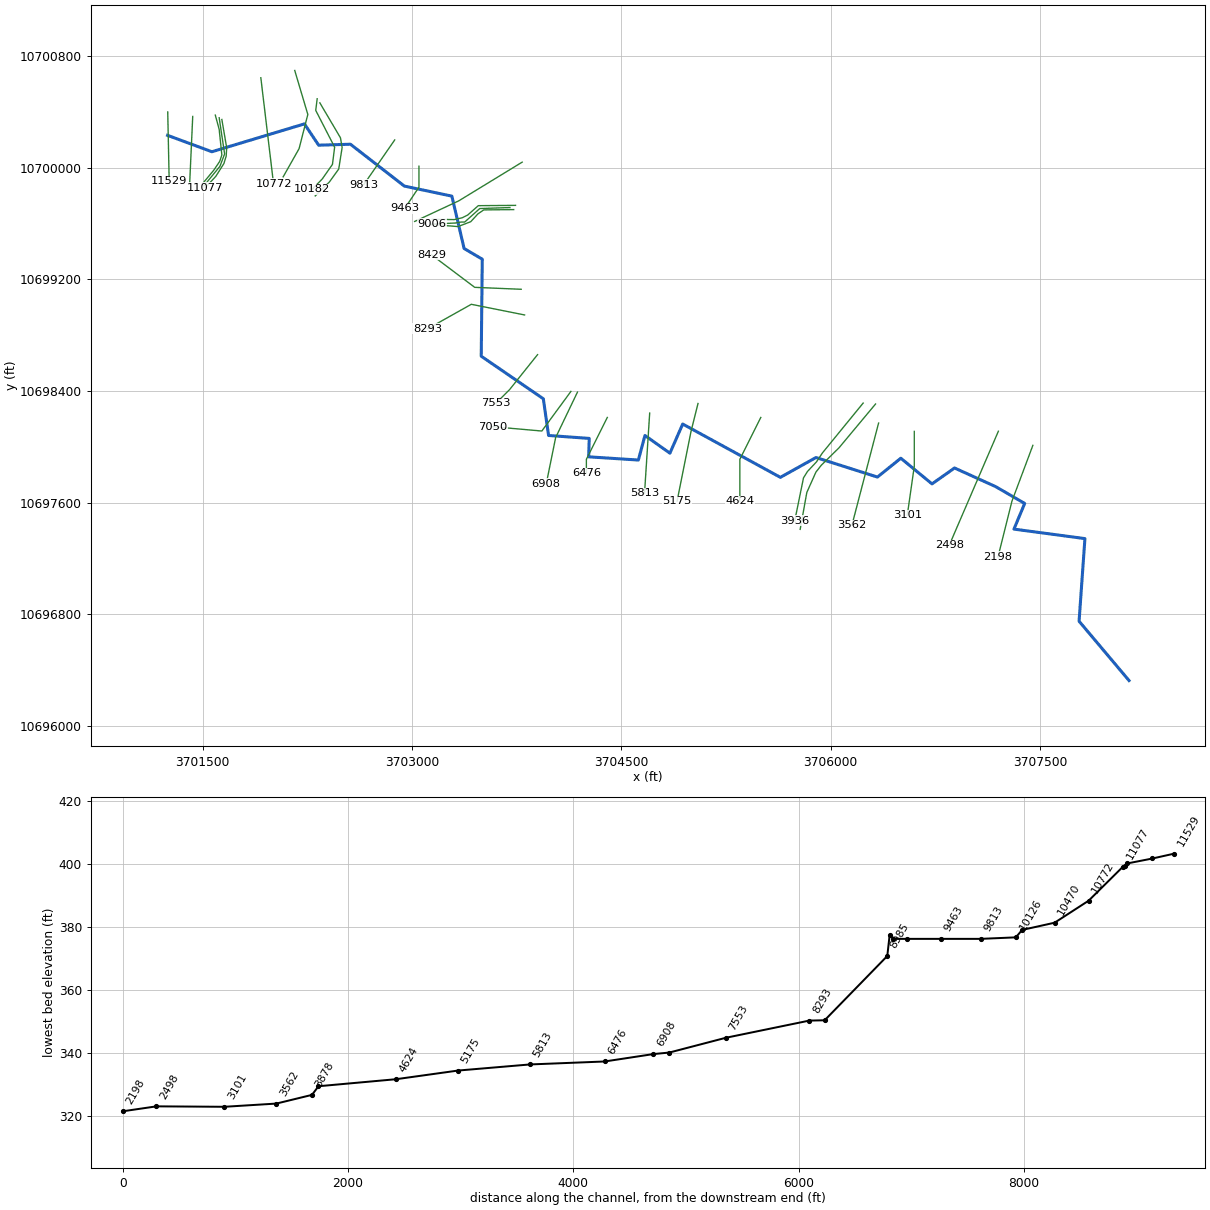
--- UNT 149 IN CACR.prj (project) ---

Proj Title=UNT 149 IN CACR Base Level Engineering
Current Plan=p01
Default Exp/Contr=0.3,0.1
English Units
Geom File=g01
Flow File=f01
Plan File=p01
Y Axis Title=Elevation
X Axis Title(PF)=Main Channel Distance
X Axis Title(XS)=Station
BEGIN DESCRIPTION:
UNT 149 IN CACR
END DESCRIPTION:
DSS Export Rating Curves= 0
DSS Export Rating Curve Sorted= 0
DSS Export Volume Flow Curves= 0
DXF OffsetX= 0
DXF OffsetY= 0
DXF ScaleX= 1
DXF ScaleY= 10

--- UNT 149 IN CACR.p01 (plan) ---

Plan Title=Multiple Run
Short Identifier=Multiple
Geom File=g01
Flow File=f01
Subcritical Flow
K Sum by GR= 0
Std Step Tol= 0.01
Critical Tol= 0.01
Num of Std Step Trials= 20
Max Error Tol= 0.3
Flow Tol Ratio= 0.001
Split Flow NTrial= 30
Split Flow Tol= 0.02
Split Flow Ratio= 0.02
Log Output Level= 0
Friction Slope Method= 1
Unsteady Friction Slope Method= 2
Unsteady Bridges Friction Slope Method= 1
Parabolic Critical Depth
Global Vel Dist=  1 , 1 , 1
Global Log Level= 0
CheckData=True
Encroach Param= -1, 0, 0, 0
BEGIN DESCRIPTION:
Multiple Run
END DESCRIPTION:

--- UNT 149 IN CACR.f01 (steady flow) ---

Flow Title=Multiple
Program Version=4.10
Number of Profiles= 7
Profile Names=10-year,25-year,50-year,1pct_min,100-year,1pct_plu,500-year
River Rch & RM=UNT 149 IN CACR,Reach-1         ,11529
     160     201     233     199     270     365     361
River Rch & RM=UNT 149 IN CACR,Reach-1         ,9161
     283     371     442     388     525     710     743
River Rch & RM=UNT 149 IN CACR,Reach-1         ,8293
     369     492     592     525     710     960    1024
River Rch & RM=UNT 149 IN CACR,Reach-1         ,6908
     596     813     994     894    1209    1635    1793
Boundary for River Rch & Prof#=UNT 149 IN CACR,Reach-1         , 1
Up Type= 0
Dn Type= 3
Dn Slope=0.00394
Boundary for River Rch & Prof#=UNT 149 IN CACR,Reach-1         , 2
Up Type= 0
Dn Type= 3
Dn Slope=0.00394
Boundary for River Rch & Prof#=UNT 149 IN CACR,Reach-1         , 3
Up Type= 0
Dn Type= 3
Dn Slope=0.00394
Boundary for River Rch & Prof#=UNT 149 IN CACR,Reach-1         , 4
Up Type= 0
Dn Type= 3
Dn Slope=0.00394
Boundary for River Rch & Prof#=UNT 149 IN CACR,Reach-1         , 5
Up Type= 0
Dn Type= 3
Dn Slope=0.00394
Boundary for River Rch & Prof#=UNT 149 IN CACR,Reach-1         , 6
Up Type= 0
Dn Type= 3
Dn Slope=0.00394
Boundary for River Rch & Prof#=UNT 149 IN CACR,Reach-1         , 7
Up Type= 0
Dn Type= 3
Dn Slope=0.00394
DSS Import GetInterval= 0
DSS Import GetPeak= 0
DSS Import FillOption= 0

--- UNT 149 IN CACR.g01 (geometry) ---

Geom Title=Existing Conditions
Program Version=4.10

River Reach=UNT 149 IN CACR ,Reach-1
Reach XY= 30
      3701247.93     10700231.68       3701565.8     10700114.09
      3702228.89     10700313.65      3702330.75       10700161.
       3702558.5       10700168.        3702945.       10699868.
       3703285.5       10699796.      3703373.25       10699421.
       3703503.5       10699344.        3703496.       10698649.
        3703941.       10698344.      3703978.75       10698081.
      3704270.25       10698060.        3704266.       10697928.
      3704622.25       10697905.       3704669.5       10698081.
      3704848.25       10697954.        3704940.       10698163.
        3705640.       10697781.      3705895.25       10697923.
       3706335.5       10697783.      3706503.25       10697918.
      3706726.75       10697734.      3706888.25       10697848.
        3707182.       10697715.        3707391.       10697594.
        3707314.       10697410.      3707822.75       10697342.
      3707780.75       10696750.      3708138.75       10696325.

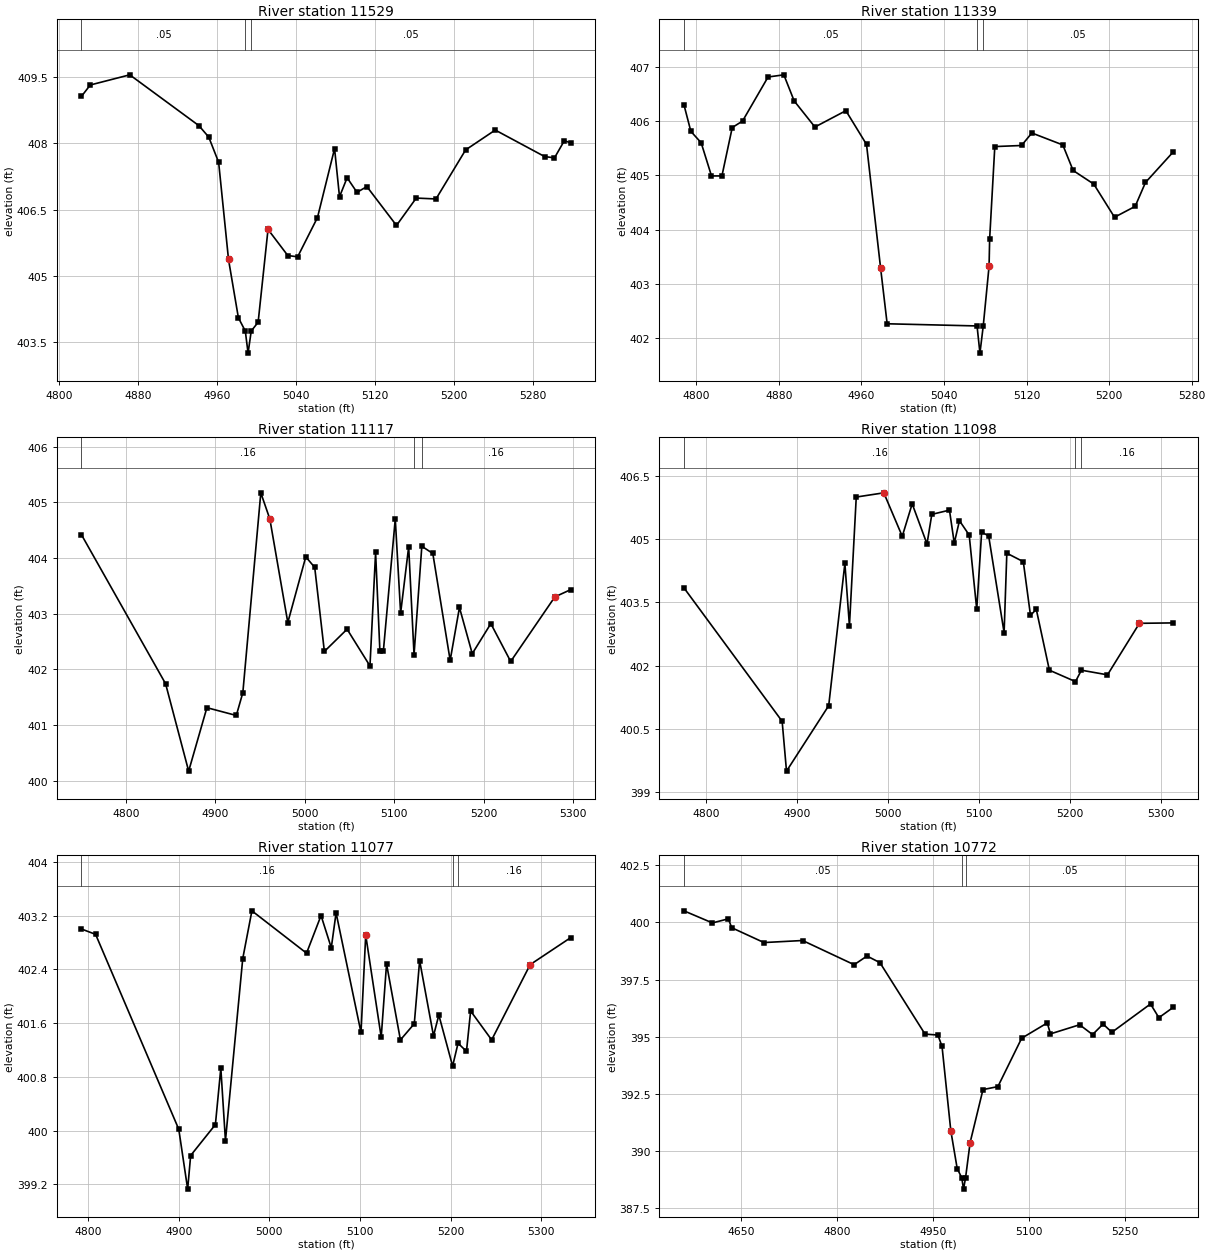
Type RM Length L Ch R = 1 ,11529   ,190,190,190
BEGIN DESCRIPTION:
Mapping XS 9fc22ad8
END DESCRIPTION:
XS GIS Cut Line= 2
      3701249.18     10700399.19      3701259.57      10699903.9
#Sta/Elev= 30
  4822.5  409.06  4831.5  409.32  4871.5  409.55  4941.5   408.4  4951.5  408.14
  4961.5  407.57  4971.5  405.37  4981.5  404.05  4988.5  403.75  4991.3  403.25
  4994.5  403.75  5001.5  403.95  5011.5  406.05  5031.5  405.46  5041.5  405.43
  5061.6  406.32  5078.9  407.88  5083.9  406.79  5091.6  407.22  5101.6  406.89
  5111.6  407.02  5141.6  406.14  5161.6  406.76  5181.6  406.74  5211.6  407.85
  5241.6   408.3  5291.6   407.7  5301.6  407.67  5311.6  408.06  5317.9  408.01
#Mann= 3 ,-1 , 0
  4822.5     .05       0  4988.5     .03       0  4994.5     .05       0
Bank Sta=4971.5,5011.5
XS Rating Curve= 0 ,0
Exp/Cntr=0.3,0.1

Type RM Length L Ch R = 1 ,11339   ,222,222,222
BEGIN DESCRIPTION:
Mapping XS 4bccf407
END DESCRIPTION:
XS GIS Cut Line= 2
      3701428.31     10700366.91      3701406.69      10699893.4
#Sta/Elev= 30
    4788   406.3  4794.7  405.81  4804.7   405.6  4814.7  404.99  4824.8  404.99
  4834.8  405.88  4844.8     406  4869.5  406.81  4884.8  406.85  4894.8  406.37
  4914.9  405.89  4944.9  406.19  4964.9  405.57 4978.58  403.29  4984.9  402.27
    5072  402.23  5074.8  401.73    5078  402.23 5083.65  403.33  5084.2  403.83
  5089.2  405.53  5115.1  405.55  5125.1  405.78  5155.1  405.56  5165.1  405.09
  5185.1  404.84  5205.2  404.23  5225.2  404.43  5235.2  404.87    5262  405.43
#Mann= 3 ,-1 , 0
    4788     .05       0    5072     .03       0    5078     .05       0
Bank Sta=4978.58,5083.65
XS Rating Curve= 0 ,0
Exp/Cntr=0.3,0.1

Type RM Length L Ch R = 1 ,11117   ,19,19,19
BEGIN DESCRIPTION:
Mapping XS 0e549c86
END DESCRIPTION:
XS GIS Cut Line= 6
       3701590.1     10700376.68      3701617.88     10700274.26
      3701636.97      10700091.1      3701622.22     10700045.96
      3701579.68      10699982.6      3701494.63     10699880.19
#Sta/Elev= 30
  4750.1  404.42  4844.3  401.74  4870.1  400.17  4890.5  401.31  4923.4  401.17
  4930.7  401.58  4950.8  405.17  4960.9   404.7    4981  402.84  5001.1  404.02
  5011.1  403.83  5021.9  402.32  5047.3  402.72  5072.9  402.06  5079.2   404.1
    5084  402.33  5087.9  402.33  5101.2   404.7  5107.2  403.01  5116.2   404.2
  5122.2  402.26  5130.9  404.21  5143.2  404.08  5162.6  402.16    5173  403.11
  5187.3  402.28  5208.1  402.82  5230.3  402.14  5279.7   403.3  5297.3  403.43
#Mann= 3 ,-1 , 0
  4750.1     .16       0  5122.2     .07       0  5130.9     .16       0
#XS Ineff= 1 ,-1
 4762.39 4951.93  404.05
Permanent Ineff=
       F
Bank Sta=4960.9,5279.7
XS Rating Curve= 0 ,0
Exp/Cntr=0.3,0.1

Type RM Length L Ch R = 1 ,11098   ,21,21,21
BEGIN DESCRIPTION:
Mapping XS b4d9f5a2
END DESCRIPTION:
XS GIS Cut Line= 4
      3701617.88     10700357.59      3701656.94     10700098.05
      3701623.08     10700009.51      3701508.49     10699869.73
#Sta/Elev= 30
  4775.9  403.84  4883.9  400.68  4888.7   399.5  4935.1  401.05  4952.9  404.42
  4957.9  402.94  4965.4  405.99  4995.7  406.09    5016  405.06  5026.9  405.83
  5043.2  404.88  5048.5  405.58  5067.9  405.68  5073.2   404.9  5078.9  405.43
  5089.6  405.09  5097.9  403.33  5103.3  405.16    5111  405.07    5128  402.78
    5131  404.66  5149.1  404.46    5157  403.19  5163.4  403.33  5177.8  401.89
  5206.5  401.62    5213  401.89  5241.7  401.78  5276.8     403  5313.9  403.01
#Mann= 3 ,-1 , 0
  4775.9     .16       0  5206.5     .07       0    5213     .16       0
Bank Sta=4995.7,5276.8
XS Rating Curve= 0 ,0
Exp/Cntr=0.3,0.1

Type RM Length L Ch R = 1 ,11077   ,305,305,305
BEGIN DESCRIPTION:
Mapping XS 107b8411
END DESCRIPTION:
XS GIS Cut Line= 6
      3701636.98     10700345.43      3701671.69     10700142.32
      3701668.22     10700083.29      3701651.73     10700029.47
      3701593.57     10699937.46       3701518.9     10699857.58
#Sta/Elev= 30
  4792.6     403  4808.3  402.92  4900.1  400.02  4909.9  399.13  4913.2  399.63
  4940.5  400.09  4946.5  400.93  4951.6  399.85  4970.7  402.56  4980.8  403.27
  5041.1  402.64  5057.1   403.2  5068.4  402.72  5073.7  403.24  5101.2  401.46
  5106.4  402.91  5123.5  401.39  5129.4  402.48  5144.7  401.35    5160  401.59
  5165.9  402.53  5181.2  401.41  5187.1  401.72  5202.3  400.96  5208.3   401.3
  5217.6  401.18  5222.2  401.78  5245.4  401.35  5287.9  402.47  5332.5  402.87
#Mann= 3 ,-1 , 0
  4792.6     .16       0  5202.3     .07       0  5208.3     .16       0
#XS Ineff= 1 ,-1
 4798.64 5074.26  402.83
Permanent Ineff=
       F
Bank Sta=5106.4,5287.9
XS Rating Curve= 0 ,0
Exp/Cntr=0.3,0.1

Type RM Length L Ch R = 1 ,10772   ,302,302,302
BEGIN DESCRIPTION:
Mapping XS 51e3c311
END DESCRIPTION:
XS GIS Cut Line= 2
      3701916.37     10700644.39      3702007.49     10699885.04
#Sta/Elev= 30
  4560.9  400.51  4605.4  399.98  4630.3  400.16  4635.6  399.77    4686  399.12
  4746.4  399.21    4827  398.15  4847.1  398.53  4867.3  398.24  4937.8  395.11
  4957.9  395.07  4964.4  394.57  4978.1  390.88  4988.1  389.22  4995.2  388.82
    4998  388.32  5001.2  388.82  5008.3  390.36  5028.4  392.68  5051.7  392.81
  5088.9  394.93  5128.9   395.6  5133.9  395.12  5179.5  395.52  5199.7  395.09
  5216.2  395.55  5229.9  395.19  5290.3  396.43  5303.4  395.83  5325.7  396.28
#Mann= 3 ,-1 , 0
  4560.9     .05       0  4995.2     .03       0  5001.2     .05       0
Bank Sta=4978.1,5008.3
XS Rating Curve= 0 ,0
Exp/Cntr=0.3,0.1

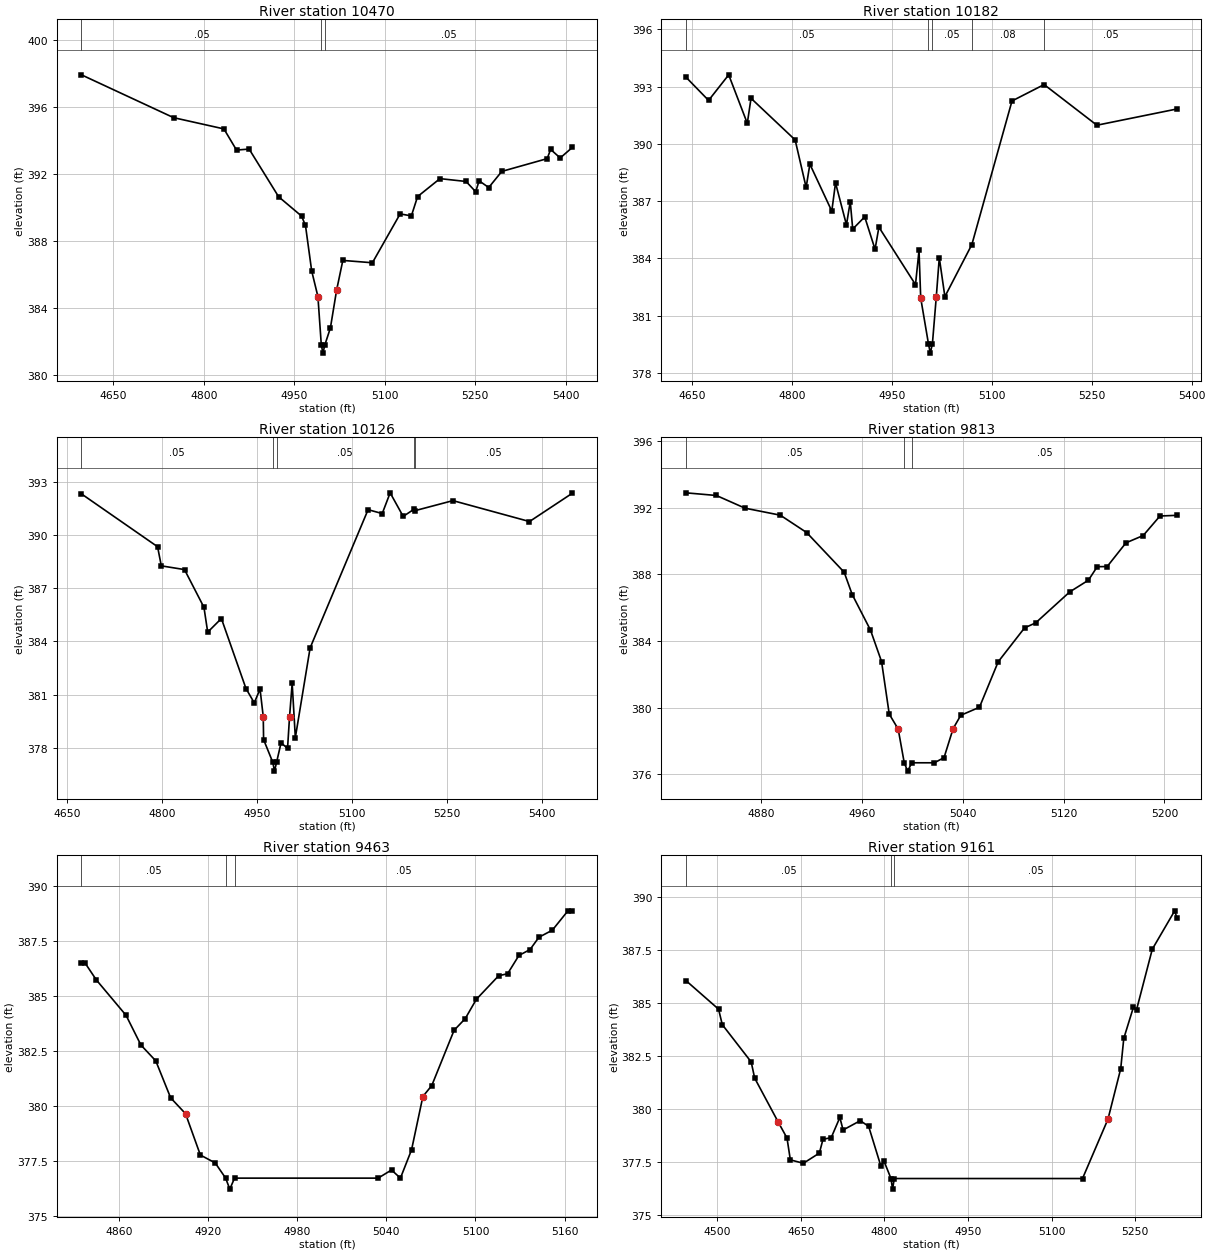
Type RM Length L Ch R = 1 ,10470   ,288,288,288
BEGIN DESCRIPTION:
Mapping XS 8ca8bf0d
END DESCRIPTION:
XS GIS Cut Line= 4
      3702159.41     10700696.52      3702253.18     10700381.37
      3702190.68     10700136.57      3702076.57     10699934.29
#Sta/Elev= 30
  4597.3   397.9    4750  395.35  4833.4  394.68  4854.3  393.42  4875.2  393.48
  4924.1  390.64  4962.1  389.49  4968.6  388.93  4978.9  386.22  4989.2   384.7
  4994.8  381.83  4997.5  381.33  5000.8  381.83  5009.9  382.83  5020.2  385.08
  5030.5  386.85  5079.5  386.71  5125.5  389.62  5144.1   389.5  5154.4  390.65
  5191.5  391.72  5234.8  391.55  5250.7  390.94  5256.4  391.59  5272.3  391.19
    5294  392.15  5369.2  392.91  5374.9  393.46  5390.8  392.95    5411  393.58
#Mann= 3 ,-1 , 0
  4597.3     .05       0  4994.8     .03       0  5000.8     .05       0
Bank Sta=4989.2,5020.2
XS Rating Curve= 0 ,0
Exp/Cntr=0.3,0.1

Type RM Length L Ch R = 1 ,10182   ,56,56,56
BEGIN DESCRIPTION:
UNT 149 IN CACR 19.0
END DESCRIPTION:
XS GIS Cut Line= 6
      3702320.33     10700493.89      3702309.91     10700410.54
      3702445.32     10700146.65       3702429.7     10700023.39
      3702356.78     10699919.22      3702284.54     10699845.25
#Sta/Elev= 30
  4641.1   393.5  4675.1  392.28  4705.3  393.62  4733.2  391.08  4738.8  392.39
    4805  390.21  4821.5  387.72  4827.1  388.94    4860  386.48  4865.6  387.96
    4882  385.76  4887.7  386.98  4891.4  385.54  4909.4  386.18  4924.9  384.48
  4930.7  385.64  4985.6  382.63  4990.9  384.42 4993.41  381.93    5005  379.54
  5007.8  379.04    5011  379.54  5016.8  381.99  5021.3  384.04  5029.7     382
  5070.2  384.73  5130.4  392.25  5178.6  393.11  5257.8  390.98  5377.8  391.83
#Mann= 5 ,-1 , 0
  4641.1     .05       0    5005     .03       0    5011     .05       0
  5070.2     .08       0  5178.6     .05       0
Bank Sta=4993.41,5016.8
XS Rating Curve= 0 ,0
Exp/Cntr=0.3,0.1

Type RM Length L Ch R = 1 ,10126   ,313,313,313
BEGIN DESCRIPTION:
UNT 149 IN CACR 18.0
END DESCRIPTION:
XS GIS Cut Line= 6
      3702339.43     10700464.34      3702486.99     10700214.36
      3702499.14     10700144.91      3702474.84      10699990.4
      3702407.13     10699896.65       3702306.4     10699797.66
#Sta/Elev= 30
  4673.1  392.32  4793.2  389.34  4799.1  388.26  4835.7  388.05  4866.4  385.92
  4872.3  384.52  4893.9  385.29  4932.7  381.34  4945.8  380.53  4954.9  381.31
 4959.98  379.75  4960.5  378.46    4975  377.18  4977.7  376.68    4981  377.18
  4988.1  378.28  4998.3  377.96 5001.46  379.75  5005.6  381.63  5010.6  378.57
  5033.9  383.63  5125.4  391.43  5147.7  391.21  5160.2  392.38  5180.8  391.05
  5197.7  391.45    5199  391.37  5259.3  391.94  5380.1  390.76  5447.8  392.36
#Mann= 5 ,-1 , 0
  4673.1     .05       0    4975     .03       0    4981     .05       0
  5197.7     .08       0    5199     .05       0
Bank Sta=4959.98,5001.46
XS Rating Curve= 0 ,0
Exp/Cntr=0.3,0.1

Type RM Length L Ch R = 1 ,9813    ,350,350,350
BEGIN DESCRIPTION:
Mapping XS 472b420d
END DESCRIPTION:
XS GIS Cut Line= 2
      3702875.88     10700198.73      3702654.15     10699878.26
#Sta/Elev= 30
  4820.2  392.89  4844.4  392.73  4867.1  391.97  4895.1  391.55    4916  390.51
  4945.8  388.13  4952.2  386.79  4966.7  384.66  4975.5  382.77  4981.6  379.62
  4988.7  378.72  4993.5   376.7  4996.2   376.2  4999.5   376.7  5017.4   376.7
  5025.1  377.01  5032.3  378.75  5038.4  379.55  5053.2  380.03  5068.1  382.76
    5089  384.79  5097.8  385.09  5124.9  386.95  5139.7  387.65  5146.7  388.46
  5154.6  388.47  5169.5  389.89  5183.2  390.33  5196.5   391.5  5209.9  391.54
#Mann= 3 ,-1 , 0
  4820.2     .05       0  4993.5     .03       0  4999.5     .05       0
Bank Sta=4988.7,5032.3
XS Rating Curve= 0 ,0
Exp/Cntr=0.3,0.1

Type RM Length L Ch R = 1 ,9463    ,302,302,302
BEGIN DESCRIPTION:
UNT 149 IN CACR 17.0
END DESCRIPTION:
XS GIS Cut Line= 3
      3703049.61     10700010.22      3703049.61     10699860.19
      3702949.61     10699710.19
#Sta/Elev= 30
  4834.9  386.47  4837.4  386.47  4844.9  385.71  4864.9   384.1  4874.9  382.75
  4884.9  382.03  4894.9  380.35  4904.9  379.63  4914.9  377.75  4924.9  377.39
  4931.9   376.7  4934.7   376.2  4937.9   376.7  5034.5   376.7  5043.5  377.07
  5049.5   376.7    5057  377.99  5064.6  380.41  5070.6  380.91  5085.6  383.42
  5093.1  383.95  5100.6  384.83  5115.6   385.9  5121.6  385.99  5129.2  386.82
  5136.7  387.09  5142.7  387.65  5151.7  387.97  5162.2  388.85  5165.2  388.85
#Mann= 3 ,-1 , 0
  4834.9     .05       0  4931.9    .033       0  4937.9     .05       0
Bank Sta=4904.9,5064.6
XS Rating Curve= 0 ,0
Exp/Cntr=0.3,0.1

Type RM Length L Ch R = 1 ,9161    ,121,121,121
BEGIN DESCRIPTION:
UNT 149 IN CACR 16.0
END DESCRIPTION:
XS GIS Cut Line= 3
      3703789.65     10700039.68      3703335.25     10699762.35
      3703018.91     10699614.56
#Sta/Elev= 30
  4443.5  386.04  4502.1  384.69  4508.8  383.96  4560.7   382.2  4566.9  381.44
  4609.5  379.35    4625  378.61    4631  377.58  4654.4  377.42  4683.1   377.9
  4689.6  378.55  4704.4  378.63  4719.9  379.58  4725.7  378.99  4756.6  379.43
  4771.6  379.16  4793.4   377.3  4799.2  377.52  4811.7   376.7  4814.5   376.2
  4817.7   376.7  5155.6   376.7  5201.3   379.5  5224.2  381.88  5229.7  383.31
    5247  384.78  5252.6  384.66  5280.9  387.52  5321.1  389.33    5325     389
#Mann= 3 ,-1 , 0
  4443.5     .05       0  4811.7    .033       0  4817.7     .05       0
Bank Sta=4609.5,5201.3
XS Rating Curve= 0 ,0
Exp/Cntr=0.3,0.1

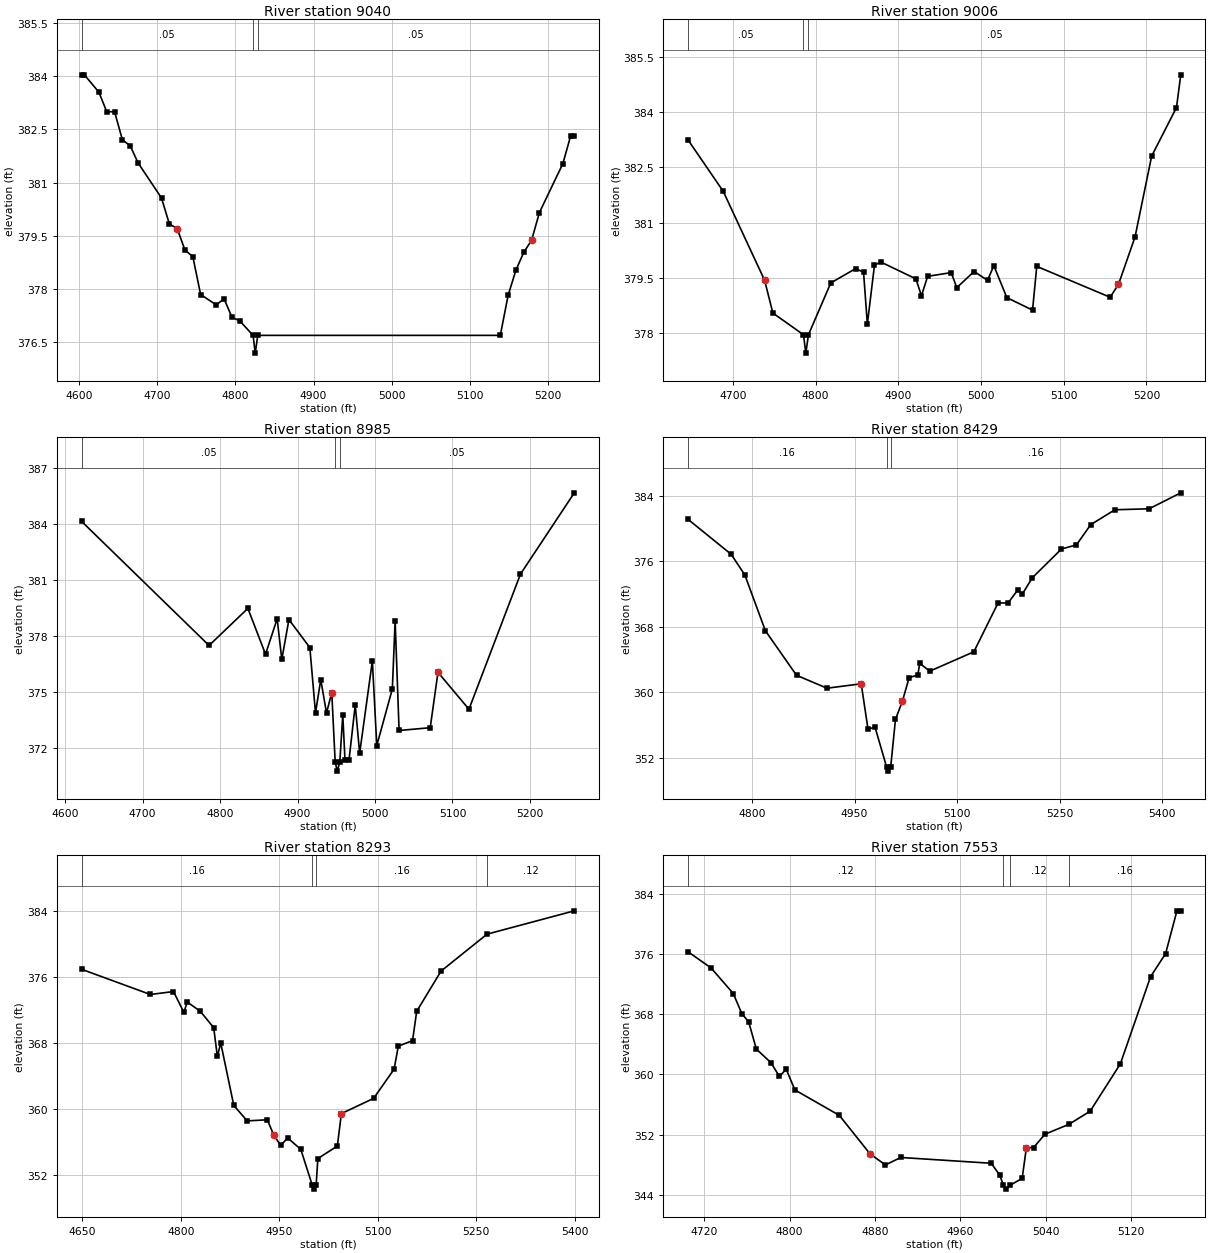
Type RM Length L Ch R = 1 ,9040    ,34,34,34
BEGIN DESCRIPTION:
Mapping XS c9c65d4e
END DESCRIPTION:
XS GIS Cut Line= 6
      3703741.84     10699729.91      3703474.91     10699727.74
      3703398.96     10699660.47      3703359.89     10699640.93
      3703303.47     10699627.91      3703145.03     10699630.08
#Sta/Elev= 30
  4603.5  384.04  4607.1  384.04  4625.7  383.55  4635.7     383  4645.7     383
  4655.7  382.21  4665.7  382.04  4675.7  381.56  4705.7  380.57  4715.7  379.84
  4725.7  379.71  4735.7   379.1  4745.7  378.92  4755.7  377.85  4775.7  377.56
  4785.7  377.73  4795.7  377.21  4805.7  377.11  4822.7   376.7  4825.5   376.2
  4828.7   376.7  5138.7   376.7  5148.7  377.83  5158.7  378.54  5168.7  379.04
  5178.7  379.38  5188.7  380.16  5218.7  381.54  5228.5  382.31  5233.3  382.31
#Mann= 3 ,-1 , 0
  4603.5     .05       0  4822.7    .033       0  4828.7     .05       0
Bank Sta=4725.7,5178.7
XS Rating Curve= 0 ,0
Exp/Cntr=0.3,0.1

Type RM Length L Ch R = 1 ,9006    ,21,21,21
BEGIN DESCRIPTION:
Mapping XS 09c8ed8c
END DESCRIPTION:
XS GIS Cut Line= 6
      3703702.15     10699714.26       3703485.5     10699706.97
      3703377.17      10699610.1      3703353.21     10699610.62
      3703311.02     10699603.33      3703144.45     10699596.04
#Sta/Elev= 30
  4645.8  383.25  4688.4  381.85  4738.4  379.43  4748.4  378.54  4785.4  377.95
  4788.2  377.45  4791.4  377.95  4818.4  379.36  4848.5  379.75    4858  379.65
  4862.6  378.24  4871.2  379.84  4878.7  379.93  4921.3  379.47    4928  379.01
  4935.5  379.54    4964  379.64  4970.7  379.23  4991.6  379.67  5007.9  379.43
  5015.5  379.83  5031.2  378.96  5062.3  378.62  5067.4  379.81  5156.1  378.97
  5166.2  379.32  5186.2  380.61  5206.3  382.81  5236.3  384.13  5241.5  385.02
#Mann= 3 ,-1 , 0
  4645.8     .05       0  4785.4     .03       0  4791.4     .05       0
Bank Sta=4738.4,5166.2
XS Rating Curve= 0 ,0
Exp/Cntr=0.3,0.1

Type RM Length L Ch R = 1 ,8985    ,556,556,556
BEGIN DESCRIPTION:
Mapping XS 7afd9e8e
END DESCRIPTION:
XS GIS Cut Line= 6
      3703728.81     10699699.53      3703513.97     10699697.36
      3703472.74     10699669.15      3703420.66     10699612.72
      3703329.51       10699578.      3703134.42     10699593.17
#Sta/Elev= 30
  4621.2  384.16  4785.8   377.5  4835.9  379.49  4858.7  377.03  4873.7  378.93
  4879.7  376.75  4888.9  378.89  4915.9  377.39  4923.2  373.88    4930  375.67
  4937.4  373.88  4944.2  374.97  4948.6  371.26  4951.3  370.76  4954.6  371.26
  4958.4  373.78  4961.3  371.34  4966.4  371.34  4974.5  374.31  4980.2  371.72
  4996.6  376.67  5002.3  372.13  5022.4  375.17    5026  378.83  5031.1  372.94
  5071.3  373.09  5081.3  376.06  5121.3  374.08  5187.8  381.33  5257.3  385.69
#Mann= 3 ,-1 , 0
  4621.2     .05       0  4948.6     .03       0  4954.6     .05       0
Bank Sta=4944.2,5081.3
XS Rating Curve= 0 ,0
Exp/Cntr=0.3,0.1

Type RM Length L Ch R = 1 ,8429    ,136,136,136
BEGIN DESCRIPTION:
UNT 149 IN CACR 15.0
END DESCRIPTION:
XS GIS Cut Line= 3
      3703782.63     10699128.56       3703449.3     10699142.45
      3703140.29     10699375.08
#Sta/Elev= 30
  4706.6   381.1  4769.7  376.83  4789.7   374.3  4819.7  367.49  4865.2  362.05
  4909.8  360.47  4959.8  361.01  4969.8  355.43  4979.9  355.75  4996.9  350.84
  4999.6  350.34  5002.9  350.84  5009.9  356.67  5019.9  358.85  5029.9  361.77
  5042.5  362.08  5045.4  363.51    5060  362.55  5124.5  364.92  5159.9  370.89
  5174.5  370.88  5189.1  372.52  5195.3  371.96  5209.9  373.96  5252.6  377.48
  5274.5  377.98  5295.3  380.45  5330.7  382.27  5380.7  382.39    5427  384.34
#Mann= 3 ,-1 , 0
  4706.6     .16       0  4996.9     .07       0  5002.9     .16       0
Bank Sta=4959.8,5019.9
XS Rating Curve= 0 ,0
Exp/Cntr=0.3,0.1

Type RM Length L Ch R = 1 ,8293    ,740,740,740
BEGIN DESCRIPTION:
UNT 149 IN CACR 14.0
END DESCRIPTION:
XS GIS Cut Line= 3
      3703806.92     10698944.54        3703425.     10699020.93
      3703110.24     10698844.52
#Sta/Elev= 30
    4649  376.91  4753.8  373.85    4789  374.21  4804.8  371.68  4809.9  372.94
  4829.8  371.81  4850.2  369.83  4855.8  366.33  4860.9  367.98  4880.8  360.39
  4901.2  358.52  4931.8  358.65    4942  356.75  4952.2  355.55  4962.9  356.44
  4982.8  355.07  5000.2  350.74  5002.9  350.24  5006.2  350.74  5008.8  353.95
  5038.5  355.47  5044.6   359.4  5093.7  361.25  5124.9  364.79  5131.3  367.58
    5153  368.26  5159.3  371.81  5196.4  376.69  5266.4  381.17  5399.3     384
#Mann= 4 ,-1 , 0
    4649     .16       0  5000.2     .07       0  5006.2     .16       0
  5266.4     .12       0
Bank Sta=4942,5044.6
XS Rating Curve= 0 ,0
Exp/Cntr=0.3,0.1

Type RM Length L Ch R = 1 ,7553    ,503,503,503
BEGIN DESCRIPTION:
UNT 149 IN CACR 13.0
END DESCRIPTION:
XS GIS Cut Line= 3
      3703899.61     10698660.19      3703699.61     10698410.19
       3703599.6     10698310.18
#Sta/Elev= 30
  4704.9  376.28  4726.5  374.13  4747.3  370.74  4755.3  368.07  4761.7  366.98
  4768.9  363.37  4782.5  361.58  4790.5  359.75  4796.9  360.69    4805  357.95
  4846.6  354.58  4875.4  349.47  4889.8     348  4904.2  348.99    4989  348.22
    4997  346.62  5000.4  345.29  5003.2  344.79  5006.4  345.29  5017.9  346.21
  5021.9   350.3  5028.6   350.3  5039.2  352.07  5061.5  353.37  5081.6  355.13
  5109.9  361.41  5138.2  372.97  5152.3  376.04  5162.9  381.71  5166.5  381.71
#Mann= 4 ,-1 , 0
  4704.9     .12       0  5000.4     .07       0  5006.4     .12       0
  5061.5     .16       0
Bank Sta=4875.4,5021.9
XS Rating Curve= 0 ,0
Exp/Cntr=0.3,0.1

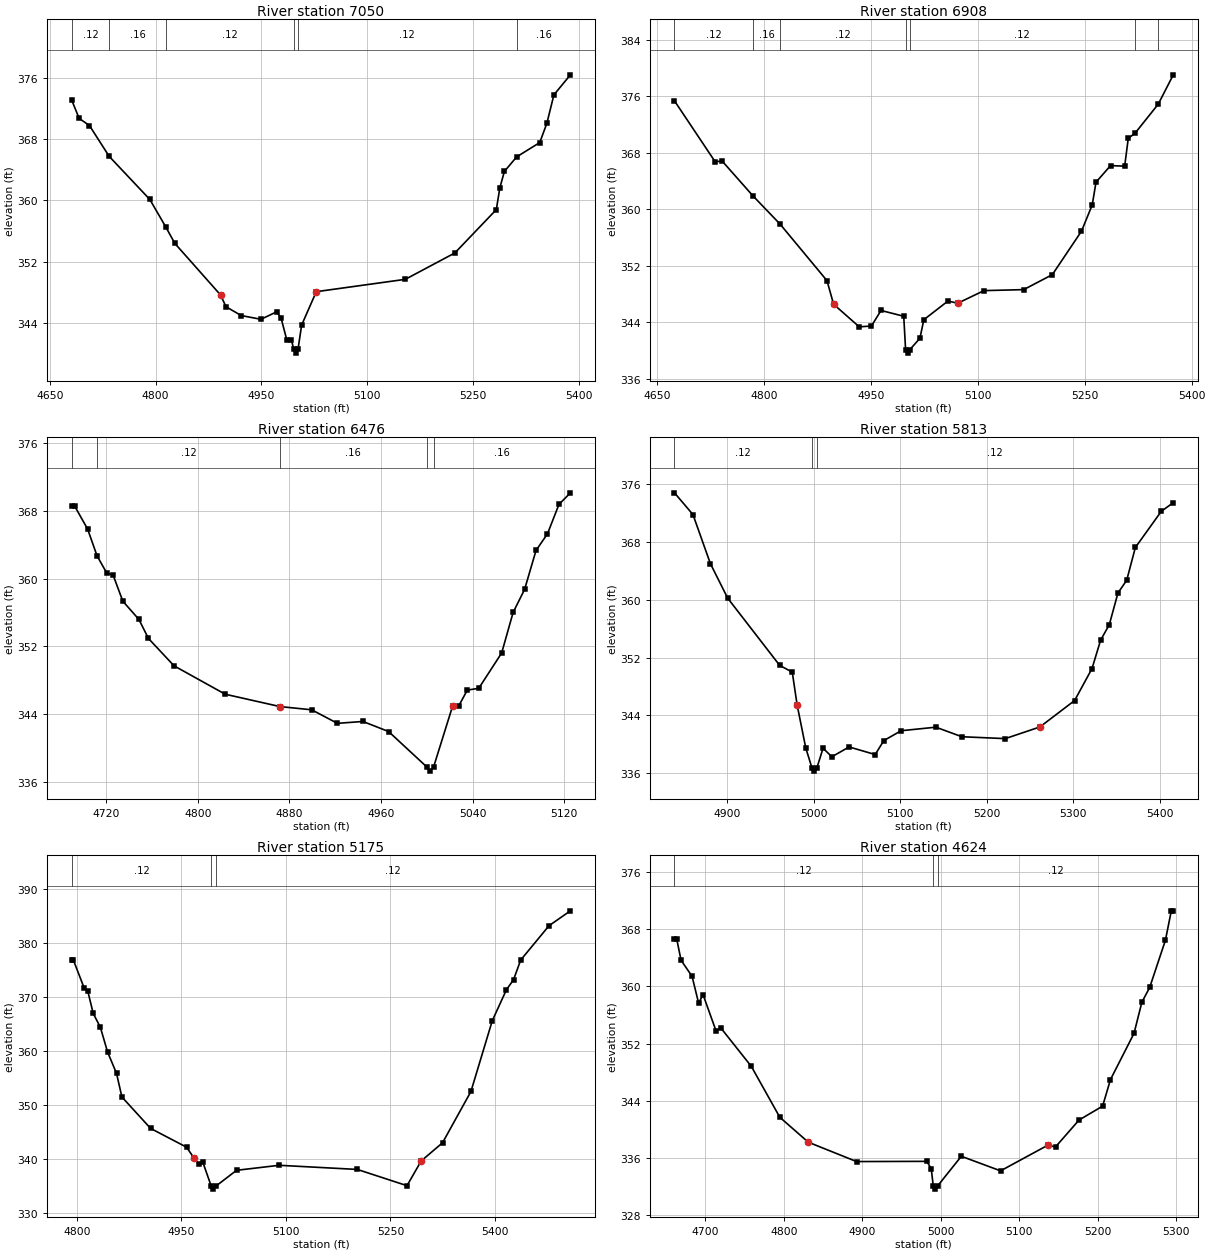
Type RM Length L Ch R = 1 ,7050    ,142,142,142
BEGIN DESCRIPTION:
Mapping XS 500ec6db
END DESCRIPTION:
XS GIS Cut Line= 3
      3704138.75     10698396.72      3703930.42     10698112.87
       3703576.3     10698144.11
#Sta/Elev= 30
  4680.9  373.11  4691.6  370.69  4706.2  369.76  4734.2  365.74  4791.9  360.12
  4814.4  356.55  4827.4  354.39  4892.2  347.67  4899.9  346.14  4921.5  344.99
  4949.5   344.5  4971.7  345.47  4977.9  344.71  4986.3  341.77  4992.5  341.86
  4996.1  340.59  4998.9  340.09  5002.1  340.59  5007.2  343.74    5028   348.1
  5154.3  349.71  5224.6  353.15  5283.4   358.8  5288.4  361.63  5294.8  363.77
  5312.2  365.67    5345  367.54  5355.1  370.05  5365.1  373.76  5388.5  376.37
#Mann= 6 ,-1 , 0
  4680.9     .12       0  4734.2     .16       0  4814.4     .12       0
  4996.1     .07       0  5002.1     .12       0  5312.2     .16       0
Bank Sta=4892.2,5028
XS Rating Curve= 0 ,0
Exp/Cntr=0.3,0.1

Type RM Length L Ch R = 1 ,6908    ,432,432,432
BEGIN DESCRIPTION:
UNT 149 IN CACR 12.0
END DESCRIPTION:
XS GIS Cut Line= 3
      3704185.62     10698391.49      3704029.38     10698065.99
      3703961.93     10697733.93
#Sta/Elev= 30
  4674.3  375.32  4731.2  366.72  4741.4  366.77  4784.2  361.89  4822.7  357.84
  4888.3  349.86  4897.6  346.52  4933.6  343.32  4950.7  343.44  4964.1  345.64
    4996  344.82  4998.6   340.1  5001.3   339.6  5004.6   340.1  5018.7   341.7
  5024.2  344.33    5058  346.97  5071.9  346.67  5108.6  348.45  5164.3  348.59
  5204.5  350.71  5245.4  356.86  5260.5  360.59  5265.8   363.8  5286.2  366.15
    5306  366.07  5311.1  370.03  5320.3   370.7  5353.2  374.86  5374.2     379
#Mann= 7 ,-1 , 0
  4674.3     .12       0  4784.2     .16       0  4822.7     .12       0
  4998.6     .07       0  5004.6     .12       0  5320.3     .16       0
  5353.2     .12       0
Bank Sta=4897.6,5071.9
XS Rating Curve= 0 ,0
Exp/Cntr=0.3,0.1

Type RM Length L Ch R = 1 ,6476    ,663,663,663
BEGIN DESCRIPTION:
UNT 149 IN CACR 11.0
END DESCRIPTION:
XS GIS Cut Line= 3
       3704399.6     10698210.17      3704249.61     10697910.19
      3704249.61     10697810.18
#Sta/Elev= 30
  4689.9  368.55  4692.7  368.55  4703.9  365.86  4712.1   362.7  4720.6  360.66
  4726.2   360.4  4734.6  357.34  4748.6  355.19    4757  352.93  4779.3   349.7
    4824  346.34  4871.8  344.88  4899.5   344.5  4921.9   342.9  4944.2  343.12
  4966.6  341.93  4999.9  337.75  5002.7  337.25  5005.9  337.75  5022.5  344.95
  5027.8  344.95  5035.3  346.83  5045.3  347.04  5065.3  351.22  5075.3  356.01
  5085.3  358.73  5095.3  363.34  5105.3  365.31  5115.3  368.78  5125.3  370.15
#Mann= 5 ,-1 , 0
  4689.9     .16       0  4712.1     .12       0  4871.8     .16       0
  4999.9     .07       0  5005.9     .16       0
Bank Sta=4871.8,5022.5
XS Rating Curve= 0 ,0
Exp/Cntr=0.3,0.1

Type RM Length L Ch R = 1 ,5813    ,638,638,638
BEGIN DESCRIPTION:
UNT 149 IN CACR 10.0
END DESCRIPTION:
XS GIS Cut Line= 2
      3704703.28     10698241.57      3704666.39     10697666.45
#Sta/Elev= 30
  4839.1  374.75  4860.5  371.74  4880.6  364.97  4900.6   360.2  4960.7  350.91
  4975.2  349.99  4980.8  345.46  4990.8  339.51  4997.8  336.81  5000.6  336.31
  5003.8  336.81  5010.8  339.48  5020.9  338.29  5040.9  339.65    5071   338.6
    5081  340.53    5101  341.89  5141.1  342.38  5171.2  341.06  5221.3   340.8
  5261.3  342.41  5301.4  346.06  5321.5  350.47  5331.5  354.41  5341.5  356.54
  5351.5  360.92  5361.6  362.67  5371.6   367.2  5401.6   372.2  5415.4  373.39
#Mann= 3 ,-1 , 0
  4839.1     .12       0  4997.8     .07       0  5003.8     .12       0
Bank Sta=4980.8,5261.3
XS Rating Curve= 0 ,0
Exp/Cntr=0.3,0.1

Type RM Length L Ch R = 1 ,5175    ,551,551,551
BEGIN DESCRIPTION:
UNT 149 IN CACR 9.0
END DESCRIPTION:
XS GIS Cut Line= 3
      3705049.62     10698310.23      3704999.61     10698110.19
      3704899.61     10697610.19
#Sta/Elev= 30
  4792.3  376.83  4794.9  376.83  4810.4  371.64  4815.5  371.11  4823.3  366.96
  4833.6  364.38  4843.9  359.81  4856.8  355.83  4864.5  351.46  4905.7  345.63
  4957.3  342.15  4967.6  340.21  4975.3  338.97  4980.5  339.44  4992.9  334.87
  4995.7  334.37  4998.9  334.87  5029.1  337.86  5090.3  338.79  5202.5  338.02
  5273.8  335.01  5294.2   339.6  5324.8  342.96  5365.6  352.48  5396.2  365.59
  5416.6  371.36  5426.8  373.21    5437  376.85  5477.8  383.23  5508.4  385.98
#Mann= 3 ,-1 , 0
  4792.3     .12       0  4992.9     .07       0  4998.9     .12       0
Bank Sta=4967.6,5294.2
XS Rating Curve= 0 ,0
Exp/Cntr=0.3,0.1

Type RM Length L Ch R = 1 ,4624    ,688,688,688
BEGIN DESCRIPTION:
UNT 149 IN CACR 8.0
END DESCRIPTION:
XS GIS Cut Line= 3
      3705499.62     10698210.21      3705349.61     10697910.19
      3705349.61     10697610.23
#Sta/Elev= 30
  4660.8  366.68  4663.6  366.68  4669.2  363.67  4683.2  361.42  4691.6  357.65
  4697.2  358.86  4713.9  353.73  4719.5  354.24  4758.7  348.81    4795  341.68
  4831.3  338.19  4892.8  335.48  4982.3  335.51  4987.9  334.47  4990.4  332.12
  4993.2  331.62  4996.4  332.12  5026.2  336.22  5076.2  334.18  5136.2  337.76
  5146.2  337.53  5176.2   341.3  5206.2  343.24  5216.2  346.96  5246.2  353.43
  5256.2  357.79  5266.2  359.87  5286.2  366.47  5293.7  370.59  5296.2  370.59
#Mann= 3 ,-1 , 0
  4660.8     .12       0  4990.4     .07       0  4996.4     .12       0
Bank Sta=4831.3,5136.2
XS Rating Curve= 0 ,0
Exp/Cntr=0.3,0.1

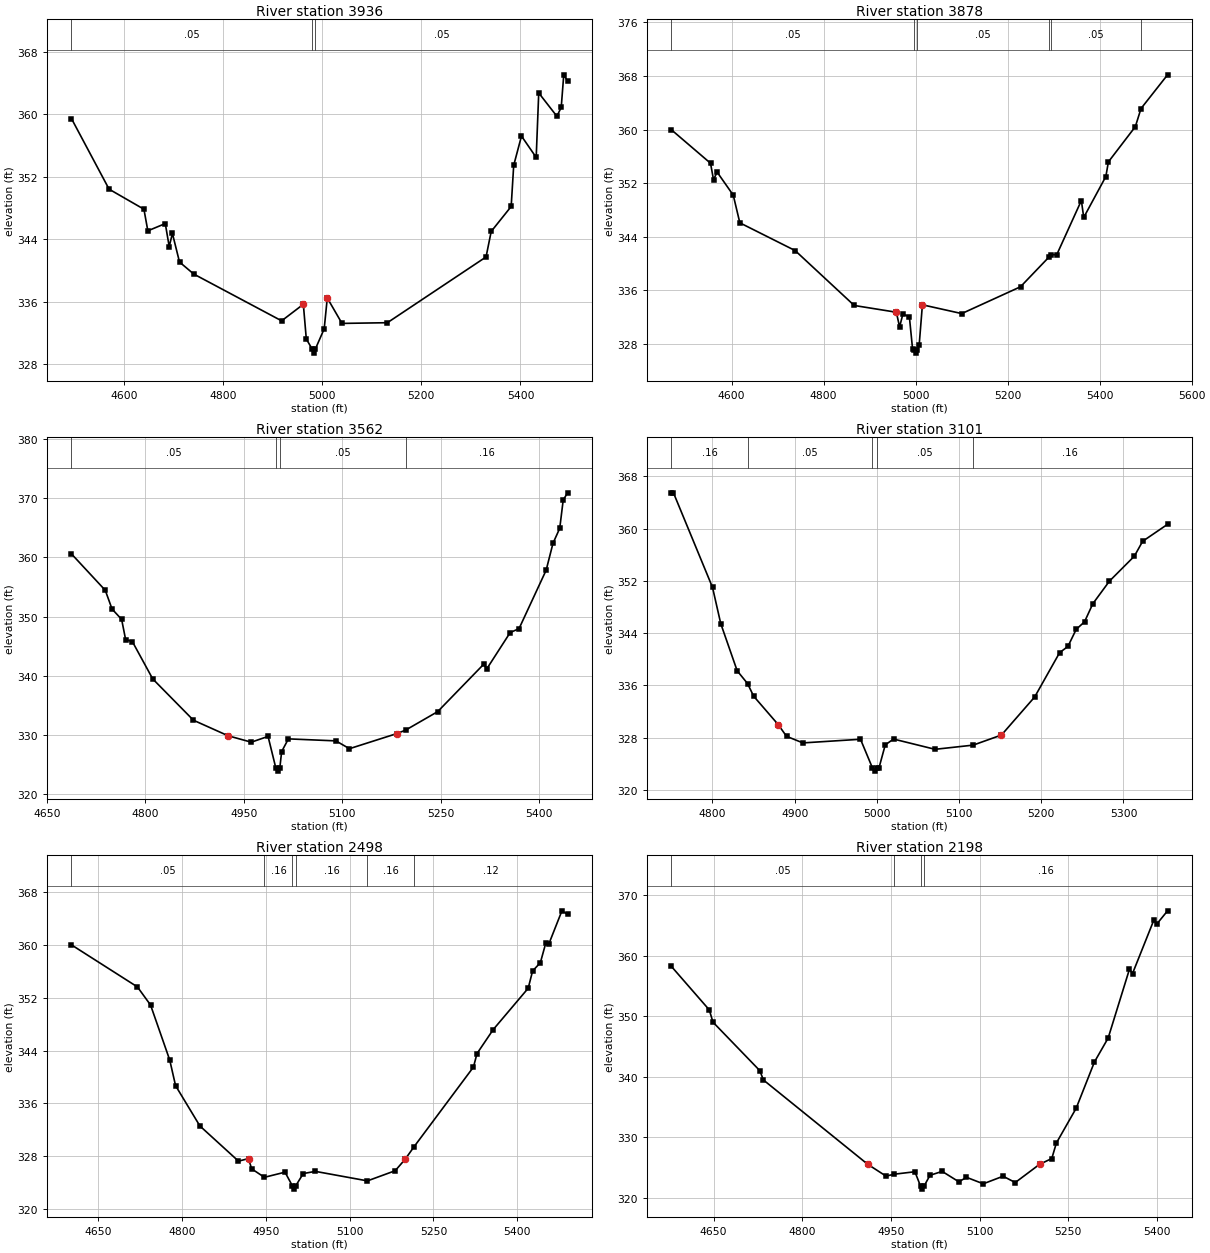
Type RM Length L Ch R = 1 ,3936    ,58,58,58
BEGIN DESCRIPTION:
UNT 149 IN CACR 7.0
END DESCRIPTION:
XS GIS Cut Line= 6
      3706233.25     10698313.19      3705942.43     10697957.27
      3705899.03     10697892.16      3705833.92     10697822.72
      3705805.71     10697777.15      3705742.77     10697468.97
#Sta/Elev= 30
    4494  359.46  4569.9  350.41  4640.2  347.84  4648.1  345.07  4683.3     346
  4691.2  343.06  4697.7  344.73    4712  341.07  4740.7  339.53  4918.1  333.53
  4961.9  335.65  4967.9  331.19    4980  329.89  4982.7  329.39    4986  329.89
    5004  332.51  5010.2  336.46  5039.9   333.2  5131.5  333.29  5330.6  341.72
    5341  344.99  5381.3  348.19  5386.4  353.46  5402.1  357.22  5431.8  354.48
  5436.9  362.75  5473.5  359.76  5482.3  360.89  5487.4  365.07  5495.2  364.28
#Mann= 3 ,-1 , 0
    4494     .05       0    4980     .04       0    4986     .05       0
Bank Sta=4961.9,5010.2
XS Rating Curve= 0 ,0
Exp/Cntr=0.3,0.1

Type RM Length L Ch R = 1 ,3878    ,316,316,316
BEGIN DESCRIPTION:
Mapping XS c705e2d1
END DESCRIPTION:
XS GIS Cut Line= 6
       3706322.2     10698306.65      3706059.62     10697991.99
      3705933.75     10697868.29      3705894.69     10697818.38
      3705829.58     10697672.98      3705781.85     10697408.25
#Sta/Elev= 30
  4469.3  359.96  4554.3  354.97  4560.8  352.51  4568.6  353.65  4603.7  350.21
    4618  346.08  4738.2  341.94  4866.6  333.75  4958.2  332.74  4965.2  330.54
  4972.4  332.48  4986.5  332.05  4993.5  327.21  4997.6  327.14  5000.4  326.64
  5003.6  327.14  5007.7  327.79  5014.8  333.85  5100.3  332.54    5228  336.54
  5289.3  340.93  5293.5  341.34  5306.7  341.31  5360.3  349.41  5365.4  346.88
  5413.5  352.99    5419  355.17  5477.6  360.43  5489.9  363.13  5547.6  368.16
#Mann= 6 ,-1 , 0
  4469.3     .05       0  4997.6     .04       0  5003.6     .05       0
  5289.3     .16       0  5293.5     .05       0  5489.9     .08       0
Bank Sta=4958.2,5014.8
XS Rating Curve= 0 ,0
Exp/Cntr=0.3,0.1

Type RM Length L Ch R = 1 ,3562    ,461,461,461
BEGIN DESCRIPTION:
UNT 149 IN CACR 6.0
END DESCRIPTION:
XS GIS Cut Line= 2
      3706343.91     10698169.97      3706152.93      10697438.6
#Sta/Elev= 30
  4687.5  360.58    4739  354.43  4749.3  351.27  4763.9  349.52    4770   346.1
  4780.3  345.76  4811.3  339.46  4873.3  332.48  4926.2  329.85  4961.5  328.77
    4987  329.75  4998.9  324.38  5001.7  323.88  5004.9  324.38  5007.7  327.18
    5018  329.33  5090.4  328.99    5111  327.67  5183.4  330.23  5196.6  330.81
  5245.4  333.93  5315.3  341.91  5320.5   341.2  5355.8  347.28  5369.4  347.96
  5410.7  357.83  5421.1  362.37  5431.4  364.91  5436.7   369.7  5443.4   370.9
#Mann= 4 ,-1 , 0
  4687.5     .05       0  4998.9     .03       0  5004.9     .05       0
  5196.6     .16       0
Bank Sta=4926.2,5183.4
XS Rating Curve= 0 ,0
Exp/Cntr=0.3,0.1

Type RM Length L Ch R = 1 ,3101    ,603,603,603
BEGIN DESCRIPTION:
UNT 149 IN CACR 5.0
END DESCRIPTION:
XS GIS Cut Line= 3
      3706599.61     10698110.15      3706599.61     10697860.19
      3706549.61      10697510.2
#Sta/Elev= 30
  4750.1  365.47  4752.6  365.47  4800.1  350.99  4810.1  345.45  4830.1  338.22
  4842.7  336.27  4850.1  334.34  4880.1  329.97  4890.1  328.19  4910.1  327.18
  4980.1  327.74  4994.6  323.36  4997.3  322.86  5000.6  323.36  5002.6  323.36
  5010.2  326.88  5020.3  327.77  5070.8   326.2  5117.1  326.84  5151.6  328.39
    5192  334.22  5222.3     341  5232.4  341.95  5242.5  344.57  5252.6  345.72
  5262.7  348.49  5282.9  351.95  5313.2  355.77  5323.3  358.05  5353.6  360.65
#Mann= 5 ,-1 , 0
  4750.1     .16       0  4842.7     .05       0  4994.6     .03       0
  5000.6     .05       0  5117.1     .16       0
Bank Sta=4880.1,5151.6
XS Rating Curve= 0 ,0
Exp/Cntr=0.3,0.1

Type RM Length L Ch R = 1 ,2498    ,300,300,300
BEGIN DESCRIPTION:
UNT 149 IN CACR 4.0
END DESCRIPTION:
XS GIS Cut Line= 2
      3707202.32     10698111.37      3706850.75     10697295.39
#Sta/Elev= 30
  4601.7  360.01  4719.8  353.64  4743.3   350.9  4777.7  342.55  4788.1  338.68
  4831.7  332.57  4900.8  327.24  4918.8  327.63  4924.3  326.08  4947.2  324.79
  4984.1  325.57  4997.3   323.5  5000.1     323  5003.3   323.5  5016.8  325.36
  5038.5  325.69  5131.7  324.25  5181.4  325.79  5199.4  327.54  5214.8  329.38
  5321.6   341.5  5327.9  343.54  5356.9  347.17  5419.6  353.44  5427.5  356.06
  5441.4  357.31    5451  360.26  5456.5  360.13    5480  365.17  5490.2  364.64
#Mann= 6 ,-1 , 0
  4601.7     .05       0  4947.2     .16       0  4997.3     .07       0
  5003.3     .16       0  5131.7     .16       0  5214.8     .12       0
Bank Sta=4918.8,5199.4
XS Rating Curve= 0 ,0
Exp/Cntr=0.3,0.1

Type RM Length L Ch R = 1 ,2198    ,621,621,621
BEGIN DESCRIPTION:
UNT 149 IN CACR 3.0
END DESCRIPTION:
XS GIS Cut Line= 3
       3707449.6     10698010.17      3707299.61     10697610.19
      3707199.61     10697210.17
#Sta/Elev= 30
  4578.5   358.2  4642.6  351.02  4648.8     349    4728     341  4734.2  339.45
  4910.4  325.55  4941.6  323.58  4955.2  323.89  4990.5   324.3    5000  321.93
  5002.8  321.43    5006  321.93    5016  323.71  5036.6  324.36  5064.9  322.64
  5077.8  323.38  5106.2  322.31  5139.7  323.56  5160.3  322.52  5201.5  325.53
  5222.1  326.48  5229.9  329.05  5263.4  334.79  5294.3  342.43  5317.5  346.38
  5353.6  357.76  5358.7  357.02  5394.8  365.85  5399.9  365.21    5418  367.38
#Mann= 4 ,-1 , 0
  4578.5     .05       0  4955.2     .16       0    5000     .07       0
    5006     .16       0
Bank Sta=4910.4,5201.5
XS Rating Curve= 0 ,0
Exp/Cntr=0.3,0.1