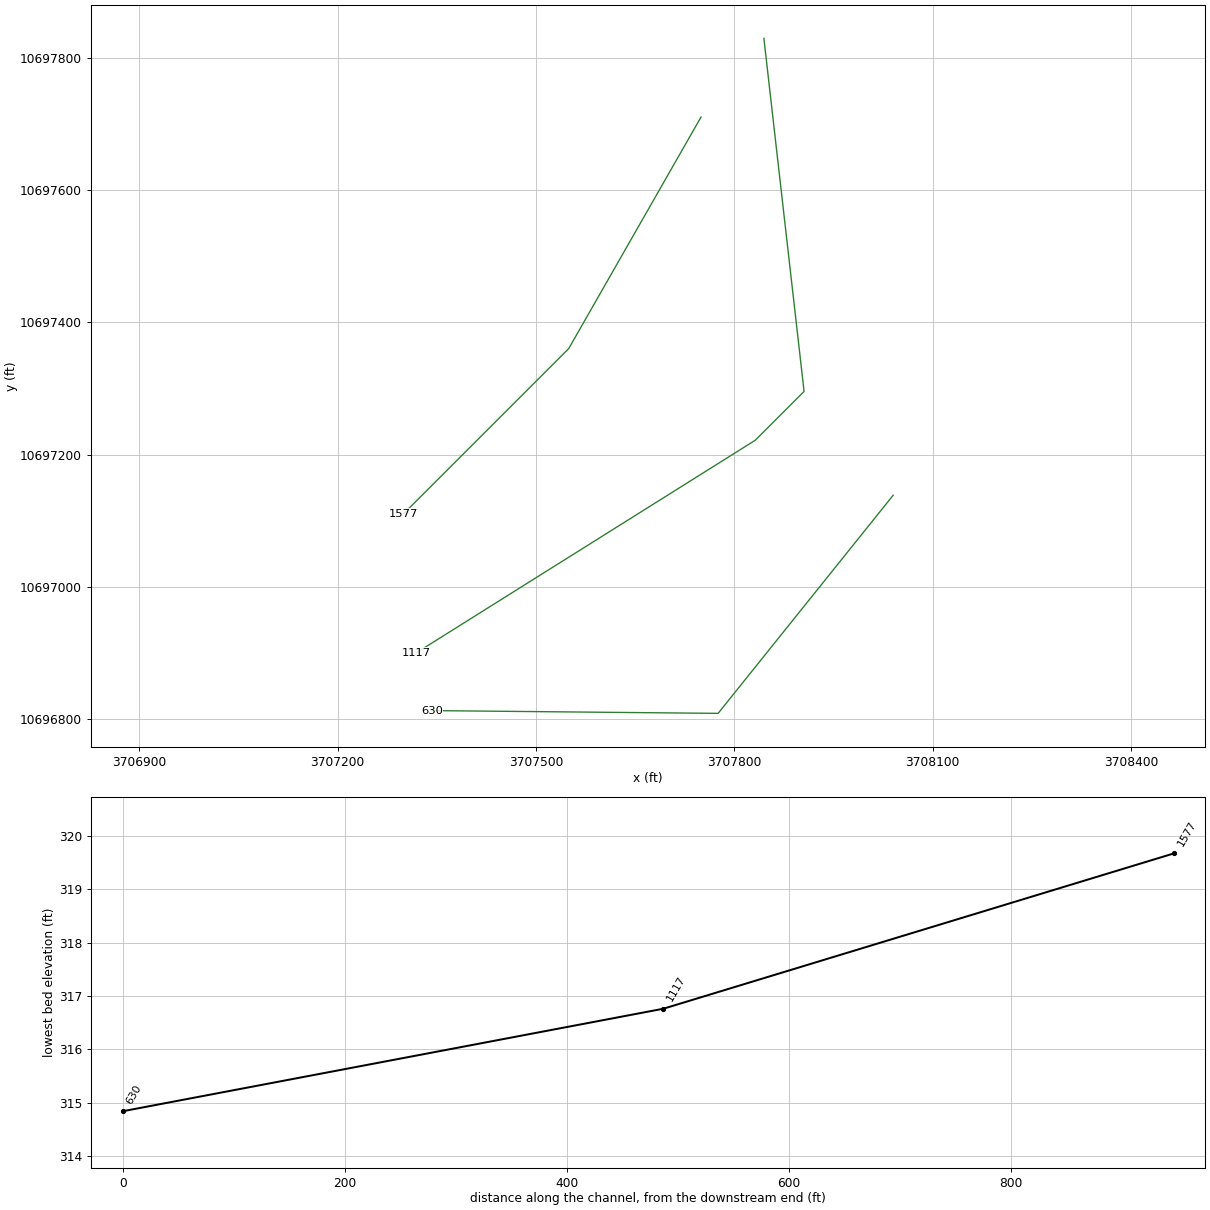
HEC-RAS study UNT 149 IN CACR.prj: UNT 149 IN CACR Base Level Engineering

--- UNT 149 IN CACR.g01 (geometry) --- (continued)

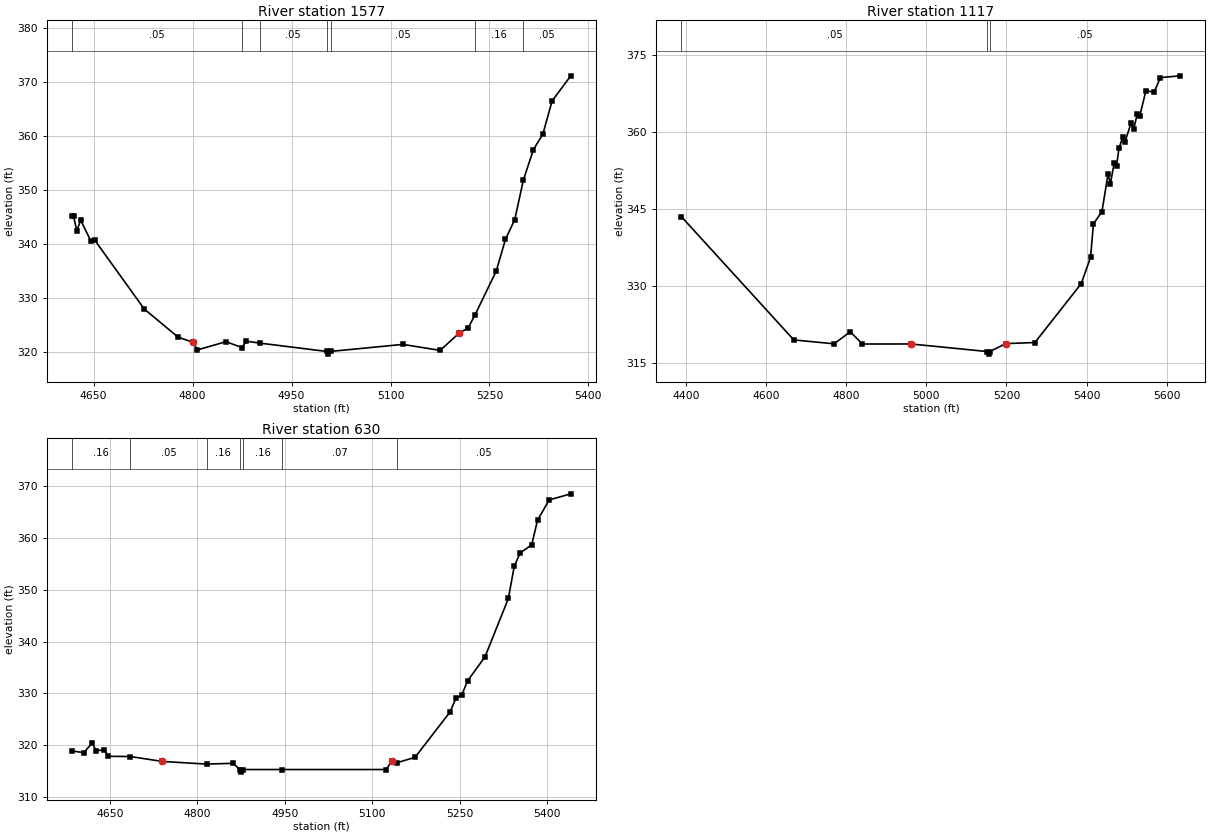
Type RM Length L Ch R = 1 ,1577    ,460,460,460
BEGIN DESCRIPTION:
UNT 149 IN CACR 2.0
END DESCRIPTION:
XS GIS Cut Line= 3
      3707749.62     10697710.21      3707549.61     10697360.19
       3707299.6     10697110.18
#Sta/Elev= 30
  4616.6  345.18  4619.5  345.18  4624.5  342.49  4630.3  344.45  4646.1  340.51
  4651.9  340.71  4726.8     328  4777.9  322.82  4800.9  321.84  4807.4  320.46
  4850.6  321.97  4874.7  320.89  4881.5  322.06  4901.8  321.71  5003.1  320.17
  5005.8  319.67  5009.1  320.17  5118.7  321.47  5175.3  320.36  5203.6  323.51
  5217.7  324.51  5228.3  326.97  5260.2  335.01  5274.3   340.9  5288.4  344.57
  5301.4  351.86  5316.7  357.51  5330.9  360.35    5345  366.51  5373.3  371.15
#Mann= 7 ,-1 , 0
  4616.6     .05       0  4874.7     .16       0  4901.8     .05       0
  5003.1     .03       0  5009.1     .05       0  5228.3     .16       0
  5301.4     .05       0
Bank Sta=4800.9,5203.6
XS Rating Curve= 0 ,0
Exp/Cntr=0.3,0.1

Type RM Length L Ch R = 1 ,1117    ,487,487,487
BEGIN DESCRIPTION:
UNT 149 IN CACR 1.0
END DESCRIPTION:
XS GIS Cut Line= 4
      3707844.66     10697829.24      3707905.43     10697295.38
      3707831.65     10697221.59      3707319.48     10696900.41
#Sta/Elev= 30
  4388.2  343.57  4669.1  319.53  4769.7  318.77    4810  321.12  4840.2  318.73
  4961.6  318.74  5152.5  317.26  5155.3  316.76  5158.5  317.26    5198  318.81
    5271  319.02  5386.5  330.48    5410  335.64  5417.1  342.15  5438.3  344.52
  5453.6  351.84  5459.5  349.98    5469  354.04  5474.9  353.43  5480.8  356.85
  5490.2  359.01  5496.1  358.18  5511.4  361.86  5517.3  360.55  5526.7  363.57
  5532.6  363.13  5547.9     368  5569.1   367.9  5584.4  370.66  5634.4     371
#Mann= 3 ,-1 , 0
  4388.2     .05       0  5152.5     .03       0  5158.5     .05       0
Bank Sta=4961.6,5198
XS Rating Curve= 0 ,0
Exp/Cntr=0.3,0.1

Type RM Length L Ch R = 1 ,630     ,0,0,0
BEGIN DESCRIPTION:
Mapping XS 2c3d21ba
END DESCRIPTION:
XS GIS Cut Line= 3
      3708040.17     10697138.47      3707775.42     10696808.62
       3707342.6     10696812.81
#Sta/Elev= 30
  4584.7  318.94  4605.6  318.59    4620  320.48  4626.5  318.99  4640.9  319.12
  4647.3  317.89  4685.1  317.85  4740.1   316.9    4816  316.39  4861.7  316.54
  4873.1  315.34  4875.8  314.84  4879.1  315.34  4945.8  315.34  5123.5  315.34
  5133.5   316.9  5142.1  316.63  5173.5   317.7  5233.5  326.43  5243.5  329.06
  5253.5  329.67  5263.5  332.42  5293.5  337.08  5333.5  348.32  5343.5  354.49
  5353.5  357.07  5373.5  358.66  5383.5  363.41  5403.5  367.32  5440.5  368.49
#Mann= 7 ,-1 , 0
  4584.7     .16       0  4685.1     .05       0    4816     .16       0
  4873.1     .07       0  4879.1     .16       0  4945.8     .07       0
  5142.1     .05       0
Bank Sta=4740.1,5133.5
XS Rating Curve= 0 ,0
Exp/Cntr=0.3,0.1

Chan Stop Cuts=-1
Use User Specified Reach Order=0
Composite Channel Slope=5