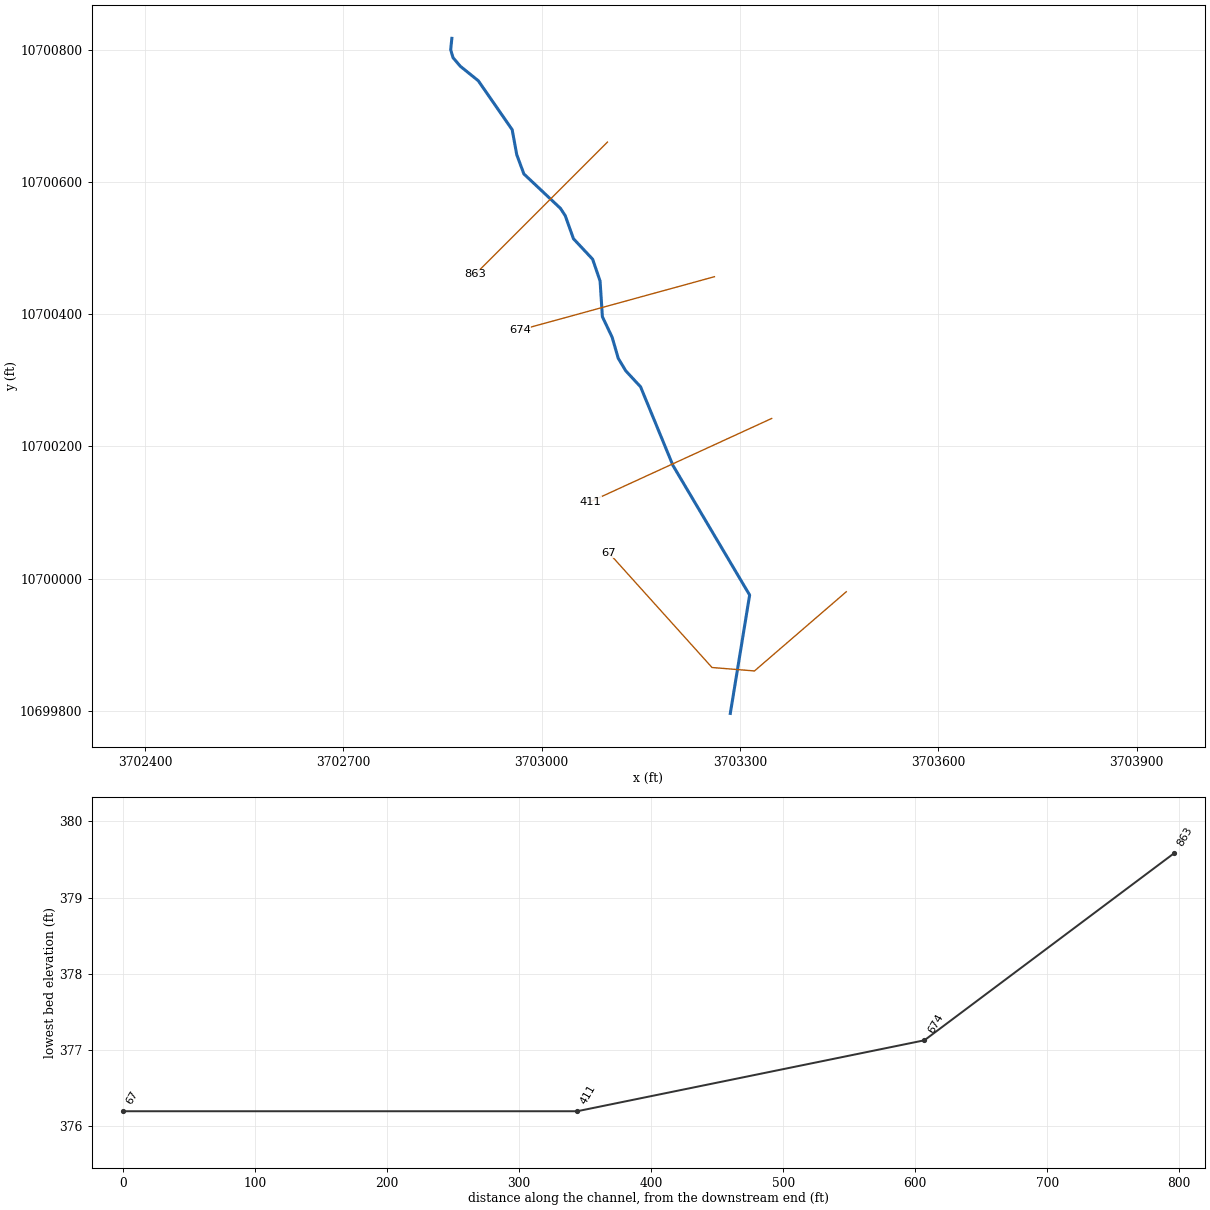
--- UNT 150 IN CACR.prj (project) ---

Proj Title=UNT 150 IN CACR Base Level Engineering
Current Plan=p01
Default Exp/Contr=0.3,0.1
English Units
Geom File=g01
Flow File=f01
Plan File=p01
BEGIN DESCRIPTION:
UNT 150 IN CACR
END DESCRIPTION:

--- UNT 150 IN CACR.p01 (plan) ---

Plan Title=Multiple Run
Short Identifier=Multiple
Geom File=g01
Flow File=f01
Subcritical Flow
K Sum by GR= 0
Std Step Tol= 0.01
Critical Tol= 0.01
Num of Std Step Trials= 20
Max Error Tol= 0.3
Flow Tol Ratio= 0.001
Split Flow NTrial= 30
Split Flow Tol= 0.02
Split Flow Ratio= 0.02
Log Output Level= 0
Friction Slope Method= 1
Unsteady Friction Slope Method= 2
Unsteady Bridges Friction Slope Method= 1
Parabolic Critical Depth
Global Vel Dist=  1 , 1 , 1
Global Log Level= 0
CheckData=True
Encroach Param= -1, 0, 0, 0
BEGIN DESCRIPTION:
Multiple Run
END DESCRIPTION:

--- UNT 150 IN CACR.f01 (steady flow) ---

Flow Title=Multiple
Number of Profiles=7
Profile Names=10-year,25-year,50-year,1pct_min,100-year,1pct_plu,500-year
River Rch & RM= UNT 150 IN CACR,Reach-1,863
     119     146     166     140     190     257     247
Boundary for River Rch & Prof#=UNT 150 IN CACR,Reach-1,1
Up Type=0
Dn Type=3
Dn Slope=0.005
Boundary for River Rch & Prof#=UNT 150 IN CACR,Reach-1,2
Up Type=0
Dn Type=3
Dn Slope=0.005
Boundary for River Rch & Prof#=UNT 150 IN CACR,Reach-1,3
Up Type=0
Dn Type=3
Dn Slope=0.005
Boundary for River Rch & Prof#=UNT 150 IN CACR,Reach-1,4
Up Type=0
Dn Type=3
Dn Slope=0.005
Boundary for River Rch & Prof#=UNT 150 IN CACR,Reach-1,5
Up Type=0
Dn Type=3
Dn Slope=0.005
Boundary for River Rch & Prof#=UNT 150 IN CACR,Reach-1,6
Up Type=0
Dn Type=3
Dn Slope=0.005
Boundary for River Rch & Prof#=UNT 150 IN CACR,Reach-1,7
Up Type=0
Dn Type=3
Dn Slope=0.005

--- UNT 150 IN CACR.g01 (geometry) ---

Geom Title=Existing Conditions

River Reach=UNT 150 IN CACR,Reach-1
Reach XY= 21
      3702864.28     10700817.16      3702862.50     10700800.00
      3702866.00     10700788.00      3702877.00     10700775.00
      3702904.25     10700753.00      3702955.50     10700679.00
      3702962.50     10700641.00      3702973.25     10700612.00
      3703028.50     10700560.00      3703035.75     10700549.00
      3703048.25     10700514.00      3703077.25     10700483.00
      3703088.50     10700450.00      3703092.00     10700396.00
      3703106.75     10700365.00      3703116.00     10700333.00
      3703127.50     10700314.00      3703149.75     10700290.00
      3703198.75     10700171.00      3703314.75     10699975.00
      3703285.50     10699796.00

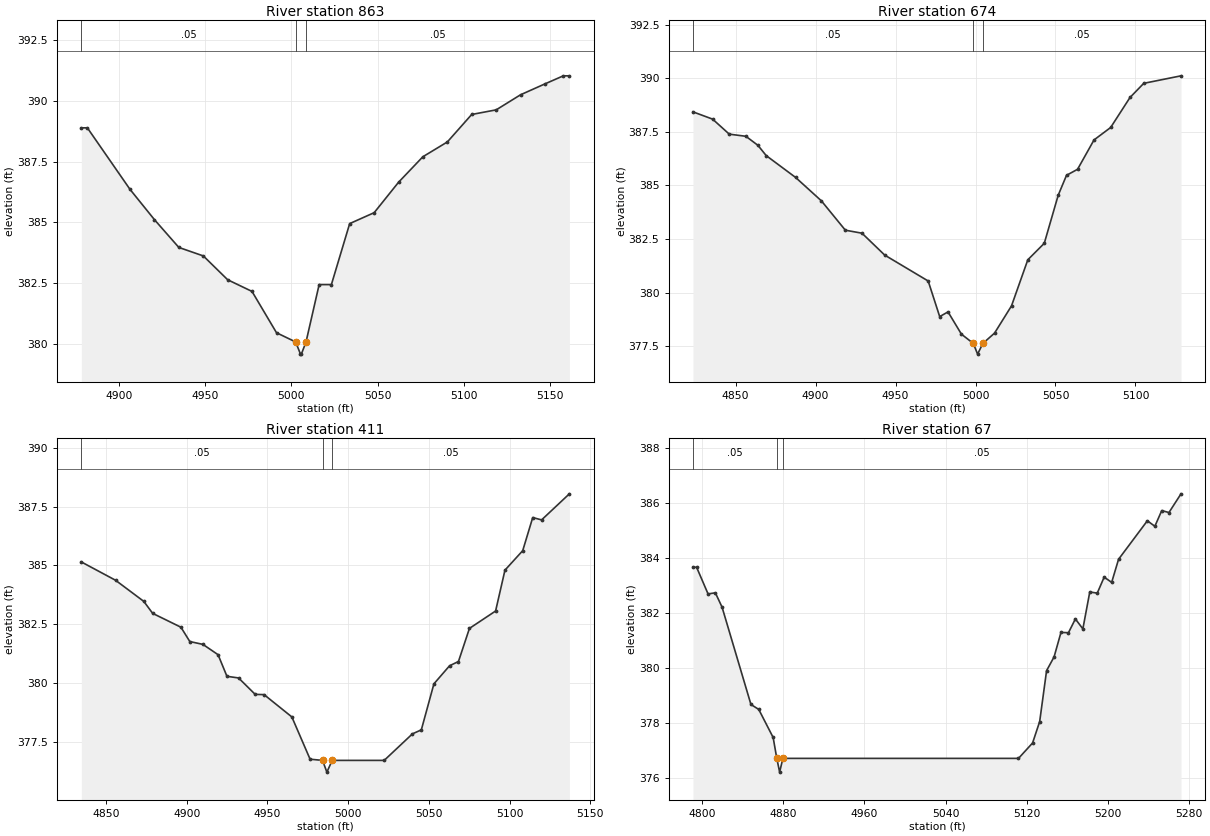
Type RM Length L Ch R = 1,863,189,189,189
BEGIN DESCRIPTION:
UNT 150 IN CACR 2.0
END DESCRIPTION:
XS GIS Cut Line= 3
      3703099.57     10700660.15      3702999.61     10700560.19
      3702899.60     10700460.18
#Sta/Elev= 26
  4878.3  388.89  4881.8  388.89  4906.5  386.36  4920.7  385.11  4934.8  383.97
  4949.0  383.62  4963.1  382.64  4977.2  382.16  4991.4  380.46  5002.5  380.08
  5005.3  379.58  5005.8  379.58  5008.5  380.08  5016.1  382.44  5023.2  382.44
  5033.8  384.95  5048.0  385.40  5062.1  386.65  5076.2  387.70  5090.4  388.31
  5104.5  389.44  5118.7  389.63  5132.8  390.25  5147.0  390.70  5157.6  391.03
  5161.1  391.03
#Mann=3,-1,0
  4878.3    0.05       0  5002.5    0.03       0  5008.5    0.05       0
Bank Sta=5002.5,5008.5
Exp/Cntr=0.3,0.1

Type RM Length L Ch R = 1,674,263,263,263
BEGIN DESCRIPTION:
Mapping XS bd62c246
END DESCRIPTION:
XS GIS Cut Line= 2
      3703261.51     10700456.56      3702967.18     10700375.81
#Sta/Elev= 30
  4823.3  388.43  4835.6  388.09  4846.0  387.39  4856.4  387.29  4863.9  386.87
  4869.1  386.39  4887.5  385.37  4903.6  384.28  4918.6  382.91  4929.0  382.77
  4943.2  381.75  4970.4  380.54  4977.6  378.88  4982.8  379.10  4991.2  378.06
  4998.6  377.63  5001.3  377.13  5004.6  377.63  5011.9  378.11  5022.5  379.38
  5032.7  381.53  5043.0  382.30  5051.7  384.54  5056.9  385.47  5063.8  385.75
  5074.1  387.12  5084.5  387.70  5096.6  389.10  5105.2  389.76  5128.5  390.11
#Mann=3,-1,0
  4823.3    0.05       0  4998.6    0.03       0  5004.6    0.05       0
Bank Sta=4998.6,5004.6
Exp/Cntr=0.3,0.1

Type RM Length L Ch R = 1,411,344,344,344
BEGIN DESCRIPTION:
Mapping XS d00a4c91
END DESCRIPTION:
XS GIS Cut Line= 2
      3703348.09     10700242.13      3703073.36     10700115.99
#Sta/Elev= 30
  4834.7  385.15  4855.9  384.37  4873.4  383.47  4878.9  382.96  4896.4  382.37
  4901.9  381.76  4910.0  381.64  4919.4  381.20  4924.9  380.28  4932.1  380.21
  4942.4  379.51  4947.9  379.50  4965.1  378.55  4976.4  376.75  4984.1  376.70
  4986.8  376.20  4990.1  376.70  5022.3  376.70  5039.8  377.83  5045.3  378.00
  5053.1  379.96  5062.8  380.73  5068.3  380.91  5075.1  382.32  5091.3  383.06
  5097.1  384.80  5108.1  385.63  5114.3  387.04  5119.8  386.94  5137.0  388.05
#Mann=3,-1,0
  4834.7    0.05       0  4984.1    0.03       0  4990.1    0.05       0
Bank Sta=4984.1,4990.1
Exp/Cntr=0.3,0.1

Type RM Length L Ch R = 1,67,0,0,0
BEGIN DESCRIPTION:
UNT 150 IN CACR 1.0
END DESCRIPTION:
XS GIS Cut Line= 4
      3703460.93     10699979.96      3703322.06     10699860.19
      3703257.82     10699865.40      3703101.58     10700039.01
#Sta/Elev= 30
  4790.8  383.65  4794.4  383.65  4805.7  382.68  4812.9  382.72  4819.5  382.20
  4848.0  378.66  4855.7  378.48  4869.9  377.46  4873.5  376.70  4876.3  376.20
  4879.5  376.70  5111.9  376.70  5125.8  377.26  5132.8  378.04  5139.6  379.89
  5147.0  380.39  5153.8  381.28  5161.2  381.27  5168.0  381.77  5175.4  381.41
  5182.2  382.75  5189.6  382.71  5196.4  383.29  5203.8  383.10  5210.6  383.94
  5239.0  385.34  5246.4  385.14  5253.2  385.71  5260.3  385.64  5272.2  386.32
#Mann=3,-1,0
  4790.8    0.05       0  4873.5   0.033       0  4879.5    0.05       0
Bank Sta=4873.5,4879.5
Exp/Cntr=0.3,0.1

Chan Stop Cuts=-1