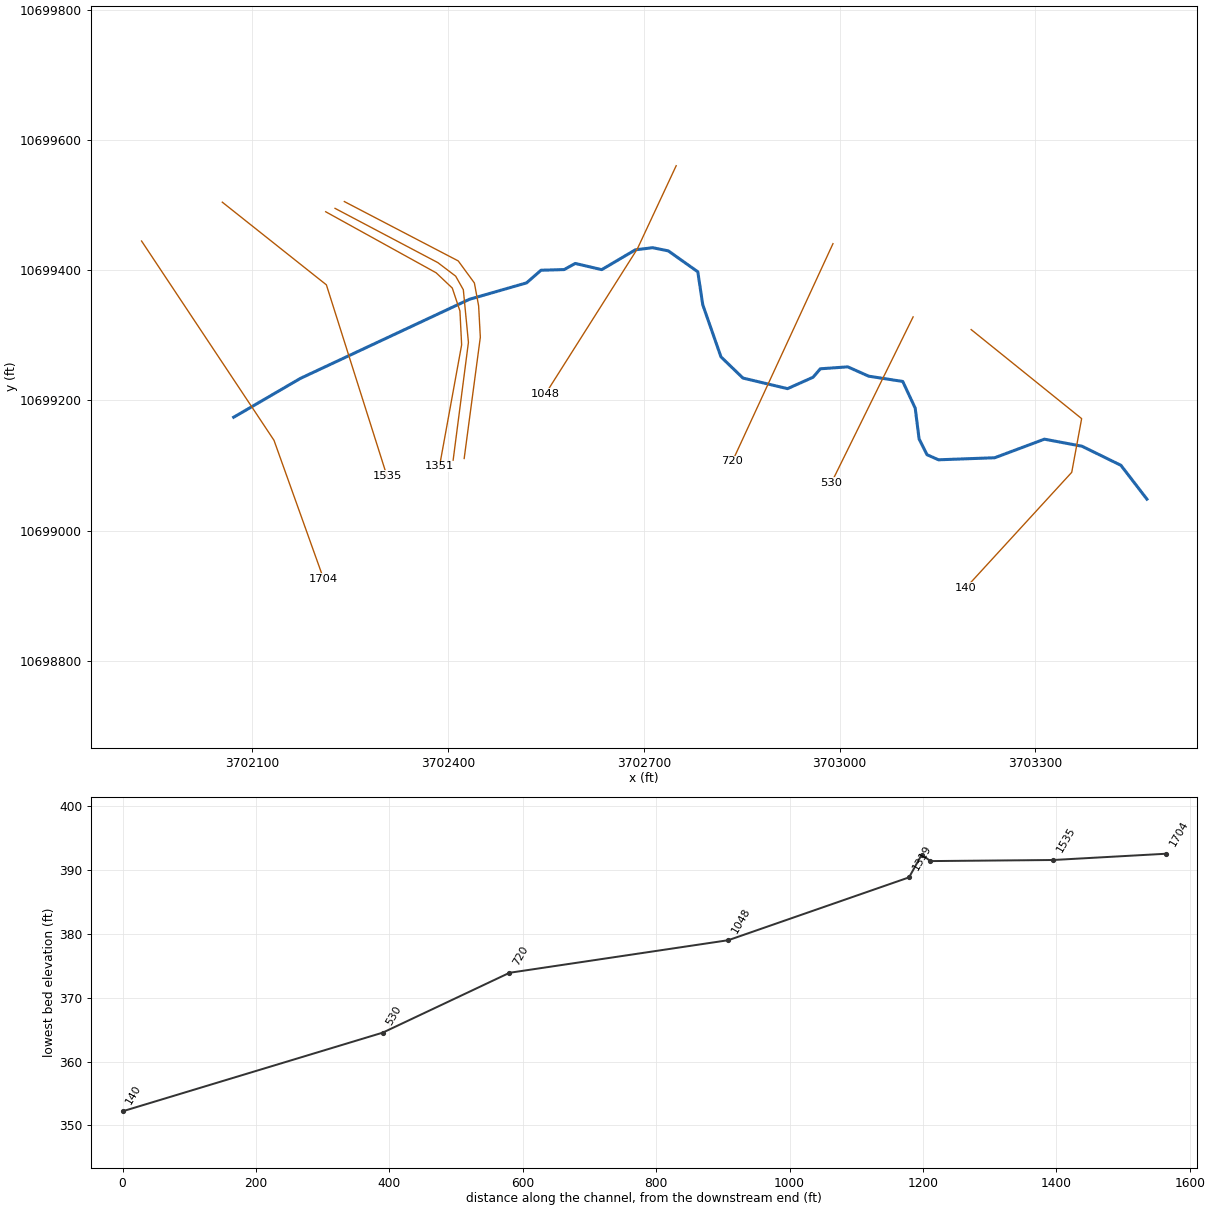
--- UNT 151 IN CACR.prj (project) ---

Proj Title=UNT 151 IN CACR Base Level Engineering
Current Plan=p01
Default Exp/Contr=0.3,0.1
English Units
Geom File=g01
Flow File=f01
Plan File=p01
Y Axis Title=Elevation
X Axis Title(PF)=Main Channel Distance
X Axis Title(XS)=Station
BEGIN DESCRIPTION:
UNT 151 IN CACR
END DESCRIPTION:
DSS Export Rating Curves= 0
DSS Export Rating Curve Sorted= 0
DSS Export Volume Flow Curves= 0
DXF OffsetX= 0
DXF OffsetY= 0
DXF ScaleX= 1
DXF ScaleY= 10

--- UNT 151 IN CACR.p01 (plan) ---

Plan Title=Multiple Run
Short Identifier=Multiple
Geom File=g01
Flow File=f01
Subcritical Flow
K Sum by GR= 0
Std Step Tol= 0.01
Critical Tol= 0.01
Num of Std Step Trials= 20
Max Error Tol= 0.3
Flow Tol Ratio= 0.001
Split Flow NTrial= 30
Split Flow Tol= 0.02
Split Flow Ratio= 0.02
Log Output Level= 0
Friction Slope Method= 1
Unsteady Friction Slope Method= 2
Unsteady Bridges Friction Slope Method= 1
Parabolic Critical Depth
Global Vel Dist=  1 , 1 , 1
Global Log Level= 0
CheckData=True
Encroach Param= -1, 0, 0, 0
BEGIN DESCRIPTION:
Multiple Run
END DESCRIPTION:

--- UNT 151 IN CACR.f01 (steady flow) ---

Flow Title=Multiple
Number of Profiles=7
Profile Names=10-year,25-year,50-year,1pct_min,100-year,1pct_plu,500-year
River Rch & RM= UNT 151 IN CACR,Reach-1,1704
     109     132     150     126     170     230     219
Boundary for River Rch & Prof#=UNT 151 IN CACR,Reach-1,1
Up Type=0
Dn Type=3
Dn Slope=0.005
Boundary for River Rch & Prof#=UNT 151 IN CACR,Reach-1,2
Up Type=0
Dn Type=3
Dn Slope=0.005
Boundary for River Rch & Prof#=UNT 151 IN CACR,Reach-1,3
Up Type=0
Dn Type=3
Dn Slope=0.005
Boundary for River Rch & Prof#=UNT 151 IN CACR,Reach-1,4
Up Type=0
Dn Type=3
Dn Slope=0.005
Boundary for River Rch & Prof#=UNT 151 IN CACR,Reach-1,5
Up Type=0
Dn Type=3
Dn Slope=0.005
Boundary for River Rch & Prof#=UNT 151 IN CACR,Reach-1,6
Up Type=0
Dn Type=3
Dn Slope=0.005
Boundary for River Rch & Prof#=UNT 151 IN CACR,Reach-1,7
Up Type=0
Dn Type=3
Dn Slope=0.005

--- UNT 151 IN CACR.g01 (geometry) ---

Geom Title=Existing Conditions
Program Version=4.10

River Reach=UNT 151 IN CACR ,Reach-1
Reach XY= 30
      3702071.51     10699173.92      3702173.91     10699233.67
      3702432.84     10699355.12      3702520.29     10699380.26
      3702542.52      10699399.7      3702577.93     10699400.74
      3702594.95     10699410.12      3702635.55     10699400.61
      3702687.06     10699431.04      3702713.49     10699434.34
      3702737.58     10699429.42      3702782.72     10699397.31
      3702790.36     10699346.61      3702818.24     10699266.68
      3702851.88     10699234.12      3702920.24     10699217.85
      3702959.31     10699235.34      3702970.57     10699248.35
      3703012.52     10699251.34      3703044.59     10699237.02
      3703096.78      10699228.9      3703115.88     10699187.93
      3703121.84     10699140.66        3703134.     10699116.36
      3703151.65     10699108.59      3703237.77     10699111.74
      3703313.91     10699140.28      3703371.42     10699129.43
       3703431.1     10699100.13      3703470.96     10699048.13

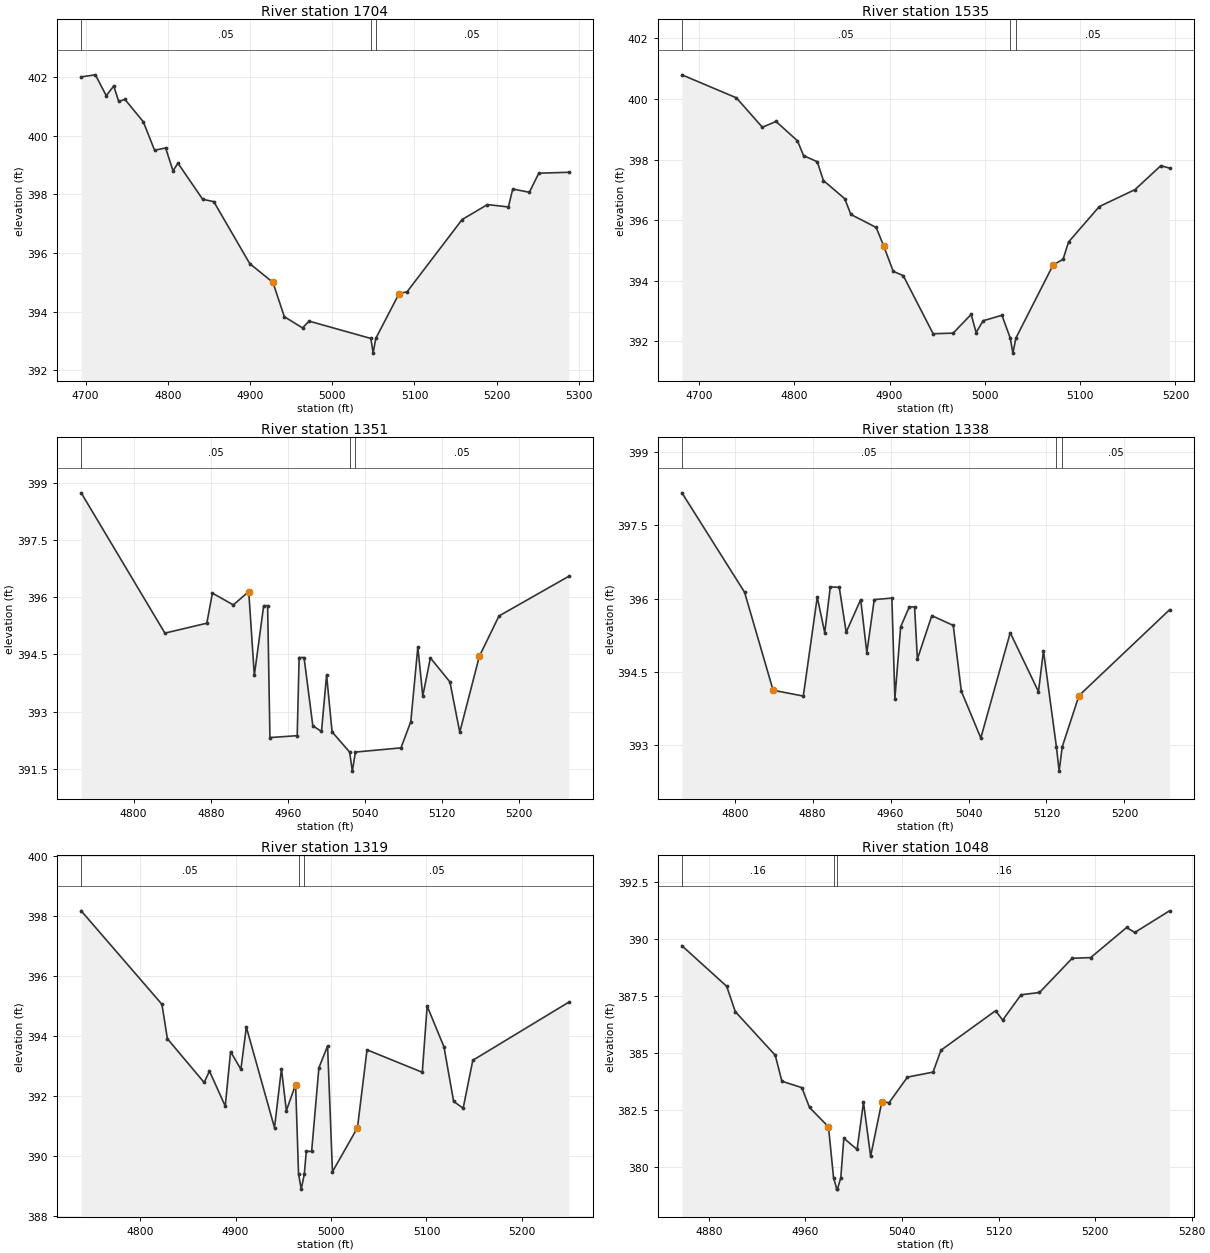
Type RM Length L Ch R = 1 ,1704    ,169,169,169
BEGIN DESCRIPTION:
UNT 151 IN CACR 3.0
END DESCRIPTION:
XS GIS Cut Line= 3
      3701930.38     10699444.58      3702133.31     10699138.55
      3702209.26      10698925.9
#Sta/Elev= 30
  4694.6     402  4711.9  402.07  4725.1  401.36  4734.2  401.69  4740.2  401.17
  4747.9  401.23  4770.2  400.47  4783.9   399.5  4797.3  399.58  4806.3   398.8
  4812.3  399.06  4842.4  397.83  4855.9  397.75  4899.6  395.64  4927.8     395
  4941.7  393.83  4963.8  393.45  4971.8  393.68  5046.9  393.09  5049.7  392.59
  5052.9  393.09  5081.3  394.62    5091  394.68  5157.9  397.14  5188.7  397.65
  5214.2  397.57  5219.5  398.18  5239.7  398.07  5251.2  398.72  5287.6  398.75
#Mann= 3 ,-1 , 0
  4694.6     .05       0  5046.9     .03       0  5052.9     .05       0
Bank Sta=4927.8,5081.3
XS Rating Curve= 0 ,0
Exp/Cntr=0.3,0.1

Type RM Length L Ch R = 1 ,1535    ,184,184,184
BEGIN DESCRIPTION:
Mapping XS 91171e55
END DESCRIPTION:
XS GIS Cut Line= 3
       3702054.1     10699504.22      3702213.61     10699377.26
      3702306.44     10699083.65
#Sta/Elev= 30
    4682   400.8  4739.2  400.04  4766.4  399.07  4780.8  399.26  4803.3  398.62
  4809.7  398.13  4824.1  397.93  4830.5  397.31  4852.9  396.71  4859.3  396.19
  4885.9  395.76  4893.9  395.14  4903.8  394.31  4914.3  394.17  4945.7  392.25
  4966.7  392.27  4985.6  392.89  4990.8  392.29  4998.2  392.68  5017.9  392.86
  5026.6  392.11  5029.4  391.61  5032.6  392.11  5071.6  394.52  5082.1  394.71
  5087.8  395.28  5120.1  396.45  5157.6  397.01  5184.7   397.8  5193.8  397.72
#Mann= 3 ,-1 , 0
    4682     .05       0  5026.6     .03       0  5032.6     .05       0
Bank Sta=4893.9,5071.6
XS Rating Curve= 0 ,0
Exp/Cntr=0.3,0.1

Type RM Length L Ch R = 1 ,1351    ,13,13,13
BEGIN DESCRIPTION:
Mapping XS eae0d7cd
END DESCRIPTION:
XS GIS Cut Line= 6
      3702212.53     10699489.52      3702381.78     10699395.78
      3702406.52     10699372.34      3702418.24     10699337.19
      3702420.85      10699285.1      3702386.99     10699098.91
#Sta/Elev= 30
  4745.5  398.74  4832.4  395.06  4875.9  395.32  4881.7  396.11  4903.4   395.8
  4919.4  396.15  4925.2  393.95  4934.9  395.78    4939  395.78  4941.4  392.32
  4969.7  392.37  4971.7  394.42  4976.8  394.42  4985.9  392.63  4994.9  392.48
  5000.2  393.96  5005.9  392.47  5024.1  391.94  5026.9  391.44  5030.1  391.94
  5077.4  392.05  5087.6  392.74  5094.9   394.7    5100  393.41  5107.9  394.41
  5128.2  393.78  5138.4  392.46  5158.7  394.45  5179.1  395.51  5251.5  396.55
#Mann= 3 ,-1 , 0
  4745.5     .05       0  5024.1     .03       0  5030.1     .05       0
Bank Sta=4919.4,5158.7
XS Rating Curve= 0 ,0
Exp/Cntr=0.3,0.1

Type RM Length L Ch R = 1 ,1338    ,19,19,19
BEGIN DESCRIPTION:
Mapping XS e8052ed5
END DESCRIPTION:
XS GIS Cut Line= 6
      3702226.85     10699494.73      3702384.39     10699411.41
      3702411.73     10699390.57      3702423.45     10699369.74
      3702431.26     10699289.01      3702407.83     10699108.05
#Sta/Elev= 30
  4745.8  398.17  4810.1  396.13  4839.4  394.12  4870.4     394  4884.7  396.03
  4892.4   395.3  4898.1  396.24  4907.3  396.23  4914.4  395.31  4929.3  395.98
  4935.6  394.89  4943.2  395.98  4961.3  396.01  4964.4  393.95  4970.3  395.42
  4979.2  395.83  4984.6  395.83  4987.5  394.76  5002.3  395.65  5024.3  395.45
  5032.6   394.1  5052.6  393.14  5082.8   395.3  5111.8  394.09  5116.9  394.93
  5130.2  392.96    5133  392.46  5136.2  392.96  5153.4  394.01  5246.3  395.77
#Mann= 3 ,-1 , 0
  4745.8     .05       0  5130.2     .03       0  5136.2     .05       0
Bank Sta=4839.4,5153.4
XS Rating Curve= 0 ,0
Exp/Cntr=0.3,0.1

Type RM Length L Ch R = 1 ,1319    ,271,271,271
BEGIN DESCRIPTION:
Mapping XS ff4c9848
END DESCRIPTION:
XS GIS Cut Line= 6
      3702241.12     10699505.17      3702415.64     10699414.01
      3702440.38     10699380.16      3702446.89       10699345.
      3702449.49     10699296.82      3702424.75     10699110.59
#Sta/Elev= 30
  4738.3  398.18  4822.9  395.06  4828.6  393.91  4867.1  392.45  4872.7  392.83
  4889.2  391.66  4894.8  393.48  4905.6  392.89  4911.3   394.3  4940.8  390.94
  4948.1  392.91  4953.2  391.51  4962.9  392.38    4966  389.39  4968.8  388.89
    4972  389.39  4974.1  390.15  4979.7  390.15  4987.3  392.94  4996.4  393.67
  5001.5  389.47  5027.7  390.94  5037.7  393.54  5095.6  392.79  5100.7     395
  5118.3  393.64  5128.4  391.82  5138.4  391.59  5148.5  393.19    5249  395.13
#Mann= 3 ,-1 , 0
  4738.3     .05       0    4966     .03       0    4972     .05       0
Bank Sta=4962.9,5027.7
XS Rating Curve= 0 ,0
Exp/Cntr=0.3,0.1

Type RM Length L Ch R = 1 ,1048    ,328,328,328
BEGIN DESCRIPTION:
UNT 151 IN CACR 2.0
END DESCRIPTION:
XS GIS Cut Line= 3
      3702749.62     10699560.22       3702690.2     10699432.69
       3702549.6     10699210.18
#Sta/Elev= 30
  4857.7  389.71  4894.8  387.93  4901.9  386.82    4935  384.91  4940.5  383.77
    4957  383.49  4963.4  382.62  4979.1  381.77  4983.3  379.54    4986  379.04
  4986.5  379.04  4989.3  379.54  4991.8  381.27  5002.8  380.78  5008.1  382.85
    5014  380.48  5023.3  382.87  5029.3  382.83  5044.5  383.95  5065.7  384.17
  5072.3  385.13  5117.5  386.86  5123.4  386.45  5138.6  387.56  5153.9  387.66
    5181  389.16  5196.3  389.19  5226.1  390.51  5232.8  390.29  5261.6  391.24
#Mann= 3 ,-1 , 0
  4857.7     .16       0  4983.3     .07       0  4986.5     .16       0
Bank Sta=4979.1,5023.3
XS Rating Curve= 0 ,0
Exp/Cntr=0.3,0.1

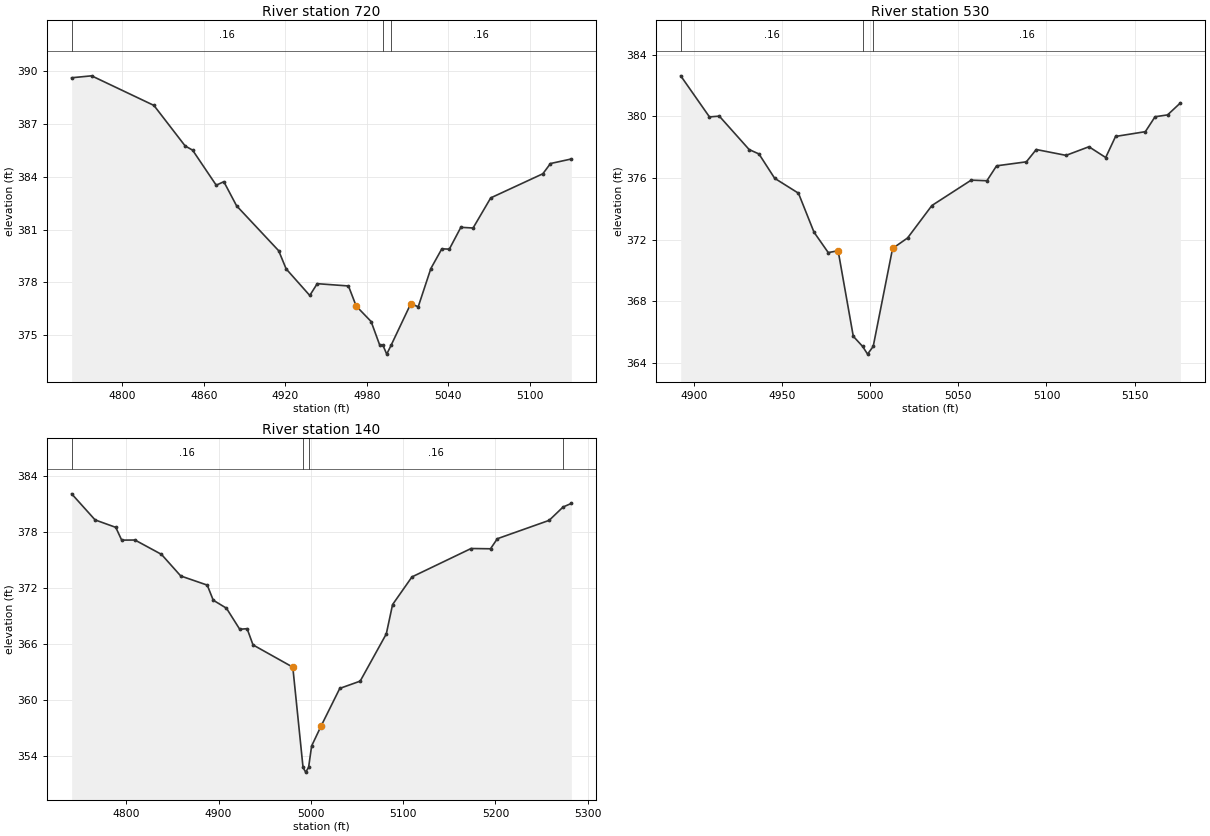
Type RM Length L Ch R = 1 ,720     ,190,190,190
BEGIN DESCRIPTION:
Mapping XS 4cba1219
END DESCRIPTION:
XS GIS Cut Line= 2
      3702989.87     10699440.52      3702835.76     10699106.24
#Sta/Elev= 30
  4762.6  389.62  4777.3  389.73  4823.2  388.05  4846.2  385.75  4851.7  385.51
  4869.1  383.52  4874.7  383.72  4884.1  382.35  4915.1   379.8  4920.6  378.77
    4938  377.26  4943.5  377.93  4966.5   377.8  4972.2  376.66  4983.2  375.78
  4989.4  374.47  4991.9  374.43  4994.7  373.93  4997.9  374.43  5012.4  376.79
  5017.9  376.62  5027.2  378.79  5035.3  379.91  5040.8  379.89  5049.3  381.13
  5058.3  381.09  5071.3   382.8  5109.7  384.17  5115.3  384.75  5130.7  385.01
#Mann= 3 ,-1 , 0
  4762.6     .16       0  4991.9     .07       0  4997.9     .16       0
Bank Sta=4972.2,5012.4
XS Rating Curve= 0 ,0
Exp/Cntr=0.3,0.1

Type RM Length L Ch R = 1 ,530     ,390,390,390
BEGIN DESCRIPTION:
Mapping XS 54a1fa58
END DESCRIPTION:
XS GIS Cut Line= 2
      3703112.68     10699328.05      3702987.62     10699073.63
#Sta/Elev= 30
  4892.5  382.64  4908.8  379.97  4914.4  380.02  4931.3  377.85  4936.9  377.56
  4945.8  375.98  4959.3  375.01  4968.1  372.48  4976.2  371.15  4981.8  371.27
  4990.4  365.71  4995.7  365.05  4998.5  364.55  5001.7  365.05  5012.7  371.42
  5021.2   372.1    5035  374.21  5057.3  375.86  5066.2  375.82  5071.7  376.79
  5088.6  377.05  5094.2  377.85  5111.1  377.47  5124.1  378.03  5133.6  377.33
  5139.2   378.7  5156.1  379.01  5161.6  379.98  5168.7   380.1    5176  380.88
#Mann= 3 ,-1 , 0
  4892.5     .16       0  4995.7     .07       0  5001.7     .16       0
Bank Sta=4981.8,5012.7
XS Rating Curve= 0 ,0
Exp/Cntr=0.3,0.1

Type RM Length L Ch R = 1 ,140     ,0,0,0
BEGIN DESCRIPTION:
UNT 151 IN CACR 1.0
END DESCRIPTION:
XS GIS Cut Line= 4
      3703201.63     10699308.57      3703370.93     10699171.82
      3703355.74     10699089.36      3703193.82     10698912.32
#Sta/Elev= 30
  4740.8   382.1  4766.2   379.3  4788.6   378.5    4795  377.13  4809.4  377.14
  4838.1   375.6    4859  373.28  4887.7   372.3  4894.2  370.68  4908.5  369.82
  4922.9  367.56  4930.9  367.62  4937.3  365.88  4980.4  363.49  4991.5  352.72
  4994.3  352.22  4997.5  352.72  5000.8  355.03  5010.9  357.14  5031.3  361.21
  5053.4  361.99  5081.7  367.06  5088.5  370.21  5109.5  373.18  5173.6  376.23
  5194.6   376.2    5202  377.28  5258.1  379.25  5273.3  380.69  5282.2  381.07
#Mann= 4 ,-1 , 0
  4740.8     .16       0  4991.5     .07       0  4997.5     .16       0
  5273.3     .12       0
Bank Sta=4980.4,5010.9
XS Rating Curve= 0 ,0
Exp/Cntr=0.3,0.1

Chan Stop Cuts=-1
Use User Specified Reach Order=0
Composite Channel Slope=5