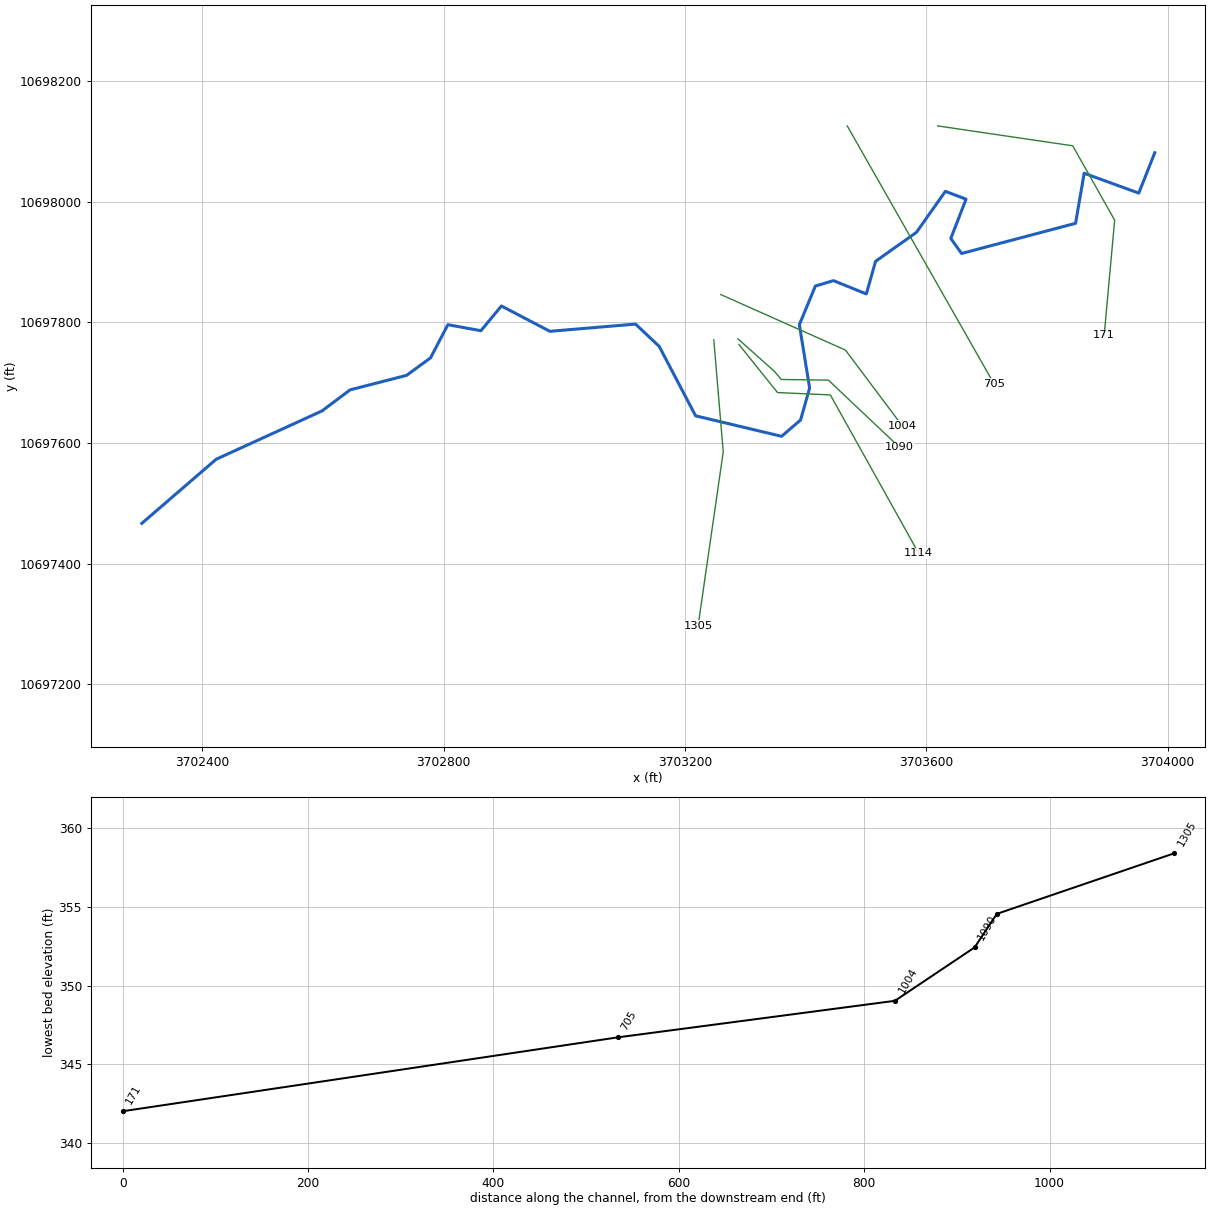
--- UNT 152 IN CACR.prj (project) ---

Proj Title=UNT 152 IN CACR Base Level Engineering
Current Plan=p01
Default Exp/Contr=0.3,0.1
English Units
Geom File=g01
Flow File=f01
Plan File=p01
Y Axis Title=Elevation
X Axis Title(PF)=Main Channel Distance
X Axis Title(XS)=Station
BEGIN DESCRIPTION:
UNT 152 IN CACR
END DESCRIPTION:
DSS Export Rating Curves= 0
DSS Export Rating Curve Sorted= 0
DSS Export Volume Flow Curves= 0
DXF OffsetX= 0
DXF OffsetY= 0
DXF ScaleX= 1
DXF ScaleY= 10

--- UNT 152 IN CACR.p01 (plan) ---

Plan Title=Multiple Run
Short Identifier=Multiple
Geom File=g01
Flow File=f01
Subcritical Flow
K Sum by GR= 0
Std Step Tol= 0.01
Critical Tol= 0.01
Num of Std Step Trials= 20
Max Error Tol= 0.3
Flow Tol Ratio= 0.001
Split Flow NTrial= 30
Split Flow Tol= 0.02
Split Flow Ratio= 0.02
Log Output Level= 0
Friction Slope Method= 1
Unsteady Friction Slope Method= 2
Unsteady Bridges Friction Slope Method= 1
Parabolic Critical Depth
Global Vel Dist=  1 , 1 , 1
Global Log Level= 0
CheckData=True
Encroach Param= -1, 0, 0, 0
BEGIN DESCRIPTION:
Multiple Run
END DESCRIPTION:

--- UNT 152 IN CACR.f01 (steady flow) ---

Flow Title=Multiple
Program Version=4.10
Number of Profiles= 7
Profile Names=10-year,25-year,50-year,1pct_min,100-year,1pct_plu,500-year
River Rch & RM=UNT 152 IN CACR,Reach-1         ,1305
     209     267     313     271     366     495     501
Boundary for River Rch & Prof#=UNT 152 IN CACR,Reach-1         , 1
Up Type= 0
Dn Type= 3
Dn Slope=0.00879
Boundary for River Rch & Prof#=UNT 152 IN CACR,Reach-1         , 2
Up Type= 0
Dn Type= 3
Dn Slope=0.00879
Boundary for River Rch & Prof#=UNT 152 IN CACR,Reach-1         , 3
Up Type= 0
Dn Type= 3
Dn Slope=0.00879
Boundary for River Rch & Prof#=UNT 152 IN CACR,Reach-1         , 4
Up Type= 0
Dn Type= 3
Dn Slope=0.00879
Boundary for River Rch & Prof#=UNT 152 IN CACR,Reach-1         , 5
Up Type= 0
Dn Type= 3
Dn Slope=0.00879
Boundary for River Rch & Prof#=UNT 152 IN CACR,Reach-1         , 6
Up Type= 0
Dn Type= 3
Dn Slope=0.00879
Boundary for River Rch & Prof#=UNT 152 IN CACR,Reach-1         , 7
Up Type= 0
Dn Type= 3
Dn Slope=0.00879
DSS Import GetInterval= 0
DSS Import GetPeak= 0
DSS Import FillOption= 0

--- UNT 152 IN CACR.g01 (geometry) ---

Geom Title=Existing Conditions
Program Version=4.10

River Reach=UNT 152 IN CACR ,Reach-1
Reach XY= 30
      3702300.02     10697466.71      3702423.25       10697573.
       3702598.5       10697653.      3702645.25       10697688.
      3702738.75       10697712.       3702778.5       10697741.
      3702807.25       10697796.        3702862.       10697786.
        3702896.       10697827.      3702976.25       10697785.
      3703118.25       10697797.       3703157.5       10697760.
      3703217.75       10697645.      3703360.25       10697611.
      3703391.75       10697638.      3703406.75       10697691.
      3703389.75       10697796.      3703416.25       10697860.
      3703446.25       10697869.      3703500.75       10697847.
        3703516.       10697901.      3703583.75       10697949.
      3703631.75       10698017.        3703666.       10698004.
      3703640.75       10697939.       3703658.5       10697914.
       3703847.5       10697964.      3703861.75       10698047.
      3703952.25       10698014.      3703978.75       10698081.

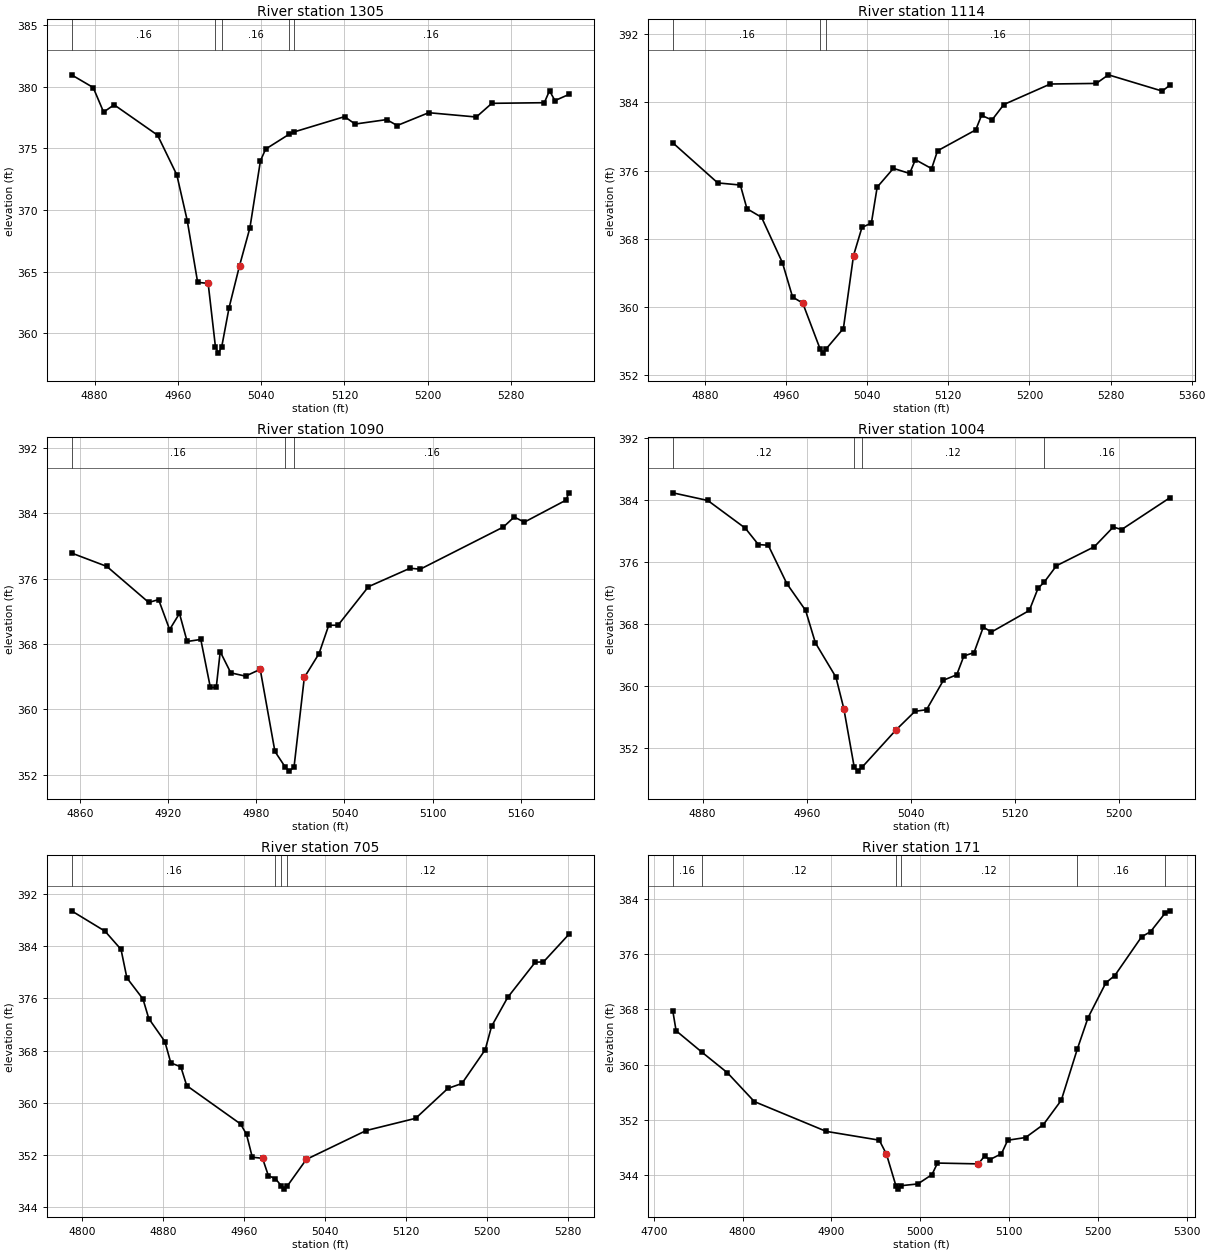
Type RM Length L Ch R = 1 ,1305    ,191,191,191
BEGIN DESCRIPTION:
Mapping XS 831a15f8
END DESCRIPTION:
XS GIS Cut Line= 3
      3703247.97     10697770.91      3703263.59     10697585.19
      3703221.92     10697296.96
#Sta/Elev= 30
  4857.9  380.95  4878.7  379.92  4888.7  377.93  4898.8  378.52  4940.5  376.06
    4959  372.84    4969  369.14    4979  364.13  4989.1  364.04  4996.1  358.89
  4998.9  358.39  5002.1  358.89  5009.2  362.08  5019.2  365.47  5029.2  368.55
  5039.3  373.98  5044.3  374.93    5067  376.14  5071.2  376.31  5120.1  377.56
  5130.2  376.96  5160.5  377.32  5170.6  376.84  5200.9  377.88  5246.6  377.53
  5261.5  378.64  5311.9  378.69  5316.9  379.66  5322.1  378.86  5335.5  379.36
#Mann= 5 ,-1 , 0
  4857.9     .16       0  4996.1     .07       0  5002.1     .16       0
    5067     .12       0  5071.2     .16       0
Bank Sta=4989.1,5019.2
XS Rating Curve= 0 ,0
Exp/Cntr=0.3,0.1

Type RM Length L Ch R = 1 ,1114    ,24,24,24
BEGIN DESCRIPTION:
Mapping XS 3cfdd35e
END DESCRIPTION:
XS GIS Cut Line= 4
      3703289.65     10697763.12      3703353.56     10697683.54
      3703441.11     10697679.59       3703587.6     10697416.99
#Sta/Elev= 30
  4848.4  379.26  4892.7  374.55    4915   374.3  4921.5  371.52  4935.9  370.51
  4956.5  365.17  4966.5  361.14  4976.5  360.43  4993.6  355.05  4996.3  354.55
  4999.6  355.05  5016.6  357.44  5026.6  366.02  5034.9  369.32  5044.2  369.83
  5049.9  374.05  5065.9  376.26  5081.9  375.66  5087.6  377.28  5103.6  376.23
  5109.4  378.32  5147.1  380.78  5152.8  382.49  5163.1  381.94  5174.8  383.76
  5220.6  386.17  5265.9  386.24  5277.9  387.25    5331  385.34  5338.8  386.06
#Mann= 3 ,-1 , 0
  4848.4     .16       0  4993.6     .07       0  4999.6     .16       0
Bank Sta=4976.5,5026.6
XS Rating Curve= 0 ,0
Exp/Cntr=0.3,0.1

Type RM Length L Ch R = 1 ,1090    ,86,86,86
BEGIN DESCRIPTION:
Mapping XS 04071935
END DESCRIPTION:
XS GIS Cut Line= 5
       3703288.1     10697772.48      3703348.88     10697718.21
      3703359.73     10697705.19      3703437.86     10697704.11
      3703555.34     10697593.09
#Sta/Elev= 30
  4854.4  379.12  4878.4  377.48  4906.9  373.07  4913.6  373.42  4921.1  369.75
  4927.8  371.72    4933  368.29  4942.3  368.54  4948.8  362.66  4952.8  362.66
  4955.5  367.04  4962.7  364.45  4972.7  364.05  4982.7  364.88  4992.7  354.83
  4999.7  352.92  5002.5  352.42  5005.7  352.92  5012.7  363.89  5022.7  366.81
  5029.3  370.28  5035.6  370.28  5056.3     375  5084.6  377.26  5091.5  377.14
  5148.1  382.31  5155.4  383.53  5162.3   382.9  5190.6  385.59  5192.6  386.49
#Mann= 3 ,-1 , 0
  4854.4     .16       0  4999.7     .07       0  5005.7     .16       0
Bank Sta=4982.7,5012.7
XS Rating Curve= 0 ,0
Exp/Cntr=0.3,0.1

Type RM Length L Ch R = 1 ,1004    ,299,299,299
BEGIN DESCRIPTION:
UNT 152 IN CACR 2.0
END DESCRIPTION:
XS GIS Cut Line= 3
      3703259.48     10697845.92      3703466.07     10697753.91
      3703559.82     10697628.92
#Sta/Elev= 30
  4857.1  384.96    4884  383.97  4912.8   380.4  4922.9  378.28  4930.5  378.19
  4944.8  373.23  4959.2  369.78  4966.7   365.6  4982.5  361.17  4988.6  357.09
  4996.6  349.53  4999.3  349.03  5002.6  349.53  5028.9  354.38  5043.3  356.75
  5052.2  356.96  5065.2  360.77  5075.4  361.47  5080.9   363.9  5088.7  364.33
  5095.8  367.62  5102.1  366.99  5131.2  369.77  5137.9  372.63  5142.7  373.44
  5152.1  375.55  5181.2     378  5195.8  380.55  5202.1  380.21  5239.5  384.35
#Mann= 4 ,-1 , 0
  4857.1     .12       0  4996.6     .07       0  5002.6     .12       0
  5142.7     .16       0
Bank Sta=4988.6,5028.9
XS Rating Curve= 0 ,0
Exp/Cntr=0.3,0.1

Type RM Length L Ch R = 1 ,705     ,534,534,534
BEGIN DESCRIPTION:
Mapping XS 380c1f57
END DESCRIPTION:
XS GIS Cut Line= 2
      3703469.09     10698125.42      3703712.15     10697698.34
#Sta/Elev= 30
  4789.8  389.47  4822.9  386.34  4838.7  383.54  4844.5  379.16  4860.4  375.92
  4866.1  372.92    4882  369.39  4887.9   366.1  4897.8   365.5  4903.6  362.61
  4956.9  356.71  4962.7  355.11  4968.4  351.61  4978.5  351.45  4984.3  348.77
  4991.3  348.31  4997.1  347.21  4999.9  346.71  5003.1  347.21  5021.8  351.28
  5080.9  355.71  5129.8  357.59  5161.6  362.18  5175.5  362.94  5198.5  368.12
  5204.8  371.72  5220.7  376.16    5248  381.58  5256.1  381.62  5281.2  385.86
#Mann= 4 ,-1 , 0
  4789.8     .16       0  4991.3     .12       0  4997.1     .07       0
  5003.1     .12       0
Bank Sta=4978.5,5021.8
XS Rating Curve= 0 ,0
Exp/Cntr=0.3,0.1

Type RM Length L Ch R = 1 ,171     ,0,0,0
BEGIN DESCRIPTION:
UNT 152 IN CACR 1.0
END DESCRIPTION:
XS GIS Cut Line= 4
      3703618.89     10698125.43      3703842.81     10698092.45
      3703912.25     10697969.19      3703894.89     10697778.19
#Sta/Elev= 30
  4721.5  367.78  4725.2  364.92  4753.8  361.87  4782.9  358.85  4813.2  354.68
  4894.1  350.37  4953.8   349.1  4961.9  347.07  4972.5  342.52  4975.2  342.02
  4978.5  342.52  4997.2  342.77  5013.1  344.12  5019.3  345.79  5065.2  345.67
  5072.3   346.8  5078.1  346.28  5091.3  347.14  5098.3  349.09  5118.4  349.48
  5138.5  351.36  5158.6  354.87  5176.7   362.3  5188.7  366.81  5208.8  371.86
  5218.8   372.9    5249  378.51    5259  379.24  5275.5  381.94  5281.1  382.26
#Mann= 6 ,-1 , 0
  4721.5     .16       0  4753.8     .12       0  4972.5     .07       0
  4978.5     .12       0  5176.7     .16       0  5275.5     .12       0
Bank Sta=4961.9,5065.2
XS Rating Curve= 0 ,0
Exp/Cntr=0.3,0.1

Chan Stop Cuts=-1
Use User Specified Reach Order=0
Composite Channel Slope=5