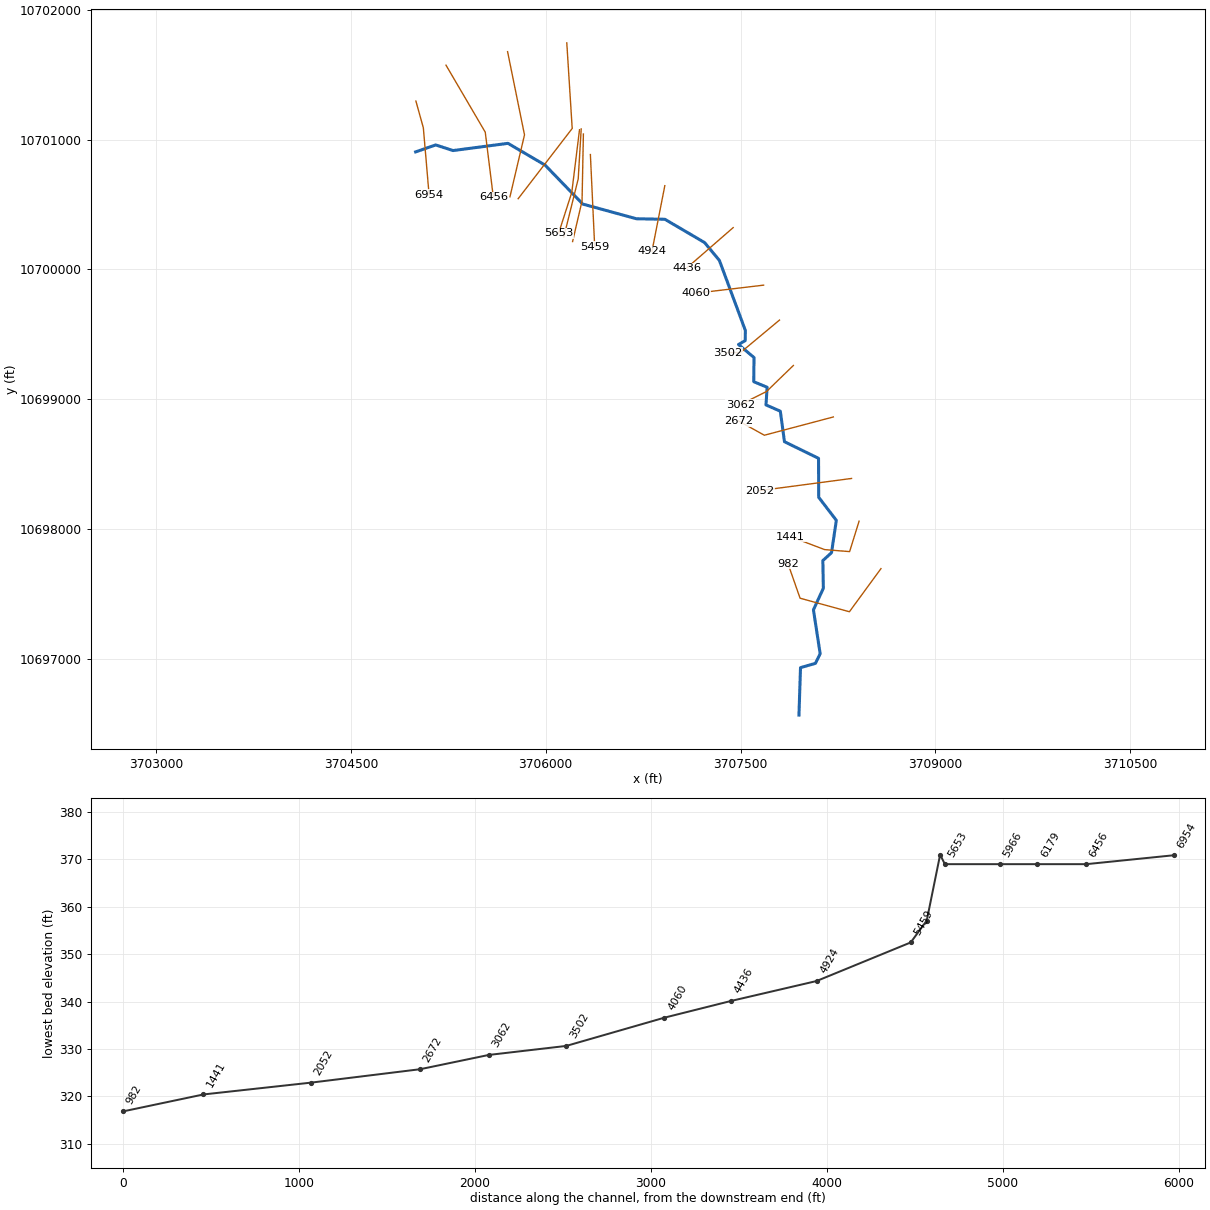
--- UNT 153 IN CACR.prj (project) ---

Proj Title=UNT 153 IN CACR Base Level Engineering
Current Plan=p01
Default Exp/Contr=0.3,0.1
English Units
Geom File=g01
Flow File=f01
Plan File=p01
BEGIN DESCRIPTION:
UNT 153 IN CACR
END DESCRIPTION:

--- UNT 153 IN CACR.p01 (plan) ---

Plan Title=Multiple Run
Short Identifier=Multiple
Geom File=g01
Flow File=f01
Subcritical Flow
K Sum by GR= 0
Std Step Tol= 0.01
Critical Tol= 0.01
Num of Std Step Trials= 20
Max Error Tol= 0.3
Flow Tol Ratio= 0.001
Split Flow NTrial= 30
Split Flow Tol= 0.02
Split Flow Ratio= 0.02
Log Output Level= 0
Friction Slope Method= 1
Unsteady Friction Slope Method= 2
Unsteady Bridges Friction Slope Method= 1
Parabolic Critical Depth
Global Vel Dist=  1 , 1 , 1
Global Log Level= 0
CheckData=True
Encroach Param= -1, 0, 0, 0
BEGIN DESCRIPTION:
Multiple Run
END DESCRIPTION:

--- UNT 153 IN CACR.f01 (steady flow) ---

Flow Title=Multiple
Number of Profiles=7
Profile Names=10-year,25-year,50-year,1pct_min,100-year,1pct_plu,500-year
River Rch & RM= UNT 153 IN CACR,Reach-1,6954
     430     575     694     616     833    1127    1204
Boundary for River Rch & Prof#=UNT 153 IN CACR,Reach-1,1
Up Type=0
Dn Type=3
Dn Slope=0.005
Boundary for River Rch & Prof#=UNT 153 IN CACR,Reach-1,2
Up Type=0
Dn Type=3
Dn Slope=0.005
Boundary for River Rch & Prof#=UNT 153 IN CACR,Reach-1,3
Up Type=0
Dn Type=3
Dn Slope=0.005
Boundary for River Rch & Prof#=UNT 153 IN CACR,Reach-1,4
Up Type=0
Dn Type=3
Dn Slope=0.005
Boundary for River Rch & Prof#=UNT 153 IN CACR,Reach-1,5
Up Type=0
Dn Type=3
Dn Slope=0.005
Boundary for River Rch & Prof#=UNT 153 IN CACR,Reach-1,6
Up Type=0
Dn Type=3
Dn Slope=0.005
Boundary for River Rch & Prof#=UNT 153 IN CACR,Reach-1,7
Up Type=0
Dn Type=3
Dn Slope=0.005

--- UNT 153 IN CACR.g01 (geometry) ---

Geom Title=Existing Conditions

River Reach=UNT 153 IN CACR,Reach-1
Reach XY= 30
      3704998.70     10700904.50      3705153.22     10700958.32
      3705286.90     10700914.92      3705709.64     10700970.48
      3705995.25     10700803.00      3706285.50     10700503.00
      3706698.50     10700390.00      3706917.50     10700386.00
      3707222.75     10700207.00      3707337.25     10700069.00
      3707537.00     10699530.00      3707535.75     10699452.00
      3707484.00     10699422.00      3707603.50     10699322.00
      3707601.50     10699136.00      3707704.50     10699093.00
      3707695.75     10698957.00      3707806.00     10698909.00
      3707838.00     10698674.00      3708100.25     10698546.00
      3708101.50     10698246.00      3708237.25     10698069.00
      3708200.25     10697820.00      3708133.50     10697759.00
      3708137.25     10697546.00      3708061.00     10697380.00
      3708112.75     10697042.00      3708076.00     10696968.00
      3707961.50     10696935.00      3707949.50     10696570.00

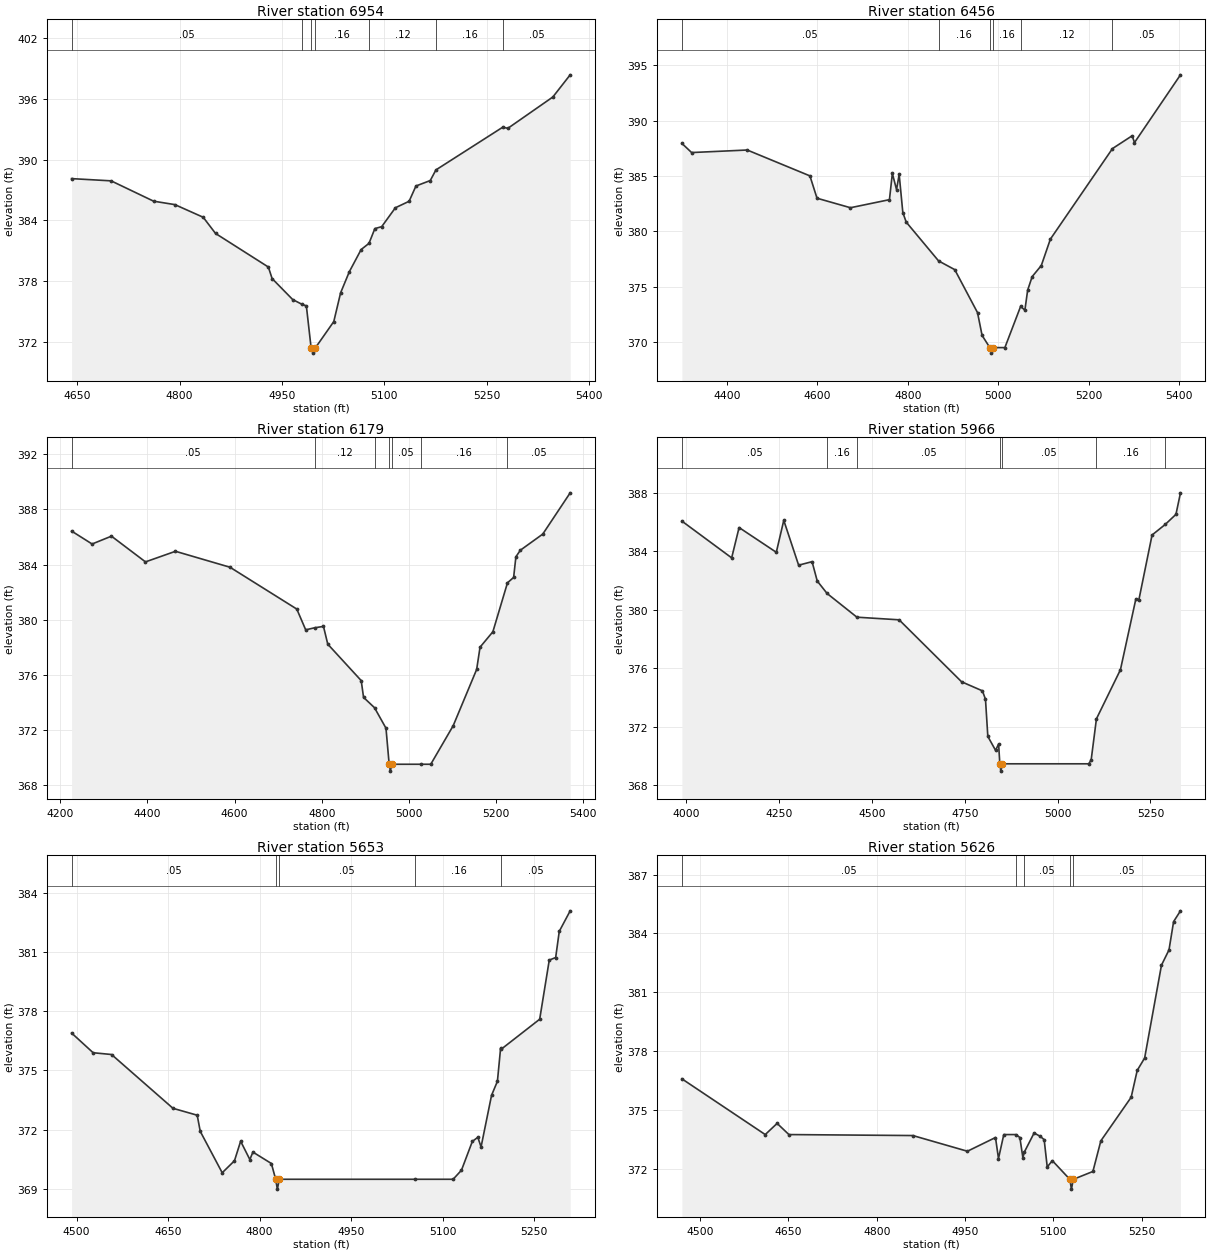
Type RM Length L Ch R = 1,6954,498,498,498
BEGIN DESCRIPTION:
UNT 153 IN CACR 10.0
END DESCRIPTION:
XS GIS Cut Line= 3
      3705000.96     10701295.99      3705058.25     10701090.27
      3705102.50     10700574.92
#Sta/Elev= 30
  4641.6  388.11  4699.5  387.89  4761.8  385.88  4793.0  385.54  4834.5  384.29
  4852.6  382.69  4930.0  379.37  4935.5  378.23  4965.6  376.16  4979.4  375.68
  4985.7  375.53  4992.7  371.36  4995.5  370.86  4998.7  371.36  5025.9  373.98
  5035.9  376.82  5048.7  378.91  5066.0  381.10  5077.5  381.71  5086.1  383.17
  5096.1  383.36  5116.2  385.23  5136.3  385.87  5146.3  387.38  5167.3  387.92
  5175.6  388.97  5273.7  393.20  5281.0  393.08  5347.0  396.18  5372.4  398.37
#Mann=7,-1,0
  4641.6    0.05       0  4979.4    0.16       0  4992.7    0.07       0
  4998.7    0.16       0  5077.5    0.12       0  5175.6    0.16       0
  5273.7    0.05       0
Bank Sta=4992.7,4998.7
Exp/Cntr=0.3,0.1

Type RM Length L Ch R = 1,6456,277,277,277
BEGIN DESCRIPTION:
Mapping XS f922e4b5
END DESCRIPTION:
XS GIS Cut Line= 3
      3705232.75     10701572.00      3705534.82     10701056.41
      3705597.23     10700554.53
#Sta/Elev= 30
  4300.1  387.95  4321.6  387.12  4444.7  387.35  4583.4  385.01  4599.1  382.99
  4673.1  382.13  4759.4  382.86  4765.8  385.23  4775.1  383.77  4780.9  385.14
  4789.0  381.69  4796.5  380.83  4868.1  377.32  4903.9  376.53  4954.3  372.64
  4964.4  370.58  4981.5  369.48  4984.3  368.98  4987.5  369.48  5014.8  369.48
  5049.6  373.20  5059.1  372.87  5065.2  374.67  5075.2  375.90  5095.4  376.90
  5115.5  379.29  5252.9  387.48  5296.5  388.64  5301.6  388.02  5403.4  394.15
#Mann=6,-1,0
  4300.1    0.05       0  4868.1    0.16       0  4981.5    0.07       0
  4987.5    0.16       0  5049.6    0.12       0  5252.9    0.05       0
Bank Sta=4981.5,4987.5
Exp/Cntr=0.3,0.1

Type RM Length L Ch R = 1,6179,213,213,213
BEGIN DESCRIPTION:
Mapping XS ced45dcb
END DESCRIPTION:
XS GIS Cut Line= 3
      3705706.69     10701676.21      3705836.90     10701035.58
      3705724.91     10700558.99
#Sta/Elev= 30
  4226.4  386.43  4273.4  385.49  4317.8  386.06  4395.8  384.19  4464.6  384.96
  4589.7  383.80  4742.8  380.76  4763.2  379.25  4783.7  379.40  4804.0  379.50
  4813.8  378.21  4890.5  375.56  4895.9  374.34  4921.0  373.59  4947.3  372.10
  4954.6  369.48  4957.3  368.98  4960.6  369.48  5026.5  369.48  5050.0  369.48
  5101.4  372.28  5155.2  376.37  5163.0  377.99  5192.4  379.11  5225.9  382.67
  5240.0  383.06  5245.2  384.56  5255.5  385.04  5306.8  386.21  5369.7  389.21
#Mann=7,-1,0
  4226.4    0.05       0  4783.7    0.12       0  4921.0    0.05       0
  4954.6   0.035       0  4960.6    0.05       0  5026.5    0.16       0
  5225.9    0.05       0
Bank Sta=4954.6,4960.6
Exp/Cntr=0.3,0.1

Type RM Length L Ch R = 1,5966,313,313,313
BEGIN DESCRIPTION:
Mapping XS 7f550bca
END DESCRIPTION:
XS GIS Cut Line= 3
      3706162.42     10701743.91      3706204.09     10701085.06
      3705788.12     10700544.30
#Sta/Elev= 30
  3988.4  386.05  4122.4  383.54  4142.4  385.61  4242.6  383.92  4262.7  386.10
  4302.7  383.04  4338.9  383.28  4352.8  381.96  4379.3  381.11  4459.6  379.49
  4573.3  379.31  4741.4  375.08  4797.6  374.46  4805.8  373.88  4812.1  371.35
  4832.9  370.40  4841.1  370.83  4844.4  369.48  4847.1  368.98  4850.4  369.48
  5083.7  369.48  5090.3  369.74  5104.5  372.55  5169.1  375.90  5210.7  380.74
  5218.9  380.69  5254.3  385.10  5289.7  385.82  5318.6  386.51  5330.8  387.98
#Mann=7,-1,0
  3988.4    0.05       0  4379.3    0.16       0  4459.6    0.05       0
  4844.4   0.033       0  4850.4    0.05       0  5104.5    0.16       0
  5289.7    0.05       0
Bank Sta=4844.4,4850.4
Exp/Cntr=0.3,0.1

Type RM Length L Ch R = 1,5653,27,27,27
BEGIN DESCRIPTION:
Mapping XS 48db9405
END DESCRIPTION:
XS GIS Cut Line= 3
      3706260.32     10701075.19      3706200.88     10700592.57
      3706099.32     10700277.50
#Sta/Elev= 30
  4491.7  376.90  4527.0  375.90  4557.2  375.81  4657.9  373.08  4697.6  372.73
  4702.6  371.91  4738.6  369.81  4758.7  370.42  4768.8  371.41  4783.9  370.48
  4788.9  370.86  4819.2  370.28  4826.2  369.48  4829.0  368.98  4832.2  369.48
  5055.1  369.48  5117.1  369.48  5130.8  369.94  5148.6  371.40  5157.6  371.61
  5162.9  371.12  5180.1  373.74  5189.7  374.45  5194.9  376.12  5196.4  376.09
  5259.0  377.60  5274.7  380.60  5285.2  380.73  5291.1  382.06  5309.0  383.10
#Mann=5,-1,0
  4491.7    0.05       0  4826.2   0.033       0  4832.2    0.05       0
  5055.1    0.16       0  5196.4    0.05       0
Bank Sta=4826.2,4832.2
Exp/Cntr=0.3,0.1

Type RM Length L Ch R = 1,5626,76,76,76
BEGIN DESCRIPTION:
Mapping XS 0e771928
END DESCRIPTION:
XS GIS Cut Line= 3
      3706273.33     10701081.69      3706250.36     10700696.74
      3706139.25     10700248.85
#Sta/Elev= 30
  4469.0  376.59  4610.6  373.75  4630.8  374.32  4650.8  373.75  4861.4  373.70
  4954.1  372.90  5001.8  373.60  5006.9  372.53  5015.9  373.75  5036.5  373.75
  5043.2  373.60  5048.3  372.58  5051.0  372.87  5067.4  373.83  5077.8  373.66
  5084.5  373.49  5089.7  372.10  5098.4  372.42  5128.1  371.47  5130.8  370.97
  5134.1  371.47  5167.3  371.87  5180.8  373.43  5232.3  375.65  5242.6  377.02
  5255.2  377.65  5283.8  382.38  5296.6  383.16  5304.4  384.60  5316.1  385.15
#Mann=5,-1,0
  4469.0    0.05       0  5036.5    0.16       0  5051.0    0.05       0
  5128.1    0.03       0  5134.1    0.05       0
Bank Sta=5128.1,5134.1
Exp/Cntr=0.3,0.1

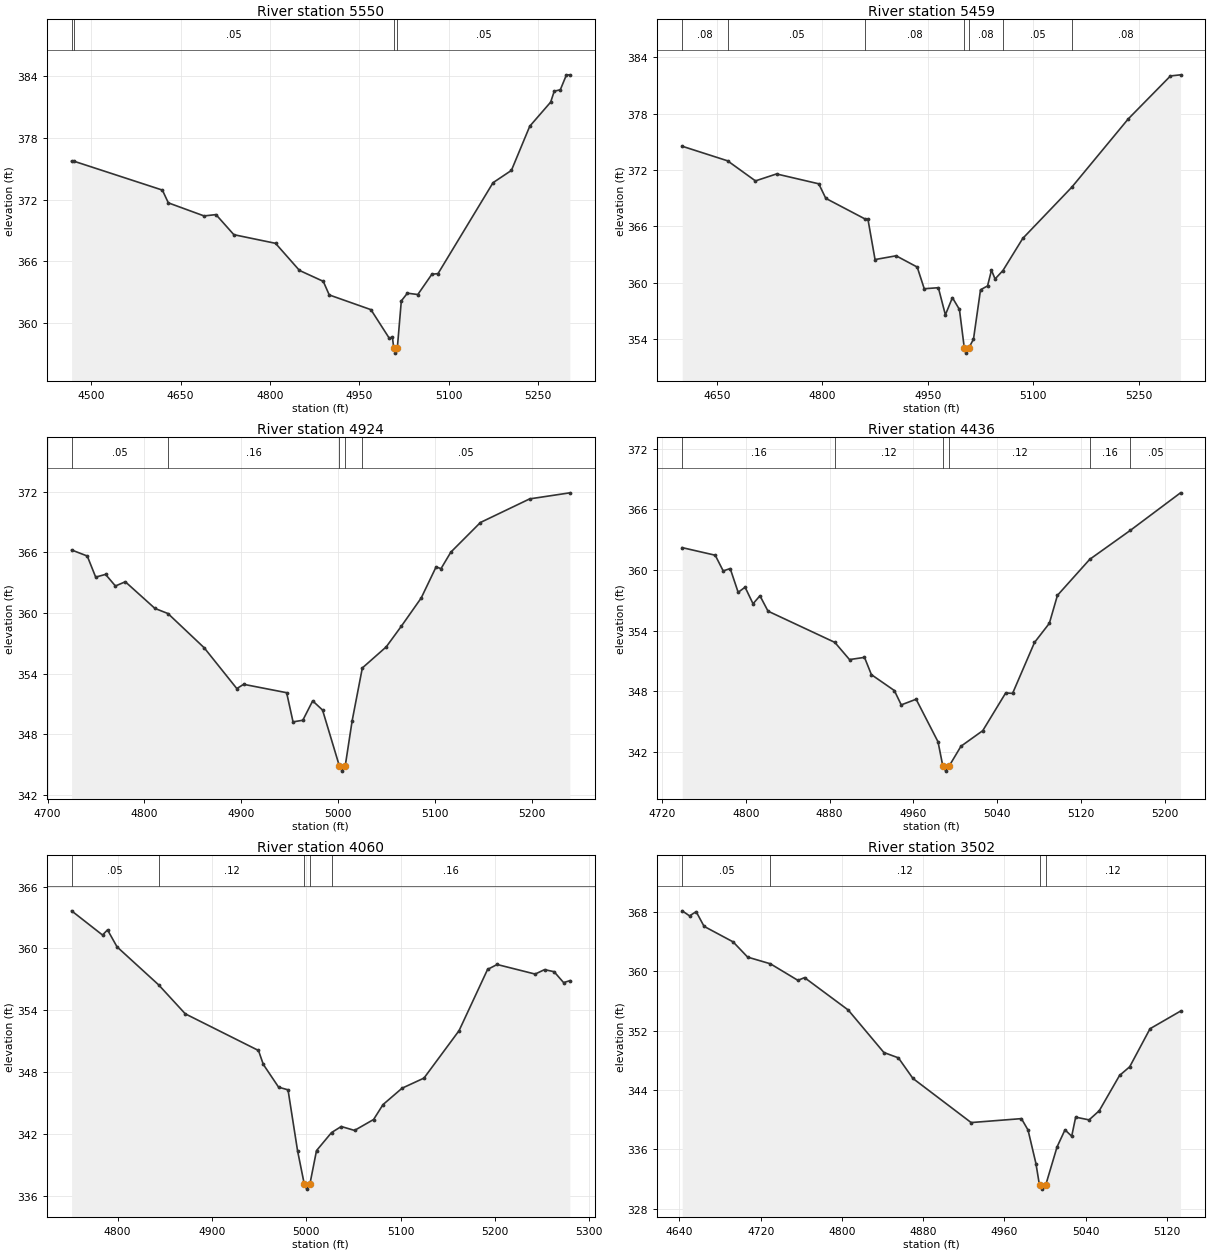
Type RM Length L Ch R = 1,5550,91,91,91
BEGIN DESCRIPTION:
Mapping XS b3e09c53
END DESCRIPTION:
XS GIS Cut Line= 3
      3706290.26     10701042.57      3706279.87     10700526.60
      3706207.08     10700214.65
#Sta/Elev= 30
  4467.0  375.72  4471.6  375.71  4619.4  372.92  4629.4  371.68  4689.4  370.41
  4709.4  370.54  4739.4  368.59  4809.4  367.75  4849.5  365.12  4889.5  364.06
  4899.5  362.74  4969.5  361.31  4999.9  358.57  5005.6  358.61  5007.8  357.59
  5010.5  357.09  5013.8  357.59  5020.5  362.16  5030.7  362.91  5048.2  362.78
  5071.8  364.75  5082.1  364.81  5174.5  373.64  5205.3  374.83  5236.1  379.12
  5271.2  381.46  5277.2  382.52  5287.4  382.66  5297.7  384.11  5303.4  384.10
#Mann=4,-1,0
  4467.0    0.08       0  4471.6    0.05       0  5007.8    0.03       0
  5013.8    0.05       0
Bank Sta=5007.8,5013.8
Exp/Cntr=0.3,0.1

Type RM Length L Ch R = 1,5459,535,535,535
BEGIN DESCRIPTION:
Mapping XS 98d162e7
END DESCRIPTION:
XS GIS Cut Line= 2
      3706344.11     10700884.25      3706377.09     10700175.91
#Sta/Elev= 30
  4600.4  374.52  4664.9  372.97  4704.6  370.83  4734.6  371.57  4794.7  370.52
  4804.7  368.97  4860.9  366.76  4864.7  366.74  4874.8  362.45  4904.8  362.85
  4934.8  361.65  4944.8  359.34  4964.9  359.45  4974.9  356.56  4984.9  358.39
  4994.9  357.13  5001.9  352.98  5004.6  352.48  5007.9  352.98  5014.9  353.97
  5024.9  359.23  5034.9  359.64  5040.5  361.32  5045.6  360.38  5056.8  361.28
  5085.0  364.70  5154.8  370.16  5235.1  377.43  5295.2  382.01  5309.5  382.13
#Mann=7,-1,0
  4600.4    0.08       0  4664.9    0.05       0  4860.9    0.08       0
  5001.9    0.07       0  5007.9    0.08       0  5056.8    0.05       0
  5154.8    0.08       0
Bank Sta=5001.9,5007.9
Exp/Cntr=0.3,0.1

Type RM Length L Ch R = 1,4924,488,488,488
BEGIN DESCRIPTION:
Mapping XS c5306bec
END DESCRIPTION:
XS GIS Cut Line= 2
      3706917.03     10700644.67      3706818.07     10700139.47
#Sta/Elev= 30
  4724.8  366.25  4741.0  365.65  4749.7  363.56  4759.9  363.83  4770.1  362.68
  4780.3  363.10  4810.9  360.46  4824.4  359.95  4861.8  356.56  4895.5  352.52
  4902.6  352.94  4947.0  352.11  4953.6  349.22  4963.7  349.38  4973.9  351.30
  4984.1  350.39  5001.5  344.84  5004.3  344.34  5007.5  344.84  5014.7  349.34
  5025.2  354.56  5049.9  356.65  5065.6  358.71  5086.0  361.49  5101.4  364.57
  5106.5  364.40  5116.6  366.03  5147.2  368.97  5198.1  371.31  5239.6  371.91
#Mann=5,-1,0
  4724.8    0.05       0  4824.4    0.16       0  5001.5    0.07       0
  5007.5    0.16       0  5025.2    0.05       0
Bank Sta=5001.5,5007.5
Exp/Cntr=0.3,0.1

Type RM Length L Ch R = 1,4436,376,376,376
BEGIN DESCRIPTION:
Mapping XS 8ae8cfb2
END DESCRIPTION:
XS GIS Cut Line= 2
      3707443.09     10700321.76      3707084.13     10700009.62
#Sta/Elev= 30
  4739.4  362.22  4770.9  361.47  4778.5  359.92  4785.2  360.15  4792.8  357.80
  4799.4  358.31  4807.0  356.67  4813.6  357.46  4821.3  355.94  4885.1  352.85
  4899.1  351.15  4913.4  351.37  4920.0  349.66  4941.9  348.09  4948.5  346.67
  4962.7  347.23  4983.6  343.02  4988.2  340.62  4991.0  340.12  4994.2  340.62
  5005.5  342.58  5026.3  344.12  5048.2  347.85  5054.8  347.81  5075.7  352.84
  5089.9  354.74  5097.6  357.50  5128.4  361.06  5167.1  363.92  5215.1  367.64
#Mann=6,-1,0
  4739.4    0.16       0  4885.1    0.12       0  4988.2    0.07       0
  4994.2    0.12       0  5128.4    0.16       0  5167.1    0.05       0
Bank Sta=4988.2,4994.2
Exp/Cntr=0.3,0.1

Type RM Length L Ch R = 1,4060,558,558,558
BEGIN DESCRIPTION:
Mapping XS 30b7dfa5
END DESCRIPTION:
XS GIS Cut Line= 2
      3707677.44     10699879.03      3707153.03     10699816.72
#Sta/Elev= 30
  4751.2  363.64  4784.0  361.29  4789.3  361.79  4799.4  360.14  4843.5  356.45
  4871.7  353.64  4949.3  350.08  4954.4  348.73  4970.6  346.52  4980.6  346.26
  4990.7  340.35  4997.8  337.12  5000.5  336.62  5003.8  337.12  5010.8  340.36
  5026.7  342.11  5037.0  342.70  5051.1  342.32  5071.3  343.38  5081.3  344.83
  5101.5  346.42  5124.7  347.40  5161.9  352.01  5192.1  357.95  5202.2  358.43
  5242.5  357.50  5252.5  357.93  5262.6  357.73  5272.7  356.67  5279.3  356.86
#Mann=5,-1,0
  4751.2    0.05       0  4843.5    0.12       0  4997.8    0.07       0
  5003.8    0.12       0  5026.7    0.16       0
Bank Sta=4997.8,5003.8
Exp/Cntr=0.3,0.1

Type RM Length L Ch R = 1,3502,440,440,440
BEGIN DESCRIPTION:
UNT 153 IN CACR 5.0
END DESCRIPTION:
XS GIS Cut Line= 3
      3707799.61     10699610.19      3707499.61     10699360.19
      3707399.62     10699360.19
#Sta/Elev= 30
  4642.8  368.12  4650.0  367.44  4656.5  368.01  4664.3  366.03  4692.9  363.94
  4707.2  361.89  4729.6  360.99  4756.7  358.76  4763.2  359.13  4806.2  354.77
  4841.3  349.05  4855.6  348.33  4869.9  345.56  4927.2  339.62  4976.7  340.15
  4983.2  338.62  4991.0  334.10  4994.5  331.16  4997.3  330.66  5000.5  331.16
  5011.8  336.35  5019.6  338.64  5026.2  337.78  5030.1  340.35  5043.3  339.98
  5053.3  341.21  5073.3  345.96  5083.3  347.13  5103.3  352.25  5133.3  354.62
#Mann=4,-1,0
  4642.8    0.05       0  4729.6    0.12       0  4994.5    0.07       0
  5000.5    0.12       0
Bank Sta=4994.5,5000.5
Exp/Cntr=0.3,0.1

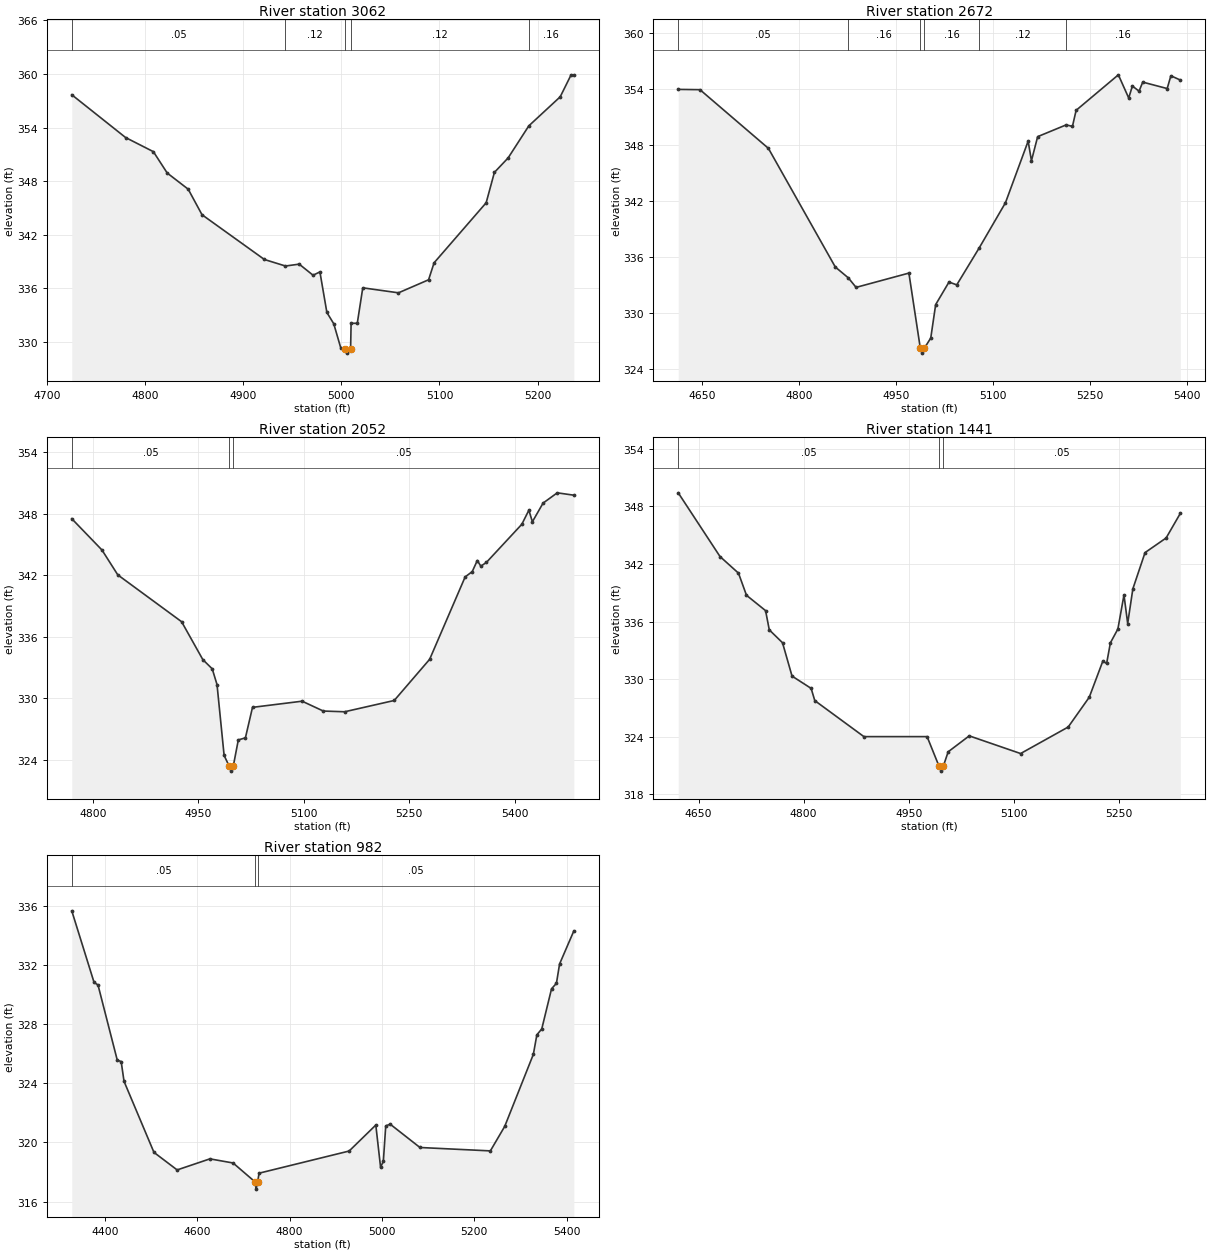
Type RM Length L Ch R = 1,3062,390,390,390
BEGIN DESCRIPTION:
UNT 153 IN CACR 4.0
END DESCRIPTION:
XS GIS Cut Line= 3
      3707906.57     10699260.94      3707699.61     10699060.19
      3707499.64     10698960.21
#Sta/Elev= 30
  4725.1  357.68  4780.0  352.89  4808.3  351.31  4822.4  348.92  4843.8  347.11
  4857.9  344.25  4921.5  339.24  4943.0  338.51  4957.0  338.72  4971.1  337.48
  4978.1  337.85  4985.2  333.31  4992.2  332.05  4999.4  329.33  5003.4  329.26
  5006.1  328.76  5009.4  329.26  5009.9  332.10  5016.2  332.10  5021.8  336.07
  5058.2  335.51  5088.9  336.97  5094.5  338.87  5147.6  345.59  5156.0  348.99
  5170.0  350.61  5191.1  354.20  5223.1  357.45  5234.2  359.91  5237.0  359.91
#Mann=5,-1,0
  4725.1    0.05       0  4943.0    0.12       0  5003.4    0.07       0
  5009.4    0.12       0  5191.1    0.16       0
Bank Sta=5003.4,5009.4
Exp/Cntr=0.3,0.1

Type RM Length L Ch R = 1,2672,620,620,620
BEGIN DESCRIPTION:
UNT 153 IN CACR 3.0
END DESCRIPTION:
XS GIS Cut Line= 3
      3708214.41     10698864.50      3707683.14     10698723.87
      3707484.77     10698833.87
#Sta/Elev= 30
  4613.7  353.99  4647.3  353.96  4753.1  347.68  4856.6  334.97  4876.7  333.81
  4888.7  332.79  4970.4  334.32  4988.1  326.25  4990.8  325.75  4994.1  326.25
  5004.2  327.37  5011.8  330.95  5032.4  333.36  5044.4  333.06  5079.4  337.05
  5119.7  341.85  5154.8  348.45  5159.9  346.35  5169.5  348.93  5213.6  350.19
  5223.3  350.03  5229.0  351.75  5294.3  355.55  5310.3  353.07  5316.0  354.35
  5326.3  353.80  5332.0  354.77  5369.8  354.08  5375.5  355.45  5390.1  354.99
#Mann=6,-1,0
  4613.7    0.05       0  4876.7    0.16       0  4988.1    0.07       0
  4994.1    0.16       0  5079.4    0.12       0  5213.6    0.16       0
Bank Sta=4988.1,4994.1
Exp/Cntr=0.3,0.1

Type RM Length L Ch R = 1,2052,611,611,611
BEGIN DESCRIPTION:
Mapping XS a4417d32
END DESCRIPTION:
XS GIS Cut Line= 2
      3708354.54     10698391.18      3707646.22     10698297.44
#Sta/Elev= 30
  4769.9  347.50  4812.9  344.45  4835.4  342.03  4926.2  337.47  4956.4  333.78
  4969.8  332.88  4976.6  331.35  4986.7  324.45  4993.8  323.42  4996.5  322.92
  4999.8  323.42  5006.9  325.96  5017.0  326.16  5027.1  329.13  5097.7  329.73
  5127.9  328.77  5158.2  328.70  5228.8  329.80  5279.2  333.81  5329.7  341.83
  5339.8  342.35  5347.0  343.43  5352.0  342.88  5359.9  343.24  5410.4  346.96
  5420.4  348.33  5425.4  347.20  5440.6  349.02  5460.8  350.02  5484.4  349.79
#Mann=3,-1,0
  4769.9    0.05       0  4993.8    0.03       0  4999.8    0.05       0
Bank Sta=4993.8,4999.8
Exp/Cntr=0.3,0.1

Type RM Length L Ch R = 1,1441,459,459,459
BEGIN DESCRIPTION:
UNT 153 IN CACR 1.0
END DESCRIPTION:
XS GIS Cut Line= 4
      3708412.30     10698062.42      3708339.39     10697828.04
      3708146.68     10697843.66      3707886.25     10697942.62
#Sta/Elev= 30
  4620.8  349.39  4680.5  342.76  4706.9  341.03  4718.3  338.73  4745.6  337.13
  4750.9  335.13  4769.8  333.79  4783.4  330.32  4810.7  329.04  4815.9  327.77
  4886.1  324.02  4976.4  324.02  4993.5  320.93  4996.2  320.43  4999.5  320.93
  5006.5  322.44  5036.6  324.10  5110.0  322.26  5178.0  325.02  5208.1  328.12
  5227.5  331.88  5232.9  331.63  5238.3  333.78  5249.0  335.22  5257.7  338.76
  5263.0  335.79  5270.4  339.40  5287.8  343.17  5317.9  344.69  5338.2  347.25
#Mann=3,-1,0
  4620.8    0.05       0  4993.5    0.03       0  4999.5    0.05       0
Bank Sta=4993.5,4999.5
Exp/Cntr=0.3,0.1

Type RM Length L Ch R = 1,982,0,0,0
BEGIN DESCRIPTION:
Mapping XS e6fb905a
END DESCRIPTION:
XS GIS Cut Line= 4
      3708580.86     10697697.33      3708337.81     10697365.31
      3707958.04     10697469.47      3707864.93     10697735.79
#Sta/Elev= 30
  4328.4  335.69  4376.7  330.84  4385.2  330.67  4426.9  325.58  4435.4  325.48
  4441.6  324.14  4506.4  319.33  4556.6  318.14  4627.6  318.89  4677.8  318.61
  4725.0  317.34  4727.7  316.84  4731.0  317.34  4734.1  317.92  4929.1  319.42
  4986.9  321.18  4997.2  318.33  5003.2  318.72  5008.4  321.12  5018.0  321.24
  5082.5  319.66  5235.0  319.43  5266.1  321.09  5328.1  325.97  5335.7  327.29
  5346.3  327.69  5367.5  330.41  5378.1  330.78  5384.9  332.09  5415.8  334.33
#Mann=3,-1,0
  4328.4    0.05       0  4725.0    0.03       0  4731.0    0.05       0
Bank Sta=4725,4731
Exp/Cntr=0.3,0.1

Chan Stop Cuts=-1