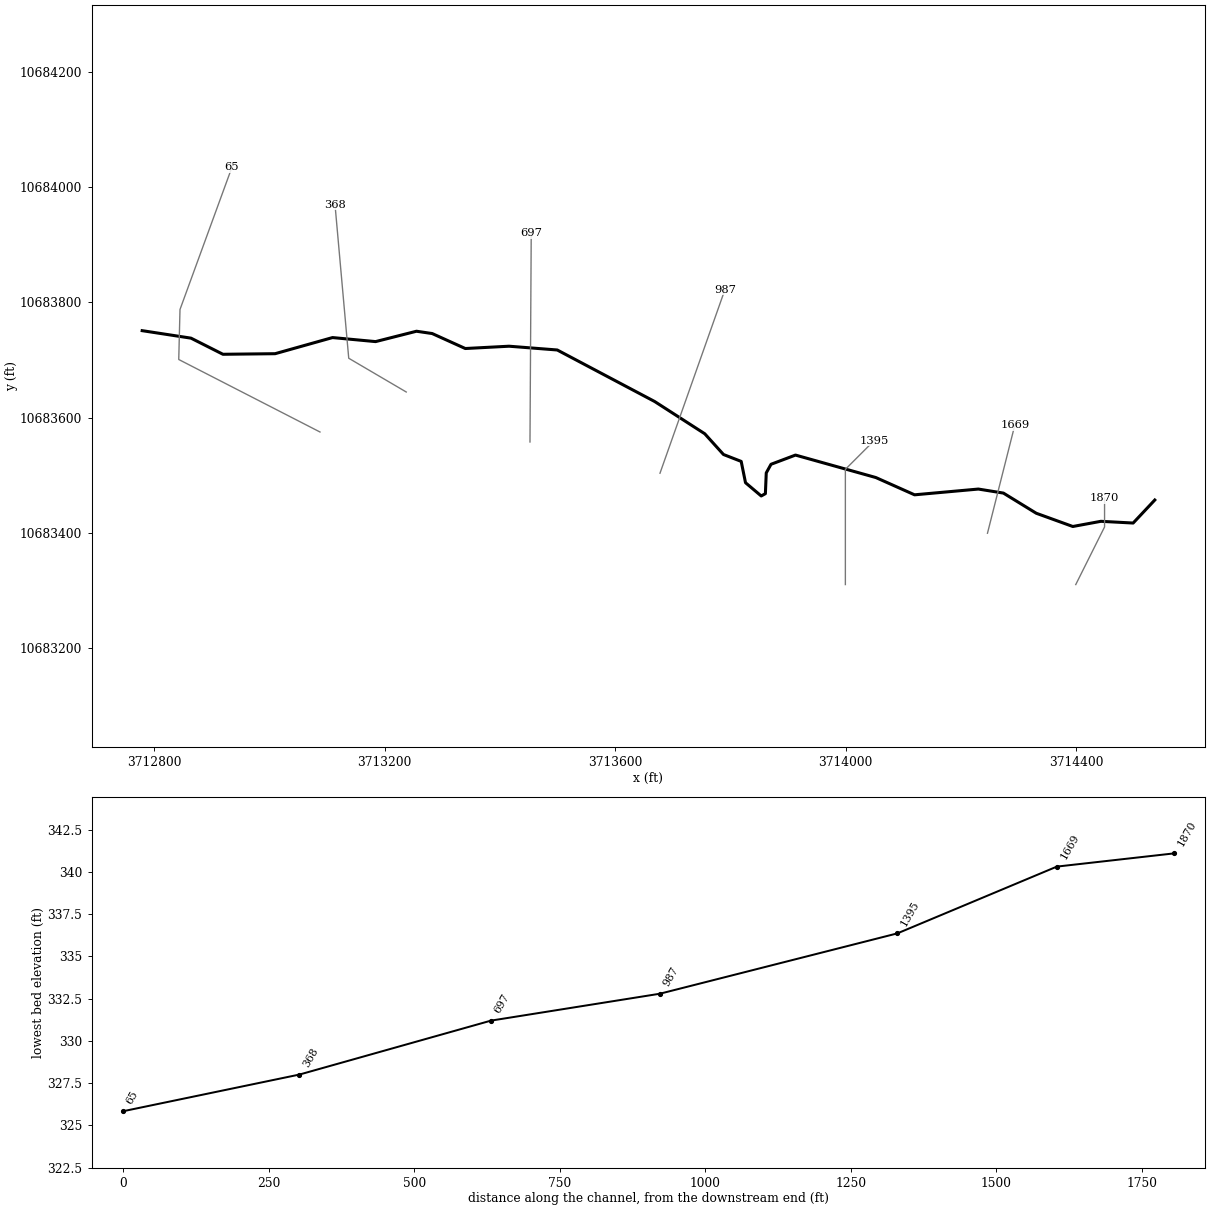
--- UNT 155 IN CACR.prj (project) ---

Proj Title=UNT 155 IN CACR Base Level Engineering
Current Plan=p01
Default Exp/Contr=0.3,0.1
English Units
Geom File=g01
Flow File=f01
Plan File=p01
BEGIN DESCRIPTION:
UNT 155 IN CACR
END DESCRIPTION:

--- UNT 155 IN CACR.p01 (plan) ---

Plan Title=Multiple Run
Short Identifier=Multiple
Geom File=g01
Flow File=f01
Subcritical Flow
K Sum by GR= 0
Std Step Tol= 0.01
Critical Tol= 0.01
Num of Std Step Trials= 20
Max Error Tol= 0.3
Flow Tol Ratio= 0.001
Split Flow NTrial= 30
Split Flow Tol= 0.02
Split Flow Ratio= 0.02
Log Output Level= 0
Friction Slope Method= 1
Unsteady Friction Slope Method= 2
Unsteady Bridges Friction Slope Method= 1
Parabolic Critical Depth
Global Vel Dist=  1 , 1 , 1
Global Log Level= 0
CheckData=True
Encroach Param= -1, 0, 0, 0
BEGIN DESCRIPTION:
Multiple Run
END DESCRIPTION:

--- UNT 155 IN CACR.f01 (steady flow) ---

Flow Title=Multiple
Number of Profiles=7
Profile Names=10-year,25-year,50-year,1pct_min,100-year,1pct_plu,500-year
River Rch & RM= UNT 155 IN CACR,Reach-1,1870
     462     620     749     666     901    1218    1308
Boundary for River Rch & Prof#=UNT 155 IN CACR,Reach-1,1
Up Type=0
Dn Type=3
Dn Slope=0.005
Boundary for River Rch & Prof#=UNT 155 IN CACR,Reach-1,2
Up Type=0
Dn Type=3
Dn Slope=0.005
Boundary for River Rch & Prof#=UNT 155 IN CACR,Reach-1,3
Up Type=0
Dn Type=3
Dn Slope=0.005
Boundary for River Rch & Prof#=UNT 155 IN CACR,Reach-1,4
Up Type=0
Dn Type=3
Dn Slope=0.005
Boundary for River Rch & Prof#=UNT 155 IN CACR,Reach-1,5
Up Type=0
Dn Type=3
Dn Slope=0.005
Boundary for River Rch & Prof#=UNT 155 IN CACR,Reach-1,6
Up Type=0
Dn Type=3
Dn Slope=0.005
Boundary for River Rch & Prof#=UNT 155 IN CACR,Reach-1,7
Up Type=0
Dn Type=3
Dn Slope=0.005

--- UNT 155 IN CACR.g01 (geometry) ---

Geom Title=Existing Conditions

River Reach=UNT 155 IN CACR,Reach-1
Reach XY= 30
      3714536.81     10683456.97      3714499.25     10683417.00
      3714443.25     10683420.00      3714394.50     10683411.00
      3714331.00     10683434.00      3714274.00     10683469.00
      3714230.50     10683476.00      3714119.75     10683466.00
      3714052.50     10683496.00      3713913.00     10683535.00
      3713870.50     10683519.00      3713862.25     10683504.00
      3713860.75     10683468.00      3713853.50     10683464.00
      3713826.25     10683487.00      3713818.75     10683524.00
      3713788.00     10683536.00      3713755.50     10683572.00
      3713668.50     10683628.00      3713499.38     10683717.45
      3713415.75     10683724.00      3713339.75     10683720.00
      3713282.25     10683746.00      3713255.00     10683750.00
      3713184.00     10683732.00      3713109.25     10683739.00
      3713009.50     10683711.00      3712919.00     10683710.00
      3712863.50     10683738.00      3712778.75     10683751.00

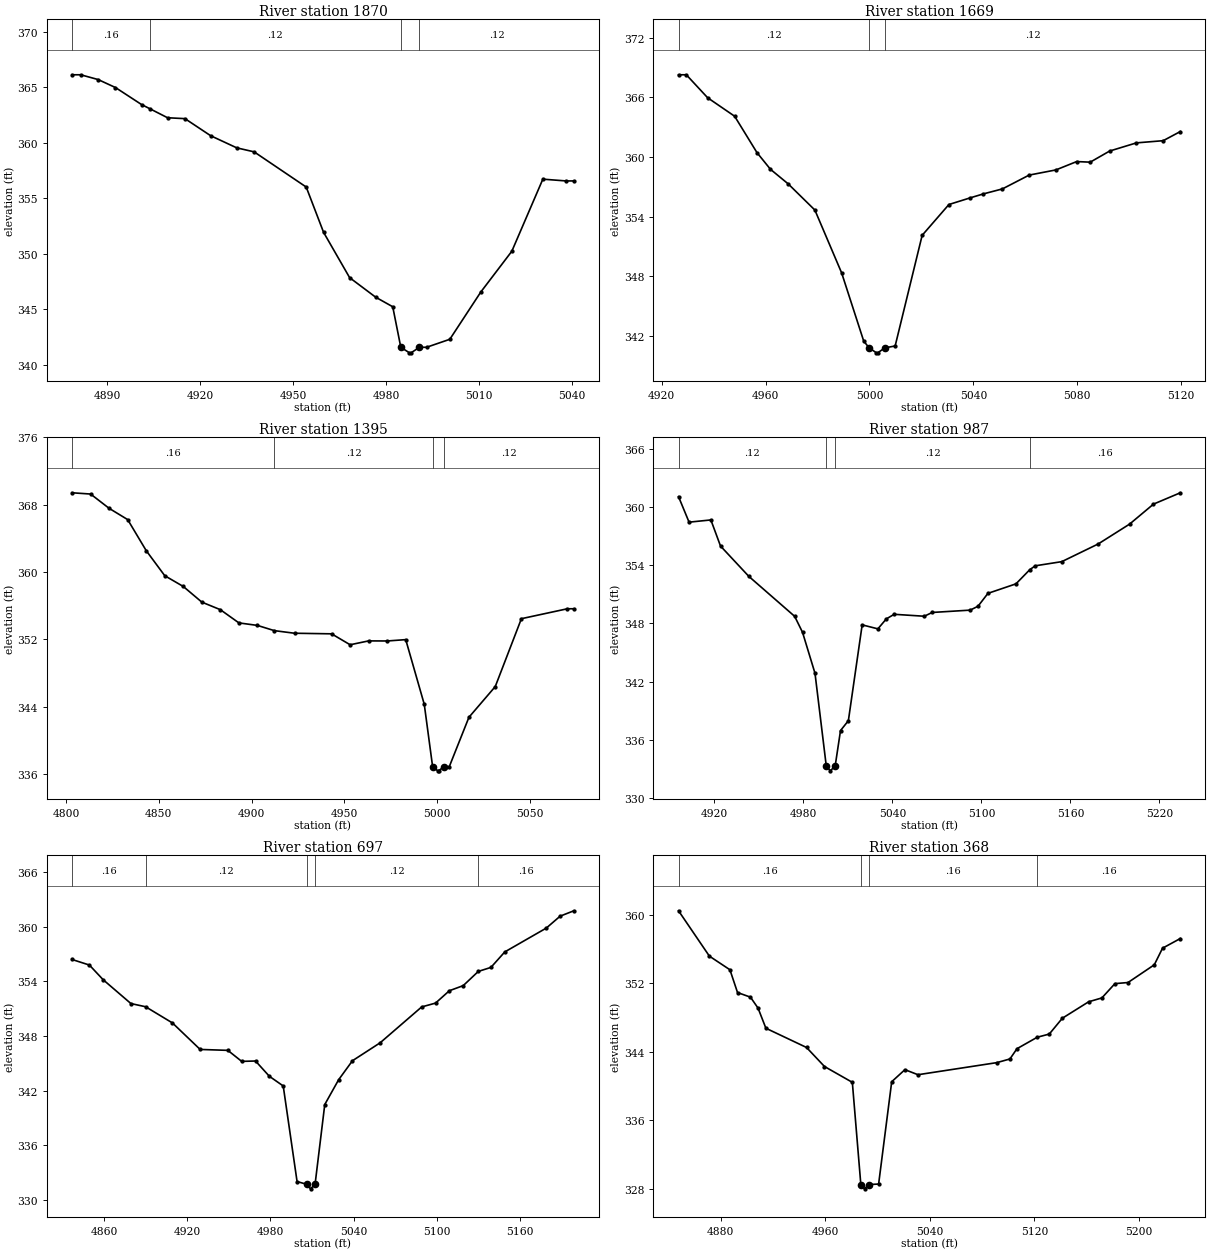
Type RM Length L Ch R = 1,1870,201,201,201
BEGIN DESCRIPTION:
UNT 155 IN CACR 4.0
END DESCRIPTION:
XS GIS Cut Line= 3
      3714399.60     10683310.17      3714449.61     10683410.19
      3714449.61     10683460.16
#Sta/Elev= 27
  4878.7  366.13  4881.5  366.13  4887.1  365.70  4892.7  364.98  4901.1  363.45
  4903.8  363.07  4909.5  362.26  4915.1  362.18  4923.4  360.64  4931.8  359.55
  4937.4  359.19  4954.2  356.02  4959.8  351.94  4968.2  347.86  4976.6  346.10
  4982.1  345.24  4984.7  341.59  4987.5  341.09  4988.0  341.09  4990.7  341.59
  4993.0  341.59  5000.5  342.31  5010.5  346.57  5020.5  350.24  5030.5  356.73
  5038.0  356.57  5040.5  356.57
#Mann=4,-1,0
  4878.7    0.16       0  4903.8    0.12       0  4984.7    0.07       0
  4990.7    0.12       0
Bank Sta=4984.7,4990.7
Exp/Cntr=0.3,0.1

Type RM Length L Ch R = 1,1669,274,274,274
BEGIN DESCRIPTION:
Mapping XS ba62c0e5
END DESCRIPTION:
XS GIS Cut Line= 2
      3714246.33     10683399.30      3714293.69     10683586.60
#Sta/Elev= 28
  4926.5  368.28  4929.5  368.28  4937.7  365.97  4948.1  364.11  4956.7  360.45
  4961.9  358.77  4968.7  357.31  4979.0  354.67  4989.3  348.35  4997.8  341.49
  4999.9  340.81  5002.7  340.31  5003.2  340.31  5005.9  340.81  5009.9  341.00
  5020.3  352.13  5030.6  355.23  5038.8  355.90  5043.9  356.30  5051.2  356.80
  5061.5  358.19  5071.8  358.71  5079.8  359.55  5085.0  359.49  5092.5  360.61
  5102.8  361.43  5113.1  361.65  5119.7  362.57
#Mann=3,-1,0
  4926.5    0.12       0  4999.9    0.07       0  5005.9    0.12       0
Bank Sta=4999.9,5005.9
Exp/Cntr=0.3,0.1

Type RM Length L Ch R = 1,1395,408,408,408
BEGIN DESCRIPTION:
UNT 155 IN CACR 3.0
END DESCRIPTION:
XS GIS Cut Line= 3
      3713999.61     10683310.18      3713999.61     10683510.19
      3714049.60     10683560.18
#Sta/Elev= 29
  4803.2  369.42  4813.2  369.27  4823.2  367.57  4833.2  366.23  4843.2  362.54
  4853.2  359.56  4863.2  358.28  4873.2  356.42  4883.2  355.52  4893.2  353.95
  4903.2  353.65  4912.3  353.03  4923.2  352.72  4943.2  352.65  4953.2  351.35
  4963.2  351.81  4973.2  351.80  4983.2  351.96  4993.2  344.27  4997.7  336.86
  5000.5  336.36  5001.0  336.36  5003.7  336.86  5006.7  336.86  5017.3  342.73
  5031.5  346.38  5045.6  354.45  5070.4  355.63  5073.9  355.63
#Mann=4,-1,0
  4803.2    0.16       0  4912.3    0.12       0  4997.7    0.07       0
  5003.7    0.12       0
Bank Sta=4997.7,5003.7
Exp/Cntr=0.3,0.1

Type RM Length L Ch R = 1,987,290,290,290
BEGIN DESCRIPTION:
Mapping XS 810ef323
END DESCRIPTION:
XS GIS Cut Line= 2
      3713677.76     10683503.49      3713790.58     10683822.42
#Sta/Elev= 30
  4895.8  361.06  4902.9  358.43  4917.6  358.66  4924.1  355.97  4943.2  352.84
  4974.1  348.72  4979.4  347.07  4987.8  342.85  4995.4  333.29  4998.1  332.79
  5001.4  333.29  5005.0  336.94  5010.3  337.96  5019.6  347.84  5030.2  347.43
  5035.9  348.46  5041.2  348.93  5061.5  348.73  5066.8  349.12  5092.4  349.36
  5097.7  349.76  5104.4  351.09  5123.3  352.07  5132.6  353.53  5136.3  353.93
  5154.2  354.36  5178.7  356.18  5199.9  358.23  5216.0  360.29  5234.1  361.46
#Mann=4,-1,0
  4895.8    0.12       0  4995.4    0.07       0  5001.4    0.12       0
  5132.6    0.16       0
Bank Sta=4995.4,5001.4
Exp/Cntr=0.3,0.1

Type RM Length L Ch R = 1,697,329,329,329
BEGIN DESCRIPTION:
Mapping XS e9869124
END DESCRIPTION:
XS GIS Cut Line= 2
      3713452.05     10683557.72      3713454.22     10683920.11
#Sta/Elev= 30
  4836.7  356.39  4849.2  355.78  4859.2  354.16  4879.2  351.55  4889.8  351.20
  4909.2  349.42  4929.2  346.51  4949.2  346.41  4959.2  345.20  4969.2  345.24
  4979.2  343.56  4989.2  342.50  4999.2  332.00  5006.2  331.70  5008.9  331.20
  5012.2  331.70  5019.2  340.46  5029.2  343.18  5039.2  345.27  5059.2  347.24
  5089.2  351.18  5099.2  351.60  5109.2  352.96  5119.2  353.52  5130.1  355.08
  5139.2  355.52  5149.2  357.22  5179.2  359.84  5189.2  361.15  5199.1  361.74
#Mann=5,-1,0
  4836.7    0.16       0  4889.8    0.12       0  5006.2    0.07       0
  5012.2    0.12       0  5130.1    0.16       0
Bank Sta=5006.2,5012.2
Exp/Cntr=0.3,0.1

Type RM Length L Ch R = 1,368,303,303,303
BEGIN DESCRIPTION:
UNT 155 IN CACR 2.0
END DESCRIPTION:
XS GIS Cut Line= 3
      3713237.20     10683644.52      3713137.38     10683703.10
      3713113.52     10683970.00
#Sta/Elev= 30
  4847.9  360.49  4871.5  355.19  4887.2  353.60  4893.0  350.94  4902.9  350.40
  4908.7  349.12  4914.7  346.77  4945.8  344.52  4959.5  342.30  4980.8  340.45
  4987.3  328.51  4990.1  328.01  4993.3  328.51  5000.9  328.57  5010.9  340.52
  5021.0  341.93  5031.0  341.34  5091.2  342.75  5101.3  343.18  5106.7  344.38
  5122.2  345.72  5131.4  346.09  5141.4  347.94  5161.5  349.86  5171.6  350.31
  5181.6  351.98  5191.6  352.11  5211.7  354.18  5218.0  356.12  5231.6  357.25
#Mann=4,-1,0
  4847.9    0.16       0  4987.3    0.07       0  4993.3    0.16       0
  5122.2    0.16       0
Bank Sta=4987.3,4993.3
Exp/Cntr=0.3,0.1

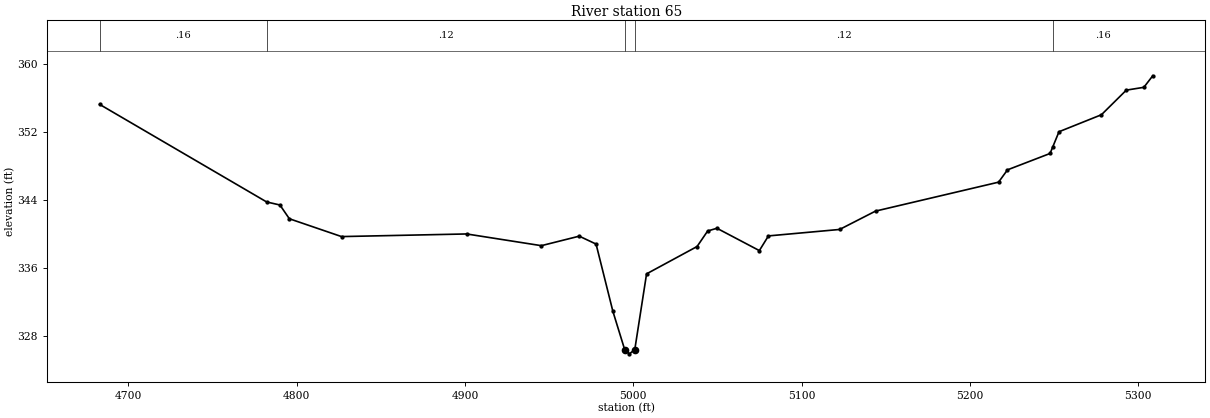
Type RM Length L Ch R = 1,65,0,0,0
BEGIN DESCRIPTION:
UNT 155 IN CACR 1.0
END DESCRIPTION:
XS GIS Cut Line= 4
      3713087.47     10683575.06      3712842.25     10683700.93
      3712844.42     10683787.74      3712934.68     10684034.90
#Sta/Elev= 30
  4683.0  355.22  4782.2  343.73  4790.1  343.37  4795.7  341.75  4826.7  339.65
  4901.0  339.96  4945.4  338.58  4967.9  339.70  4977.9  338.77  4987.9  330.84
  4994.9  326.34  4997.7  325.84  5000.9  326.34  5007.9  335.26  5037.9  338.48
  5044.2  340.31  5049.7  340.63  5074.9  338.00  5080.3  339.73  5122.6  340.49
  5143.9  342.65  5217.0  346.06  5222.3  347.51  5247.6  349.44  5249.3  350.26
  5252.9  352.00  5278.1  354.00  5292.9  356.90  5303.3  357.23  5308.6  358.59
#Mann=5,-1,0
  4683.0    0.16       0  4782.2    0.12       0  4994.9    0.07       0
  5000.9    0.12       0  5249.3    0.16       0
Bank Sta=4994.9,5000.9
Exp/Cntr=0.3,0.1

Chan Stop Cuts=-1