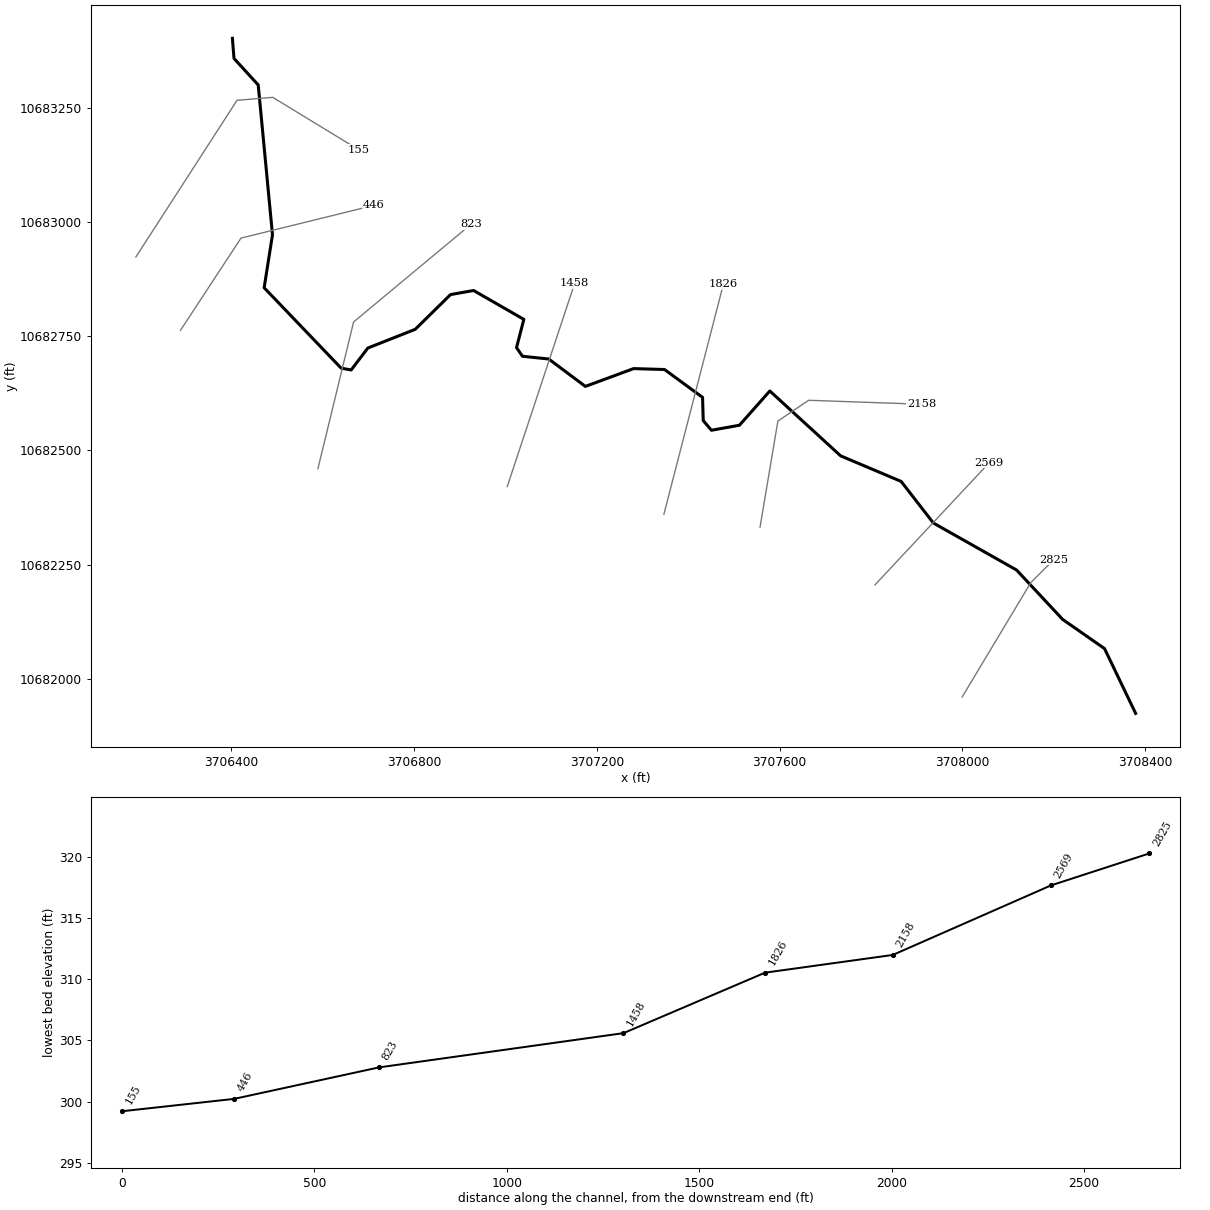
--- UNT 156 IN CACR.prj (project) ---

Proj Title=UNT 156 IN CACR Base Level Engineering
Current Plan=p01
Default Exp/Contr=0.3,0.1
English Units
Geom File=g01
Flow File=f01
Plan File=p01
BEGIN DESCRIPTION:
UNT 156 IN CACR
END DESCRIPTION:

--- UNT 156 IN CACR.p01 (plan) ---

Plan Title=Multiple Run
Short Identifier=Multiple
Geom File=g01
Flow File=f01
Subcritical Flow
K Sum by GR= 0
Std Step Tol= 0.01
Critical Tol= 0.01
Num of Std Step Trials= 20
Max Error Tol= 0.3
Flow Tol Ratio= 0.001
Split Flow NTrial= 30
Split Flow Tol= 0.02
Split Flow Ratio= 0.02
Log Output Level= 0
Friction Slope Method= 1
Unsteady Friction Slope Method= 2
Unsteady Bridges Friction Slope Method= 1
Parabolic Critical Depth
Global Vel Dist=  1 , 1 , 1
Global Log Level= 0
CheckData=True
Encroach Param= -1, 0, 0, 0
BEGIN DESCRIPTION:
Multiple Run
END DESCRIPTION:

--- UNT 156 IN CACR.f01 (steady flow) ---

Flow Title=Multiple
Number of Profiles=7
Profile Names=10-year,25-year,50-year,1pct_min,100-year,1pct_plu,500-year
River Rch & RM= UNT 156 IN CACR,Reach-1,2825
     224     286     335     290     392     530     536
River Rch & RM= UNT 156 IN CACR,Reach-1,2158
     391     519     622     550     744    1006    1065
Boundary for River Rch & Prof#=UNT 156 IN CACR,Reach-1,1
Up Type=0
Dn Type=3
Dn Slope=0.005
Boundary for River Rch & Prof#=UNT 156 IN CACR,Reach-1,2
Up Type=0
Dn Type=3
Dn Slope=0.005
Boundary for River Rch & Prof#=UNT 156 IN CACR,Reach-1,3
Up Type=0
Dn Type=3
Dn Slope=0.005
Boundary for River Rch & Prof#=UNT 156 IN CACR,Reach-1,4
Up Type=0
Dn Type=3
Dn Slope=0.005
Boundary for River Rch & Prof#=UNT 156 IN CACR,Reach-1,5
Up Type=0
Dn Type=3
Dn Slope=0.005
Boundary for River Rch & Prof#=UNT 156 IN CACR,Reach-1,6
Up Type=0
Dn Type=3
Dn Slope=0.005
Boundary for River Rch & Prof#=UNT 156 IN CACR,Reach-1,7
Up Type=0
Dn Type=3
Dn Slope=0.005

--- UNT 156 IN CACR.g01 (geometry) ---

Geom Title=Existing Conditions

River Reach=UNT 156 IN CACR,Reach-1
Reach XY= 30
      3708379.32     10681924.22      3708311.25     10682066.00
      3708219.50     10682130.00      3708118.75     10682238.00
      3707936.50     10682341.00      3707866.00     10682432.00
      3707733.50     10682488.00      3707578.50     10682630.00
      3707512.00     10682555.00      3707450.75     10682544.00
      3707432.75     10682565.00      3707431.25     10682616.00
      3707348.00     10682677.00      3707280.25     10682679.00
      3707174.75     10682640.00      3707094.50     10682700.00
      3707037.00     10682706.00      3707024.00     10682725.00
      3707040.02     10682786.75      3706930.00     10682850.00
      3706879.50     10682841.00      3706802.25     10682765.00
      3706698.50     10682724.00      3706662.00     10682676.00
      3706640.00     10682680.00      3706471.50     10682856.00
      3706489.75     10682972.00      3706458.50     10683300.00
      3706405.50     10683358.00      3706402.00     10683402.00

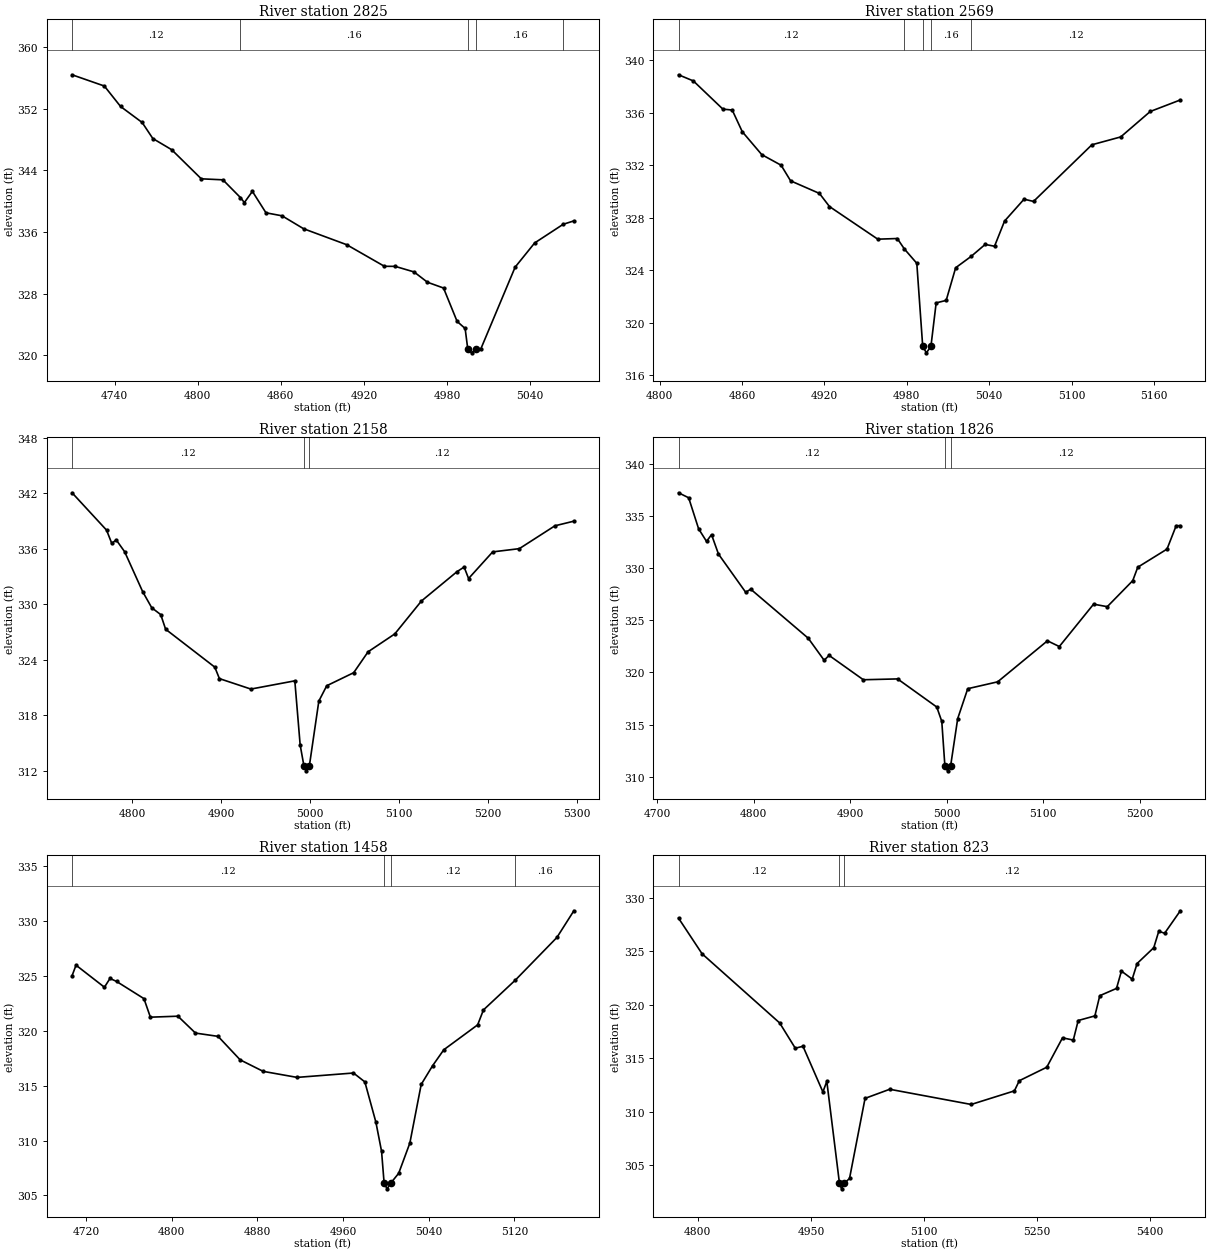
Type RM Length L Ch R = 1,2825,256,256,256
BEGIN DESCRIPTION:
UNT 156 IN CACR 6.0
END DESCRIPTION:
XS GIS Cut Line= 3
      3707999.60     10681960.17      3708149.61     10682210.19
      3708199.62     10682260.20
#Sta/Elev= 30
  4709.3  356.39  4732.6  354.93  4744.3  352.28  4759.9  350.20  4767.6  348.12
  4781.2  346.67  4802.6  342.89  4818.2  342.76  4830.9  340.45  4833.7  339.81
  4839.5  341.26  4849.3  338.48  4860.9  338.09  4876.5  336.41  4907.6  334.34
  4934.8  331.54  4942.6  331.53  4956.2  330.81  4965.9  329.47  4977.5  328.72
  4987.3  324.39  4993.1  323.47  4995.0  320.81  4997.7  320.31  5001.0  320.81
  5004.4  320.81  5029.2  331.43  5043.3  334.57  5063.9  336.99  5071.6  337.43
#Mann=5,-1,0
  4709.3    0.12       0  4830.9    0.16       0  4995.0    0.07       0
  5001.0    0.16       0  5063.9    0.12       0
Bank Sta=4995,5001
Exp/Cntr=0.3,0.1

Type RM Length L Ch R = 1,2569,411,411,411
BEGIN DESCRIPTION:
Mapping XS 533df010
END DESCRIPTION:
XS GIS Cut Line= 2
      3707808.82     10682205.63      3708058.37     10682472.54
#Sta/Elev= 30
  4813.8  338.90  4824.6  338.43  4846.1  336.28  4852.9  336.21  4860.2  334.56
  4874.4  332.81  4888.5  332.00  4895.4  330.81  4916.4  329.85  4923.7  328.85
  4958.9  326.36  4973.1  326.41  4978.2  325.62  4987.3  324.52  4991.6  318.19
  4994.3  317.69  4997.6  318.19  5001.4  321.50  5008.7  321.69  5015.6  324.18
  5026.9  325.05  5037.1  325.96  5043.9  325.82  5051.2  327.74  5065.4  329.41
  5072.3  329.24  5114.8  333.56  5135.8  334.16  5157.3  336.10  5179.2  336.98
#Mann=5,-1,0
  4813.8    0.12       0  4978.2    0.16       0  4991.6    0.07       0
  4997.6    0.16       0  5026.9    0.12       0
Bank Sta=4991.6,4997.6
Exp/Cntr=0.3,0.1

Type RM Length L Ch R = 1,2158,332,332,332
BEGIN DESCRIPTION:
UNT 156 IN CACR 5.0
END DESCRIPTION:
XS GIS Cut Line= 4
      3707557.09     10682331.88      3707596.15     10682564.07
      3707663.43     10682609.64      3707910.86     10682600.96
#Sta/Elev= 30
  4732.5  342.06  4771.3  338.02  4777.1  336.60  4782.2  336.96  4791.6  335.69
  4811.9  331.37  4822.1  329.63  4832.2  328.89  4837.7  327.31  4893.0  323.21
  4898.2  321.97  4933.6  320.84  4983.0  321.73  4989.0  314.80  4993.3  312.50
  4996.0  312.00  4999.3  312.50  5010.0  319.54  5018.9  321.20  5049.2  322.61
  5065.4  324.87  5095.4  326.80  5125.4  330.36  5165.5  333.54  5173.4  334.03
  5178.4  332.79  5205.5  335.67  5235.5  336.02  5275.5  338.49  5296.8  338.99
#Mann=3,-1,0
  4732.5    0.12       0  4993.3    0.07       0  4999.3    0.12       0
Bank Sta=4993.3,4999.3
Exp/Cntr=0.3,0.1

Type RM Length L Ch R = 1,1826,368,368,368
BEGIN DESCRIPTION:
UNT 156 IN CACR 4.0
END DESCRIPTION:
XS GIS Cut Line= 2
      3707346.58     10682360.07      3707476.78     10682863.51
#Sta/Elev= 30
  4722.0  337.26  4732.5  336.78  4742.8  333.80  4751.0  332.59  4756.2  333.24
  4763.4  331.37  4791.6  327.70  4796.8  328.00  4856.4  323.29  4872.9  321.17
  4878.0  321.64  4913.5  319.30  4949.0  319.38  4989.6  316.68  4994.8  315.30
  4998.0  311.05  5000.8  310.55  5004.0  311.05  5011.3  315.57  5021.7  318.44
  5052.7  319.10  5104.3  323.04  5116.6  322.49  5152.1  326.56  5166.3  326.32
  5192.7  328.82  5197.9  330.11  5228.2  331.85  5237.7  334.10  5242.0  334.10
#Mann=3,-1,0
  4722.0    0.12       0  4998.0    0.07       0  5004.0    0.12       0
Bank Sta=4998,5004
Exp/Cntr=0.3,0.1

Type RM Length L Ch R = 1,1458,635,635,635
BEGIN DESCRIPTION:
UNT 156 IN CACR 3.0
END DESCRIPTION:
XS GIS Cut Line= 2
      3707003.70     10682420.83      3707151.17     10682865.41
#Sta/Elev= 30
  4707.1  325.03  4710.8  325.99  4737.3  323.98  4742.5  324.78  4748.6  324.51
  4774.2  322.94  4780.2  321.25  4805.9  321.34  4822.3  319.80  4843.4  319.50
  4864.0  317.36  4885.5  316.31  4917.1  315.76  4969.8  316.16  4980.4  315.35
  4990.7  311.68  4996.0  309.02  4998.4  306.10  5001.2  305.60  5004.4  306.10
  5012.0  307.02  5022.4  309.77  5033.0  315.12  5043.6  316.82  5054.1  318.28
  5085.7  320.55  5091.1  321.91  5121.0  324.64  5159.7  328.52  5175.5  330.95
#Mann=4,-1,0
  4707.1    0.12       0  4998.4    0.07       0  5004.4    0.12       0
  5121.0    0.16       0
Bank Sta=4998.4,5004.4
Exp/Cntr=0.3,0.1

Type RM Length L Ch R = 1,823,377,377,377
BEGIN DESCRIPTION:
Mapping XS b3cd6d2b
END DESCRIPTION:
XS GIS Cut Line= 3
      3706589.20     10682459.87      3706667.33     10682781.08
      3706924.65     10682995.16
#Sta/Elev= 30
  4774.5  328.11  4805.7  324.78  4908.6  318.31  4929.3  315.95  4939.5  316.13
  4965.9  311.86  4971.1  312.85  4987.9  303.30  4990.7  302.80  4993.9  303.30
  5001.2  303.77  5021.8  311.26  5054.5  312.11  5162.5  310.69  5219.8  311.96
  5226.3  312.91  5262.7  314.17  5283.6  316.92  5297.9  316.71  5304.4  318.54
  5326.5  318.97  5333.0  320.86  5355.2  321.54  5361.7  323.16  5376.0  322.41
  5382.5  323.87  5404.6  325.35  5411.2  326.88  5419.0  326.70  5439.8  328.80
#Mann=3,-1,0
  4774.5    0.12       0  4987.9    0.07       0  4993.9    0.12       0
Bank Sta=4987.9,4993.9
Exp/Cntr=0.3,0.1

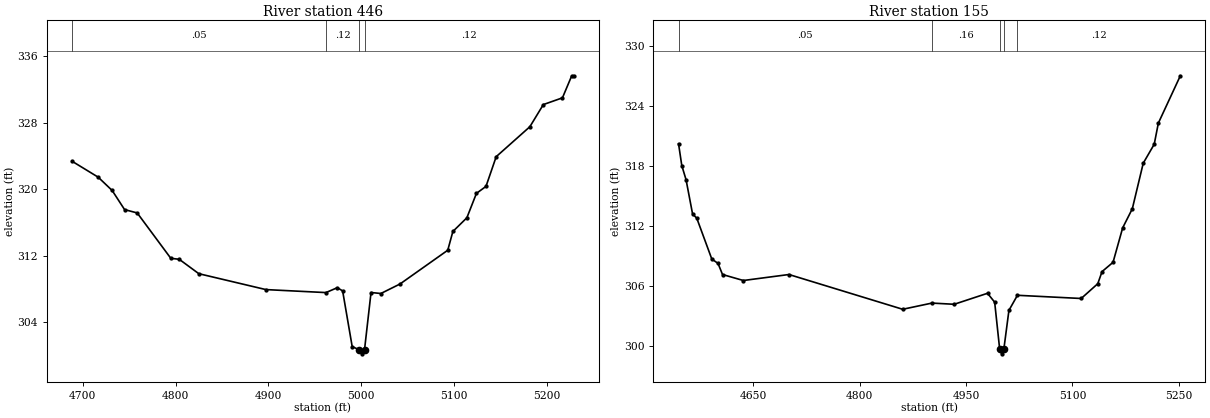
Type RM Length L Ch R = 1,446,291,291,291
BEGIN DESCRIPTION:
UNT 156 IN CACR 2.0
END DESCRIPTION:
XS GIS Cut Line= 3
      3706288.44     10682762.87      3706420.80     10682964.68
      3706711.58     10683036.29
#Sta/Elev= 30
  4688.5  323.36  4716.6  321.45  4731.7  319.85  4745.1  317.55  4758.7  317.15
  4794.9  311.70  4804.0  311.58  4825.1  309.85  4897.4  307.94  4962.1  307.58
  4974.4  308.17  4980.1  307.78  4990.4  301.09  4997.7  300.72  5000.5  300.22
  5003.7  300.72  5010.7  307.59  5021.3  307.47  5041.9  308.61  5093.4  312.67
  5098.9  314.92  5114.0  316.57  5124.3  319.50  5134.6  320.34  5145.6  323.91
  5181.9  327.51  5196.4  330.17  5217.0  330.98  5227.0  333.63  5229.3  333.63
#Mann=4,-1,0
  4688.5    0.05       0  4962.1    0.12       0  4997.7    0.07       0
  5003.7    0.12       0
Bank Sta=4997.7,5003.7
Exp/Cntr=0.3,0.1

Type RM Length L Ch R = 1,155,0,0,0
BEGIN DESCRIPTION:
UNT 156 IN CACR 1.0
END DESCRIPTION:
XS GIS Cut Line= 4
      3706190.75     10682923.41      3706412.12     10683266.33
      3706490.25     10683272.84      3706679.02     10683157.84
#Sta/Elev= 30
  4544.5  320.24  4549.1  318.05  4555.1  316.64  4564.3  313.21  4570.2  312.79
  4591.4  308.70  4600.2  308.26  4606.5  307.15  4635.9  306.55  4700.2  307.15
  4860.6  303.67  4901.8  304.29  4933.2  304.17  4980.2  305.27  4990.3  304.38
  4997.3  299.71  5000.1  299.21  5003.3  299.71  5010.4  303.56  5022.4  305.07
  5112.3  304.75  5135.7  306.23  5141.7  307.44  5157.2  308.37  5170.8  311.82
  5184.4  313.73  5199.8  318.29  5215.3  320.19  5221.1  322.30  5252.1  327.04
#Mann=5,-1,0
  4544.5    0.05       0  4901.8    0.16       0  4997.3    0.07       0
  5003.3    0.16       0  5022.4    0.12       0
Bank Sta=4997.3,5003.3
Exp/Cntr=0.3,0.1

Chan Stop Cuts=-1