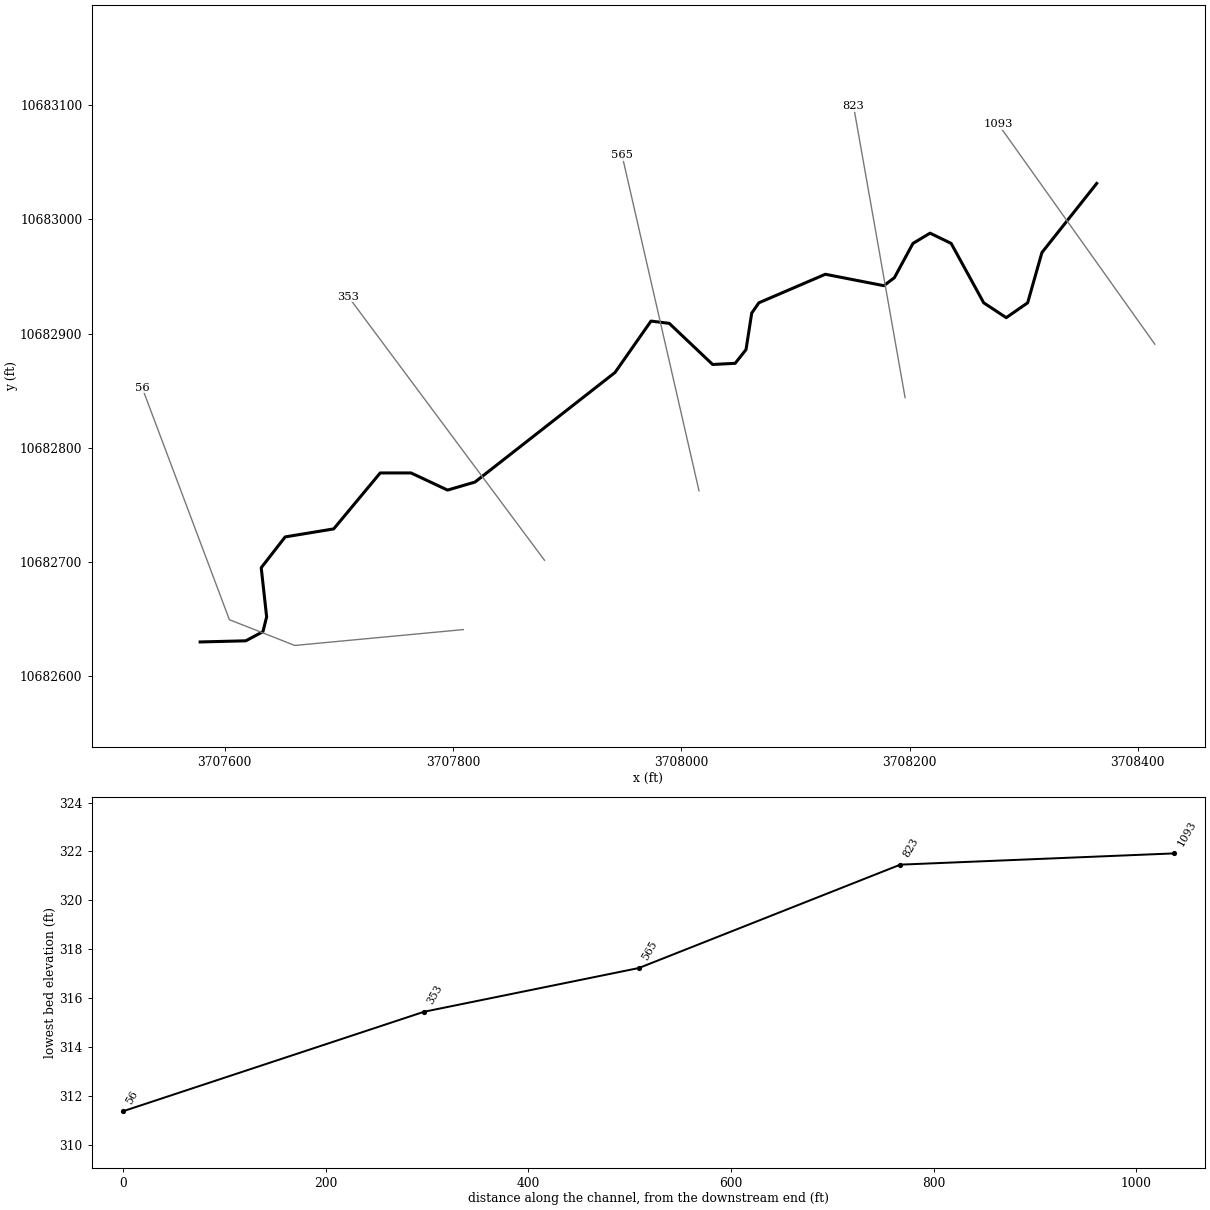
--- UNT 157 IN CACR.prj (project) ---

Proj Title=UNT 157 IN CACR Base Level Engineering
Current Plan=p01
Default Exp/Contr=0.3,0.1
English Units
Geom File=g01
Flow File=f01
Plan File=p01
BEGIN DESCRIPTION:
UNT 157 IN CACR
END DESCRIPTION:

--- UNT 157 IN CACR.p01 (plan) ---

Plan Title=Multiple Run
Short Identifier=Multiple
Geom File=g01
Flow File=f01
Subcritical Flow
K Sum by GR= 0
Std Step Tol= 0.01
Critical Tol= 0.01
Num of Std Step Trials= 20
Max Error Tol= 0.3
Flow Tol Ratio= 0.001
Split Flow NTrial= 30
Split Flow Tol= 0.02
Split Flow Ratio= 0.02
Log Output Level= 0
Friction Slope Method= 1
Unsteady Friction Slope Method= 2
Unsteady Bridges Friction Slope Method= 1
Parabolic Critical Depth
Global Vel Dist=  1 , 1 , 1
Global Log Level= 0
CheckData=True
Encroach Param= -1, 0, 0, 0
BEGIN DESCRIPTION:
Multiple Run
END DESCRIPTION:

--- UNT 157 IN CACR.f01 (steady flow) ---

Flow Title=Multiple
Number of Profiles=7
Profile Names=10-year,25-year,50-year,1pct_min,100-year,1pct_plu,500-year
River Rch & RM= UNT 157 IN CACR,Reach-1,1093
     202     256     299     257     348     470     472
Boundary for River Rch & Prof#=UNT 157 IN CACR,Reach-1,1
Up Type=0
Dn Type=3
Dn Slope=0.005
Boundary for River Rch & Prof#=UNT 157 IN CACR,Reach-1,2
Up Type=0
Dn Type=3
Dn Slope=0.005
Boundary for River Rch & Prof#=UNT 157 IN CACR,Reach-1,3
Up Type=0
Dn Type=3
Dn Slope=0.005
Boundary for River Rch & Prof#=UNT 157 IN CACR,Reach-1,4
Up Type=0
Dn Type=3
Dn Slope=0.005
Boundary for River Rch & Prof#=UNT 157 IN CACR,Reach-1,5
Up Type=0
Dn Type=3
Dn Slope=0.005
Boundary for River Rch & Prof#=UNT 157 IN CACR,Reach-1,6
Up Type=0
Dn Type=3
Dn Slope=0.005
Boundary for River Rch & Prof#=UNT 157 IN CACR,Reach-1,7
Up Type=0
Dn Type=3
Dn Slope=0.005

--- UNT 157 IN CACR.g01 (geometry) ---

Geom Title=Existing Conditions

River Reach=UNT 157 IN CACR,Reach-1
Reach XY= 30
      3708364.00     10683031.53      3708316.00     10682971.00
      3708303.50     10682927.00      3708284.75     10682914.00
      3708265.00     10682927.00      3708236.50     10682979.00
      3708218.00     10682988.00      3708203.00     10682979.00
      3708186.75     10682949.00      3708177.50     10682942.00
      3708126.25     10682952.00      3708068.00     10682927.00
      3708061.75     10682918.00      3708056.75     10682886.00
      3708047.25     10682874.00      3708027.50     10682873.00
      3707989.50     10682909.00      3707973.50     10682911.00
      3707942.00     10682866.00      3707819.25     10682770.00
      3707795.25     10682763.00      3707763.25     10682778.00
      3707736.25     10682778.00      3707695.50     10682729.00
      3707653.00     10682722.00      3707632.00     10682695.00
      3707636.75     10682652.00      3707633.50     10682639.00
      3707618.50     10682631.00      3707578.50     10682630.00

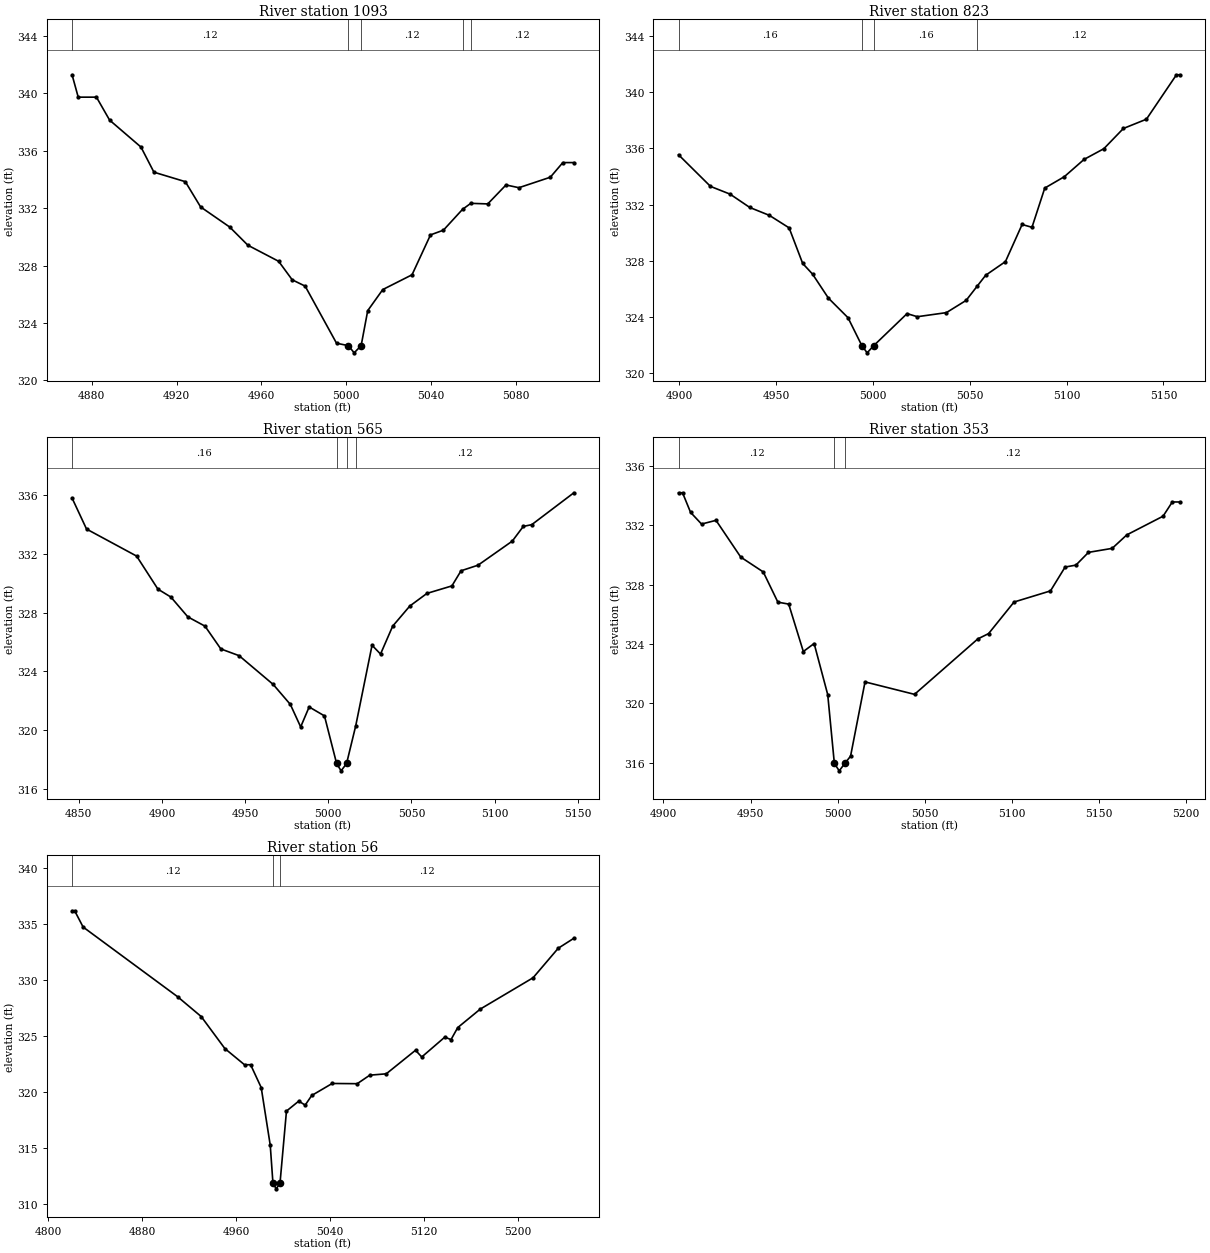
Type RM Length L Ch R = 1,1093,270,270,270
BEGIN DESCRIPTION:
UNT 157 IN CACR 1.0
END DESCRIPTION:
XS GIS Cut Line= 2
      3708414.89     10682890.79      3708277.70     10683083.56
#Sta/Elev= 30
  4870.7  341.30  4873.6  339.74  4882.2  339.74  4888.4  338.14  4903.2  336.26
  4909.3  334.51  4924.1  333.85  4931.3  332.09  4945.0  330.69  4953.6  329.42
  4968.1  328.30  4974.5  327.01  4980.6  326.57  4995.4  322.59  5001.0  322.42
  5003.7  321.92  5007.0  322.42  5010.1  324.86  5017.2  326.33  5031.0  327.36
  5039.7  330.14  5045.8  330.47  5054.8  331.92  5058.7  332.34  5066.7  332.30
  5075.3  333.62  5081.4  333.43  5096.2  334.16  5102.1  335.18  5107.3  335.18
#Mann=5,-1,0
  4870.7    0.12       0  5001.0    0.07       0  5007.0    0.12       0
  5054.8    0.16       0  5058.7    0.12       0
Bank Sta=5001,5007
Exp/Cntr=0.3,0.1

Type RM Length L Ch R = 1,823,258,258,258
BEGIN DESCRIPTION:
Mapping XS dcc3a7d6
END DESCRIPTION:
XS GIS Cut Line= 2
      3708196.12     10682843.99      3708150.99     10683099.13
#Sta/Elev= 30
  4899.6  335.55  4916.1  333.30  4926.2  332.75  4936.4  331.80  4946.5  331.24
  4956.7  330.35  4963.7  327.82  4968.8  327.06  4977.0  325.35  4987.1  323.96
  4994.3  321.96  4997.0  321.46  5000.3  321.96  5017.6  324.25  5022.9  324.03
  5037.9  324.32  5048.1  325.19  5053.9  326.22  5058.2  326.98  5068.4  327.95
  5077.0  330.59  5082.1  330.39  5088.7  333.18  5098.8  333.99  5109.0  335.22
  5119.2  335.98  5129.3  337.42  5141.2  338.08  5156.7  341.24  5158.7  341.24
#Mann=4,-1,0
  4899.6    0.16       0  4994.3    0.07       0  5000.3    0.16       0
  5053.9    0.12       0
Bank Sta=4994.3,5000.3
Exp/Cntr=0.3,0.1

Type RM Length L Ch R = 1,565,212,212,212
BEGIN DESCRIPTION:
Mapping XS f7e9b392
END DESCRIPTION:
XS GIS Cut Line= 2
      3708015.57     10682762.33      3707948.13     10683056.29
#Sta/Elev= 30
  4846.0  335.80  4854.7  333.69  4884.8  331.85  4897.6  329.60  4905.4  329.06
  4915.6  327.71  4925.9  327.08  4935.4  325.53  4946.4  325.07  4966.9  323.11
  4977.2  321.75  4983.4  320.22  4988.5  321.58  4997.7  320.97  5005.0  317.73
  5007.7  317.23  5011.0  317.73  5016.5  320.30  5026.3  325.78  5031.4  325.18
  5038.7  327.08  5049.0  328.45  5059.3  329.31  5074.3  329.82  5079.8  330.85
  5090.0  331.23  5110.6  332.87  5117.2  333.87  5122.3  333.99  5147.6  336.16
#Mann=4,-1,0
  4846.0    0.16       0  5005.0    0.07       0  5011.0    0.16       0
  5016.5    0.12       0
Bank Sta=5005,5011
Exp/Cntr=0.3,0.1

Type RM Length L Ch R = 1,353,297,297,297
BEGIN DESCRIPTION:
Mapping XS da1b1108
END DESCRIPTION:
XS GIS Cut Line= 2
      3707880.18     10682701.55      3707708.27     10682932.49
#Sta/Elev= 30
  4908.7  334.20  4911.0  334.20  4915.6  332.88  4921.9  332.09  4930.2  332.34
  4944.4  329.86  4957.3  328.86  4965.7  326.82  4971.9  326.69  4980.3  323.49
  4986.5  324.03  4994.3  320.58  4998.1  315.94  5000.9  315.44  5004.1  315.94
  5007.4  316.43  5015.7  321.44  5044.1  320.60  5080.4  324.34  5086.6  324.70
  5101.2  326.83  5122.1  327.58  5130.5  329.19  5136.7  329.32  5143.9  330.18
  5157.5  330.45  5165.9  331.36  5186.7  332.62  5192.0  333.58  5196.6  333.58
#Mann=3,-1,0
  4908.7    0.12       0  4998.1    0.07       0  5004.1    0.12       0
Bank Sta=4998.1,5004.1
Exp/Cntr=0.3,0.1

Type RM Length L Ch R = 1,56,0,0,0
BEGIN DESCRIPTION:
UNT 157 IN CACR 2.0
END DESCRIPTION:
XS GIS Cut Line= 4
      3707809.01     10682640.82      3707661.40     10682626.93
      3707604.11     10682649.50      3707527.70     10682852.67
#Sta/Elev= 30
  4820.5  336.15  4822.7  336.15  4829.9  334.70  4910.3  328.49  4930.4  326.72
  4950.5  323.87  4967.2  322.43  4972.4  322.43  4981.4  320.40  4989.1  315.26
  4991.4  311.87  4994.2  311.37  4997.4  311.87  5002.9  318.30  5013.4  319.19
  5018.8  318.83  5024.4  319.69  5041.8  320.76  5063.1  320.74  5073.8  321.50
  5087.8  321.62  5112.7  323.72  5118.0  323.12  5137.6  324.89  5142.9  324.67
  5148.6  325.74  5167.8  327.39  5212.7  330.18  5234.1  332.81  5247.4  333.70
#Mann=3,-1,0
  4820.5    0.12       0  4991.4    0.07       0  4997.4    0.12       0
Bank Sta=4991.4,4997.4
Exp/Cntr=0.3,0.1

Chan Stop Cuts=-1