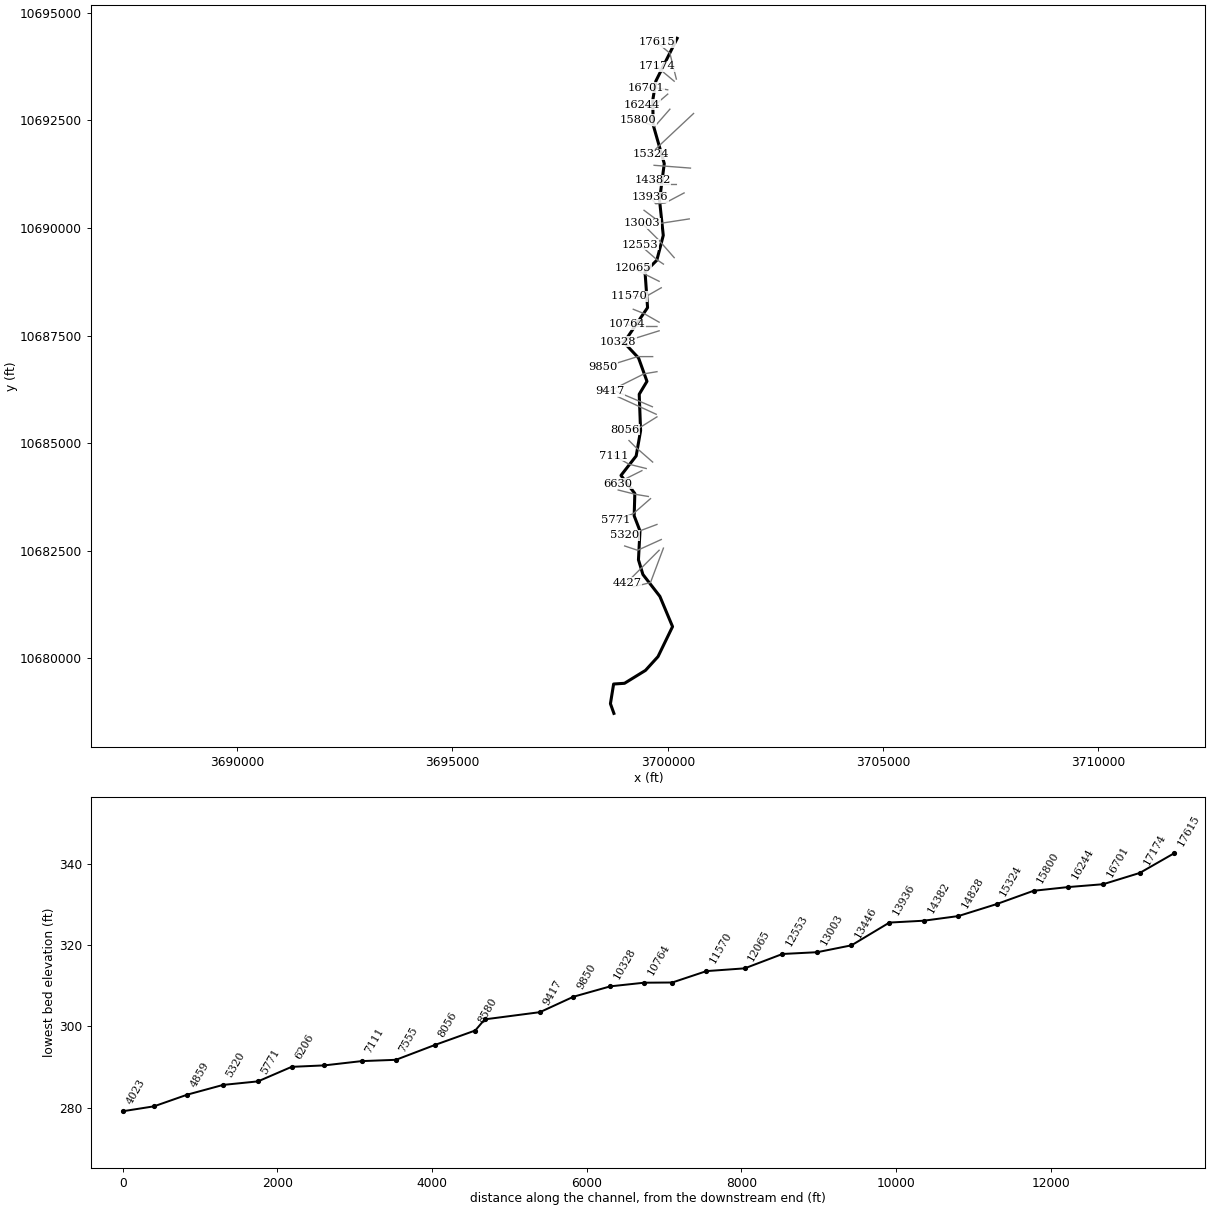
--- UNT 158 IN CACR.prj (project) ---

Proj Title=UNT 158 IN CACR Base Level Engineering
Current Plan=p01
Default Exp/Contr=0.3,0.1
English Units
Geom File=g01
Flow File=f01
Plan File=p01
BEGIN DESCRIPTION:
UNT 158 IN CACR
END DESCRIPTION:

--- UNT 158 IN CACR.p01 (plan) ---

Plan Title=Multiple Run
Short Identifier=Multiple
Geom File=g01
Flow File=f01
Subcritical Flow
K Sum by GR= 0
Std Step Tol= 0.01
Critical Tol= 0.01
Num of Std Step Trials= 20
Max Error Tol= 0.3
Flow Tol Ratio= 0.001
Split Flow NTrial= 30
Split Flow Tol= 0.02
Split Flow Ratio= 0.02
Log Output Level= 0
Friction Slope Method= 1
Unsteady Friction Slope Method= 2
Unsteady Bridges Friction Slope Method= 1
Parabolic Critical Depth
Global Vel Dist=  1 , 1 , 1
Global Log Level= 0
CheckData=True
Encroach Param= -1, 0, 0, 0
BEGIN DESCRIPTION:
Multiple Run
END DESCRIPTION:

--- UNT 158 IN CACR.f01 (steady flow) ---

Flow Title=Multiple
Number of Profiles=7
Profile Names=10-year,25-year,50-year,1pct_min,100-year,1pct_plu,500-year
River Rch & RM= UNT 158 IN CACR,Reach-1,17615
     752    1045    1293    1177    1591    2152    2420
River Rch & RM= UNT 158 IN CACR,Reach-1,16701
     897    1251    1552    1413    1911    2585    2912
River Rch & RM= UNT 158 IN CACR,Reach-1,9850
    1157    1633    2040    1870    2529    3421    3906
River Rch & RM= UNT 158 IN CACR,Reach-1,6630
    1238    1745    2180    1995    2698    3649    4156
Boundary for River Rch & Prof#=UNT 158 IN CACR,Reach-1,1
Up Type=0
Dn Type=3
Dn Slope=0.005
Boundary for River Rch & Prof#=UNT 158 IN CACR,Reach-1,2
Up Type=0
Dn Type=3
Dn Slope=0.005
Boundary for River Rch & Prof#=UNT 158 IN CACR,Reach-1,3
Up Type=0
Dn Type=3
Dn Slope=0.005
Boundary for River Rch & Prof#=UNT 158 IN CACR,Reach-1,4
Up Type=0
Dn Type=3
Dn Slope=0.005
Boundary for River Rch & Prof#=UNT 158 IN CACR,Reach-1,5
Up Type=0
Dn Type=3
Dn Slope=0.005
Boundary for River Rch & Prof#=UNT 158 IN CACR,Reach-1,6
Up Type=0
Dn Type=3
Dn Slope=0.005
Boundary for River Rch & Prof#=UNT 158 IN CACR,Reach-1,7
Up Type=0
Dn Type=3
Dn Slope=0.005

--- UNT 158 IN CACR.g01 (geometry) ---

Geom Title=Existing Conditions

River Reach=UNT 158 IN CACR,Reach-1
Reach XY= 30
      3700218.41     10694406.33      3699723.50     10693413.00
      3699651.75     10692964.00      3699661.50     10692396.00
      3699919.00     10691496.00      3699809.50     10690645.00
      3699896.00     10689827.00      3699746.50     10689251.00
      3699472.50     10688977.00      3699531.50     10688149.00
      3698983.25     10687339.00      3699322.25     10686978.00
      3699517.50     10686436.00      3699337.50     10686136.00
      3699369.50     10685289.00      3699266.75     10684702.00
      3698914.00     10684249.00      3699235.50     10683829.00
      3699220.50     10683310.00      3699355.25     10682960.00
      3699319.75     10682289.00      3699423.50     10681947.00
      3699817.00     10681439.00      3700111.25     10680736.00
      3699773.75     10680039.00      3699483.00     10679719.00
      3698996.25     10679419.00      3698743.00     10679402.00
      3698669.00     10678945.00      3698749.50     10678720.00

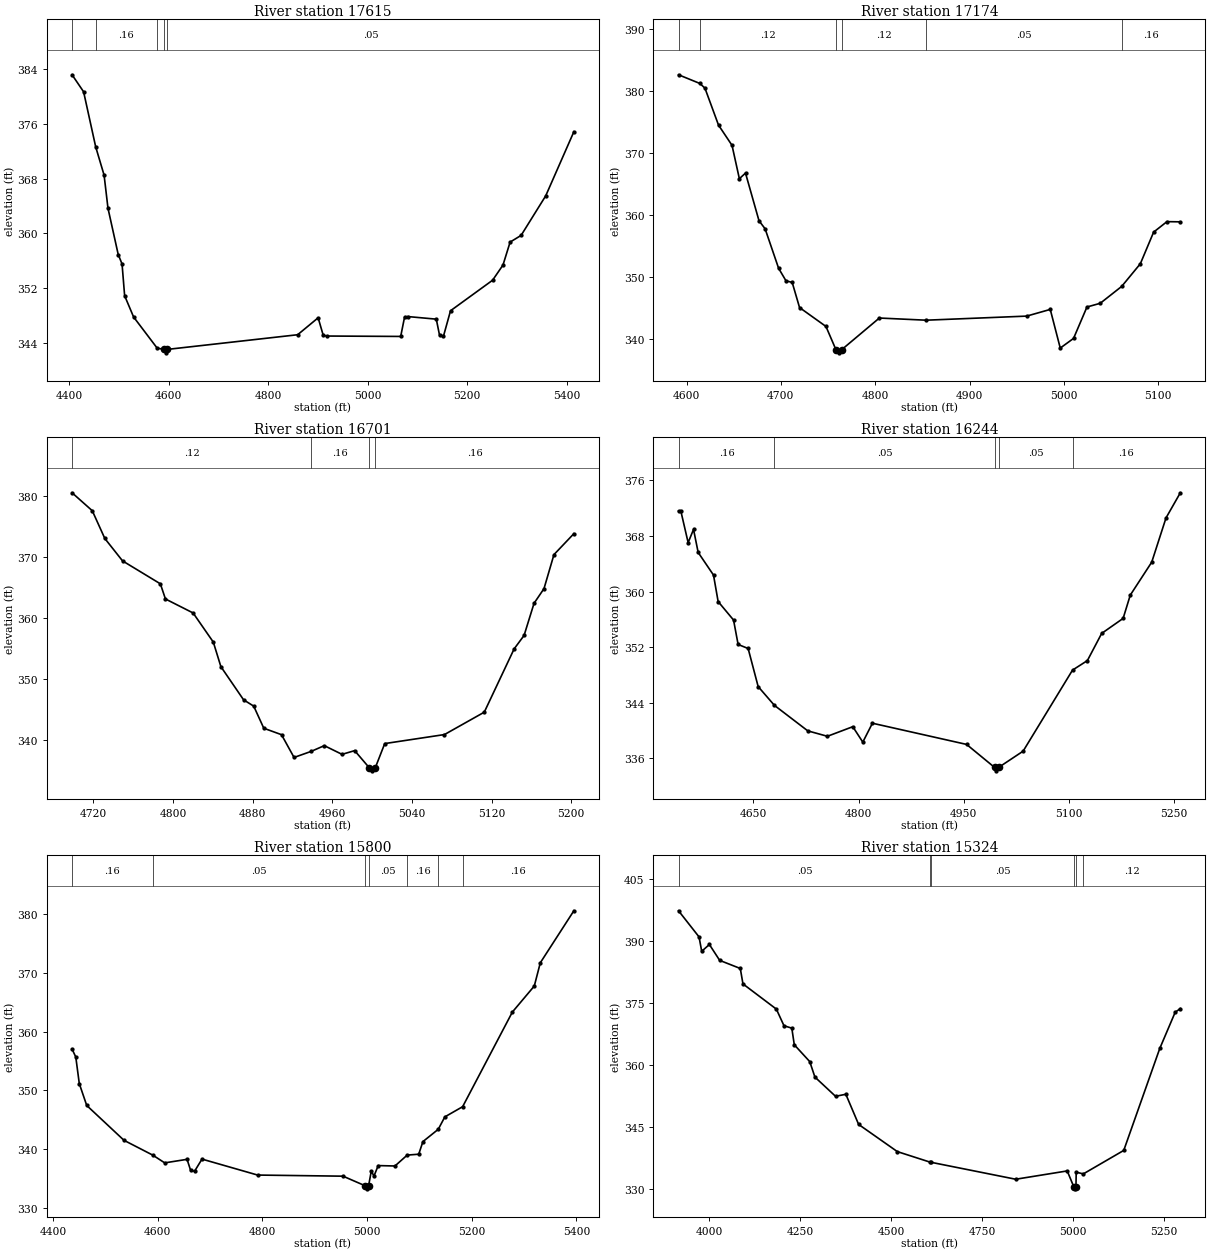
Type RM Length L Ch R = 1,17615,441,441,441
BEGIN DESCRIPTION:
UNT 158 IN CACR 31.0
END DESCRIPTION:
XS GIS Cut Line= 3
      3700199.62     10693460.16      3700049.61     10694060.19
      3699749.61     10694310.19
#Sta/Elev= 30
  4405.8  383.19  4429.0  380.70  4453.3  372.64  4470.2  368.50  4478.0  363.66
  4498.6  356.88  4506.3  355.50  4511.5  350.85  4529.5  347.74  4576.9  343.18
  4590.9  342.99  4593.7  342.49  4596.9  342.99  4859.4  345.14  4900.6  347.62
  4910.9  345.04  4918.6  344.95  5066.6  344.89  5074.4  347.73  5080.9  347.80
  5138.2  347.42  5144.7  345.07  5152.5  344.90  5166.8  348.65  5251.4  353.12
  5272.3  355.34  5286.6  358.70  5308.7  359.68  5358.2  365.47  5414.8  374.85
#Mann=5,-1,0
  4405.8    0.05       0  4453.3    0.16       0  4576.9    0.05       0
  4590.9    0.03       0  4596.9    0.05       0
Bank Sta=4590.9,4596.9
Exp/Cntr=0.3,0.1

Type RM Length L Ch R = 1,17174,473,473,473
BEGIN DESCRIPTION:
UNT 158 IN CACR 30.0
END DESCRIPTION:
XS GIS Cut Line= 3
      3700149.64     10693410.16      3699849.61     10693660.19
      3699749.59     10693760.20
#Sta/Elev= 30
  4591.5  382.58  4614.1  381.18  4619.5  380.42  4633.9  374.45  4648.2  371.19
  4656.0  365.80  4662.5  366.71  4676.8  359.02  4683.3  357.71  4697.6  351.34
  4705.4  349.32  4712.0  349.06  4719.8  345.00  4747.8  341.95  4758.4  338.19
  4761.2  337.69  4764.4  338.19  4804.4  343.31  4854.0  342.96  4960.6  343.62
  4985.6  344.70  4996.2  338.46  5010.3  340.02  5024.5  345.09  5038.6  345.69
  5061.3  348.41  5081.1  352.07  5095.2  357.18  5109.3  358.87  5123.5  358.84
#Mann=6,-1,0
  4591.5    0.05       0  4614.1    0.12       0  4758.4    0.03       0
  4764.4    0.12       0  4854.0    0.05       0  5061.3    0.16       0
Bank Sta=4758.4,4764.4
Exp/Cntr=0.3,0.1

Type RM Length L Ch R = 1,16701,457,457,457
BEGIN DESCRIPTION:
UNT 158 IN CACR 29.0
END DESCRIPTION:
XS GIS Cut Line= 3
      3699999.60     10693210.19      3699699.61     10693260.19
      3699499.64     10693260.19
#Sta/Elev= 30
  4698.6  380.61  4718.9  377.66  4731.5  373.10  4749.3  369.42  4787.3  365.65
  4792.4  363.16  4820.2  360.86  4840.5  356.07  4848.1  352.04  4870.9  346.59
  4881.1  345.55  4891.2  341.92  4909.0  340.86  4921.6  337.12  4938.7  338.11
  4952.0  339.06  4969.8  337.63  4982.5  338.24  4997.2  335.42  4999.9  334.92
  5003.2  335.42  5012.7  339.40  5072.7  340.88  5112.7  344.56  5142.7  354.96
  5152.7  357.17  5162.7  362.45  5172.7  364.86  5182.7  370.45  5202.7  373.89
#Mann=4,-1,0
  4698.6    0.12       0  4938.7    0.16       0  4997.2    0.07       0
  5003.2    0.16       0
Bank Sta=4997.2,5003.2
Exp/Cntr=0.3,0.1

Type RM Length L Ch R = 1,16244,444,444,444
BEGIN DESCRIPTION:
UNT 158 IN CACR 28.0
END DESCRIPTION:
XS GIS Cut Line= 3
      3699999.60     10693110.18      3699649.61     10692810.19
      3699399.62     10692860.19
#Sta/Elev= 30
  4543.2  371.58  4546.5  371.58  4556.9  367.04  4564.6  368.94  4571.2  365.63
  4593.1  362.37  4599.7  358.56  4621.7  355.90  4628.2  352.39  4642.5  351.81
  4656.8  346.33  4680.0  343.63  4727.6  339.96  4755.6  339.18  4791.8  340.56
  4806.1  338.34  4819.8  341.06  4954.2  338.01  4994.0  334.71  4996.8  334.21
  5000.0  334.71  5034.8  337.04  5105.3  348.70  5126.5  350.07  5146.9  353.98
  5177.5  356.14  5187.7  359.49  5218.3  364.23  5238.7  370.60  5259.1  374.21
#Mann=5,-1,0
  4543.2    0.16       0  4680.0    0.05       0  4994.0    0.03       0
  5000.0    0.05       0  5105.3    0.16       0
Bank Sta=4994,5000
Exp/Cntr=0.3,0.1

Type RM Length L Ch R = 1,15800,476,476,476
BEGIN DESCRIPTION:
UNT 158 IN CACR 27.0
END DESCRIPTION:
XS GIS Cut Line= 3
      3700049.61     10692760.19      3699699.61     10692360.19
      3699299.61     10692510.19
#Sta/Elev= 30
  4436.3  357.03  4443.4  355.69  4450.1  351.17  4464.3  347.46  4535.5  341.54
  4590.4  339.03  4613.3  337.71  4656.0  338.31  4662.7  336.47  4670.3  336.28
  4684.5  338.35  4790.8  335.64  4954.0  335.45  4996.8  333.80  4999.6  333.30
  5002.8  333.80  5007.9  336.29  5013.2  335.49  5021.2  337.25  5053.2  337.18
  5076.6  339.03  5098.6  339.18  5106.6  341.32  5135.9  343.41  5148.5  345.52
  5182.5  347.25  5277.5  363.32  5319.4  367.74  5330.9  371.69  5395.0  380.52
#Mann=7,-1,0
  4436.3    0.16       0  4590.4    0.05       0  4996.8    0.03       0
  5002.8    0.05       0  5076.6    0.16       0  5135.9    0.05       0
  5182.5    0.16       0
Bank Sta=4996.8,5002.8
Exp/Cntr=0.3,0.1

Type RM Length L Ch R = 1,15324,496,496,496
BEGIN DESCRIPTION:
UNT 158 IN CACR 26.0
END DESCRIPTION:
XS GIS Cut Line= 3
      3700599.62     10692660.20      3699799.61     10691910.19
      3699599.64     10691710.22
#Sta/Elev= 30
  3915.9  397.26  3972.3  390.94  3979.6  387.46  4000.7  389.11  4029.0  385.27
  4085.7  383.31  4093.0  379.58  4184.8  373.49  4205.8  369.46  4227.3  368.89
  4234.1  364.87  4276.6  360.80  4290.8  357.06  4347.5  352.41  4375.8  352.90
  4411.0  345.61  4517.4  339.04  4607.9  336.48  4611.0  336.44  4842.8  332.36
  4984.4  334.37  5002.4  330.54  5005.2  330.04  5008.4  330.54  5009.1  334.07
  5028.6  333.65  5139.8  339.33  5238.8  363.98  5281.2  372.74  5295.3  373.61
#Mann=6,-1,0
  3915.9    0.05       0  4607.9    0.16       0  4611.0    0.05       0
  5002.4    0.03       0  5008.4    0.05       0  5028.6    0.12       0
Bank Sta=5002.4,5008.4
Exp/Cntr=0.3,0.1

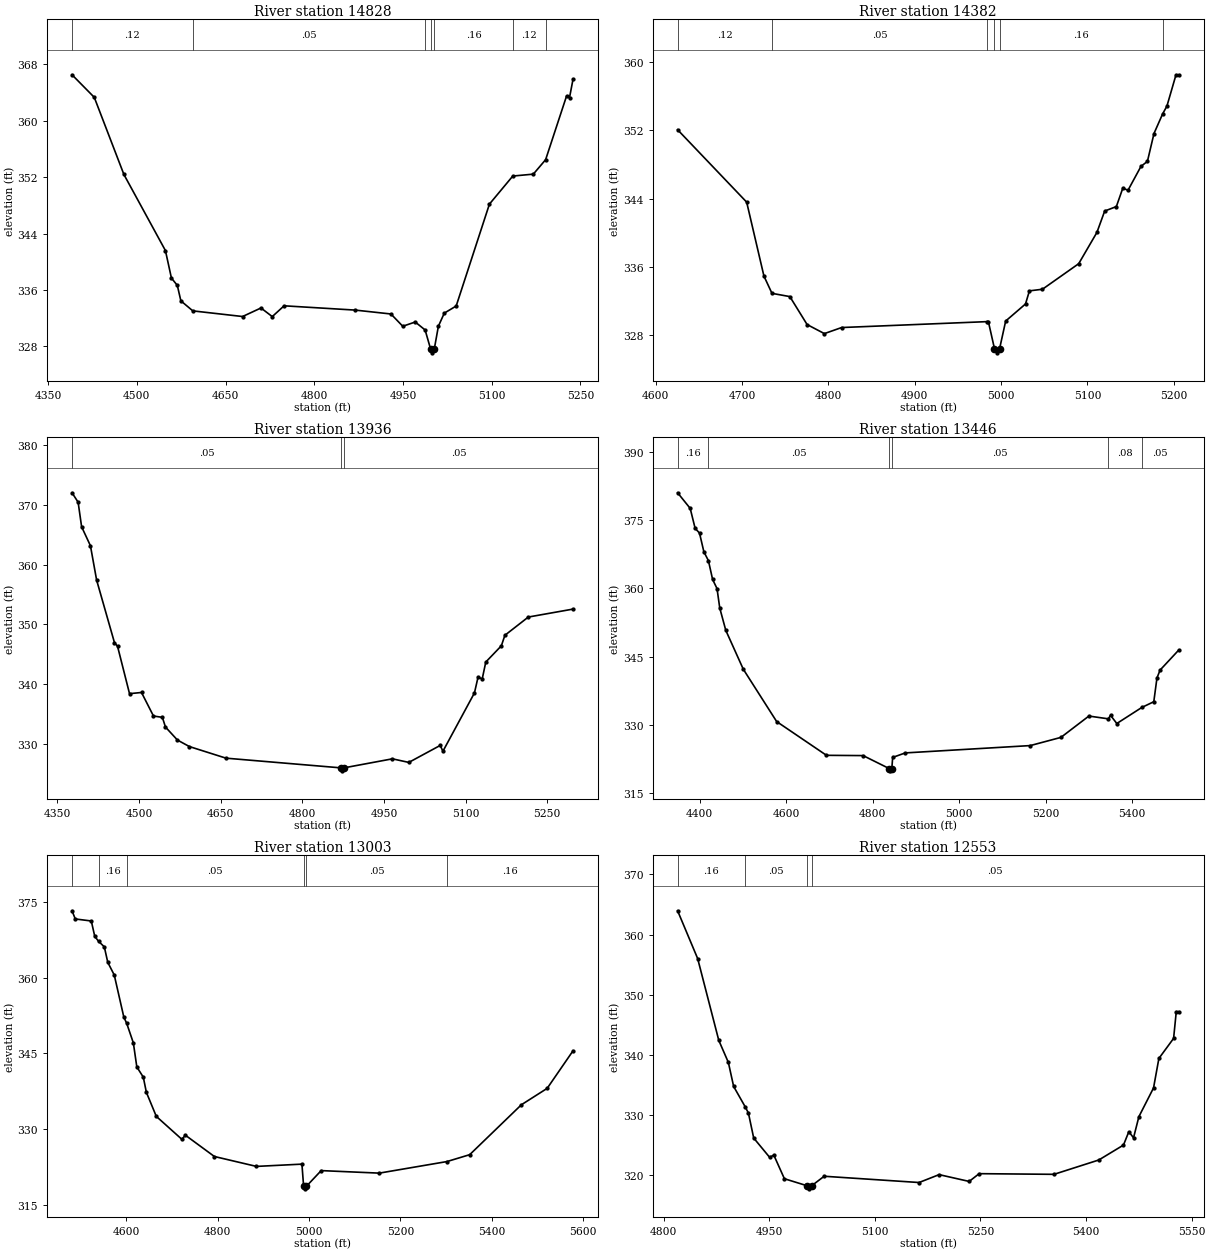
Type RM Length L Ch R = 1,14828,446,446,446
BEGIN DESCRIPTION:
UNT 158 IN CACR 25.0
END DESCRIPTION:
XS GIS Cut Line= 2
      3700527.08     10691390.99      3699682.68     10691455.95
#Sta/Elev= 30
  4390.5  366.52  4428.1  363.32  4478.2  352.38  4548.4  341.59  4558.5  337.70
  4568.5  336.65  4574.5  334.46  4594.7  333.04  4678.8  332.24  4709.9  333.45
  4729.0  332.23  4749.0  333.76  4869.4  333.15  4929.6  332.60  4949.6  330.86
  4970.7  331.46  4987.4  330.33  4996.8  327.59  4999.5  327.09  5002.8  327.59
  5009.8  330.86  5019.8  332.72  5039.9  333.73  5096.1  348.18  5135.6  352.16
  5170.3  352.43  5191.1  354.48  5226.5  363.51  5231.5  363.28  5237.4  365.88
#Mann=7,-1,0
  4390.5    0.12       0  4594.7    0.05       0  4987.4    0.16       0
  4996.8    0.07       0  5002.8    0.16       0  5135.6    0.12       0
  5191.1    0.05       0
Bank Sta=4996.8,5002.8
Exp/Cntr=0.3,0.1

Type RM Length L Ch R = 1,14382,446,446,446
BEGIN DESCRIPTION:
UNT 158 IN CACR 24.0
END DESCRIPTION:
XS GIS Cut Line= 3
      3700199.63     10691010.19      3699799.61     10691010.19
      3699649.61     10691110.19
#Sta/Elev= 30
  4625.3  352.05  4705.3  343.58  4725.3  334.93  4734.6  332.91  4755.3  332.53
  4775.3  329.26  4795.3  328.20  4815.3  328.91  4983.6  329.60  4985.3  329.59
  4992.3  326.45  4995.1  325.95  4998.3  326.45  5005.3  329.67  5028.3  331.67
  5032.8  333.20  5047.9  333.39  5089.9  336.38  5111.0  340.04  5120.0  342.54
  5133.5  343.06  5141.0  345.22  5147.0  344.97  5162.0  347.76  5169.5  348.35
  5177.1  351.61  5187.1  353.90  5192.1  354.82  5202.6  358.48  5205.6  358.48
#Mann=6,-1,0
  4625.3    0.12       0  4734.6    0.05       0  4983.6    0.16       0
  4992.3    0.07       0  4998.3    0.16       0  5187.1    0.05       0
Bank Sta=4992.3,4998.3
Exp/Cntr=0.3,0.1

Type RM Length L Ch R = 1,13936,490,490,490
BEGIN DESCRIPTION:
UNT 158 IN CACR 23.0
END DESCRIPTION:
XS GIS Cut Line= 4
      3700379.51     10690813.76      3699936.76     10690579.37
      3699719.75     10690562.00      3699590.79     10690716.75
#Sta/Elev= 30
  4377.2  372.01  4388.4  370.43  4394.8  366.32  4411.0  363.15  4422.4  357.39
  4455.1  346.95  4460.8  346.32  4482.8  338.40  4504.8  338.60  4526.8  334.66
  4543.1  334.44  4548.8  332.82  4570.8  330.64  4592.8  329.55  4660.0  327.61
  4870.7  325.99  4873.5  325.49  4876.7  325.99  4965.6  327.50  4995.7  326.90
  5053.4  329.74  5058.4  328.77  5116.3  338.53  5122.8  341.14  5130.6  340.89
  5137.1  343.69  5165.7  346.41  5172.2  348.17  5215.2  351.22  5297.3  352.55
#Mann=3,-1,0
  4377.2    0.05       0  4870.7    0.03       0  4876.7    0.05       0
Bank Sta=4870.7,4876.7
Exp/Cntr=0.3,0.1

Type RM Length L Ch R = 1,13446,443,443,443
BEGIN DESCRIPTION:
UNT 158 IN CACR 22.0
END DESCRIPTION:
XS GIS Cut Line= 3
      3700499.62     10690210.19      3699849.61     10690110.19
      3699449.57     10690410.22
#Sta/Elev= 30
  4349.3  381.01  4378.4  377.58  4389.8  373.19  4399.9  372.16  4410.0  368.04
  4420.5  366.09  4430.2  361.96  4440.4  359.95  4446.7  355.68  4460.6  350.79
  4501.1  342.23  4578.2  330.73  4693.3  323.31  4778.0  323.25  4838.3  320.40
  4841.0  319.90  4844.3  320.40  4846.3  322.85  4875.4  323.84  5164.2  325.45
  5235.1  327.25  5299.7  331.94  5344.7  331.33  5349.7  332.11  5364.2  330.30
  5422.2  333.84  5449.7  335.09  5457.0  340.30  5464.2  342.04  5507.0  346.41
#Mann=6,-1,0
  4349.3    0.16       0  4420.5    0.05       0  4838.3    0.03       0
  4844.3    0.05       0  5344.7    0.08       0  5422.2    0.05       0
Bank Sta=4838.3,4844.3
Exp/Cntr=0.3,0.1

Type RM Length L Ch R = 1,13003,450,450,450
BEGIN DESCRIPTION:
UNT 158 IN CACR 21.0
END DESCRIPTION:
XS GIS Cut Line= 3
      3700149.61     10689310.18      3699799.61     10689710.19
      3699399.61     10690110.19
#Sta/Elev= 30
  4481.0  373.25  4488.1  371.63  4523.2  371.23  4530.8  368.18  4539.2  367.20
  4551.7  366.11  4559.3  363.04  4573.5  360.53  4594.4  352.22  4600.8  350.95
  4615.3  347.10  4622.9  342.34  4637.1  340.31  4643.8  337.32  4665.6  332.55
  4721.6  328.01  4729.2  328.83  4792.8  324.61  4884.9  322.65  4984.5  323.10
  4988.2  318.71  4990.9  318.21  4994.2  318.71  5026.7  321.82  5153.9  321.32
  5302.1  323.61  5351.9  324.97  5465.1  334.85  5521.6  338.10  5578.2  345.53
#Mann=6,-1,0
  4481.0    0.05       0  4539.2    0.16       0  4600.8    0.05       0
  4988.2    0.03       0  4994.2    0.05       0  5302.1    0.16       0
Bank Sta=4988.2,4994.2
Exp/Cntr=0.3,0.1

Type RM Length L Ch R = 1,12553,488,488,488
BEGIN DESCRIPTION:
UNT 158 IN CACR 20.0
END DESCRIPTION:
XS GIS Cut Line= 3
      3699899.57     10689160.22      3699749.61     10689260.19
      3699349.64     10689610.16
#Sta/Elev= 30
  4819.8  363.96  4848.3  356.02  4878.3  342.43  4891.9  338.77  4899.4  334.78
  4915.6  331.44  4920.4  330.36  4927.9  326.21  4950.5  323.01  4956.5  323.37
  4971.5  319.45  5004.1  318.27  5006.9  317.77  5010.1  318.27  5028.0  319.86
  5162.8  318.82  5191.3  320.13  5234.0  319.00  5248.2  320.29  5354.5  320.18
  5418.1  322.56  5453.2  325.04  5460.8  327.26  5467.5  326.25  5475.1  329.76
  5495.9  334.53  5503.5  339.43  5524.4  342.76  5528.2  347.20  5531.5  347.20
#Mann=4,-1,0
  4819.8    0.16       0  4915.6    0.05       0  5004.1    0.03       0
  5010.1    0.05       0
Bank Sta=5004.1,5010.1
Exp/Cntr=0.3,0.1

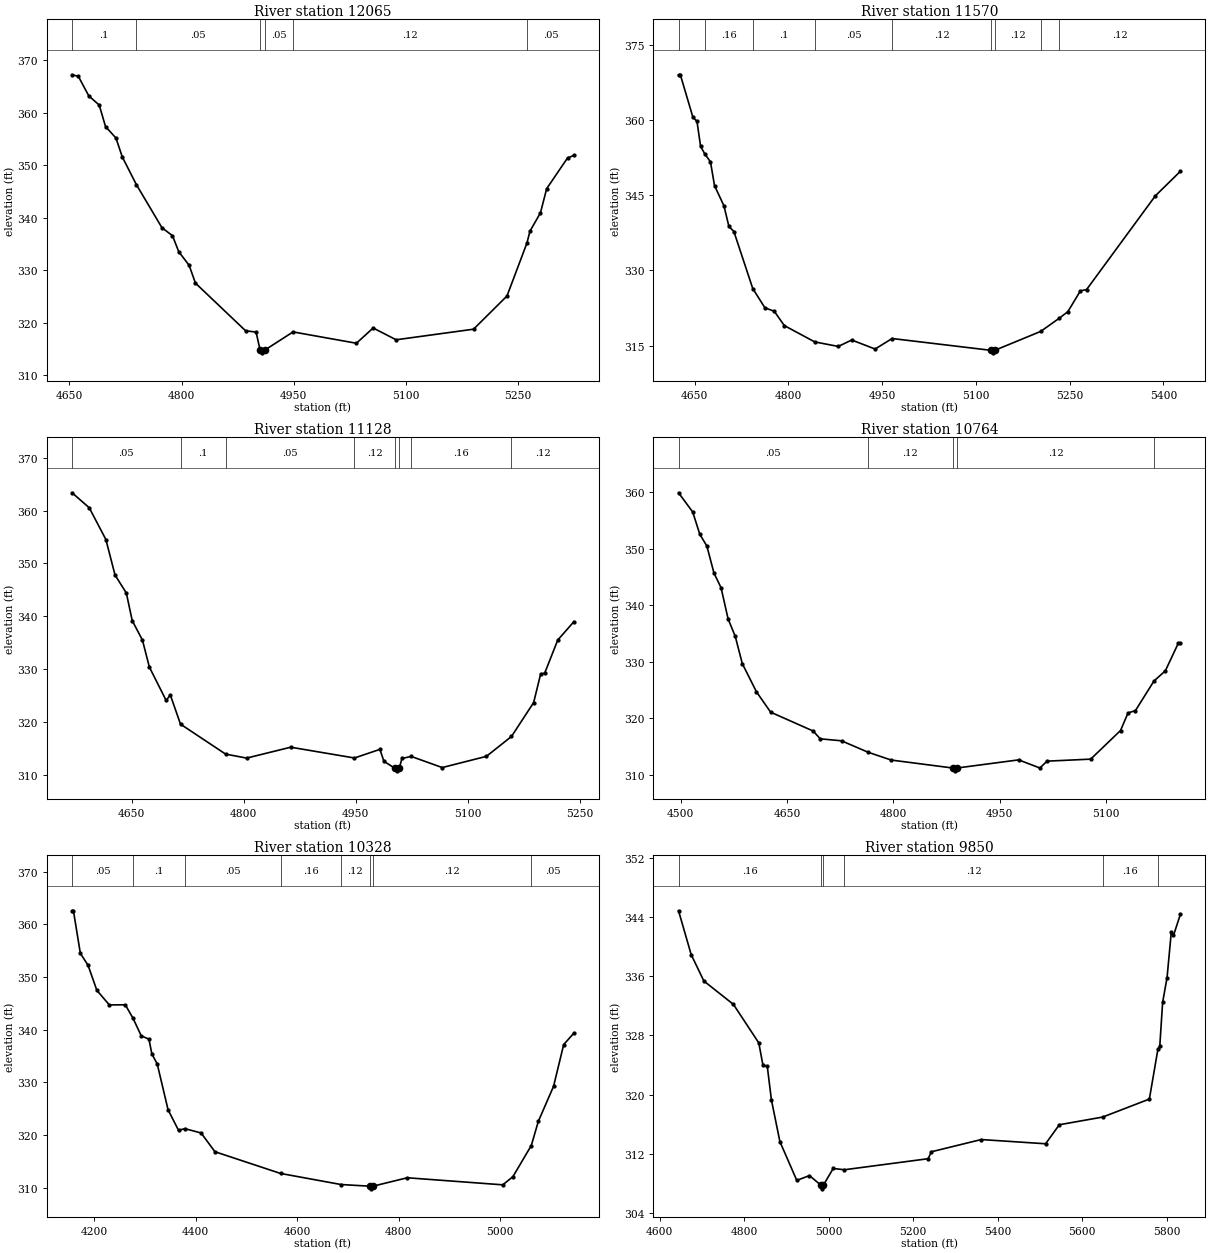
Type RM Length L Ch R = 1,12065,495,495,495
BEGIN DESCRIPTION:
UNT 158 IN CACR 19.0
END DESCRIPTION:
XS GIS Cut Line= 3
      3699799.61     10688760.19      3699499.61     10688910.19
      3699199.63     10689060.18
#Sta/Elev= 30
  4653.6  367.27  4662.0  366.97  4676.0  363.23  4689.9  361.50  4698.3  357.40
  4712.3  355.20  4720.7  351.61  4739.5  346.34  4773.8  338.09  4787.8  336.59
  4796.2  333.53  4810.1  330.93  4818.5  327.54  4885.6  318.44  4899.6  318.20
  4905.0  314.74  4907.7  314.24  4911.0  314.74  4949.0  318.23  5033.7  316.07
  5056.1  318.98  5086.8  316.73  5190.3  318.75  5235.0  325.08  5261.7  335.19
  5265.7  337.44  5279.7  340.93  5288.1  345.56  5316.0  351.42  5324.4  351.88
#Mann=6,-1,0
  4653.6     0.1       0  4739.5    0.05       0  4905.0    0.07       0
  4911.0    0.05       0  4949.0    0.12       0  5261.7    0.05       0
Bank Sta=4905,4911
Exp/Cntr=0.3,0.1

Type RM Length L Ch R = 1,11570,442,442,442
BEGIN DESCRIPTION:
UNT 158 IN CACR 18.0
END DESCRIPTION:
XS GIS Cut Line= 3
      3699849.62     10688610.20      3699499.61     10688410.19
      3699099.64     10688410.19
#Sta/Elev= 30
  4624.1  369.07  4627.0  369.07  4647.2  360.56  4653.6  359.79  4659.4  354.78
  4666.4  353.21  4675.2  351.70  4681.7  346.94  4696.8  342.90  4704.7  338.80
  4712.7  337.78  4742.9  326.39  4762.3  322.56  4777.4  321.85  4793.3  319.01
  4842.1  315.74  4879.7  314.84  4901.3  316.12  4938.7  314.32  4965.9  316.42
  5124.2  314.06  5127.0  313.56  5130.2  314.06  5203.6  317.83  5233.5  320.47
  5247.2  321.78  5267.2  325.92  5277.2  326.20  5387.2  344.90  5427.2  349.79
#Mann=9,-1,0
  4624.1    0.05       0  4666.4    0.16       0  4742.9     0.1       0
  4842.1    0.05       0  4965.9    0.12       0  5124.2    0.07       0
  5130.2    0.12       0  5203.6    0.16       0  5233.5    0.12       0
Bank Sta=5124.2,5130.2
Exp/Cntr=0.3,0.1

Type RM Length L Ch R = 1,11128,364,364,364
BEGIN DESCRIPTION:
UNT 158 IN CACR 17.0
END DESCRIPTION:
XS GIS Cut Line= 3
      3699799.59     10687810.20      3699449.61     10688010.19
      3699199.56     10688110.21
#Sta/Elev= 30
  4570.0  363.36  4593.0  360.53  4615.3  354.52  4627.6  347.79  4642.7  344.41
  4650.6  339.18  4664.3  335.49  4673.6  330.38  4696.0  324.09  4701.7  325.10
  4715.3  319.59  4775.7  313.93  4803.9  313.17  4863.0  315.23  4948.4  313.19
  4982.5  314.82  4987.9  312.56  5002.4  311.26  5005.2  310.76  5008.4  311.26
  5012.1  313.10  5024.4  313.49  5066.0  311.38  5125.2  313.50  5158.8  317.26
  5188.5  323.67  5197.9  329.08  5203.3  329.23  5220.8  335.50  5242.4  338.97
#Mann=8,-1,0
  4570.0    0.05       0  4715.3     0.1       0  4775.7    0.05       0
  4948.4    0.12       0  5002.4    0.07       0  5008.4    0.12       0
  5024.4    0.16       0  5158.8    0.12       0
Bank Sta=5002.4,5008.4
Exp/Cntr=0.3,0.1

Type RM Length L Ch R = 1,10764,436,436,436
BEGIN DESCRIPTION:
UNT 158 IN CACR 16.0
END DESCRIPTION:
XS GIS Cut Line= 3
      3699749.65     10687710.19      3699199.61     10687710.19
      3699049.57     10687760.20
#Sta/Elev= 30
  4496.7  359.87  4516.7  356.48  4526.7  352.54  4536.7  350.45  4546.7  345.68
  4556.7  343.09  4566.7  337.54  4576.7  334.51  4586.7  329.66  4606.7  324.68
  4626.7  321.08  4686.7  317.75  4696.7  316.37  4726.7  316.02  4764.2  314.00
  4796.7  312.62  4883.7  311.21  4886.5  310.71  4889.7  311.21  4976.7  312.65
  5006.7  311.21  5016.7  312.42  5078.4  312.78  5120.5  317.84  5131.1  320.94
  5141.6  321.37  5167.7  326.59  5183.8  328.40  5202.2  333.31  5204.9  333.31
#Mann=5,-1,0
  4496.7    0.05       0  4764.2    0.12       0  4883.7    0.07       0
  4889.7    0.12       0  5167.7    0.05       0
Bank Sta=4883.7,4889.7
Exp/Cntr=0.3,0.1

Type RM Length L Ch R = 1,10328,478,478,478
BEGIN DESCRIPTION:
UNT 158 IN CACR 15.0
END DESCRIPTION:
XS GIS Cut Line= 3
      3699799.65     10687610.20      3698999.61     10687360.19
      3698849.60     10687360.19
#Sta/Elev= 30
  4156.8  362.56  4159.5  362.56  4173.1  354.49  4188.3  352.22  4205.6  347.47
  4230.2  344.70  4261.6  344.73  4276.6  342.22  4293.0  338.85  4308.2  338.20
  4314.0  335.40  4324.5  333.50  4345.9  324.80  4366.4  320.93  4379.0  321.23
  4410.9  320.42  4438.1  316.86  4567.3  312.74  4686.3  310.64  4743.2  310.32
  4745.9  309.82  4749.2  310.32  4816.9  311.92  5005.0  310.58  5025.0  312.13
  5061.2  318.04  5075.0  322.61  5105.0  329.26  5125.0  337.19  5145.0  339.35
#Mann=8,-1,0
  4156.8    0.05       0  4276.6     0.1       0  4379.0    0.05       0
  4567.3    0.16       0  4686.3    0.12       0  4743.2    0.07       0
  4749.2    0.12       0  5061.2    0.05       0
Bank Sta=4743.2,4749.2
Exp/Cntr=0.3,0.1

Type RM Length L Ch R = 1,9850,433,433,433
BEGIN DESCRIPTION:
UNT 158 IN CACR 14.0
END DESCRIPTION:
XS GIS Cut Line= 3
      3699649.59     10687010.19      3699299.61     10687010.19
      3698499.64     10686760.20
#Sta/Elev= 30
  4644.2  344.83  4674.2  338.90  4704.2  335.34  4774.2  332.18  4834.2  326.98
  4844.2  323.93  4854.2  323.86  4864.2  319.25  4884.2  313.64  4924.2  308.40
  4954.2  309.05  4981.2  307.76  4983.9  307.26  4987.2  307.76  5010.4  310.01
  5037.1  309.84  5235.1  311.33  5243.0  312.27  5360.9  313.92  5513.3  313.35
  5545.8  315.92  5648.6  316.96  5759.0  319.39  5779.4  326.18  5783.6  326.50
  5790.4  332.46  5800.9  335.80  5810.9  341.97  5816.1  341.49  5832.3  344.33
#Mann=6,-1,0
  4644.2    0.16       0  4981.2    0.07       0  4987.2    0.16       0
  5037.1    0.12       0  5648.6    0.16       0  5779.4    0.12       0
Bank Sta=4981.2,4987.2
Exp/Cntr=0.3,0.1

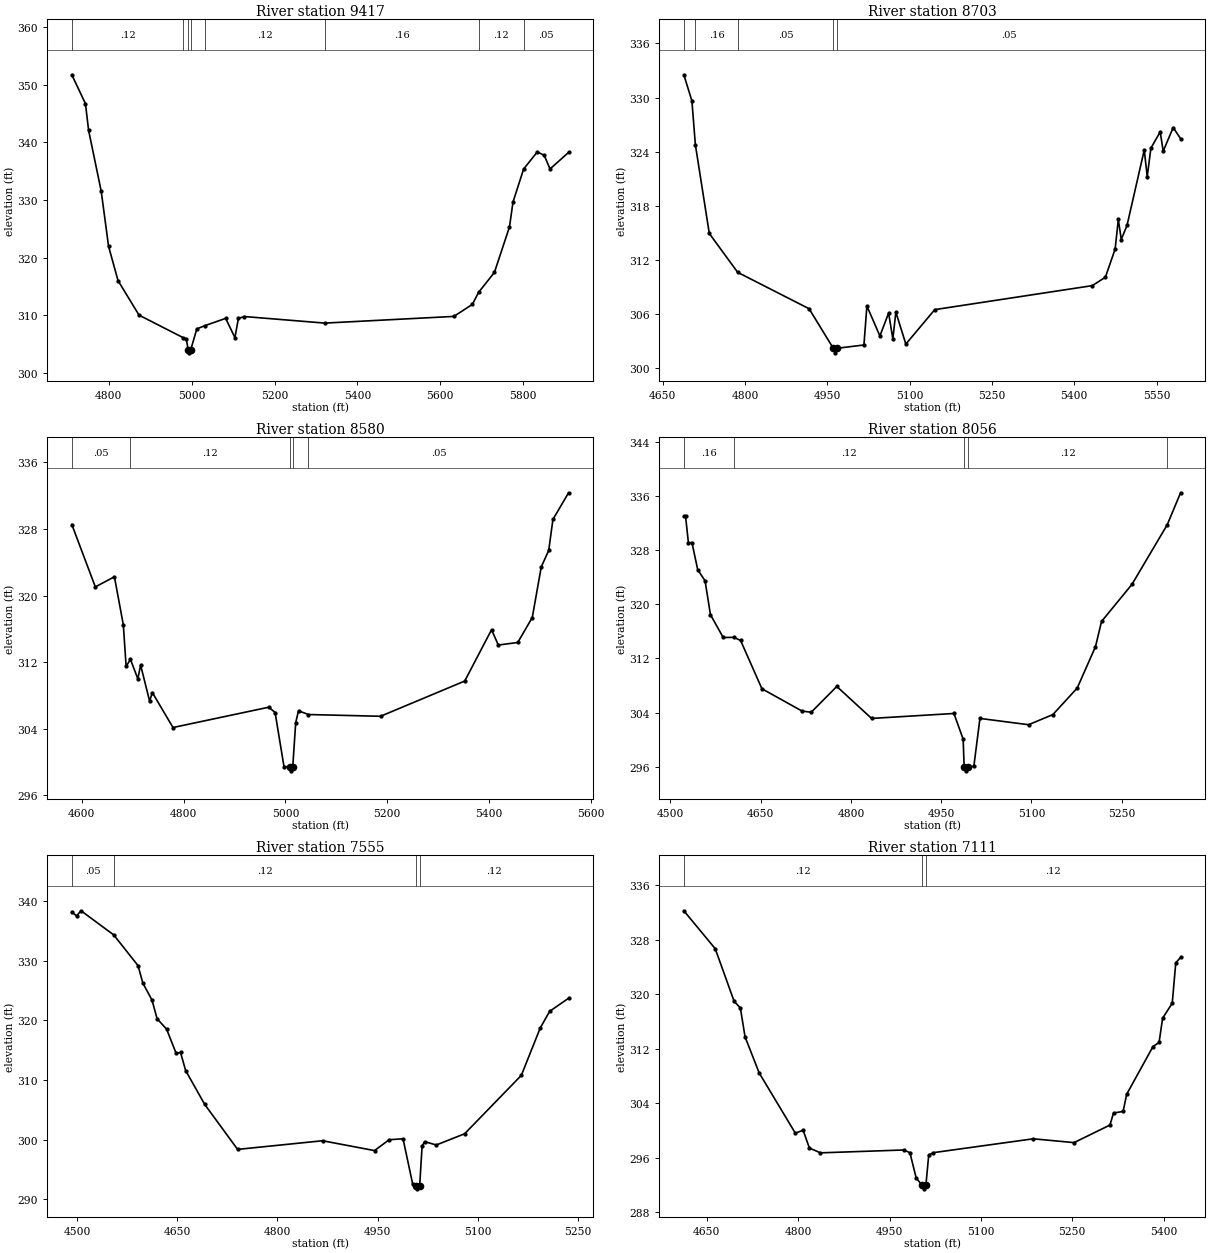
Type RM Length L Ch R = 1,9417,714,714,714
BEGIN DESCRIPTION:
UNT 158 IN CACR 13.0
END DESCRIPTION:
XS GIS Cut Line= 3
      3699749.57     10686660.18      3699449.61     10686610.19
      3698649.63     10686210.20
#Sta/Elev= 30
  4710.9  351.71  4743.8  346.70  4751.4  342.07  4781.8  331.52  4799.6  321.94
  4822.4  316.00  4873.1  310.01  4979.6  306.10  4987.1  305.89  4991.7  303.97
  4994.5  303.47  4997.7  303.97  5012.5  307.63  5032.5  308.20  5082.1  309.45
  5104.4  306.11  5112.8  309.43  5126.8  309.77  5321.1  308.63  5632.7  309.79
  5677.4  311.88  5692.4  313.97  5730.5  317.42  5766.9  325.33  5775.3  329.62
  5801.0  335.36  5834.0  338.33  5850.7  337.73  5864.7  335.37  5909.4  338.23
#Mann=8,-1,0
  4710.9    0.12       0  4979.6    0.16       0  4991.7    0.07       0
  4997.7    0.16       0  5032.5    0.12       0  5321.1    0.16       0
  5692.4    0.12       0  5801.0    0.05       0
Bank Sta=4991.7,4997.7
Exp/Cntr=0.3,0.1

Type RM Length L Ch R = 1,8703,123,123,123
BEGIN DESCRIPTION:
UNT 158 IN CACR 12.0
END DESCRIPTION:
XS GIS Cut Line= 2
      3699643.14     10685845.24      3698809.78     10686199.42
#Sta/Elev= 30
  4688.3  332.52  4703.0  329.63  4709.3  324.78  4734.7  314.93  4786.5  310.62
  4916.6  306.59  4960.8  302.20  4963.5  301.70  4966.8  302.20  5016.6  302.57
  5022.0  306.89  5045.7  303.57  5061.6  306.11  5069.3  303.24  5074.8  306.21
  5093.0  302.67  5145.7  306.49  5433.0  309.15  5456.7  310.08  5474.5  313.20
  5480.3  316.48  5485.7  314.26  5496.2  315.83  5527.6  324.19  5533.0  321.23
  5539.7  324.39  5556.7  326.19  5562.1  324.05  5580.3  326.67  5593.8  325.44
#Mann=5,-1,0
  4688.3    0.05       0  4709.3    0.16       0  4786.5    0.05       0
  4960.8    0.04       0  4966.8    0.05       0
Bank Sta=4960.8,4966.8
Exp/Cntr=0.3,0.1

Type RM Length L Ch R = 1,8580,524,524,524
BEGIN DESCRIPTION:
UNT 158 IN CACR 11.0
END DESCRIPTION:
XS GIS Cut Line= 2
      3699731.65     10685670.78      3698844.11     10686076.81
#Sta/Elev= 30
  4580.4  328.53  4626.6  321.04  4664.1  322.26  4681.6  316.49  4687.1  311.50
  4695.6  312.34  4710.1  310.01  4715.6  311.65  4733.2  307.34  4738.7  308.35
  4779.2  304.16  4967.5  306.60  4979.8  305.96  4997.3  299.46  5008.5  299.46
  5011.3  298.96  5014.5  299.46  5020.3  304.76  5025.8  306.17  5045.3  305.72
  5187.0  305.51  5352.4  309.74  5405.1  315.90  5418.4  314.06  5456.6  314.37
  5485.1  317.36  5502.7  323.43  5517.4  325.42  5525.7  329.14  5556.4  332.34
#Mann=5,-1,0
  4580.4    0.05       0  4695.6    0.12       0  5008.5    0.07       0
  5014.5    0.12       0  5045.3    0.05       0
Bank Sta=5008.5,5014.5
Exp/Cntr=0.3,0.1

Type RM Length L Ch R = 1,8056,501,501,501
BEGIN DESCRIPTION:
UNT 158 IN CACR 10.0
END DESCRIPTION:
XS GIS Cut Line= 3
      3699749.57     10685610.17      3699349.61     10685360.19
      3698999.62     10685310.19
#Sta/Elev= 30
  4522.5  332.95  4525.4  332.95  4530.1  329.07  4536.0  329.09  4545.5  325.11
  4557.8  323.44  4566.7  318.45  4587.9  315.08  4605.8  315.10  4616.8  314.64
  4652.2  307.51  4718.8  304.22  4734.1  304.04  4776.6  307.85  4834.4  303.13
  4971.2  303.86  4986.5  300.07  4988.2  295.89  4991.0  295.39  4994.2  295.89
  5004.3  296.08  5014.4  303.13  5095.2  302.20  5135.6  303.70  5176.0  307.62
  5206.3  313.71  5216.4  317.45  5266.9  322.92  5325.5  331.72  5347.7  336.45
#Mann=5,-1,0
  4522.5    0.16       0  4605.8    0.12       0  4988.2    0.07       0
  4994.2    0.12       0  5325.5    0.16       0
Bank Sta=4988.2,4994.2
Exp/Cntr=0.3,0.1

Type RM Length L Ch R = 1,7555,444,444,444
BEGIN DESCRIPTION:
UNT 158 IN CACR 9.0
END DESCRIPTION:
XS GIS Cut Line= 3
      3699649.63     10684560.17      3699249.61     10684910.19
      3699099.59     10685060.21
#Sta/Elev= 30
  4492.2  338.16  4499.3  337.50  4506.0  338.36  4555.0  334.31  4591.4  329.16
  4598.5  326.26  4612.3  323.38  4619.9  320.26  4634.1  318.53  4648.4  314.46
  4655.0  314.61  4662.6  311.59  4691.1  305.92  4740.4  298.37  4867.6  299.82
  4945.4  298.17  4967.3  299.99  4988.1  300.15  5002.4  292.62  5007.0  292.26
  5009.7  291.76  5013.0  292.26  5016.6  298.90  5020.4  299.67  5037.9  299.11
  5080.3  300.99  5165.2  310.78  5193.4  318.69  5207.6  321.51  5235.9  323.70
#Mann=4,-1,0
  4492.2    0.05       0  4555.0    0.12       0  5007.0    0.07       0
  5013.0    0.12       0
Bank Sta=5007,5013
Exp/Cntr=0.3,0.1

Type RM Length L Ch R = 1,7111,481,481,481
BEGIN DESCRIPTION:
UNT 158 IN CACR 8.0
END DESCRIPTION:
XS GIS Cut Line= 3
      3699499.60     10684410.19      3699099.61     10684510.19
      3698749.62     10684710.18
#Sta/Elev= 30
  4612.4  332.23  4663.9  326.67  4694.9  318.96  4705.2  317.97  4712.9  313.73
  4736.1  308.44  4795.4  299.61  4808.2  300.03  4818.5  297.43  4836.6  296.72
  4973.2  297.14  4983.5  296.75  4993.8  293.03  5003.7  291.94  5006.4  291.44
  5009.7  291.94  5014.4  296.41  5022.1  296.75  5186.0  298.78  5252.9  298.22
  5311.9  300.80  5317.7  302.56  5333.5  302.80  5339.3  305.31  5382.5  312.31
  5392.5  312.91  5398.3  316.47  5414.1  318.67  5419.9  324.59  5427.8  325.39
#Mann=3,-1,0
  4612.4    0.12       0  5003.7    0.07       0  5009.7    0.12       0
Bank Sta=5003.7,5009.7
Exp/Cntr=0.3,0.1

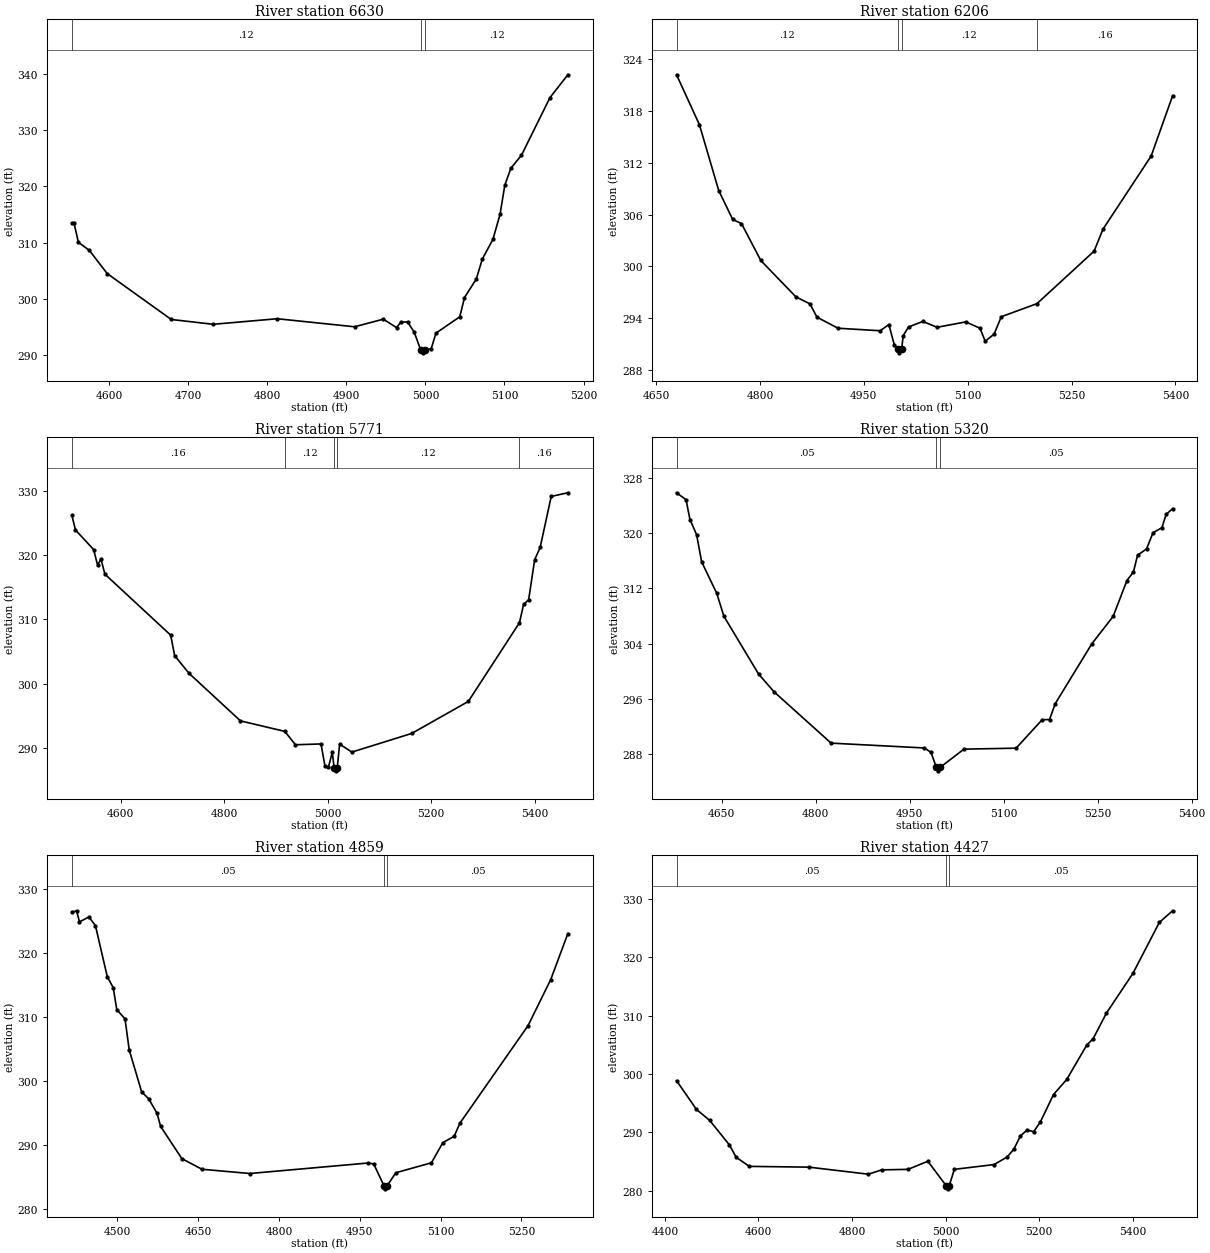
Type RM Length L Ch R = 1,6630,424,424,424
BEGIN DESCRIPTION:
UNT 158 IN CACR 7.0
END DESCRIPTION:
XS GIS Cut Line= 3
      3699399.58     10684360.18      3698999.61     10684160.19
      3698849.58     10684060.17
#Sta/Elev= 30
  4552.6  313.49  4555.4  313.49  4561.0  310.06  4574.9  308.62  4597.3  304.51
  4678.4  296.33  4731.5  295.47  4812.5  296.46  4910.3  295.03  4946.7  296.38
  4963.4  294.88  4969.0  295.86  4977.4  295.89  4985.8  294.07  4994.0  290.89
  4996.7  290.39  5000.0  290.89  5007.3  291.13  5013.3  293.90  5043.4  296.80
  5049.4  300.23  5064.4  303.55  5071.9  307.07  5085.4  310.60  5094.4  315.06
  5100.4  320.22  5108.0  323.23  5121.5  325.57  5157.5  335.81  5180.1  339.88
#Mann=3,-1,0
  4552.6    0.12       0  4994.0    0.07       0  5000.0    0.12       0
Bank Sta=4994,5000
Exp/Cntr=0.3,0.1

Type RM Length L Ch R = 1,6206,435,435,435
BEGIN DESCRIPTION:
UNT 158 IN CACR 6.0
END DESCRIPTION:
XS GIS Cut Line= 3
      3699549.64     10683760.18      3699249.61     10683810.19
      3698849.59     10683910.19
#Sta/Elev= 30
  4679.5  322.13  4712.5  316.37  4740.4  308.77  4760.6  305.43  4773.3  304.95
  4801.2  300.69  4851.9  296.49  4872.2  295.68  4882.3  294.15  4912.7  292.87
  4973.5  292.58  4986.2  293.29  4994.0  290.95  4998.7  290.53  5001.5  290.03
  5004.7  290.53  5006.9  292.02  5014.6  293.02  5035.2  293.65  5055.8  292.98
  5097.1  293.60  5117.7  292.88  5125.4  291.36  5138.3  292.21  5148.6  294.20
  5200.1  295.71  5282.6  301.77  5295.5  304.31  5365.1  312.76  5396.0  319.70
#Mann=4,-1,0
  4679.5    0.12       0  4998.7    0.07       0  5004.7    0.12       0
  5200.1    0.16       0
Bank Sta=4998.7,5004.7
Exp/Cntr=0.3,0.1

Type RM Length L Ch R = 1,5771,451,451,451
BEGIN DESCRIPTION:
UNT 158 IN CACR 5.0
END DESCRIPTION:
XS GIS Cut Line= 3
      3699599.59     10683710.18      3699199.61     10683360.19
      3698799.60     10683210.18
#Sta/Elev= 30
  4505.6  326.21  4512.7  323.88  4547.8  320.83  4555.4  318.43  4562.1  319.34
  4569.6  317.01  4696.8  307.53  4704.4  304.35  4731.9  301.63  4831.6  294.22
  4917.3  292.59  4937.9  290.51  4987.3  290.64  4994.9  287.22  5001.5  287.01
  5009.1  289.31  5012.7  286.96  5015.5  286.46  5018.7  286.96  5023.3  290.61
  5046.9  289.37  5162.6  292.27  5272.0  297.24  5370.9  309.47  5378.8  312.31
  5388.6  313.03  5400.2  319.24  5410.9  321.18  5432.2  329.08  5464.3  329.65
#Mann=5,-1,0
  4505.6    0.16       0  4917.3    0.12       0  5012.7    0.07       0
  5018.7    0.12       0  5370.9    0.16       0
Bank Sta=5012.7,5018.7
Exp/Cntr=0.3,0.1

Type RM Length L Ch R = 1,5320,461,461,461
BEGIN DESCRIPTION:
UNT 158 IN CACR 4.0
END DESCRIPTION:
XS GIS Cut Line= 3
      3699749.60     10683110.19      3699349.61     10682960.19
      3698999.61     10682860.19
#Sta/Elev= 30
  4578.3  325.83  4593.4  324.83  4599.7  321.96  4610.3  319.76  4618.3  315.84
  4642.4  311.28  4653.9  307.94  4709.1  299.60  4734.0  297.01  4824.8  289.60
  4973.5  288.90  4984.1  288.27  4992.7  286.09  4995.5  285.59  4998.7  286.09
  5036.7  288.73  5119.9  288.87  5161.5  292.99  5173.2  293.01  5182.3  295.31
  5240.8  303.99  5274.6  307.93  5296.7  313.13  5307.1  314.39  5313.6  316.79
  5327.9  317.70  5338.3  320.05  5352.6  320.79  5359.1  322.69  5369.5  323.53
#Mann=3,-1,0
  4578.3    0.05       0  4992.7    0.03       0  4998.7    0.05       0
Bank Sta=4992.7,4998.7
Exp/Cntr=0.3,0.1

Type RM Length L Ch R = 1,4859,432,432,432
BEGIN DESCRIPTION:
UNT 158 IN CACR 3.0
END DESCRIPTION:
XS GIS Cut Line= 3
      3699849.59     10682760.18      3699299.61     10682510.19
      3698999.57     10682610.20
#Sta/Elev= 30
  4415.7  326.30  4424.5  326.54  4430.0  324.81  4447.5  325.58  4459.6  324.22
  4481.6  316.26  4492.6  314.56  4499.2  311.15  4514.5  309.69  4522.2  304.89
  4545.3  298.33  4558.5  297.23  4573.9  294.98  4580.5  292.95  4620.0  287.91
  4657.3  286.26  4746.3  285.60  4964.9  287.23  4975.9  287.10  4994.9  283.71
  4997.6  283.21  5000.9  283.71  5017.1  285.72  5083.1  287.27  5104.2  290.41
  5125.2  291.39  5135.8  293.43  5262.3  308.64  5304.4  315.82  5336.1  322.97
#Mann=3,-1,0
  4415.7    0.05       0  4994.9    0.03       0  5000.9    0.05       0
Bank Sta=4994.9,5000.9
Exp/Cntr=0.3,0.1

Type RM Length L Ch R = 1,4427,404,404,404
BEGIN DESCRIPTION:
UNT 158 IN CACR 2.0
END DESCRIPTION:
XS GIS Cut Line= 3
      3699799.64     10682510.22      3699399.61     10682110.19
      3699049.61     10681760.19
#Sta/Elev= 30
  4424.8  298.87  4467.3  293.95  4495.6  292.07  4538.0  287.84  4552.1  285.75
  4580.4  284.18  4707.7  284.05  4835.0  282.84  4863.3  283.58  4919.8  283.67
  4962.2  285.06  5001.7  280.83  5004.4  280.33  5007.7  280.83  5018.8  283.67
  5103.7  284.49  5132.0  285.80  5146.1  287.14  5160.2  289.41  5174.4  290.41
  5188.5  290.13  5202.7  291.79  5230.9  296.50  5259.2  299.09  5301.7  304.94
  5315.8  306.10  5344.1  310.47  5400.7  317.27  5457.2  326.01  5485.5  328.00
#Mann=3,-1,0
  4424.8    0.05       0  5001.7    0.03       0  5007.7    0.05       0
Bank Sta=5001.7,5007.7
Exp/Cntr=0.3,0.1

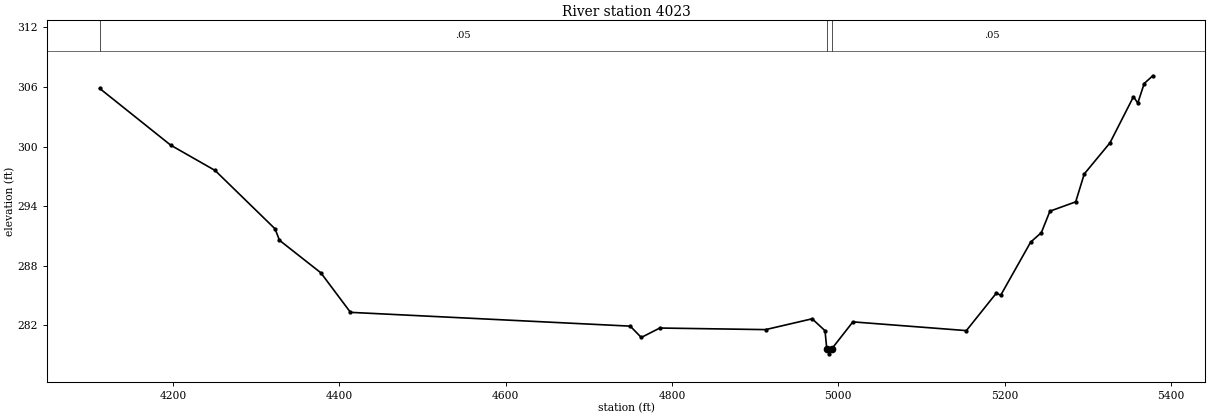
Type RM Length L Ch R = 1,4023,0,0,0
BEGIN DESCRIPTION:
UNT 158 IN CACR 1.0
END DESCRIPTION:
XS GIS Cut Line= 3
      3699899.62     10682560.21      3699599.61     10681760.19
      3699199.64     10681660.20
#Sta/Elev= 30
  4111.6  305.86  4197.1  300.14  4250.5  297.59  4322.6  291.71  4327.9  290.56
  4377.7  287.28  4413.3  283.30  4749.8  281.91  4763.1  280.77  4785.4  281.72
  4912.6  281.56  4968.6  282.65  4984.1  281.45  4986.2  279.62  4989.0  279.12
  4992.2  279.62  5017.6  282.34  5154.1  281.46  5190.2  285.24  5195.4  285.02
  5231.4  290.37  5244.3  291.33  5254.6  293.49  5285.6  294.43  5295.9  297.24
  5326.8  300.37  5355.1  305.02  5360.3  304.38  5368.0  306.35  5378.3  307.13
#Mann=3,-1,0
  4111.6    0.05       0  4986.2    0.03       0  4992.2    0.05       0
Bank Sta=4986.2,4992.2
Exp/Cntr=0.3,0.1

Chan Stop Cuts=-1