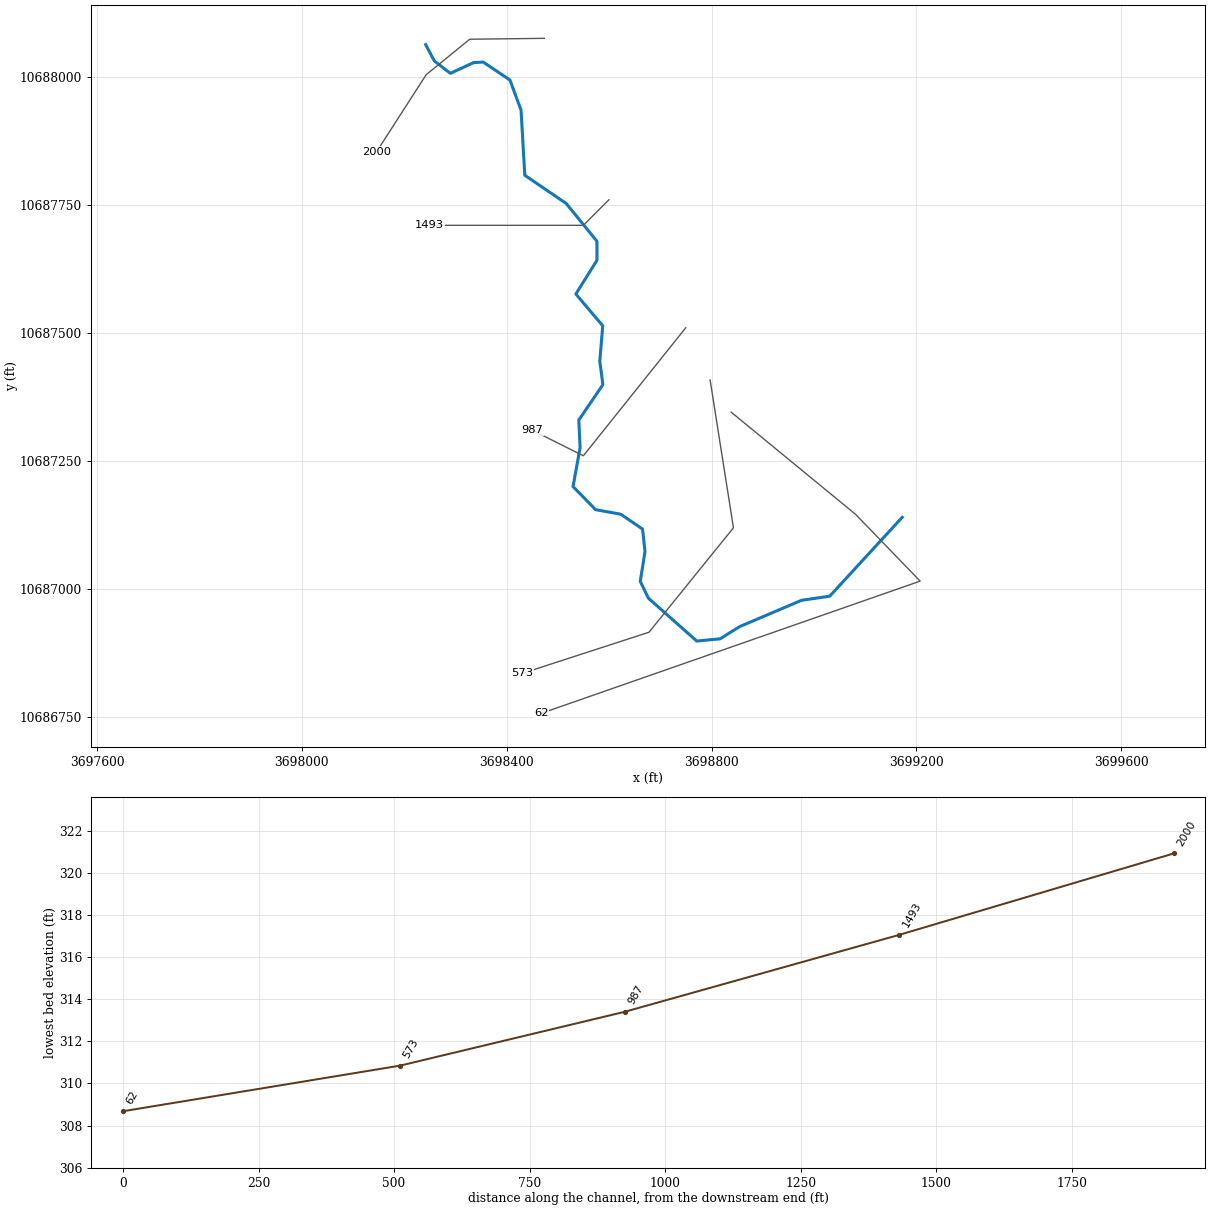
--- UNT 159 IN CACR.prj (project) ---

Proj Title=UNT 159 IN CACR Base Level Engineering
Current Plan=p01
Default Exp/Contr=0.3,0.1
English Units
Geom File=g01
Flow File=f01
Plan File=p01
BEGIN DESCRIPTION:
UNT 159 IN CACR
END DESCRIPTION:

--- UNT 159 IN CACR.p01 (plan) ---

Plan Title=Multiple Run
Short Identifier=Multiple
Geom File=g01
Flow File=f01
Subcritical Flow
K Sum by GR= 0
Std Step Tol= 0.01
Critical Tol= 0.01
Num of Std Step Trials= 20
Max Error Tol= 0.3
Flow Tol Ratio= 0.001
Split Flow NTrial= 30
Split Flow Tol= 0.02
Split Flow Ratio= 0.02
Log Output Level= 0
Friction Slope Method= 1
Unsteady Friction Slope Method= 2
Unsteady Bridges Friction Slope Method= 1
Parabolic Critical Depth
Global Vel Dist=  1 , 1 , 1
Global Log Level= 0
CheckData=True
Encroach Param= -1, 0, 0, 0
BEGIN DESCRIPTION:
Multiple Run
END DESCRIPTION:

--- UNT 159 IN CACR.f01 (steady flow) ---

Flow Title=Multiple
Number of Profiles=7
Profile Names=10-year,25-year,50-year,1pct_min,100-year,1pct_plu,500-year
River Rch & RM= UNT 159 IN CACR,Reach-1,2000
     377     499     598     527     713     964    1017
River Rch & RM= UNT 159 IN CACR,Reach-1,62
    1157    1633    2040    1870    2529    3421    3906
Boundary for River Rch & Prof#=UNT 159 IN CACR,Reach-1,1
Up Type=0
Dn Type=3
Dn Slope=0.005
Boundary for River Rch & Prof#=UNT 159 IN CACR,Reach-1,2
Up Type=0
Dn Type=3
Dn Slope=0.005
Boundary for River Rch & Prof#=UNT 159 IN CACR,Reach-1,3
Up Type=0
Dn Type=3
Dn Slope=0.005
Boundary for River Rch & Prof#=UNT 159 IN CACR,Reach-1,4
Up Type=0
Dn Type=3
Dn Slope=0.005
Boundary for River Rch & Prof#=UNT 159 IN CACR,Reach-1,5
Up Type=0
Dn Type=3
Dn Slope=0.005
Boundary for River Rch & Prof#=UNT 159 IN CACR,Reach-1,6
Up Type=0
Dn Type=3
Dn Slope=0.005
Boundary for River Rch & Prof#=UNT 159 IN CACR,Reach-1,7
Up Type=0
Dn Type=3
Dn Slope=0.005

--- UNT 159 IN CACR.g01 (geometry) ---

Geom Title=Existing Conditions

River Reach=UNT 159 IN CACR,Reach-1
Reach XY= 30
      3698241.75     10688063.00      3698258.75     10688031.00
      3698290.00     10688007.00      3698335.50     10688028.00
      3698354.00     10688029.00      3698406.25     10687994.00
      3698428.00     10687935.00      3698435.25     10687808.00
      3698516.00     10687753.00      3698576.25     10687679.00
      3698576.25     10687642.00      3698535.00     10687576.00
      3698587.50     10687514.00      3698581.75     10687445.00
      3698587.75     10687399.00      3698540.75     10687330.00
      3698543.25     10687276.00      3698529.50     10687200.00
      3698573.50     10687155.00      3698622.75     10687146.00
      3698665.25     10687117.00      3698670.00     10687073.00
      3698660.75     10687015.00      3698676.75     10686982.00
      3698771.08     10686898.40      3698816.65     10686902.74
      3698854.85     10686926.61      3698975.75     10686978.00
      3699030.75     10686986.00      3699172.25     10687140.00

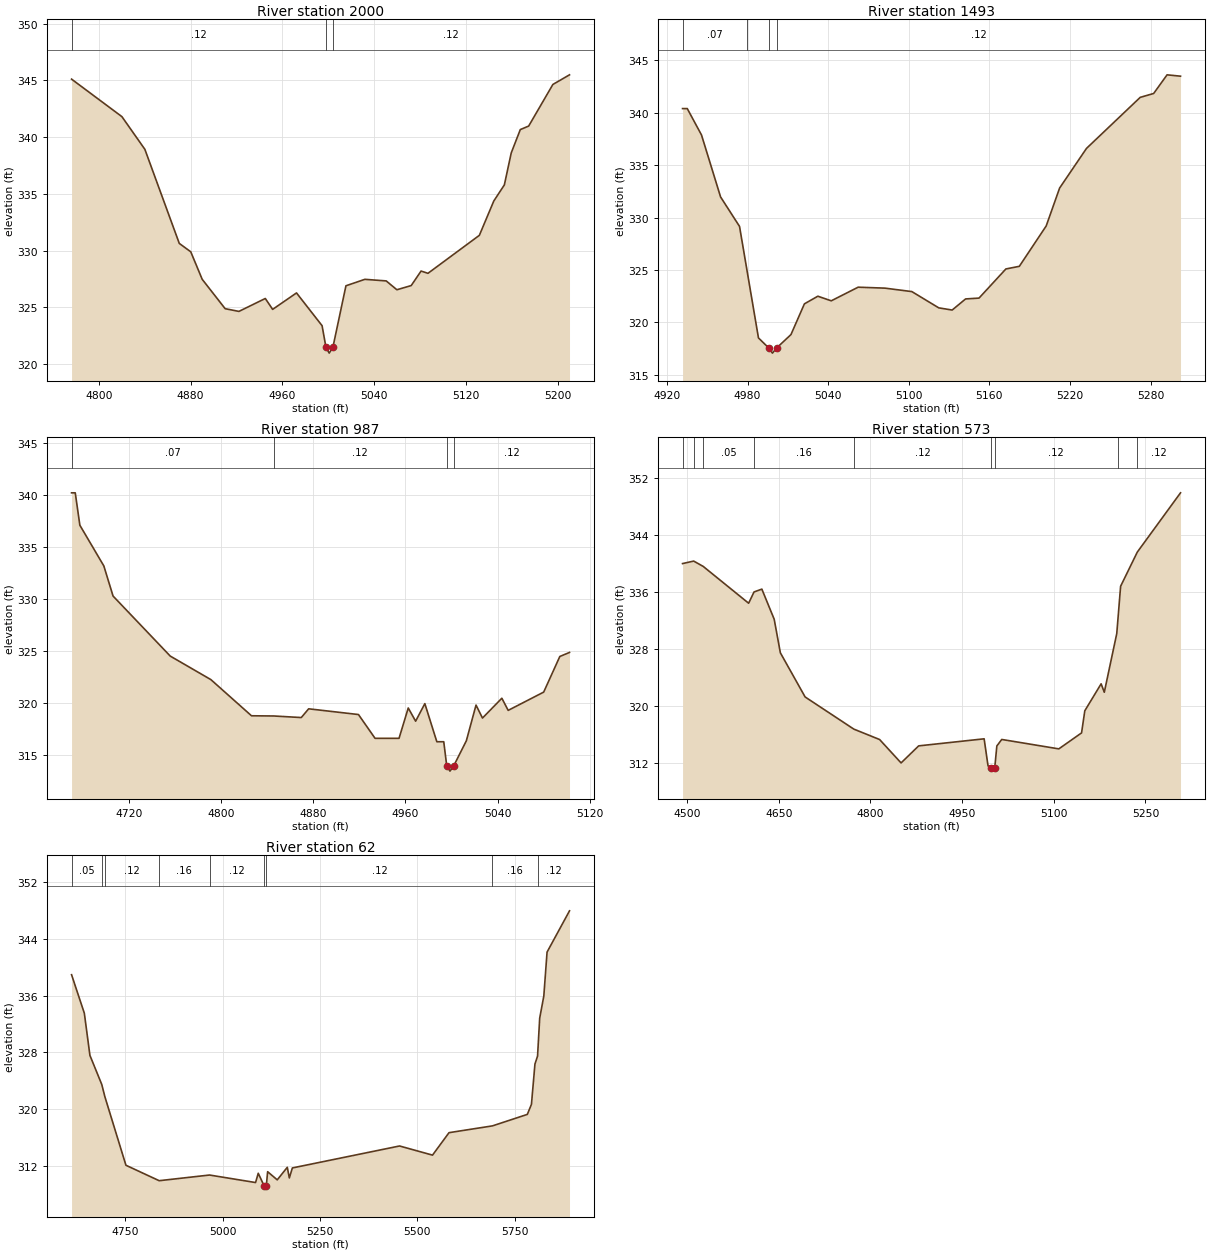
Type RM Length L Ch R = 1,2000,507,507,507
BEGIN DESCRIPTION:
UNT 159 IN CACR 4.0
END DESCRIPTION:
XS GIS Cut Line= 4
      3698473.52     10688075.34      3698327.68     10688073.60
      3698242.61     10688004.16      3698146.04     10687854.12
#Sta/Elev= 30
  4776.3  345.12  4820.2  341.81  4840.2  338.93  4870.2  330.63  4880.2  329.89
  4890.2  327.46  4910.2  324.87  4922.2  324.63  4945.2  325.77  4951.6  324.81
  4972.4  326.26  4994.7  323.37  4998.1  321.45  5000.9  320.95  5004.1  321.45
  5015.5  326.89  5032.0  327.46  5050.6  327.32  5059.9  326.54  5072.4  326.91
  5081.0  328.19  5087.0  327.99  5131.8  331.34  5144.4  334.37  5153.6  335.79
  5159.6  338.61  5167.5  340.67  5174.8  340.98  5195.9  344.65  5210.4  345.50
#Mann=3,-1,0
  4776.3    0.12       0  4998.1    0.07       0  5004.1    0.12       0
Bank Sta=4998.1,5004.1
Exp/Cntr=0.3,0.1

Type RM Length L Ch R = 1,1493,506,506,506
BEGIN DESCRIPTION:
UNT 159 IN CACR 3.0
END DESCRIPTION:
XS GIS Cut Line= 3
      3698599.59     10687760.17      3698549.61     10687710.19
      3698249.59     10687710.19
#Sta/Elev= 30
  4931.6  340.40  4935.1  340.40  4945.7  337.88  4959.9  331.97  4974.0  329.16
  4979.9  324.71  4988.1  318.52  4995.7  317.57  4998.5  317.07  5001.7  317.57
  5012.3  318.84  5022.3  321.77  5032.3  322.50  5042.3  322.06  5062.3  323.36
  5082.3  323.27  5102.3  322.94  5122.3  321.39  5132.3  321.18  5142.3  322.24
  5152.3  322.32  5172.3  325.10  5182.3  325.35  5202.3  329.20  5212.3  332.82
  5232.3  336.60  5272.3  341.47  5282.3  341.84  5292.3  343.62  5302.3  343.49
#Mann=4,-1,0
  4931.6    0.07       0  4979.9    0.12       0  4995.7    0.07       0
  5001.7    0.12       0
Bank Sta=4995.7,5001.7
Exp/Cntr=0.3,0.1

Type RM Length L Ch R = 1,987,414,414,414
BEGIN DESCRIPTION:
UNT 159 IN CACR 2.0
END DESCRIPTION:
XS GIS Cut Line= 3
      3698749.60     10687510.18      3698549.61     10687260.19
      3698449.56     10687310.21
#Sta/Elev= 30
  4670.4  340.21  4673.6  340.21  4677.6  337.09  4698.4  333.17  4706.4  330.27
  4756.0  324.49  4791.3  322.22  4826.5  318.74  4845.8  318.72  4869.7  318.57
  4876.1  319.41  4919.3  318.86  4933.7  316.57  4954.5  316.57  4962.5  319.49
  4968.9  318.22  4976.9  319.91  4987.3  316.24  4993.3  316.24  4995.9  313.91
  4998.7  313.41  5001.9  313.91  5012.9  316.33  5021.3  319.77  5026.9  318.52
  5043.7  320.43  5049.2  319.26  5080.0  321.02  5094.0  324.45  5102.4  324.84
#Mann=4,-1,0
  4670.4    0.07       0  4845.8    0.12       0  4995.9    0.07       0
  5001.9    0.12       0
Bank Sta=4995.9,5001.9
Exp/Cntr=0.3,0.1

Type RM Length L Ch R = 1,573,511,511,511
BEGIN DESCRIPTION:
Mapping XS 52f2e5c5
END DESCRIPTION:
XS GIS Cut Line= 4
      3698797.15     10687408.26      3698842.73     10687119.59
      3698677.80     10686915.59      3698430.38     10686835.29
#Sta/Elev= 30
  4492.7  339.95  4510.9  340.30  4526.5  339.55  4600.8  334.39  4609.6  335.97
  4622.4  336.37  4642.6  332.15  4652.7  327.44  4693.2  321.25  4772.9  316.74
  4815.1  315.28  4850.2  312.00  4879.0  314.39  4986.1  315.38  4992.5  311.58
  4997.5  311.35  5000.3  310.85  5003.5  311.35  5006.9  314.38  5014.9  315.29
  5108.3  313.97  5145.5  316.21  5150.8  319.31  5177.5  323.09  5182.7  321.91
  5203.1  330.14  5205.0  332.14  5209.4  336.77  5236.7  341.56  5307.4  349.87
#Mann=9,-1,0
  4492.7    0.07       0  4510.9    0.12       0  4526.5    0.05       0
  4609.6    0.16       0  4772.9    0.12       0  4997.5    0.07       0
  5003.5    0.12       0  5205.0    0.16       0  5236.7    0.12       0
Bank Sta=4997.5,5003.5
Exp/Cntr=0.3,0.1

Type RM Length L Ch R = 1,62,0,0,0
BEGIN DESCRIPTION:
UNT 159 IN CACR 1.0
END DESCRIPTION:
XS GIS Cut Line= 4
      3698838.37     10687345.30      3699081.45     10687145.63
      3699207.31     10687015.42      3698467.25     10686757.16
#Sta/Elev= 30
  4611.6  338.95  4644.4  333.52  4658.8  327.56  4689.2  323.46  4697.3  321.71
  4751.3  312.05  4836.7  309.87  4966.2  310.67  5084.4  309.61  5091.3  310.92
  5106.1  309.18  5108.8  308.68  5112.1  309.18  5115.4  311.14  5140.1  309.99
  5165.9  311.76  5171.2  310.26  5179.0  311.67  5454.4  314.77  5539.1  313.48
  5581.5  316.65  5693.2  317.61  5782.7  319.23  5793.3  320.65  5802.3  326.34
  5809.0  327.46  5814.5  332.82  5825.1  335.95  5833.4  342.14  5891.1  347.97
#Mann=9,-1,0
  4611.6    0.05       0  4689.2    0.16       0  4697.3    0.12       0
  4836.7    0.16       0  4966.2    0.12       0  5106.1    0.07       0
  5112.1    0.12       0  5693.2    0.16       0  5809.0    0.12       0
Bank Sta=5106.1,5112.1
Exp/Cntr=0.3,0.1

Chan Stop Cuts=-1