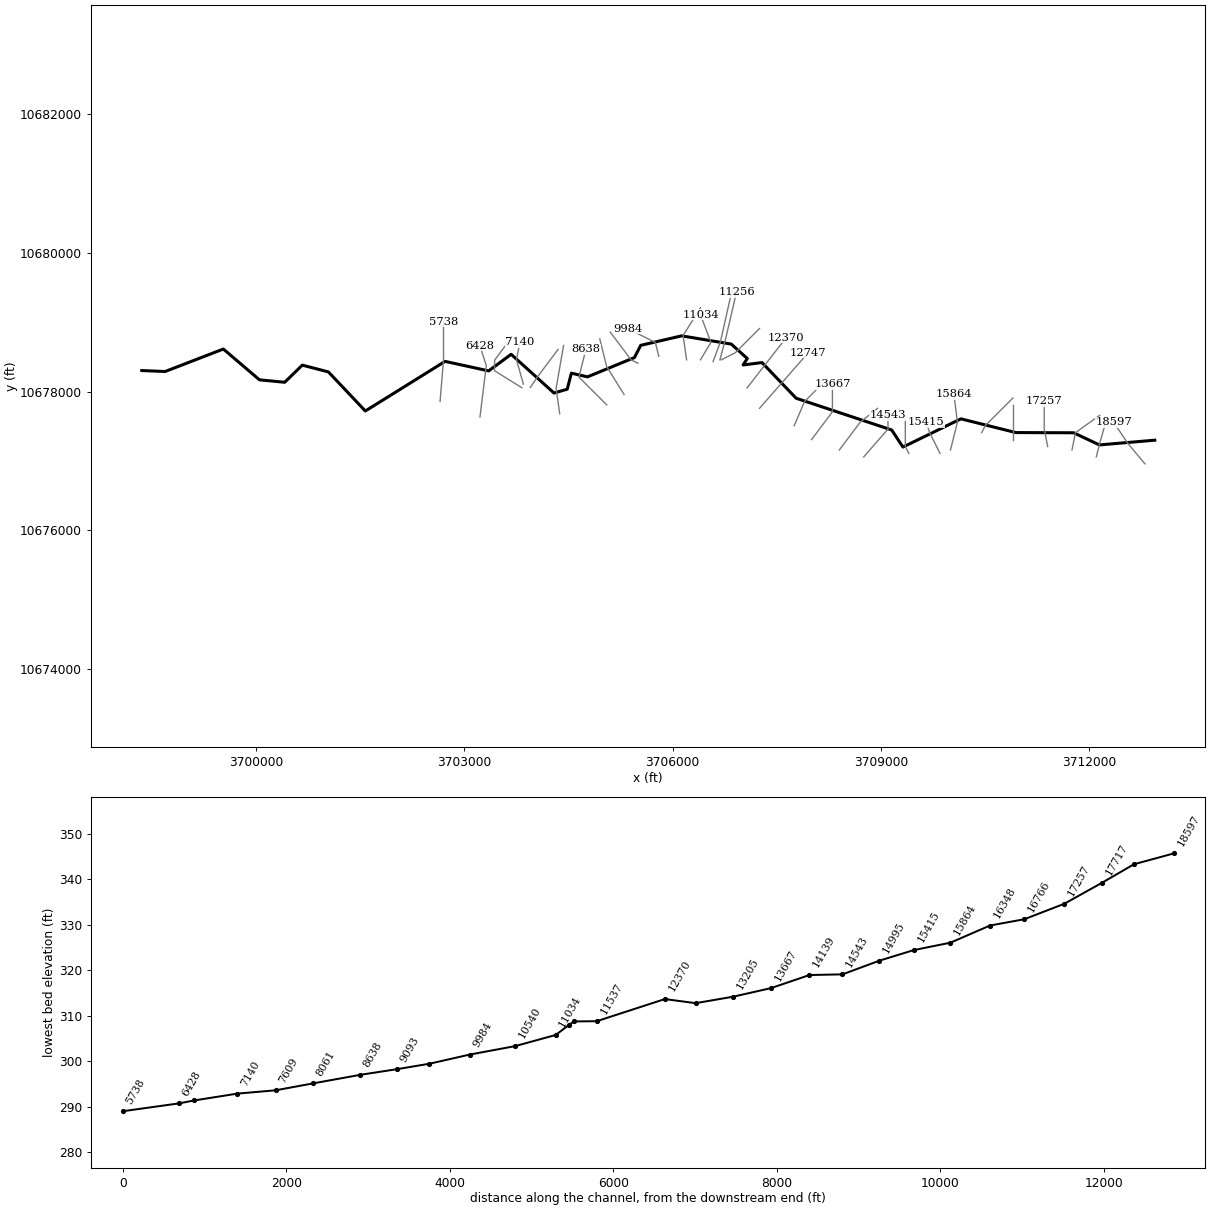
--- UNT 160 IN CACR.prj (project) ---

Proj Title=UNT 160 IN CACR Base Level Engineering
Current Plan=p01
Default Exp/Contr=0.3,0.1
English Units
Geom File=g01
Flow File=f01
Plan File=p01
BEGIN DESCRIPTION:
UNT 160 IN CACR
END DESCRIPTION:

--- UNT 160 IN CACR.p01 (plan) ---

Plan Title=Multiple Run
Short Identifier=Multiple
Geom File=g01
Flow File=f01
Subcritical Flow
K Sum by GR= 0
Std Step Tol= 0.01
Critical Tol= 0.01
Num of Std Step Trials= 20
Max Error Tol= 0.3
Flow Tol Ratio= 0.001
Split Flow NTrial= 30
Split Flow Tol= 0.02
Split Flow Ratio= 0.02
Log Output Level= 0
Friction Slope Method= 1
Unsteady Friction Slope Method= 2
Unsteady Bridges Friction Slope Method= 1
Parabolic Critical Depth
Global Vel Dist=  1 , 1 , 1
Global Log Level= 0
CheckData=True
Encroach Param= -1, 0, 0, 0
BEGIN DESCRIPTION:
Multiple Run
END DESCRIPTION:

--- UNT 160 IN CACR.f01 (steady flow) ---

Flow Title=Multiple
Number of Profiles=7
Profile Names=10-year,25-year,50-year,1pct_min,100-year,1pct_plu,500-year
River Rch & RM= UNT 160 IN CACR,Reach-1,18597
     595     812     993     893    1207    1633    1793
River Rch & RM= UNT 160 IN CACR,Reach-1,18109
     877    1219    1507    1369    1851    2503    2804
River Rch & RM= UNT 160 IN CACR,Reach-1,13667
     996    1390    1726    1572    2126    2874    3239
River Rch & RM= UNT 160 IN CACR,Reach-1,11194
    1106    1547    1923    1752    2370    3205    3617
River Rch & RM= UNT 160 IN CACR,Reach-1,6428
    1769    2523    3175    2925    3955    5349    6171
Boundary for River Rch & Prof#=UNT 160 IN CACR,Reach-1,1
Up Type=0
Dn Type=3
Dn Slope=0.005
Boundary for River Rch & Prof#=UNT 160 IN CACR,Reach-1,2
Up Type=0
Dn Type=3
Dn Slope=0.005
Boundary for River Rch & Prof#=UNT 160 IN CACR,Reach-1,3
Up Type=0
Dn Type=3
Dn Slope=0.005
Boundary for River Rch & Prof#=UNT 160 IN CACR,Reach-1,4
Up Type=0
Dn Type=3
Dn Slope=0.005
Boundary for River Rch & Prof#=UNT 160 IN CACR,Reach-1,5
Up Type=0
Dn Type=3
Dn Slope=0.005
Boundary for River Rch & Prof#=UNT 160 IN CACR,Reach-1,6
Up Type=0
Dn Type=3
Dn Slope=0.005
Boundary for River Rch & Prof#=UNT 160 IN CACR,Reach-1,7
Up Type=0
Dn Type=3
Dn Slope=0.005

--- UNT 160 IN CACR.g01 (geometry) ---

Geom Title=Existing Conditions

River Reach=UNT 160 IN CACR,Reach-1
Reach XY= 30
      3712941.54     10677301.16      3712143.75     10677233.00
      3711774.00     10677408.00      3710940.00     10677411.00
      3710150.00     10677609.00      3709315.00     10677202.00
      3709153.75     10677448.00      3707777.00     10677906.00
      3707285.25     10678420.00      3707013.00     10678385.00
      3707074.25     10678478.00      3706843.75     10678686.00
      3706128.75     10678805.00      3705538.75     10678668.00
      3705449.00     10678492.00      3704772.50     10678214.00
      3704540.75     10678267.00      3704480.50     10678036.00
      3704290.25     10677981.00      3703673.25     10678539.00
      3703349.50     10678300.00      3702721.50     10678437.00
      3701573.50     10677722.00      3701042.00     10678285.00
      3700666.00     10678383.00      3700412.50     10678136.00
      3700049.00     10678171.00      3699528.75     10678615.00
      3698690.50     10678291.00      3698354.75     10678305.00

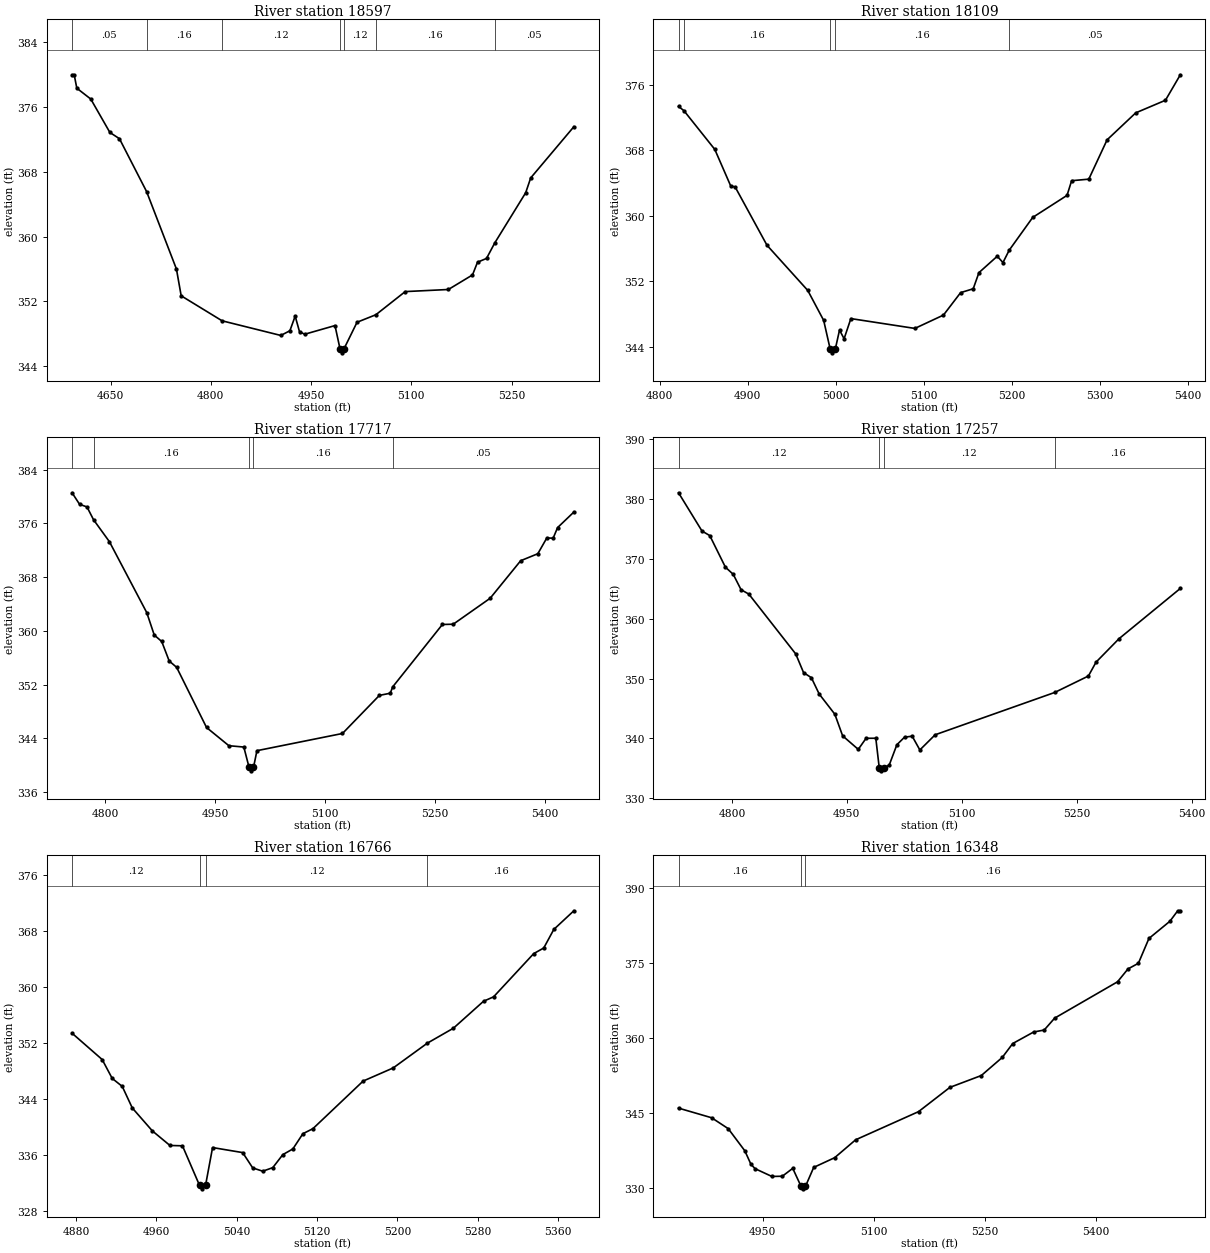
Type RM Length L Ch R = 1,18597,488,488,488
BEGIN DESCRIPTION:
UNT 160 IN CACR 37.0
END DESCRIPTION:
XS GIS Cut Line= 3
      3712799.59     10676960.21      3712549.61     10677260.19
      3712349.63     10677560.16
#Sta/Elev= 30
  4592.3  380.00  4595.5  380.00  4599.4  378.34  4620.3  377.00  4648.9  372.87
  4663.2  372.10  4703.8  365.57  4748.5  355.99  4755.6  352.68  4816.8  349.59
  4904.7  347.78  4918.3  348.36  4926.2  350.17  4932.7  348.24  4940.5  347.93
  4985.8  349.00  4993.3  346.13  4996.1  345.63  4999.3  346.13  5018.8  349.41
  5047.0  350.34  5090.9  353.20  5155.5  353.46  5191.6  355.26  5199.1  356.83
  5212.6  357.30  5224.8  359.20  5271.2  365.42  5278.7  367.25  5343.3  373.58
#Mann=7,-1,0
  4592.3    0.05       0  4703.8    0.16       0  4816.8    0.12       0
  4993.3    0.07       0  4999.3    0.12       0  5047.0    0.16       0
  5224.8    0.05       0
Bank Sta=4993.3,4999.3
Exp/Cntr=0.3,0.1

Type RM Length L Ch R = 1,18109,392,392,392
BEGIN DESCRIPTION:
UNT 160 IN CACR 36.0
END DESCRIPTION:
XS GIS Cut Line= 3
      3712099.62     10677060.23      3712149.61     10677260.19
      3712249.60     10677610.17
#Sta/Elev= 30
  4821.6  373.33  4827.7  372.81  4862.8  368.08  4880.8  363.64  4886.0  363.48
  4922.1  356.38  4968.4  350.87  4986.5  347.21  4993.8  343.75  4996.5  343.25
  4999.8  343.75  5004.5  346.03  5009.7  344.97  5017.4  347.43  5090.1  346.23
  5122.6  347.86  5142.1  350.60  5156.4  351.07  5162.9  353.04  5183.7  355.04
  5190.2  354.27  5197.3  355.78  5224.0  359.78  5263.0  362.47  5268.2  364.26
  5287.7  364.45  5308.5  369.25  5341.0  372.54  5374.8  374.08  5391.7  377.19
#Mann=5,-1,0
  4821.6    0.05       0  4827.7    0.16       0  4993.8    0.07       0
  4999.8    0.16       0  5197.3    0.05       0
Bank Sta=4993.8,4999.8
Exp/Cntr=0.3,0.1

Type RM Length L Ch R = 1,17717,460,460,460
BEGIN DESCRIPTION:
UNT 160 IN CACR 35.0
END DESCRIPTION:
XS GIS Cut Line= 3
      3711749.61     10677160.20      3711799.61     10677410.19
      3712149.65     10677660.22
#Sta/Elev= 30
  4754.7  380.55  4764.9  378.84  4775.1  378.44  4784.0  376.54  4805.7  373.27
  4856.7  362.71  4866.9  359.38  4877.1  358.42  4887.3  355.52  4897.5  354.57
  4938.3  345.62  4968.8  342.91  4989.2  342.71  4996.4  339.67  4999.2  339.17
  5002.4  339.67  5007.1  342.17  5123.9  344.73  5174.3  350.40  5189.1  350.72
  5192.5  351.67  5260.3  360.95  5275.1  360.99  5325.5  364.85  5367.2  370.44
  5390.6  371.48  5402.9  373.83  5411.5  373.79  5417.6  375.37  5439.8  377.68
#Mann=5,-1,0
  4754.7    0.12       0  4784.0    0.16       0  4996.4    0.07       0
  5002.4    0.16       0  5192.5    0.05       0
Bank Sta=4996.4,5002.4
Exp/Cntr=0.3,0.1

Type RM Length L Ch R = 1,17257,491,491,491
BEGIN DESCRIPTION:
UNT 160 IN CACR 34.0
END DESCRIPTION:
XS GIS Cut Line= 3
      3711399.61     10677210.18      3711349.61     10677460.19
      3711349.61     10677860.22
#Sta/Elev= 30
  4730.3  381.05  4760.9  374.66  4771.1  373.89  4791.5  368.61  4801.7  367.42
  4811.9  364.85  4822.1  364.11  4883.3  354.11  4893.5  350.99  4903.7  350.14
  4913.9  347.41  4934.3  344.04  4944.5  340.42  4964.9  338.16  4975.1  340.01
  4987.8  340.02  4992.3  335.07  4995.0  334.57  4998.3  335.07  5005.3  335.53
  5015.3  338.93  5025.3  340.20  5035.3  340.36  5045.3  338.06  5065.3  340.60
  5221.3  347.67  5265.3  350.42  5275.3  352.74  5305.3  356.66  5385.3  365.06
#Mann=4,-1,0
  4730.3    0.12       0  4992.3    0.07       0  4998.3    0.12       0
  5221.3    0.16       0
Bank Sta=4992.3,4998.3
Exp/Cntr=0.3,0.1

Type RM Length L Ch R = 1,16766,418,418,418
BEGIN DESCRIPTION:
UNT 160 IN CACR 33.0
END DESCRIPTION:
XS GIS Cut Line= 3
      3710899.61     10677310.22      3710899.61     10677410.19
      3710899.61     10677810.22
#Sta/Elev= 30
  4875.9  353.40  4905.9  349.64  4915.9  346.94  4925.9  345.80  4935.9  342.72
  4955.9  339.44  4973.4  337.36  4985.9  337.31  5002.9  331.66  5005.6  331.16
  5008.9  331.66  5015.9  337.06  5045.9  336.34  5055.9  334.15  5065.9  333.68
  5075.9  334.19  5085.9  336.05  5095.9  336.86  5105.9  339.04  5115.9  339.76
  5165.9  346.56  5195.9  348.44  5229.9  351.98  5255.9  354.12  5285.9  357.97
  5295.9  358.60  5335.9  364.78  5345.9  365.58  5355.9  368.23  5375.9  370.90
#Mann=4,-1,0
  4875.9    0.12       0  5002.9    0.07       0  5008.9    0.12       0
  5229.9    0.16       0
Bank Sta=5002.9,5008.9
Exp/Cntr=0.3,0.1

Type RM Length L Ch R = 1,16348,484,484,484
BEGIN DESCRIPTION:
UNT 160 IN CACR 32.0
END DESCRIPTION:
XS GIS Cut Line= 3
      3710449.60     10677410.17      3710499.61     10677510.19
      3710899.60     10677910.18
#Sta/Elev= 30
  4836.3  345.94  4881.0  344.01  4903.4  341.83  4925.8  337.40  4934.1  334.69
  4939.7  333.82  4962.3  332.27  4976.4  332.31  4990.5  333.89  5001.7  330.29
  5004.4  329.79  5007.7  330.29  5018.8  334.08  5047.1  336.02  5075.4  339.60
  5160.3  345.23  5202.7  350.09  5245.1  352.46  5273.4  356.08  5287.5  358.86
  5315.8  361.17  5330.0  361.56  5344.1  363.94  5429.0  371.21  5443.1  373.78
  5457.2  374.92  5471.4  379.88  5499.7  383.32  5510.3  385.42  5513.8  385.42
#Mann=3,-1,0
  4836.3    0.16       0  5001.7    0.07       0  5007.7    0.16       0
Bank Sta=5001.7,5007.7
Exp/Cntr=0.3,0.1

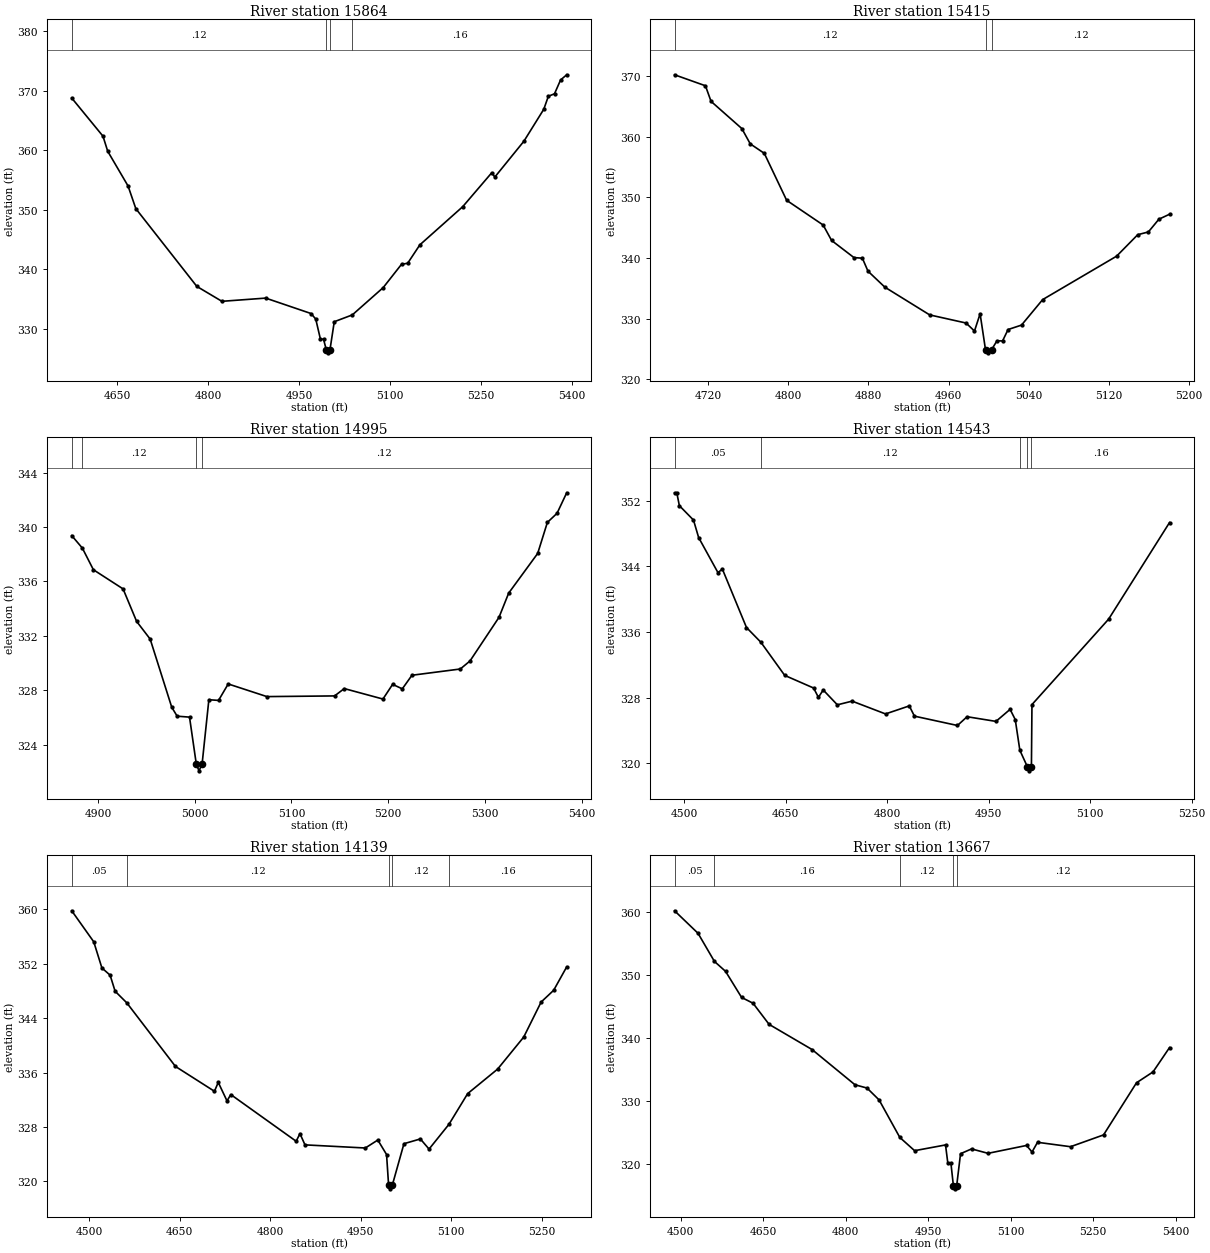
Type RM Length L Ch R = 1,15864,449,449,449
BEGIN DESCRIPTION:
UNT 160 IN CACR 31.0
END DESCRIPTION:
XS GIS Cut Line= 3
      3709999.61     10677160.20      3710099.61     10677560.19
      3710049.61     10677960.18
#Sta/Elev= 30
  4575.4  368.75  4626.9  362.35  4634.7  359.82  4668.2  354.00  4681.0  350.20
  4781.5  337.16  4822.8  334.66  4894.9  335.20  4969.7  332.61  4977.4  331.68
  4985.1  328.31  4990.2  328.31  4994.8  326.52  4997.5  326.02  5000.8  326.52
  5007.9  331.24  5037.6  332.38  5088.5  336.96  5118.7  340.87  5128.8  341.04
  5148.9  344.13  5219.5  350.53  5267.4  356.23  5272.4  355.50  5320.3  361.51
  5353.0  366.86  5360.6  369.05  5370.7  369.46  5380.7  371.78  5390.8  372.65
#Mann=4,-1,0
  4575.4    0.12       0  4994.8    0.07       0  5000.8    0.12       0
  5037.6    0.16       0
Bank Sta=4994.8,5000.8
Exp/Cntr=0.3,0.1

Type RM Length L Ch R = 1,15415,420,420,420
BEGIN DESCRIPTION:
UNT 160 IN CACR 30.0
END DESCRIPTION:
XS GIS Cut Line= 3
      3709849.62     10677110.16      3709699.61     10677410.19
      3709649.59     10677560.23
#Sta/Elev= 30
  4686.7  370.19  4717.5  368.38  4723.1  365.81  4753.8  361.33  4762.2  358.81
  4776.2  357.25  4798.5  349.51  4834.9  345.44  4843.3  342.90  4865.6  340.08
  4874.0  339.98  4879.6  337.84  4896.4  335.21  4941.1  330.64  4977.4  329.30
  4985.8  327.98  4991.4  330.83  4996.8  324.89  4999.5  324.39  5002.8  324.89
  5008.2  326.37  5013.8  326.35  5019.3  328.23  5032.7  328.96  5053.8  333.16
  5127.5  340.31  5148.6  343.85  5159.2  344.30  5169.7  346.40  5180.3  347.22
#Mann=3,-1,0
  4686.7    0.12       0  4996.8    0.07       0  5002.8    0.12       0
Bank Sta=4996.8,5002.8
Exp/Cntr=0.3,0.1

Type RM Length L Ch R = 1,14995,452,452,452
BEGIN DESCRIPTION:
UNT 160 IN CACR 29.0
END DESCRIPTION:
XS GIS Cut Line= 3
      3709399.61     10677110.19      3709349.61     10677210.19
      3709349.61     10677610.19
#Sta/Elev= 30
  4872.8  339.37  4883.8  338.45  4895.2  336.86  4925.9  335.45  4939.9  333.06
  4953.9  331.76  4976.2  326.75  4981.8  326.09  4994.6  326.02  5001.6  322.57
  5004.4  322.07  5007.6  322.57  5014.6  327.30  5024.6  327.25  5034.6  328.46
  5074.6  327.53  5144.6  327.58  5154.6  328.12  5194.6  327.35  5204.6  328.43
  5214.6  328.10  5224.6  329.10  5274.6  329.56  5284.6  330.15  5314.6  333.36
  5324.6  335.14  5354.6  338.06  5364.6  340.34  5374.6  341.01  5384.6  342.52
#Mann=4,-1,0
  4872.8    0.05       0  4883.8    0.12       0  5001.6    0.07       0
  5007.6    0.12       0
Bank Sta=5001.6,5007.6
Exp/Cntr=0.3,0.1

Type RM Length L Ch R = 1,14543,404,404,404
BEGIN DESCRIPTION:
UNT 160 IN CACR 28.0
END DESCRIPTION:
XS GIS Cut Line= 3
      3708749.60     10677060.18      3709099.61     10677460.19
      3709099.61     10677660.17
#Sta/Elev= 30
  4485.7  352.97  4489.0  352.97  4492.8  351.40  4513.7  349.64  4521.3  347.51
  4549.8  343.24  4556.4  343.66  4592.0  336.54  4613.3  334.74  4648.5  330.70
  4691.2  329.16  4698.3  328.02  4705.4  328.92  4726.3  327.11  4748.1  327.56
  4797.5  326.00  4832.6  326.98  4840.2  325.73  4903.8  324.59  4918.0  325.66
  4960.7  325.09  4981.6  326.56  4989.2  325.31  4996.0  321.57  5007.1  319.56
  5009.9  319.06  5013.1  319.56  5013.9  327.14  5127.2  337.56  5217.2  349.34
#Mann=5,-1,0
  4485.7    0.05       0  4613.3    0.12       0  4996.0    0.16       0
  5007.1    0.07       0  5013.1    0.16       0
Bank Sta=5007.1,5013.1
Exp/Cntr=0.3,0.1

Type RM Length L Ch R = 1,14139,472,472,472
BEGIN DESCRIPTION:
UNT 160 IN CACR 27.0
END DESCRIPTION:
XS GIS Cut Line= 3
      3708399.58     10677160.15      3708699.61     10677560.19
      3708949.61     10677760.19
#Sta/Elev= 30
  4471.0  359.76  4507.5  355.20  4521.0  351.36  4534.6  350.30  4542.9  347.94
  4562.2  346.24  4642.9  336.89  4707.5  333.24  4713.8  334.55  4728.3  331.83
  4734.6  332.76  4842.9  325.90  4849.2  327.02  4857.5  325.37  4957.5  324.91
  4978.2  326.08  4992.7  323.95  4996.1  319.41  4998.8  318.91  5002.1  319.41
  5021.5  325.54  5048.7  326.24  5063.1  324.75  5096.1  328.39  5127.1  332.90
  5176.7  336.50  5220.0  341.21  5248.8  346.35  5269.6  348.08  5291.2  351.52
#Mann=5,-1,0
  4471.0    0.05       0  4562.2    0.12       0  4996.1    0.07       0
  5002.1    0.12       0  5096.1    0.16       0
Bank Sta=4996.1,5002.1
Exp/Cntr=0.3,0.1

Type RM Length L Ch R = 1,13667,462,462,462
BEGIN DESCRIPTION:
UNT 160 IN CACR 26.0
END DESCRIPTION:
XS GIS Cut Line= 3
      3707999.61     10677310.18      3708299.61     10677710.19
      3708299.61     10678110.18
#Sta/Elev= 30
  4489.0  360.12  4531.7  356.55  4561.5  352.09  4581.7  350.52  4610.9  346.38
  4631.7  345.46  4660.9  342.11  4739.0  338.12  4817.1  332.53  4839.0  332.01
  4860.9  330.13  4898.6  324.18  4925.5  322.08  4981.7  322.99  4985.9  320.10
  4991.5  320.10  4996.0  316.53  4998.8  316.03  5002.0  316.53  5009.0  321.60
  5029.0  322.36  5059.0  321.66  5129.0  322.91  5139.0  321.87  5149.0  323.41
  5209.0  322.71  5269.0  324.58  5329.0  332.85  5359.0  334.57  5389.0  338.43
#Mann=5,-1,0
  4489.0    0.05       0  4561.5    0.16       0  4898.6    0.12       0
  4996.0    0.07       0  5002.0    0.12       0
Bank Sta=4996,5002
Exp/Cntr=0.3,0.1

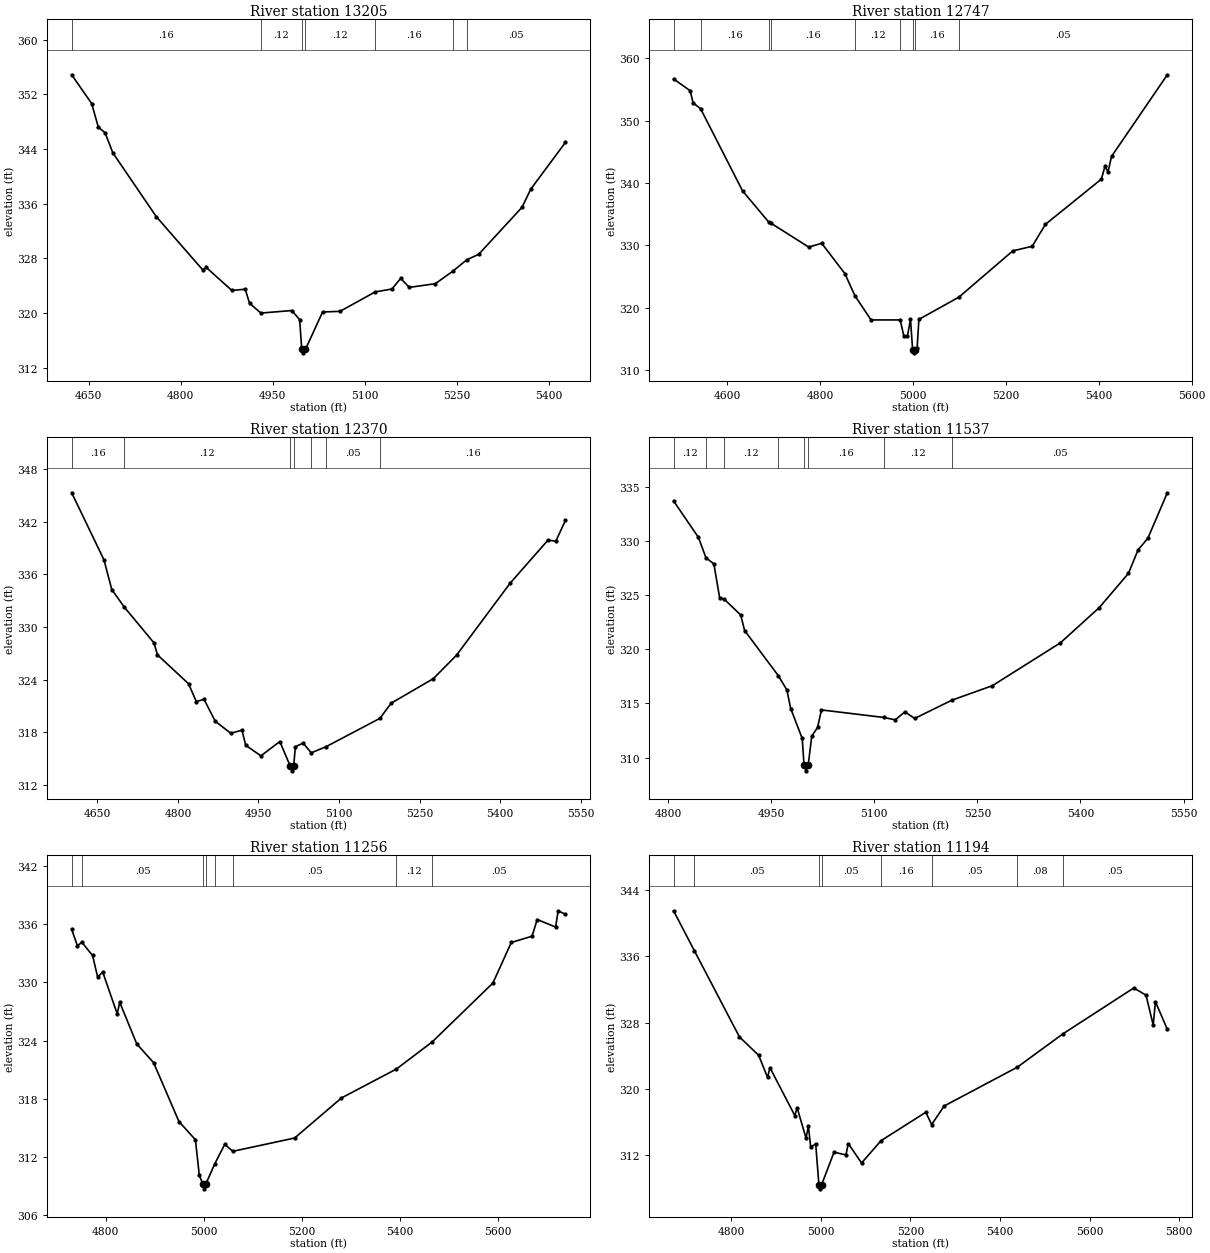
Type RM Length L Ch R = 1,13205,458,458,458
BEGIN DESCRIPTION:
UNT 160 IN CACR 25.0
END DESCRIPTION:
XS GIS Cut Line= 3
      3707749.61     10677510.19      3707899.61     10677860.19
      3708199.57     10678160.15
#Sta/Elev= 30
  4622.2  354.84  4654.8  350.63  4665.7  347.17  4676.6  346.37  4689.3  343.42
  4760.0  334.10  4836.2  326.25  4841.6  326.65  4883.3  323.28  4905.1  323.46
  4912.3  321.39  4930.7  319.97  4981.2  320.34  4993.9  319.00  4997.3  314.65
  5000.0  314.15  5003.3  314.65  5031.3  320.13  5059.6  320.22  5117.1  323.07
  5144.4  323.49  5158.5  325.05  5172.7  323.73  5215.1  324.27  5243.2  326.07
  5266.3  327.76  5285.8  328.57  5356.5  335.46  5370.7  338.11  5427.2  344.95
#Mann=7,-1,0
  4622.2    0.16       0  4930.7    0.12       0  4997.3    0.07       0
  5003.3    0.12       0  5117.1    0.16       0  5243.2    0.12       0
  5266.3    0.05       0
Bank Sta=4997.3,5003.3
Exp/Cntr=0.3,0.1

Type RM Length L Ch R = 1,12747,377,377,377
BEGIN DESCRIPTION:
UNT 160 IN CACR 24.0
END DESCRIPTION:
XS GIS Cut Line= 3
      3707249.62     10677760.21      3707599.61     10678160.19
      3707949.61     10678560.20
#Sta/Elev= 30
  4484.6  356.69  4520.2  354.80  4526.8  352.83  4542.8  351.91  4633.1  338.73
  4689.3  333.73  4694.2  333.54  4775.5  329.70  4803.5  330.31  4853.3  325.46
  4875.2  321.87  4909.8  318.01  4972.6  318.01  4980.5  315.36  4988.1  315.40
  4994.7  318.10  4999.3  313.23  5002.1  312.73  5005.3  313.23  5009.0  313.54
  5012.8  318.10  5098.8  321.66  5214.9  329.09  5256.7  329.83  5285.2  333.35
  5405.7  340.61  5413.3  342.66  5419.9  341.77  5427.5  344.25  5547.6  357.35
#Mann=9,-1,0
  4484.6    0.05       0  4542.8    0.16       0  4689.3    0.05       0
  4694.2    0.16       0  4875.2    0.12       0  4972.6    0.16       0
  4999.3    0.07       0  5005.3    0.16       0  5098.8    0.05       0
Bank Sta=4999.3,5005.3
Exp/Cntr=0.3,0.1

Type RM Length L Ch R = 1,12370,833,833,833
BEGIN DESCRIPTION:
UNT 160 IN CACR 23.0
END DESCRIPTION:
XS GIS Cut Line= 2
      3707070.27     10678054.26      3707634.98     10678780.30
#Sta/Elev= 30
  4602.0  345.30  4662.2  337.66  4676.7  334.28  4699.9  332.29  4755.4  328.20
  4761.8  326.84  4819.7  323.55  4834.2  321.52  4848.6  321.77  4869.4  319.28
  4898.4  317.91  4919.2  318.26  4926.2  316.54  4954.5  315.34  4989.8  316.97
  5009.4  314.13  5012.2  313.63  5015.4  314.13  5018.8  316.38  5033.2  316.79
  5048.3  315.68  5076.2  316.39  5176.3  319.61  5197.0  321.33  5275.7  324.13
  5319.0  326.81  5418.7  335.00  5489.3  339.91  5503.8  339.79  5521.8  342.15
#Mann=7,-1,0
  4602.0    0.16       0  4699.9    0.12       0  5009.4    0.07       0
  5015.4    0.12       0  5048.3    0.16       0  5076.2    0.05       0
  5176.3    0.16       0
Bank Sta=5009.4,5015.4
Exp/Cntr=0.3,0.1

Type RM Length L Ch R = 1,11537,281,281,281
BEGIN DESCRIPTION:
UNT 160 IN CACR 22.0
END DESCRIPTION:
XS GIS Cut Line= 3
      3706699.61     10678460.19      3706899.61     10678560.19
      3707249.63     10678910.21
#Sta/Elev= 30
  4807.8  333.72  4844.1  330.34  4854.9  328.47  4866.5  327.89  4874.9  324.76
  4881.1  324.66  4905.6  323.17  4911.2  321.74  4960.1  317.58  4972.7  316.25
  4978.3  314.53  4995.1  311.76  4997.7  309.27  5000.4  308.77  5003.7  309.27
  5009.0  311.99  5017.4  312.78  5023.0  314.40  5114.3  313.70  5130.4  313.48
  5144.5  314.22  5158.7  313.61  5212.8  315.30  5271.8  316.64  5370.8  320.60
  5427.4  323.86  5469.8  327.02  5483.9  329.20  5498.1  330.27  5526.4  334.47
#Mann=8,-1,0
  4807.8    0.12       0  4854.9    0.05       0  4881.1    0.12       0
  4960.1    0.16       0  4997.7    0.07       0  5003.7    0.16       0
  5114.3    0.12       0  5212.8    0.05       0
Bank Sta=4997.7,5003.7
Exp/Cntr=0.3,0.1

Type RM Length L Ch R = 1,11256,62,62,62
BEGIN DESCRIPTION:
Mapping XS 44911808
END DESCRIPTION:
XS GIS Cut Line= 3
      3706679.46     10678459.03      3706765.39     10678776.73
      3706918.68     10679436.64
#Sta/Elev= 30
  4730.3  335.48  4741.9  333.79  4751.1  334.14  4772.9  332.78  4783.2  330.57
  4793.7  331.06  4823.1  326.77  4828.3  327.95  4863.0  323.66  4897.3  321.73
  4949.0  315.66  4982.6  313.78  4990.5  310.10  4997.8  309.22  5000.6  308.72
  5003.8  309.22  5022.1  311.31  5042.3  313.30  5059.0  312.59  5184.8  313.96
  5280.3  318.09  5392.2  321.07  5465.3  323.87  5589.0  329.94  5626.5  334.12
  5668.7  334.77  5679.4  336.49  5716.9  335.71  5722.0  337.39  5736.9  337.02
#Mann=8,-1,0
  4730.3    0.12       0  4751.1    0.05       0  4997.8    0.04       0
  5003.8    0.05       0  5022.1    0.16       0  5059.0    0.05       0
  5392.2    0.12       0  5465.3    0.05       0
Bank Sta=4997.8,5003.8
Exp/Cntr=0.3,0.1

Type RM Length L Ch R = 1,11194,160,160,160
BEGIN DESCRIPTION:
Mapping XS 3e92d004
END DESCRIPTION:
XS GIS Cut Line= 3
      3706580.50     10678432.11      3706688.14     10678723.77
      3706861.41     10679496.59
#Sta/Elev= 30
  4670.9  341.53  4717.3  336.71  4818.1  326.27  4861.1  324.04  4880.8  321.37
  4886.2  322.55  4941.7  316.76  4947.0  317.69  4966.8  314.03  4972.1  315.47
  4977.2  312.96  4988.4  313.31  4995.6  308.39  4998.4  307.89  5001.6  308.39
  5029.4  312.32  5056.0  312.00  5061.2  313.36  5090.9  311.02  5134.4  313.72
  5234.3  317.15  5247.5  315.67  5275.3  317.91  5438.5  322.60  5539.8  326.61
  5698.8  332.19  5726.2  331.32  5742.2  327.72  5747.3  330.52  5773.8  327.18
#Mann=8,-1,0
  4670.9    0.08       0  4717.3    0.05       0  4995.6    0.04       0
  5001.6    0.05       0  5134.4    0.16       0  5247.5    0.05       0
  5438.5    0.08       0  5539.8    0.05       0
Bank Sta=4995.6,5001.6
Exp/Cntr=0.3,0.1

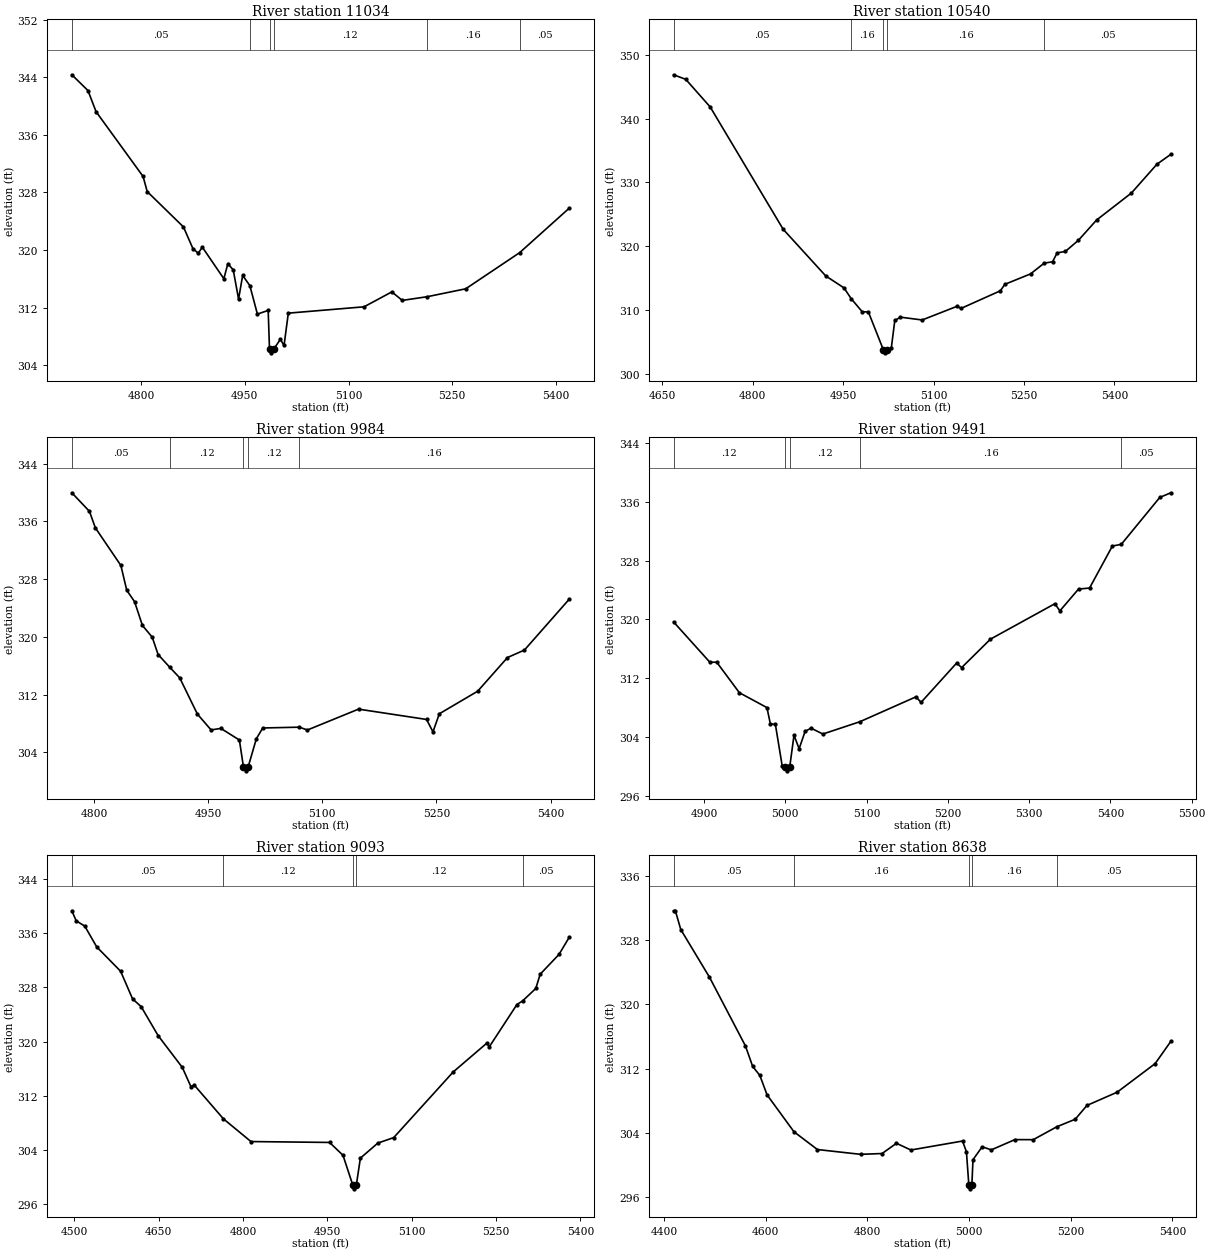
Type RM Length L Ch R = 1,11034,494,494,494
BEGIN DESCRIPTION:
UNT 160 IN CACR 21.0
END DESCRIPTION:
XS GIS Cut Line= 3
      3706399.60     10678460.17      3706549.61     10678710.19
      3706399.60     10679110.21
#Sta/Elev= 30
  4700.1  344.34  4723.4  342.15  4735.1  339.22  4803.1  330.22  4809.0  328.13
  4861.4  323.22  4875.1  320.21  4882.8  319.57  4888.7  320.41  4919.8  316.03
  4925.6  318.12  4933.4  317.25  4941.1  313.20  4947.0  316.49  4957.4  315.07
  4968.3  311.12  4983.9  311.63  4985.8  306.24  4988.5  305.74  4991.8  306.24
  5001.5  307.61  5006.8  306.76  5013.0  311.25  5122.5  312.13  5162.6  314.20
  5177.7  313.02  5213.7  313.53  5269.4  314.63  5347.4  319.65  5418.9  325.81
#Mann=6,-1,0
  4700.1    0.05       0  4957.4    0.12       0  4985.8    0.07       0
  4991.8    0.12       0  5213.7    0.16       0  5347.4    0.05       0
Bank Sta=4985.8,4991.8
Exp/Cntr=0.3,0.1

Type RM Length L Ch R = 1,10540,556,556,556
BEGIN DESCRIPTION:
UNT 160 IN CACR 20.0
END DESCRIPTION:
XS GIS Cut Line= 3
      3706199.62     10678460.14      3706149.61     10678810.19
      3706399.61     10679210.19
#Sta/Elev= 30
  4668.4  346.88  4688.6  346.17  4729.1  341.85  4850.3  322.67  4921.0  315.35
  4951.3  313.48  4963.2  311.79  4981.6  309.73  4991.7  309.72  5016.5  303.80
  5019.2  303.30  5022.5  303.80  5029.7  303.99  5035.6  308.37  5045.0  308.89
  5081.0  308.45  5139.3  310.61  5145.2  310.25  5210.7  313.02  5218.3  314.04
  5260.8  315.67  5283.6  317.36  5297.4  317.57  5305.0  318.97  5318.6  319.19
  5340.4  320.95  5370.5  324.12  5428.3  328.35  5470.7  332.87  5493.7  334.41
#Mann=5,-1,0
  4668.4    0.05       0  4963.2    0.16       0  5016.5    0.07       0
  5022.5    0.16       0  5283.6    0.05       0
Bank Sta=5016.5,5022.5
Exp/Cntr=0.3,0.1

Type RM Length L Ch R = 1,9984,493,493,493
BEGIN DESCRIPTION:
UNT 160 IN CACR 19.0
END DESCRIPTION:
XS GIS Cut Line= 3
      3705799.60     10678510.24      3705749.61     10678710.19
      3705349.63     10678910.18
#Sta/Elev= 30
  4771.0  339.97  4794.1  337.40  4801.9  335.11  4835.4  329.90  4843.1  326.47
  4853.4  324.88  4863.7  321.59  4876.6  319.96  4884.3  317.56  4899.9  315.76
  4912.7  314.33  4935.9  309.31  4953.9  307.11  4966.8  307.32  4991.1  305.71
  4996.5  301.94  4999.2  301.44  5002.5  301.94  5013.4  305.89  5021.8  307.38
  5069.8  307.49  5080.5  307.10  5147.6  309.99  5237.0  308.56  5245.4  306.84
  5253.8  309.35  5304.1  312.47  5343.3  317.14  5365.6  318.18  5424.3  325.21
#Mann=5,-1,0
  4771.0    0.05       0  4899.9    0.12       0  4996.5    0.07       0
  5002.5    0.12       0  5069.8    0.16       0
Bank Sta=4996.5,5002.5
Exp/Cntr=0.3,0.1

Type RM Length L Ch R = 1,9491,398,398,398
BEGIN DESCRIPTION:
UNT 160 IN CACR 18.0
END DESCRIPTION:
XS GIS Cut Line= 3
      3705499.59     10678410.20      3705399.61     10678460.19
      3705099.60     10678860.20
#Sta/Elev= 30
  4862.6  319.66  4907.3  314.18  4915.7  314.19  4943.6  310.04  4977.5  308.02
  4981.7  305.81  4987.9  305.73  4996.3  300.08  4999.5  299.93  5002.3  299.43
  5005.5  299.93  5010.8  304.27  5017.1  302.43  5024.4  304.78  5031.7  305.23
  5046.3  304.43  5091.8  306.10  5160.8  309.48  5167.1  308.73  5210.8  314.06
  5217.1  313.46  5252.5  317.32  5331.7  322.13  5337.9  321.16  5360.8  324.12
  5374.4  324.26  5402.5  329.97  5413.4  330.19  5460.8  336.57  5474.4  337.20
#Mann=5,-1,0
  4862.6    0.12       0  4999.5    0.07       0  5005.5    0.12       0
  5091.8    0.16       0  5413.4    0.05       0
Bank Sta=4999.5,5005.5
Exp/Cntr=0.3,0.1

Type RM Length L Ch R = 1,9093,455,455,455
BEGIN DESCRIPTION:
UNT 160 IN CACR 17.0
END DESCRIPTION:
XS GIS Cut Line= 3
      3705299.61     10677960.18      3705049.61     10678360.19
      3704949.61     10678760.17
#Sta/Elev= 30
  4495.9  339.34  4503.6  337.86  4518.9  337.07  4540.1  334.00  4582.6  330.40
  4603.8  326.32  4619.1  325.17  4649.2  320.89  4692.3  316.18  4707.6  313.33
  4713.5  313.57  4765.3  308.58  4814.3  305.22  4954.0  305.09  4977.9  303.19
  4995.5  298.73  4998.3  298.23  5001.5  298.73  5008.8  302.77  5039.8  304.99
  5068.1  305.81  5173.8  315.51  5233.0  319.73  5238.2  319.26  5287.1  325.48
  5297.1  326.01  5320.6  327.85  5328.4  329.96  5361.9  332.89  5379.9  335.40
#Mann=5,-1,0
  4495.9    0.05       0  4765.3    0.12       0  4995.5    0.07       0
  5001.5    0.12       0  5297.1    0.05       0
Bank Sta=4995.5,5001.5
Exp/Cntr=0.3,0.1

Type RM Length L Ch R = 1,8638,577,577,577
BEGIN DESCRIPTION:
UNT 160 IN CACR 16.0
END DESCRIPTION:
XS GIS Cut Line= 3
      3705049.62     10677810.18      3704649.61     10678210.19
      3704749.61     10678610.17
#Sta/Elev= 30
  4418.8  331.70  4422.4  331.70  4433.0  329.36  4489.5  323.40  4560.2  314.82
  4574.4  312.26  4588.5  311.14  4602.7  308.71  4655.6  304.10  4701.7  301.88
  4786.5  301.28  4828.9  301.38  4857.2  302.66  4885.5  301.82  4987.1  302.94
  4994.8  301.60  4999.5  297.47  5002.3  296.97  5005.5  297.47  5007.7  300.61
  5025.7  302.22  5043.8  301.84  5090.2  303.12  5126.2  303.11  5172.8  304.73
  5208.7  305.66  5231.9  307.39  5291.2  309.04  5365.9  312.61  5396.8  315.39
#Mann=5,-1,0
  4418.8    0.05       0  4655.6    0.16       0  4999.5    0.07       0
  5005.5    0.16       0  5172.8    0.05       0
Bank Sta=4999.5,5005.5
Exp/Cntr=0.3,0.1

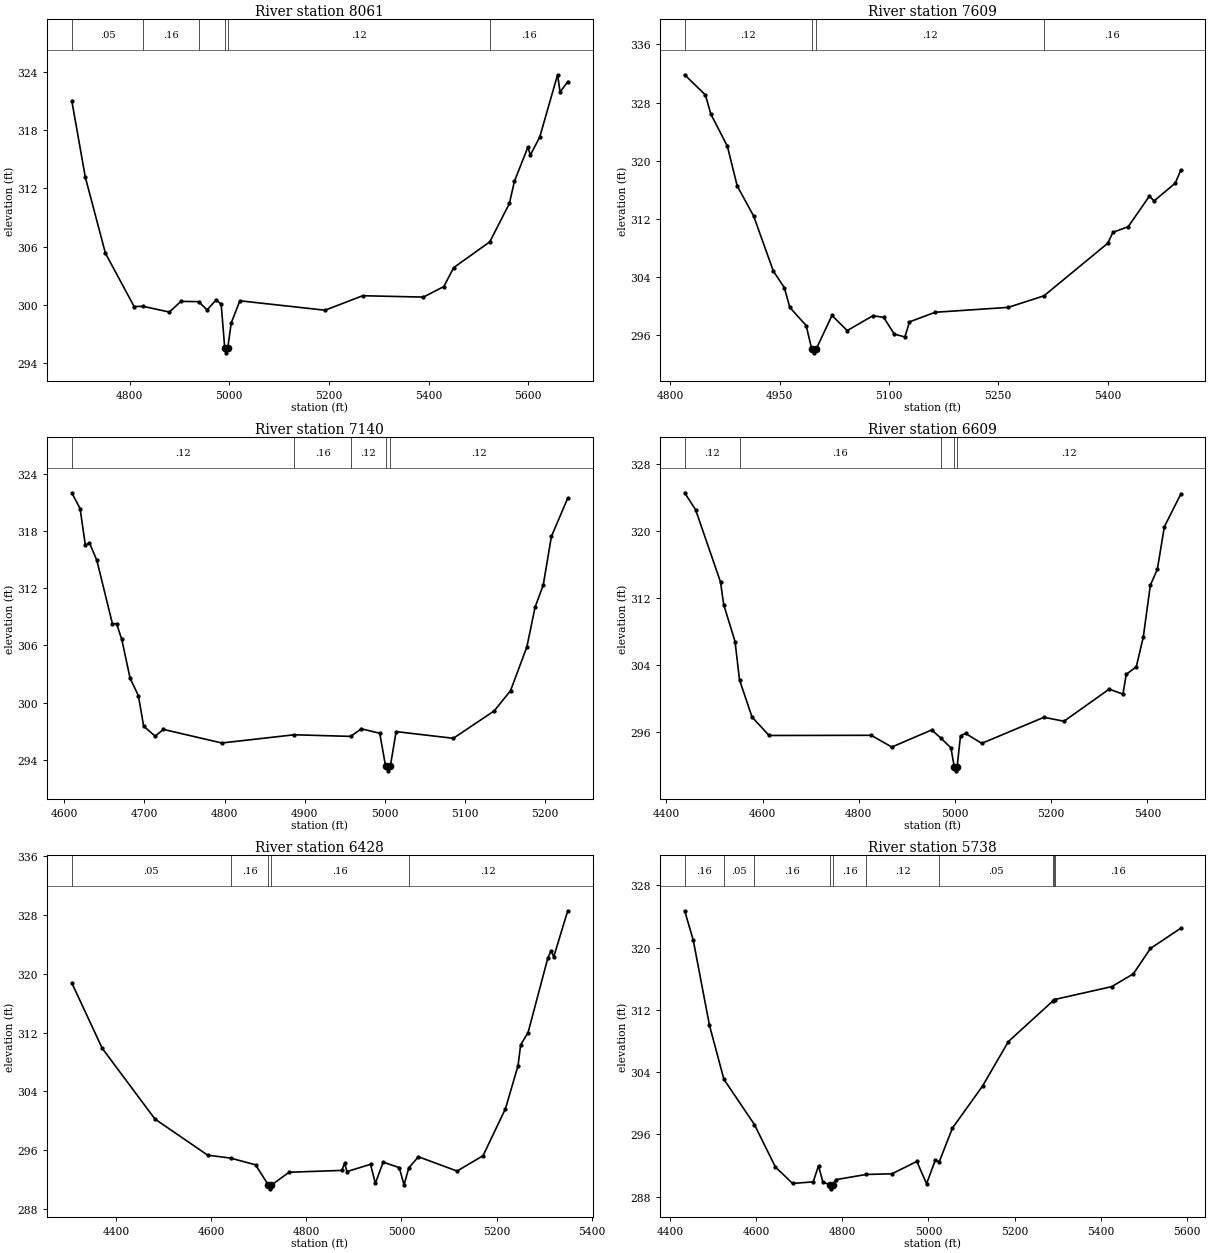
Type RM Length L Ch R = 1,8061,452,452,452
BEGIN DESCRIPTION:
UNT 160 IN CACR 15.0
END DESCRIPTION:
XS GIS Cut Line= 3
      3704372.60     10677683.38      3704320.52     10678047.99
      3704428.07     10678665.58
#Sta/Elev= 30
  4683.9  321.01  4711.0  313.16  4751.4  305.33  4809.0  299.85  4827.2  299.87
  4879.7  299.28  4902.9  300.38  4938.4  300.35  4955.5  299.50  4973.6  300.54
  4983.7  300.09  4990.8  295.59  4993.6  295.09  4996.8  295.59  5003.9  298.17
  5021.2  300.44  5192.1  299.47  5267.6  300.96  5389.4  300.82  5430.4  301.90
  5450.3  303.85  5522.7  306.50  5562.0  310.44  5572.1  312.72  5599.1  316.23
  5604.1  315.42  5622.9  317.27  5658.7  323.67  5663.7  321.90  5679.1  322.95
#Mann=6,-1,0
  4683.9    0.05       0  4827.2    0.16       0  4938.4    0.12       0
  4990.8    0.07       0  4996.8    0.12       0  5522.7    0.16       0
Bank Sta=4990.8,4996.8
Exp/Cntr=0.3,0.1

Type RM Length L Ch R = 1,7609,469,469,469
BEGIN DESCRIPTION:
UNT 160 IN CACR 14.0
END DESCRIPTION:
XS GIS Cut Line= 3
      3703949.62     10678060.21      3704049.61     10678210.19
      3704349.64     10678610.22
#Sta/Elev= 30
  4819.8  331.82  4848.3  329.04  4855.8  326.40  4878.4  322.00  4891.9  316.53
  4914.4  312.41  4941.5  304.82  4956.5  302.56  4964.0  299.84  4986.5  297.34
  4994.1  294.09  4996.8  293.59  5000.1  294.09  5021.9  298.73  5042.8  296.65
  5078.2  298.70  5092.8  298.46  5107.3  296.17  5121.9  295.77  5128.2  297.85
  5163.6  299.17  5263.6  299.84  5312.7  301.43  5400.1  308.65  5407.3  310.16
  5428.2  310.93  5457.3  315.14  5463.6  314.47  5492.8  316.92  5500.1  318.66
#Mann=4,-1,0
  4819.8    0.12       0  4994.1    0.07       0  5000.1    0.12       0
  5312.7    0.16       0
Bank Sta=4994.1,5000.1
Exp/Cntr=0.3,0.1

Type RM Length L Ch R = 1,7140,531,531,531
BEGIN DESCRIPTION:
UNT 160 IN CACR 13.0
END DESCRIPTION:
XS GIS Cut Line= 3
      3703849.61     10678110.17      3703749.61     10678460.19
      3703799.61     10678710.22
#Sta/Elev= 30
  4609.3  322.00  4619.7  320.34  4626.2  316.52  4631.4  316.73  4640.5  314.94
  4660.0  308.28  4665.2  308.28  4671.7  306.63  4682.1  302.56  4692.5  300.72
  4699.0  297.54  4713.3  296.50  4723.7  297.20  4796.5  295.78  4887.0  296.64
  4957.3  296.47  4970.7  297.26  4993.7  296.80  5000.9  293.36  5003.7  292.86
  5006.9  293.36  5014.1  296.97  5085.5  296.27  5136.5  299.14  5156.9  301.26
  5177.3  305.85  5187.5  310.01  5197.7  312.33  5207.9  317.42  5228.3  321.44
#Mann=5,-1,0
  4609.3    0.12       0  4887.0    0.16       0  4957.3    0.12       0
  5000.9    0.07       0  5006.9    0.12       0
Bank Sta=5000.9,5006.9
Exp/Cntr=0.3,0.1

Type RM Length L Ch R = 1,6609,181,181,181
BEGIN DESCRIPTION:
UNT 160 IN CACR 12.0
END DESCRIPTION:
XS GIS Cut Line= 4
      3703828.49     10678055.99      3703432.67     10678303.37
      3703435.27     10678454.42      3703681.69     10678786.43
#Sta/Elev= 30
  4437.8  324.53  4460.6  322.50  4512.4  313.88  4519.0  311.18  4542.6  306.78
  4551.9  302.19  4578.0  297.76  4613.4  295.57  4825.6  295.59  4868.6  294.19
  4951.4  296.23  4970.3  295.27  4991.4  294.10  4998.4  291.85  5001.1  291.35
  5004.4  291.85  5011.4  295.52  5021.8  295.82  5055.6  294.63  5184.9  297.74
  5226.6  297.27  5320.6  301.10  5349.2  300.50  5356.0  302.86  5376.9  303.77
  5391.5  307.32  5406.1  313.49  5420.7  315.40  5435.3  320.48  5469.1  324.33
#Mann=5,-1,0
  4437.8    0.12       0  4551.9    0.16       0  4970.3    0.12       0
  4998.4    0.07       0  5004.4    0.12       0
Bank Sta=4998.4,5004.4
Exp/Cntr=0.3,0.1

Type RM Length L Ch R = 1,6428,690,690,690
BEGIN DESCRIPTION:
UNT 160 IN CACR 11.0
END DESCRIPTION:
XS GIS Cut Line= 3
      3703224.34     10677636.72      3703315.48     10678376.29
      3703224.46     10678659.77
#Sta/Elev= 30
  4306.8  318.76  4370.8  309.86  4481.6  300.23  4592.4  295.31  4641.1  294.90
  4693.2  293.99  4720.4  291.22  4723.2  290.72  4726.4  291.22  4763.7  292.98
  4874.5  293.23  4880.5  294.21  4885.5  293.07  4935.0  294.06  4945.1  291.46
  4961.6  294.35  4995.4  293.61  5005.5  291.26  5015.5  293.58  5035.7  295.09
  5117.0  293.14  5171.6  295.23  5218.6  301.61  5245.1  307.47  5250.7  310.34
  5266.1  311.96  5308.1  322.21  5314.9  323.15  5320.2  322.29  5349.7  328.58
#Mann=5,-1,0
  4306.8    0.05       0  4641.1    0.16       0  4720.4    0.07       0
  4726.4    0.16       0  5015.5    0.12       0
Bank Sta=4720.4,4726.4
Exp/Cntr=0.3,0.1

Type RM Length L Ch R = 1,5738,449,449,449
BEGIN DESCRIPTION:
UNT 160 IN CACR 10.0
END DESCRIPTION:
XS GIS Cut Line= 3
      3702649.61     10677860.23      3702699.61     10678460.19
      3702699.61     10679010.15
#Sta/Elev= 30
  4433.7  324.74  4453.7  320.96  4491.4  310.00  4524.9  303.07  4595.7  297.26
  4644.4  291.81  4684.5  289.68  4732.2  289.89  4744.7  291.95  4754.8  289.86
  4771.8  289.49  4774.6  288.99  4777.8  289.49  4784.9  290.17  4855.6  290.84
  4915.3  290.92  4973.0  292.52  4995.6  289.64  5015.7  292.66  5025.2  292.49
  5055.7  296.80  5125.7  302.21  5185.7  307.93  5289.9  313.19  5292.7  313.32
  5292.9  313.33  5425.7  314.99  5475.7  316.62  5515.7  319.90  5585.7  322.48
#Mann=10,-1,0
  4433.7    0.16       0  4524.9    0.05       0  4595.7    0.16       0
  4771.8    0.07       0  4777.8    0.16       0  4855.6    0.12       0
  5025.2    0.05       0  5289.9    0.16       0  5292.7    0.12       0
  5292.9    0.16       0
Bank Sta=4771.8,4777.8
Exp/Cntr=0.3,0.1