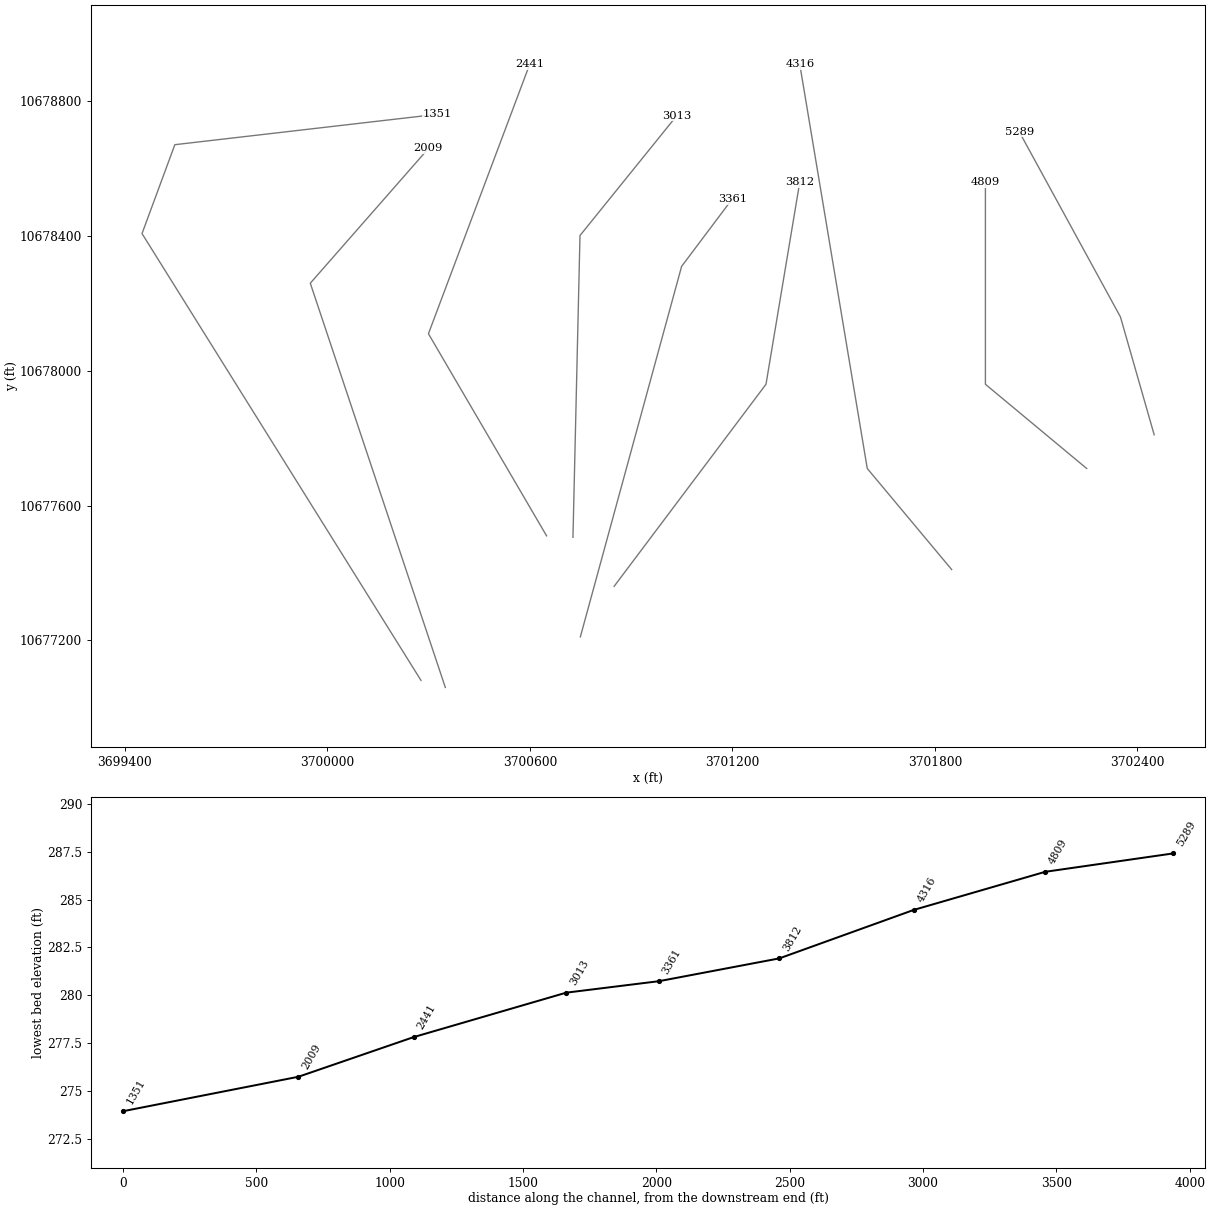
HEC-RAS study UNT 160 IN CACR.prj: UNT 160 IN CACR Base Level Engineering

--- UNT 160 IN CACR.g01 (geometry) --- (continued)

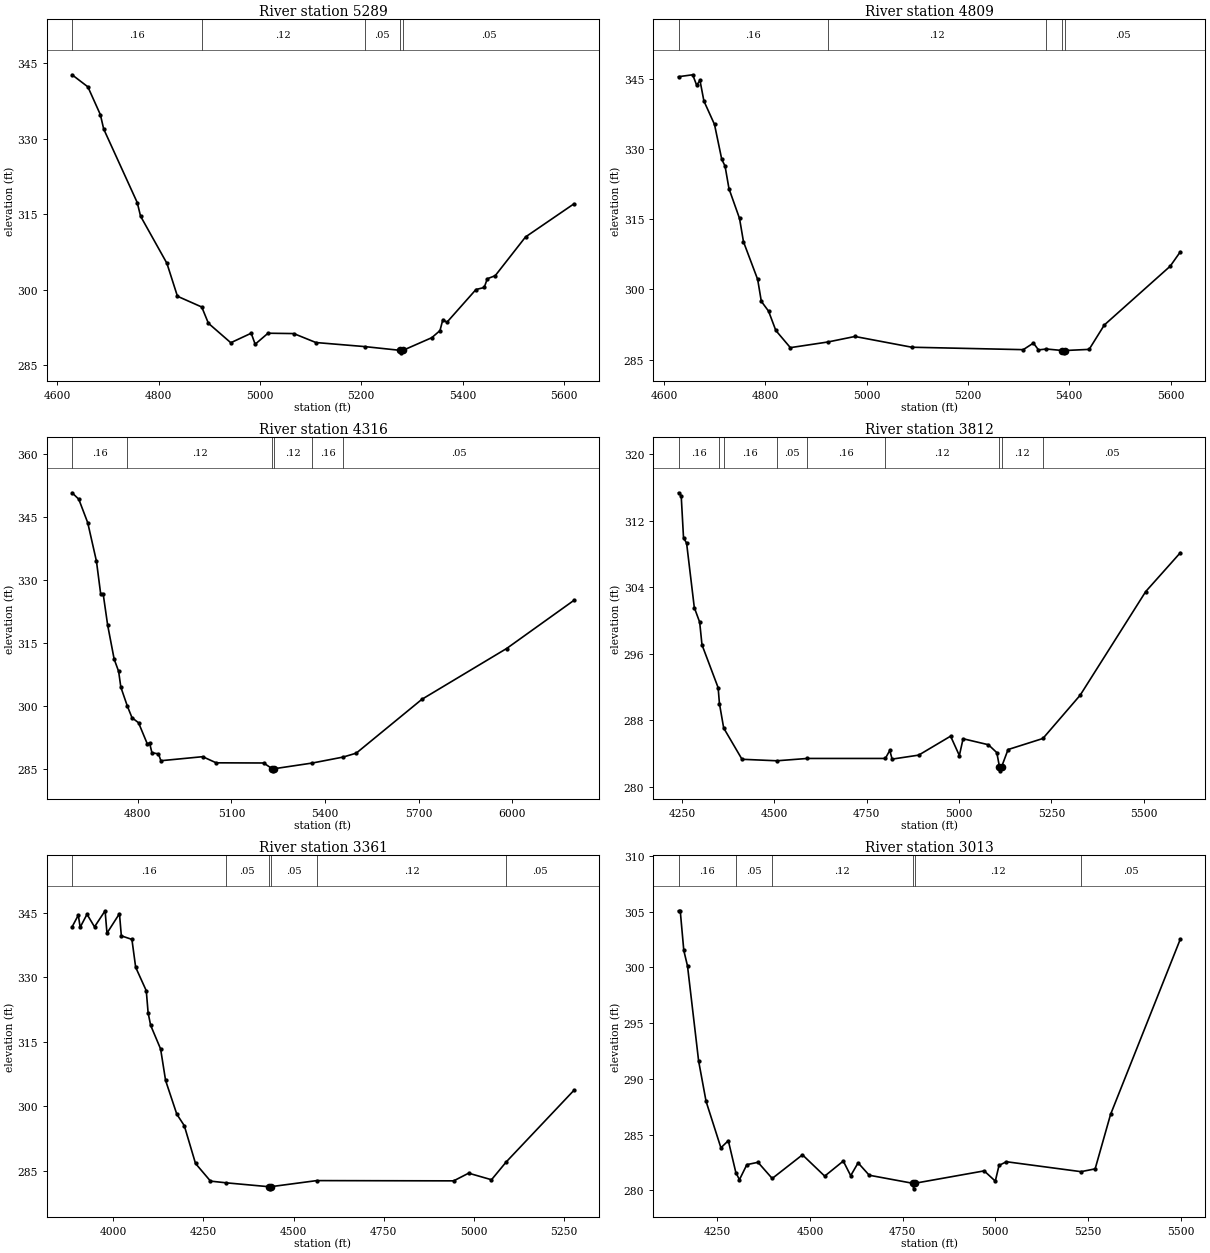
Type RM Length L Ch R = 1,5289,480,480,480
BEGIN DESCRIPTION:
UNT 160 IN CACR 9.0
END DESCRIPTION:
XS GIS Cut Line= 3
      3702449.61     10677810.17      3702349.61     10678160.19
      3702049.62     10678710.17
#Sta/Elev= 30
  4629.3  342.69  4660.5  340.29  4685.2  334.75  4691.7  331.91  4758.0  317.27
  4764.5  314.58  4816.5  305.21  4837.3  298.66  4885.3  296.52  4898.4  293.29
  4942.6  289.42  4982.9  291.31  4990.7  289.12  5016.1  291.31  5066.9  291.24
  5110.6  289.46  5207.1  288.65  5276.5  287.91  5279.3  287.41  5282.5  287.91
  5339.3  290.42  5355.5  291.83  5361.2  294.02  5369.2  293.48  5426.6  300.00
  5442.8  300.40  5449.0  302.14  5464.6  302.75  5524.4  310.45  5619.8  317.02
#Mann=5,-1,0
  4629.3    0.16       0  4885.3    0.12       0  5207.1    0.05       0
  5276.5    0.07       0  5282.5    0.05       0
Bank Sta=5276.5,5282.5
Exp/Cntr=0.3,0.1

Type RM Length L Ch R = 1,4809,493,493,493
BEGIN DESCRIPTION:
UNT 160 IN CACR 8.0
END DESCRIPTION:
XS GIS Cut Line= 3
      3702249.63     10677710.17      3701949.61     10677960.19
      3701949.61     10678560.15
#Sta/Elev= 30
  4628.8  345.51  4656.8  345.92  4664.6  343.68  4671.1  344.73  4678.9  340.30
  4699.8  335.30  4714.1  327.84  4720.6  326.40  4728.4  321.55  4749.2  315.19
  4757.0  310.21  4785.0  302.15  4792.2  297.47  4806.5  295.37  4820.8  291.24
  4849.5  287.56  4923.6  288.77  4977.0  289.95  5089.3  287.65  5309.3  287.13
  5329.3  288.54  5339.3  287.08  5355.0  287.27  5386.3  286.95  5389.1  286.45
  5392.3  286.95  5439.3  287.19  5469.3  292.41  5599.3  304.98  5619.3  308.06
#Mann=5,-1,0
  4628.8    0.16       0  4923.6    0.12       0  5355.0    0.16       0
  5386.3    0.07       0  5392.3    0.05       0
Bank Sta=5386.3,5392.3
Exp/Cntr=0.3,0.1

Type RM Length L Ch R = 1,4316,504,504,504
BEGIN DESCRIPTION:
UNT 160 IN CACR 7.0
END DESCRIPTION:
XS GIS Cut Line= 3
      3701849.63     10677410.16      3701599.61     10677710.19
      3701399.61     10678910.18
#Sta/Elev= 30
  4589.7  350.68  4611.2  349.15  4639.9  343.54  4667.8  334.38  4681.5  326.50
  4689.3  326.61  4703.6  319.19  4724.5  311.06  4738.8  308.15  4745.9  304.39
  4766.7  299.88  4781.7  297.11  4802.6  295.91  4831.2  290.78  4837.7  291.15
  4845.5  288.78  4866.4  288.49  4874.2  286.87  5008.1  287.83  5051.2  286.37
  5203.3  286.33  5230.7  284.96  5233.4  284.46  5236.7  284.96  5359.1  286.32
  5457.8  287.74  5499.8  288.67  5710.2  301.50  5981.4  313.59  6196.8  325.05
#Mann=6,-1,0
  4589.7    0.16       0  4766.7    0.12       0  5230.7    0.07       0
  5236.7    0.12       0  5359.1    0.16       0  5457.8    0.05       0
Bank Sta=5230.7,5236.7
Exp/Cntr=0.3,0.1

Type RM Length L Ch R = 1,3812,451,451,451
BEGIN DESCRIPTION:
UNT 160 IN CACR 6.0
END DESCRIPTION:
XS GIS Cut Line= 3
      3700849.64     10677360.23      3701299.61     10677960.19
      3701399.60     10678560.16
#Sta/Elev= 30
  4240.5  315.37  4247.7  315.03  4254.0  309.95  4262.3  309.32  4283.2  301.56
  4297.7  299.81  4304.0  297.08  4347.7  291.93  4351.2  290.02  4362.7  287.08
  4412.3  283.32  4506.7  283.14  4589.4  283.42  4800.3  283.42  4812.3  284.39
  4818.6  283.34  4890.5  283.82  4976.9  286.10  5000.6  283.77  5010.7  285.79
  5079.2  285.07  5102.0  284.12  5109.1  282.43  5111.9  281.93  5115.1  282.43
  5132.4  284.49  5226.7  285.82  5327.5  291.02  5505.0  303.49  5598.7  308.16
#Mann=9,-1,0
  4240.5    0.16       0  4351.2    0.12       0  4362.7    0.16       0
  4506.7    0.05       0  4589.4    0.16       0  4800.3    0.12       0
  5109.1    0.07       0  5115.1    0.12       0  5226.7    0.05       0
Bank Sta=5109.1,5115.1
Exp/Cntr=0.3,0.1

Type RM Length L Ch R = 1,3361,348,348,348
BEGIN DESCRIPTION:
UNT 160 IN CACR 5.0
END DESCRIPTION:
XS GIS Cut Line= 3
      3700749.61     10677210.21      3701049.61     10678310.19
      3701199.63     10678510.22
#Sta/Elev= 30
  3886.5  341.77  3903.8  344.51  3908.9  341.68  3927.9  344.72  3948.7  341.78
  3978.0  345.53  3983.2  340.31  4017.8  344.86  4023.0  339.69  4052.3  338.86
  4062.7  332.36  4092.1  326.90  4097.2  321.75  4104.2  318.84  4131.8  313.33
  4145.6  305.99  4176.7  298.13  4197.4  295.46  4228.5  286.65  4270.0  282.54
  4312.7  282.15  4431.1  281.24  4433.9  280.74  4437.1  281.24  4564.4  282.66
  4943.7  282.60  4985.2  284.39  5048.5  282.86  5089.3  287.01  5276.7  303.68
#Mann=6,-1,0
  3886.5    0.16       0  4312.7    0.05       0  4431.1    0.07       0
  4437.1    0.05       0  4564.4    0.12       0  5089.3    0.05       0
Bank Sta=4431.1,4437.1
Exp/Cntr=0.3,0.1

Type RM Length L Ch R = 1,3013,572,572,572
BEGIN DESCRIPTION:
UNT 160 IN CACR 4.0
END DESCRIPTION:
XS GIS Cut Line= 3
      3700727.74     10677505.96      3700748.57     10678401.75
      3701035.67     10678758.03
#Sta/Elev= 30
  4145.4  305.07  4150.0  305.07  4159.6  301.51  4169.6  300.12  4199.6  291.60
  4219.7  287.98  4259.7  283.82  4279.7  284.46  4300.0  281.60  4309.7  280.96
  4329.7  282.31  4359.7  282.52  4398.1  281.07  4479.7  283.19  4539.7  281.28
  4589.8  282.63  4609.8  281.32  4629.8  282.47  4659.8  281.36  4776.8  280.64
  4779.6  280.14  4782.8  280.64  4969.9  281.75  4999.9  280.83  5009.9  282.24
  5029.9  282.57  5231.1  281.68  5269.2  281.93  5310.8  286.81  5499.0  302.53
#Mann=6,-1,0
  4145.4    0.16       0  4300.0    0.05       0  4398.1    0.12       0
  4776.8    0.07       0  4782.8    0.12       0  5231.1    0.05       0
Bank Sta=4776.8,4782.8
Exp/Cntr=0.3,0.1

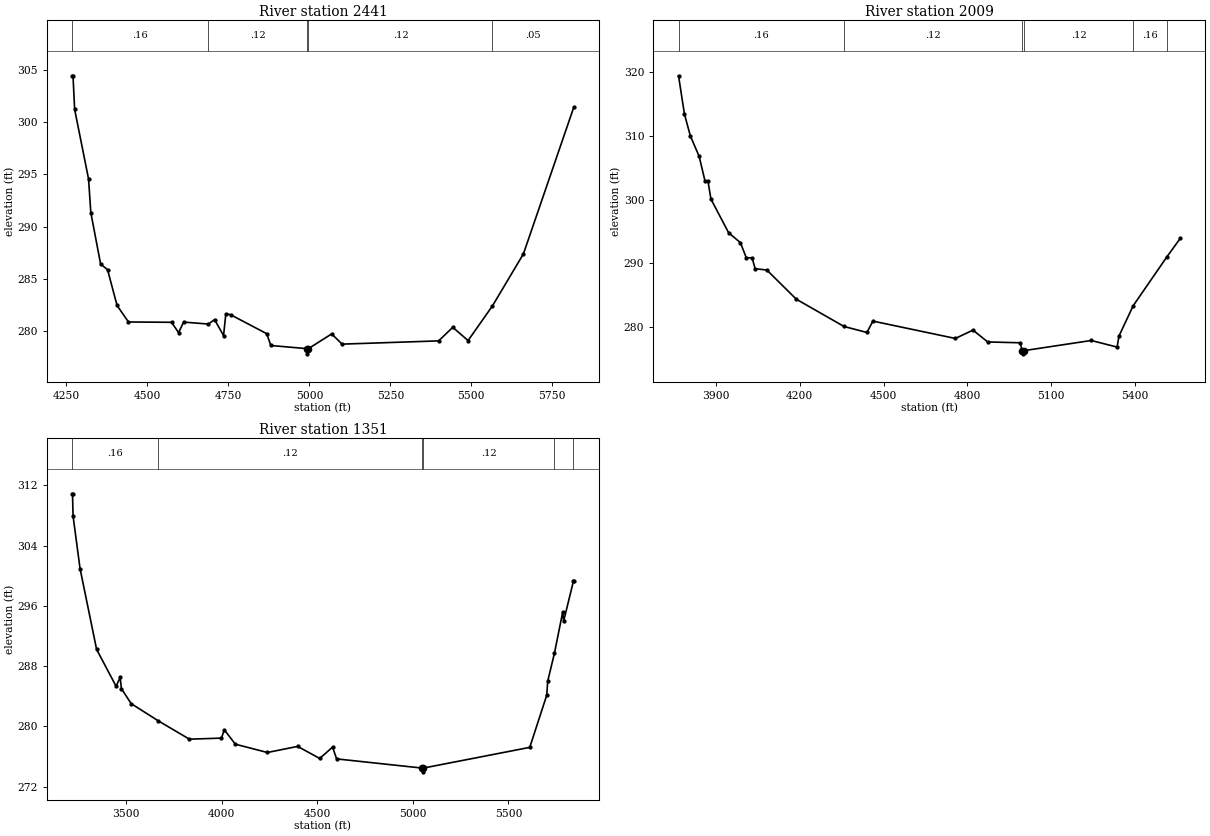
Type RM Length L Ch R = 1,2441,432,432,432
BEGIN DESCRIPTION:
UNT 160 IN CACR 3.0
END DESCRIPTION:
XS GIS Cut Line= 3
      3700649.61     10677510.19      3700299.61     10678110.19
      3700599.60     10678910.17
#Sta/Elev= 30
  4267.4  304.44  4270.3  304.44  4275.3  301.23  4318.3  294.56  4325.3  291.34
  4355.5  286.42  4377.0  285.87  4406.3  282.45  4441.5  280.87  4574.6  280.84
  4596.1  279.85  4611.8  280.86  4688.2  280.67  4707.3  281.10  4735.0  279.57
  4742.1  281.65  4756.5  281.57  4868.2  279.75  4881.0  278.62  4991.1  278.32
  4993.8  277.82  4997.1  278.32  5068.8  279.73  5100.9  278.75  5399.0  279.06
  5442.6  280.36  5489.8  279.09  5565.1  282.41  5660.7  287.39  5816.4  301.45
#Mann=5,-1,0
  4267.4    0.16       0  4688.2    0.12       0  4991.1    0.07       0
  4997.1    0.12       0  5565.1    0.05       0
Bank Sta=4991.1,4997.1
Exp/Cntr=0.3,0.1

Type RM Length L Ch R = 1,2009,658,658,658
BEGIN DESCRIPTION:
UNT 160 IN CACR 2.0
END DESCRIPTION:
XS GIS Cut Line= 3
      3700349.61     10677060.17      3699949.61     10678260.19
      3700299.59     10678660.16
#Sta/Elev= 30
  3765.9  319.48  3787.0  313.47  3808.1  310.03  3839.7  306.81  3860.8  302.90
  3871.3  302.90  3881.9  300.09  3945.1  294.80  3987.3  293.24  4008.4  290.87
  4029.4  290.84  4040.0  289.14  4082.1  288.93  4187.6  284.34  4358.5  280.05
  4440.5  279.11  4461.6  280.90  4756.8  278.17  4820.0  279.48  4872.7  277.62
  4988.7  277.49  4996.2  276.25  4999.0  275.75  5002.2  276.25  5243.4  277.85
  5336.0  276.81  5342.6  278.54  5393.3  283.30  5513.8  290.98  5562.3  293.92
#Mann=6,-1,0
  3765.9    0.16       0  4358.5    0.12       0  4996.2    0.07       0
  5002.2    0.12       0  5393.3    0.16       0  5513.8    0.12       0
Bank Sta=4996.2,5002.2
Exp/Cntr=0.3,0.1

Type RM Length L Ch R = 1,1351,0,0,0
BEGIN DESCRIPTION:
UNT 160 IN CACR 1.0
END DESCRIPTION:
XS GIS Cut Line= 4
      3700277.48     10677081.19      3699451.11     10678407.54
      3699548.34     10678671.43      3700325.37     10678761.62
#Sta/Elev= 30
  3216.3  310.89  3218.6  310.89  3221.4  307.96  3258.0  300.96  3344.7  290.22
  3446.8  285.31  3468.0  286.50  3474.3  285.01  3525.8  283.01  3666.6  280.74
  3830.3  278.29  3997.9  278.43  4013.2  279.53  4071.0  277.62  4238.6  276.52
  4396.7  277.33  4512.4  275.73  4579.6  277.23  4600.9  275.67  5048.5  274.45
  5051.3  273.95  5054.5  274.45  5611.7  277.20  5700.4  284.12  5705.8  286.01
  5740.9  289.71  5784.0  295.16  5789.1  293.98  5840.0  299.25  5842.5  299.33
#Mann=6,-1,0
  3216.3    0.16       0  3666.6    0.12       0  5048.5    0.07       0
  5054.5    0.12       0  5740.9    0.16       0  5840.0    0.05       0
Bank Sta=5048.5,5054.5
Exp/Cntr=0.3,0.1

Chan Stop Cuts=-1