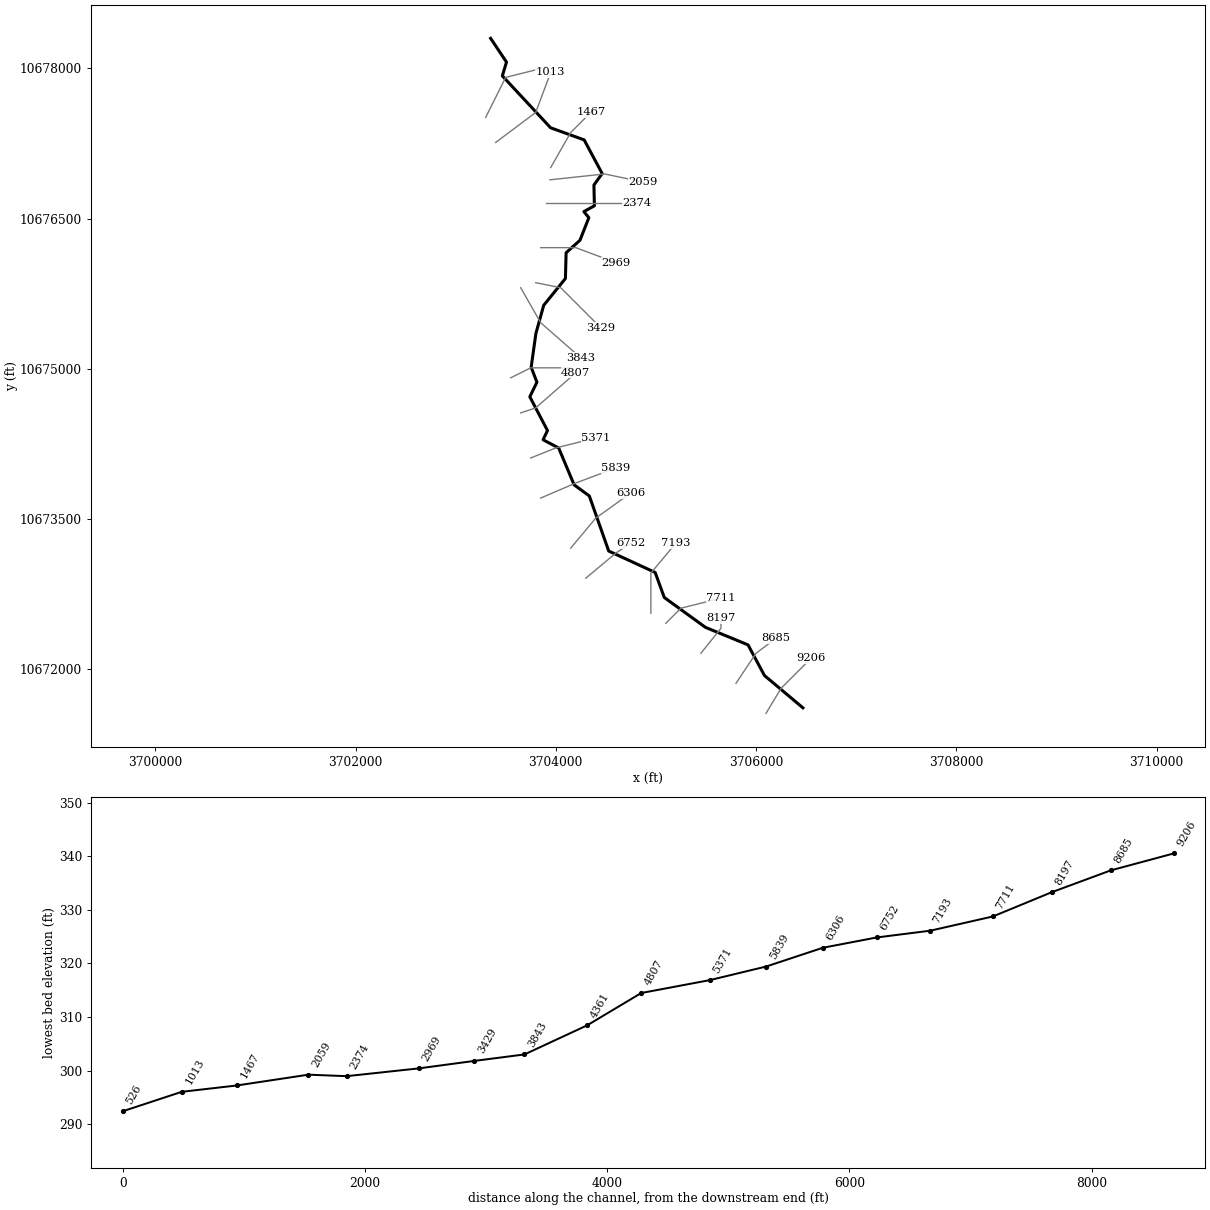
--- UNT 161 IN CACR.prj (project) ---

Proj Title=UNT 161 IN CACR Base Level Engineering
Current Plan=p01
Default Exp/Contr=0.3,0.1
English Units
Geom File=g01
Flow File=f01
Plan File=p01
Y Axis Title=Elevation
X Axis Title(PF)=Main Channel Distance
X Axis Title(XS)=Station
BEGIN DESCRIPTION:
UNT 161 IN CACR
END DESCRIPTION:
DSS Export Rating Curves= 0
DSS Export Rating Curve Sorted= 0
DSS Export Volume Flow Curves= 0
DXF OffsetX= 0
DXF OffsetY= 0
DXF ScaleX= 1
DXF ScaleY= 10

--- UNT 161 IN CACR.p01 (plan) ---

Plan Title=Multiple Run
Short Identifier=Multiple
Geom File=g01
Flow File=f01
Subcritical Flow
K Sum by GR= 0
Std Step Tol= 0.01
Critical Tol= 0.01
Num of Std Step Trials= 20
Max Error Tol= 0.3
Flow Tol Ratio= 0.001
Split Flow NTrial= 30
Split Flow Tol= 0.02
Split Flow Ratio= 0.02
Log Output Level= 0
Friction Slope Method= 1
Unsteady Friction Slope Method= 2
Unsteady Bridges Friction Slope Method= 1
Parabolic Critical Depth
Global Vel Dist=  1 , 1 , 1
Global Log Level= 0
CheckData=True
Encroach Param= -1, 0, 0, 0
BEGIN DESCRIPTION:
Multiple Run
END DESCRIPTION:

--- UNT 161 IN CACR.f01 (steady flow) ---

Flow Title=Multiple
Number of Profiles=7
Profile Names=10-year,25-year,50-year,1pct_min,100-year,1pct_plu,500-year
River Rch & RM= UNT 161 IN CACR,Reach-1,9206
     446     590     706     622     841    1137    1195
River Rch & RM= UNT 161 IN CACR,Reach-1,7711
     673     911    1107     988    1336    1806    1952
River Rch & RM= UNT 161 IN CACR,Reach-1,2374
     766    1044    1274    1141    1543    2086    2271
Boundary for River Rch & Prof#=UNT 161 IN CACR,Reach-1,1
Up Type=0
Dn Type=3
Dn Slope=0.005
Boundary for River Rch & Prof#=UNT 161 IN CACR,Reach-1,2
Up Type=0
Dn Type=3
Dn Slope=0.005
Boundary for River Rch & Prof#=UNT 161 IN CACR,Reach-1,3
Up Type=0
Dn Type=3
Dn Slope=0.005
Boundary for River Rch & Prof#=UNT 161 IN CACR,Reach-1,4
Up Type=0
Dn Type=3
Dn Slope=0.005
Boundary for River Rch & Prof#=UNT 161 IN CACR,Reach-1,5
Up Type=0
Dn Type=3
Dn Slope=0.005
Boundary for River Rch & Prof#=UNT 161 IN CACR,Reach-1,6
Up Type=0
Dn Type=3
Dn Slope=0.005
Boundary for River Rch & Prof#=UNT 161 IN CACR,Reach-1,7
Up Type=0
Dn Type=3
Dn Slope=0.005

--- UNT 161 IN CACR.g01 (geometry) ---

Geom Title=Existing Conditions
Program Version=4.10

River Reach=UNT 161 IN CACR ,Reach-1
Reach XY= 30
      3706468.12     10671615.71      3706084.25       10671938.
      3705920.25       10672244.        3705495.       10672419.
      3705083.75       10672717.      3704992.75       10672967.
      3704528.75       10673181.        3704335.       10673731.
      3704183.25       10673842.        3704029.       10674210.
      3703873.25       10674292.      3703917.25       10674384.
        3703741.       10674721.      3703811.75       10674867.
      3703754.25       10675016.       3703801.5       10675354.
      3703879.75       10675635.      3704096.25       10675902.
      3704103.25       10676159.      3704241.75       10676284.
      3704330.25       10676509.      3704280.75       10676570.
      3704385.75       10676628.        3704381.       10676835.
      3704463.25       10676950.       3704283.5       10677286.
      3703948.25       10677407.       3703466.5       10677925.
      3703507.75       10678063.       3703349.5       10678300.

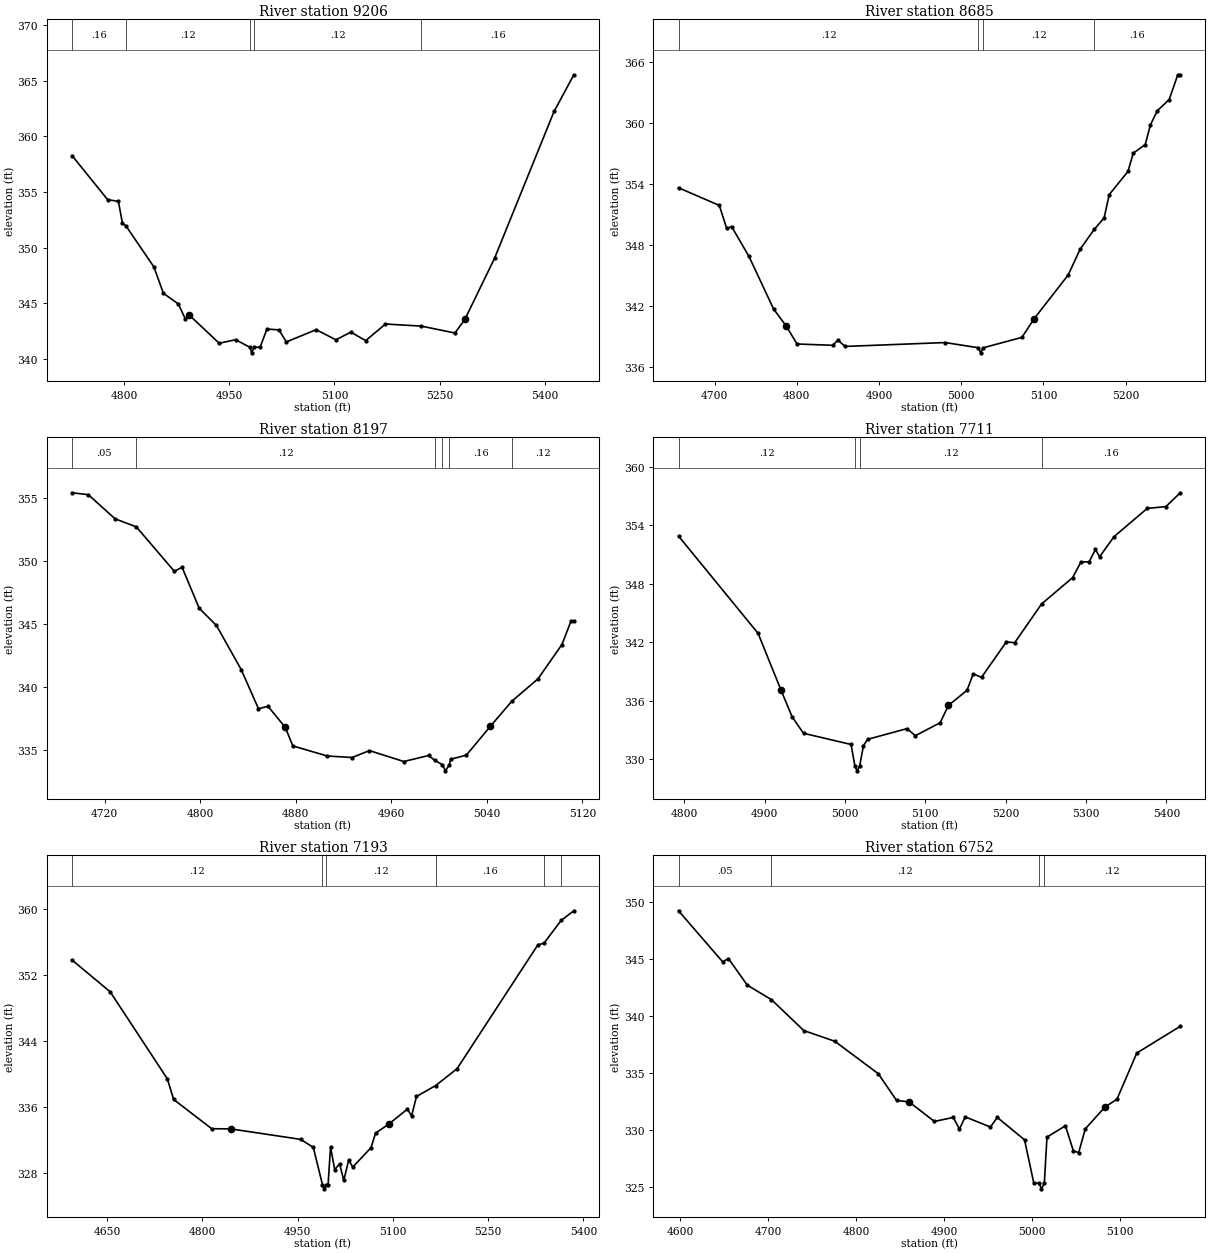
Type RM Length L Ch R = 1 ,9206    ,521,521,521
BEGIN DESCRIPTION:
UNT 161 IN CACR 19.0
END DESCRIPTION:
XS GIS Cut Line= 3
      3706099.59     10671560.16      3706249.61     10671810.19
      3706549.58     10672110.16
#Sta/Elev= 30
  4725.8  358.28  4776.4  354.33  4791.9  354.16  4797.7  352.19  4802.7  351.96
  4842.5  348.28  4856.1  345.91  4877.4  344.95  4887.2  343.62    4893  343.95
  4935.7  341.42  4959.1  341.74  4979.4  341.06  4982.1  340.56  4985.4  341.06
  4994.1  341.07  5003.8   342.7  5020.9  342.62  5031.5  341.54    5074  342.64
  5102.2  341.73  5123.4  342.42  5144.7  341.66  5172.9  343.15  5224.1  342.96
  5271.9  342.34  5286.1  343.56  5328.5  349.06  5413.4  362.25  5441.6  365.54
#Mann= 5 ,-1 , 0
  4725.8     .16       0  4802.7     .12       0  4979.4     .07       0
  4985.4     .12       0  5224.1     .16       0
Bank Sta=4893,5286.1
XS Rating Curve= 0 ,0
Exp/Cntr=0.3,0.1

Type RM Length L Ch R = 1 ,8685    ,488,488,488
BEGIN DESCRIPTION:
UNT 161 IN CACR 18.0
END DESCRIPTION:
XS GIS Cut Line= 3
      3705799.59     10671860.17      3705999.61     10672160.19
      3706199.62      10672310.2
#Sta/Elev= 30
    4656   353.6  4705.6  351.87  4714.6  349.61  4720.6  349.79  4741.7  346.86
  4771.7  341.69  4786.7  340.06  4800.2  338.26  4843.8  338.13  4849.8  338.64
  4858.8  338.02  4980.5   338.4  5020.9  337.89  5023.6  337.39  5026.9  337.89
  5073.9  338.91  5088.5  340.72  5130.1  345.03  5144.7  347.57    5162  349.53
  5173.9  350.65  5180.1  352.93    5203  355.22  5209.3     357  5223.9  357.84
  5230.1  359.76  5238.5  361.16    5253  362.26  5263.5   364.7  5266.6   364.7
#Mann= 4 ,-1 , 0
    4656     .12       0  5020.9     .07       0  5026.9     .12       0
    5162     .16       0
Bank Sta=4786.7,5088.5
XS Rating Curve= 0 ,0
Exp/Cntr=0.3,0.1

Type RM Length L Ch R = 1 ,8197    ,486,486,486
BEGIN DESCRIPTION:
UNT 161 IN CACR 17.0
END DESCRIPTION:
XS GIS Cut Line= 3
      3705449.59     10672160.16      3705649.61     10672410.19
      3705649.61      10672510.2
#Sta/Elev= 30
  4692.7  355.42  4706.3  355.27  4728.7  353.35  4746.5  352.71  4778.4  349.17
  4784.8   349.5  4799.2  346.23  4813.6  344.87  4834.4  341.35  4848.8  338.25
  4856.8  338.44  4871.2  336.77  4877.6  335.29  4906.4  334.49  4927.2  334.37
  4941.7  334.92  4970.5  334.05  4991.3  334.53  4996.3  334.15  5002.7  333.81
  5005.4  333.31  5008.7  333.81  5009.7  334.23  5022.9  334.56  5042.9  336.84
  5060.8  338.83  5082.9  340.63  5102.9  343.35  5110.4  345.19  5112.9  345.19
#Mann= 6 ,-1 , 0
  4692.7     .05       0  4746.5     .12       0  4996.3     .16       0
  5002.7     .07       0  5008.7     .16       0  5060.8     .12       0
Bank Sta=4871.2,5042.9
XS Rating Curve= 0 ,0
Exp/Cntr=0.3,0.1

Type RM Length L Ch R = 1 ,7711    ,518,518,518
BEGIN DESCRIPTION:
UNT 161 IN CACR 16.0
END DESCRIPTION:
XS GIS Cut Line= 3
      3705099.63     10672460.21      3705249.61     10672610.19
       3705649.6     10672710.19
#Sta/Elev= 30
    4793  352.91    4892  342.91  4920.2  337.14  4934.4  334.32  4948.5  332.64
  5007.7  331.49  5012.4  329.28  5015.2  328.78  5018.4  329.28  5023.1  331.37
  5028.3  332.02  5077.3  333.12  5087.6  332.39  5118.5  333.72  5128.8   335.5
    5152  337.06  5159.7  338.75    5170  338.39  5200.9  342.03  5211.3  341.95
  5244.7  345.93  5283.4  348.64  5293.7  350.24    5304  350.27  5311.8  351.54
  5316.9  350.78  5334.9  352.85  5376.2  355.75  5399.4  355.94  5417.4  357.36
#Mann= 4 ,-1 , 0
    4793     .12       0  5012.4     .07       0  5018.4     .12       0
  5244.7     .16       0
Bank Sta=4920.2,5128.8
XS Rating Curve= 0 ,0
Exp/Cntr=0.3,0.1

Type RM Length L Ch R = 1 ,7193    ,441,441,441
BEGIN DESCRIPTION:
UNT 161 IN CACR 15.0
END DESCRIPTION:
XS GIS Cut Line= 3
      3704949.61     10672560.16      3704949.61     10672960.19
      3705199.58     10673260.15
#Sta/Elev= 30
  4594.6  353.86  4654.6  350.02  4744.6  339.47  4754.6  336.96  4814.6  333.41
  4844.6  333.39  4954.6  332.12  4974.6  331.15  4989.1  326.62  4991.9  326.12
  4995.1  326.62  4997.9  326.62  5001.8  331.23  5008.3  328.44  5016.1  329.16
  5022.6  327.14  5030.4  329.59  5036.9  328.77  5065.6  331.12  5072.7  332.87
  5094.2  334.01  5122.9  335.79  5129.4  334.96  5137.2  337.32  5167.3  338.64
    5201  340.68  5328.5  355.72  5337.9   355.9  5365.2  358.68  5385.1  359.84
#Mann= 6 ,-1 , 0
  4594.6     .12       0  4989.1     .07       0  4995.1     .12       0
  5167.3     .16       0  5337.9     .12       0  5365.2     .05       0
Bank Sta=4844.6,5094.2
XS Rating Curve= 0 ,0
Exp/Cntr=0.3,0.1

Type RM Length L Ch R = 1 ,6752    ,446,446,446
BEGIN DESCRIPTION:
UNT 161 IN CACR 14.0
END DESCRIPTION:
XS GIS Cut Line= 3
      3704299.57     10672910.16      3704599.61     10673160.19
      3704749.58     10673260.17
#Sta/Elev= 30
  4598.1   349.2  4648.3  344.73  4654.8  345.02  4676.3  342.69  4703.8  341.42
  4740.7  338.71  4775.8  337.78  4825.3  334.94  4846.1   332.6  4860.4  332.47
  4889.1  330.76  4910.6  331.11  4917.7  330.09  4924.2  331.16  4952.9  330.27
  4960.7  331.11  4991.7  329.15  5002.2  325.37  5008.2  325.36  5010.9  324.86
  5014.2  325.36  5017.2  329.39  5038.2  330.38  5047.3  328.17  5053.3  328.04
  5060.8  330.11  5083.3  332.03  5096.8   332.7  5119.4  336.75  5168.9  339.09
#Mann= 4 ,-1 , 0
  4598.1     .05       0  4703.8     .12       0  5008.2     .07       0
  5014.2     .12       0
Bank Sta=4860.4,5083.3
XS Rating Curve= 0 ,0
Exp/Cntr=0.3,0.1

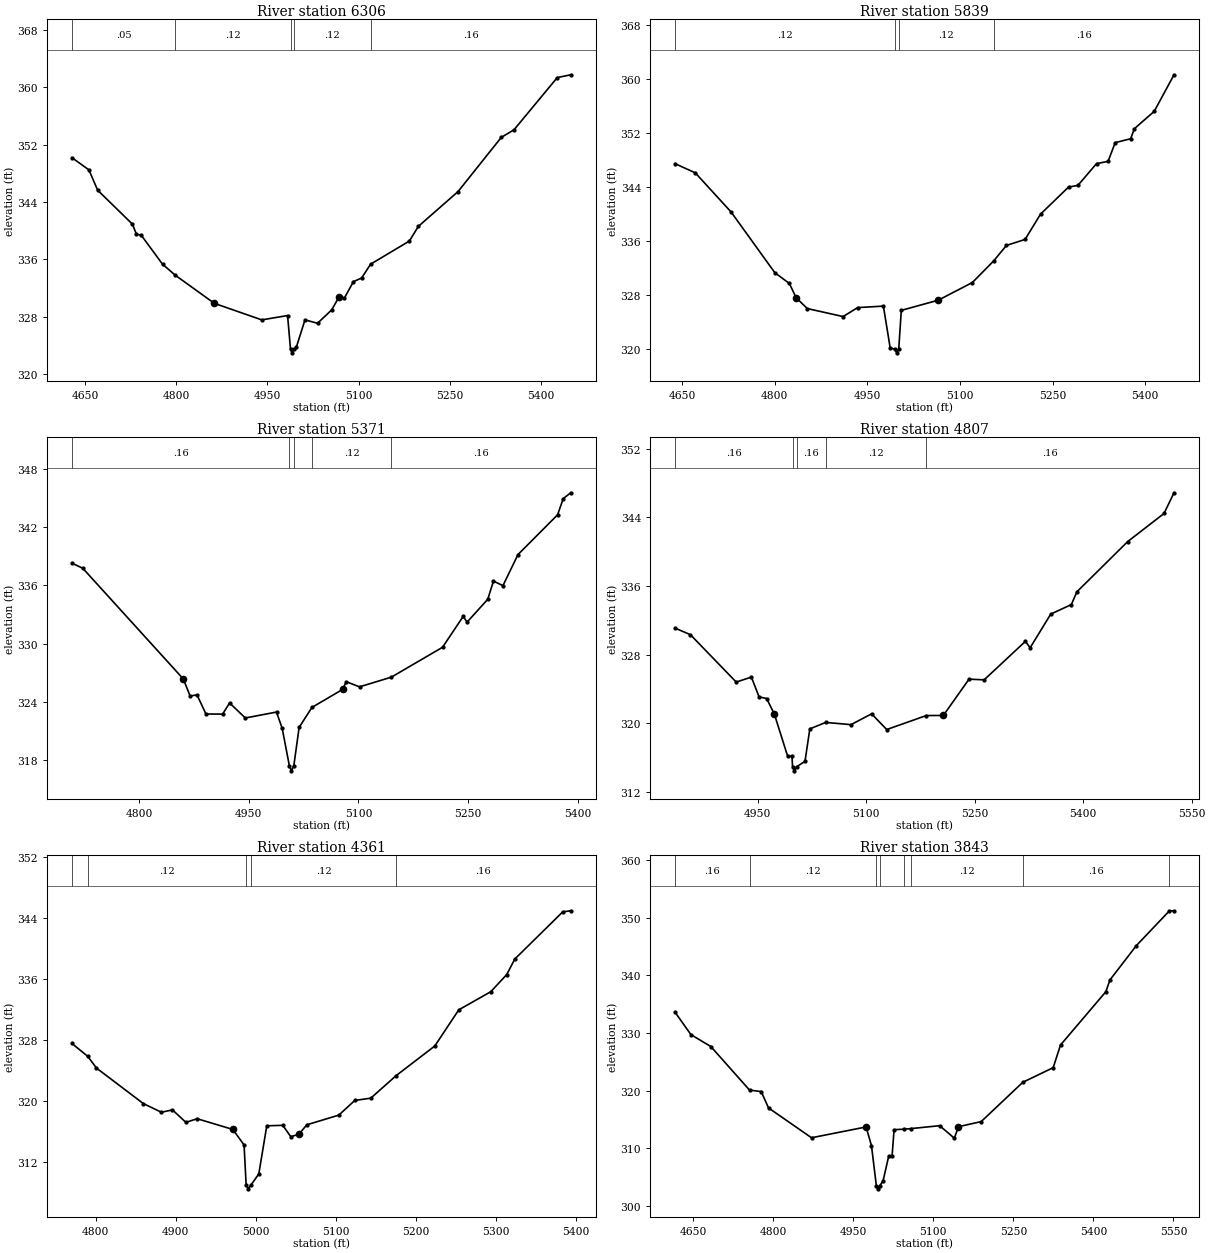
Type RM Length L Ch R = 1 ,6306    ,467,467,467
BEGIN DESCRIPTION:
UNT 161 IN CACR 13.0
END DESCRIPTION:
XS GIS Cut Line= 3
      3704149.59     10673210.16      3704399.61     10673510.19
      3704749.64     10673760.21
#Sta/Elev= 30
  4628.3  350.18  4656.3  348.47  4670.6  345.64  4727.9  340.89  4734.4  339.48
  4742.2  339.37  4777.4   335.3  4798.3  333.77  4862.6  329.84  4940.7  327.53
  4983.1  328.14  4987.9  323.43  4990.6  322.93  4993.9  323.43  4997.4  323.69
  5011.7  327.53  5032.4  327.06  5055.7  328.93    5068  330.77  5076.6  330.58
  5091.4  332.87  5104.9  333.38  5119.7  335.31  5183.5  338.54  5198.3  340.59
  5263.4  345.43  5334.7  353.01  5355.6  354.07  5426.8  361.36    5449  361.75
#Mann= 5 ,-1 , 0
  4628.3     .05       0  4798.3     .12       0  4987.9     .07       0
  4993.9     .12       0  5119.7     .16       0
Bank Sta=4862.6,5068
XS Rating Curve= 0 ,0
Exp/Cntr=0.3,0.1

Type RM Length L Ch R = 1 ,5839    ,468,468,468
BEGIN DESCRIPTION:
UNT 161 IN CACR 12.0
END DESCRIPTION:
XS GIS Cut Line= 3
      3703849.56     10673710.17      3704199.61     10673860.19
      3704599.57     10674010.18
#Sta/Elev= 30
  4638.5  347.48  4671.2  346.12  4729.2  340.31  4799.9  331.32  4823.5  329.72
  4834.4  327.61  4852.5     326  4910.5  324.81  4934.1  326.14  4975.8  326.36
  4986.7   320.2  4994.6  319.93  4997.3  319.43  5000.6  319.93  5004.8  325.73
  5064.7  327.24  5119.9  329.86  5154.2  333.04  5175.1  335.36  5205.3  336.25
  5230.3     340  5275.7  344.02  5290.8  344.26    5321  347.49  5339.7  347.83
  5351.3  350.61  5376.2  351.18  5382.5  352.69  5414.5  355.25  5446.5  360.67
#Mann= 4 ,-1 , 0
  4638.5     .12       0  4994.6     .07       0  5000.6     .12       0
  5154.2     .16       0
Bank Sta=4834.4,5064.7
XS Rating Curve= 0 ,0
Exp/Cntr=0.3,0.1

Type RM Length L Ch R = 1 ,5371    ,564,564,564
BEGIN DESCRIPTION:
UNT 161 IN CACR 11.0
END DESCRIPTION:
XS GIS Cut Line= 3
      3703749.65     10674110.21      3703999.61     10674210.19
      3704399.59     10674310.18
#Sta/Elev= 30
  4708.5  338.29  4723.3  337.77  4860.6  326.36    4870   324.6  4879.4  324.71
  4891.6  322.74  4914.4  322.73  4923.9  323.88  4945.4  322.33    4988  322.94
  4995.8  321.25  5005.6  317.38  5008.4  316.88  5011.6  317.38  5018.9  321.36
  5036.4  323.42  5078.2  325.27  5083.4  326.07  5101.4  325.54  5144.9  326.54
  5214.8  329.62  5243.1  332.81  5248.3  332.21  5276.6  334.57  5284.4  336.45
  5297.3  335.97  5317.9  339.18    5372  343.28  5379.7  344.95    5390  345.55
#Mann= 5 ,-1 , 0
  4708.5     .16       0  5005.6     .07       0  5011.6     .16       0
  5036.4     .12       0  5144.9     .16       0
Bank Sta=4860.6,5078.2
XS Rating Curve= 0 ,0
Exp/Cntr=0.3,0.1

Type RM Length L Ch R = 1 ,4807    ,446,446,446
BEGIN DESCRIPTION:
UNT 161 IN CACR 10.0
END DESCRIPTION:
XS GIS Cut Line= 3
      3703649.57     10674560.18      3703799.61     10674610.19
      3704199.64     10674960.22
#Sta/Elev= 30
  4835.9   331.1    4857  330.34  4920.3  324.82  4941.3   325.4  4951.9   323.1
  4962.4   322.9    4973   321.1  4991.4  316.19  4997.4  316.19  4998.2  314.98
  5000.9  314.48  5004.2  314.98  5015.4  315.58  5022.1  319.37  5044.1  320.12
    5079  319.86  5107.5  321.12  5128.4  319.29  5183.1  320.92  5206.7  320.93
  5242.2  325.16  5263.1  325.08  5320.1  329.56  5326.7  328.82  5355.2  332.74
  5383.7  333.85  5391.3  335.33  5461.5  341.18  5511.8  344.46  5525.6  346.87
#Mann= 5 ,-1 , 0
  4835.9     .16       0  4998.2     .07       0  5004.2     .16       0
  5044.1     .12       0  5183.1     .16       0
Bank Sta=4973,5206.7
XS Rating Curve= 0 ,0
Exp/Cntr=0.3,0.1

Type RM Length L Ch R = 1 ,4361    ,518,518,518
BEGIN DESCRIPTION:
UNT 161 IN CACR 9.0
END DESCRIPTION:
XS GIS Cut Line= 3
      3703549.65     10674910.21      3703749.61     10675010.19
      3704149.64     10675010.19
#Sta/Elev= 30
  4770.1  327.54  4789.8  325.86  4800.8  324.31  4859.5  319.64  4881.9  318.51
  4895.8  318.82  4912.6  317.18  4926.6  317.66  4971.3  316.25  4985.3  314.21
  4987.9  308.95  4990.6  308.45  4993.9  308.95  5003.7  310.41  5013.7  316.73
  5033.7  316.79  5043.7   315.3  5053.7  315.61  5063.7  316.86  5103.7  318.13
  5123.7  320.06  5143.7  320.36  5175.3  323.31  5223.7  327.21  5253.7  331.96
  5293.7  334.34  5313.7   336.6  5323.7  338.63  5383.7  344.83  5393.7  344.97
#Mann= 5 ,-1 , 0
  4770.1     .16       0  4789.8     .12       0  4987.9     .07       0
  4993.9     .12       0  5175.3     .16       0
Bank Sta=4971.3,5053.7
XS Rating Curve= 0 ,0
Exp/Cntr=0.3,0.1

Type RM Length L Ch R = 1 ,3843    ,414,414,414
BEGIN DESCRIPTION:
UNT 161 IN CACR 8.0
END DESCRIPTION:
XS GIS Cut Line= 3
      3703649.63     10675810.15      3703849.61     10675460.19
      3704249.63     10675110.17
#Sta/Elev= 30
  4616.4  333.58  4645.9  329.73  4683.3  327.66  4755.7  320.12  4777.6  319.86
  4791.3  317.03  4871.9  311.86  4974.1  313.73  4984.2  310.49  4993.4  303.51
  4996.2  303.01  4999.4  303.51  5005.8  304.35  5016.6  308.71  5022.8  308.71
  5026.6  313.26  5044.7  313.34  5058.5  313.45    5112  313.95  5139.5  311.78
  5147.1  313.77  5189.8  314.66  5267.7  321.47  5324.6     324  5338.4  327.93
  5423.3  337.16  5430.9  339.19  5480.3  345.13  5542.3  351.16    5551  351.18
#Mann= 8 ,-1 , 0
  4616.4     .16       0  4755.7     .12       0  4993.4     .07       0
  4999.4     .12       0  5044.7     .16       0  5058.5     .12       0
  5267.7     .16       0  5542.3     .12       0
Bank Sta=4974.1,5147.1
XS Rating Curve= 0 ,0
Exp/Cntr=0.3,0.1

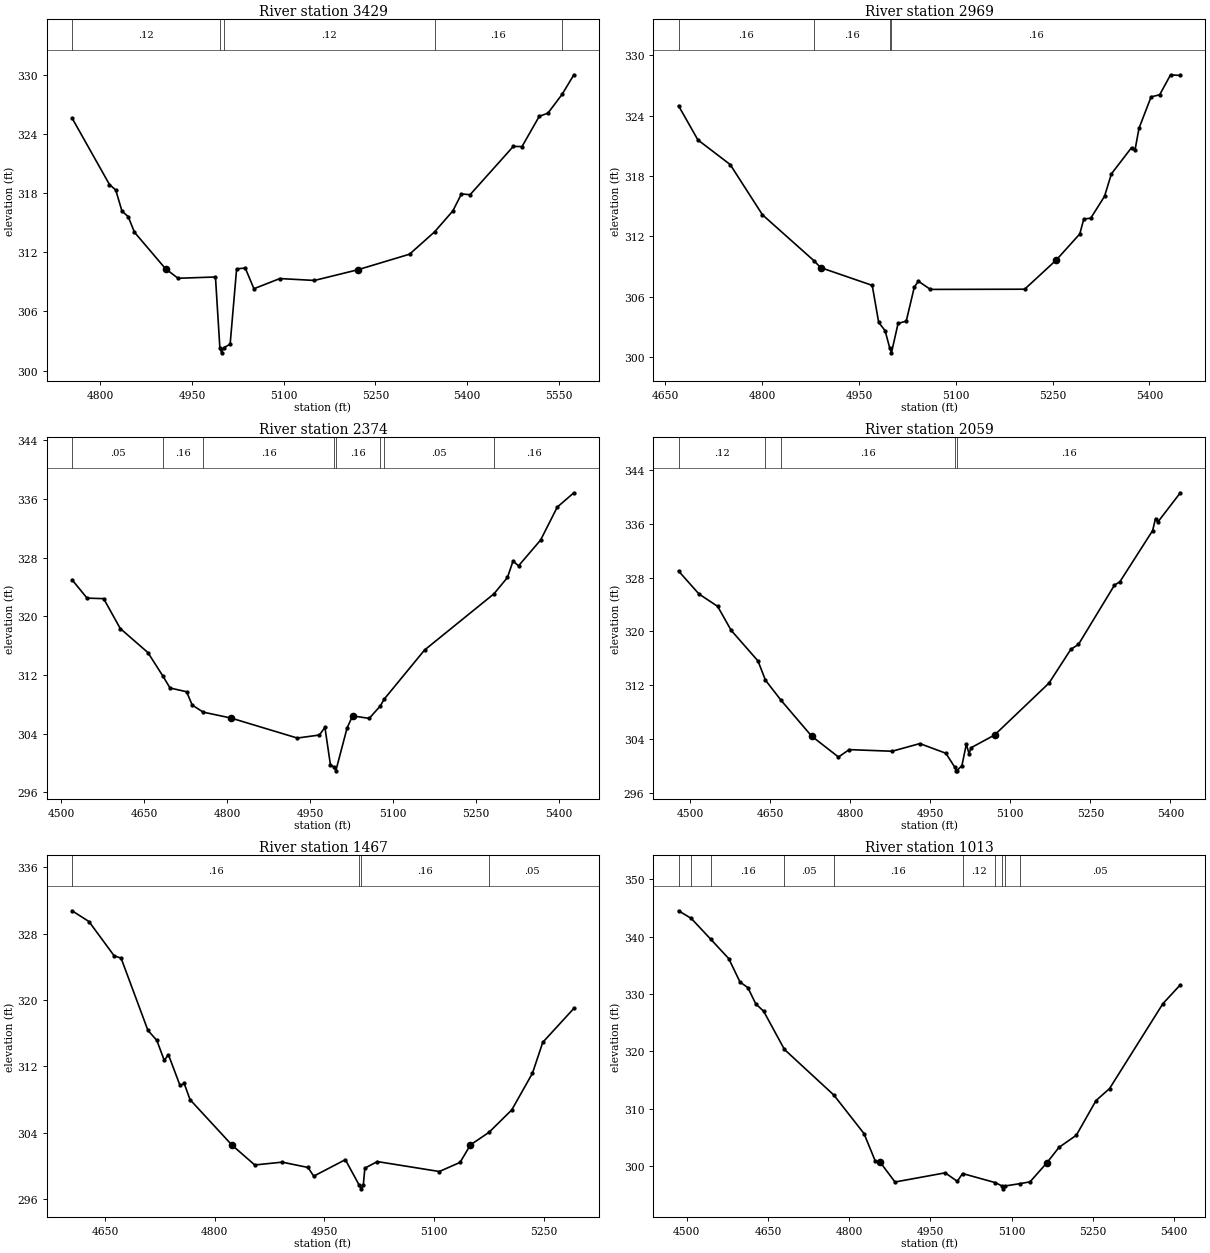
Type RM Length L Ch R = 1 ,3429    ,460,460,460
BEGIN DESCRIPTION:
UNT 161 IN CACR 7.0
END DESCRIPTION:
XS GIS Cut Line= 3
      3703799.63     10675860.18      3704049.61     10675810.19
       3704449.6      10675410.2
#Sta/Elev= 30
  4753.9   325.6  4815.1  318.86  4825.3  318.31  4835.5  316.17  4845.7  315.61
  4855.9  314.03  4906.8  310.32  4927.2  309.36  4988.4  309.49  4995.6   302.3
  4998.4   301.8  5001.6   302.3  5012.4  302.68    5023  310.31  5037.1   310.4
  5051.3   308.3  5093.7  309.33  5150.3  309.14    5221  310.22  5305.8   311.8
  5346.8  314.07  5376.5  316.18  5390.7  317.91  5404.8  317.83  5475.5  322.73
  5489.7  322.71  5517.9  325.78  5532.1   326.1  5555.2     328  5574.5  329.99
#Mann= 5 ,-1 , 0
  4753.9     .12       0  4995.6     .07       0  5001.6     .12       0
  5346.8     .16       0  5555.2     .12       0
Bank Sta=4906.8,5221
XS Rating Curve= 0 ,0
Exp/Cntr=0.3,0.1

Type RM Length L Ch R = 1 ,2969    ,595,595,595
BEGIN DESCRIPTION:
UNT 161 IN CACR 6.0
END DESCRIPTION:
XS GIS Cut Line= 3
      3703849.56     10676210.19      3704199.61     10676210.19
      3704599.57     10676060.21
#Sta/Elev= 30
  4670.6  324.98  4700.6  321.58  4750.6  319.13  4800.6  314.13  4880.6  309.55
  4890.6  308.88  4970.6  307.11  4980.6  303.43  4990.6   302.6  4997.6   300.9
  5000.4   300.4  5010.6  303.32  5023.3  303.56  5035.8  306.94    5042  307.53
  5060.7  306.71  5206.7  306.73  5255.6  309.63  5292.1  312.23  5298.3  313.72
    5309  313.79  5330.4  315.97    5341   318.2  5372.2  320.81  5377.5  320.54
  5383.8  322.74  5402.5  325.86  5415.8  326.07  5432.7  328.06  5447.8  327.99
#Mann= 4 ,-1 , 0
  4670.6     .16       0  4880.6     .16       0  4997.6     .07       0
  5000.4     .16       0
Bank Sta=4890.6,5255.6
XS Rating Curve= 0 ,0
Exp/Cntr=0.3,0.1

Type RM Length L Ch R = 1 ,2374    ,315,315,315
BEGIN DESCRIPTION:
UNT 161 IN CACR 5.0
END DESCRIPTION:
XS GIS Cut Line= 2
      3703902.55     10676659.52      3704809.65     10676659.52
#Sta/Elev= 30
  4519.6  324.99  4546.7  322.49  4576.7  322.42  4606.7  318.35  4656.7  315.07
  4684.1  311.83  4696.7  310.24  4726.7  309.73  4736.7  307.92  4756.7  306.95
  4806.7  306.15  4926.7  303.42  4966.7  303.83  4976.7  304.88  4986.7  299.74
  4993.7  299.45  4996.4  298.95  5016.7  304.78  5026.7  306.44  5056.7   306.1
  5076.7  307.78  5083.8  308.72  5156.7  315.41  5282.3  323.08  5306.7  325.31
  5316.7  327.54  5326.7  326.89  5366.7  330.42  5396.7   334.9  5426.7  336.85
#Mann= 8 ,-1 , 0
  4519.6     .05       0  4684.1     .16       0  4756.7     .16       0
  4993.7     .03       0  4996.4     .16       0  5076.7     .16       0
  5083.8     .05       0  5282.3     .16       0
Bank Sta=4806.7,5026.7
XS Rating Curve= 0 ,0
Exp/Cntr=0.3,0.1

Type RM Length L Ch R = 1 ,2059    ,592,592,592
BEGIN DESCRIPTION:
UNT 161 IN CACR 4.0
END DESCRIPTION:
XS GIS Cut Line= 3
      3703941.58     10676887.39      3704488.47     10676945.98
       3704870.4     10676865.69
#Sta/Elev= 30
  4478.2     329  4516.4  325.58  4551.5  323.73  4576.8  320.16  4627.1   315.6
  4641.1  312.73  4670.6  309.71  4727.6   304.4  4777.9  301.29    4798  302.39
  4878.5  302.15  4930.4  303.29  4979.1  301.85  4996.2  299.73  4998.9  299.23
  4999.4  299.23  5009.2     300  5017.5  303.19  5022.6  301.76  5026.3  302.67
  5070.3  304.56  5172.4   312.3  5213.3  317.33  5227.6  318.06  5295.1  326.89
  5305.3   327.4  5366.6  335.02    5372  336.81  5377.1  336.37  5418.5  340.65
#Mann= 5 ,-1 , 0
  4478.2     .12       0  4641.1     .16       0  4670.6     .16       0
  4996.2     .07       0  4999.4     .16       0
Bank Sta=4727.6,5070.3
XS Rating Curve= 0 ,0
Exp/Cntr=0.3,0.1

Type RM Length L Ch R = 1 ,1467    ,454,454,454
BEGIN DESCRIPTION:
UNT 161 IN CACR 3.0
END DESCRIPTION:
XS GIS Cut Line= 3
       3703949.6     10677010.17      3704149.61     10677360.19
      3704349.63     10677560.21
#Sta/Elev= 30
  4605.1  330.76  4628.2  329.46  4662.7  325.32  4672.1  325.05  4708.8  316.33
    4721  315.12  4731.1  312.71  4736.8   313.4  4752.7  309.68  4758.4  309.92
  4766.4  307.97  4823.9  302.47  4854.9  300.09  4892.3  300.43  4927.6  299.79
  4935.5  298.74  4978.7  300.73  4997.3  297.71  5000.1  297.21  5003.3  297.71
  5005.4  299.71  5022.4   300.5  5107.2   299.3  5135.5   300.4  5149.7  302.51
  5175.1  304.03  5206.2  306.73  5234.5  311.16  5248.6  314.89  5291.1  318.98
#Mann= 4 ,-1 , 0
  4605.1     .16       0  4997.3     .07       0  5000.1     .16       0
  5175.1     .05       0
Bank Sta=4823.9,5149.7
XS Rating Curve= 0 ,0
Exp/Cntr=0.3,0.1

Type RM Length L Ch R = 1 ,1013    ,487,487,487
BEGIN DESCRIPTION:
UNT 161 IN CACR 2.0
END DESCRIPTION:
XS GIS Cut Line= 3
       3703399.6     10677260.18      3703799.61     10677560.19
      3703949.61     10677960.18
#Sta/Elev= 30
  4484.6  344.51    4508  343.19    4544  339.56  4577.3  336.18  4598.2  332.09
  4612.7  331.11  4627.3  328.28  4641.9  326.99  4680.3  320.33  4771.5  312.39
  4827.3  305.67  4848.2  300.86  4856.5  300.75  4884.6  297.22  4977.3  298.82
  4999.7  297.34  5009.4   298.7    5070  297.11  5082.2  296.53  5084.9  296.03
  5088.2  296.53  5115.7  296.94  5134.1  297.25  5165.3  300.58  5187.5  303.25
  5219.6  305.37  5256.1  311.43    5281  313.51  5379.8  328.34  5411.8   331.6
#Mann= 10 ,-1 , 0
  4484.6     .16       0    4508     .05       0    4544     .16       0
  4680.3     .05       0  4771.5     .16       0  5009.4     .12       0
    5070     .16       0  5082.2     .07       0  5088.2     .16       0
  5115.7     .05       0
Bank Sta=4856.5,5165.3
XS Rating Curve= 0 ,0
Exp/Cntr=0.3,0.1

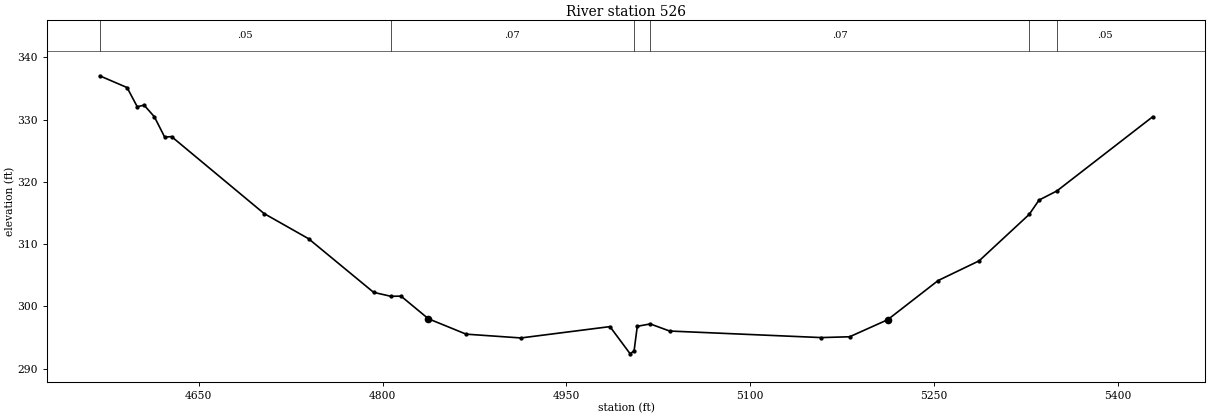
Type RM Length L Ch R = 1 ,526     ,0,0,0
BEGIN DESCRIPTION:
UNT 161 IN CACR 1.0
END DESCRIPTION:
XS GIS Cut Line= 3
      3703299.61     10677510.19      3703499.61     10677910.19
      3703899.59     10678010.18
#Sta/Elev= 30
  4569.1  337.03  4591.5  335.14  4599.8  332.06  4605.4  332.32  4613.8  330.44
  4622.2  327.18  4627.8  327.27  4703.3  314.92  4739.6  310.88  4792.7  302.27
  4806.7  301.64  4815.1  301.66  4837.4  298.03  4868.2  295.56  4912.9  294.95
  4985.6  296.77  5002.1   292.4  5005.3   292.9  5007.9  296.82  5018.5   297.2
  5034.3  296.06    5158  295.01  5181.2  295.14  5212.2  297.87  5253.4  304.16
  5286.9  307.33  5327.7  314.77  5335.8  317.08  5350.4  318.55  5428.6  330.46
#Mann= 6 ,-1 , 0
  4569.1     .05       0  4806.7     .07       0  5005.3     .05       0
  5018.5     .07       0  5327.7     .12       0  5350.4     .05       0
Bank Sta=4837.4,5212.2
XS Rating Curve= 0 ,0
Exp/Cntr=0.3,0.1

Chan Stop Cuts=-1
Use User Specified Reach Order=0
Composite Channel Slope=5