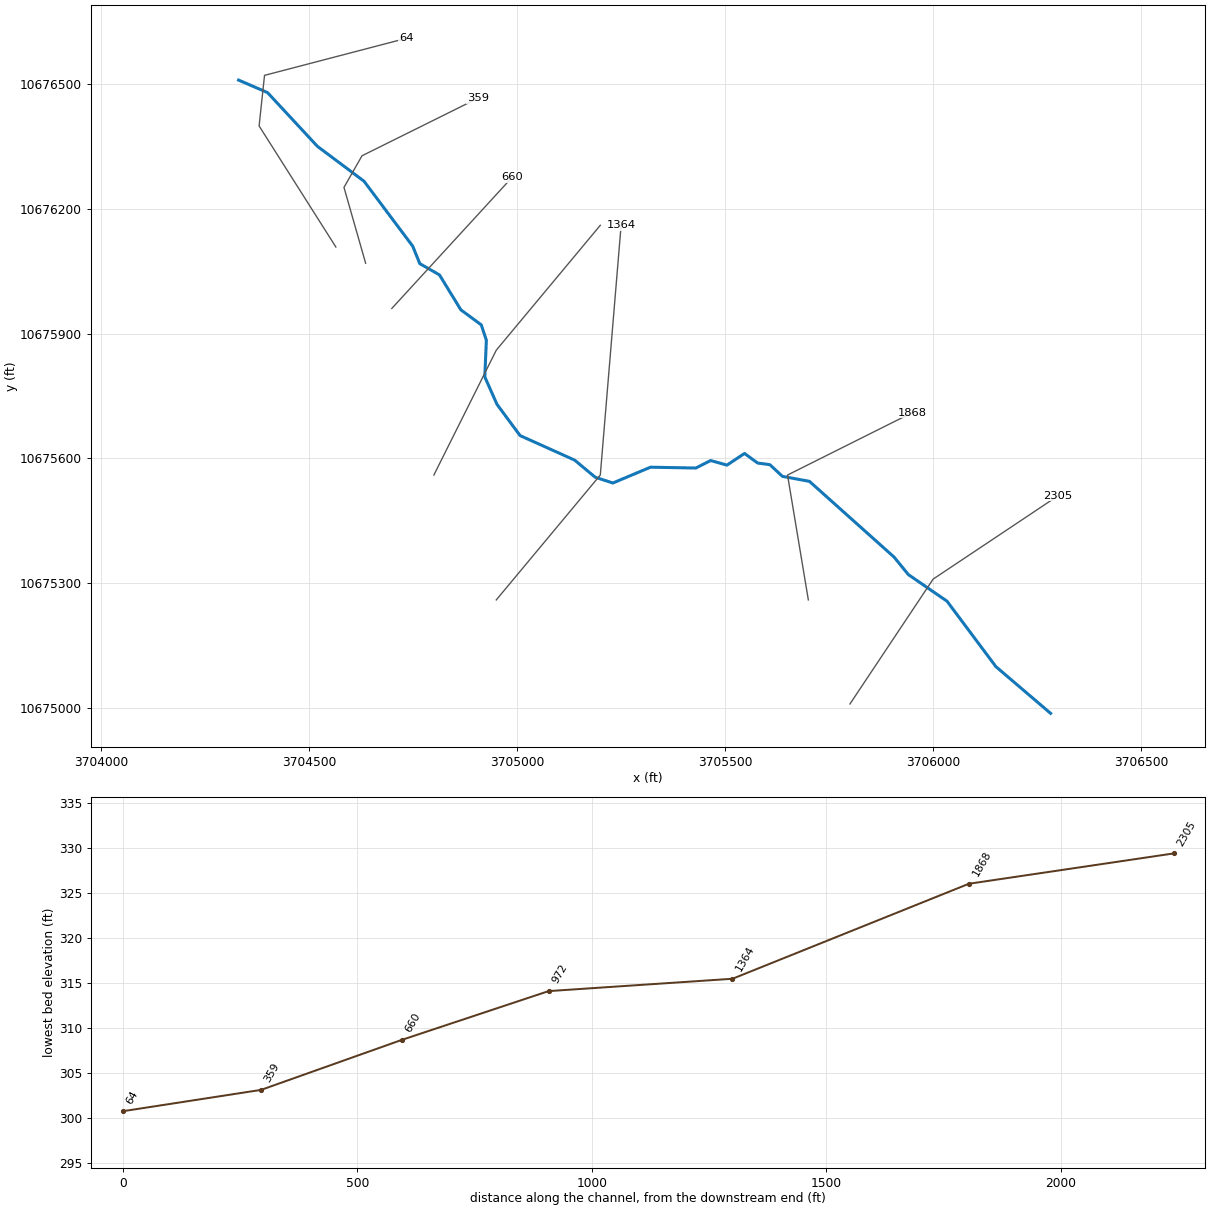
--- UNT 162 IN CACR.prj (project) ---

Proj Title=UNT 162 IN CACR Base Level Engineering
Current Plan=p01
Default Exp/Contr=0.3,0.1
English Units
Geom File=g01
Flow File=f01
Plan File=p01
Y Axis Title=Elevation
X Axis Title(PF)=Main Channel Distance
X Axis Title(XS)=Station
BEGIN DESCRIPTION:
UNT 162 IN CACR
END DESCRIPTION:
DSS Export Rating Curves= 0
DSS Export Rating Curve Sorted= 0
DSS Export Volume Flow Curves= 0
DXF OffsetX= 0
DXF OffsetY= 0
DXF ScaleX= 1
DXF ScaleY= 10

--- UNT 162 IN CACR.p01 (plan) ---

Plan Title=Multiple Run
Short Identifier=Multiple
Geom File=g01
Flow File=f01
Subcritical Flow
K Sum by GR= 0
Std Step Tol= 0.01
Critical Tol= 0.01
Num of Std Step Trials= 20
Max Error Tol= 0.3
Flow Tol Ratio= 0.001
Split Flow NTrial= 30
Split Flow Tol= 0.02
Split Flow Ratio= 0.02
Log Output Level= 0
Friction Slope Method= 1
Unsteady Friction Slope Method= 2
Unsteady Bridges Friction Slope Method= 1
Parabolic Critical Depth
Global Vel Dist=  1 , 1 , 1
Global Log Level= 0
CheckData=True
Encroach Param= -1, 0, 0, 0
BEGIN DESCRIPTION:
Multiple Run
END DESCRIPTION:

--- UNT 162 IN CACR.f01 (steady flow) ---

Flow Title=Multiple
Program Version=4.10
Number of Profiles= 7
Profile Names=10-year,25-year,50-year,1pct_min,100-year,1pct_plu,500-year
River Rch & RM=UNT 162 IN CACR,Reach-1         ,2305
     217     279     327     284     384     520     529
River Rch & RM=UNT 162 IN CACR,Reach-1         ,64
     217     279     327     284     384     520     529
Boundary for River Rch & Prof#=UNT 162 IN CACR,Reach-1         , 1
Up Type= 0
Dn Type= 3
Dn Slope=0.00794
Boundary for River Rch & Prof#=UNT 162 IN CACR,Reach-1         , 2
Up Type= 0
Dn Type= 3
Dn Slope=0.00794
Boundary for River Rch & Prof#=UNT 162 IN CACR,Reach-1         , 3
Up Type= 0
Dn Type= 3
Dn Slope=0.00794
Boundary for River Rch & Prof#=UNT 162 IN CACR,Reach-1         , 4
Up Type= 0
Dn Type= 3
Dn Slope=0.00794
Boundary for River Rch & Prof#=UNT 162 IN CACR,Reach-1         , 5
Up Type= 0
Dn Type= 3
Dn Slope=0.00794
Boundary for River Rch & Prof#=UNT 162 IN CACR,Reach-1         , 6
Up Type= 0
Dn Type= 3
Dn Slope=0.00794
Boundary for River Rch & Prof#=UNT 162 IN CACR,Reach-1         , 7
Up Type= 0
Dn Type= 3
Dn Slope=0.00794
DSS Import GetInterval= 0
DSS Import GetPeak= 0
DSS Import FillOption= 0

--- UNT 162 IN CACR.g01 (geometry) ---

Geom Title=Existing Conditions
Program Version=4.10

River Reach=UNT 162 IN CACR ,Reach-1
Reach XY= 30
      3706281.96     10674987.58      3706150.25       10675100.
        3706033.       10675257.        3705940.       10675321.
      3705905.75       10675363.      3705702.25       10675545.
      3705637.25       10675557.      3705607.25       10675585.
      3705577.75       10675589.      3705546.25       10675612.
        3705504.       10675584.      3705464.75       10675595.
      3705429.25       10675577.      3705320.25       10675579.
      3705229.75       10675541.      3705187.25       10675555.
        3705138.       10675596.      3705006.75       10675655.
      3704951.25       10675730.        3704922.       10675796.
      3704925.75       10675884.       3704913.5       10675921.
       3704864.5       10675957.        3704813.       10676041.
      3704765.75       10676068.      3704748.75       10676110.
      3704631.75       10676266.       3704519.5       10676350.
      3704399.75       10676479.      3704330.25       10676509.

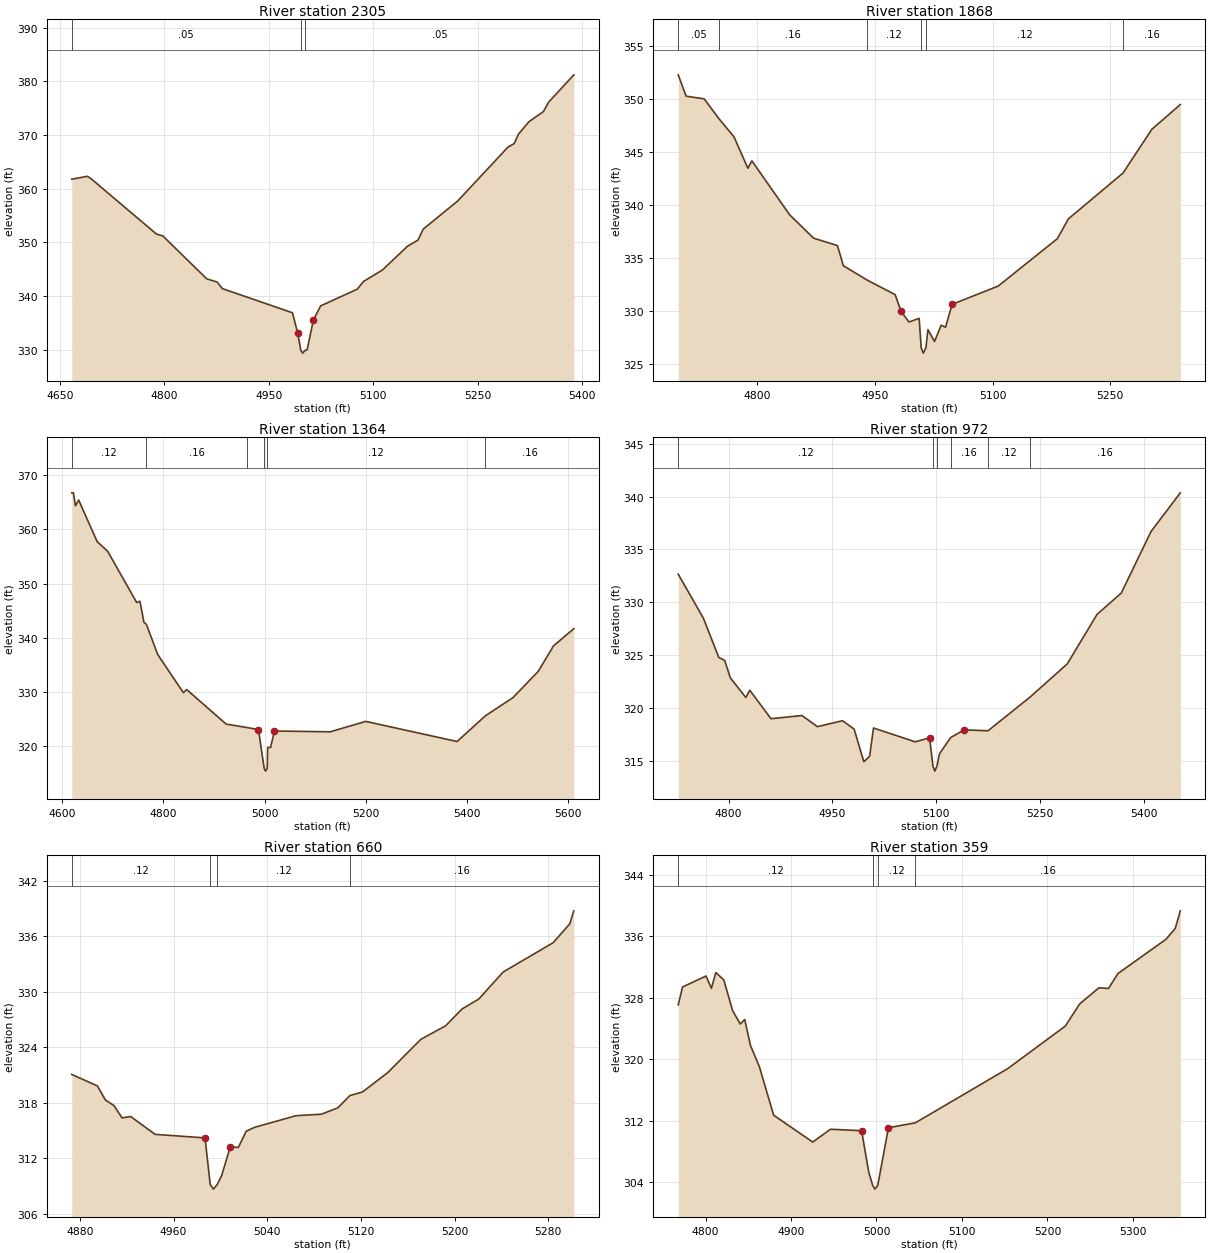
Type RM Length L Ch R = 1 ,2305    ,437,437,437
BEGIN DESCRIPTION:
UNT 162 IN CACR 5.0
END DESCRIPTION:
XS GIS Cut Line= 3
      3705799.63     10675010.21      3705999.61     10675310.19
      3706299.63      10675510.2
#Sta/Elev= 30
  4667.2  361.77  4689.7  362.31  4695.7  361.78  4788.9  351.54  4797.9  351.21
    4861  343.21    4876   342.6  4883.5  341.38  4984.2  336.88  4991.7  333.09
  4996.2  329.86  4998.9  329.36  5002.2  329.86  5005.2  329.95  5014.2  335.51
  5024.7  338.17  5077.3  341.28  5086.3  342.72  5113.4  344.85  5149.4  349.28
  5164.4  350.42  5171.9  352.46  5221.5  357.71  5293.6  367.74  5302.6  368.41
  5308.7  370.15  5323.7  372.47  5344.7  374.39  5352.2  376.15  5388.3  381.22
#Mann= 3 ,-1 , 0
  4667.2     .05       0  4996.2     .03       0  5002.2     .05       0
Bank Sta=4991.7,5014.2
XS Rating Curve= 0 ,0
Exp/Cntr=0.3,0.1

Type RM Length L Ch R = 1 ,1868    ,504,504,504
BEGIN DESCRIPTION:
UNT 162 IN CACR 4.0
END DESCRIPTION:
XS GIS Cut Line= 3
      3705699.61     10675260.18      3705649.61     10675560.19
      3705949.65     10675710.21
#Sta/Elev= 30
  4699.5   352.3  4709.6  350.28  4732.5  350.03  4751.3  348.16  4770.5  346.44
  4788.2  343.47  4793.3  344.17  4841.4  339.07  4871.9  336.86  4902.3  336.16
  4909.9  334.25  4940.6  332.88  4975.8  331.52  4983.4  329.93  4993.5  328.93
  5006.4  329.28    5009  326.49  5011.8  325.99    5015  326.49  5017.6  328.21
    5026  327.09  5034.4  328.63    5040  328.44  5048.4   330.6  5107.1  332.33
  5182.5  336.81  5196.5  338.68  5266.2  343.02  5302.7  347.14  5339.1  349.49
#Mann= 6 ,-1 , 0
  4699.5     .05       0  4751.3     .16       0  4940.6     .12       0
    5009     .07       0    5015     .12       0  5266.2     .16       0
Bank Sta=4983.4,5048.4
XS Rating Curve= 0 ,0
Exp/Cntr=0.3,0.1

Type RM Length L Ch R = 1 ,1364    ,392,392,392
BEGIN DESCRIPTION:
UNT 162 IN CACR 3.0
END DESCRIPTION:
XS GIS Cut Line= 3
      3704949.58     10675260.15      3705199.61     10675560.19
      3705249.61     10676160.15
#Sta/Elev= 30
  4618.9  366.76  4622.2  366.76  4626.1  364.37  4632.6  365.42  4669.1  357.76
  4689.9  355.98  4747.2  346.54  4753.7  346.76  4761.5  342.91  4766.5  342.49
  4788.8  336.94  4839.6   329.9  4846.1  330.48  4924.2  324.11  4964.5  323.49
    4988   323.1  4999.3  315.94    5002  315.44  5005.3  315.94  5006.2   319.8
    5012   319.8  5019.5  322.84  5129.9  322.69  5200.1  324.61  5380.7   320.9
  5436.6  325.64  5491.1  328.99  5541.3  333.86  5571.4  338.55  5611.5  341.71
#Mann= 6 ,-1 , 0
  4618.9     .12       0  4766.5     .16       0  4964.5     .12       0
  4999.3     .07       0  5005.3     .12       0  5436.6     .16       0
Bank Sta=4988,5019.5
XS Rating Curve= 0 ,0
Exp/Cntr=0.3,0.1

Type RM Length L Ch R = 1 ,972     ,312,312,312
BEGIN DESCRIPTION:
UNT 162 IN CACR 2.0
END DESCRIPTION:
XS GIS Cut Line= 3
      3704799.62     10675560.22      3704949.61     10675860.19
      3705199.61     10676160.19
#Sta/Elev= 30
  4727.2  332.67  4763.5  328.52  4785.9   324.8  4794.3  324.53  4802.6  322.87
    4825  321.02  4830.6  321.71  4861.3  319.02  4906.1  319.32  4928.4  318.27
  4964.8  318.83  4981.5  318.04  4995.5  314.96  5003.9  315.46  5009.5  318.14
  5069.7  316.84  5090.6  317.21  5095.4  314.57  5098.1  314.07  5101.4  314.57
  5104.9  315.71  5121.1  317.24  5140.7  317.97  5175.1  317.88  5236.2  321.08
  5289.7   324.2  5332.7  328.87  5367.8  330.89  5410.8   336.7  5453.1  340.35
#Mann= 6 ,-1 , 0
  4727.2     .12       0  5095.4     .07       0  5101.4     .12       0
  5121.1     .16       0  5175.1     .12       0  5236.2     .16       0
Bank Sta=5090.6,5140.7
XS Rating Curve= 0 ,0
Exp/Cntr=0.3,0.1

Type RM Length L Ch R = 1 ,660     ,301,301,301
BEGIN DESCRIPTION:
Mapping XS c642e6f3
END DESCRIPTION:
XS GIS Cut Line= 2
      3704698.52     10675960.43       3704988.4     10676276.26
#Sta/Elev= 30
  4873.1  321.07    4895  319.83  4901.8  318.31  4909.2   317.7    4916  316.37
  4923.4  316.52  4944.3  314.59  4986.9  314.21  4991.3  309.17    4994  308.67
  4997.3  309.17  5001.1  310.15  5008.5  313.26  5015.3  313.17  5022.1  314.94
  5029.4  315.36  5064.6  316.61  5086.2  316.77  5100.3  317.46  5110.6  318.79
  5121.3  319.17  5142.9  321.27  5171.2  324.87  5192.2  326.32  5206.4  328.15
  5220.6  329.22  5241.5  332.15  5284.1  335.31  5298.3  337.35  5301.8  338.76
#Mann= 4 ,-1 , 0
  4873.1     .12       0  4991.3     .07       0  4997.3     .12       0
  5110.6     .16       0
Bank Sta=4986.9,5008.5
XS Rating Curve= 0 ,0
Exp/Cntr=0.3,0.1

Type RM Length L Ch R = 1 ,359     ,295,295,295
BEGIN DESCRIPTION:
Mapping XS 4f74bdde
END DESCRIPTION:
XS GIS Cut Line= 4
       3704635.6     10676068.99      3704583.52     10676251.25
      3704626.92      10676327.2      3704904.86     10676465.09
#Sta/Elev= 30
  4768.1  327.07  4773.1  329.39  4800.6  330.82  4806.9  329.22  4812.1  331.27
  4821.4  330.32  4831.8  326.29  4840.7  324.58  4845.9  325.16  4852.6  321.79
    4863  319.03  4879.7  312.72  4925.4  309.22  4946.2  310.89  4982.6   310.7
    4991  305.28  4995.5   303.6  4998.2   303.1  5001.5   303.6    5014  311.09
  5045.4  311.72  5153.6  318.78  5220.9  324.31  5237.7  327.19  5260.1  329.28
  5271.4  329.21  5282.5  331.15  5338.5  335.58  5349.5  337.01  5355.4   339.3
#Mann= 4 ,-1 , 0
  4768.1     .12       0  4995.5     .07       0  5001.5     .12       0
  5045.4     .16       0
Bank Sta=4982.6,5014
XS Rating Curve= 0 ,0
Exp/Cntr=0.3,0.1

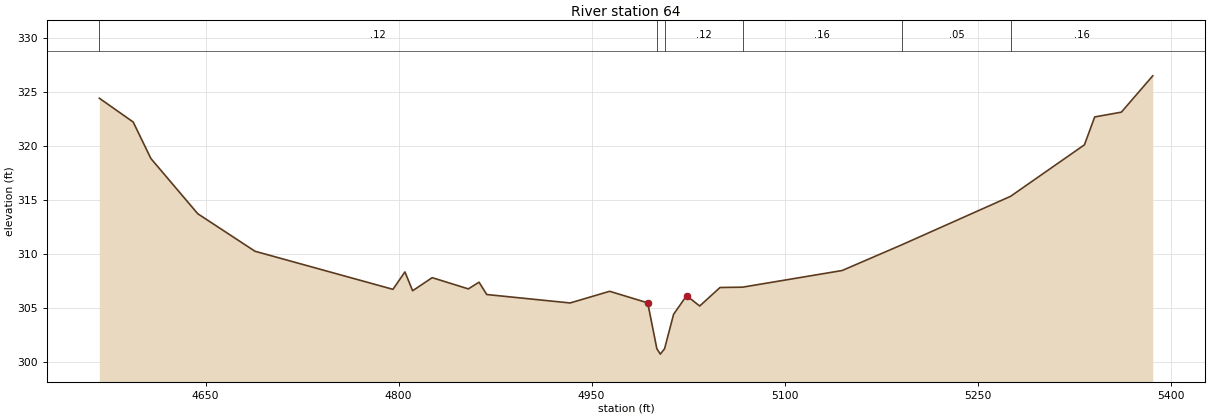
Type RM Length L Ch R = 1 ,64      ,0,0,0
BEGIN DESCRIPTION:
UNT 162 IN CACR 1.0
END DESCRIPTION:
XS GIS Cut Line= 4
        3704564.       10676108.      3704379.53     10676398.82
      3704392.55     10676520.35      3704733.22     10676609.31
#Sta/Elev= 30
  4567.4  324.39  4593.7  322.19  4607.5  318.81  4643.9  313.71  4688.4  310.24
  4795.6  306.72  4804.9  308.33  4810.9  306.59  4826.1   307.8  4854.2  306.76
  4862.5  307.38  4868.5  306.24  4933.3  305.46    4964  306.54  4993.6  305.47
  5000.7  301.23  5003.4  300.73  5006.7  301.23  5013.7  304.41  5023.8  306.13
    5034  305.18  5049.8  306.89  5067.3  306.92  5144.7  308.46  5191.3  310.85
  5275.6  315.32    5333  320.08    5341  322.66  5361.7   323.1  5386.1  326.46
#Mann= 6 ,-1 , 0
  4567.4     .12       0  5000.7     .07       0  5006.7     .12       0
  5067.3     .16       0  5191.3     .05       0  5275.6     .16       0
Bank Sta=4993.6,5023.8
XS Rating Curve= 0 ,0
Exp/Cntr=0.3,0.1

Chan Stop Cuts=-1
Use User Specified Reach Order=0
Composite Channel Slope=5