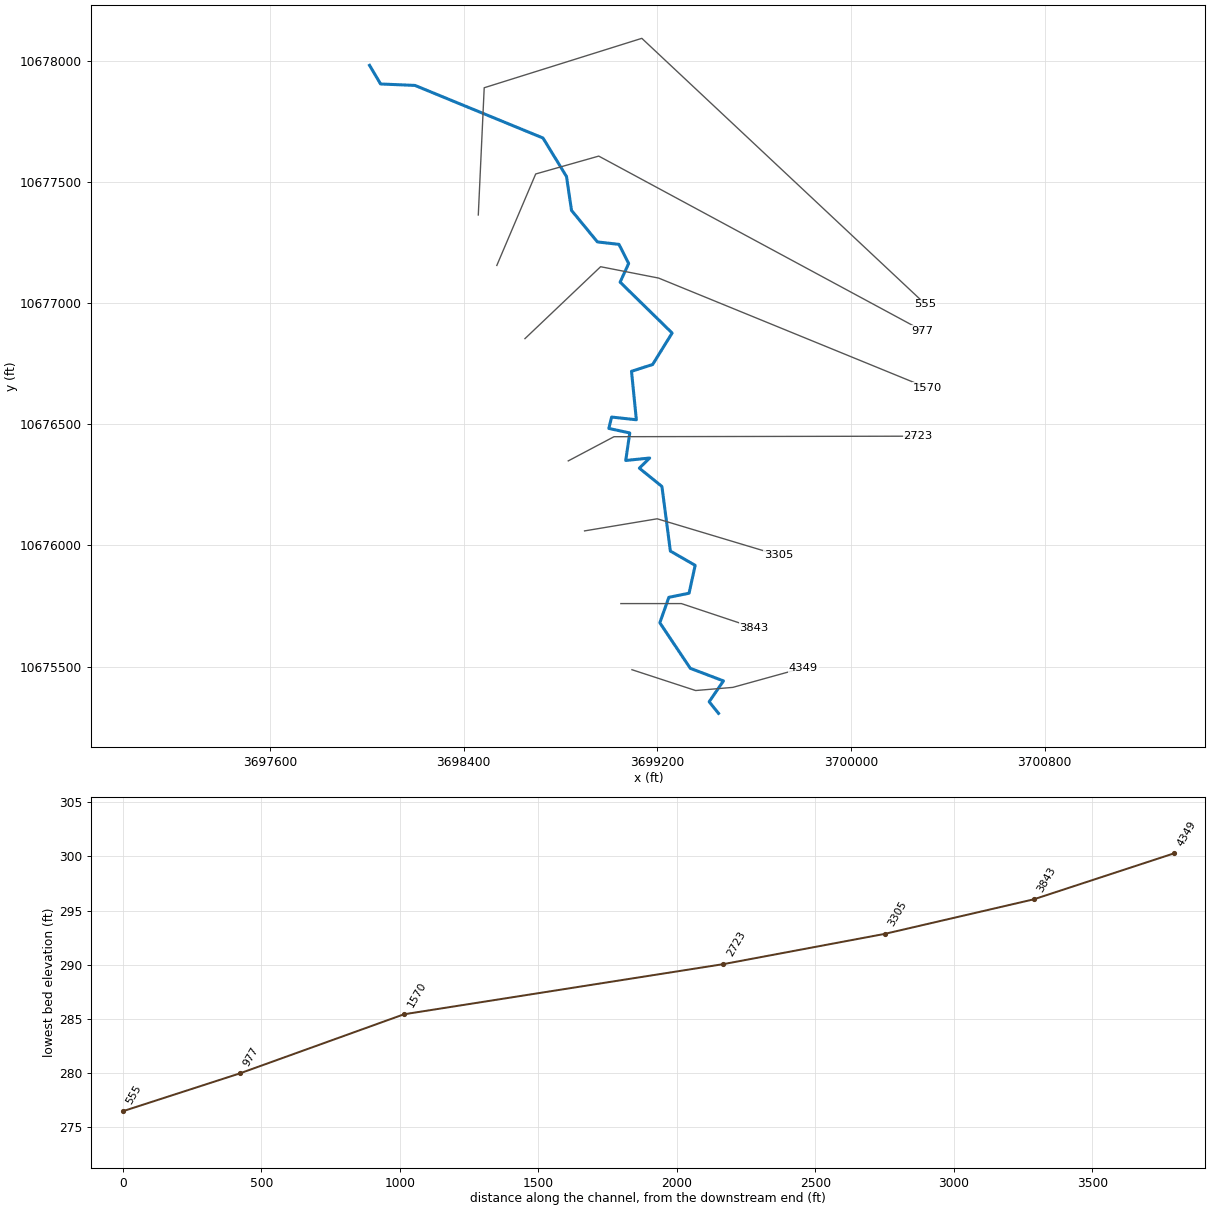
--- UNT 163 IN CACR.prj (project) ---

Proj Title=UNT 163 IN CACR Base Level Engineering
Current Plan=p01
Default Exp/Contr=0.3,0.1
English Units
Geom File=g01
Flow File=f01
Plan File=p01
BEGIN DESCRIPTION:
UNT 163 IN CACR
END DESCRIPTION:

--- UNT 163 IN CACR.p01 (plan) ---

Plan Title=Multiple Run
Short Identifier=Multiple
Geom File=g01
Flow File=f01
Subcritical Flow
K Sum by GR= 0
Std Step Tol= 0.01
Critical Tol= 0.01
Num of Std Step Trials= 20
Max Error Tol= 0.3
Flow Tol Ratio= 0.001
Split Flow NTrial= 30
Split Flow Tol= 0.02
Split Flow Ratio= 0.02
Log Output Level= 0
Friction Slope Method= 1
Unsteady Friction Slope Method= 2
Unsteady Bridges Friction Slope Method= 1
Parabolic Critical Depth
Global Vel Dist=  1 , 1 , 1
Global Log Level= 0
CheckData=True
Encroach Param= -1, 0, 0, 0
BEGIN DESCRIPTION:
Multiple Run
END DESCRIPTION:

--- UNT 163 IN CACR.f01 (steady flow) ---

Flow Title=Multiple
Number of Profiles=7
Profile Names=10-year,25-year,50-year,1pct_min,100-year,1pct_plu,500-year
River Rch & RM= UNT 163 IN CACR,Reach-1,4349
     427     573     693     617     834    1128    1213
Boundary for River Rch & Prof#=UNT 163 IN CACR,Reach-1,1
Up Type=0
Dn Type=3
Dn Slope=0.005
Boundary for River Rch & Prof#=UNT 163 IN CACR,Reach-1,2
Up Type=0
Dn Type=3
Dn Slope=0.005
Boundary for River Rch & Prof#=UNT 163 IN CACR,Reach-1,3
Up Type=0
Dn Type=3
Dn Slope=0.005
Boundary for River Rch & Prof#=UNT 163 IN CACR,Reach-1,4
Up Type=0
Dn Type=3
Dn Slope=0.005
Boundary for River Rch & Prof#=UNT 163 IN CACR,Reach-1,5
Up Type=0
Dn Type=3
Dn Slope=0.005
Boundary for River Rch & Prof#=UNT 163 IN CACR,Reach-1,6
Up Type=0
Dn Type=3
Dn Slope=0.005
Boundary for River Rch & Prof#=UNT 163 IN CACR,Reach-1,7
Up Type=0
Dn Type=3
Dn Slope=0.005

--- UNT 163 IN CACR.g01 (geometry) ---

Geom Title=Existing Conditions

River Reach=UNT 163 IN CACR,Reach-1
Reach XY= 30
      3699453.00     10675307.00      3699414.25     10675355.00
      3699473.25     10675441.00      3699336.25     10675493.00
      3699210.50     10675681.00      3699247.75     10675786.00
      3699331.25     10675803.00      3699356.50     10675918.00
      3699254.00     10675977.00      3699219.15     10676243.63
      3699125.92     10676319.15      3699168.50     10676361.00
      3699069.67     10676350.92      3699086.33     10676464.46
      3698999.87     10676483.21      3699011.33     10676530.08
      3699113.50     10676519.00      3699093.50     10676719.00
      3699180.75     10676747.00      3699261.25     10676877.00
      3699046.50     10677087.00      3699081.75     10677164.00
      3699041.75     10677243.00      3698952.75     10677253.00
      3698845.75     10677383.00      3698825.00     10677523.00
      3698727.75     10677682.00      3698199.25     10677899.00
      3698057.00     10677905.00      3698011.50     10677982.00

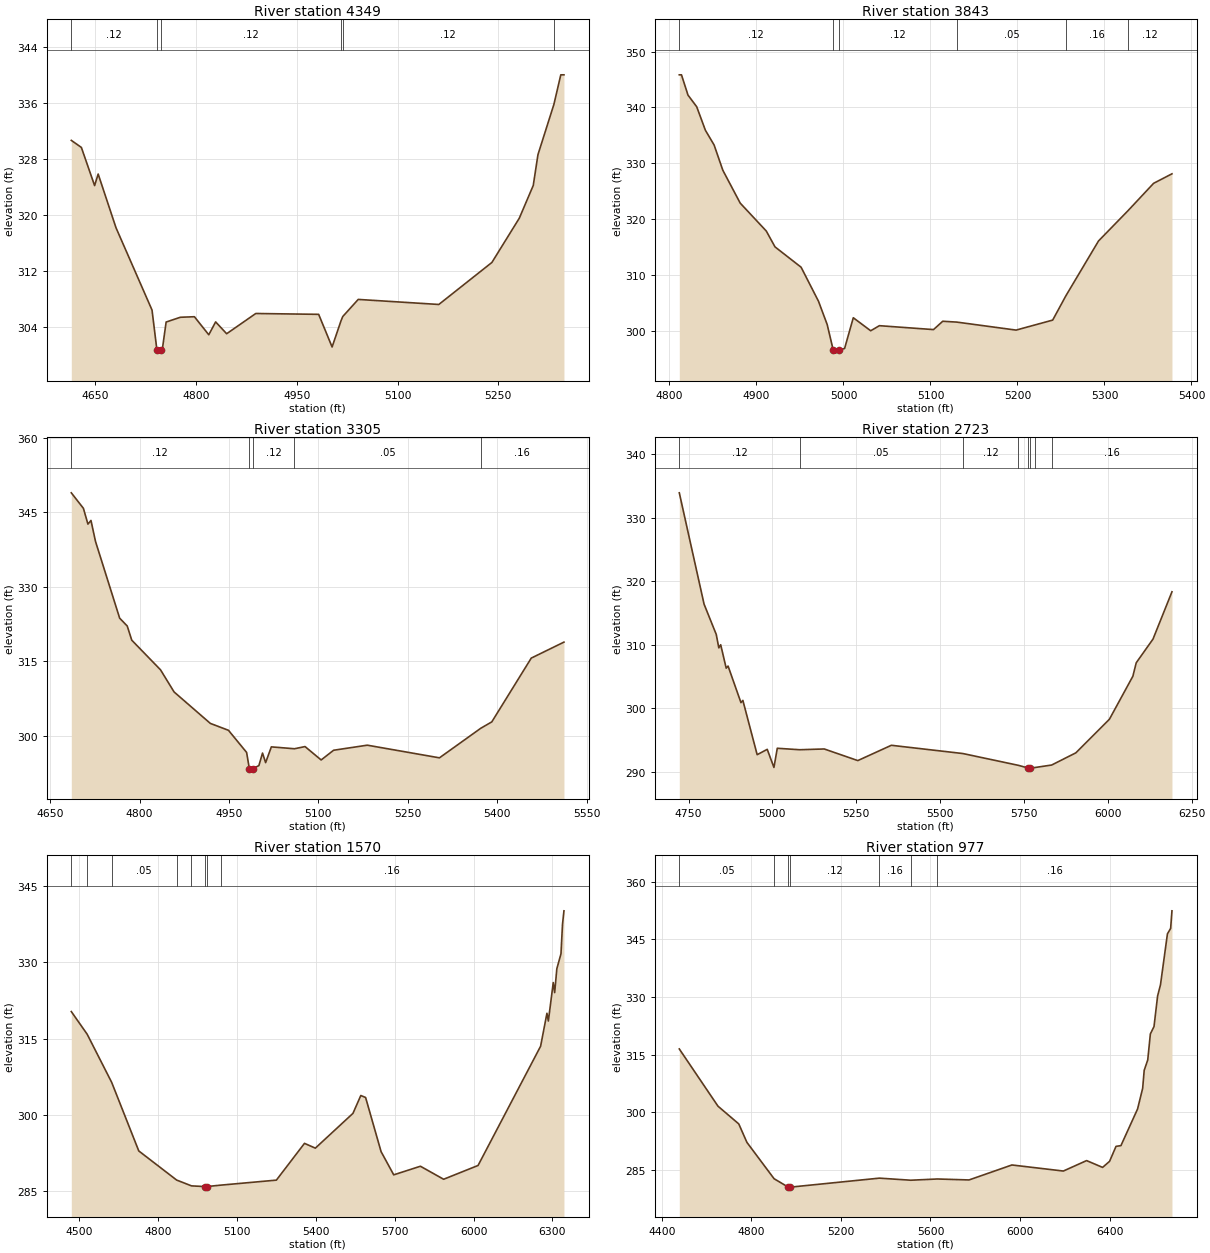
Type RM Length L Ch R = 1,4349,506,506,506
BEGIN DESCRIPTION:
UNT 163 IN CACR 5.0
END DESCRIPTION:
XS GIS Cut Line= 4
      3699095.37     10675487.22      3699358.38     10675401.28
      3699512.02     10675414.31      3699803.67     10675495.03
#Sta/Elev= 30
  4614.2  330.67  4629.2  329.66  4648.9  324.21  4654.2  325.86  4680.8  318.18
  4734.4  306.43  4741.6  300.78  4744.3  300.28  4747.6  300.78  4749.8  300.86
  4755.4  304.72  4776.5  305.40  4797.5  305.48  4818.9  302.90  4829.1  304.74
  4845.5  303.05  4888.9  305.94  4982.5  305.82  5002.5  301.16  5015.7  304.88
  5018.4  305.51  5041.4  307.95  5161.4  307.23  5240.4  313.23  5281.2  319.55
  5302.0  324.23  5309.0  328.63  5332.7  335.80  5343.0  340.03  5347.7  340.03
#Mann=6,-1,0
  4614.2    0.12       0  4741.6    0.07       0  4747.6    0.12       0
  5015.7    0.05       0  5018.4    0.12       0  5332.7    0.16       0
Bank Sta=4741.6,4747.6
Exp/Cntr=0.3,0.1

Type RM Length L Ch R = 1,3843,538,538,538
BEGIN DESCRIPTION:
UNT 163 IN CACR 4.0
END DESCRIPTION:
XS GIS Cut Line= 3
      3699049.56     10675760.19      3699299.61     10675760.19
      3699599.63     10675660.18
#Sta/Elev= 30
  4811.3  345.83  4813.8  345.83  4821.3  342.20  4831.3  340.12  4841.3  335.91
  4851.3  333.28  4861.3  328.77  4881.3  322.88  4911.3  317.88  4921.3  315.05
  4951.3  311.41  4971.3  305.32  4981.3  301.15  4988.3  296.54  4991.1  296.04
  4994.3  296.54  5001.3  296.87  5011.3  302.37  5031.3  300.04  5041.3  300.95
  5103.5  300.25  5114.1  301.74  5130.3  301.59  5198.4  300.16  5240.5  301.95
  5255.6  306.28  5293.2  316.11  5327.0  321.51  5356.5  326.42  5377.6  328.12
#Mann=6,-1,0
  4811.3    0.12       0  4988.3    0.07       0  4994.3    0.12       0
  5130.3    0.05       0  5255.6    0.16       0  5327.0    0.12       0
Bank Sta=4988.3,4994.3
Exp/Cntr=0.3,0.1

Type RM Length L Ch R = 1,3305,582,582,582
BEGIN DESCRIPTION:
UNT 163 IN CACR 3.0
END DESCRIPTION:
XS GIS Cut Line= 3
      3698899.59     10676060.19      3699199.61     10676110.19
      3699699.64     10675960.18
#Sta/Elev= 30
  4685.6  348.96  4705.9  345.84  4713.5  342.65  4718.6  343.39  4726.2  339.16
  4766.7  323.69  4779.4  322.11  4787.0  319.25  4835.2  313.28  4858.0  308.81
  4918.8  302.47  4949.2  301.08  4979.6  296.62  4984.2  293.35  4987.0  292.85
  4990.2  293.35  5000.2  293.97  5006.3  296.49  5011.5  294.56  5021.1  297.74
  5059.9  297.36  5077.6  297.80  5104.6  295.10  5125.5  297.06  5182.0  298.08
  5303.0  295.53  5372.3  301.49  5390.8  302.78  5457.0  315.64  5511.8  318.86
#Mann=5,-1,0
  4685.6    0.12       0  4984.2    0.07       0  4990.2    0.12       0
  5059.9    0.05       0  5372.3    0.16       0
Bank Sta=4984.2,4990.2
Exp/Cntr=0.3,0.1

Type RM Length L Ch R = 1,2723,1153,1153,1153
BEGIN DESCRIPTION:
UNT 163 IN CACR 2.0
END DESCRIPTION:
XS GIS Cut Line= 3
      3698832.30     10676349.18      3699021.14     10676449.03
      3700276.13     10676451.19
#Sta/Elev= 30
  4722.5  333.90  4796.3  316.37  4832.6  311.60  4840.3  309.48  4845.9  309.97
  4862.3  306.28  4867.9  306.61  4906.3  300.85  4912.0  301.20  4954.6  292.65
  4984.6  293.49  5004.6  290.64  5014.6  293.66  5081.4  293.43  5154.6  293.55
  5254.6  291.72  5354.6  294.13  5567.8  292.83  5733.5  290.97  5761.6  290.56
  5764.3  290.06  5767.6  290.56  5782.9  290.63  5832.5  291.02  5904.6  292.94
  6004.6  298.23  6074.6  305.01  6084.6  307.13  6134.6  310.86  6191.1  318.31
#Mann=8,-1,0
  4722.5    0.12       0  5081.4    0.05       0  5567.8    0.12       0
  5733.5    0.05       0  5761.6    0.07       0  5767.6    0.05       0
  5782.9    0.12       0  5832.5    0.16       0
Bank Sta=5761.6,5767.6
Exp/Cntr=0.3,0.1

Type RM Length L Ch R = 1,1570,593,593,593
BEGIN DESCRIPTION:
Mapping XS dd76323e
END DESCRIPTION:
XS GIS Cut Line= 4
      3698653.40     10676853.86      3698965.87     10677150.71
      3699205.45     10677103.83      3700314.68     10676650.77
#Sta/Elev= 30
  4470.6  320.35  4530.9  315.90  4624.2  306.42  4727.2  292.94  4871.0  287.22
  4927.6  286.07  4979.1  285.93  4981.9  285.43  4985.1  285.93  5038.1  286.21
  5250.4  287.20  5357.3  294.43  5398.6  293.49  5541.6  300.33  5571.5  303.84
  5589.7  303.45  5648.5  292.81  5696.6  288.24  5798.1  289.93  5886.4  287.37
  6017.3  290.08  6255.1  313.53  6279.2  320.01  6284.6  318.49  6303.2  326.05
  6308.6  324.07  6316.8  328.76  6332.6  331.72  6338.4  337.51  6343.9  340.16
#Mann=8,-1,0
  4470.6    0.12       0  4530.9    0.16       0  4624.2    0.05       0
  4871.0    0.16       0  4927.6    0.12       0  4979.1    0.07       0
  4985.1    0.12       0  5038.1    0.16       0
Bank Sta=4979.1,4985.1
Exp/Cntr=0.3,0.1

Type RM Length L Ch R = 1,977,422,422,422
BEGIN DESCRIPTION:
Mapping XS 0a945447
END DESCRIPTION:
XS GIS Cut Line= 4
      3698537.15     10677155.91      3698697.74     10677533.50
      3698958.16     10677607.29      3700294.79     10676886.89
#Sta/Elev= 30
  4478.6  316.47  4651.3  301.57  4744.1  296.95  4780.4  292.15  4901.7  282.68
  4965.6  280.47  4968.4  279.97  4971.6  280.47  5371.7  282.83  5512.0  282.29
  5630.6  282.61  5772.1  282.36  5963.5  286.26  6193.1  284.68  6296.9  287.40
  6368.3  285.63  6399.5  287.21  6428.3  291.11  6450.2  291.30  6524.4  300.83
  6547.2  306.22  6554.0  310.89  6569.9  313.62  6581.6  320.39  6597.8  322.29
  6614.0  330.30  6626.7  333.16  6657.8  346.45  6672.1  347.86  6678.0  352.44
#Mann=7,-1,0
  4478.6    0.05       0  4901.7    0.12       0  4965.6    0.07       0
  4971.6    0.12       0  5371.7    0.16       0  5512.0    0.12       0
  5630.6    0.16       0
Bank Sta=4965.6,4971.6
Exp/Cntr=0.3,0.1

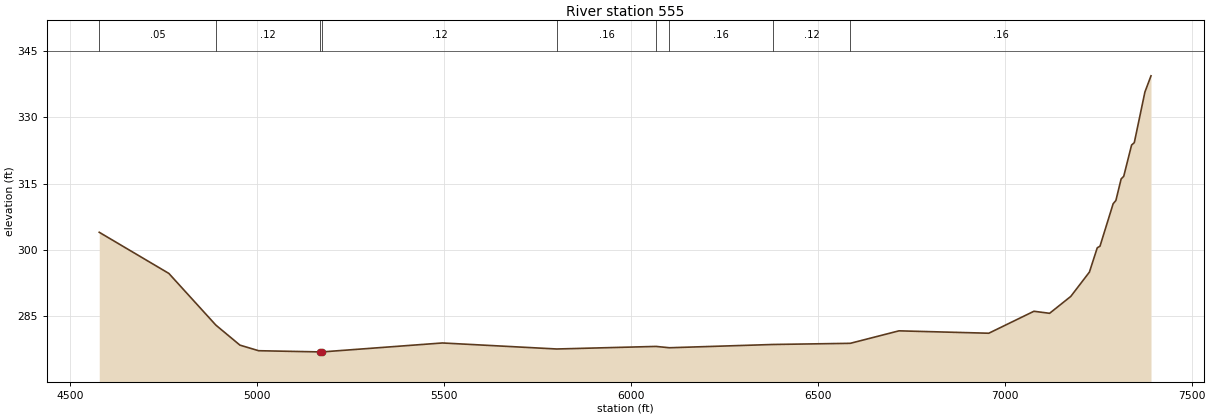
Type RM Length L Ch R = 1,555,0,0,0
BEGIN DESCRIPTION:
UNT 163 IN CACR 1.0
END DESCRIPTION:
XS GIS Cut Line= 4
      3698460.66     10677364.24      3698485.07     10677889.41
      3699136.11     10678093.40      3700307.95     10676995.34
#Sta/Elev= 30
  4577.4  304.00  4763.6  294.71  4889.3  283.04  4953.8  278.51  5003.8  277.25
  5167.8  276.98  5170.5  276.48  5173.8  276.98  5495.6  279.00  5801.4  277.64
  6067.0  278.22  6102.7  277.92  6380.3  278.66  6586.7  278.92  6717.0  281.74
  6957.3  281.20  7078.0  286.16  7120.0  285.70  7176.7  289.52  7226.5  295.01
  7247.5  300.50  7254.8  300.86  7290.0  310.45  7297.3  311.18  7311.4  316.06
  7318.3  316.64  7339.3  323.70  7346.6  324.25  7375.0  335.69  7391.3  339.34
#Mann=9,-1,0
  4577.4    0.05       0  4889.3    0.12       0  5167.8    0.07       0
  5173.8    0.12       0  5801.4    0.16       0  6067.0    0.12       0
  6102.7    0.16       0  6380.3    0.12       0  6586.7    0.16       0
Bank Sta=5167.8,5173.8
Exp/Cntr=0.3,0.1

Chan Stop Cuts=-1