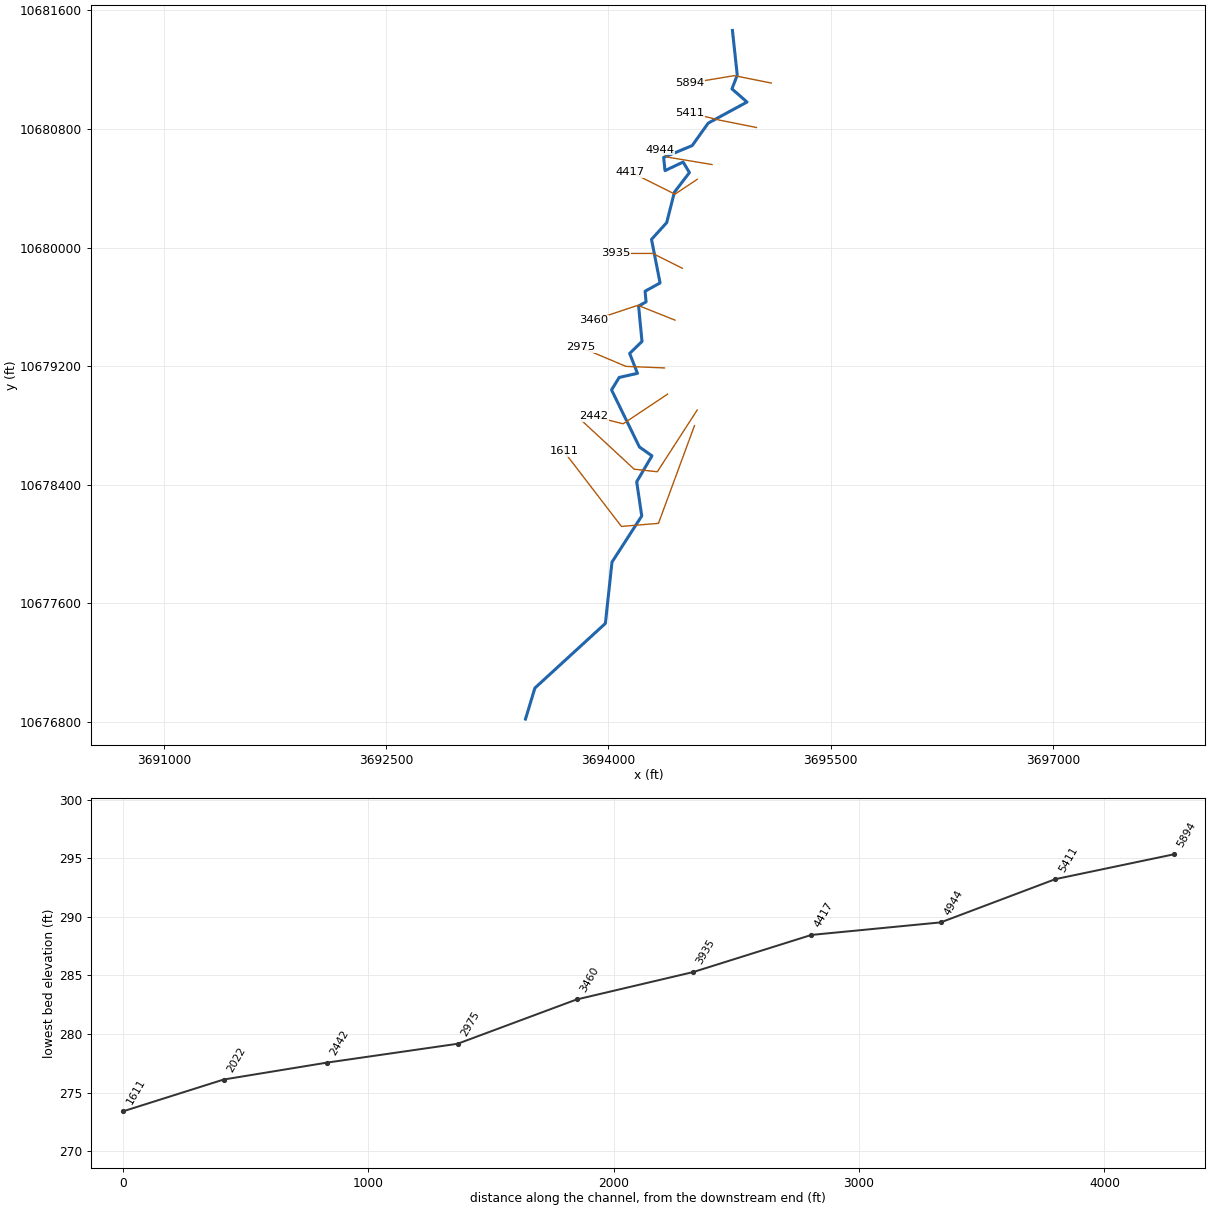
--- UNT 164 IN CACR.prj (project) ---

Proj Title=UNT 164 IN CACR Base Level Engineering
Current Plan=p01
Default Exp/Contr=0.3,0.1
English Units
Geom File=g01
Flow File=f01
Plan File=p01
BEGIN DESCRIPTION:
UNT 164 IN CACR
END DESCRIPTION:

--- UNT 164 IN CACR.p01 (plan) ---

Plan Title=Multiple Run
Short Identifier=Multiple
Geom File=g01
Flow File=f01
Subcritical Flow
K Sum by GR= 0
Std Step Tol= 0.01
Critical Tol= 0.01
Num of Std Step Trials= 20
Max Error Tol= 0.3
Flow Tol Ratio= 0.001
Split Flow NTrial= 30
Split Flow Tol= 0.02
Split Flow Ratio= 0.02
Log Output Level= 0
Friction Slope Method= 1
Unsteady Friction Slope Method= 2
Unsteady Bridges Friction Slope Method= 1
Parabolic Critical Depth
Global Vel Dist=  1 , 1 , 1
Global Log Level= 0
CheckData=True
Encroach Param= -1, 0, 0, 0
BEGIN DESCRIPTION:
Multiple Run
END DESCRIPTION:

--- UNT 164 IN CACR.f01 (steady flow) ---

Flow Title=Multiple
Number of Profiles=7
Profile Names=10-year,25-year,50-year,1pct_min,100-year,1pct_plu,500-year
River Rch & RM= UNT 164 IN CACR,Reach-1,5894
     458     612     737     652     882    1193    1270
Boundary for River Rch & Prof#=UNT 164 IN CACR,Reach-1,1
Up Type=0
Dn Type=3
Dn Slope=0.005
Boundary for River Rch & Prof#=UNT 164 IN CACR,Reach-1,2
Up Type=0
Dn Type=3
Dn Slope=0.005
Boundary for River Rch & Prof#=UNT 164 IN CACR,Reach-1,3
Up Type=0
Dn Type=3
Dn Slope=0.005
Boundary for River Rch & Prof#=UNT 164 IN CACR,Reach-1,4
Up Type=0
Dn Type=3
Dn Slope=0.005
Boundary for River Rch & Prof#=UNT 164 IN CACR,Reach-1,5
Up Type=0
Dn Type=3
Dn Slope=0.005
Boundary for River Rch & Prof#=UNT 164 IN CACR,Reach-1,6
Up Type=0
Dn Type=3
Dn Slope=0.005
Boundary for River Rch & Prof#=UNT 164 IN CACR,Reach-1,7
Up Type=0
Dn Type=3
Dn Slope=0.005

--- UNT 164 IN CACR.g01 (geometry) ---

Geom Title=Existing Conditions

River Reach=UNT 164 IN CACR,Reach-1
Reach XY= 30
      3694837.75     10681465.00      3694870.25     10681163.00
      3694834.50     10681071.00      3694936.00     10680982.00
      3694674.50     10680840.00      3694566.00     10680688.00
      3694373.25     10680608.00      3694382.75     10680519.00
      3694504.75     10680577.00      3694547.50     10680506.00
      3694445.75     10680373.00      3694394.00     10680168.00
      3694291.50     10680055.00      3694349.25     10679761.00
      3694248.00     10679705.00      3694254.75     10679633.00
      3694204.25     10679605.00      3694227.25     10679366.00
      3694144.00     10679285.00      3694196.75     10679151.00
      3694073.25     10679123.00      3694021.75     10679039.00
      3694209.75     10678654.00      3694294.50     10678594.00
      3694191.50     10678419.00      3694225.50     10678188.00
      3694024.75     10677877.00      3693980.25     10677463.00
      3693504.50     10677027.00      3693440.75     10676817.00

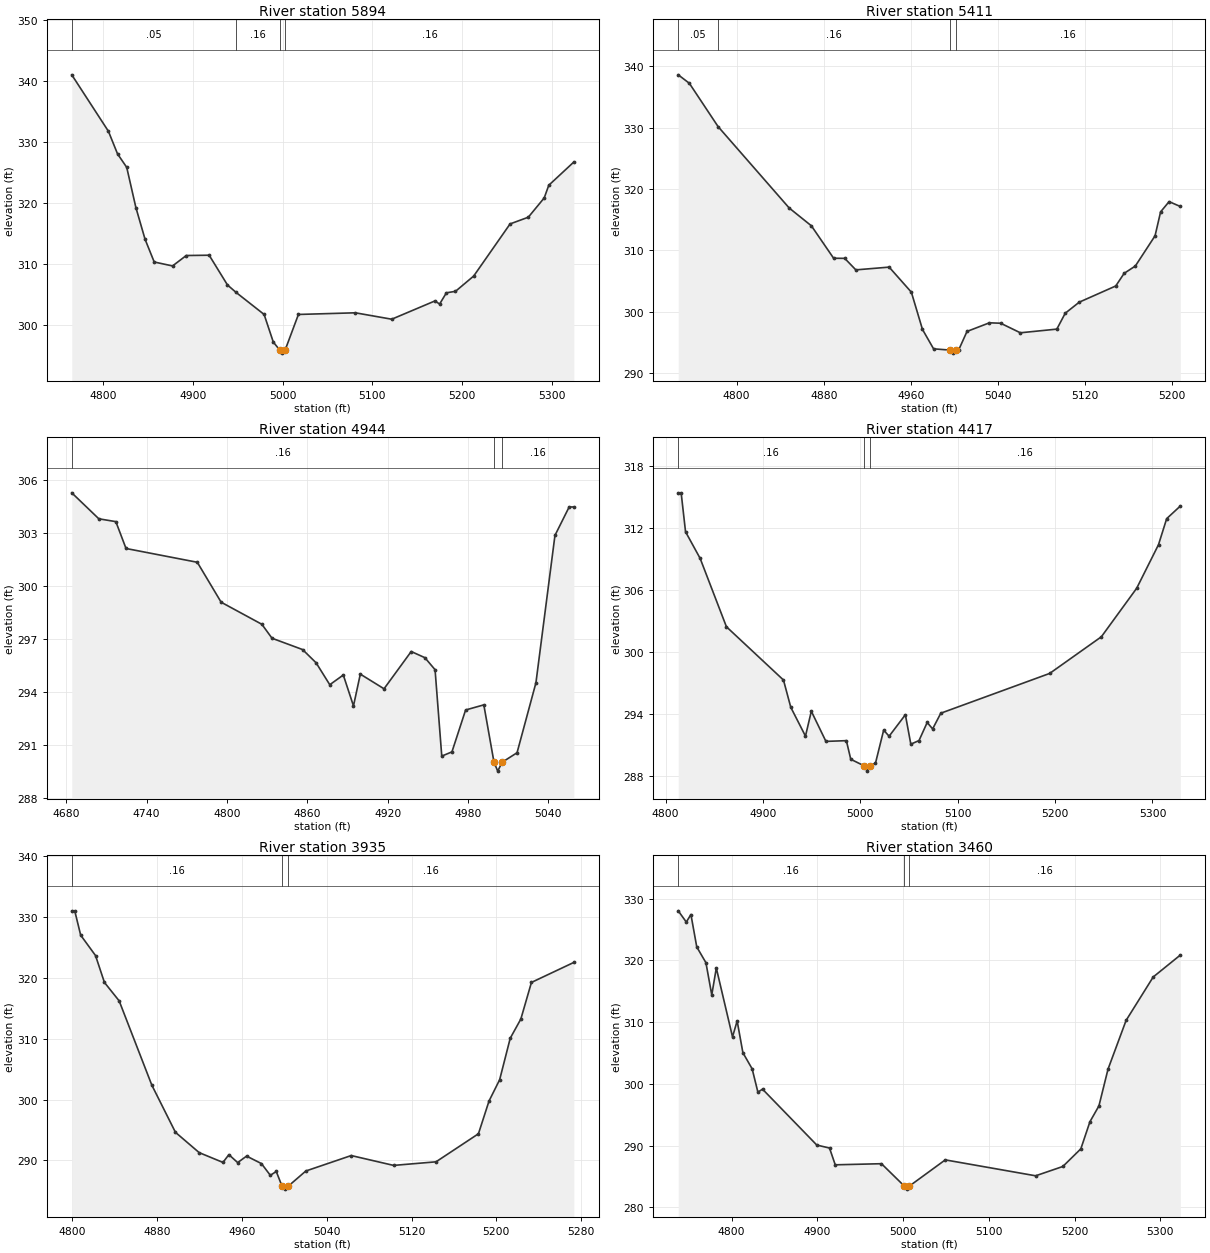
Type RM Length L Ch R = 1,5894,483,483,483
BEGIN DESCRIPTION:
UNT 164 IN CACR 9.0
END DESCRIPTION:
XS GIS Cut Line= 3
      3695099.61     10681110.19      3694849.61     10681160.19
      3694549.60     10681110.19
#Sta/Elev= 30
  4765.3  340.95  4806.1  331.70  4816.3  327.98  4826.5  325.78  4836.7  319.19
  4846.9  314.00  4857.1  310.27  4877.5  309.62  4892.8  311.33  4918.3  311.38
  4938.7  306.50  4948.3  305.28  4979.5  301.67  4989.7  297.15  4996.9  295.83
  4999.6  295.33  5002.9  295.83  5017.7  301.67  5081.1  301.94  5121.6  300.89
  5169.8  303.89  5174.9  303.37  5182.5  305.22  5192.6  305.46  5212.9  307.97
  5253.4  316.51  5273.7  317.61  5291.4  320.77  5296.5  322.85  5324.4  326.66
#Mann=4,-1,0
  4765.3    0.05       0  4948.3    0.16       0  4996.9    0.07       0
  5002.9    0.16       0
Bank Sta=4996.9,5002.9
Exp/Cntr=0.3,0.1

Type RM Length L Ch R = 1,5411,467,467,467
BEGIN DESCRIPTION:
UNT 164 IN CACR 8.0
END DESCRIPTION:
XS GIS Cut Line= 3
      3694999.57     10680810.20      3694749.61     10680860.19
      3694549.58     10680910.20
#Sta/Elev= 30
  4746.4  338.64  4756.6  337.26  4783.0  330.19  4848.3  316.90  4868.7  313.99
  4889.1  308.70  4899.3  308.68  4909.5  306.80  4940.1  307.25  4960.5  303.16
  4970.7  297.08  4980.9  293.91  4995.8  293.71  4998.5  293.21  5001.8  293.71
  5003.9  293.71  5011.6  296.75  5032.2  298.16  5042.5  298.09  5060.6  296.53
  5094.1  297.13  5101.8  299.72  5114.7  301.53  5148.2  304.17  5155.9  306.23
  5166.2  307.43  5184.3  312.36  5189.4  316.27  5197.2  317.94  5207.5  317.15
#Mann=4,-1,0
  4746.4    0.05       0  4783.0    0.16       0  4995.8    0.07       0
  5001.8    0.16       0
Bank Sta=4995.8,5001.8
Exp/Cntr=0.3,0.1

Type RM Length L Ch R = 1,4944,527,527,527
BEGIN DESCRIPTION:
UNT 164 IN CACR 7.0
END DESCRIPTION:
XS GIS Cut Line= 3
      3694699.57     10680560.19      3694399.61     10680610.19
      3694349.62     10680660.18
#Sta/Elev= 30
  4684.2  305.27  4704.4  303.80  4717.1  303.64  4724.7  302.12  4777.9  301.34
  4795.7  299.08  4826.1  297.83  4833.7  297.04  4856.5  296.40  4866.6  295.65
  4876.8  294.41  4886.9  294.96  4894.5  293.21  4899.6  295.01  4917.3  294.18
  4937.6  296.29  4947.8  295.94  4955.4  295.26  4960.4  290.37  4968.0  290.61
  4978.2  292.98  4991.8  293.27  4999.4  290.02  5002.2  289.52  5005.4  290.02
  5016.6  290.56  5030.7  294.52  5044.9  302.86  5055.5  304.47  5059.0  304.47
#Mann=3,-1,0
  4684.2    0.16       0  4999.4    0.07       0  5005.4    0.16       0
Bank Sta=4999.4,5005.4
Exp/Cntr=0.3,0.1

Type RM Length L Ch R = 1,4417,482,482,482
BEGIN DESCRIPTION:
UNT 164 IN CACR 6.0
END DESCRIPTION:
XS GIS Cut Line= 3
      3694599.58     10680460.17      3694449.61     10680360.19
      3694149.57     10680510.21
#Sta/Elev= 30
  4812.9  315.40  4815.9  315.40  4820.4  311.63  4835.4  309.05  4862.4  302.43
  4921.0  297.27  4928.5  294.63  4943.6  291.84  4949.6  294.25  4964.6  291.33
  4985.6  291.40  4990.1  289.60  5004.1  288.95  5006.9  288.45  5010.1  288.95
  5015.5  289.22  5023.9  292.42  5029.5  291.83  5046.2  293.91  5051.8  291.06
  5060.2  291.41  5068.6  293.16  5074.2  292.54  5082.6  294.06  5194.4  297.91
  5247.5  301.46  5283.8  306.16  5306.2  310.38  5314.6  312.90  5328.6  314.12
#Mann=3,-1,0
  4812.9    0.16       0  5004.1    0.07       0  5010.1    0.16       0
Bank Sta=5004.1,5010.1
Exp/Cntr=0.3,0.1

Type RM Length L Ch R = 1,3935,475,475,475
BEGIN DESCRIPTION:
UNT 164 IN CACR 5.0
END DESCRIPTION:
XS GIS Cut Line= 3
      3694499.62     10679860.18      3694299.61     10679960.19
      3694049.63     10679960.19
#Sta/Elev= 30
  4799.5  331.03  4802.3  331.03  4807.9  327.03  4821.9  323.68  4830.3  319.26
  4844.2  316.23  4875.0  302.38  4897.3  294.62  4919.7  291.28  4942.1  289.67
  4947.7  290.95  4956.0  289.64  4964.4  290.71  4978.4  289.48  4986.8  287.55
  4992.4  288.18  4997.8  285.78  5000.5  285.28  5003.8  285.78  5020.3  288.26
  5063.1  290.80  5103.1  289.18  5143.1  289.77  5183.1  294.38  5193.1  299.77
  5203.1  303.26  5213.1  310.09  5223.1  313.24  5233.1  319.26  5273.1  322.55
#Mann=3,-1,0
  4799.5    0.16       0  4997.8    0.07       0  5003.8    0.16       0
Bank Sta=4997.8,5003.8
Exp/Cntr=0.3,0.1

Type RM Length L Ch R = 1,3460,485,485,485
BEGIN DESCRIPTION:
UNT 164 IN CACR 4.0
END DESCRIPTION:
XS GIS Cut Line= 3
      3694449.62     10679510.18      3694199.61     10679610.19
      3693899.61     10679510.19
#Sta/Elev= 30
  4737.8  328.04  4747.2  326.22  4752.6  327.44  4759.4  322.19  4770.1  319.63
  4776.9  314.41  4782.2  318.77  4801.1  307.61  4806.5  310.20  4813.2  305.05
  4824.0  302.43  4830.7  298.65  4836.1  299.14  4899.4  290.08  4914.2  289.60
  4920.9  286.88  4974.8  287.06  5001.4  283.44  5004.1  282.94  5007.4  283.44
  5049.2  287.68  5154.6  285.10  5186.3  286.61  5207.3  289.47  5217.9  293.86
  5228.4  296.43  5239.0  302.38  5260.1  310.29  5291.7  317.32  5323.3  320.87
#Mann=3,-1,0
  4737.8    0.16       0  5001.4    0.07       0  5007.4    0.16       0
Bank Sta=5001.4,5007.4
Exp/Cntr=0.3,0.1

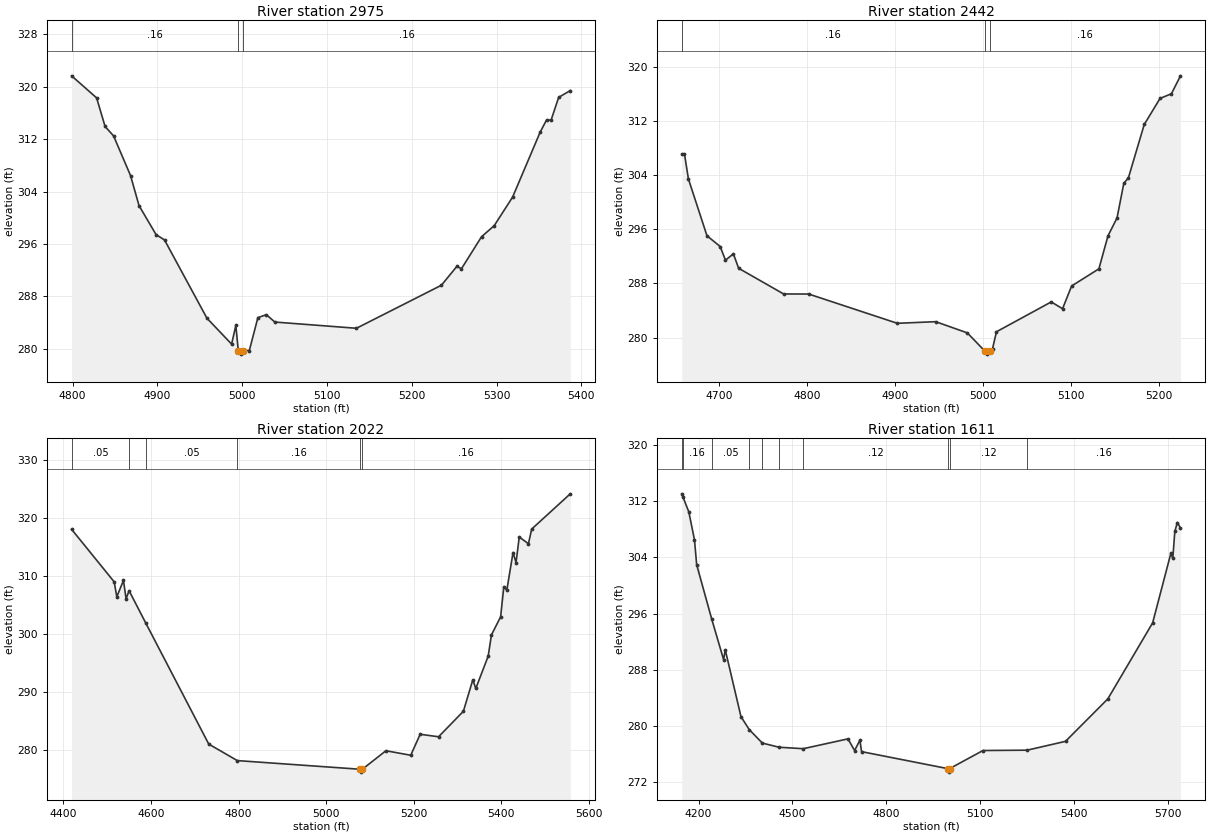
Type RM Length L Ch R = 1,2975,533,533,533
BEGIN DESCRIPTION:
UNT 164 IN CACR 3.0
END DESCRIPTION:
XS GIS Cut Line= 3
      3694379.09     10679187.48      3694118.68     10679197.90
      3693817.01     10679325.33
#Sta/Elev= 30
  4798.9  321.67  4828.4  318.30  4838.4  313.93  4848.4  312.49  4868.4  306.44
  4878.4  301.85  4898.5  297.42  4908.5  296.60  4958.5  284.65  4987.6  280.69
  4992.6  283.54  4995.5  279.66  4998.3  279.16  5001.5  279.66  5008.5  279.71
  5018.6  284.74  5028.6  285.18  5038.6  284.06  5134.8  283.11  5235.0  289.68
  5253.3  292.57  5258.7  292.21  5282.4  297.10  5297.3  298.78  5319.0  303.15
  5351.6  313.10  5359.0  314.92  5364.4  314.91  5373.3  318.38  5387.0  319.42
#Mann=3,-1,0
  4798.9    0.16       0  4995.5    0.07       0  5001.5    0.16       0
Bank Sta=4995.5,5001.5
Exp/Cntr=0.3,0.1

Type RM Length L Ch R = 1,2442,420,420,420
BEGIN DESCRIPTION:
UNT 164 IN CACR 2.0
END DESCRIPTION:
XS GIS Cut Line= 3
      3694399.62     10679010.19      3694099.61     10678810.19
      3693899.63     10678860.18
#Sta/Elev= 30
  4657.7  307.18  4660.7  307.18  4665.2  303.47  4686.3  295.06  4701.3  293.47
  4707.3  291.45  4716.3  292.38  4722.3  290.25  4773.4  286.45  4801.9  286.44
  4902.6  282.11  4946.2  282.35  4982.2  280.69  5001.7  278.05  5004.5  277.55
  5007.7  278.05  5010.8  278.35  5015.3  280.86  5077.5  285.27  5090.4  284.27
  5100.7  287.63  5131.7  290.17  5142.0  295.04  5152.3  297.70  5160.0  302.82
  5165.2  303.62  5183.2  311.52  5201.2  315.38  5214.1  316.07  5224.4  318.72
#Mann=3,-1,0
  4657.7    0.16       0  5001.7    0.07       0  5007.7    0.16       0
Bank Sta=5001.7,5007.7
Exp/Cntr=0.3,0.1

Type RM Length L Ch R = 1,2022,411,411,411
BEGIN DESCRIPTION:
Mapping XS 2b80873e
END DESCRIPTION:
XS GIS Cut Line= 4
      3694599.79     10678903.19      3694330.70     10678486.53
      3694174.45     10678503.89      3693818.52     10678833.77
#Sta/Elev= 30
  4418.9  318.00  4516.2  308.93  4522.1  306.35  4537.3  309.18  4543.3  306.01
  4550.1  307.41  4588.7  301.76  4732.0  280.95  4797.2  278.10  5076.8  276.61
  5079.5  276.11  5082.8  276.61  5136.5  279.80  5193.2  279.02  5214.7  282.64
  5256.7  282.21  5313.4  286.61  5334.9  292.04  5341.7  290.54  5370.0  296.12
  5377.4  299.77  5398.4  302.91  5405.7  308.11  5412.6  307.53  5426.7  313.99
  5433.6  312.27  5440.9  316.67  5461.9  315.51  5469.3  318.04  5557.4  324.12
#Mann=6,-1,0
  4418.9    0.05       0  4550.1    0.16       0  4588.7    0.05       0
  4797.2    0.16       0  5076.8    0.07       0  5082.8    0.16       0
Bank Sta=5076.8,5082.8
Exp/Cntr=0.3,0.1

Type RM Length L Ch R = 1,1611,0,0,0
BEGIN DESCRIPTION:
UNT 164 IN CACR 1.0
END DESCRIPTION:
XS GIS Cut Line= 4
      3694581.58     10678798.19      3694338.51     10678138.44
      3694088.51     10678117.60      3693699.62     10678624.55
#Sta/Elev= 30
  4146.6  313.06  4150.0  312.63  4168.9  310.50  4187.1  306.50  4194.1  302.95
  4242.3  295.18  4280.1  289.43  4285.4  290.82  4335.6  281.30  4362.0  279.45
  4403.9  277.53  4457.0  276.94  4534.5  276.73  4677.3  278.13  4698.6  276.47
  4715.5  277.95  4720.8  276.31  4996.1  273.89  4998.9  273.39  5002.1  273.89
  5108.6  276.47  5249.8  276.52  5372.3  277.78  5507.4  283.83  5650.6  294.67
  5708.7  304.57  5715.0  303.87  5721.4  307.69  5729.5  308.97  5739.5  308.19
#Mann=10,-1,0
  4146.6    0.05       0  4150.0    0.16       0  4242.3    0.05       0
  4362.0    0.16       0  4403.9    0.05       0  4457.0    0.16       0
  4534.5    0.12       0  4996.1    0.07       0  5002.1    0.12       0
  5249.8    0.16       0
Bank Sta=4996.1,5002.1
Exp/Cntr=0.3,0.1

Chan Stop Cuts=-1