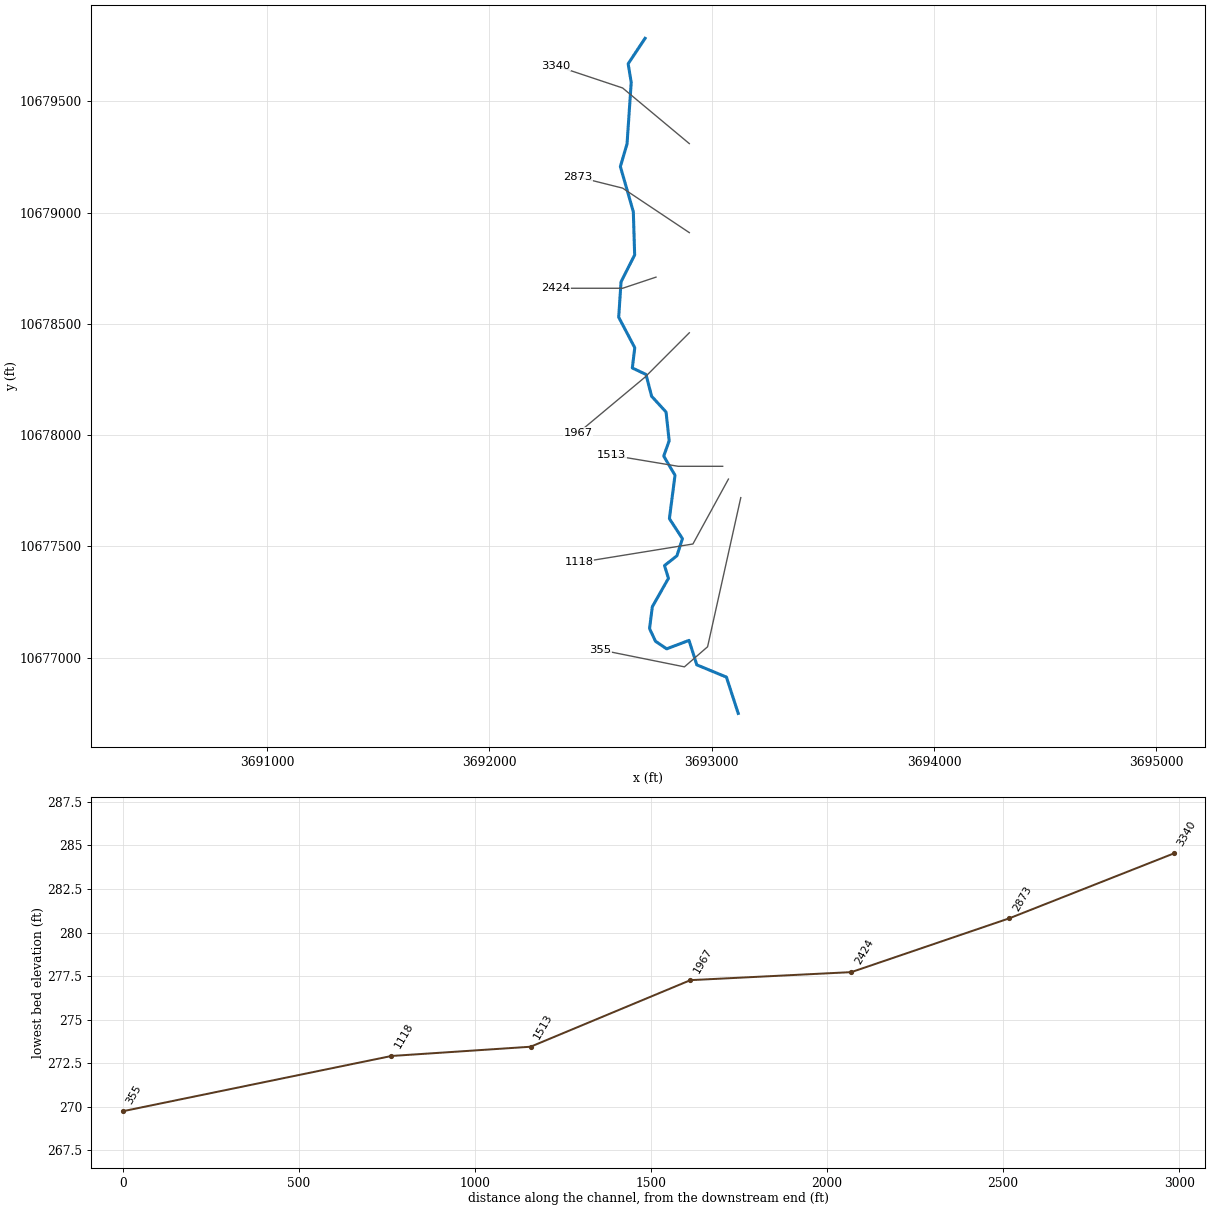
--- UNT 165 IN CACR.prj (project) ---

Proj Title=UNT 165 IN CACR Base Level Engineering
Current Plan=p01
Default Exp/Contr=0.3,0.1
English Units
Geom File=g01
Flow File=f01
Plan File=p01
BEGIN DESCRIPTION:
UNT 165 IN CACR
END DESCRIPTION:

--- UNT 165 IN CACR.p01 (plan) ---

Plan Title=Multiple Run
Short Identifier=Multiple
Geom File=g01
Flow File=f01
Subcritical Flow
K Sum by GR= 0
Std Step Tol= 0.01
Critical Tol= 0.01
Num of Std Step Trials= 20
Max Error Tol= 0.3
Flow Tol Ratio= 0.001
Split Flow NTrial= 30
Split Flow Tol= 0.02
Split Flow Ratio= 0.02
Log Output Level= 0
Friction Slope Method= 1
Unsteady Friction Slope Method= 2
Unsteady Bridges Friction Slope Method= 1
Parabolic Critical Depth
Global Vel Dist=  1 , 1 , 1
Global Log Level= 0
CheckData=True
Encroach Param= -1, 0, 0, 0
BEGIN DESCRIPTION:
Multiple Run
END DESCRIPTION:

--- UNT 165 IN CACR.f01 (steady flow) ---

Flow Title=Multiple
Number of Profiles=7
Profile Names=10-year,25-year,50-year,1pct_min,100-year,1pct_plu,500-year
River Rch & RM= UNT 165 IN CACR,Reach-1,3340
     488     658     798     712     963    1302    1406
Boundary for River Rch & Prof#=UNT 165 IN CACR,Reach-1,1
Up Type=0
Dn Type=3
Dn Slope=0.005
Boundary for River Rch & Prof#=UNT 165 IN CACR,Reach-1,2
Up Type=0
Dn Type=3
Dn Slope=0.005
Boundary for River Rch & Prof#=UNT 165 IN CACR,Reach-1,3
Up Type=0
Dn Type=3
Dn Slope=0.005
Boundary for River Rch & Prof#=UNT 165 IN CACR,Reach-1,4
Up Type=0
Dn Type=3
Dn Slope=0.005
Boundary for River Rch & Prof#=UNT 165 IN CACR,Reach-1,5
Up Type=0
Dn Type=3
Dn Slope=0.005
Boundary for River Rch & Prof#=UNT 165 IN CACR,Reach-1,6
Up Type=0
Dn Type=3
Dn Slope=0.005
Boundary for River Rch & Prof#=UNT 165 IN CACR,Reach-1,7
Up Type=0
Dn Type=3
Dn Slope=0.005

--- UNT 165 IN CACR.g01 (geometry) ---

Geom Title=Existing Conditions

River Reach=UNT 165 IN CACR,Reach-1
Reach XY= 30
      3692700.52     10679783.25      3692624.50     10679669.00
      3692638.25     10679585.00      3692619.50     10679309.00
      3692589.50     10679207.00      3692647.75     10679004.00
      3692653.75     10678810.00      3692592.50     10678689.00
      3692582.00     10678530.00      3692654.25     10678393.00
      3692643.25     10678302.00      3692704.75     10678273.00
      3692730.00     10678175.00      3692795.00     10678104.00
      3692809.00     10677975.00      3692784.50     10677906.00
      3692835.25     10677820.00      3692810.00     10677625.00
      3692868.75     10677535.00      3692843.75     10677458.00
      3692788.00     10677414.00      3692805.75     10677357.00
      3692733.25     10677229.00      3692720.75     10677131.00
      3692747.50     10677074.00      3692797.75     10677040.00
      3692898.25     10677078.00      3692933.25     10676968.00
      3693066.50     10676913.00      3693119.50     10676750.00

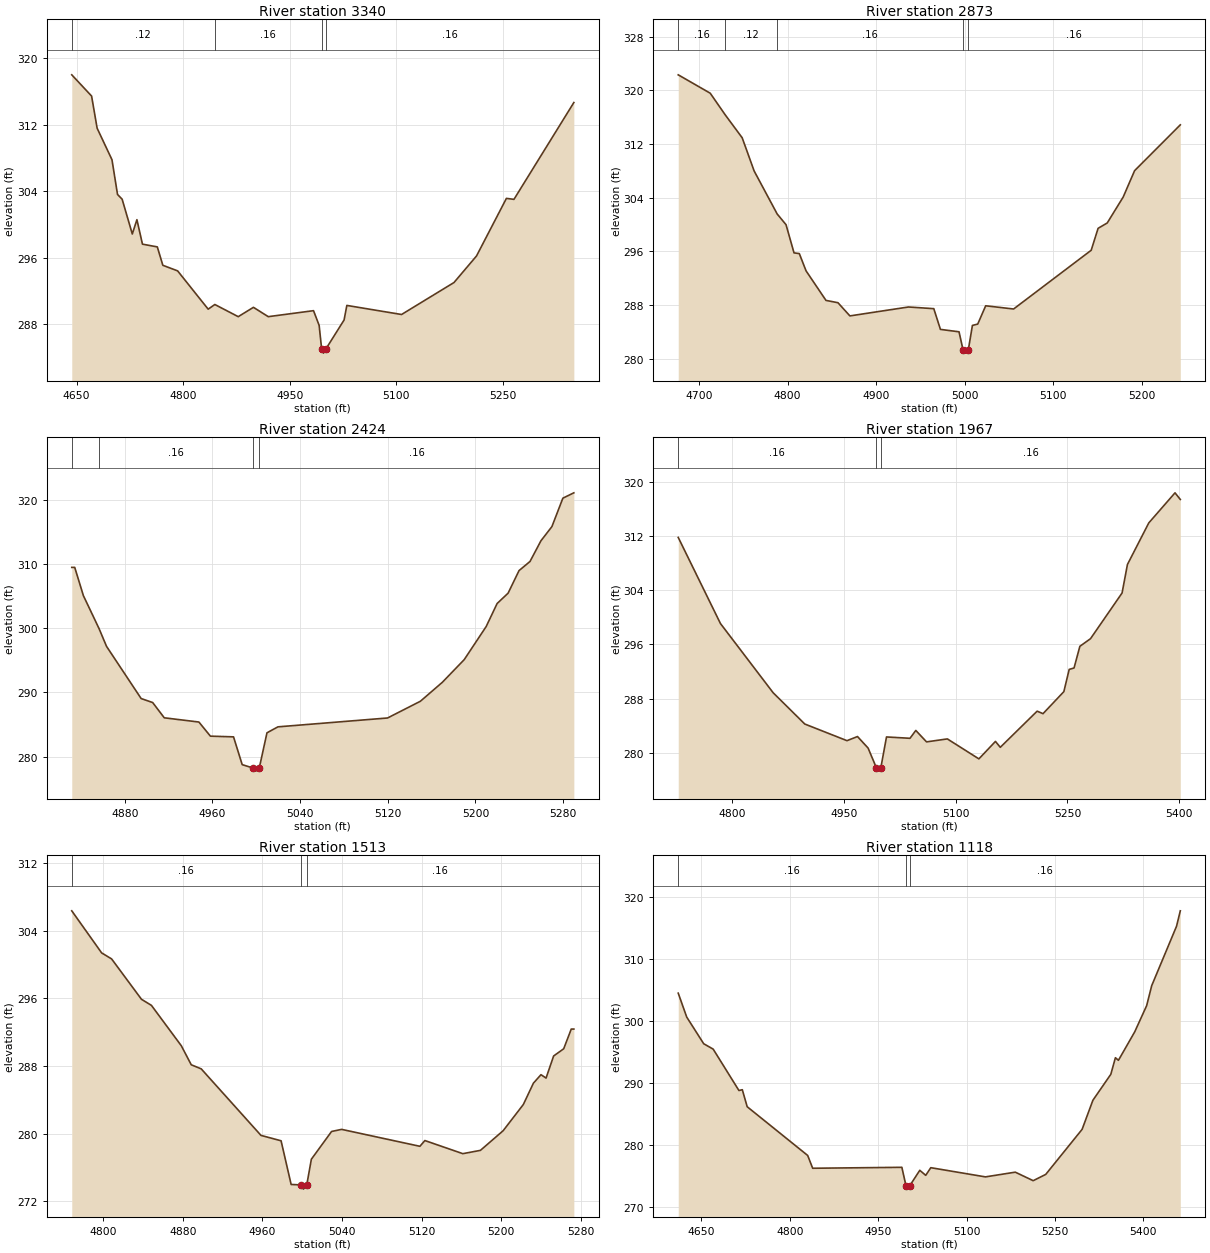
Type RM Length L Ch R = 1,3340,467,467,467
BEGIN DESCRIPTION:
UNT 165 IN CACR 6.0
END DESCRIPTION:
XS GIS Cut Line= 3
      3692899.57     10679310.22      3692599.61     10679560.19
      3692299.60     10679660.19
#Sta/Elev= 30
  4643.1  317.97  4671.0  315.42  4678.8  311.56  4699.7  307.77  4707.5  303.60
  4714.0  303.03  4728.3  298.85  4734.8  300.57  4742.6  297.63  4763.5  297.30
  4771.3  295.09  4792.1  294.42  4835.1  289.82  4844.5  290.38  4877.4  288.92
  4898.8  290.04  4919.7  288.92  4983.4  289.64  4991.3  287.87  4994.8  285.04
  4997.5  284.54  5000.8  285.04  5026.4  288.52  5030.3  290.27  5107.3  289.18
  5181.1  293.02  5212.8  296.21  5254.9  303.13  5265.5  303.01  5349.8  314.64
#Mann=4,-1,0
  4643.1    0.12       0  4844.5    0.16       0  4994.8    0.07       0
  5000.8    0.16       0
Bank Sta=4994.8,5000.8
Exp/Cntr=0.3,0.1

Type RM Length L Ch R = 1,2873,449,449,449
BEGIN DESCRIPTION:
UNT 165 IN CACR 5.0
END DESCRIPTION:
XS GIS Cut Line= 3
      3692899.64     10678910.17      3692599.61     10679110.19
      3692399.56     10679160.20
#Sta/Elev= 30
  4676.5  322.32  4712.6  319.58  4729.5  316.36  4748.7  312.93  4762.2  307.98
  4788.2  301.57  4798.2  299.97  4807.2  295.77  4813.2  295.66  4820.8  293.09
  4843.3  288.68  4856.8  288.34  4870.3  286.37  4936.4  287.70  4965.0  287.45
  4972.5  284.36  4993.5  284.00  4998.0  281.32  5000.8  280.82  5004.0  281.32
  5008.6  284.95  5014.6  285.15  5023.6  287.88  5055.1  287.40  5142.7  296.16
  5150.5  299.43  5160.8  300.23  5178.8  304.09  5191.7  308.03  5243.3  314.86
#Mann=5,-1,0
  4676.5    0.16       0  4729.5    0.12       0  4788.2    0.16       0
  4998.0    0.07       0  5004.0    0.16       0
Bank Sta=4998,5004
Exp/Cntr=0.3,0.1

Type RM Length L Ch R = 1,2424,457,457,457
BEGIN DESCRIPTION:
UNT 165 IN CACR 4.0
END DESCRIPTION:
XS GIS Cut Line= 3
      3692749.64     10678710.20      3692599.61     10678660.19
      3692299.65     10678660.19
#Sta/Elev= 30
  4831.7  309.48  4834.4  309.48  4842.3  305.08  4856.6  299.94  4863.4  297.18
  4895.0  289.04  4905.5  288.42  4916.1  286.04  4947.7  285.38  4958.2  283.18
  4979.3  283.07  4987.2  278.74  4996.8  278.23  4999.6  277.73  5002.8  278.23
  5009.8  283.70  5019.8  284.63  5119.8  286.01  5149.8  288.62  5169.8  291.57
  5189.8  295.11  5209.8  300.26  5219.8  303.85  5229.8  305.46  5239.8  308.98
  5249.8  310.40  5259.8  313.63  5269.8  315.84  5279.8  320.27  5289.8  321.10
#Mann=4,-1,0
  4831.7    0.12       0  4856.6    0.16       0  4996.8    0.07       0
  5002.8    0.16       0
Bank Sta=4996.8,5002.8
Exp/Cntr=0.3,0.1

Type RM Length L Ch R = 1,1967,454,454,454
BEGIN DESCRIPTION:
UNT 165 IN CACR 3.0
END DESCRIPTION:
XS GIS Cut Line= 3
      3692899.60     10678460.18      3692699.61     10678260.19
      3692399.65     10678010.22
#Sta/Elev= 30
  4728.0  311.80  4784.6  299.08  4855.3  288.85  4897.7  284.23  4954.3  281.77
  4968.4  282.38  4982.6  280.68  4993.7  277.77  4996.4  277.27  4999.7  277.77
  5007.3  282.32  5038.8  282.12  5046.6  283.28  5061.0  281.59  5088.9  282.03
  5131.2  279.08  5153.4  281.66  5159.9  280.79  5209.3  286.13  5217.2  285.76
  5245.1  289.01  5252.3  292.30  5258.8  292.51  5266.6  295.71  5280.9  296.84
  5323.2  303.59  5330.4  307.80  5359.0  313.94  5394.2  318.39  5401.3  317.41
#Mann=3,-1,0
  4728.0    0.16       0  4993.7    0.07       0  4999.7    0.16       0
Bank Sta=4993.7,4999.7
Exp/Cntr=0.3,0.1

Type RM Length L Ch R = 1,1513,395,395,395
BEGIN DESCRIPTION:
UNT 165 IN CACR 2.0
END DESCRIPTION:
XS GIS Cut Line= 3
      3693049.64     10677860.19      3692849.61     10677860.19
      3692549.58     10677910.19
#Sta/Elev= 30
  4768.6  306.33  4798.6  301.36  4808.6  300.65  4838.6  295.88  4848.6  295.16
  4878.6  290.39  4888.6  288.14  4898.6  287.66  4958.6  279.80  4978.8  279.16
  4988.9  274.00  4998.6  273.95  5001.3  273.45  5004.6  273.95  5009.2  276.98
  5029.5  280.26  5039.6  280.51  5118.2  278.51  5123.2  279.19  5161.3  277.64
  5179.0  278.03  5201.8  280.35  5222.1  283.45  5232.2  285.97  5239.8  286.97
  5244.9  286.57  5252.5  289.18  5262.6  290.03  5270.2  292.36  5272.8  292.36
#Mann=3,-1,0
  4768.6    0.16       0  4998.6    0.07       0  5004.6    0.16       0
Bank Sta=4998.6,5004.6
Exp/Cntr=0.3,0.1

Type RM Length L Ch R = 1,1118,763,763,763
BEGIN DESCRIPTION:
Mapping XS 8967c12f
END DESCRIPTION:
XS GIS Cut Line= 3
      3693075.55     10677802.79      3692915.83     10677511.12
      3692403.26     10677428.00
#Sta/Elev= 30
  4610.9  304.46  4625.3  300.61  4654.1  296.32  4670.2  295.45  4713.9  288.79
  4719.6  288.92  4727.9  286.18  4830.5  278.34  4839.0  276.28  4990.3  276.43
  4997.4  273.42  5000.1  272.92  5003.4  273.42  5020.7  275.95  5030.8  275.14
  5039.4  276.37  5132.1  274.89  5182.7  275.65  5213.1  274.28  5234.4  275.29
  5296.1  282.54  5314.4  287.22  5344.8  291.40  5352.6  294.07  5357.7  293.65
  5385.4  298.24  5405.6  302.45  5414.2  305.67  5456.3  315.23  5462.7  317.71
#Mann=3,-1,0
  4610.9    0.16       0  4997.4    0.07       0  5003.4    0.16       0
Bank Sta=4997.4,5003.4
Exp/Cntr=0.3,0.1

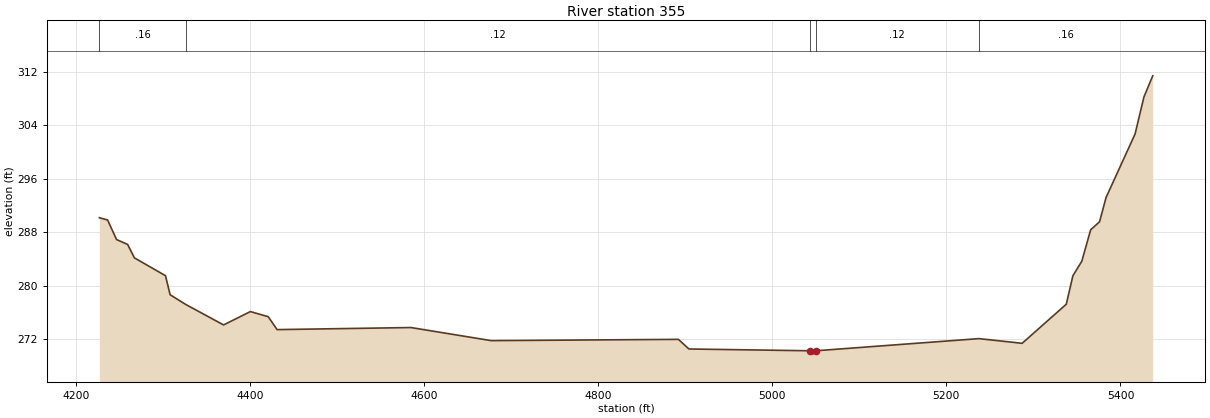
Type RM Length L Ch R = 1,355,0,0,0
BEGIN DESCRIPTION:
UNT 165 IN CACR 1.0
END DESCRIPTION:
XS GIS Cut Line= 4
      3693131.12     10677719.50      3692981.80     10677049.32
      3692877.63     10676959.04      3692499.71     10677035.32
#Sta/Elev= 30
  4227.1  290.17  4236.6  289.83  4246.9  286.90  4259.6  286.17  4267.4  284.16
  4303.1  281.49  4308.4  278.64  4326.3  277.19  4369.8  274.12  4400.6  276.12
  4421.1  275.35  4431.3  273.42  4585.0  273.73  4677.2  271.77  4892.3  271.96
  4904.3  270.52  5043.9  270.25  5046.7  269.75  5049.9  270.25  5237.4  272.07
  5287.1  271.37  5337.8  277.22  5345.4  281.49  5355.6  283.65  5365.8  288.36
  5376.0  289.56  5383.5  293.20  5416.8  302.70  5427.0  308.25  5437.1  311.41
#Mann=5,-1,0
  4227.1    0.16       0  4326.3    0.12       0  5043.9    0.07       0
  5049.9    0.12       0  5237.4    0.16       0
Bank Sta=5043.9,5049.9
Exp/Cntr=0.3,0.1

Chan Stop Cuts=-1