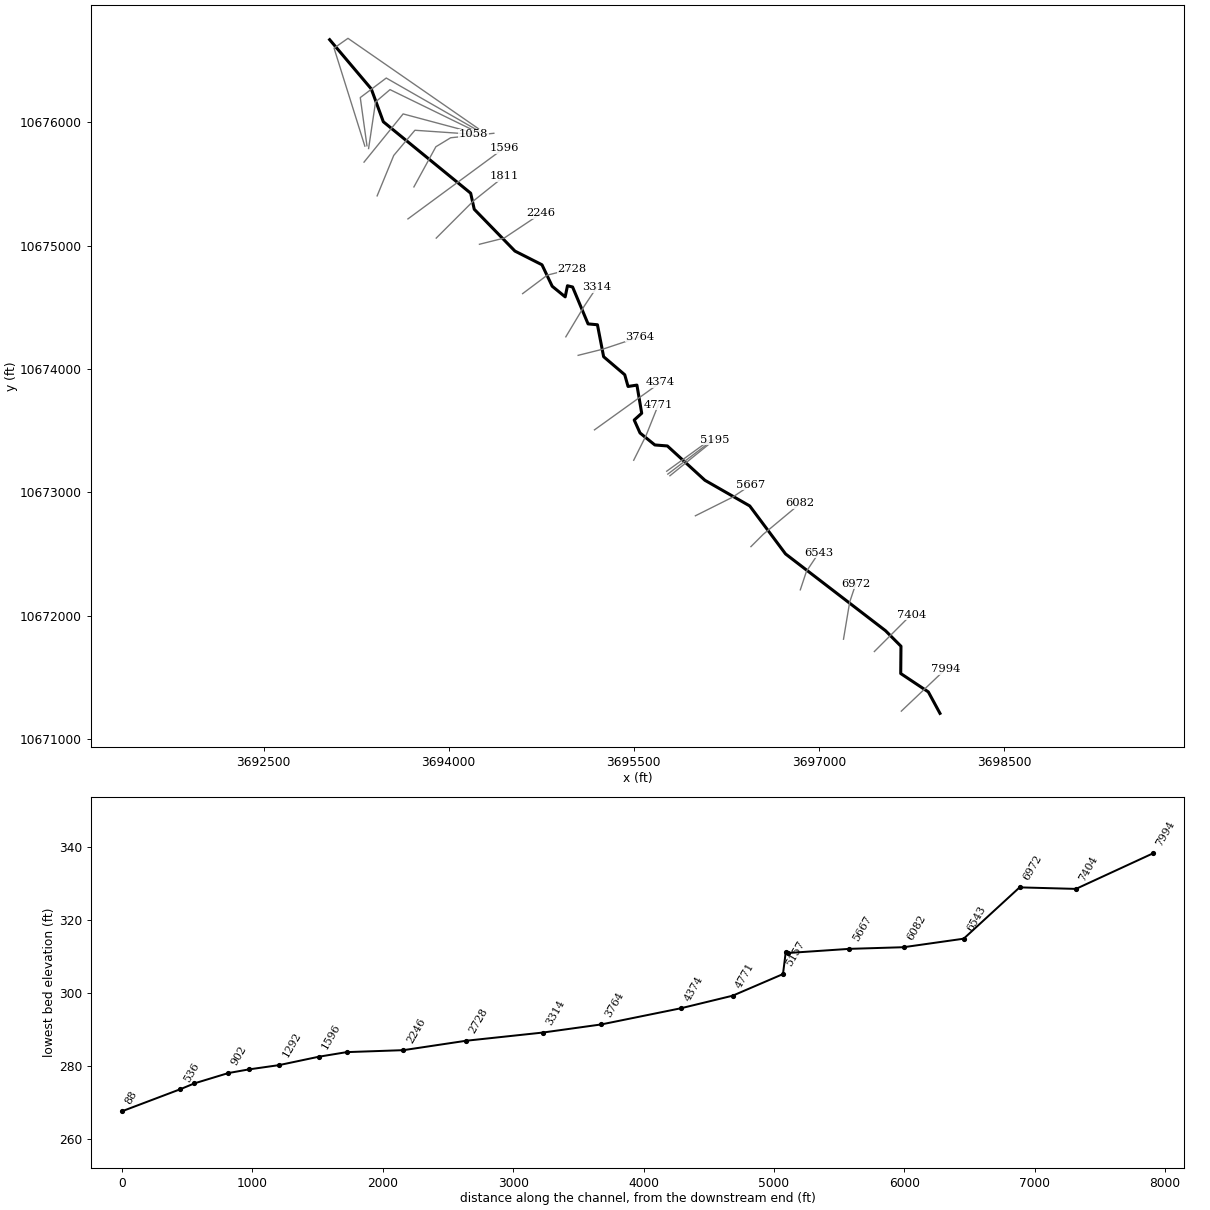
--- UNT 166 IN CACR.prj (project) ---

Proj Title=UNT 166 IN CACR Base Level Engineering
Current Plan=p01
Default Exp/Contr=0.3,0.1
English Units
Geom File=g01
Flow File=f01
Plan File=p01
Y Axis Title=Elevation
X Axis Title(PF)=Main Channel Distance
X Axis Title(XS)=Station
BEGIN DESCRIPTION:
UNT 166 IN CACR
END DESCRIPTION:
DSS Export Rating Curves= 0
DSS Export Rating Curve Sorted= 0
DSS Export Volume Flow Curves= 0
DXF OffsetX= 0
DXF OffsetY= 0
DXF ScaleX= 1
DXF ScaleY= 10

--- UNT 166 IN CACR.p01 (plan) ---

Plan Title=Multiple Run
Short Identifier=Multiple
Geom File=g01
Flow File=f01
Subcritical Flow
K Sum by GR= 0
Std Step Tol= 0.01
Critical Tol= 0.01
Num of Std Step Trials= 20
Max Error Tol= 0.3
Flow Tol Ratio= 0.001
Split Flow NTrial= 30
Split Flow Tol= 0.02
Split Flow Ratio= 0.02
Log Output Level= 0
Friction Slope Method= 1
Unsteady Friction Slope Method= 2
Unsteady Bridges Friction Slope Method= 1
Parabolic Critical Depth
Global Vel Dist=  1 , 1 , 1
Global Log Level= 0
CheckData=True
Encroach Param= -1, 0, 0, 0
BEGIN DESCRIPTION:
Multiple Run
END DESCRIPTION:

--- UNT 166 IN CACR.f01 (steady flow) ---

Flow Title=Multiple
Program Version=4.10
Number of Profiles= 7
Profile Names=10-year,25-year,50-year,1pct_min,100-year,1pct_plu,500-year
River Rch & RM=UNT 166 IN CACR,Reach-1         ,7994
     454     608     734     652     881    1192    1275
Boundary for River Rch & Prof#=UNT 166 IN CACR,Reach-1         , 1
Up Type= 0
Dn Type= 3
Dn Slope=0.01
Boundary for River Rch & Prof#=UNT 166 IN CACR,Reach-1         , 2
Up Type= 0
Dn Type= 3
Dn Slope=0.01
Boundary for River Rch & Prof#=UNT 166 IN CACR,Reach-1         , 3
Up Type= 0
Dn Type= 3
Dn Slope=0.01
Boundary for River Rch & Prof#=UNT 166 IN CACR,Reach-1         , 4
Up Type= 0
Dn Type= 3
Dn Slope=0.01
Boundary for River Rch & Prof#=UNT 166 IN CACR,Reach-1         , 5
Up Type= 0
Dn Type= 3
Dn Slope=0.01
Boundary for River Rch & Prof#=UNT 166 IN CACR,Reach-1         , 6
Up Type= 0
Dn Type= 3
Dn Slope=0.01
Boundary for River Rch & Prof#=UNT 166 IN CACR,Reach-1         , 7
Up Type= 0
Dn Type= 3
Dn Slope=0.01
DSS Import GetInterval= 0
DSS Import GetPeak= 0
DSS Import FillOption= 0

--- UNT 166 IN CACR.g01 (geometry) ---

Geom Title=Existing Conditions
Program Version=4.10

River Reach=UNT 166 IN CACR ,Reach-1
Reach XY= 30
      3697981.34     10671209.06        3697887.       10671383.
      3697663.25       10671532.      3697665.25       10671753.
        3697540.       10671879.        3696730.       10672501.
      3696439.75       10672890.       3696076.5       10673098.
       3695772.5       10673376.        3695671.       10673384.
        3695551.       10673481.      3695503.75       10673586.
       3695564.5       10673641.      3695525.75       10673869.
      3695453.75       10673858.        3695427.       10673953.
        3695256.       10674099.      3695205.75       10674358.
      3695129.75       10674365.       3695004.5       10674664.
        3694963.       10674674.       3694944.5       10674584.
      3694839.25       10674670.       3694756.5       10674844.
      3694537.25       10674955.       3694207.5       10675294.
      3694178.54     10675424.08      3693470.88     10676002.83
      3693373.13     10676269.26        3693036.       10676668.

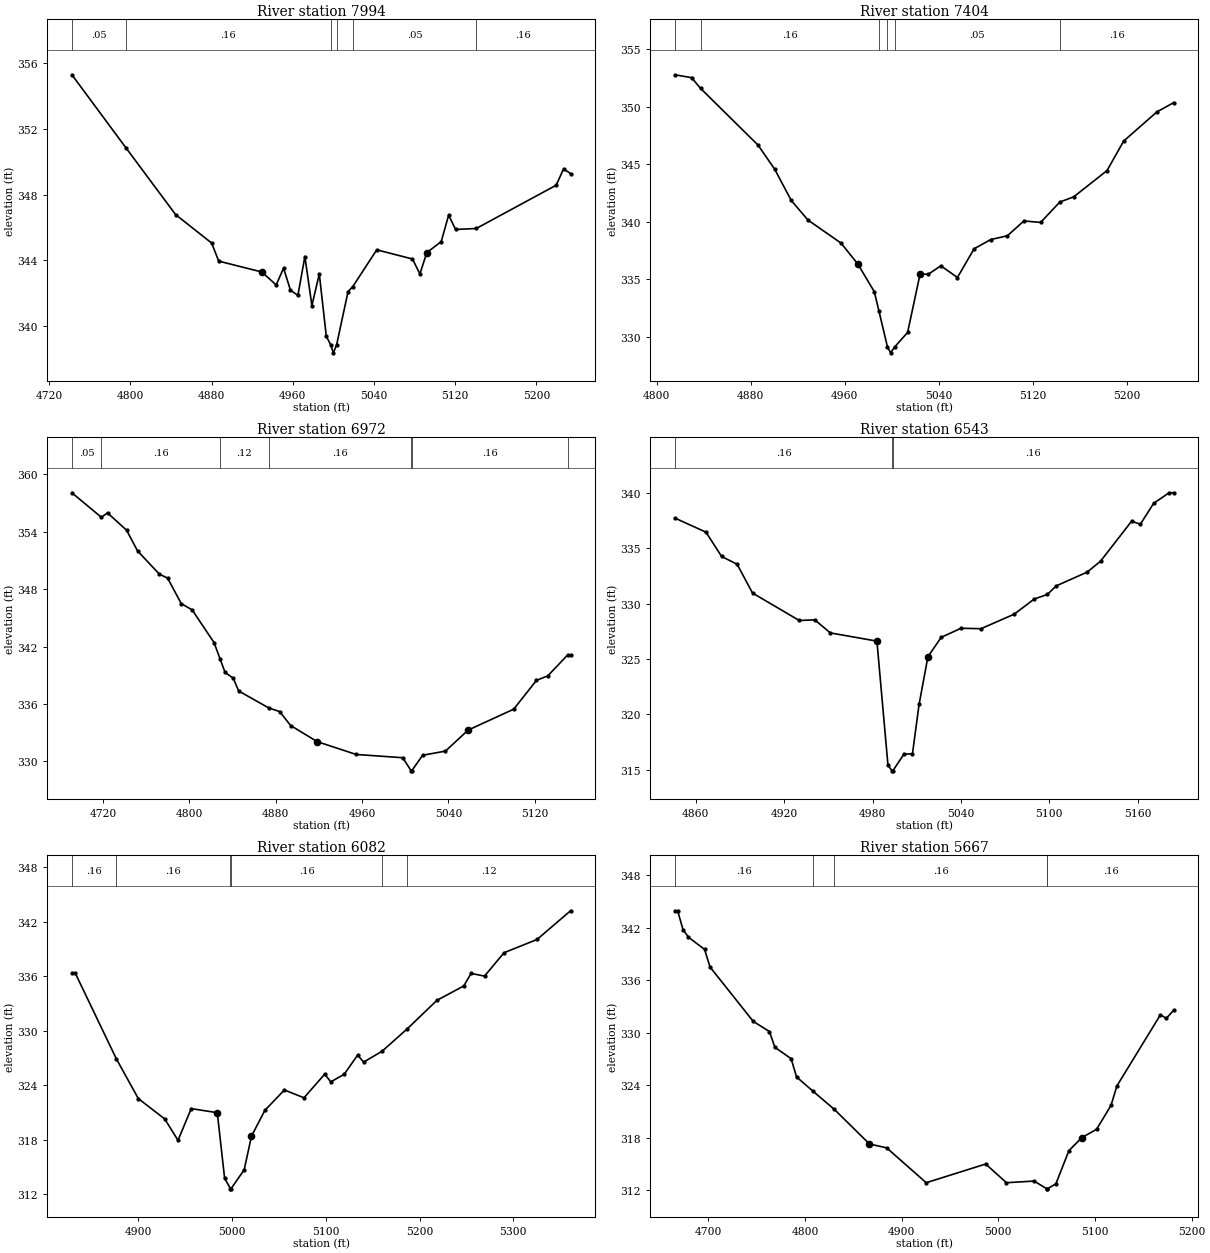
Type RM Length L Ch R = 1 ,7994    ,590,590,590
BEGIN DESCRIPTION:
UNT 166 IN CACR 15.0
END DESCRIPTION:
XS GIS Cut Line= 2
      3697668.13     10671227.21      3698024.45     10671565.32
#Sta/Elev= 30
  4742.4   355.3  4795.6  350.85  4844.5  346.78  4880.1  345.04    4887  343.94
  4929.4  343.28  4943.6  342.49  4950.9  343.51  4957.7  342.17    4965  341.85
  4971.9  344.22  4978.8  341.23  4986.1  343.16    4993  339.36  4997.2  338.85
    5000  338.35  5003.2  338.85  5014.4  342.08  5019.1  342.39  5042.7  344.63
  5077.9  344.07  5085.2  343.16    5092  344.46  5106.2  345.13  5113.5  346.74
  5120.4  345.87  5140.7  345.93  5219.5  348.57  5226.7  349.56  5233.6  349.28
#Mann= 6 ,-1 , 0
  4742.4     .05       0  4795.6     .16       0  4997.2     .07       0
  5003.2     .16       0  5019.1     .05       0  5140.7     .16       0
Bank Sta=4929.4,5092
XS Rating Curve= 0 ,0
Exp/Cntr=0.3,0.1

Type RM Length L Ch R = 1 ,7404    ,432,432,432
BEGIN DESCRIPTION:
UNT 166 IN CACR 14.0
END DESCRIPTION:
XS GIS Cut Line= 3
      3697449.59     10671710.17      3697599.61     10671860.19
      3697749.62      10672010.2
#Sta/Elev= 30
  4815.6  352.78  4829.8  352.53  4837.4   351.6  4886.3  346.67  4900.5  344.57
  4914.6  341.85  4928.8  340.15    4957  338.14  4971.2  336.33  4985.3  333.91
  4989.2  332.24  4996.5   329.1  4999.2   328.6  5002.5   329.1  5013.6  330.37
  5024.2  335.44  5031.3  335.44  5041.9  336.17    5056  335.15  5070.2  337.65
  5084.3  338.45  5098.5  338.78  5112.6  340.07  5126.8  339.94  5143.1  341.71
    5155  342.17  5183.3  344.45  5197.5  347.02  5225.7  349.55  5239.9  350.35
#Mann= 6 ,-1 , 0
  4815.6     .12       0  4837.4     .16       0  4989.2     .05       0
  4996.5     .04       0  5002.5     .05       0  5143.1     .16       0
Bank Sta=4971.2,5024.2
XS Rating Curve= 0 ,0
Exp/Cntr=0.3,0.1

Type RM Length L Ch R = 1 ,6972    ,429,429,429
BEGIN DESCRIPTION:
UNT 166 IN CACR 13.0
END DESCRIPTION:
XS GIS Cut Line= 3
       3697199.6     10671810.16      3697249.61     10672110.19
      3697299.62     10672260.21
#Sta/Elev= 30
    4691  358.06  4718.3   355.5    4724  355.96  4741.7  354.15  4751.9  351.98
  4772.1  349.56  4779.7  349.15  4792.4  346.48  4802.5  345.83  4822.8  342.41
  4828.4   340.7    4833   339.3  4840.6  338.69  4845.6  337.36  4873.5  335.59
  4883.6  335.21  4893.8  333.75  4918.4  332.07  4954.6  330.73  4997.8  330.39
  5005.5  329.02    5006  329.02  5016.2  330.65  5037.3  331.08  5058.4  333.28
  5100.6  335.46  5121.7  338.47  5132.2  338.94  5150.6  341.12  5153.3  341.12
#Mann= 7 ,-1 , 0
    4691     .05       0  4718.3     .16       0  4828.4     .12       0
  4873.5     .16       0  5005.5     .07       0    5006     .16       0
  5150.6     .05       0
Bank Sta=4918.4,5058.4
XS Rating Curve= 0 ,0
Exp/Cntr=0.3,0.1

Type RM Length L Ch R = 1 ,6543    ,461,461,461
BEGIN DESCRIPTION:
UNT 166 IN CACR 12.0
END DESCRIPTION:
XS GIS Cut Line= 3
       3696849.6     10672210.15      3696899.61     10672360.19
      3696999.59     10672510.16
#Sta/Elev= 30
  4845.9   337.7    4867  336.43  4877.6  334.24  4888.1  333.54  4898.6  330.94
  4930.3  328.47  4940.8  328.53  4951.4  327.35    4983  326.61  4990.5  315.42
  4993.3  314.92  4993.8  314.92  5001.4  316.44  5007.1  316.44  5011.6   320.9
  5017.6   325.2  5026.6  326.95  5040.1  327.77  5053.6  327.73  5076.2  329.04
  5089.7   330.4  5098.7  330.82  5104.7  331.59  5125.7  332.83  5134.8  333.82
  5155.8  337.41  5161.8  337.15  5170.8  339.03  5181.3  339.98  5184.3  339.98
#Mann= 3 ,-1 , 0
  4845.9     .16       0  4993.3     .07       0  4993.8     .16       0
Bank Sta=4983,5017.6
XS Rating Curve= 0 ,0
Exp/Cntr=0.3,0.1

Type RM Length L Ch R = 1 ,6082    ,415,415,415
BEGIN DESCRIPTION:
UNT 166 IN CACR 11.0
END DESCRIPTION:
XS GIS Cut Line= 3
      3696449.58     10672560.16      3696549.61     10672660.19
      3696849.63      10672910.2
#Sta/Elev= 30
  4829.1  336.31  4832.7  336.31  4876.4  326.91  4899.9  322.52  4928.1  320.27
  4942.3  317.92  4956.4  321.41  4984.2  320.96    4992  313.76  4998.3  312.58
  4998.8  312.58  5012.9  314.68  5020.7  318.38    5035  321.22  5055.8  323.46
  5076.7   322.6  5098.8   325.2  5105.3  324.35  5119.6  325.19  5133.9  327.29
  5140.4  326.53    5160  327.72    5187   330.2  5218.5  333.32  5247.2  334.91
    5255  336.29  5269.3  335.99  5290.1  338.56  5325.3  340.02  5361.1  343.18
#Mann= 6 ,-1 , 0
  4829.1     .16       0  4876.4     .16       0  4998.3     .07       0
  4998.8     .16       0    5160     .16       0    5187     .12       0
Bank Sta=4984.2,5020.7
XS Rating Curve= 0 ,0
Exp/Cntr=0.3,0.1

Type RM Length L Ch R = 1 ,5667    ,472,472,472
BEGIN DESCRIPTION:
UNT 166 IN CACR 10.0
END DESCRIPTION:
XS GIS Cut Line= 3
      3695999.62     10672810.19      3696299.61     10672960.19
      3696449.63      10673060.2
#Sta/Elev= 30
  4665.5  343.94  4668.3  343.94  4673.9  341.78  4679.5  340.92  4696.2  339.52
  4701.8  337.51  4746.5  331.29  4763.3  330.12  4768.9  328.32  4785.7  327.02
  4791.3  324.93  4808.1  323.32  4830.4  321.22  4866.7  317.26  4884.5  316.82
  4925.4  312.83  4986.9  314.97  5008.4  312.83    5037  313.02  5050.2  312.13
  5050.7  312.13  5059.5   312.7    5073   316.5  5086.5     318  5101.6  318.94
  5116.6  321.69  5122.6   323.9  5167.7  332.05  5173.7  331.63  5181.2  332.54
#Mann= 5 ,-1 , 0
  4665.5     .16       0  4808.1     .12       0  4830.4     .16       0
  5050.2     .07       0  5050.7     .16       0
Bank Sta=4866.7,5086.5
XS Rating Curve= 0 ,0
Exp/Cntr=0.3,0.1

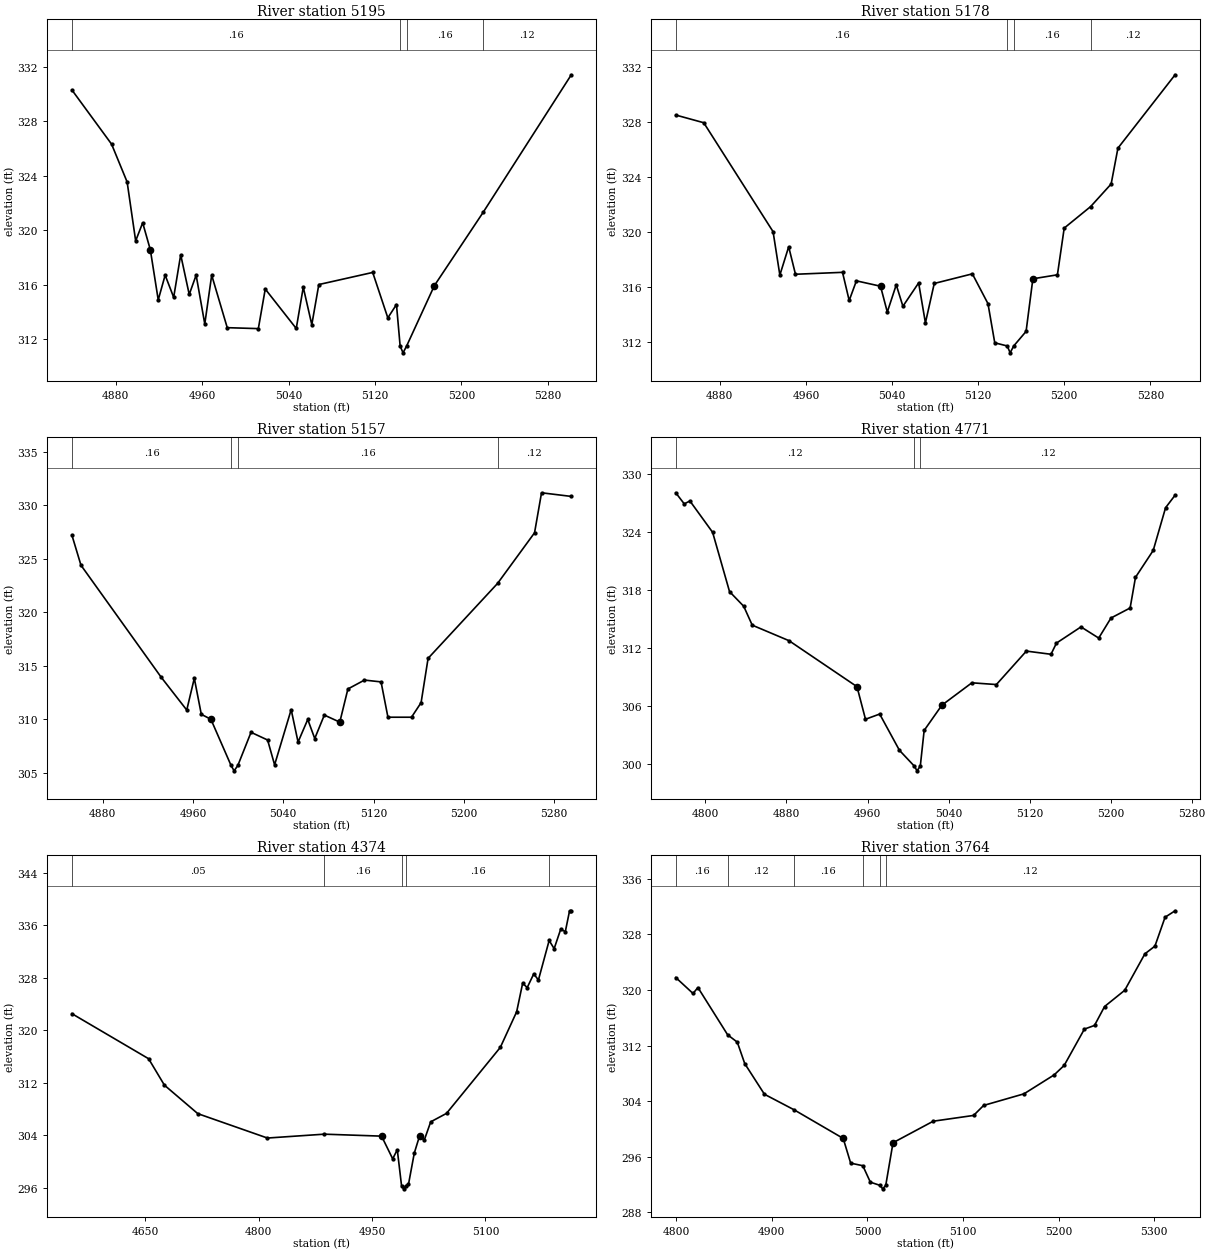
Type RM Length L Ch R = 1 ,5195    ,17,17,17
BEGIN DESCRIPTION:
UNT 166 IN CACR 9.0
END DESCRIPTION:
XS GIS Cut Line= 2
       3695793.2     10673134.41      3696152.53     10673425.43
#Sta/Elev= 30
  4839.4  330.31  4876.1  326.33  4890.5  323.55  4898.4  319.22  4904.9  320.55
    4912  318.56  4919.3  314.88  4925.7   316.7  4933.6  315.07  4940.1   318.2
    4948  315.28  4954.4   316.7  4962.4  313.11  4968.8   316.7  4983.2  312.84
    5012  312.77  5018.4  315.68  5047.1  312.78  5053.6  315.81  5061.5  313.06
    5068  316.01  5117.9   316.9  5131.9  313.56  5139.9  314.54  5143.3  311.49
    5146  310.99  5149.3  311.49    5175  315.93  5220.1  321.31  5301.8  331.43
#Mann= 4 ,-1 , 0
  4839.4     .16       0  5143.3     .07       0  5149.3     .16       0
  5220.1     .12       0
Bank Sta=4912,5175
XS Rating Curve= 0 ,0
Exp/Cntr=0.3,0.1

Type RM Length L Ch R = 1 ,5178    ,21,21,21
BEGIN DESCRIPTION:
Mapping XS 8736dea1
END DESCRIPTION:
XS GIS Cut Line= 2
      3695776.06     10673147.86      3696145.22     10673428.63
#Sta/Elev= 30
  4839.1   328.5  4865.1  327.94  4929.5  320.01  4935.8  316.85    4944  318.91
  4950.3  316.91    4994  317.05  5000.2     315  5006.9  316.43  5029.3  316.04
  5035.6  314.16  5043.9  316.14  5050.1  314.58  5064.7  316.28    5071  313.37
  5079.2  316.24  5114.6  316.94  5129.1  314.77  5135.4  311.92    5147  311.69
  5149.7  311.19    5153  311.69  5164.5  312.75  5170.8  316.58  5193.6  316.87
  5199.9  320.27  5224.5  321.84  5243.5  323.48  5249.8  326.09  5302.9  331.43
#Mann= 4 ,-1 , 0
  4839.1     .16       0    5147     .07       0    5153     .16       0
  5224.5     .12       0
Bank Sta=5029.3,5170.8
XS Rating Curve= 0 ,0
Exp/Cntr=0.3,0.1

Type RM Length L Ch R = 1 ,5157    ,386,386,386
BEGIN DESCRIPTION:
Mapping XS 281cfbf8
END DESCRIPTION:
XS GIS Cut Line= 2
      3695767.13     10673171.28      3696125.98     10673430.69
#Sta/Elev= 30
  4852.6  327.21  4860.6  324.41  4931.7  313.95  4954.4  310.88  4961.1  313.85
  4967.3  310.48  4975.8  310.02  4993.7   305.7  4996.4   305.2  4999.7   305.7
  5011.4   308.8  5026.1  308.08  5032.3  305.76    5047  310.92  5053.1  307.89
  5061.7     310  5067.9  308.22  5076.4  310.41  5090.1  309.75  5097.3  312.85
    5112  313.68  5126.7  313.51  5132.8  310.21  5153.7  310.21  5162.2  311.57
  5168.4  315.71    5230  322.71  5262.8  327.44    5269  331.18  5295.4  330.84
#Mann= 4 ,-1 , 0
  4852.6     .16       0  4993.7     .07       0  4999.7     .16       0
    5230     .12       0
Bank Sta=4975.8,5090.1
XS Rating Curve= 0 ,0
Exp/Cntr=0.3,0.1

Type RM Length L Ch R = 1 ,4771    ,397,397,397
BEGIN DESCRIPTION:
UNT 166 IN CACR 8.0
END DESCRIPTION:
XS GIS Cut Line= 3
       3695499.6     10673260.17      3695599.61     10673460.19
      3695699.62     10673710.21
#Sta/Elev= 30
  4770.7   328.1  4779.1  326.95  4784.7  327.25  4807.1     324  4823.8  317.85
  4837.8  316.33  4846.2  314.37  4882.5  312.76  4949.6  307.99    4958  304.61
    4972  305.15  4991.5  301.39  5006.1  299.76  5008.9  299.26  5012.1  299.76
  5015.9  303.45  5033.4  306.07    5063  308.39  5087.2  308.21  5116.8  311.68
  5141.1  311.35  5146.5  312.51  5170.7  314.19  5188.2  313.03  5200.3  315.11
  5219.2  316.15  5224.5  319.33    5242  322.12  5254.2  326.55  5263.6  327.85
#Mann= 3 ,-1 , 0
  4770.7     .12       0  5006.1     .07       0  5012.1     .12       0
Bank Sta=4949.6,5033.4
XS Rating Curve= 0 ,0
Exp/Cntr=0.3,0.1

Type RM Length L Ch R = 1 ,4374    ,610,610,610
BEGIN DESCRIPTION:
UNT 166 IN CACR 7.0
END DESCRIPTION:
XS GIS Cut Line= 2
      3695181.82     10673506.33      3695718.32     10673891.78
#Sta/Elev= 30
    4553  322.53  4654.4  315.66  4675.3  311.63  4719.5  307.28  4811.6  303.56
  4886.8  304.15  4962.6  303.85  4977.3  300.39  4983.4  301.77    4989  296.31
  4991.8  295.81    4995  296.31  4998.2  296.49  5005.9  301.27  5012.9  303.89
  5019.1  303.25  5027.6  306.03  5048.5  307.32  5119.7  317.39  5141.3  322.82
  5149.2  327.16  5155.3  326.52  5163.9   328.6  5170.1  327.67  5184.3   333.7
  5190.9  332.45  5199.5  335.39  5205.7  335.06  5211.3  338.23  5213.6  338.23
#Mann= 5 ,-1 , 0
    4553     .05       0  4886.8     .16       0    4989     .07       0
    4995     .16       0  5184.3     .12       0
Bank Sta=4962.6,5012.9
XS Rating Curve= 0 ,0
Exp/Cntr=0.3,0.1

Type RM Length L Ch R = 1 ,3764    ,450,450,450
BEGIN DESCRIPTION:
UNT 166 IN CACR 6.0
END DESCRIPTION:
XS GIS Cut Line= 3
       3695049.6     10674110.19      3695249.61     10674160.19
      3695549.61     10674260.19
#Sta/Elev= 30
  4799.5   321.8  4817.6   319.5  4822.7  320.36  4853.8  313.55  4863.9  312.49
  4871.7   309.4  4892.3  304.99  4923.2  302.76  4974.7  298.63  4982.5  295.07
  4995.2   294.7  5003.1  292.33  5013.2  291.87    5016  291.37  5019.2  291.87
  5026.8  298.01  5068.9  301.11  5111.1  301.94  5121.6  303.38  5163.8  305.05
  5195.4  307.78  5205.9  309.15    5227  314.37  5237.6   314.9  5248.1  317.62
  5269.2  319.96  5290.3  325.21  5300.8  326.32  5311.4  330.48  5321.9  331.41
#Mann= 6 ,-1 , 0
  4799.5     .16       0  4853.8     .12       0  4923.2     .16       0
  4995.2     .12       0  5013.2     .07       0  5019.2     .12       0
Bank Sta=4974.7,5026.8
XS Rating Curve= 0 ,0
Exp/Cntr=0.3,0.1

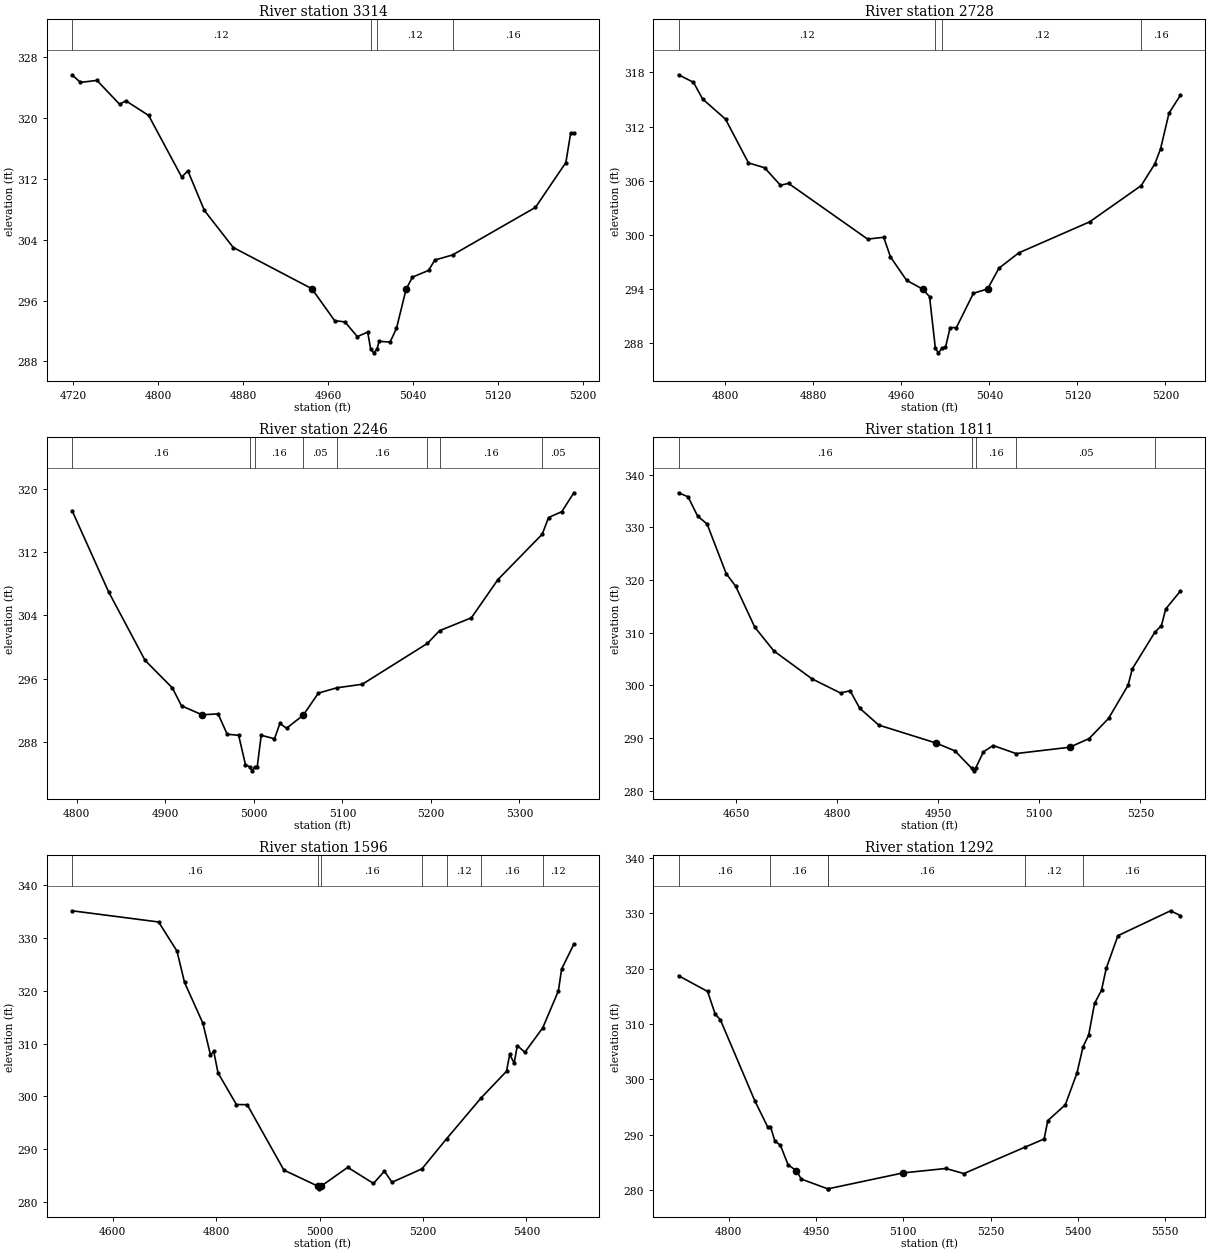
Type RM Length L Ch R = 1 ,3314    ,586,586,586
BEGIN DESCRIPTION:
UNT 166 IN CACR 5.0
END DESCRIPTION:
XS GIS Cut Line= 3
      3694949.59     10674260.15      3695099.61     10674510.19
      3695199.63     10674660.21
#Sta/Elev= 30
  4719.3  325.64  4727.1  324.64  4742.7   324.9    4764  321.77  4769.9  322.22
  4791.3   320.3  4822.4  312.21  4828.2  313.03  4843.7  307.83  4870.9  302.96
  4944.8  297.55  4966.2  293.36  4975.9  293.19  4987.6  291.26  4997.3  291.86
  5000.1  289.63  5002.9  289.13  5006.1  289.63    5008  290.64  5018.4  290.55
  5024.4  292.35  5033.4  297.47  5039.4  299.07  5054.5  299.95  5060.5  301.32
  5077.1  301.98  5155.1  308.23  5183.7  314.12  5188.2  317.99  5191.2  317.99
#Mann= 4 ,-1 , 0
  4719.3     .12       0  5000.1     .07       0  5006.1     .12       0
  5077.1     .16       0
Bank Sta=4944.8,5033.4
XS Rating Curve= 0 ,0
Exp/Cntr=0.3,0.1

Type RM Length L Ch R = 1 ,2728    ,482,482,482
BEGIN DESCRIPTION:
UNT 166 IN CACR 4.0
END DESCRIPTION:
XS GIS Cut Line= 3
      3694599.58     10674610.17      3694799.61     10674760.19
      3694999.62     10674810.19
#Sta/Elev= 30
  4757.4  317.74    4771   316.9  4779.3  315.05  4800.1  312.82    4821  307.96
  4835.6  307.43  4850.1  305.48  4857.4  305.69  4929.3  299.51  4943.9  299.71
  4950.1  297.53  4964.7  294.94  4979.3  293.96  4985.6  293.13  4990.9  287.39
  4993.6  286.89  4996.9  287.39  5000.1  287.49  5004.3  289.69    5010  289.69
  5025.5   293.5  5038.4  293.98  5048.7  296.28  5066.7  297.98  5131.1  301.42
    5178  305.44  5190.4  307.85  5195.6  309.51  5203.3  313.48  5213.6  315.46
#Mann= 4 ,-1 , 0
  4757.4     .12       0  4990.9     .07       0  4996.9     .12       0
    5178     .16       0
Bank Sta=4979.3,5038.4
XS Rating Curve= 0 ,0
Exp/Cntr=0.3,0.1

Type RM Length L Ch R = 1 ,2246    ,435,435,435
BEGIN DESCRIPTION:
UNT 166 IN CACR 3.0
END DESCRIPTION:
XS GIS Cut Line= 3
      3694249.66      10675010.2      3694449.61     10675060.19
      3694749.64     10675260.21
#Sta/Elev= 30
  4794.7   317.3  4835.9  307.01  4877.1  298.32    4908  294.81  4918.3  292.54
  4941.5  291.41  4959.6  291.52  4969.9  288.94  4982.8  288.81  4990.5   285.1
  4995.2   284.8    4998   284.3  5001.2   284.8  5003.8   284.8  5008.3  288.81
  5023.3  288.37  5029.4  290.31  5036.9   289.7  5055.8  291.36  5072.9  294.16
  5093.8  294.83  5122.5  295.28    5196  300.46  5209.7  302.07  5245.7  303.71
  5275.7  308.56  5325.7  314.31  5332.8  316.42  5347.8  317.17  5361.4  319.56
#Mann= 8 ,-1 , 0
  4794.7     .16       0  4995.2     .07       0  5001.2     .16       0
  5055.8     .05       0  5093.8     .16       0    5196     .05       0
  5209.7     .16       0  5325.7     .05       0
Bank Sta=4941.5,5055.8
XS Rating Curve= 0 ,0
Exp/Cntr=0.3,0.1

Type RM Length L Ch R = 1 ,1811    ,215,215,215
BEGIN DESCRIPTION:
UNT 166 IN CACR 2.0
END DESCRIPTION:
XS GIS Cut Line= 3
      3693899.63     10675060.21      3694199.61     10675360.19
      3694449.62     10675560.19
#Sta/Elev= 30
  4564.7  336.56  4578.8   335.8    4593  332.14  4607.1  330.62  4635.4  321.21
  4649.5  318.81  4677.8  311.04  4706.1  306.53  4762.7  301.23  4805.1  298.53
  4819.2  298.98  4833.4  295.66  4861.7  292.45  4946.5  289.05  4974.8  287.55
  4999.5  284.26  5002.3  283.76  5005.5  284.26  5016.9  287.36  5031.4  288.57
  5065.4  287.04    5145  288.24  5173.8  289.89  5202.6  293.71  5231.5  299.99
  5237.9  303.13  5271.2  310.06  5281.1  311.34  5287.5  314.51  5309.1  317.88
#Mann= 5 ,-1 , 0
  4564.7     .16       0  4999.5     .07       0  5005.5     .16       0
  5065.4     .05       0  5271.2     .12       0
Bank Sta=4946.5,5145
XS Rating Curve= 0 ,0
Exp/Cntr=0.3,0.1

Type RM Length L Ch R = 1 ,1596    ,304,304,304
BEGIN DESCRIPTION:
Mapping XS 22062fa8
END DESCRIPTION:
XS GIS Cut Line= 2
      3693670.34     10675215.68       3694451.6     10675790.77
#Sta/Elev= 30
  4521.6  335.13  4688.9  333.01  4724.4   327.5    4739  321.58  4774.5  313.84
  4789.2  307.82  4795.4  308.54  4803.8  304.43  4839.3  298.45  4860.2  298.42
  4931.1  286.04    4997  282.99  4999.8  282.49    5003  282.99  5054.5  286.56
  5104.3  283.51  5125.5  285.84  5140.1  283.73  5198.1  286.28  5245.5  291.95
  5312.1  299.67  5361.5  304.75  5367.7  307.97  5376.2  306.28  5382.4   309.6
    5397  308.35  5431.5  312.96  5461.8  319.96    5468  324.08  5491.7  328.82
#Mann= 7 ,-1 , 0
  4521.6     .16       0    4997     .07       0    5003     .16       0
  5198.1     .05       0  5245.5     .12       0  5312.1     .16       0
  5431.5     .12       0
Bank Sta=4997,5003
XS Rating Curve= 0 ,0
Exp/Cntr=0.3,0.1

Type RM Length L Ch R = 1 ,1292    ,234,234,234
BEGIN DESCRIPTION:
Mapping XS 98455eae
END DESCRIPTION:
XS GIS Cut Line= 4
      3693718.66     10675474.87      3693896.67     10675800.28
      3694016.47     10675873.19      3694366.33     10675909.47
#Sta/Elev= 30
  4713.5  318.71  4763.5  315.87  4776.6  311.75  4785.3  310.78  4844.9  296.05
  4866.9  291.36  4871.6  291.43  4879.1  288.86  4888.7  288.06  4901.9  284.54
  4916.2  283.46  4924.7  281.95    4970  280.19  4970.5  280.19  5099.6  283.07
  5173.2  283.87  5204.2  282.95    5310  287.76  5342.2   289.2  5348.5  292.52
  5378.6  295.38  5398.7  301.13  5409.1  305.87  5418.8     308  5428.9   313.7
  5440.9   316.1    5449  320.05  5469.1  325.95  5559.6  330.45  5576.4  329.59
#Mann= 6 ,-1 , 0
  4713.5     .16       0  4871.6     .16       0    4970     .07       0
  4970.5     .16       0    5310     .12       0  5409.1     .16       0
Bank Sta=4916.2,5099.6
XS Rating Curve= 0 ,0
Exp/Cntr=0.3,0.1

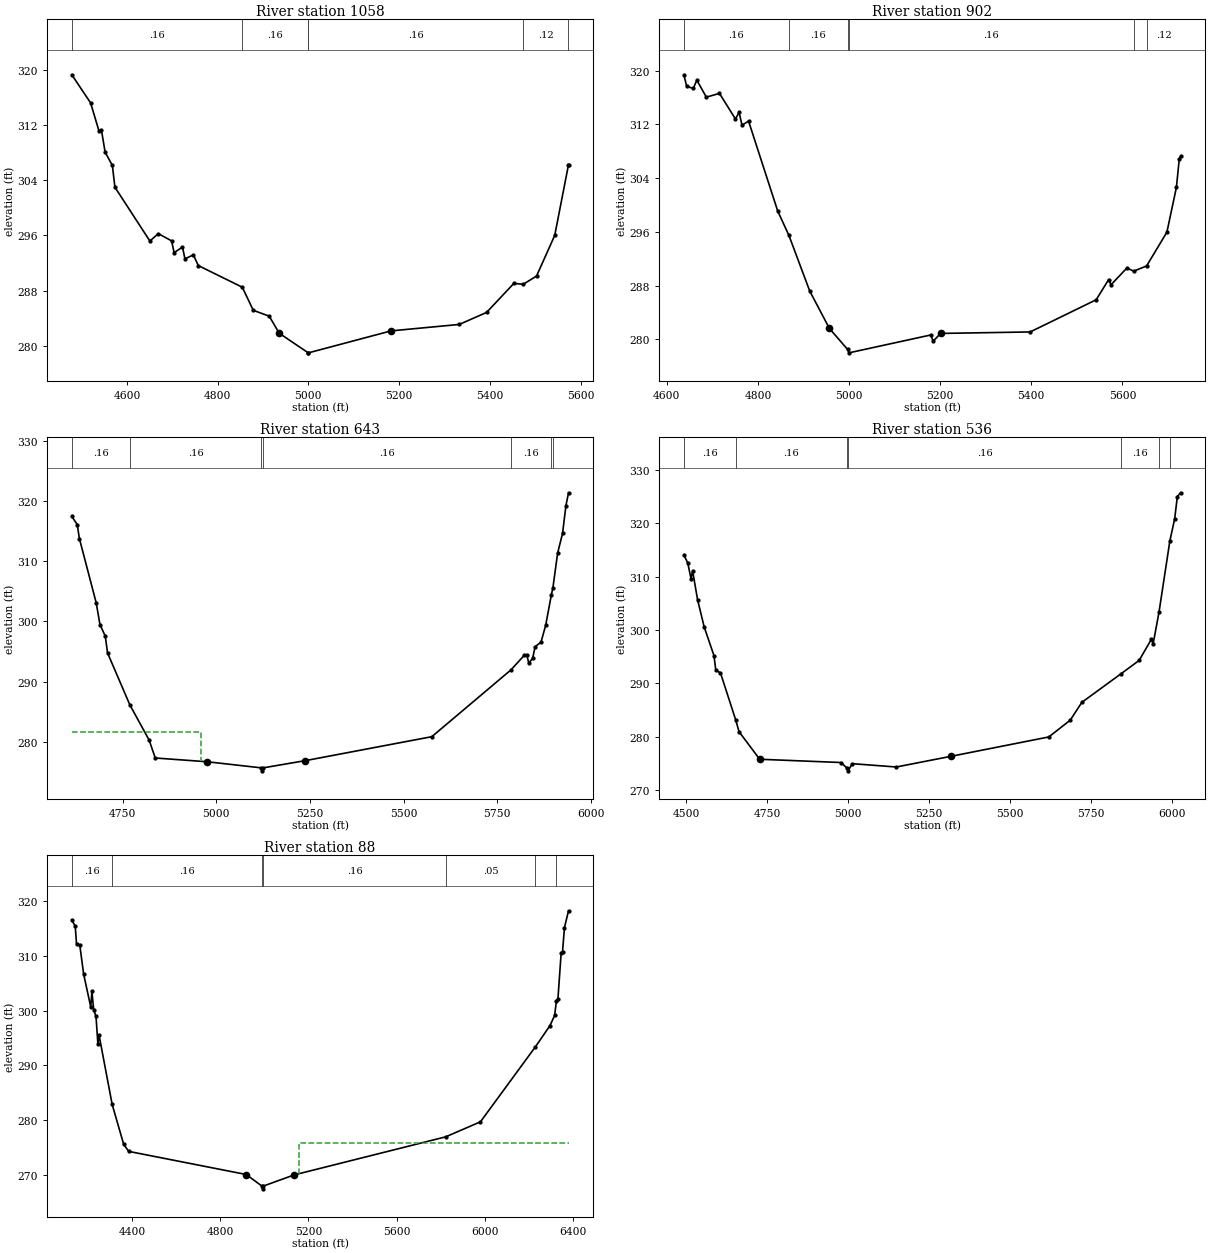
Type RM Length L Ch R = 1 ,1058    ,156,156,156
BEGIN DESCRIPTION:
Mapping XS 94276299
END DESCRIPTION:
XS GIS Cut Line= 4
      3693420.77     10675402.27      3693555.33       10675730.
      3693726.77     10675933.99      3694199.91     10675901.44
#Sta/Elev= 30
  4478.6  319.26    4520  315.19  4538.6   311.1    4544  311.23    4552  308.06
    4568  306.13  4573.6  302.98  4650.7  295.19  4669.3  296.26  4698.6  295.21
  4704.1   293.5  4722.6  294.32    4728  292.61  4746.6  293.18  4757.4  291.64
  4854.4   288.5  4878.6  285.16  4913.8  284.31  4935.8  281.84  4999.8     279
  5000.3     279  5182.4  282.18  5332.7  283.11  5392.9  284.85    5453  289.05
  5473.8  288.93  5503.1  290.12  5543.2  296.01  5573.3  306.16  5573.6  306.16
#Mann= 6 ,-1 , 0
  4478.6     .16       0  4854.4     .16       0  4999.8     .07       0
  5000.3     .16       0  5473.8     .12       0  5573.3     .16       0
Bank Sta=4935.8,5182.4
XS Rating Curve= 0 ,0
Exp/Cntr=0.3,0.1

Type RM Length L Ch R = 1 ,902     ,259,259,259
BEGIN DESCRIPTION:
Mapping XS 61dd0bf2
END DESCRIPTION:
XS GIS Cut Line= 3
      3693314.46     10675675.77      3693631.29     10676066.37
      3694198.55     10675914.81
#Sta/Elev= 30
  4637.5  319.39  4643.7  317.68  4658.1  317.35    4666  318.59  4686.8  316.06
  4715.6  316.62  4750.7  312.81  4758.7  313.79  4765.1  311.89  4779.5  312.49
  4843.4  299.12  4868.1  295.47  4913.8  287.19  4956.9  281.63    4997   278.5
  4999.8     278  5179.4  280.66  5184.5  279.72  5200.8  280.89  5397.5  281.11
  5542.4   285.9  5569.7   288.9  5574.9  288.13  5609.8  290.63  5624.7  290.16
    5653  290.93  5697.6  295.97  5718.4  302.62  5724.8  306.89  5727.6  307.25
#Mann= 6 ,-1 , 0
  4637.5     .16       0  4868.1     .16       0    4997     .07       0
  4999.8     .16       0  5624.7     .16       0    5653     .12       0
Bank Sta=4956.9,5200.8
XS Rating Curve= 0 ,0
Exp/Cntr=0.3,0.1

Type RM Length L Ch R = 1 ,643     ,107,107,107
BEGIN DESCRIPTION:
Mapping XS b5aaf566
END DESCRIPTION:
XS GIS Cut Line= 4
      3693351.52     10675785.84      3693407.94     10676163.42
      3693525.13     10676263.25      3694235.77      10675916.6
#Sta/Elev= 30
  4614.2  317.42  4628.7  316.06  4634.4  313.75  4679.3  303.08  4689.4  299.46
  4703.6  297.53  4709.6  294.76  4769.3  286.11  4820.8  280.27    4837  277.31
  4975.5  276.69  5119.5  275.68  5122.3  275.18  5125.5  275.68  5237.5  276.87
  5575.5  280.85  5786.7  291.93  5822.5  294.36  5828.9  294.48  5834.5  293.05
  5844.7  293.86  5851.4   295.8    5867  296.53  5879.5  299.31  5894.8  304.42
  5898.9  305.59  5911.5  311.33  5924.6   314.6  5933.7  319.22  5940.6  321.34
#Mann= 7 ,-1 , 0
  4614.2     .16       0  4769.3     .16       0  5119.5     .07       0
  5125.5     .16       0  5786.7     .16       0  5894.8     .12       0
  5898.9     .16       0
#XS Ineff= 2 , 0
         4957.95  281.56
Permanent Ineff=
       F       F
Bank Sta=4975.5,5237.5
XS Rating Curve= 0 ,0
Exp/Cntr=0.3,0.1

Type RM Length L Ch R = 1 ,536     ,448,448,448
BEGIN DESCRIPTION:
Mapping XS 37bcde5f
END DESCRIPTION:
XS GIS Cut Line= 4
      3693338.32     10675808.13      3693284.06     10676198.75
      3693494.57     10676357.17      3694255.42     10675921.47
#Sta/Elev= 30
  4492.9  314.08  4505.1   312.5    4515  309.59    4520  311.03  4535.4  305.61
  4555.6  300.57  4585.8   295.2  4591.7  292.44    4606  291.95  4652.9  283.16
  4663.4  280.92  4727.2  275.76  4978.3  275.15    4997  274.09  4999.8  273.59
  5013.7  274.93  5149.1  274.31  5319.7  276.33  5620.4  279.94  5686.6  283.08
  5722.6  286.43  5844.2  291.81  5899.5  294.28    5937  298.21  5942.7  297.38
  5960.8  303.31  5994.4  316.68  6009.3  320.82  6017.5  324.98  6027.5  325.69
#Mann= 7 ,-1 , 0
  4492.9     .16       0  4652.9     .16       0    4997     .07       0
  4999.8     .16       0  5844.2     .16       0  5960.8     .12       0
  5994.4     .16       0
Bank Sta=4727.2,5319.7
XS Rating Curve= 0 ,0
Exp/Cntr=0.3,0.1

Type RM Length L Ch R = 1 ,88      ,0,0,0
BEGIN DESCRIPTION:
UNT 166 IN CACR 1.0
END DESCRIPTION:
XS GIS Cut Line= 4
      3693321.13     10675805.37      3693071.57     10676599.62
      3693184.48     10676678.83      3694242.06     10675946.21
#Sta/Elev= 30
  4124.6  316.49  4140.1  315.37  4145.9  312.17  4161.1  311.85  4178.3  306.64
  4210.7  300.63  4215.9  303.51    4224  300.12  4234.5  298.94  4243.1  293.91
  4248.3  295.54  4307.9   282.9  4360.3  275.62  4383.2  274.34  4917.3  270.13
  4988.4  268.02  4991.1  267.52  4994.4  268.02    5135  270.06  5823.3  276.99
  5981.4  279.73  6231.3   293.4  6297.6  297.27  6318.5  299.12  6326.3  301.71
  6333.4  302.11  6348.2  310.55  6354.3   310.7  6363.1  315.12  6381.6  318.17
#Mann= 7 ,-1 , 0
  4124.6     .16       0  4307.9     .16       0  4988.4     .07       0
  4994.4     .16       0  5823.3     .05       0  6231.3     .16       0
  6326.3     .12       0
#XS Ineff= 2 , 0
                         5159.09          275.84
Permanent Ineff=
       F       F
Bank Sta=4917.3,5135
XS Rating Curve= 0 ,0
Exp/Cntr=0.3,0.1

Chan Stop Cuts=-1
Use User Specified Reach Order=0
Composite Channel Slope=5