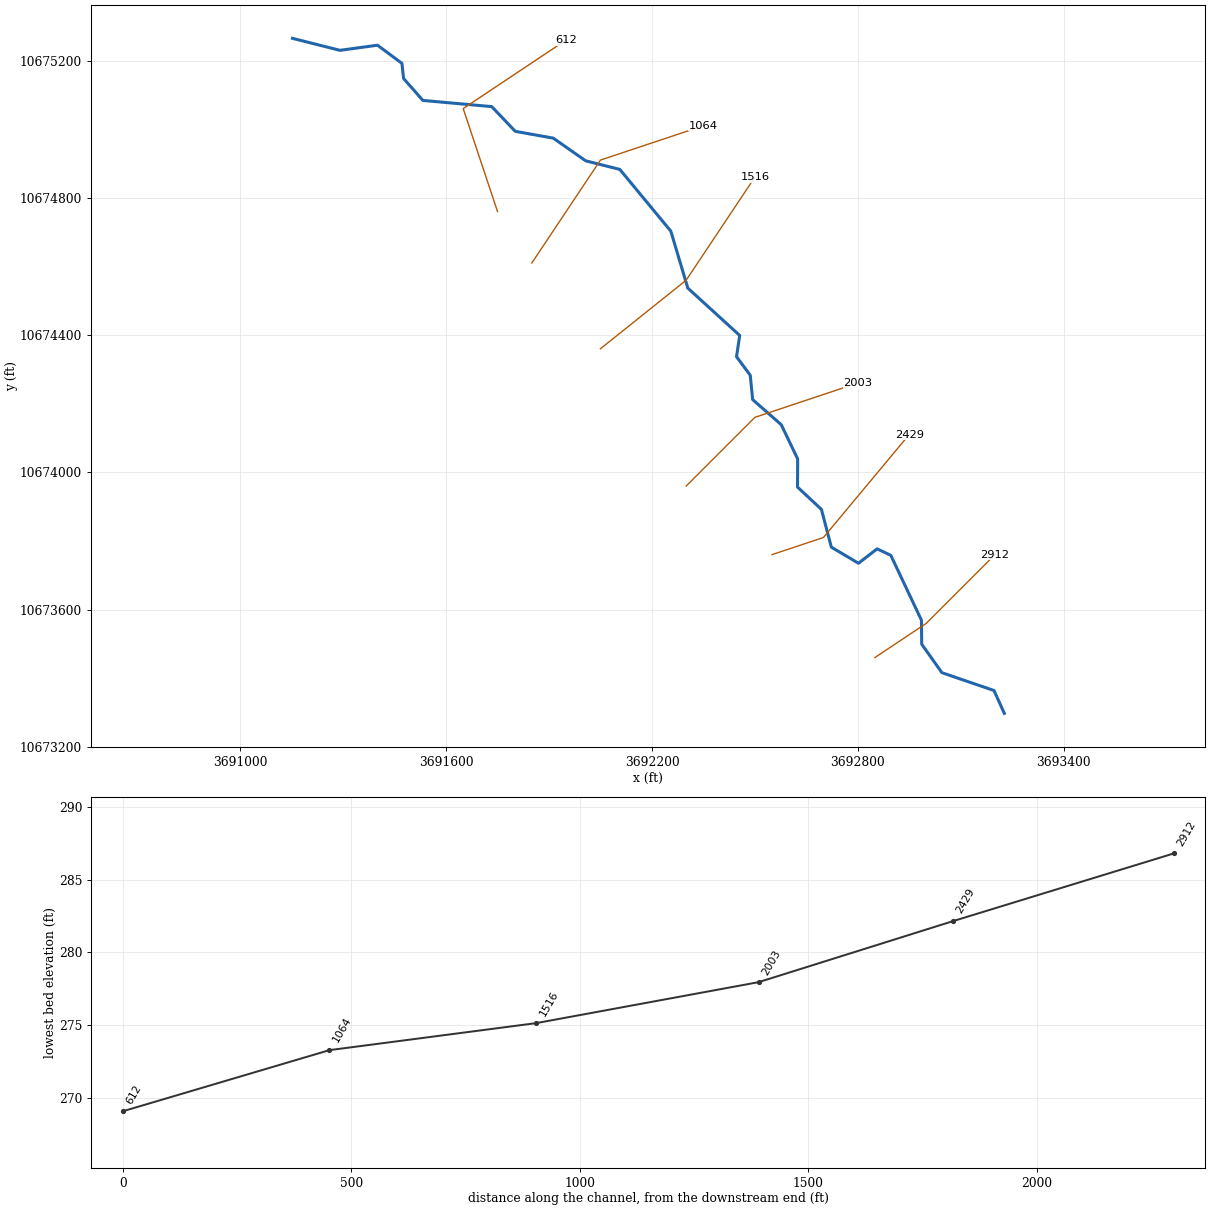
--- UNT 167 IN CACR.prj (project) ---

Proj Title=UNT 167 IN CACR Base Level Engineering
Current Plan=p01
Default Exp/Contr=0.3,0.1
English Units
Geom File=g01
Flow File=f01
Plan File=p01
BEGIN DESCRIPTION:
UNT 167 IN CACR
END DESCRIPTION:

--- UNT 167 IN CACR.p01 (plan) ---

Plan Title=Multiple Run
Short Identifier=Multiple
Geom File=g01
Flow File=f01
Subcritical Flow
K Sum by GR= 0
Std Step Tol= 0.01
Critical Tol= 0.01
Num of Std Step Trials= 20
Max Error Tol= 0.3
Flow Tol Ratio= 0.001
Split Flow NTrial= 30
Split Flow Tol= 0.02
Split Flow Ratio= 0.02
Log Output Level= 0
Friction Slope Method= 1
Unsteady Friction Slope Method= 2
Unsteady Bridges Friction Slope Method= 1
Parabolic Critical Depth
Global Vel Dist=  1 , 1 , 1
Global Log Level= 0
CheckData=True
Encroach Param= -1, 0, 0, 0
BEGIN DESCRIPTION:
Multiple Run
END DESCRIPTION:

--- UNT 167 IN CACR.f01 (steady flow) ---

Flow Title=Multiple
Number of Profiles=7
Profile Names=10-year,25-year,50-year,1pct_min,100-year,1pct_plu,500-year
River Rch & RM= UNT 167 IN CACR,Reach-1,2912
     344     454     543     478     646     874     920
Boundary for River Rch & Prof#=UNT 167 IN CACR,Reach-1,1
Up Type=0
Dn Type=3
Dn Slope=0.005
Boundary for River Rch & Prof#=UNT 167 IN CACR,Reach-1,2
Up Type=0
Dn Type=3
Dn Slope=0.005
Boundary for River Rch & Prof#=UNT 167 IN CACR,Reach-1,3
Up Type=0
Dn Type=3
Dn Slope=0.005
Boundary for River Rch & Prof#=UNT 167 IN CACR,Reach-1,4
Up Type=0
Dn Type=3
Dn Slope=0.005
Boundary for River Rch & Prof#=UNT 167 IN CACR,Reach-1,5
Up Type=0
Dn Type=3
Dn Slope=0.005
Boundary for River Rch & Prof#=UNT 167 IN CACR,Reach-1,6
Up Type=0
Dn Type=3
Dn Slope=0.005
Boundary for River Rch & Prof#=UNT 167 IN CACR,Reach-1,7
Up Type=0
Dn Type=3
Dn Slope=0.005

--- UNT 167 IN CACR.g01 (geometry) ---

Geom Title=Existing Conditions

River Reach=UNT 167 IN CACR,Reach-1
Reach XY= 30
      3693226.84     10673297.44      3693196.75     10673364.00
      3693045.00     10673416.00      3692986.00     10673499.00
      3692985.25     10673569.00      3692896.00     10673758.00
      3692856.00     10673777.00      3692801.75     10673735.00
      3692722.50     10673782.00      3692693.75     10673892.00
      3692624.00     10673957.00      3692624.50     10674039.00
      3692576.50     10674139.00      3692493.25     10674212.00
      3692486.25     10674283.00      3692446.25     10674337.00
      3692455.50     10674399.00      3692304.25     10674537.00
      3692254.75     10674703.00      3692106.00     10674883.00
      3692006.50     10674908.00      3691912.25     10674974.00
      3691801.25     10674994.00      3691732.75     10675066.00
      3691532.00     10675084.00      3691475.75     10675148.00
      3691471.00     10675192.00      3691399.75     10675245.00
      3691290.25     10675230.00      3691152.00     10675265.00

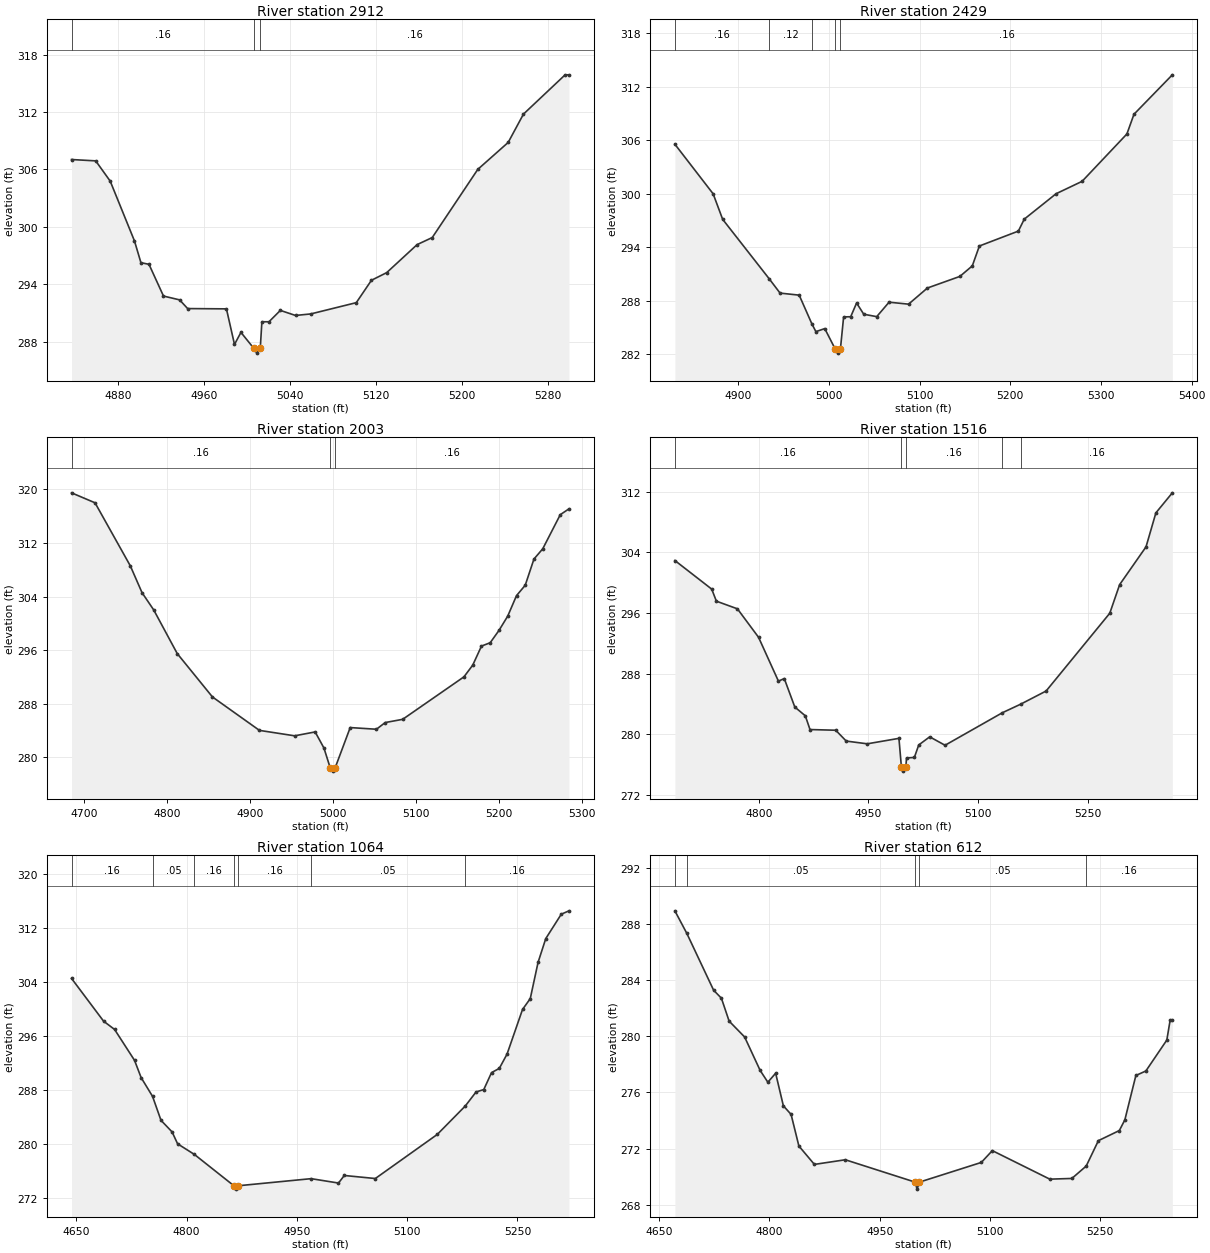
Type RM Length L Ch R = 1,2912,483,483,483
BEGIN DESCRIPTION:
UNT 167 IN CACR 6.0
END DESCRIPTION:
XS GIS Cut Line= 3
      3692849.64     10673460.21      3692999.61     10673560.19
      3693199.62     10673760.20
#Sta/Elev= 30
  4836.4  307.04  4858.9  306.90  4872.4  304.78  4895.0  298.52  4901.0  296.25
  4908.5  296.08  4922.0  292.76  4937.0  292.36  4944.5  291.45  4980.6  291.42
  4988.1  287.70  4994.1  288.96  5006.1  287.29  5008.9  286.79  5012.1  287.29
  5013.6  290.07  5020.2  290.07  5030.8  291.26  5044.9  290.73  5059.1  290.89
  5101.5  292.07  5115.6  294.41  5129.8  295.21  5158.1  298.14  5172.2  298.88
  5214.6  306.01  5242.9  308.83  5257.1  311.79  5295.9  315.90  5299.5  315.90
#Mann=3,-1,0
  4836.4    0.16       0  5006.1    0.07       0  5012.1    0.16       0
Bank Sta=5006.1,5012.1
Exp/Cntr=0.3,0.1

Type RM Length L Ch R = 1,2429,426,426,426
BEGIN DESCRIPTION:
UNT 167 IN CACR 5.0
END DESCRIPTION:
XS GIS Cut Line= 3
      3692549.59     10673760.18      3692699.61     10673810.19
      3692949.58     10674110.15
#Sta/Elev= 30
  4830.1  305.57  4872.3  300.01  4882.8  297.15  4934.3  290.46  4946.1  288.88
  4967.2  288.65  4981.1  285.45  4985.6  284.56  4995.4  284.90  5006.7  282.65
  5009.5  282.15  5012.7  282.65  5016.2  286.21  5024.0  286.23  5030.5  287.77
  5038.4  286.51  5052.7  286.24  5066.3  287.86  5087.8  287.64  5108.6  289.45
  5144.4  290.75  5158.1  291.93  5165.9  294.16  5208.9  295.83  5215.4  297.17
  5250.5  300.02  5279.2  301.41  5328.6  306.72  5336.4  308.93  5378.7  313.35
#Mann=5,-1,0
  4830.1    0.16       0  4934.3    0.12       0  4981.1    0.16       0
  5006.7    0.07       0  5012.7    0.16       0
Bank Sta=5006.7,5012.7
Exp/Cntr=0.3,0.1

Type RM Length L Ch R = 1,2003,487,487,487
BEGIN DESCRIPTION:
UNT 167 IN CACR 4.0
END DESCRIPTION:
XS GIS Cut Line= 3
      3692299.58     10673960.16      3692499.61     10674160.19
      3692799.60     10674260.18
#Sta/Elev= 30
  4685.2  319.49  4713.5  318.00  4756.0  308.59  4770.1  304.59  4784.2  302.01
  4812.5  295.50  4854.9  289.03  4911.5  284.04  4953.9  283.23  4978.6  283.81
  4989.2  281.40  4996.7  278.46  4999.5  277.96  5002.7  278.46  5020.8  284.46
  5052.4  284.21  5063.0  285.21  5084.0  285.69  5157.8  292.03  5168.4  293.78
  5178.9  296.62  5189.4  297.12  5200.0  298.96  5210.5  301.09  5221.1  304.15
  5231.6  305.70  5242.1  309.61  5252.7  311.14  5273.8  316.23  5284.3  317.10
#Mann=3,-1,0
  4685.2    0.16       0  4996.7    0.07       0  5002.7    0.16       0
Bank Sta=4996.7,5002.7
Exp/Cntr=0.3,0.1

Type RM Length L Ch R = 1,1516,452,452,452
BEGIN DESCRIPTION:
UNT 167 IN CACR 3.0
END DESCRIPTION:
XS GIS Cut Line= 3
      3692049.60     10674360.19      3692299.61     10674560.19
      3692499.60     10674860.17
#Sta/Elev= 30
  4685.1  302.91  4735.5  299.14  4741.9  297.55  4770.7  296.54  4799.6  292.79
  4826.8  287.01  4834.8  287.35  4849.2  283.60  4863.6  282.44  4870.0  280.63
  4905.2  280.54  4919.6  279.11  4948.4  278.75  4991.7  279.47  4995.1  275.65
  4997.8  275.15  5001.1  275.65  5002.1  276.89  5012.8  276.95  5018.8  278.60
  5033.8  279.67  5054.8  278.56  5133.3  282.85  5158.2  283.97  5193.1  285.71
  5280.2  295.96  5293.7  299.73  5329.8  304.71  5343.3  309.19  5365.8  311.83
#Mann=5,-1,0
  4685.1    0.16       0  4995.1    0.07       0  5001.1    0.16       0
  5133.3    0.05       0  5158.2    0.16       0
Bank Sta=4995.1,5001.1
Exp/Cntr=0.3,0.1

Type RM Length L Ch R = 1,1064,452,452,452
BEGIN DESCRIPTION:
UNT 167 IN CACR 2.0
END DESCRIPTION:
XS GIS Cut Line= 3
      3691849.59     10674610.15      3692049.61     10674910.19
      3692349.59     10675010.18
#Sta/Elev= 30
  4643.4  304.50  4687.0  298.17  4702.0  296.94  4729.1  292.37  4738.1  289.81
  4753.6  287.04  4765.1  283.49  4780.2  281.77  4787.7  280.01  4810.5  278.44
  4864.3  273.80  4867.0  273.30  4870.3  273.80  4969.4  274.85  5006.6  274.20
  5014.5  275.32  5056.7  274.87  5141.0  281.40  5179.1  285.61  5193.7  287.68
  5204.3  288.05  5214.8  290.55  5225.4  291.18  5235.9  293.29  5257.0  299.91
  5267.5  301.51  5278.1  306.87  5288.6  310.40  5309.7  314.01  5320.2  314.51
#Mann=7,-1,0
  4643.4    0.16       0  4753.6    0.05       0  4810.5    0.16       0
  4864.3    0.03       0  4870.3    0.16       0  4969.4    0.05       0
  5179.1    0.16       0
Bank Sta=4864.3,4870.3
Exp/Cntr=0.3,0.1

Type RM Length L Ch R = 1,612,0,0,0
BEGIN DESCRIPTION:
UNT 167 IN CACR 1.0
END DESCRIPTION:
XS GIS Cut Line= 3
      3691749.62     10674760.16      3691649.61     10675060.19
      3691949.60     10675260.18
#Sta/Elev= 30
  4671.3  288.92  4687.6  287.31  4724.0  283.27  4734.6  282.70  4745.1  281.07
  4766.2  279.94  4787.3  277.56  4797.8  276.72  4808.4  277.36  4818.9  275.04
  4829.4  274.43  4840.0  272.18  4861.1  270.87  4903.2  271.20  4998.1  269.61
  5000.8  269.11  5004.1  269.61  5088.2  271.01  5103.2  271.85  5181.4  269.82
  5211.4  269.87  5230.9  270.75  5247.5  272.56  5276.0  273.28  5283.5  274.04
  5298.5  277.20  5312.1  277.52  5340.6  279.72  5345.1  281.13  5348.1  281.13
#Mann=5,-1,0
  4671.3    0.12       0  4687.6    0.05       0  4998.1    0.03       0
  5004.1    0.05       0  5230.9    0.16       0
Bank Sta=4998.1,5004.1
Exp/Cntr=0.3,0.1

Chan Stop Cuts=-1