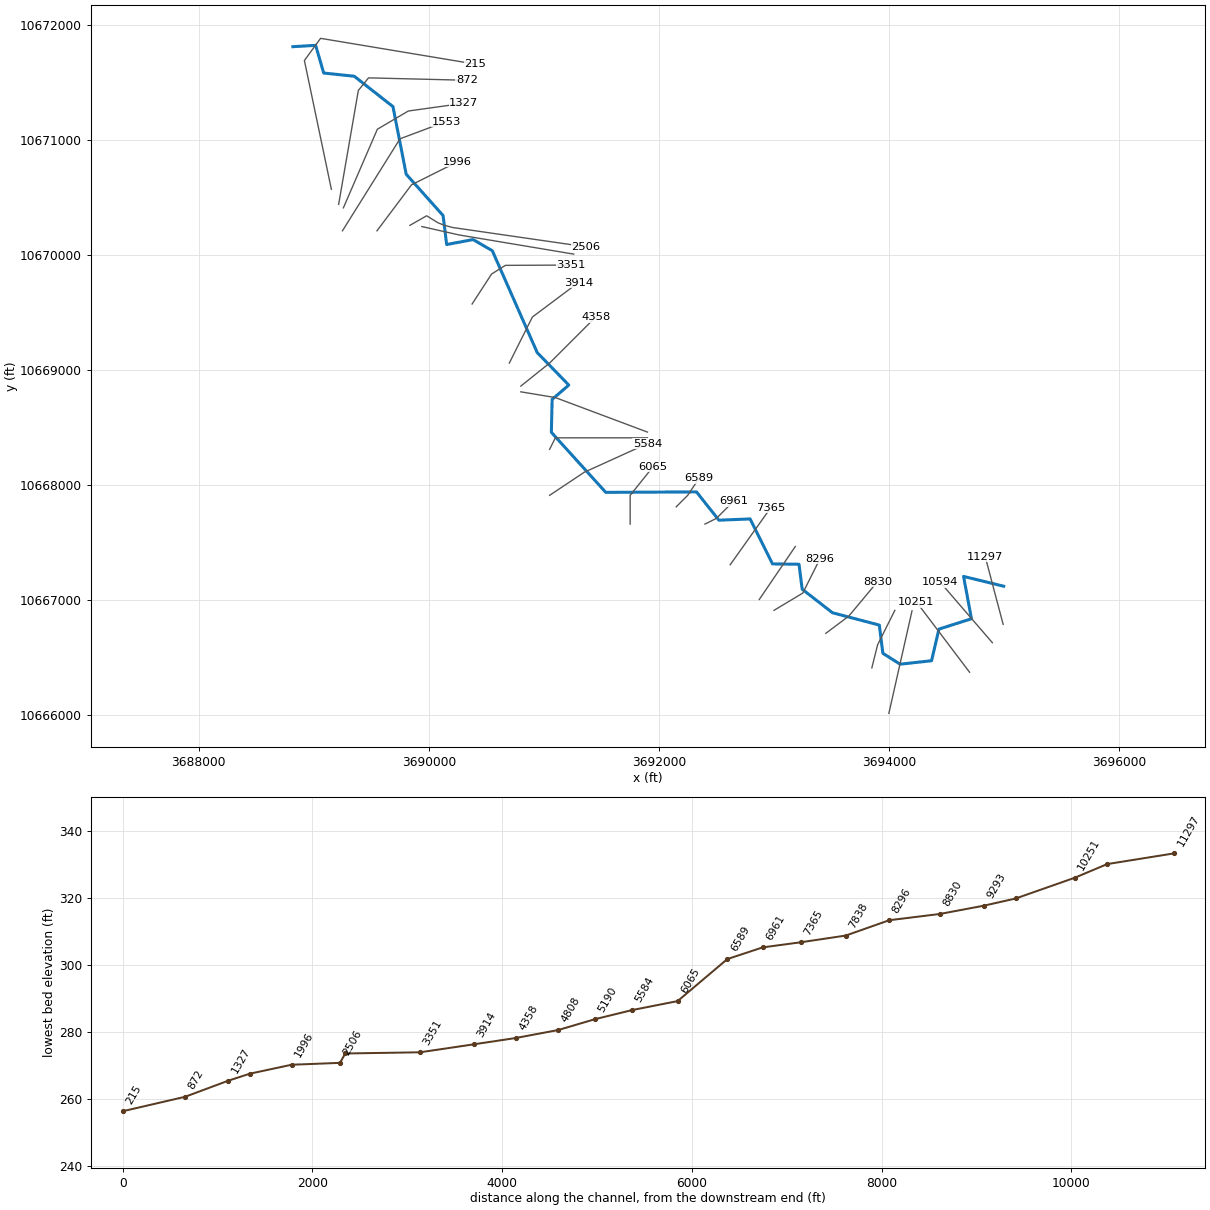
--- UNT 168 IN CACR.prj (project) ---

Proj Title=UNT 168 IN CACR Base Level Engineering
Current Plan=p01
Default Exp/Contr=0.3,0.1
English Units
Geom File=g01
Flow File=f01
Plan File=p01
Y Axis Title=Elevation
X Axis Title(PF)=Main Channel Distance
X Axis Title(XS)=Station
BEGIN DESCRIPTION:
UNT 168 IN CACR
END DESCRIPTION:
DSS Export Rating Curves= 0
DSS Export Rating Curve Sorted= 0
DSS Export Volume Flow Curves= 0
DXF OffsetX= 0
DXF OffsetY= 0
DXF ScaleX= 1
DXF ScaleY= 10

--- UNT 168 IN CACR.p01 (plan) ---

Plan Title=Multiple Run
Short Identifier=Multiple
Geom File=g01
Flow File=f01
Subcritical Flow
K Sum by GR= 0
Std Step Tol= 0.01
Critical Tol= 0.01
Num of Std Step Trials= 20
Max Error Tol= 0.3
Flow Tol Ratio= 0.001
Split Flow NTrial= 30
Split Flow Tol= 0.02
Split Flow Ratio= 0.02
Log Output Level= 0
Friction Slope Method= 1
Unsteady Friction Slope Method= 2
Unsteady Bridges Friction Slope Method= 1
Parabolic Critical Depth
Global Vel Dist=  1 , 1 , 1
Global Log Level= 0
CheckData=True
Encroach Param= -1, 0, 0, 0
BEGIN DESCRIPTION:
Multiple Run
END DESCRIPTION:

--- UNT 168 IN CACR.f01 (steady flow) ---

Flow Title=Multiple
Number of Profiles=7
Profile Names=10-year,25-year,50-year,1pct_min,100-year,1pct_plu,500-year
River Rch & RM= UNT 168 IN CACR,Reach-1,11297
     468     623     749     661     895    1210    1282
River Rch & RM= UNT 168 IN CACR,Reach-1,6589
     681     928    1132    1015    1373    1856    2026
River Rch & RM= UNT 168 IN CACR,Reach-1,1996
     720     984    1203    1080    1461    1976    2163
Boundary for River Rch & Prof#=UNT 168 IN CACR,Reach-1,1
Up Type=0
Dn Type=3
Dn Slope=0.005
Boundary for River Rch & Prof#=UNT 168 IN CACR,Reach-1,2
Up Type=0
Dn Type=3
Dn Slope=0.005
Boundary for River Rch & Prof#=UNT 168 IN CACR,Reach-1,3
Up Type=0
Dn Type=3
Dn Slope=0.005
Boundary for River Rch & Prof#=UNT 168 IN CACR,Reach-1,4
Up Type=0
Dn Type=3
Dn Slope=0.005
Boundary for River Rch & Prof#=UNT 168 IN CACR,Reach-1,5
Up Type=0
Dn Type=3
Dn Slope=0.005
Boundary for River Rch & Prof#=UNT 168 IN CACR,Reach-1,6
Up Type=0
Dn Type=3
Dn Slope=0.005
Boundary for River Rch & Prof#=UNT 168 IN CACR,Reach-1,7
Up Type=0
Dn Type=3
Dn Slope=0.005

--- UNT 168 IN CACR.g01 (geometry) ---

Geom Title=Existing Conditions
Program Version=4.10

River Reach=UNT 168 IN CACR ,Reach-1
Reach XY= 30
      3694995.25       10667120.      3694646.75       10667205.
      3694715.25       10666837.      3694432.75       10666747.
       3694368.5       10666472.      3694094.75       10666442.
      3693945.25       10666537.      3693914.75       10666782.
      3693507.75       10666889.      3693244.25       10667094.
      3693216.75       10667311.      3692986.25       10667314.
        3692792.       10667705.        3692521.       10667694.
      3692325.75       10667940.       3691537.5       10667936.
      3691064.75       10668458.      3691071.75       10668744.
      3691216.25       10668869.      3690942.25       10669151.
      3690551.75       10670037.        3690385.       10670134.
        3690155.       10670091.        3690124.       10670343.
       3689803.5       10670702.       3689688.5       10671290.
       3689352.5       10671554.      3689086.75       10671582.
       3689016.5       10671823.        3688819.       10671811.

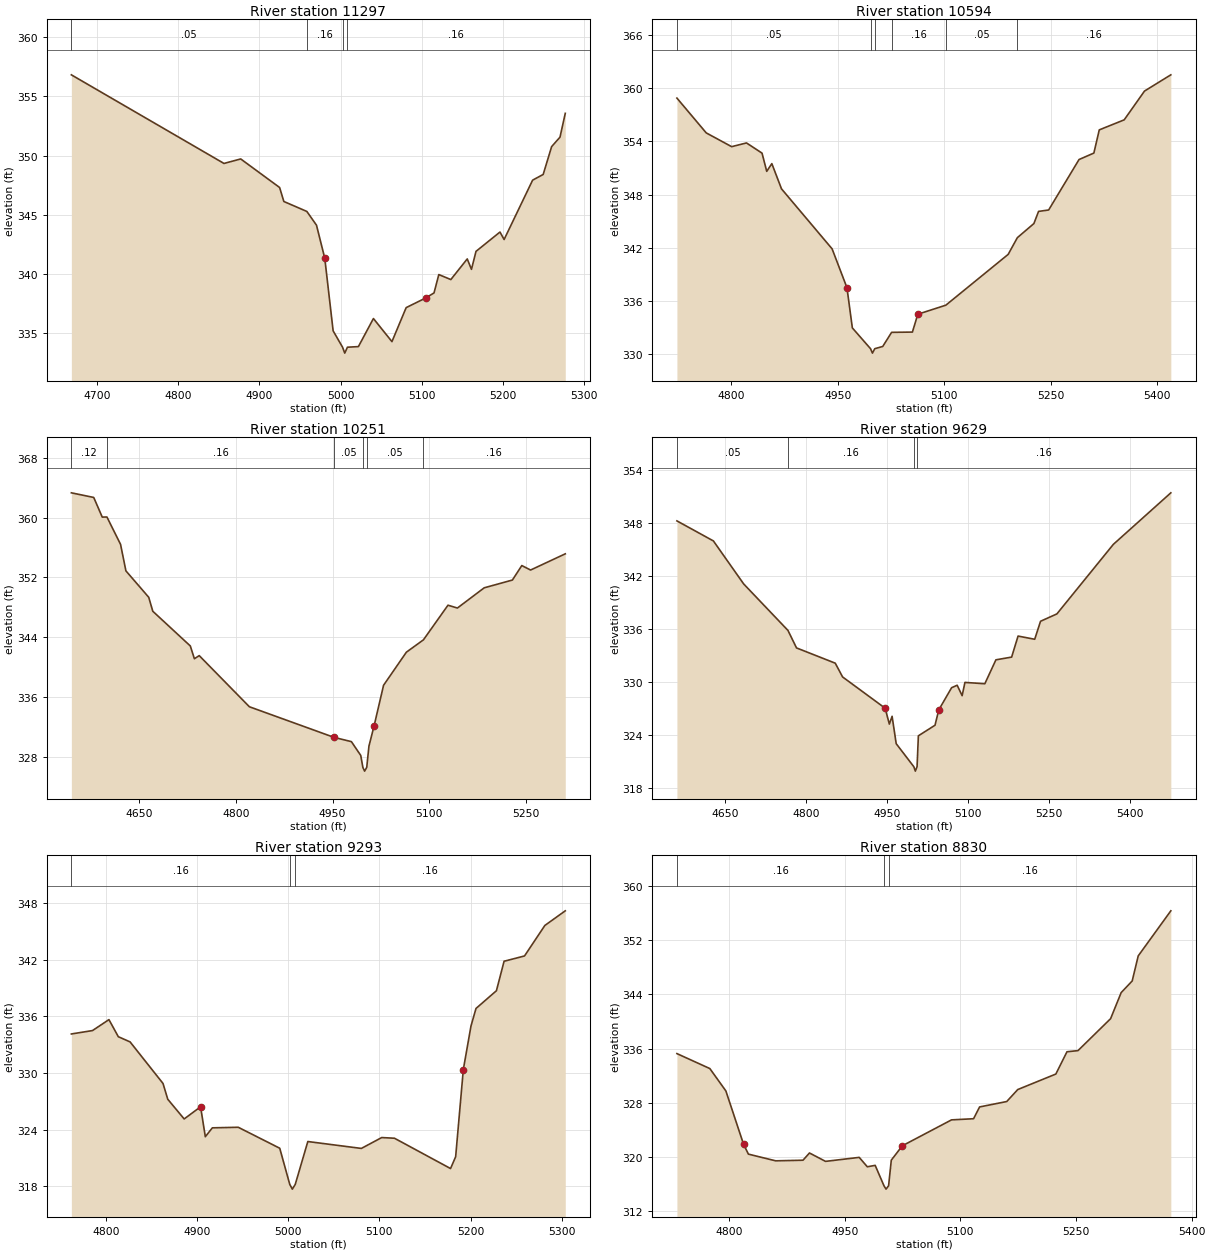
Type RM Length L Ch R = 1 ,11297   ,703,703,703
BEGIN DESCRIPTION:
UNT 168 IN CACR 23.0
END DESCRIPTION:
XS GIS Cut Line= 2
      3694990.56     10666788.58      3694834.96     10667376.44
#Sta/Elev= 30
  4668.5  356.82  4856.4  349.34    4877  349.72  4924.9  347.31  4930.1  346.13
  4958.4  345.29  4970.3  344.13  4980.5  341.34  4990.8  335.21  5002.4  333.83
  5005.1  333.33  5008.4  333.83  5021.9  333.88  5040.4  336.25  5063.2   334.3
  5080.7  337.17  5104.6  337.98    5115  338.41  5120.9  339.96  5135.7  339.54
  5155.9  341.28  5161.1   340.4  5166.7  341.92  5196.2  343.55  5201.3  342.92
  5236.4  347.93  5249.4  348.41  5259.8  350.76  5270.1  351.56  5276.6  353.57
#Mann= 4 ,-1 , 0
  4668.5     .05       0  4958.4     .16       0  5002.4     .07       0
  5008.4     .16       0
Bank Sta=4980.5,5104.6
XS Rating Curve= 0 ,0
Exp/Cntr=0.3,0.1

Type RM Length L Ch R = 1 ,10594   ,343,343,343
BEGIN DESCRIPTION:
UNT 168 IN CACR 22.0
END DESCRIPTION:
XS GIS Cut Line= 2
      3694896.78     10666628.93       3694442.6     10667155.92
#Sta/Elev= 30
  4723.2  358.86  4764.5  354.94  4800.3  353.39  4821.2  353.81  4843.1  352.66
  4849.7  350.61  4856.9  351.48  4870.5  348.64  4941.8  341.88  4962.7  337.51
  4970.3  332.98  4995.9  330.64  4998.6  330.14  5001.9  330.64  5013.1  330.89
  5025.6  332.48  5054.9  332.51  5062.5  334.52    5102  335.54  5189.8  341.26
  5202.7  343.14    5226  344.73  5232.6   346.1  5246.8  346.26  5289.6  351.94
  5310.5  352.67  5318.1  355.28  5353.2  356.41  5381.8  359.65  5418.9  361.48
#Mann= 6 ,-1 , 0
  4723.2     .05       0  4995.9     .03       0  5001.9     .05       0
  5025.6     .16       0    5102     .05       0  5202.7     .16       0
Bank Sta=4962.7,5062.5
XS Rating Curve= 0 ,0
Exp/Cntr=0.3,0.1

Type RM Length L Ch R = 1 ,10251   ,622,622,622
BEGIN DESCRIPTION:
UNT 168 IN CACR 21.0
END DESCRIPTION:
XS GIS Cut Line= 2
      3694698.88     10666371.97      3694237.06      10666983.1
#Sta/Elev= 30
  4544.9  363.32  4579.6   362.7  4592.8  360.07  4600.1  360.08  4621.2  356.42
  4629.5  352.87  4664.9  349.33  4671.2  347.46  4729.4  342.81  4735.7   341.1
  4743.2  341.52    4821  334.67  4952.3  330.57  4979.2     330  4993.7  328.15
    4997  326.55  4999.7  326.05    5003  326.55  5006.4  329.39  5014.5  332.15
  5029.1  337.55  5064.5  341.98  5090.9  343.63    5129  348.27  5143.6  347.89
  5185.2   350.6  5228.9  351.64  5243.5  353.58  5257.1  352.98  5310.9  355.15
#Mann= 6 ,-1 , 0
  4544.9     .12       0  4600.1     .16       0  4952.3     .05       0
    4997     .03       0    5003     .05       0  5090.9     .16       0
Bank Sta=4952.3,5014.5
XS Rating Curve= 0 ,0
Exp/Cntr=0.3,0.1

Type RM Length L Ch R = 1 ,9629    ,336,336,336
BEGIN DESCRIPTION:
UNT 168 IN CACR 20.0
END DESCRIPTION:
XS GIS Cut Line= 2
       3693997.5     10666014.33      3694198.71     10666905.91
#Sta/Elev= 30
  4561.1  348.21  4628.6  345.94  4684.6  341.07  4766.6   335.8  4782.4  333.82
  4854.1  332.09  4867.7  330.53  4946.4  326.99  4954.2  325.19  4959.3  326.07
  4966.9  322.97  4999.5  320.36  5002.3  319.86  5005.5  320.36  5007.9  323.86
  5038.7  325.06  5045.7   326.8  5069.4  329.31  5079.7  329.59  5088.9  328.41
  5094.1  329.91  5130.9  329.76  5151.4  332.47  5180.5  332.78  5192.4  335.16
  5223.2   334.8    5234  336.84  5264.2  337.67  5368.7  345.55  5475.1  351.39
#Mann= 4 ,-1 , 0
  4561.1     .05       0  4766.6     .16       0  4999.5     .07       0
  5005.5     .16       0
Bank Sta=4946.4,5045.7
XS Rating Curve= 0 ,0
Exp/Cntr=0.3,0.1

Type RM Length L Ch R = 1 ,9293    ,463,463,463
BEGIN DESCRIPTION:
UNT 168 IN CACR 19.0
END DESCRIPTION:
XS GIS Cut Line= 3
      3693849.61     10666410.18      3693899.61     10666610.19
      3694049.62     10666910.21
#Sta/Elev= 30
  4762.3  334.14  4785.5   334.5  4803.5  335.66  4813.8  333.85  4826.7   333.3
  4862.8   328.9    4868  327.23    4886  325.14    4904  326.43  4909.2  323.26
  4916.9   324.2  4945.3  324.26  4990.8  322.04  5001.8  318.21  5004.6  317.71
  5007.8  318.21  5021.6  322.75  5080.3  322.02  5102.6  323.17  5116.6   323.1
  5178.1  319.89  5183.7  321.14  5192.1  330.37  5200.5  334.98    5206  336.84
  5228.4  338.72  5236.8  341.84  5259.2   342.4  5281.5  345.63  5303.9  347.18
#Mann= 3 ,-1 , 0
  4762.3     .16       0  5001.8     .07       0  5007.8     .16       0
Bank Sta=4904,5192.1
XS Rating Curve= 0 ,0
Exp/Cntr=0.3,0.1

Type RM Length L Ch R = 1 ,8830    ,534,534,534
BEGIN DESCRIPTION:
UNT 168 IN CACR 18.0
END DESCRIPTION:
XS GIS Cut Line= 3
      3693449.63      10666710.2      3693649.61     10666860.19
      3693899.61     10667160.19
#Sta/Elev= 30
  4732.5  335.26  4775.2  333.05    4796  329.74  4818.9  321.87  4825.2  320.41
  4860.6  319.42    4896  319.51  4904.4  320.58  4925.2  319.34  4968.9  319.93
  4979.4  318.54  4989.6  318.75    5001  315.74  5003.7  315.24    5007  315.74
  5010.5  319.52  5024.8  321.64  5088.6  325.47  5117.2  325.64    5125  327.38
  5160.2  328.18  5174.5  329.95  5223.9  332.24  5238.3  335.53  5252.6   335.7
  5294.9  340.42  5308.6  344.27  5322.9  345.99  5330.7  349.69    5373  356.35
#Mann= 3 ,-1 , 0
  4732.5     .16       0    5001     .07       0    5007     .16       0
Bank Sta=4818.9,5024.8
XS Rating Curve= 0 ,0
Exp/Cntr=0.3,0.1

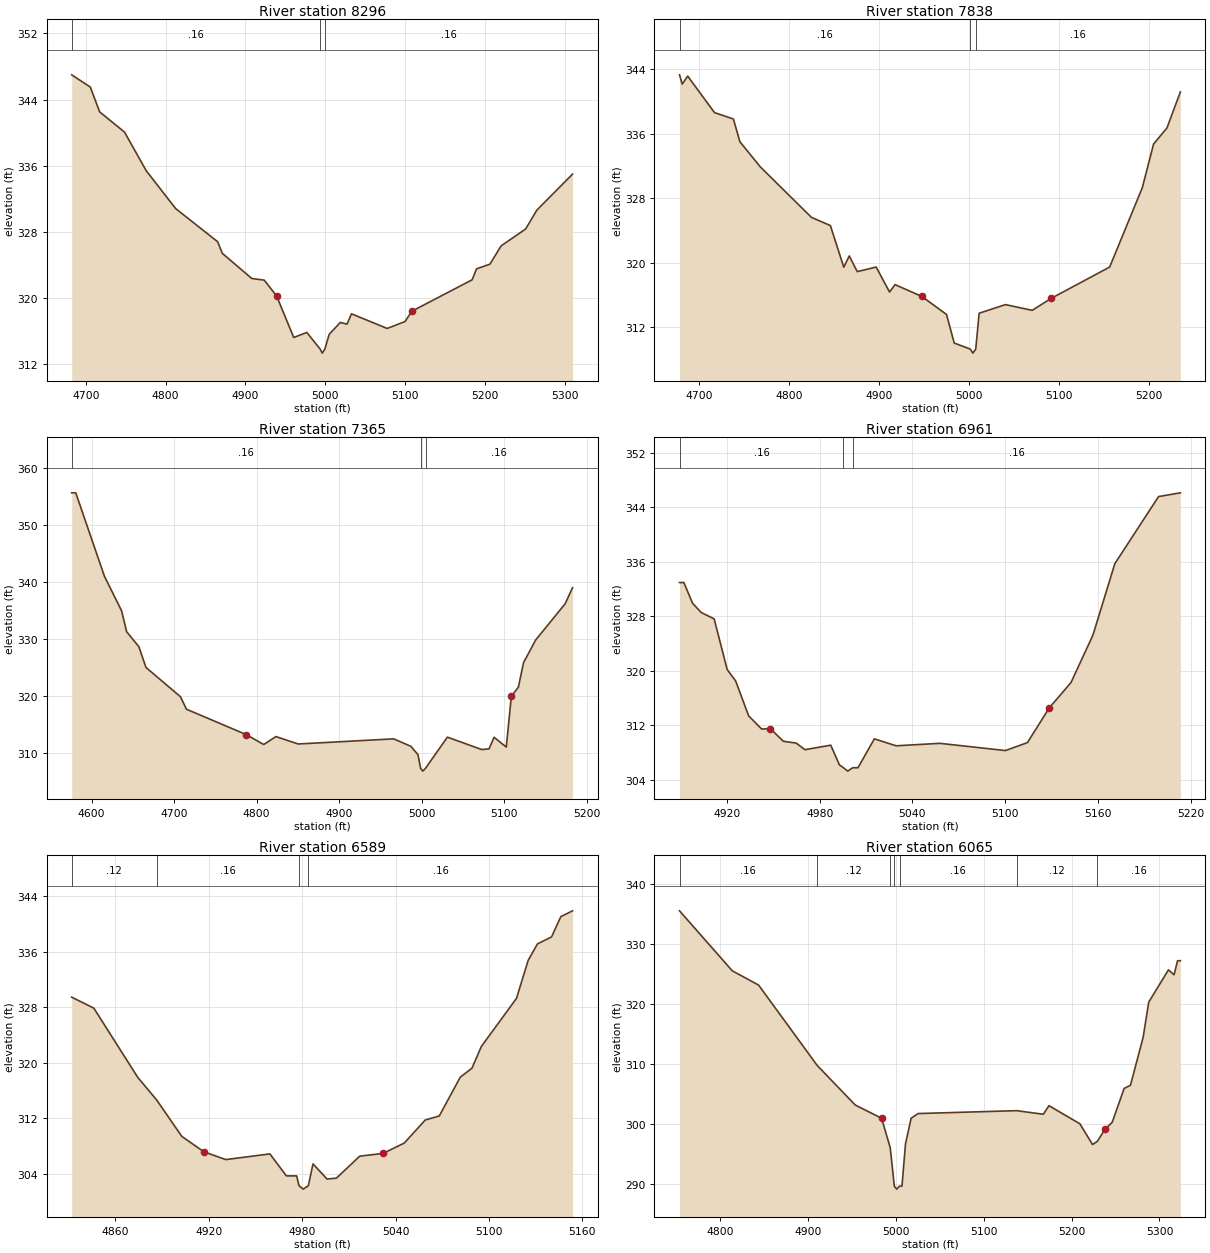
Type RM Length L Ch R = 1 ,8296    ,458,458,458
BEGIN DESCRIPTION:
UNT 168 IN CACR 17.0
END DESCRIPTION:
XS GIS Cut Line= 3
      3692999.63      10666910.2      3693249.61     10667060.19
      3693399.59     10667360.16
#Sta/Elev= 30
  4682.5     347  4705.8  345.52  4717.5  342.52  4748.6  340.08  4775.8  335.41
  4812.7  330.83  4865.2  326.83    4871  325.43  4907.9  322.39  4923.5  322.19
    4939  320.27  4960.4  315.26  4976.8  315.87  4993.4  313.87  4996.1  313.37
  4999.4  313.87  5004.8  315.64  5018.7  317.08  5027.1  316.87  5032.7  318.12
  5077.4  316.35  5099.8  317.19  5108.2  318.43  5183.7  322.23  5189.2  323.55
    5206  324.12    5220  326.33  5250.7  328.37  5264.7  330.65  5309.4     335
#Mann= 3 ,-1 , 0
  4682.5     .16       0  4993.4     .07       0  4999.4     .16       0
Bank Sta=4939,5108.2
XS Rating Curve= 0 ,0
Exp/Cntr=0.3,0.1

Type RM Length L Ch R = 1 ,7838    ,473,473,473
BEGIN DESCRIPTION:
UNT 168 IN CACR 16.0
END DESCRIPTION:
XS GIS Cut Line= 2
      3692871.54     10667004.72      3693184.56      10667465.2
#Sta/Elev= 30
  4678.4  343.32  4681.4  342.17  4687.5  343.16  4717.3  338.63  4738.3  337.84
  4745.5  335.02  4768.2   331.9  4825.1  325.63  4846.1  324.62    4861  319.45
  4867.1  320.85    4876   318.9    4897  319.47  4911.9  316.37    4918  317.29
  4947.8  315.82  4975.2  313.59  4983.8  310.04  5001.7  309.29  5004.5  308.79
  5007.7  309.29  5011.5  313.74  5040.7  314.81  5070.5   314.1  5091.5  315.58
  5156.6  319.47  5192.9  329.32  5205.4  334.73  5220.3  336.73  5235.2   341.2
#Mann= 3 ,-1 , 0
  4678.4     .16       0  5001.7     .07       0  5007.7     .16       0
Bank Sta=4947.8,5091.5
XS Rating Curve= 0 ,0
Exp/Cntr=0.3,0.1

Type RM Length L Ch R = 1 ,7365    ,404,404,404
BEGIN DESCRIPTION:
UNT 168 IN CACR 15.0
END DESCRIPTION:
XS GIS Cut Line= 2
      3692618.92     10667306.79       3692970.5      10667801.6
#Sta/Elev= 30
    4576  355.61  4580.9  355.61  4615.6     341  4636.5   334.9  4642.6  331.24
  4657.4  328.62    4666  324.98  4707.8  319.84  4715.1  317.65  4787.8  313.18
  4808.7  311.46  4823.5  312.85  4850.5  311.55  4966.1  312.45    4987  311.15
  4995.7  309.67  4998.8  307.29  5001.5  306.79  5004.8  307.29  5031.3  312.75
  5073.1  310.57  5081.8   310.7  5087.9  312.73  5102.7  311.01  5108.8  319.89
  5117.4  321.54  5123.6  325.82  5138.3  329.79    5174  336.14    5183  338.96
#Mann= 3 ,-1 , 0
    4576     .16       0  4998.8     .07       0  5004.8     .16       0
Bank Sta=4787.8,5108.8
XS Rating Curve= 0 ,0
Exp/Cntr=0.3,0.1

Type RM Length L Ch R = 1 ,6961    ,372,372,372
BEGIN DESCRIPTION:
UNT 168 IN CACR 14.0
END DESCRIPTION:
XS GIS Cut Line= 3
       3692399.6     10667660.18      3692499.61     10667710.19
      3692649.58     10667860.15
#Sta/Elev= 30
  4889.4  332.95  4892.2  332.95  4897.8  329.91  4903.4  328.55  4911.8  327.61
  4920.2  320.18  4925.7  318.49  4934.1  313.37  4942.5  311.43  4948.1   311.5
  4956.5  309.64  4964.9  309.36  4970.5   308.4  4987.2  309.06  4992.8  306.17
  4995.4  305.75  4998.2  305.25  5001.4  305.75  5004.8  305.75  5015.4  309.99
  5029.5  308.97  5057.8  309.33  5100.2  308.27  5114.4  309.44  5128.5  314.53
  5142.6  318.27  5156.8  325.25  5170.9  335.71  5199.2  345.57  5213.3  346.12
#Mann= 3 ,-1 , 0
  4889.4     .16       0  4995.4     .07       0  5001.4     .16       0
Bank Sta=4948.1,5128.5
XS Rating Curve= 0 ,0
Exp/Cntr=0.3,0.1

Type RM Length L Ch R = 1 ,6589    ,524,524,524
BEGIN DESCRIPTION:
UNT 168 IN CACR 13.0
END DESCRIPTION:
XS GIS Cut Line= 3
      3692149.58     10667810.16      3692249.61     10667910.19
      3692349.59     10668060.16
#Sta/Elev= 30
    4832  329.44  4846.2  327.86  4874.5  317.85  4886.6  314.61  4902.7  309.37
  4916.9  307.14    4931  306.02  4959.3  306.84  4969.9  303.67  4976.5  303.67
    4978  302.26  4980.7  301.76    4984  302.26    4987   305.4    4996  303.22
    5002  303.34    5017  306.51    5032  306.91  5045.6   308.4  5059.1  311.73
  5068.1  312.31  5081.6  317.91  5089.1   319.2  5095.1  322.32  5117.7  329.27
  5125.2  334.75  5131.2  337.13  5140.2  338.12  5146.2  341.06  5153.7  341.89
#Mann= 4 ,-1 , 0
    4832     .12       0  4886.6     .16       0    4978     .07       0
    4984     .16       0
Bank Sta=4916.9,5032
XS Rating Curve= 0 ,0
Exp/Cntr=0.3,0.1

Type RM Length L Ch R = 1 ,6065    ,481,481,481
BEGIN DESCRIPTION:
UNT 168 IN CACR 12.0
END DESCRIPTION:
XS GIS Cut Line= 3
      3691749.61      10667660.2      3691749.61     10667910.19
      3691949.58     10668160.16
#Sta/Elev= 30
  4753.7   335.5  4813.7  325.53  4843.7  323.15  4910.3   309.8  4953.7   303.2
  4983.7     301  4993.5  296.13  4998.2  289.71  5000.9  289.21  5004.2  289.71
  5006.9  289.71  5010.9  296.72  5017.3     301  5025.3  301.78  5137.5  302.26
  5167.8  301.66  5174.2  303.09  5209.4  300.08  5223.8  296.63  5229.2  297.14
  5238.2   299.2  5246.2  300.32  5259.8  305.96    5267  306.49  5281.4  314.45
  5287.8  320.31  5310.2  325.68  5316.6  324.86  5320.6   327.2  5323.8   327.2
#Mann= 7 ,-1 , 0
  4753.7     .16       0  4910.3     .12       0  4993.5     .16       0
  4998.2     .07       0  5004.2     .16       0  5137.5     .12       0
  5229.2     .16       0
Bank Sta=4983.7,5238.2
XS Rating Curve= 0 ,0
Exp/Cntr=0.3,0.1

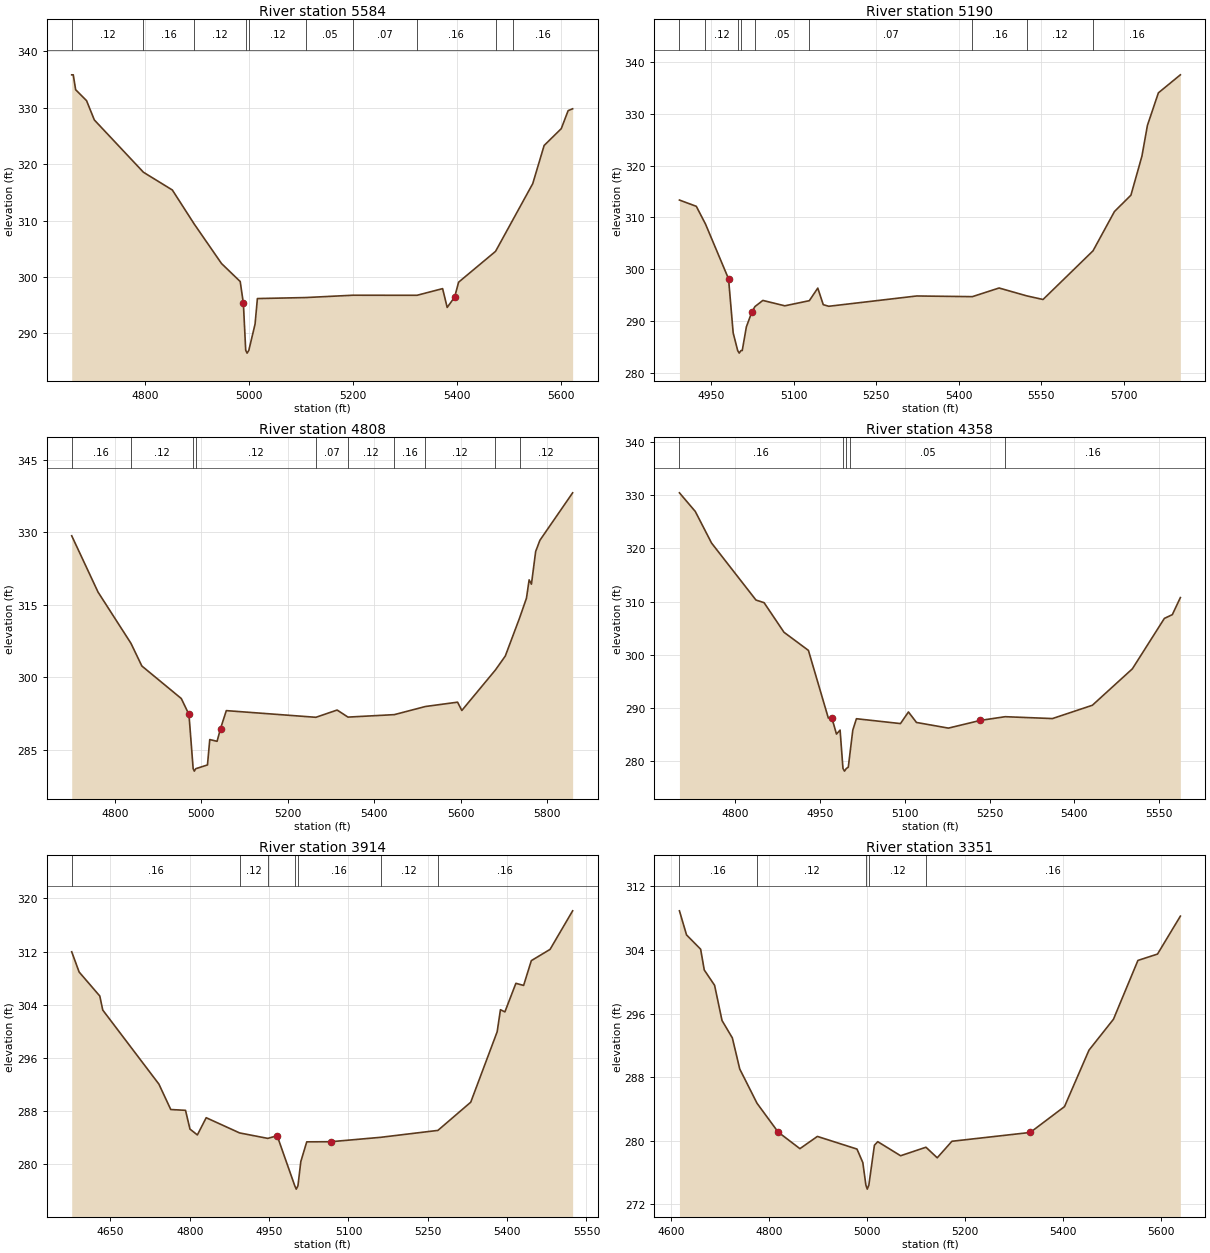
Type RM Length L Ch R = 1 ,5584    ,394,394,394
BEGIN DESCRIPTION:
UNT 168 IN CACR 11.0
END DESCRIPTION:
XS GIS Cut Line= 3
      3691049.57     10667910.17      3691349.61     10668110.19
      3691899.56     10668360.17
#Sta/Elev= 30
  4658.2  335.84  4661.2  335.84  4665.8   333.2  4686.8  331.26  4701.8  327.84
  4796.4  318.57    4852  315.43  4894.2  309.39  4946.7   302.4  4982.7  299.21
  4988.8  295.35  4993.3  287.02    4996  286.52  4999.3  287.02  5011.3  291.66
  5015.8  296.19  5109.6  296.37  5199.6  296.78  5323.2  296.77  5372.5  297.95
  5381.3  294.62  5395.6  296.44  5403.3  299.09  5474.5  304.56    5508  310.18
  5546.1  316.56    5568  323.32    5601   326.3  5614.2  329.49  5622.9  329.82
#Mann= 10 ,-1 , 0
  4658.2     .12       0  4796.4     .16       0  4894.2     .12       0
  4993.3     .07       0  4999.3     .12       0  5109.6     .05       0
  5199.6     .07       0  5323.2     .16       0  5474.5     .12       0
    5508     .16       0
Bank Sta=4988.8,5395.6
XS Rating Curve= 0 ,0
Exp/Cntr=0.3,0.1

Type RM Length L Ch R = 1 ,5190    ,382,382,382
BEGIN DESCRIPTION:
UNT 168 IN CACR 10.0
END DESCRIPTION:
XS GIS Cut Line= 3
      3691049.61     10668310.19      3691099.61     10668410.19
      3691899.61     10668410.19
#Sta/Elev= 30
  4891.7  313.35  4922.4  312.14  4939.1  308.72  4981.1  298.13  4989.5  287.69
  4997.7  284.28  5000.5  283.78  5003.7  284.28    5006  284.28  5013.5  288.84
  5023.5  291.74  5029.1  292.77  5043.5  293.96  5083.5  292.92  5128.1  293.91
  5143.5  296.34  5153.5  293.14  5163.5  292.83  5323.5  294.82  5424.9  294.69
  5473.5  296.36  5523.9  294.84  5553.5  294.14  5644.5  303.54  5683.5  311.13
  5713.5  314.29  5733.5  321.82  5743.5  327.76  5763.5  334.06  5803.5  337.54
#Mann= 9 ,-1 , 0
  4891.7     .16       0  4939.1     .12       0  4997.7     .07       0
  5003.7     .12       0  5029.1     .05       0  5128.1     .07       0
  5424.9     .16       0  5523.9     .12       0  5644.5     .16       0
Bank Sta=4981.1,5023.5
XS Rating Curve= 0 ,0
Exp/Cntr=0.3,0.1

Type RM Length L Ch R = 1 ,4808    ,450,450,450
BEGIN DESCRIPTION:
UNT 168 IN CACR 9.0
END DESCRIPTION:
XS GIS Cut Line= 3
      3690799.57     10668810.19      3691099.61     10668760.19
      3691899.63     10668460.18
#Sta/Elev= 30
  4700.6  329.28  4761.5  317.63  4837.5  307.05  4862.8  302.34  4954.1   295.6
  4971.8   292.3  4981.5  281.08  4984.2  280.58  4987.5  281.08  5014.6  281.86
  5019.9  287.11  5036.8  286.75  5044.8  289.39  5058.2   293.1  5265.4  291.72
  5314.5  293.22  5339.6  291.76  5446.8  292.27  5518.5  293.95  5593.1  294.85
  5602.9  293.13  5680.5   301.5  5703.4  304.39  5736.4  312.25  5752.4  316.37
  5758.6  320.16  5763.9  319.27  5773.7  326.04  5783.5  328.35  5859.2  338.17
#Mann= 10 ,-1 , 0
  4700.6     .16       0  4837.5     .12       0  4981.5     .07       0
  4987.5     .12       0  5265.4     .07       0  5339.6     .12       0
  5446.8     .16       0  5518.5     .12       0  5680.5     .16       0
  5736.4     .12       0
Bank Sta=4971.8,5044.8
XS Rating Curve= 0 ,0
Exp/Cntr=0.3,0.1

Type RM Length L Ch R = 1 ,4358    ,444,444,444
BEGIN DESCRIPTION:
UNT 168 IN CACR 8.0
END DESCRIPTION:
XS GIS Cut Line= 3
       3690799.6     10668860.18      3691049.61     10669060.19
      3691449.64     10669460.22
#Sta/Elev= 30
  4701.5  330.39  4729.5   326.9  4758.3  320.97  4836.8  310.28  4851.2  309.78
  4886.4  304.23  4929.6  300.83  4964.8  288.14  4971.2  288.12  4979.2  285.13
  4985.6  285.88  4990.7  278.68  4993.4  278.18  4996.7  278.68  5000.1  278.92
  5003.6  281.97  5008.1  285.88  5014.5  288.01  5092.4   287.1  5106.5  289.28
  5120.7  287.31  5177.2  286.25  5233.8   287.7  5277.6  288.39  5361.1  288.04
  5431.8  290.54  5502.5  297.37  5559.1  306.83  5573.2  307.54  5587.4  310.74
#Mann= 5 ,-1 , 0
  4701.5     .16       0  4990.7     .07       0  4996.7     .16       0
  5003.6     .05       0  5277.6     .16       0
Bank Sta=4971.2,5233.8
XS Rating Curve= 0 ,0
Exp/Cntr=0.3,0.1

Type RM Length L Ch R = 1 ,3914    ,563,563,563
BEGIN DESCRIPTION:
UNT 168 IN CACR 7.0
END DESCRIPTION:
XS GIS Cut Line= 3
      3690699.61      10669060.2      3690899.61     10669460.19
       3691299.6     10669760.18
#Sta/Elev= 30
  4576.7  311.98  4590.7  308.94  4629.8  305.33  4635.4  303.22  4741.6  292.08
    4764  288.26  4791.9  288.14  4800.3  285.32  4814.3  284.44    4831  287.03
  4894.2  284.74  4947.5  283.92  4965.2  284.32  4998.5  276.79  5001.3  276.29
  5004.5  276.79  5009.9  280.43  5021.1   283.4  5066.6  283.42  5160.7  284.08
  5269.1  285.12  5331.2  289.36  5381.2  299.95  5387.4  303.27  5395.8  302.94
  5416.6  307.24  5431.2  306.92  5445.8  310.65  5481.2  312.34  5523.9  318.14
#Mann= 7 ,-1 , 0
  4576.7     .16       0  4894.2     .12       0  4947.5     .16       0
  4998.5     .07       0  5004.5     .16       0  5160.7     .12       0
  5269.1     .16       0
Bank Sta=4965.2,5066.6
XS Rating Curve= 0 ,0
Exp/Cntr=0.3,0.1

Type RM Length L Ch R = 1 ,3351    ,790,790,790
BEGIN DESCRIPTION:
UNT 168 IN CACR 6.0
END DESCRIPTION:
XS GIS Cut Line= 4
      3690376.17     10669573.88      3690545.43     10669834.28
      3690665.22      10669909.8      3691236.33     10669912.39
#Sta/Elev= 30
  4617.1  308.93  4631.6   305.9  4660.4   304.1  4667.8  301.49  4688.9  299.56
  4704.1  295.13  4725.2  292.94  4740.3  289.03  4775.6  284.72  4818.7   281.1
  4863.2  279.01  4898.9  280.55  4979.8  278.96  4991.7  277.26    4998  274.42
  5000.8  273.92    5004  274.42  5015.4  279.44  5022.2  279.89  5068.9  278.12
  5120.7  279.19  5143.7  277.86  5173.7  279.94  5333.7  281.05  5403.7   284.3
  5453.7   291.4  5503.7  295.29  5553.7  302.69  5593.7  303.49  5640.4  308.26
#Mann= 5 ,-1 , 0
  4617.1     .16       0  4775.6     .12       0    4998     .07       0
    5004     .12       0  5120.7     .16       0
Bank Sta=4818.7,5333.7
XS Rating Curve= 0 ,0
Exp/Cntr=0.3,0.1

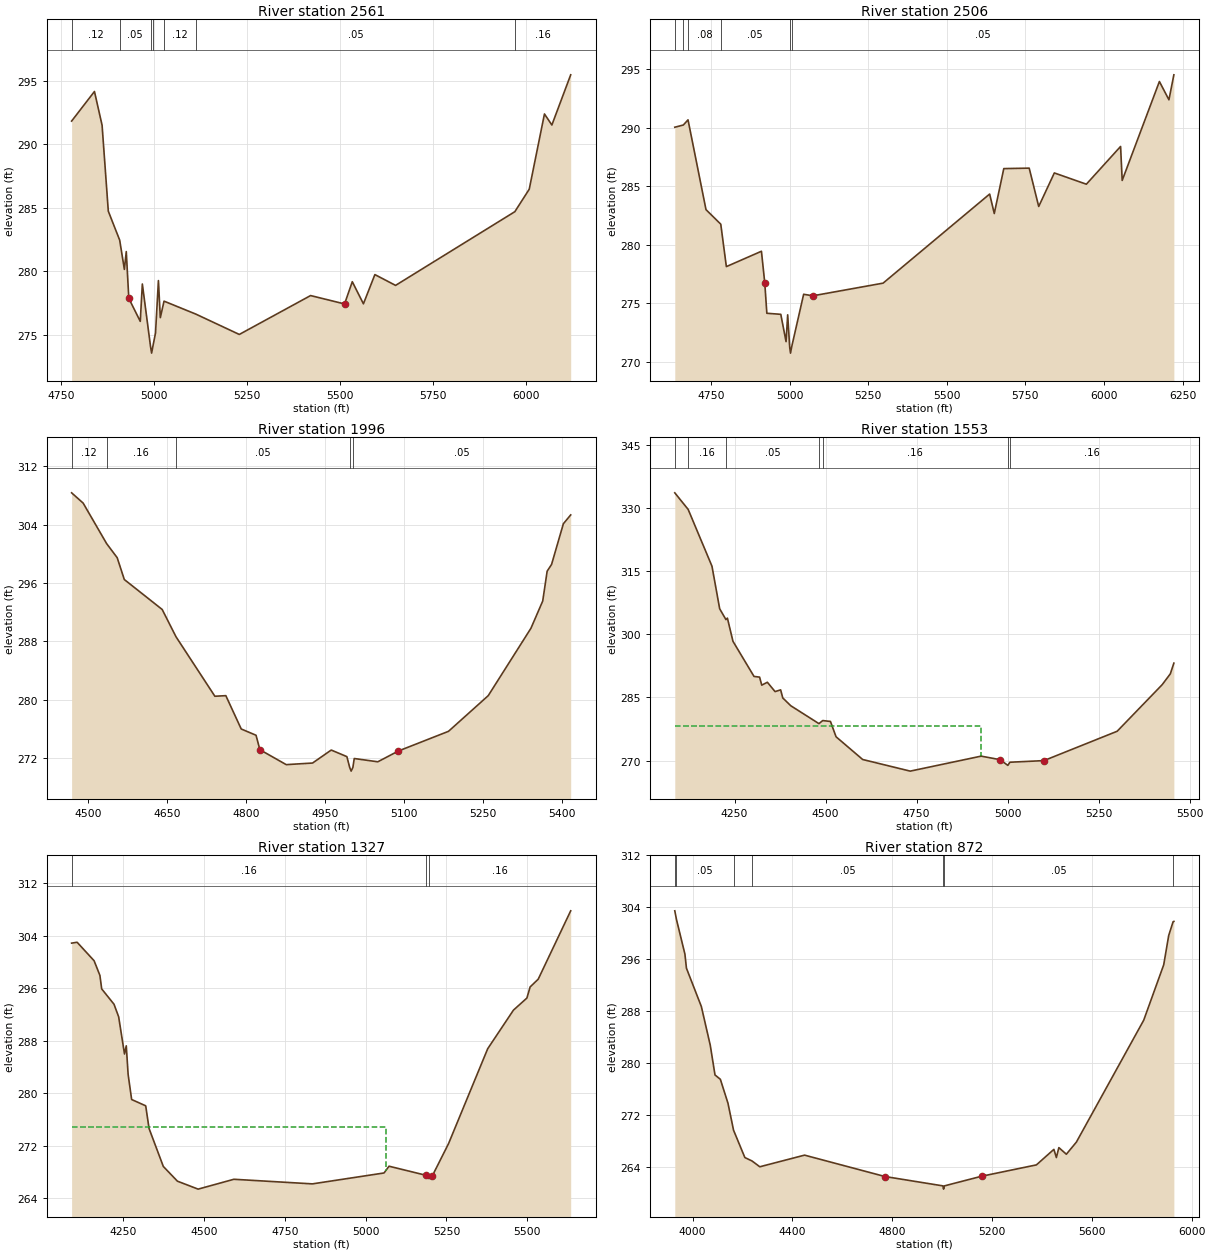
Type RM Length L Ch R = 1 ,2561    ,55,55,55
BEGIN DESCRIPTION:
UNT 168 IN CACR 5.0
END DESCRIPTION:
XS GIS Cut Line= 3
      3689939.68     10670247.18      3690262.59     10670174.27
      3691259.11      10670007.6
#Sta/Elev= 30
  4778.9  291.82  4840.3  294.15  4860.8  291.49  4877.5  284.73  4908.1  282.45
  4920.7  280.15  4925.8  281.55  4932.6  277.87  4963.4  276.06    4969     279
  4991.1  274.06  4993.9  273.56  4997.1  274.06  5004.4  275.15  5012.2  279.27
  5017.3  276.35  5027.3  277.65  5112.8  276.63  5229.6  275.03  5421.2  278.09
  5512.5  277.43  5533.3  279.18  5563.2  277.44    5594  279.74  5649.6  278.89
  5970.2  284.69  6008.9  286.46  6049.8  292.38  6069.7  291.51  6120.3  295.46
#Mann= 7 ,-1 , 0
  4778.9     .12       0  4908.1     .05       0  4991.1     .04       0
  4997.1     .05       0  5027.3     .12       0  5112.8     .05       0
  5970.2     .16       0
Bank Sta=4932.6,5512.5
XS Rating Curve= 0 ,0
Exp/Cntr=0.3,0.1

Type RM Length L Ch R = 1 ,2506    ,510,510,510
BEGIN DESCRIPTION:
UNT 168 IN CACR 4.0
END DESCRIPTION:
XS GIS Cut Line= 6
      3689835.49     10670257.59      3689981.34     10670340.93
       3690079.5     10670280.02      3690134.84     10670258.32
      3690207.54     10670238.79      3691365.16     10670071.34
#Sta/Elev= 30
  4634.6  290.03  4661.9  290.22  4676.7  290.66  4733.9     283  4780.9  281.76
  4798.7  278.14  4910.3  279.45  4920.9  276.75  4927.5  274.16  4971.9  274.07
  4988.6  271.74  4993.8  274.03  5000.2  271.26  5002.9  270.76  5006.2  271.26
  5044.6  275.78    5074  275.65  5297.4  276.73  5636.4  284.33  5651.1  282.67
  5681.4   286.5  5762.2  286.54  5792.5  283.27  5842.2  286.13  5944.1  285.17
    6053  288.39  6058.1  285.49  6176.5  293.93  6206.8  292.37  6222.5   294.5
#Mann= 6 ,-1 , 0
  4634.6     .16       0  4661.9     .12       0  4676.7     .08       0
  4780.9     .05       0  5000.2     .04       0  5006.2     .05       0
Bank Sta=4920.9,5074
XS Rating Curve= 0 ,0
Exp/Cntr=0.3,0.1

Type RM Length L Ch R = 1 ,1996    ,443,443,443
BEGIN DESCRIPTION:
UNT 168 IN CACR 3.0
END DESCRIPTION:
XS GIS Cut Line= 3
      3689549.59     10670210.16      3689849.61     10670610.19
      3690249.57     10670810.17
#Sta/Elev= 30
  4469.2  308.37  4491.1  306.96  4535.6  301.41  4555.7  299.47  4569.2  296.48
  4641.1  292.37  4667.3  288.63  4741.1  280.47  4761.9  280.55  4791.1  275.98
  4819.2  275.12  4826.5  273.14  4876.5  271.09  4926.5  271.31  4961.9  273.09
  4991.6  272.19    4997   270.7  4999.7   270.2    5003   270.7  5005.6  271.93
  5050.3  271.48  5089.4  272.96  5184.5  275.66  5259.9  280.55    5341   289.8
  5363.3  293.53  5371.7  297.62  5380.1  298.55  5402.5  304.13  5416.4  305.34
#Mann= 5 ,-1 , 0
  4469.2     .12       0  4535.6     .16       0  4667.3     .05       0
    4997     .03       0    5003     .05       0
Bank Sta=4826.5,5089.4
XS Rating Curve= 0 ,0
Exp/Cntr=0.3,0.1

Type RM Length L Ch R = 1 ,1553    ,226,226,226
BEGIN DESCRIPTION:
UNT 168 IN CACR 2.0
END DESCRIPTION:
XS GIS Cut Line= 3
      3689249.58     10670210.15      3689749.61     10671010.19
      3690149.57     10671160.17
#Sta/Elev= 30
  4085.9  333.61  4122.7  329.66    4188  316.19  4209.2  306.07  4226.4   303.5
  4230.4  303.85  4245.7  298.34  4303.5     290  4318.8  289.84  4324.7  287.93
  4340.1  288.62  4361.3   286.4  4376.6  286.81  4382.5  284.89  4404.3  283.05
  4481.8  278.79  4492.2  279.52  4513.4  279.31  4528.8  275.67  4601.9  270.27
  4732.5  267.51  4927.3  271.07  4979.2  270.23  5000.5  268.88  5006.3  269.62
  5099.7  270.01  5300.8  276.98  5424.5  288.05  5446.8  290.62  5456.5  293.16
#Mann= 7 ,-1 , 0
  4085.9     .05       0  4122.7     .16       0  4226.4     .05       0
  4481.8     .08       0  4492.2     .16       0  5000.5     .07       0
  5006.3     .16       0
#XS Ineff= 2 , 0
         4926.36  278.25
Permanent Ineff=
       F       F
Bank Sta=4979.2,5099.7
XS Rating Curve= 0 ,0
Exp/Cntr=0.3,0.1

Type RM Length L Ch R = 1 ,1327    ,455,455,455
BEGIN DESCRIPTION:
Mapping XS c3220d0c
END DESCRIPTION:
XS GIS Cut Line= 4
      3689257.74     10670409.83      3689552.87      10671093.4
      3689821.97     10671251.82      3690303.76      10671319.1
#Sta/Elev= 30
  4091.1  302.89  4108.1  303.02  4160.6  300.21  4178.6  297.97  4184.1  295.92
  4222.2  293.58  4236.6  291.66  4254.6     286  4260.1  287.25  4265.8  282.91
  4276.7  279.07  4320.2  278.11  4330.6  274.65  4374.7  268.87  4418.3  266.63
  4482.3  265.42  4592.9  266.92  4835.7  266.22  5057.1  267.88  5072.7  268.91
  5185.9  267.54    5196  267.02  5206.1   267.4  5256.6  272.34  5377.8  286.81
  5457.5  292.69  5498.9  294.52    5509  296.22    5534   297.4  5634.4  307.81
#Mann= 3 ,-1 , 0
  4091.1     .16       0  5185.9     .07       0    5196     .16       0
#XS Ineff= 2 , 0
         5062.61  274.83
Permanent Ineff=
       F       F
Bank Sta=5185.9,5206.1
XS Rating Curve= 0 ,0
Exp/Cntr=0.3,0.1

Type RM Length L Ch R = 1 ,872     ,657,657,657
BEGIN DESCRIPTION:
Mapping XS 179a549e
END DESCRIPTION:
XS GIS Cut Line= 4
       3689216.5     10670440.19      3689387.59     10671430.63
      3689476.13     10671540.01      3690330.34     10671519.17
#Sta/Elev= 30
  3928.4  303.45  3935.2  302.11    3969  296.79  3975.1  294.62  4034.9  288.72
  4070.5  282.78  4089.6  278.19  4111.1  277.52  4141.5  273.85    4164  269.68
  4209.3  265.48  4238.1  264.95  4269.1  264.06  4448.5  265.85  4770.7  262.56
    5003  261.12  5005.7  260.62    5009  261.12  5157.7   262.6  5377.8  264.35
  5447.8  266.74  5457.8  265.48  5467.8  267.01  5497.8  265.99  5537.9  267.85
  5807.9  286.62    5888  295.14    5908  299.65  5925.6  301.77  5928.7  301.82
#Mann= 7 ,-1 , 0
  3928.4     .16       0  3935.2     .05       0    4164     .16       0
  4238.1     .05       0    5003     .03       0    5009     .05       0
  5925.6     .16       0
Bank Sta=4770.7,5157.7
XS Rating Curve= 0 ,0
Exp/Cntr=0.3,0.1

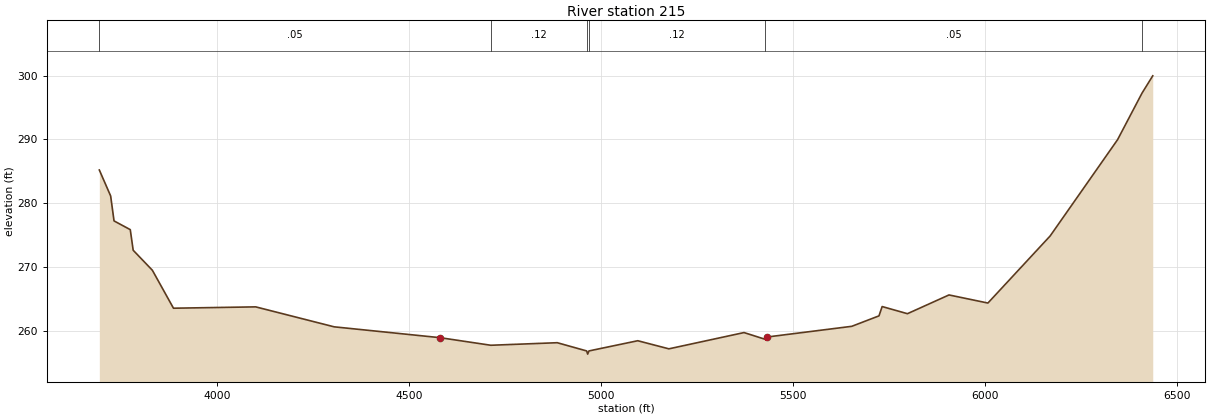
Type RM Length L Ch R = 1 ,215     ,0,0,0
BEGIN DESCRIPTION:
UNT 168 IN CACR 1.0
END DESCRIPTION:
XS GIS Cut Line= 4
       3689153.2     10670571.29      3688918.84     10671691.05
      3689059.46     10671883.76      3690403.24     10671659.79
#Sta/Elev= 30
  3692.2  285.18  3721.7  281.11  3730.5   277.2  3772.8  275.83  3780.4   272.6
  3830.4  269.46  3885.4  263.51  4099.7  263.72  4304.1  260.59  4579.9  258.89
  4712.3   257.7  4885.4   258.1    4962  256.81  4964.7  256.31    4968  256.81
  5095.2  258.41  5176.3  257.14  5372.1  259.69  5427.5  258.63  5432.9     259
  5652.8  260.67  5723.8  262.31    5732  263.77  5797.9  262.65  5906.2  265.59
  6007.6  264.32  6169.8  274.84  6345.4  289.93  6409.1  297.23  6437.1  299.95
#Mann= 6 ,-1 , 0
  3692.2     .05       0  4712.3     .12       0    4962     .07       0
    4968     .12       0  5427.5     .05       0  6409.1     .16       0
Bank Sta=4579.9,5432.9
XS Rating Curve= 0 ,0
Exp/Cntr=0.3,0.1

Chan Stop Cuts=-1
Use User Specified Reach Order=0
Composite Channel Slope=5