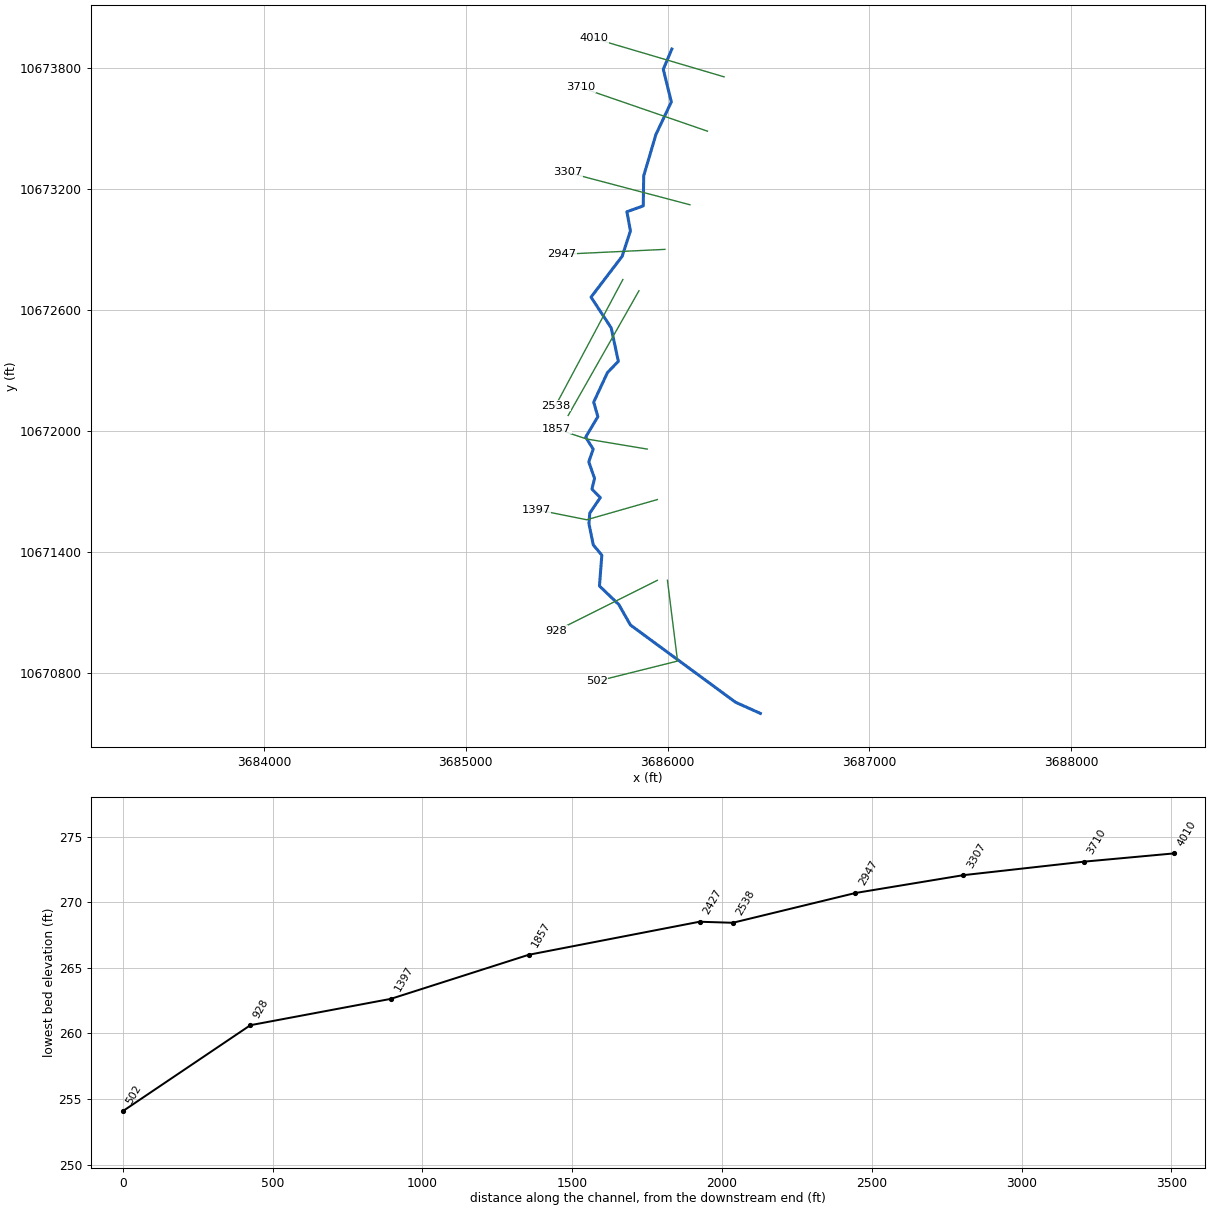
--- UNT 169 IN CACR.prj (project) ---

Proj Title=UNT 169 IN CACR Base Level Engineering
Current Plan=p01
Default Exp/Contr=0.3,0.1
English Units
Geom File=g01
Flow File=f01
Plan File=p01
BEGIN DESCRIPTION:
UNT 169 IN CACR
END DESCRIPTION:

--- UNT 169 IN CACR.p01 (plan) ---

Plan Title=Multiple Run
Short Identifier=Multiple
Geom File=g01
Flow File=f01
Subcritical Flow
K Sum by GR= 0
Std Step Tol= 0.01
Critical Tol= 0.01
Num of Std Step Trials= 20
Max Error Tol= 0.3
Flow Tol Ratio= 0.001
Split Flow NTrial= 30
Split Flow Tol= 0.02
Split Flow Ratio= 0.02
Log Output Level= 0
Friction Slope Method= 1
Unsteady Friction Slope Method= 2
Unsteady Bridges Friction Slope Method= 1
Parabolic Critical Depth
Global Vel Dist=  1 , 1 , 1
Global Log Level= 0
CheckData=True
Encroach Param= -1, 0, 0, 0
BEGIN DESCRIPTION:
Multiple Run
END DESCRIPTION:

--- UNT 169 IN CACR.f01 (steady flow) ---

Flow Title=Multiple
Number of Profiles=7
Profile Names=10-year,25-year,50-year,1pct_min,100-year,1pct_plu,500-year
River Rch & RM= UNT 169 IN CACR,Reach-1,4010
     469     626     754     667     902    1221    1298
Boundary for River Rch & Prof#=UNT 169 IN CACR,Reach-1,1
Up Type=0
Dn Type=3
Dn Slope=0.005
Boundary for River Rch & Prof#=UNT 169 IN CACR,Reach-1,2
Up Type=0
Dn Type=3
Dn Slope=0.005
Boundary for River Rch & Prof#=UNT 169 IN CACR,Reach-1,3
Up Type=0
Dn Type=3
Dn Slope=0.005
Boundary for River Rch & Prof#=UNT 169 IN CACR,Reach-1,4
Up Type=0
Dn Type=3
Dn Slope=0.005
Boundary for River Rch & Prof#=UNT 169 IN CACR,Reach-1,5
Up Type=0
Dn Type=3
Dn Slope=0.005
Boundary for River Rch & Prof#=UNT 169 IN CACR,Reach-1,6
Up Type=0
Dn Type=3
Dn Slope=0.005
Boundary for River Rch & Prof#=UNT 169 IN CACR,Reach-1,7
Up Type=0
Dn Type=3
Dn Slope=0.005

--- UNT 169 IN CACR.g01 (geometry) ---

Geom Title=Existing Conditions

River Reach=UNT 169 IN CACR,Reach-1
Reach XY= 30
      3686021.38     10673892.01      3685979.00     10673792.00
      3686018.75     10673630.00      3685942.50     10673469.00
      3685882.00     10673264.00      3685879.75     10673115.00
      3685798.75     10673086.00      3685816.25     10672991.00
      3685775.00     10672865.00      3685621.00     10672663.00
      3685720.75     10672511.00      3685756.25     10672345.00
      3685702.25     10672289.00      3685634.25     10672143.00
      3685654.75     10672071.00      3685594.50     10671969.00
      3685631.75     10671910.00      3685609.75     10671847.00
      3685638.50     10671765.00      3685625.50     10671712.00
      3685667.00     10671670.00      3685614.75     10671593.00
      3685610.50     10671541.00      3685632.00     10671436.00
      3685674.50     10671385.00      3685662.75     10671232.00
      3685758.75     10671140.00      3685816.00     10671039.00
      3686337.00     10670656.00      3686459.75     10670601.00

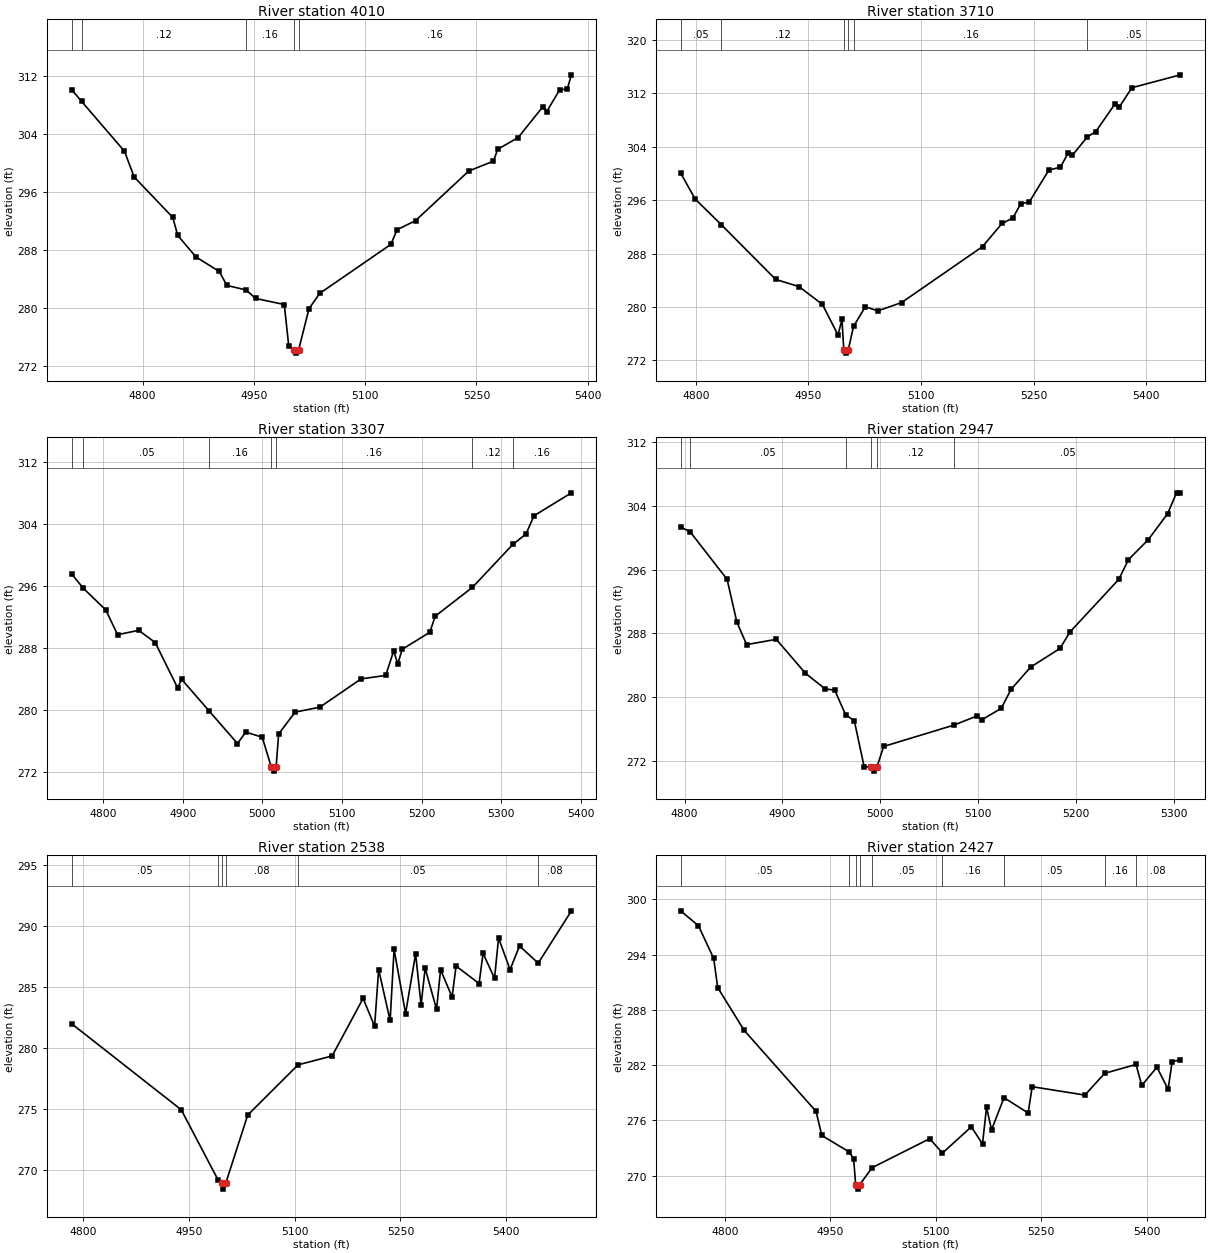
Type RM Length L Ch R = 1,4010,300,300,300
BEGIN DESCRIPTION:
UNT 169 IN CACR 8.0
END DESCRIPTION:
XS GIS Cut Line= 2
      3686280.33     10673754.27      3685634.21     10673945.07
#Sta/Elev= 30
  4704.4  310.12  4717.7  308.50  4775.6  301.61  4788.6  298.06  4840.7  292.47
  4847.4  289.98  4872.0  287.01  4903.3  285.01  4913.7  283.08  4939.5  282.45
  4952.5  281.28  4991.0  280.44  4997.1  274.65  5004.5  274.23  5007.3  273.73
  5010.5  274.23  5024.3  279.86  5038.8  281.98  5134.6  288.74  5143.1  290.78
  5167.9  292.02  5239.7  298.88  5273.0  300.24  5278.6  301.87  5306.3  303.50
  5339.6  307.76  5344.8  307.09  5362.0  310.06  5372.5  310.23  5378.1  312.16
#Mann=5,-1,0
  4704.4    0.08       0  4717.7    0.12       0  4939.5    0.16       0
  5004.5    0.07       0  5010.5    0.16       0
Bank Sta=5004.5,5010.5
Exp/Cntr=0.3,0.1

Type RM Length L Ch R = 1,3710,403,403,403
BEGIN DESCRIPTION:
Mapping XS 9c8c8c11
END DESCRIPTION:
XS GIS Cut Line= 2
      3686197.83     10673485.18      3685568.50     10673702.19
#Sta/Elev= 30
  4779.8  300.06  4799.1  296.18  4833.8  292.35  4906.3  284.14  4937.5  283.06
  4968.7  280.39  4989.4  275.81  4994.7  278.14  4997.1  273.60  4999.8  273.10
  5003.1  273.60  5010.1  277.10  5025.9  280.06  5042.4  279.42  5074.1  280.67
  5181.9  289.05  5207.8  292.51  5222.2  293.32  5232.8  295.46  5244.3  295.75
  5270.2  300.50  5285.7  300.95  5296.1  303.09  5301.4  302.70  5321.7  305.50
  5332.6  306.25  5358.5  310.44  5363.8  309.91  5380.9  312.84  5445.5  314.77
#Mann=6,-1,0
  4779.8    0.05       0  4833.8    0.12       0  4997.1    0.07       0
  5003.1    0.12       0  5010.1    0.16       0  5321.7    0.05       0
Bank Sta=4997.1,5003.1
Exp/Cntr=0.3,0.1

Type RM Length L Ch R = 1,3307,360,360,360
BEGIN DESCRIPTION:
UNT 169 IN CACR 7.0
END DESCRIPTION:
XS GIS Cut Line= 2
      3686111.02     10673120.60      3685504.06     10673281.01
#Sta/Elev= 30
  4760.5  297.53  4775.1  295.69  4803.3  292.89  4818.2  289.69  4844.7  290.25
  4865.4  288.68  4893.6  282.83  4898.7  283.92  4933.5  279.80  4968.8  275.63
  4979.2  277.11  4999.9  276.45  5011.3  272.57  5014.1  272.07  5017.3  272.57
  5020.5  276.87  5041.2  279.69  5072.3  280.33  5124.0  283.98  5155.0  284.43
  5165.0  287.59  5170.2  285.92  5175.7  287.80  5210.4  290.00  5217.1  292.07
  5264.0  295.81  5314.7  301.35  5331.2  302.69  5341.2  305.04  5388.3  308.01
#Mann=7,-1,0
  4760.5    0.12       0  4775.1    0.05       0  4933.5    0.16       0
  5011.3    0.07       0  5017.3    0.16       0  5264.0    0.12       0
  5314.7    0.16       0
Bank Sta=5011.3,5017.3
Exp/Cntr=0.3,0.1

Type RM Length L Ch R = 1,2947,409,409,409
BEGIN DESCRIPTION:
Mapping XS c1fe836e
END DESCRIPTION:
XS GIS Cut Line= 2
      3685987.02     10672899.61      3685476.60     10672875.31
#Sta/Elev= 30
  4795.9  301.37  4805.6  300.77  4843.4  294.80  4853.4  289.41  4863.4  286.60
  4893.7  287.26  4923.5  283.00  4943.5  281.05  4953.5  280.87  4964.5  277.81
  4973.5  277.02  4983.5  271.28  4990.5  271.21  4993.3  270.71  4996.5  271.21
  5003.5  273.81  5075.6  276.50  5098.9  277.64  5103.9  277.16  5123.7  278.59
  5133.7  280.97  5153.7  283.77  5183.8  286.12  5193.8  288.16  5243.8  294.78
  5253.8  297.27  5273.9  299.76  5293.9  303.06  5302.9  305.66  5306.9  305.66
#Mann=6,-1,0
  4795.9    0.12       0  4805.6    0.05       0  4964.5    0.12       0
  4990.5    0.07       0  4996.5    0.12       0  5075.6    0.05       0
Bank Sta=4990.5,4996.5
Exp/Cntr=0.3,0.1

Type RM Length L Ch R = 1,2538,111,111,111
BEGIN DESCRIPTION:
UNT 169 IN CACR 6.0
END DESCRIPTION:
XS GIS Cut Line= 2
      3685778.69     10672750.33      3685445.32     10672125.27
#Sta/Elev= 30
  4784.0  282.00  4939.3  274.95  4991.4  269.21  4996.5  268.94  4999.2  268.44
  5002.5  268.94  5033.5  274.51  5104.9  278.63  5153.2  279.36  5197.1  284.08
  5213.4  281.79  5219.1  286.44  5235.4  282.27  5241.0  288.10  5257.3  282.84
  5271.5  287.73  5279.3  283.54  5285.0  286.56  5301.2  283.18  5306.9  286.43
  5323.2  284.20  5328.9  286.73  5361.5  285.30  5367.1  287.77  5383.4  285.73
  5389.1  289.03  5405.4  286.44  5418.8  288.38  5445.3  286.97  5492.4  291.26
#Mann=6,-1,0
  4784.0    0.05       0  4991.4    0.08       0  4996.5    0.07       0
  5002.5    0.08       0  5104.9    0.05       0  5445.3    0.08       0
Bank Sta=4996.5,5002.5
Exp/Cntr=0.3,0.1

Type RM Length L Ch R = 1,2427,570,570,570
BEGIN DESCRIPTION:
UNT 169 IN CACR 5.0
END DESCRIPTION:
XS GIS Cut Line= 2
      3685858.52     10672694.73      3685507.84     10672076.69
#Sta/Elev= 30
  4737.2  298.76  4762.5  297.14  4784.2  293.59  4789.9  290.42  4827.4  285.78
  4929.8  276.96  4937.9  274.35  4977.1  272.55  4983.2  271.80  4986.0  269.02
  4988.7  268.52  4992.0  269.02  5009.4  270.85  5091.3  274.00  5109.5  272.44
  5150.5  275.29  5166.4  273.43  5172.1  277.39  5179.3  274.97  5197.0  278.46
  5231.3  276.79  5237.0  279.65  5312.0  278.74  5340.0  281.10  5384.7  282.07
  5392.8  279.79  5414.4  281.76  5430.3  279.37  5436.0  282.37  5447.8  282.57
#Mann=9,-1,0
  4737.2    0.05       0  4977.1    0.12       0  4986.0    0.07       0
  4992.0    0.12       0  5009.4    0.05       0  5109.5    0.16       0
  5197.0    0.05       0  5340.0    0.16       0  5384.7    0.08       0
Bank Sta=4986,4992
Exp/Cntr=0.3,0.1

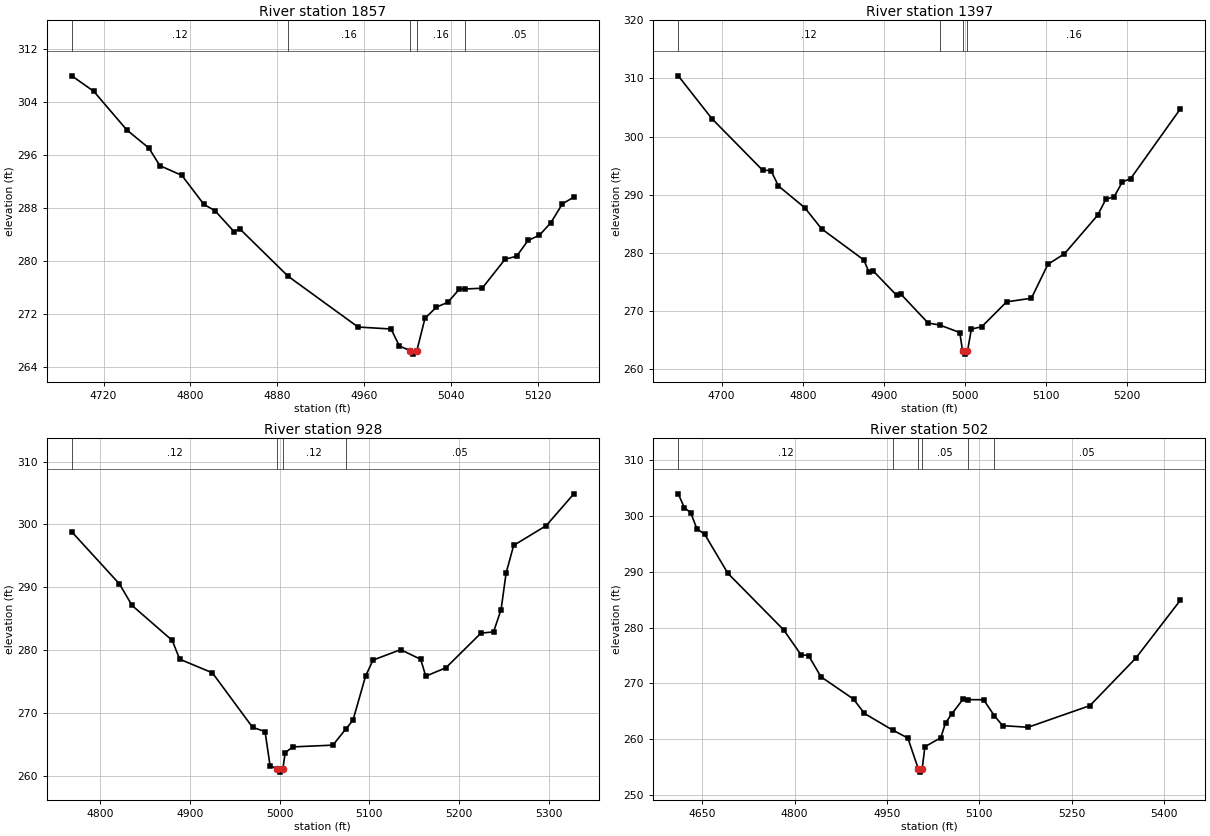
Type RM Length L Ch R = 1,1857,460,460,460
BEGIN DESCRIPTION:
UNT 169 IN CACR 4.0
END DESCRIPTION:
XS GIS Cut Line= 3
      3685899.62     10671910.19      3685599.61     10671960.19
      3685449.58     10672010.20
#Sta/Elev= 30
  4690.7  307.89  4711.0  305.55  4741.4  299.74  4761.7  297.02  4771.8  294.37
  4792.1  292.90  4812.4  288.53  4822.5  287.60  4840.2  284.42  4845.3  284.87
  4890.0  277.71  4954.3  270.08  4984.7  269.78  4992.3  267.24  5002.4  266.50
  5005.1  266.00  5008.4  266.50  5015.9  271.38  5026.5  273.08  5037.0  273.80
  5047.6  275.79  5052.5  275.80  5068.6  275.92  5089.7  280.29  5100.3  280.73
  5110.8  283.11  5121.3  283.90  5131.9  285.80  5142.4  288.61  5153.0  289.64
#Mann=5,-1,0
  4690.7    0.12       0  4890.0    0.16       0  5002.4    0.07       0
  5008.4    0.16       0  5052.5    0.05       0
Bank Sta=5002.4,5008.4
Exp/Cntr=0.3,0.1

Type RM Length L Ch R = 1,1397,469,469,469
BEGIN DESCRIPTION:
UNT 169 IN CACR 3.0
END DESCRIPTION:
XS GIS Cut Line= 3
      3685949.64     10671660.20      3685599.61     10671560.19
      3685349.59     10671610.19
#Sta/Elev= 30
  4646.5  310.45  4688.1  303.08  4750.5  294.24  4760.9  294.18  4770.0  291.53
  4802.5  287.79  4823.3  284.16  4875.3  278.82  4881.8  276.67  4887.0  276.91
  4915.6  272.77  4920.8  272.98  4954.6  267.98  4969.1  267.63  4993.6  266.35
  4997.1  263.14  4999.9  262.64  5003.1  263.14  5007.9  266.95  5020.7  267.34
  5051.3  271.62  5081.9  272.24  5102.3  278.08  5122.7  279.88  5163.5  286.49
  5173.7  289.24  5183.9  289.68  5194.1  292.23  5204.3  292.80  5265.5  304.76
#Mann=4,-1,0
  4646.5    0.12       0  4969.1    0.16       0  4997.1    0.07       0
  5003.1    0.16       0
Bank Sta=4997.1,5003.1
Exp/Cntr=0.3,0.1

Type RM Length L Ch R = 1,928,426,426,426
BEGIN DESCRIPTION:
UNT 169 IN CACR 2.0
END DESCRIPTION:
XS GIS Cut Line= 3
      3685949.63     10671260.20      3685749.61     10671160.19
      3685449.65     10671010.21
#Sta/Elev= 30
  4768.6  298.83  4821.7  290.54  4835.7  287.13  4880.4  281.57  4888.8  278.58
  4925.2  276.41  4969.9  267.75  4983.8  267.08  4989.4  261.63  4997.6  261.13
  5000.4  260.63  5003.6  261.13  5006.2  263.71  5014.6  264.64  5059.3  264.92
  5073.5  267.44  5081.7  268.88  5095.7  275.89  5104.0  278.44  5134.8  280.10
  5157.1  278.56  5162.7  275.89  5185.1  277.21  5224.2  282.73  5238.2  282.92
  5246.6  286.48  5252.2  292.29  5260.6  296.67  5296.9  299.82  5327.6  304.87
#Mann=4,-1,0
  4768.6    0.12       0  4997.6    0.07       0  5003.6    0.12       0
  5073.5    0.05       0
Bank Sta=4997.6,5003.6
Exp/Cntr=0.3,0.1

Type RM Length L Ch R = 1,502,0,0,0
BEGIN DESCRIPTION:
UNT 169 IN CACR 1.0
END DESCRIPTION:
XS GIS Cut Line= 3
      3685999.61     10671260.21      3686049.61     10670860.19
      3685649.65     10670760.20
#Sta/Elev= 30
  4610.9  304.00  4621.0  301.48  4631.1  300.63  4641.2  297.72  4653.8  296.75
  4691.5  289.74  4782.2  279.58  4810.0  275.17  4822.6  274.97  4842.7  271.17
  4895.6  267.17  4913.3  264.59  4959.3  261.60  4983.8  260.19  5001.0  254.57
  5003.7  254.07  5007.0  254.57  5011.5  258.63  5037.2  260.23  5045.0  262.89
  5055.3  264.54  5073.3  267.14  5081.0  267.07  5106.8  267.06  5124.1  264.22
  5137.7  262.41  5179.0  262.12  5279.5  266.00  5354.2  274.55  5426.3  284.90
#Mann=6,-1,0
  4610.9    0.12       0  4959.3    0.05       0  5001.0    0.04       0
  5007.0    0.05       0  5081.0    0.08       0  5124.1    0.05       0
Bank Sta=5001,5007
Exp/Cntr=0.3,0.1

Chan Stop Cuts=-1