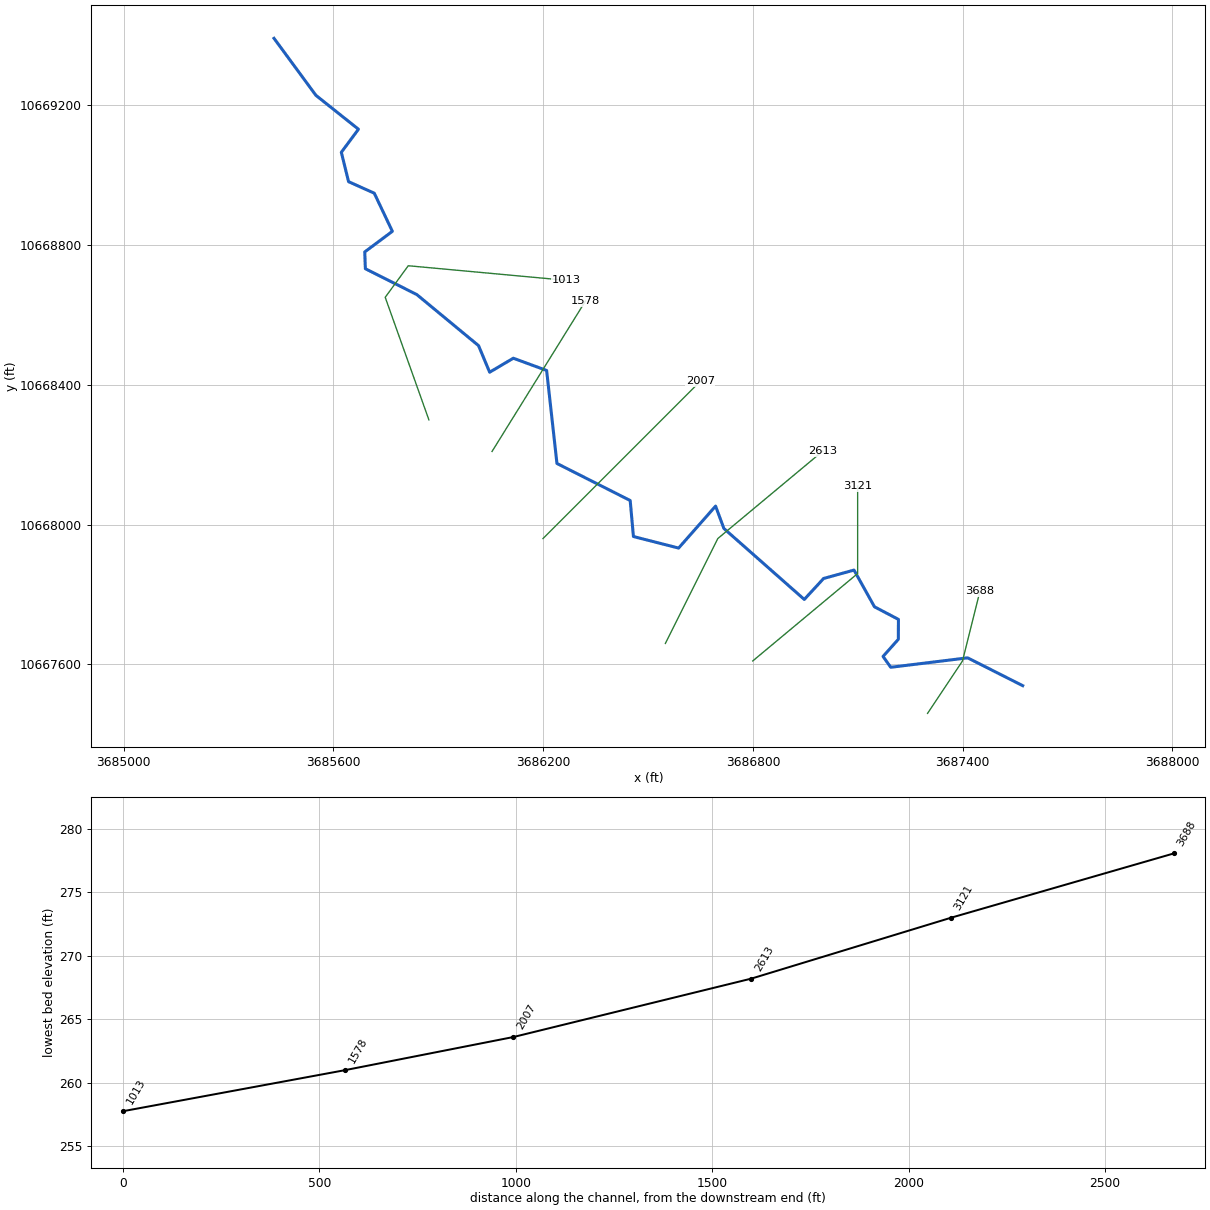
--- UNT 170 IN CACR.prj (project) ---

Proj Title=UNT 170 IN CACR Base Level Engineering
Current Plan=p01
Default Exp/Contr=0.3,0.1
English Units
Geom File=g01
Flow File=f01
Plan File=p01
BEGIN DESCRIPTION:
UNT 170 IN CACR
END DESCRIPTION:

--- UNT 170 IN CACR.p01 (plan) ---

Plan Title=Multiple Run
Short Identifier=Multiple
Geom File=g01
Flow File=f01
Subcritical Flow
K Sum by GR= 0
Std Step Tol= 0.01
Critical Tol= 0.01
Num of Std Step Trials= 20
Max Error Tol= 0.3
Flow Tol Ratio= 0.001
Split Flow NTrial= 30
Split Flow Tol= 0.02
Split Flow Ratio= 0.02
Log Output Level= 0
Friction Slope Method= 1
Unsteady Friction Slope Method= 2
Unsteady Bridges Friction Slope Method= 1
Parabolic Critical Depth
Global Vel Dist=  1 , 1 , 1
Global Log Level= 0
CheckData=True
Encroach Param= -1, 0, 0, 0
BEGIN DESCRIPTION:
Multiple Run
END DESCRIPTION:

--- UNT 170 IN CACR.f01 (steady flow) ---

Flow Title=Multiple
Number of Profiles=7
Profile Names=10-year,25-year,50-year,1pct_min,100-year,1pct_plu,500-year
River Rch & RM= UNT 170 IN CACR,Reach-1,3688
     385     515     622     553     748    1011    1084
Boundary for River Rch & Prof#=UNT 170 IN CACR,Reach-1,1
Up Type=0
Dn Type=3
Dn Slope=0.005
Boundary for River Rch & Prof#=UNT 170 IN CACR,Reach-1,2
Up Type=0
Dn Type=3
Dn Slope=0.005
Boundary for River Rch & Prof#=UNT 170 IN CACR,Reach-1,3
Up Type=0
Dn Type=3
Dn Slope=0.005
Boundary for River Rch & Prof#=UNT 170 IN CACR,Reach-1,4
Up Type=0
Dn Type=3
Dn Slope=0.005
Boundary for River Rch & Prof#=UNT 170 IN CACR,Reach-1,5
Up Type=0
Dn Type=3
Dn Slope=0.005
Boundary for River Rch & Prof#=UNT 170 IN CACR,Reach-1,6
Up Type=0
Dn Type=3
Dn Slope=0.005
Boundary for River Rch & Prof#=UNT 170 IN CACR,Reach-1,7
Up Type=0
Dn Type=3
Dn Slope=0.005

--- UNT 170 IN CACR.g01 (geometry) ---

Geom Title=Existing Conditions

River Reach=UNT 170 IN CACR,Reach-1
Reach XY= 30
      3687571.67     10667539.42      3687414.25     10667619.00
      3687194.25     10667592.00      3687172.25     10667623.00
      3687216.00     10667672.00      3687216.25     10667729.00
      3687147.75     10667765.00      3687089.25     10667870.00
      3687002.25     10667846.00      3686947.00     10667786.00
      3686717.00     10667989.00      3686693.25     10668053.00
      3686587.50     10667933.00      3686458.25     10667966.00
      3686449.00     10668069.00      3686239.50     10668175.00
      3686210.00     10668441.00      3686114.75     10668476.00
      3686047.00     10668436.00      3686015.25     10668512.00
      3685838.75     10668658.00      3685691.50     10668732.00
      3685689.75     10668780.00      3685768.75     10668839.00
      3685717.00     10668948.00      3685643.50     10668981.00
      3685622.75     10669065.00      3685671.75     10669131.00
      3685550.00     10669228.00      3685430.25     10669391.00

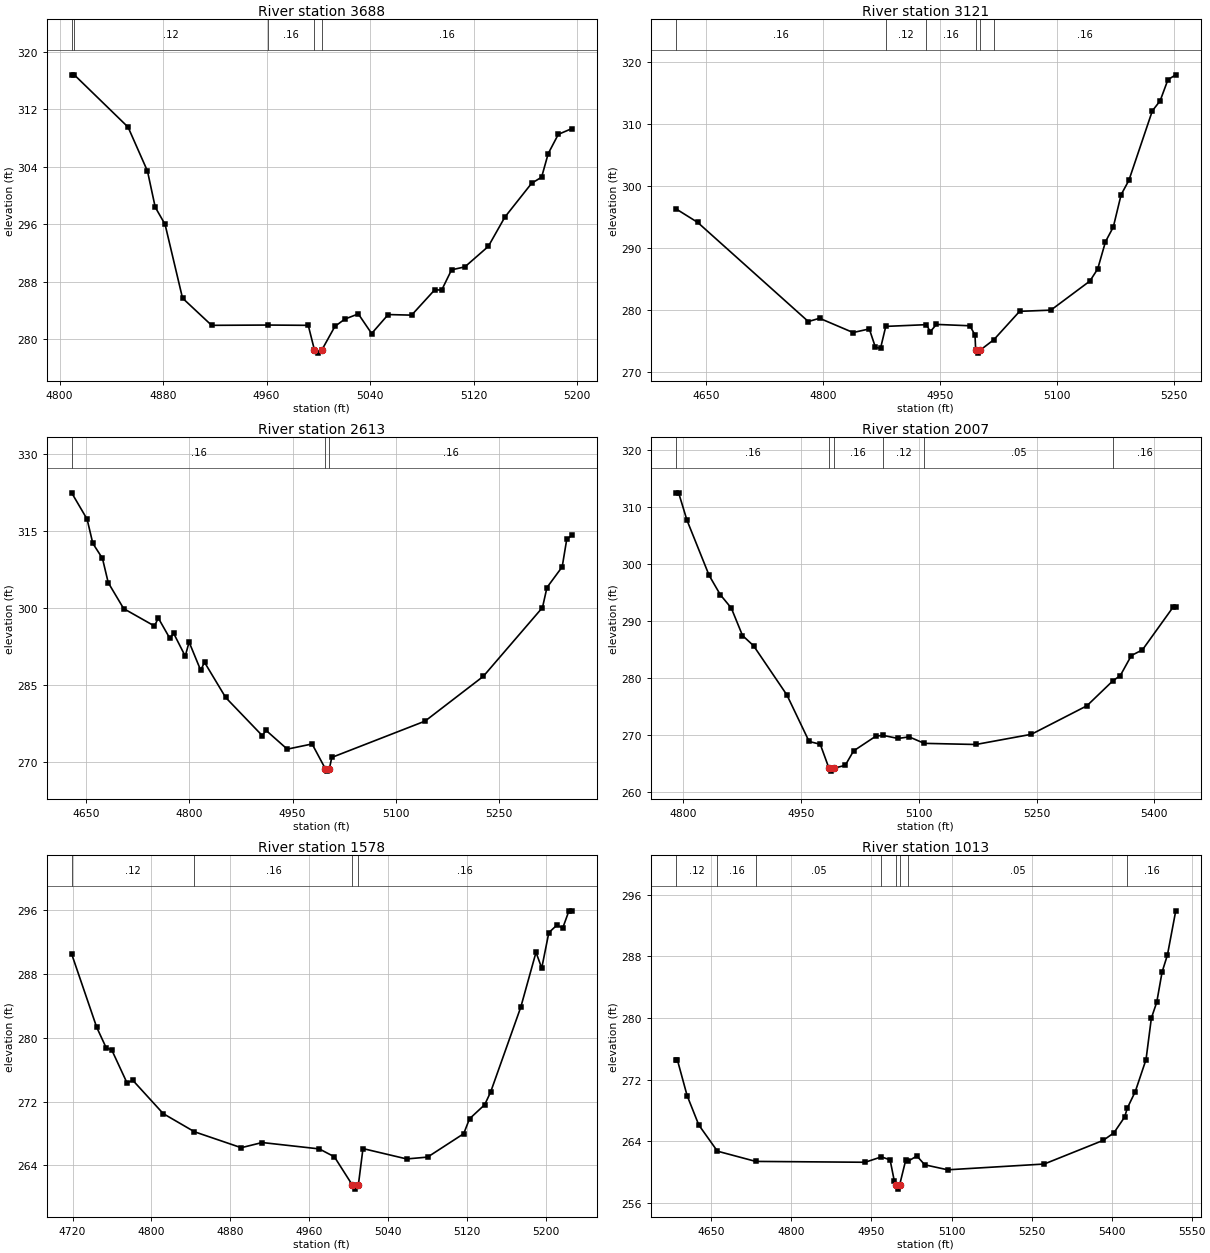
Type RM Length L Ch R = 1,3688,567,567,567
BEGIN DESCRIPTION:
UNT 170 IN CACR 5.0
END DESCRIPTION:
XS GIS Cut Line= 3
      3687299.58     10667460.15      3687399.61     10667610.19
      3687449.61     10667810.21
#Sta/Elev= 30
  4809.3  316.81  4811.3  316.81  4852.9  309.53  4867.9  303.41  4873.9  298.38
  4881.5  295.99  4895.0  285.72  4917.5  281.93  4961.3  281.97  4992.2  281.93
  4996.9  278.56  4999.7  278.06  5002.9  278.56  5012.8  281.78  5020.5  282.80
  5030.9  283.52  5041.2  280.79  5054.0  283.43  5072.1  283.35  5090.1  286.90
  5095.3  286.82  5103.0  289.66  5113.3  290.07  5131.4  292.92  5144.2  297.00
  5164.9  301.71  5172.6  302.56  5177.7  305.84  5185.5  308.52  5195.8  309.31
#Mann=5,-1,0
  4809.3    0.16       0  4811.3    0.12       0  4961.3    0.16       0
  4996.9    0.07       0  5002.9    0.16       0
Bank Sta=4996.9,5002.9
Exp/Cntr=0.3,0.1

Type RM Length L Ch R = 1,3121,508,508,508
BEGIN DESCRIPTION:
UNT 170 IN CACR 4.0
END DESCRIPTION:
XS GIS Cut Line= 3
      3686799.64     10667610.21      3687099.61     10667860.19
      3687099.61     10668110.21
#Sta/Elev= 30
  4611.4  296.28  4639.4  294.08  4781.2  278.09  4795.6  278.62  4838.5  276.32
  4859.3  276.90  4867.2  273.92  4873.7  273.78  4880.4  277.31  4932.5  277.59
  4937.4  276.45  4945.3  277.63  4988.2  277.41  4994.7  275.92  4995.6  273.50
  4998.4  273.00  5001.6  273.50  5018.9  275.17  5051.9  279.74  5091.9  279.93
  5141.9  284.62  5151.9  286.57  5161.9  290.97  5171.9  293.33  5181.9  298.54
  5191.9  300.87  5221.9  312.06  5231.9  313.68  5241.9  317.09  5251.9  317.87
#Mann=6,-1,0
  4611.4    0.16       0  4880.4    0.12       0  4932.5    0.16       0
  4995.6    0.07       0  5001.6    0.16       0  5018.9    0.16       0
Bank Sta=4995.6,5001.6
Exp/Cntr=0.3,0.1

Type RM Length L Ch R = 1,2613,606,606,606
BEGIN DESCRIPTION:
UNT 170 IN CACR 3.0
END DESCRIPTION:
XS GIS Cut Line= 3
      3686549.61     10667660.19      3686699.61     10667960.19
      3686999.60     10668210.18
#Sta/Elev= 30
  4629.3  322.41  4651.7  317.28  4660.0  312.57  4674.0  309.64  4682.4  304.91
  4704.8  299.86  4749.5  296.47  4755.1  298.02  4771.8  294.08  4777.4  295.04
  4794.2  290.60  4799.8  293.35  4816.6  287.86  4822.2  289.40  4852.9  282.55
  4906.0  275.13  4911.6  276.14  4942.3  272.49  4978.4  273.50  4997.5  268.71
  5000.2  268.21  5003.5  268.71  5007.0  270.88  5142.4  277.95  5227.0  286.67
  5312.9  300.07  5319.4  303.97  5341.5  307.99  5348.1  313.33  5355.2  314.10
#Mann=3,-1,0
  4629.3    0.16       0  4997.5    0.07       0  5003.5    0.16       0
Bank Sta=4997.5,5003.5
Exp/Cntr=0.3,0.1

Type RM Length L Ch R = 1,2007,429,429,429
BEGIN DESCRIPTION:
UNT 170 IN CACR 2.0
END DESCRIPTION:
XS GIS Cut Line= 3
      3686199.59     10667960.17      3686349.61     10668110.19
      3686649.60     10668410.18
#Sta/Elev= 30
  4790.8  312.51  4794.4  312.51  4805.0  307.71  4833.2  298.01  4847.4  294.62
  4861.5  292.25  4875.7  287.44  4889.8  285.64  4932.2  277.00  4960.5  268.82
  4974.7  268.33  4985.8  264.11  4988.6  263.61  4991.8  264.11  5006.5  264.63
  5017.1  267.16  5045.4  269.75  5054.4  269.90  5073.7  269.35  5087.8  269.63
  5107.1  268.49  5172.7  268.29  5243.4  270.08  5314.1  275.09  5347.4  279.51
  5356.5  280.37  5370.7  283.92  5384.8  284.92  5423.7  292.40  5427.2  292.40
#Mann=6,-1,0
  4790.8    0.16       0  4985.8    0.07       0  4991.8    0.16       0
  5054.4    0.12       0  5107.1    0.05       0  5347.4    0.16       0
Bank Sta=4985.8,4991.8
Exp/Cntr=0.3,0.1

Type RM Length L Ch R = 1,1578,565,565,565
BEGIN DESCRIPTION:
Mapping XS f98bb565
END DESCRIPTION:
XS GIS Cut Line= 2
      3686053.86     10668209.31      3686321.21     10668639.85
#Sta/Elev= 30
  4719.1  290.52  4744.5  281.31  4754.0  278.77  4759.9  278.43  4775.2  274.34
  4781.1  274.66  4811.9  270.48  4843.6  268.20  4891.0  266.20  4912.2  266.85
  4970.1  266.05  4985.4  265.06  5003.7  261.50  5006.4  261.00  5009.7  261.50
  5014.4  266.09  5058.7  264.79  5079.9  265.02  5116.5  267.96  5122.4  269.83
  5137.8  271.60  5143.9  273.22  5174.4  283.86  5189.8  290.73  5195.6  288.75
  5202.8  293.20  5211.0  294.15  5216.9  293.78  5223.2  295.94  5225.9  295.94
#Mann=4,-1,0
  4719.1    0.12       0  4843.6    0.16       0  5003.7    0.07       0
  5009.7    0.16       0
Bank Sta=5003.7,5009.7
Exp/Cntr=0.3,0.1

Type RM Length L Ch R = 1,1013,0,0,0
BEGIN DESCRIPTION:
UNT 170 IN CACR 1.0
END DESCRIPTION:
XS GIS Cut Line= 4
      3685873.30     10668299.55      3685748.29     10668650.26
      3685814.27     10668740.54      3686265.11     10668698.93
#Sta/Elev= 30
  4583.3  274.55  4586.3  274.55  4604.5  269.92  4626.4  266.10  4661.3  262.70
  4733.1  261.37  4938.2  261.26  4968.6  261.96  4984.9  261.57  4992.7  258.85
  4996.6  258.27  4999.3  257.77  5002.6  258.27  5014.2  261.54  5018.4  261.38
  5035.1  262.08  5049.8  260.93  5092.9  260.28  5273.7  261.03  5384.1  264.10
  5404.2  265.07  5424.3  267.12  5429.5  268.30  5444.4  270.45  5464.5  274.60
  5474.5  279.98  5484.6  282.05  5494.6  285.97  5504.6  288.18  5520.2  293.92
#Mann=8,-1,0
  4583.3    0.12       0  4661.3    0.16       0  4733.1    0.05       0
  4968.6    0.16       0  4996.6    0.07       0  5002.6    0.16       0
  5018.4    0.05       0  5429.5    0.16       0
Bank Sta=4996.6,5002.6
Exp/Cntr=0.3,0.1

Chan Stop Cuts=-1