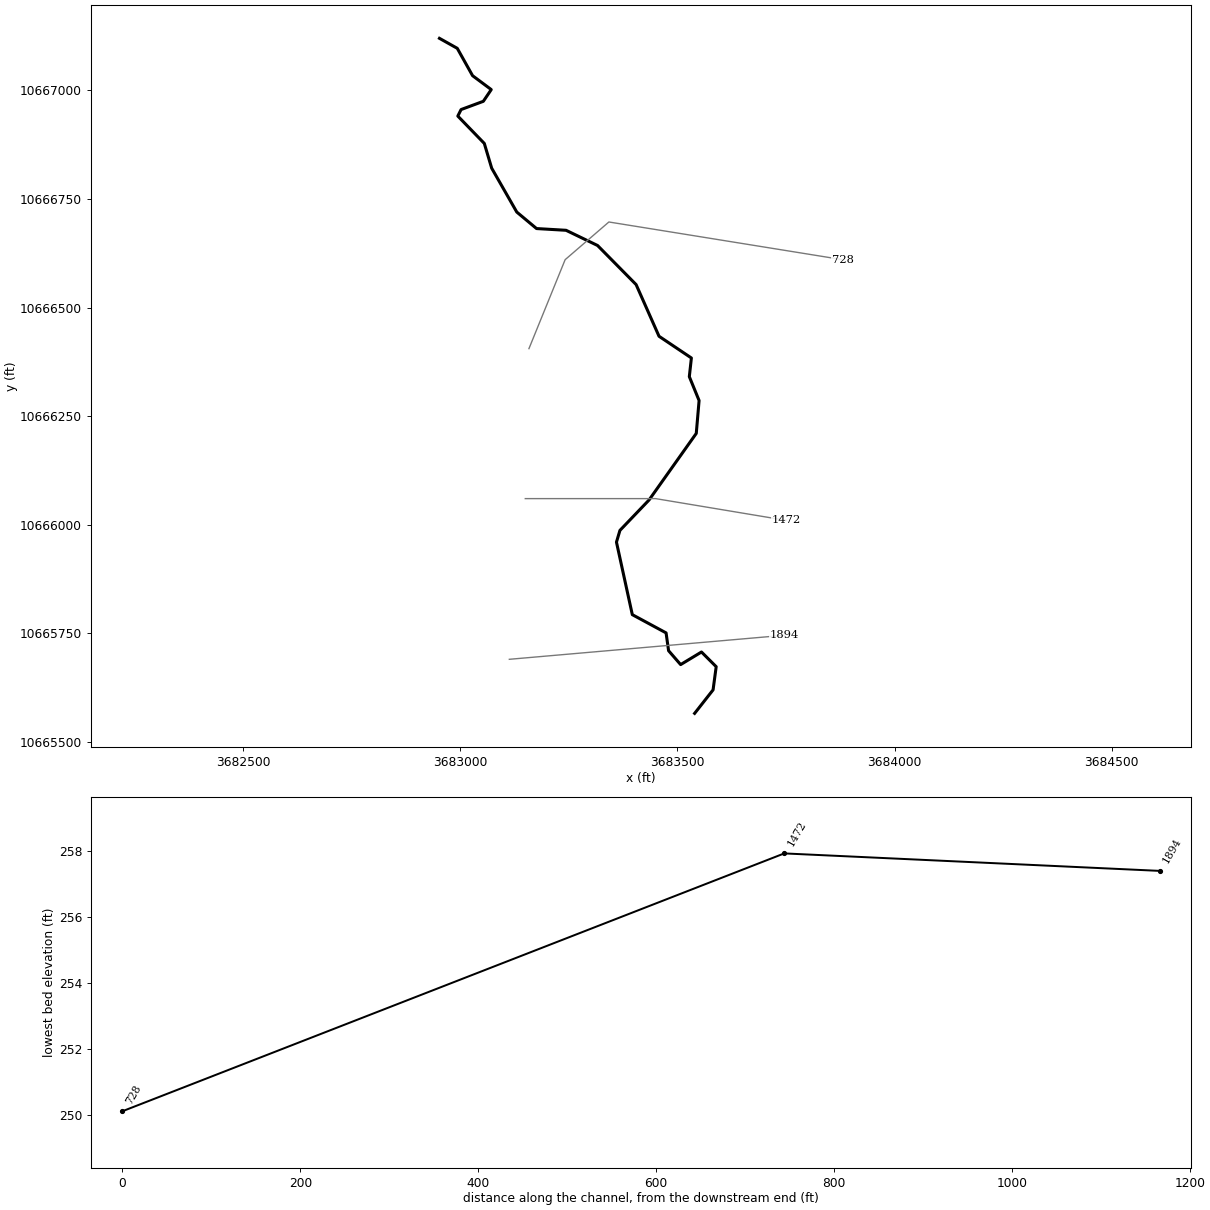
--- UNT 171 IN CACR.prj (project) ---

Proj Title=UNT 171 IN CACR Base Level Engineering
Current Plan=p01
Default Exp/Contr=0.3,0.1
English Units
Geom File=g01
Flow File=f01
Plan File=p01
BEGIN DESCRIPTION:
UNT 171 IN CACR
END DESCRIPTION:

--- UNT 171 IN CACR.p01 (plan) ---

Plan Title=Multiple Run
Short Identifier=Multiple
Geom File=g01
Flow File=f01
Subcritical Flow
K Sum by GR= 0
Std Step Tol= 0.01
Critical Tol= 0.01
Num of Std Step Trials= 20
Max Error Tol= 0.3
Flow Tol Ratio= 0.001
Split Flow NTrial= 30
Split Flow Tol= 0.02
Split Flow Ratio= 0.02
Log Output Level= 0
Friction Slope Method= 1
Unsteady Friction Slope Method= 2
Unsteady Bridges Friction Slope Method= 1
Parabolic Critical Depth
Global Vel Dist=  1 , 1 , 1
Global Log Level= 0
CheckData=True
Encroach Param= -1, 0, 0, 0
BEGIN DESCRIPTION:
Multiple Run
END DESCRIPTION:

--- UNT 171 IN CACR.f01 (steady flow) ---

Flow Title=Multiple
Number of Profiles=7
Profile Names=10-year,25-year,50-year,1pct_min,100-year,1pct_plu,500-year
River Rch & RM= UNT 171 IN CACR,Reach-1,1894
     552     749     912     816    1104    1493    1624
Boundary for River Rch & Prof#=UNT 171 IN CACR,Reach-1,1
Up Type=0
Dn Type=3
Dn Slope=0.005
Boundary for River Rch & Prof#=UNT 171 IN CACR,Reach-1,2
Up Type=0
Dn Type=3
Dn Slope=0.005
Boundary for River Rch & Prof#=UNT 171 IN CACR,Reach-1,3
Up Type=0
Dn Type=3
Dn Slope=0.005
Boundary for River Rch & Prof#=UNT 171 IN CACR,Reach-1,4
Up Type=0
Dn Type=3
Dn Slope=0.005
Boundary for River Rch & Prof#=UNT 171 IN CACR,Reach-1,5
Up Type=0
Dn Type=3
Dn Slope=0.005
Boundary for River Rch & Prof#=UNT 171 IN CACR,Reach-1,6
Up Type=0
Dn Type=3
Dn Slope=0.005
Boundary for River Rch & Prof#=UNT 171 IN CACR,Reach-1,7
Up Type=0
Dn Type=3
Dn Slope=0.005

--- UNT 171 IN CACR.g01 (geometry) ---

Geom Title=Existing Conditions

River Reach=UNT 171 IN CACR,Reach-1
Reach XY= 30
      3683539.46     10665565.69      3683581.94     10665619.80
      3683589.10     10665673.19      3683555.25     10665707.00
      3683507.25     10665678.00      3683479.50     10665710.00
      3683473.75     10665751.00      3683396.00     10665793.00
      3683359.50     10665960.00      3683367.50     10665987.00
      3683434.50     10666057.00      3683543.25     10666210.33
      3683549.75     10666286.00      3683527.25     10666341.00
      3683532.00     10666384.00      3683457.50     10666434.00
      3683404.75     10666553.00      3683316.00     10666643.00
      3683243.50     10666678.00      3683175.50     10666682.00
      3683130.00     10666720.00      3683072.25     10666821.00
      3683055.25     10666878.00      3682994.25     10666941.00
      3683001.75     10666956.00      3683053.00     10666975.00
      3683071.25     10667002.00      3683028.25     10667034.00
      3682993.00     10667097.00      3682952.00     10667120.00

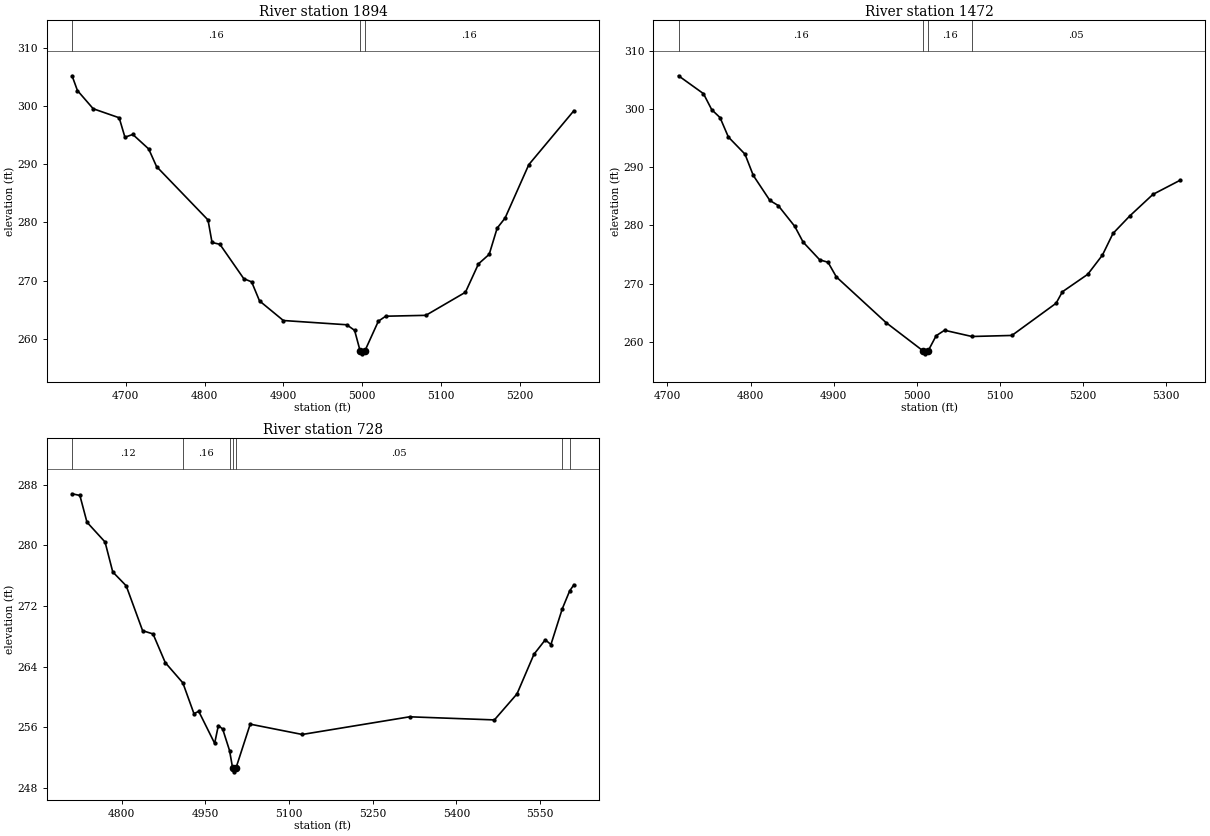
Type RM Length L Ch R = 1,1894,422,422,422
BEGIN DESCRIPTION:
UNT 171 IN CACR 3.0
END DESCRIPTION:
XS GIS Cut Line= 2
      3683112.88     10665690.19      3683746.46     10665745.59
#Sta/Elev= 30
  4632.1  305.22  4638.9  302.68  4658.9  299.55  4691.8  298.00  4699.1  294.66
  4709.1  295.13  4729.2  292.64  4739.2  289.61  4804.4  280.43  4809.5  276.56
  4819.5  276.24  4849.7  270.34  4859.7  269.78  4869.7  266.51  4899.9  263.14
  4980.2  262.41  4990.2  261.45  4997.2  257.91  5000.0  257.41  5003.2  257.91
  5020.3  263.02  5029.6  263.88  5080.5  264.03  5130.7  268.00  5147.2  272.88
  5160.8  274.52  5170.9  279.03  5180.9  280.75  5211.0  289.94  5268.1  299.21
#Mann=3,-1,0
  4632.1    0.16       0  4997.2    0.07       0  5003.2    0.16       0
Bank Sta=4997.2,5003.2
Exp/Cntr=0.3,0.1

Type RM Length L Ch R = 1,1472,744,744,744
BEGIN DESCRIPTION:
UNT 171 IN CACR 2.0
END DESCRIPTION:
XS GIS Cut Line= 3
      3683149.57     10666060.19      3683449.61     10666060.19
      3683749.63     10666010.19
#Sta/Elev= 30
  4713.3  305.71  4743.3  302.64  4753.3  299.88  4763.3  298.52  4773.3  295.19
  4793.3  292.25  4803.3  288.59  4823.3  284.29  4833.3  283.42  4853.3  279.83
  4863.3  277.14  4883.3  274.09  4893.3  273.67  4903.3  271.16  4963.3  263.29
  5007.8  258.44  5010.6  257.94  5013.8  258.44  5023.5  261.05  5033.6  261.99
  5066.6  260.92  5114.7  261.10  5167.9  266.63  5175.5  268.60  5206.0  271.60
  5223.7  274.90  5236.4  278.62  5256.7  281.64  5284.5  285.33  5317.5  287.78
#Mann=4,-1,0
  4713.3    0.16       0  5007.8    0.07       0  5013.8    0.16       0
  5066.6    0.05       0
Bank Sta=5007.8,5013.8
Exp/Cntr=0.3,0.1

Type RM Length L Ch R = 1,728,0,0,0
BEGIN DESCRIPTION:
UNT 171 IN CACR 1.0
END DESCRIPTION:
XS GIS Cut Line= 4
      3683158.02     10666405.48      3683241.35     10666610.33
      3683342.04     10666697.14      3683880.19     10666610.34
#Sta/Elev= 30
  4711.4  286.80  4725.4  286.58  4738.1  283.05  4770.5  280.44  4784.3  276.49
  4808.4  274.66  4837.8  268.74  4856.5  268.31  4878.4  264.53  4909.9  261.86
  4929.8  257.80  4938.4  258.10  4966.9  253.88  4973.5  256.22  4981.2  255.78
  4993.6  252.93  4999.1  250.62  5001.8  250.12  5005.1  250.62  5030.6  256.41
  5123.8  255.05  5316.3  257.38  5468.2  256.97  5508.7  260.40  5539.1  265.63
  5559.4  267.54  5569.5  266.91  5589.8  271.62  5603.1  273.99  5610.6  274.79
#Mann=7,-1,0
  4711.4    0.12       0  4909.9    0.16       0  4993.6    0.05       0
  4999.1    0.03       0  5005.1    0.05       0  5589.8    0.12       0
  5603.1    0.16       0
Bank Sta=4999.1,5005.1
Exp/Cntr=0.3,0.1

Chan Stop Cuts=-1