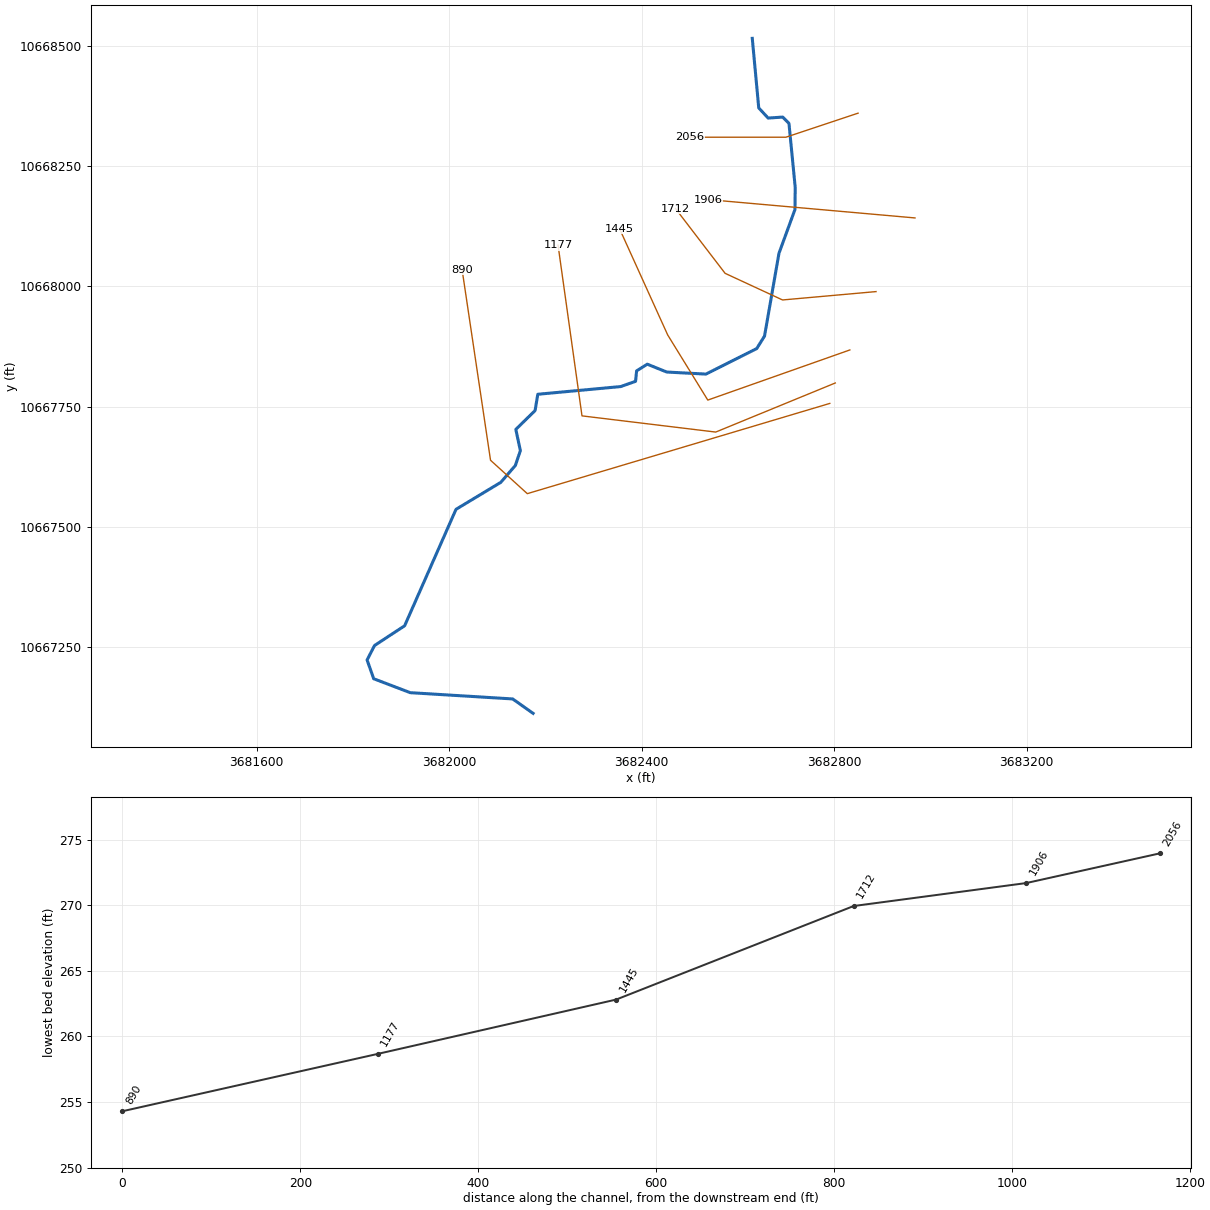
--- UNT 172 IN CACR.prj (project) ---

Proj Title=UNT 172 IN CACR Base Level Engineering
Current Plan=p01
Default Exp/Contr=0.3,0.1
English Units
Geom File=g01
Flow File=f01
Plan File=p01
BEGIN DESCRIPTION:
UNT 172 IN CACR
END DESCRIPTION:

--- UNT 172 IN CACR.p01 (plan) ---

Plan Title=Multiple Run
Short Identifier=Multiple
Geom File=g01
Flow File=f01
Subcritical Flow
K Sum by GR= 0
Std Step Tol= 0.01
Critical Tol= 0.01
Num of Std Step Trials= 20
Max Error Tol= 0.3
Flow Tol Ratio= 0.001
Split Flow NTrial= 30
Split Flow Tol= 0.02
Split Flow Ratio= 0.02
Log Output Level= 0
Friction Slope Method= 1
Unsteady Friction Slope Method= 2
Unsteady Bridges Friction Slope Method= 1
Parabolic Critical Depth
Global Vel Dist=  1 , 1 , 1
Global Log Level= 0
CheckData=True
Encroach Param= -1, 0, 0, 0
BEGIN DESCRIPTION:
Multiple Run
END DESCRIPTION:

--- UNT 172 IN CACR.f01 (steady flow) ---

Flow Title=Multiple
Number of Profiles=7
Profile Names=10-year,25-year,50-year,1pct_min,100-year,1pct_plu,500-year
River Rch & RM= UNT 172 IN CACR,Reach-1,2056
     201     256     298     256     346     468     468
Boundary for River Rch & Prof#=UNT 172 IN CACR,Reach-1,1
Up Type=0
Dn Type=3
Dn Slope=0.005
Boundary for River Rch & Prof#=UNT 172 IN CACR,Reach-1,2
Up Type=0
Dn Type=3
Dn Slope=0.005
Boundary for River Rch & Prof#=UNT 172 IN CACR,Reach-1,3
Up Type=0
Dn Type=3
Dn Slope=0.005
Boundary for River Rch & Prof#=UNT 172 IN CACR,Reach-1,4
Up Type=0
Dn Type=3
Dn Slope=0.005
Boundary for River Rch & Prof#=UNT 172 IN CACR,Reach-1,5
Up Type=0
Dn Type=3
Dn Slope=0.005
Boundary for River Rch & Prof#=UNT 172 IN CACR,Reach-1,6
Up Type=0
Dn Type=3
Dn Slope=0.005
Boundary for River Rch & Prof#=UNT 172 IN CACR,Reach-1,7
Up Type=0
Dn Type=3
Dn Slope=0.005

--- UNT 172 IN CACR.g01 (geometry) ---

Geom Title=Existing Conditions

River Reach=UNT 172 IN CACR,Reach-1
Reach XY= 30
      3682629.78     10668515.65      3682643.25     10668371.00
      3682662.75     10668350.00      3682693.00     10668352.00
      3682706.00     10668339.00      3682719.00     10668206.00
      3682718.50     10668160.00      3682685.25     10668069.00
      3682655.25     10667897.00      3682639.00     10667871.00
      3682533.50     10667818.00      3682452.07     10667822.26
      3682411.62     10667838.57      3682389.48     10667824.68
      3682387.31     10667802.98      3682356.53     10667792.06
      3682184.19     10667776.07      3682178.55     10667742.22
      3682138.50     10667703.00      3682148.00     10667659.00
      3682137.50     10667628.00      3682107.25     10667593.00
      3682014.25     10667537.00      3681907.50     10667295.00
      3681845.00     10667254.00      3681829.50     10667224.00
      3681843.25     10667185.00      3681919.25     10667156.00
      3682132.00     10667143.00      3682174.50     10667113.00

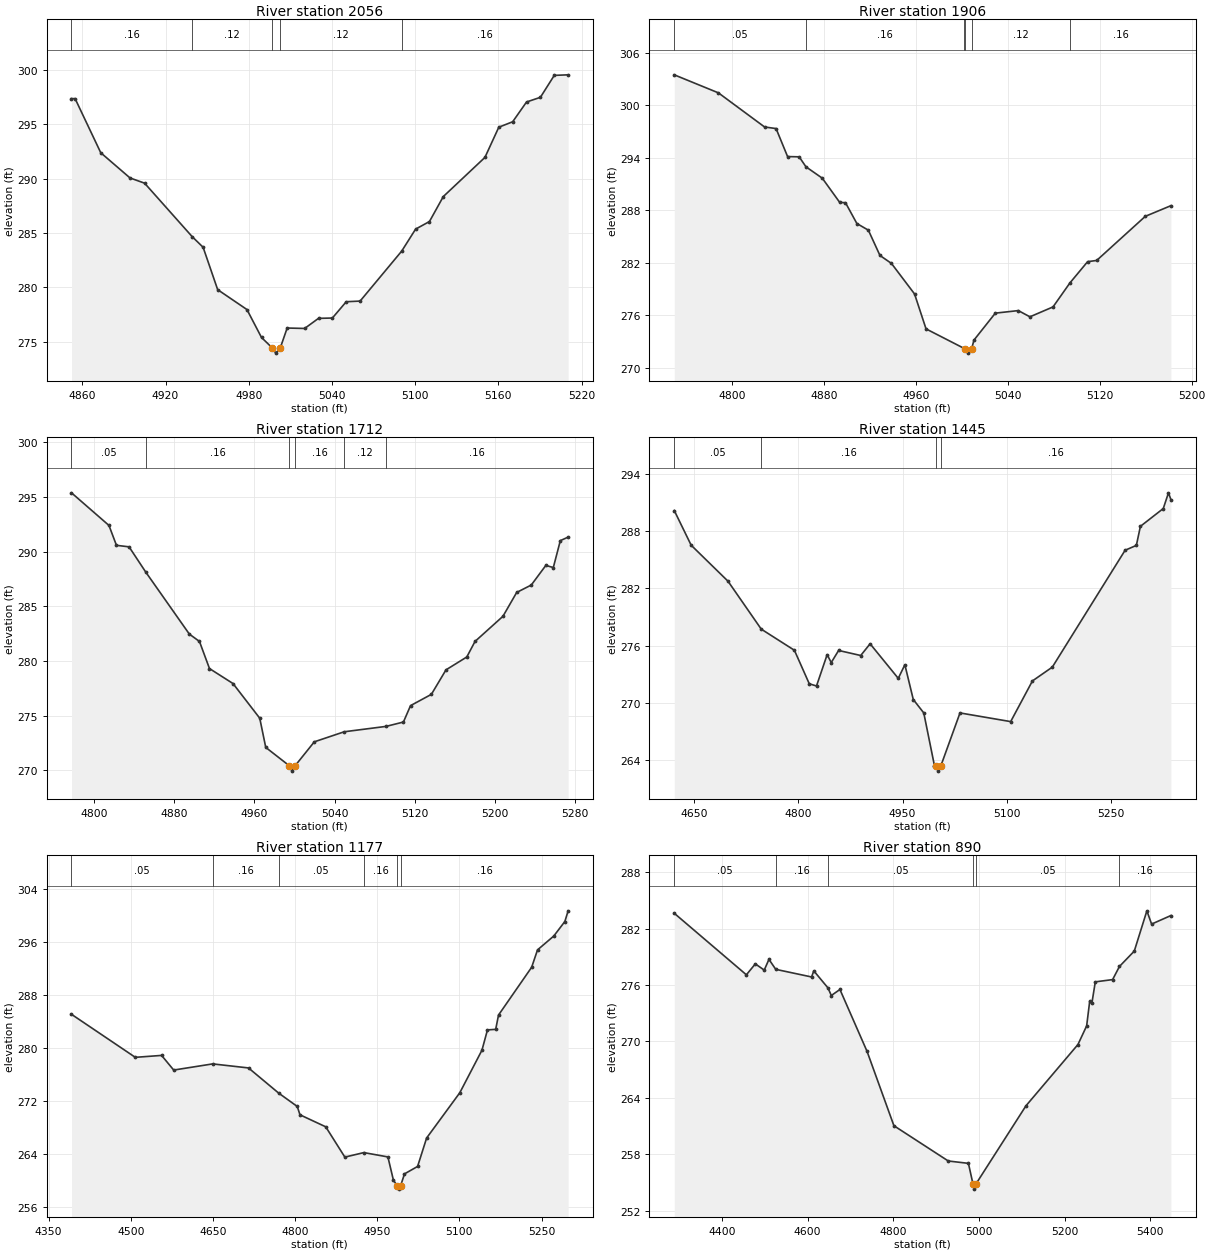
Type RM Length L Ch R = 1,2056,150,150,150
BEGIN DESCRIPTION:
UNT 172 IN CACR 2.0
END DESCRIPTION:
XS GIS Cut Line= 3
      3682849.62     10668360.19      3682699.61     10668310.19
      3682499.63     10668310.19
#Sta/Elev= 30
  4852.2  297.37  4854.8  297.37  4873.3  292.39  4894.4  290.07  4904.9  289.59
  4939.2  284.67  4947.1  283.69  4957.6  279.79  4978.7  277.96  4989.2  275.39
  4996.8  274.45  4999.5  273.95  5002.8  274.45  5007.7  276.26  5020.3  276.22
  5030.3  277.15  5040.3  277.18  5050.3  278.68  5060.3  278.74  5090.3  283.34
  5100.3  285.36  5110.3  286.06  5120.3  288.36  5150.3  291.96  5160.3  294.74
  5170.3  295.24  5180.3  297.06  5190.3  297.49  5200.3  299.51  5210.3  299.56
#Mann=5,-1,0
  4852.2    0.16       0  4939.2    0.12       0  4996.8    0.07       0
  5002.8    0.12       0  5090.3    0.16       0
Bank Sta=4996.8,5002.8
Exp/Cntr=0.3,0.1

Type RM Length L Ch R = 1,1906,194,194,194
BEGIN DESCRIPTION:
Mapping XS 94683551
END DESCRIPTION:
XS GIS Cut Line= 2
      3682967.87     10668142.46      3682537.36     10668180.65
#Sta/Elev= 30
  4749.7  303.49  4788.1  301.43  4828.3  297.53  4838.3  297.35  4848.3  294.15
  4858.4  294.12  4864.3  292.98  4878.5  291.68  4893.7  288.91  4898.7  288.88
  4908.6  286.50  4918.6  285.74  4928.7  282.85  4938.7  281.94  4958.8  278.45
  4968.8  274.46  5002.1  272.22  5002.5  272.19  5005.2  271.69  5008.5  272.19
  5010.5  273.18  5029.1  276.26  5049.1  276.55  5059.2  275.84  5079.3  276.97
  5094.0  279.71  5109.4  282.14  5117.3  282.28  5159.6  287.32  5181.9  288.54
#Mann=6,-1,0
  4749.7    0.05       0  4864.3    0.16       0  5002.1    0.12       0
  5002.5    0.07       0  5008.5    0.12       0  5094.0    0.16       0
Bank Sta=5002.5,5008.5
Exp/Cntr=0.3,0.1

Type RM Length L Ch R = 1,1712,267,267,267
BEGIN DESCRIPTION:
Mapping XS 693c30a4
END DESCRIPTION:
XS GIS Cut Line= 4
      3682886.88     10667989.40      3682692.68     10667972.04
      3682573.32     10668027.38      3682470.26     10668161.90
#Sta/Elev= 30
  4777.3  295.39  4814.7  292.41  4822.2  290.59  4834.8  290.45  4851.4  288.15
  4895.0  282.47  4905.1  281.80  4915.1  279.32  4938.6  277.95  4965.3  274.78
  4971.3  272.11  4994.7  270.44  4997.5  269.94  5000.7  270.44  5019.8  272.62
  5049.7  273.54  5091.4  274.03  5108.8  274.43  5115.9  275.93  5136.7  276.96
  5151.3  279.20  5172.1  280.38  5180.3  281.80  5208.2  284.10  5221.9  286.28
  5236.5  286.96  5251.0  288.75  5258.5  288.56  5265.5  291.02  5273.3  291.34
#Mann=6,-1,0
  4777.3    0.05       0  4851.4    0.16       0  4994.7    0.07       0
  5000.7    0.16       0  5049.7    0.12       0  5091.4    0.16       0
Bank Sta=4994.7,5000.7
Exp/Cntr=0.3,0.1

Type RM Length L Ch R = 1,1445,268,268,268
BEGIN DESCRIPTION:
Mapping XS e2cc2250
END DESCRIPTION:
XS GIS Cut Line= 4
      3682832.52     10667868.15      3682537.36     10667763.98
      3682454.02     10667899.40      3682353.98     10668120.18
#Sta/Elev= 30
  4621.7  290.17  4646.0  286.53  4699.0  282.75  4746.8  277.72  4794.5  275.50
  4815.9  271.98  4826.3  271.75  4841.6  275.04  4847.5  274.21  4858.1  275.48
  4889.9  274.95  4903.4  276.18  4943.9  272.55  4953.4  273.98  4965.5  270.33
  4980.6  268.92  4996.0  263.37  4998.9  263.31  5001.6  262.81  5004.9  263.31
  5032.7  268.92  5105.6  268.01  5136.9  272.28  5165.5  273.73  5270.2  286.00
  5286.4  286.51  5292.2  288.51  5325.1  290.38  5332.6  292.03  5336.1  291.32
#Mann=4,-1,0
  4621.7    0.05       0  4746.8    0.16       0  4998.9    0.07       0
  5004.9    0.16       0
Bank Sta=4998.9,5004.9
Exp/Cntr=0.3,0.1

Type RM Length L Ch R = 1,1177,287,287,287
BEGIN DESCRIPTION:
Mapping XS a749cf0b
END DESCRIPTION:
XS GIS Cut Line= 4
      3682802.25     10667799.51      3682553.79     10667697.52
      3682276.01     10667731.16      3682226.23     10668086.10
#Sta/Elev= 30
  4391.8  285.04  4508.3  278.55  4556.3  278.84  4578.4  276.63  4649.6  277.56
  4715.0  276.95  4770.0  273.16  4804.0  271.14  4809.0  269.88  4856.0  268.07
  4890.9  263.50  4925.6  264.18  4969.5  263.53  4979.6  260.01  4986.7  259.17
  4989.4  258.67  4992.7  259.17  4999.8  260.97  5023.7  262.09  5040.2  266.38
  5100.8  273.21  5141.2  279.62  5151.3  282.69  5166.3  282.77  5171.5  284.93
  5232.0  292.14  5242.7  294.76  5272.4  296.85  5292.6  299.04  5298.6  300.65
#Mann=6,-1,0
  4391.8    0.05       0  4649.6    0.16       0  4770.0    0.05       0
  4925.6    0.16       0  4986.7    0.07       0  4992.7    0.16       0
Bank Sta=4986.7,4992.7
Exp/Cntr=0.3,0.1

Type RM Length L Ch R = 1,890,0,0,0
BEGIN DESCRIPTION:
UNT 172 IN CACR 1.0
END DESCRIPTION:
XS GIS Cut Line= 4
      3682790.88     10667757.05      3682162.36     10667569.54
      3682085.97     10667638.98      3682026.95     10668034.77
#Sta/Elev= 30
  4289.0  283.62  4457.3  277.08  4478.2  278.24  4499.0  277.58  4510.0  278.72
  4525.9  277.66  4609.5  276.85  4614.7  277.50  4647.7  275.69  4655.6  274.88
  4675.7  275.52  4739.1  268.93  4801.7  261.04  4928.6  257.29  4975.6  257.04
  4986.5  254.80  4989.2  254.30  4992.5  254.80  5110.0  263.16  5231.3  269.67
  5251.6  271.65  5258.7  274.26  5263.7  274.03  5271.8  276.33  5312.2  276.57
  5328.2  277.97  5362.8  279.60  5392.2  283.88  5403.2  282.47  5448.3  283.38
#Mann=6,-1,0
  4289.0    0.05       0  4525.9    0.16       0  4647.7    0.05       0
  4986.5    0.03       0  4992.5    0.05       0  5328.2    0.16       0
Bank Sta=4986.5,4992.5
Exp/Cntr=0.3,0.1

Chan Stop Cuts=-1