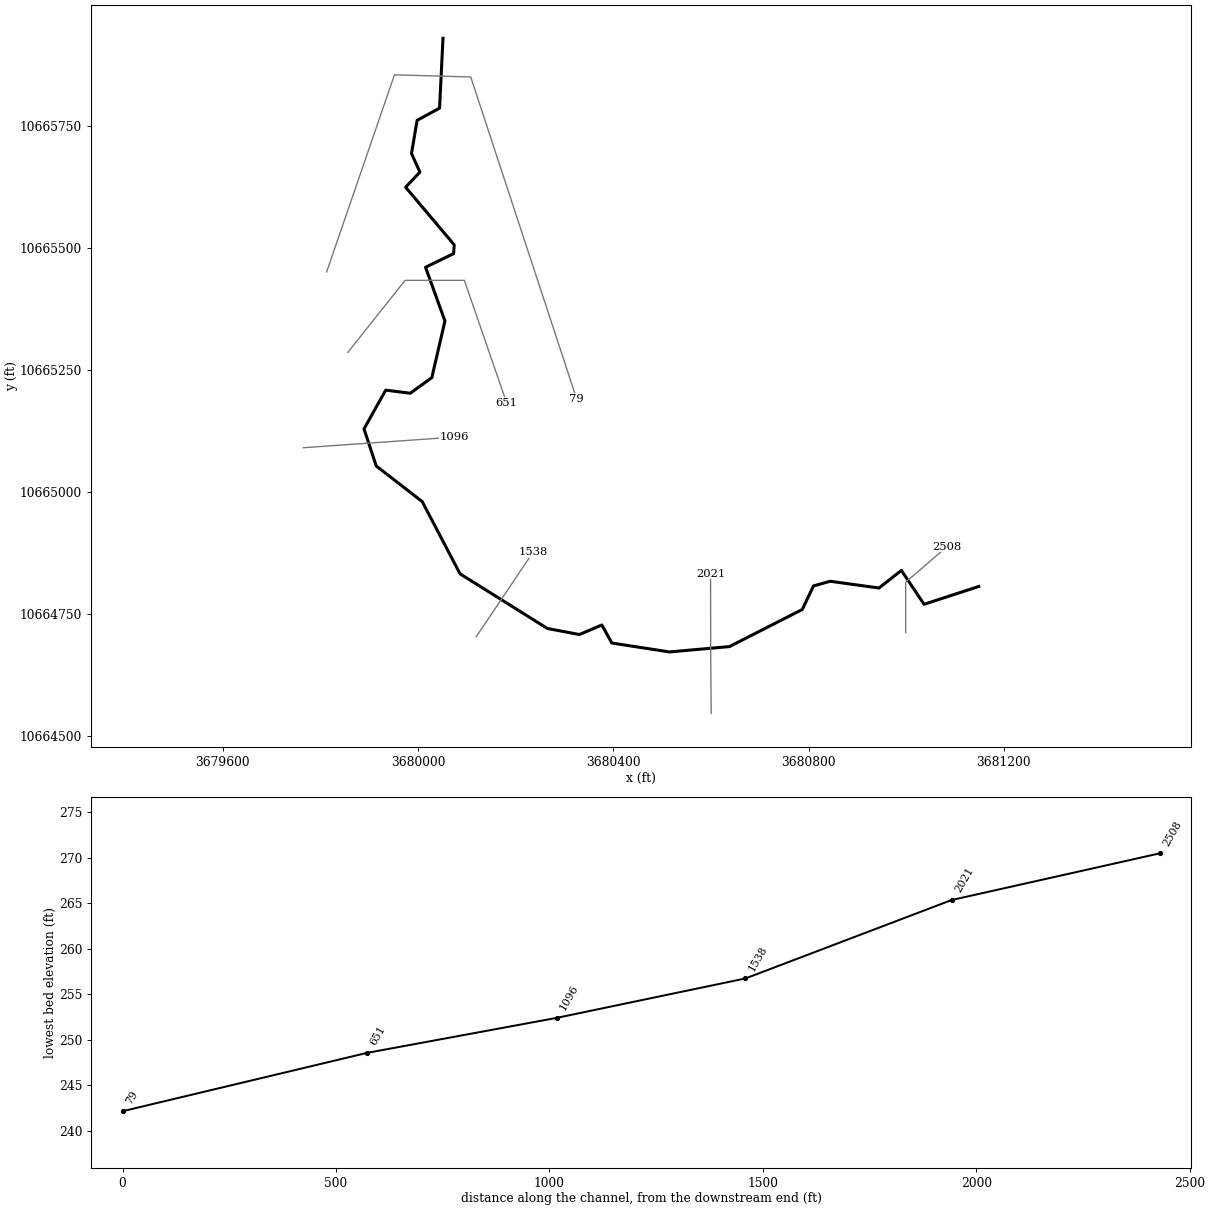
--- UNT 173 IN CACR.prj (project) ---

Proj Title=UNT 173 IN CACR Base Level Engineering
Current Plan=p01
Default Exp/Contr=0.3,0.1
English Units
Geom File=g01
Flow File=f01
Plan File=p01
BEGIN DESCRIPTION:
UNT 173 IN CACR
END DESCRIPTION:

--- UNT 173 IN CACR.p01 (plan) ---

Plan Title=Multiple Run
Short Identifier=Multiple
Geom File=g01
Flow File=f01
Subcritical Flow
K Sum by GR= 0
Std Step Tol= 0.01
Critical Tol= 0.01
Num of Std Step Trials= 20
Max Error Tol= 0.3
Flow Tol Ratio= 0.001
Split Flow NTrial= 30
Split Flow Tol= 0.02
Split Flow Ratio= 0.02
Log Output Level= 0
Friction Slope Method= 1
Unsteady Friction Slope Method= 2
Unsteady Bridges Friction Slope Method= 1
Parabolic Critical Depth
Global Vel Dist=  1 , 1 , 1
Global Log Level= 0
CheckData=True
Encroach Param= -1, 0, 0, 0
BEGIN DESCRIPTION:
Multiple Run
END DESCRIPTION:

--- UNT 173 IN CACR.f01 (steady flow) ---

Flow Title=Multiple
Number of Profiles=7
Profile Names=10-year,25-year,50-year,1pct_min,100-year,1pct_plu,500-year
River Rch & RM= UNT 173 IN CACR,Reach-1,2508
     159     198     228     194     262     354     347
Boundary for River Rch & Prof#=UNT 173 IN CACR,Reach-1,1
Up Type=0
Dn Type=3
Dn Slope=0.005
Boundary for River Rch & Prof#=UNT 173 IN CACR,Reach-1,2
Up Type=0
Dn Type=3
Dn Slope=0.005
Boundary for River Rch & Prof#=UNT 173 IN CACR,Reach-1,3
Up Type=0
Dn Type=3
Dn Slope=0.005
Boundary for River Rch & Prof#=UNT 173 IN CACR,Reach-1,4
Up Type=0
Dn Type=3
Dn Slope=0.005
Boundary for River Rch & Prof#=UNT 173 IN CACR,Reach-1,5
Up Type=0
Dn Type=3
Dn Slope=0.005
Boundary for River Rch & Prof#=UNT 173 IN CACR,Reach-1,6
Up Type=0
Dn Type=3
Dn Slope=0.005
Boundary for River Rch & Prof#=UNT 173 IN CACR,Reach-1,7
Up Type=0
Dn Type=3
Dn Slope=0.005

--- UNT 173 IN CACR.g01 (geometry) ---

Geom Title=Existing Conditions

River Reach=UNT 173 IN CACR,Reach-1
Reach XY= 30
      3681148.59     10664807.09      3681036.61     10664770.63
      3680990.25     10664840.00      3680944.25     10664804.00
      3680844.27     10664817.82      3680810.16     10664808.18
      3680787.24     10664760.01      3680638.00     10664684.00
      3680515.25     10664673.00      3680397.14     10664691.26
      3680376.57     10664728.24      3680330.73     10664708.70
      3680265.25     10664721.00      3680086.25     10664833.00
      3680008.75     10664981.00      3679914.50     10665054.00
      3679889.50     10665130.00      3679933.98     10665209.31
      3679984.25     10665203.00      3680028.42     10665235.01
      3680055.25     10665351.00      3680015.50     10665461.00
      3680073.00     10665489.00      3680074.25     10665507.00
      3679974.75     10665625.00      3680004.00     10665656.00
      3679986.75     10665694.00      3679998.25     10665762.00
      3680044.25     10665787.00      3680051.25     10665930.00

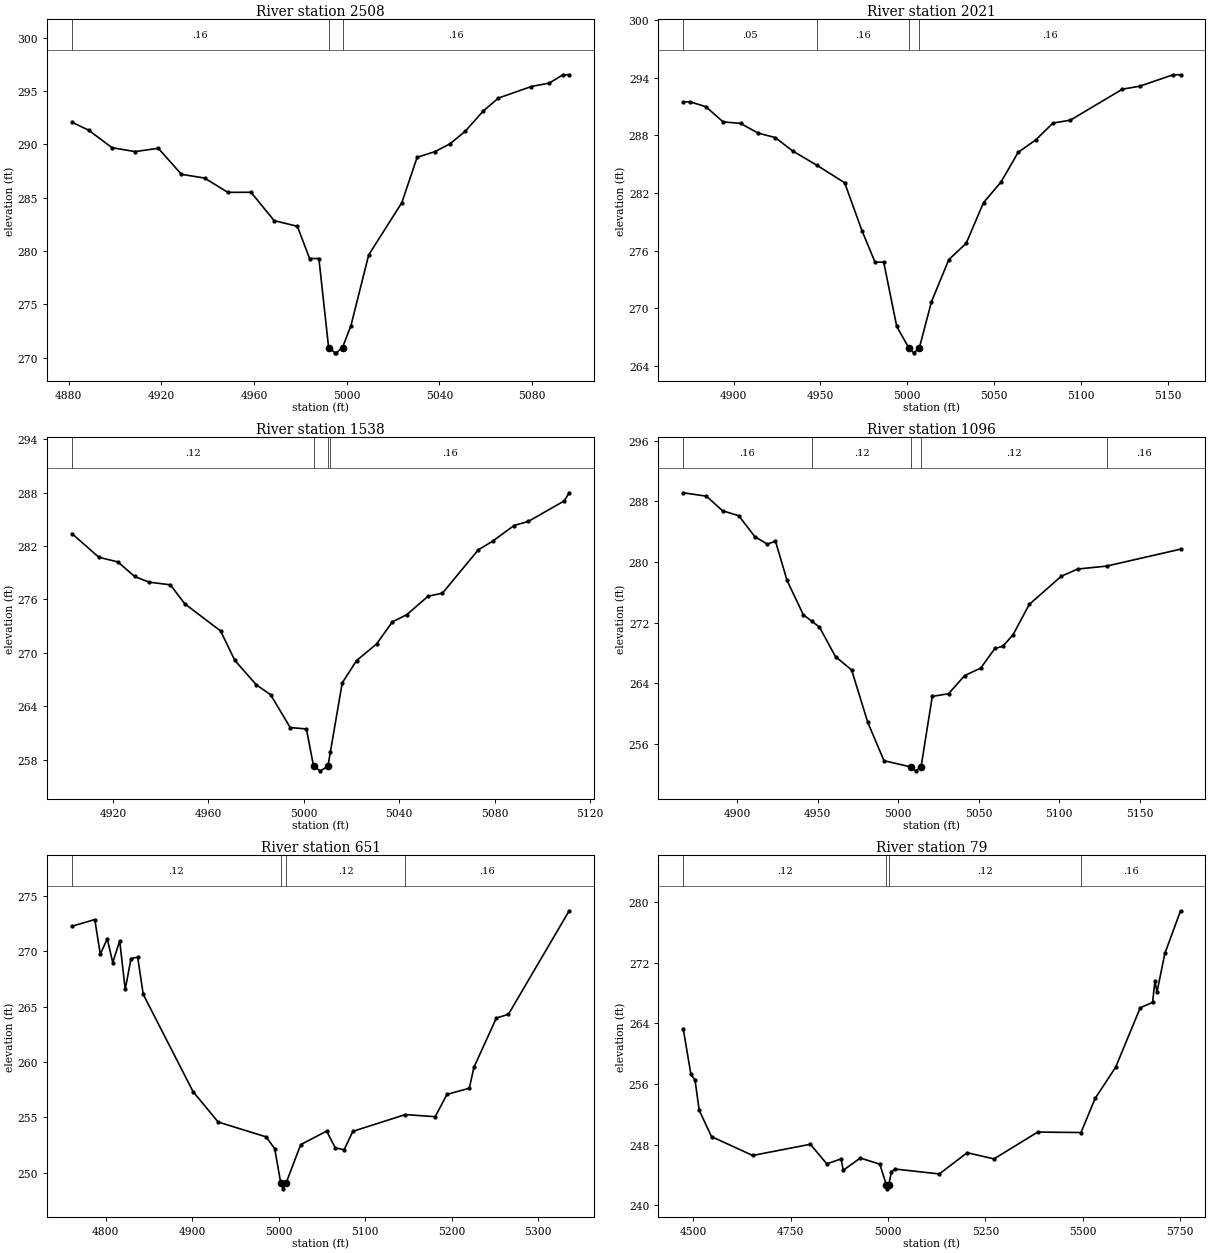
Type RM Length L Ch R = 1,2508,487,487,487
BEGIN DESCRIPTION:
Mapping XS 948aa2d8
END DESCRIPTION:
XS GIS Cut Line= 3
      3680998.94     10664712.89      3680998.94     10664815.79
      3681083.57     10664888.70
#Sta/Elev= 30
  4881.4  292.08  4888.7  291.32  4898.7  289.69  4908.7  289.32  4918.7  289.63
  4928.7  287.19  4938.7  286.84  4948.7  285.50  4958.7  285.51  4968.7  282.85
  4978.7  282.32  4984.0  279.30  4988.0  279.30  4992.2  270.96  4995.0  270.46
  4995.5  270.46  4998.2  270.96  5001.8  272.99  5009.5  279.64  5023.8  284.54
  5030.4  288.79  5038.0  289.31  5044.6  290.05  5051.2  291.24  5058.9  293.12
  5065.5  294.34  5079.7  295.42  5087.4  295.74  5093.3  296.52  5096.0  296.52
#Mann=3,-1,0
  4881.4    0.16       0  4992.2    0.07       0  4998.2    0.16       0
Bank Sta=4992.2,4998.2
Exp/Cntr=0.3,0.1

Type RM Length L Ch R = 1,2021,483,483,483
BEGIN DESCRIPTION:
UNT 173 IN CACR 4.0
END DESCRIPTION:
XS GIS Cut Line= 3
      3680600.65     10664547.16      3680599.61     10664660.19
      3680599.35     10664833.66
#Sta/Elev= 30
  4871.0  291.49  4875.0  291.49  4884.0  290.99  4894.0  289.40  4904.0  289.25
  4914.0  288.24  4924.0  287.77  4934.0  286.38  4948.1  284.87  4964.0  283.06
  4974.0  278.05  4981.5  274.79  4986.5  274.79  4994.0  268.09  5001.0  265.84
  5003.8  265.34  5007.0  265.84  5014.0  270.66  5024.0  275.05  5034.0  276.75
  5044.0  280.99  5054.0  283.12  5064.0  286.24  5074.0  287.51  5084.0  289.28
  5094.0  289.58  5124.0  292.81  5134.0  293.12  5153.2  294.31  5157.5  294.31
#Mann=4,-1,0
  4871.0    0.05       0  4948.1    0.16       0  5001.0    0.07       0
  5007.0    0.16       0
Bank Sta=5001,5007
Exp/Cntr=0.3,0.1

Type RM Length L Ch R = 1,1538,442,442,442
BEGIN DESCRIPTION:
UNT 173 IN CACR 3.0
END DESCRIPTION:
XS GIS Cut Line= 2
      3680119.40     10664704.19      3680235.59     10664877.19
#Sta/Elev= 30
  4902.8  283.42  4914.1  280.75  4922.1  280.22  4929.1  278.59  4935.1  277.95
  4944.1  277.65  4950.1  275.52  4965.1  272.47  4971.1  269.15  4980.1  266.40
  4986.1  265.29  4994.3  261.60  5001.1  261.44  5004.1  257.23  5006.9  256.73
  5010.1  257.23  5011.1  258.80  5016.1  266.62  5022.1  269.13  5030.5  271.00
  5037.1  273.48  5043.1  274.28  5052.1  276.37  5058.1  276.71  5073.1  281.58
  5079.1  282.55  5088.1  284.32  5094.1  284.78  5109.1  287.08  5111.2  288.00
#Mann=4,-1,0
  4902.8    0.12       0  5004.1    0.07       0  5010.1    0.12       0
  5011.1    0.16       0
Bank Sta=5004.1,5010.1
Exp/Cntr=0.3,0.1

Type RM Length L Ch R = 1,1096,445,445,445
BEGIN DESCRIPTION:
Mapping XS 03262983
END DESCRIPTION:
XS GIS Cut Line= 2
      3679765.24     10665091.33      3680073.38     10665113.02
#Sta/Elev= 30
  4866.4  289.15  4880.8  288.70  4890.8  286.78  4900.9  286.11  4910.9  283.35
  4918.6  282.36  4923.7  282.75  4930.9  277.56  4941.0  273.03  4946.1  272.20
  4951.0  271.40  4961.0  267.49  4971.0  265.73  4981.0  258.82  4991.1  253.74
  5008.1  252.90  5010.9  252.40  5014.1  252.90  5021.1  262.24  5031.2  262.59
  5041.2  264.99  5051.2  265.98  5060.0  268.58  5065.0  268.87  5071.3  270.40
  5081.3  274.39  5101.3  278.13  5111.4  279.07  5129.4  279.46  5175.3  281.70
#Mann=5,-1,0
  4866.4    0.16       0  4946.1    0.12       0  5008.1    0.07       0
  5014.1    0.12       0  5129.4    0.16       0
Bank Sta=5008.1,5014.1
Exp/Cntr=0.3,0.1

Type RM Length L Ch R = 1,651,572,572,572
BEGIN DESCRIPTION:
UNT 173 IN CACR 2.0
END DESCRIPTION:
XS GIS Cut Line= 4
      3679856.39     10665286.66      3679973.55     10665434.21
      3680095.08     10665434.21      3680181.42     10665183.81
#Sta/Elev= 30
  4761.0  272.24  4787.5  272.85  4793.9  269.72  4801.9  271.11  4808.3  268.97
  4816.3  270.93  4822.7  266.54  4829.4  269.33  4837.1  269.45  4843.5  266.10
  4901.2  257.31  4930.1  254.58  4985.5  253.24  4995.5  252.17  5002.5  249.05
  5005.2  248.55  5008.5  249.05  5025.5  252.54  5055.5  253.76  5065.5  252.24
  5075.7  252.08  5085.8  253.74  5146.4  255.25  5181.0  255.06  5194.5  257.07
  5220.4  257.63  5225.7  259.51  5251.6  263.96  5265.6  264.30  5335.8  273.64
#Mann=4,-1,0
  4761.0    0.12       0  5002.5    0.07       0  5008.5    0.12       0
  5146.4    0.16       0
Bank Sta=5002.5,5008.5
Exp/Cntr=0.3,0.1

Type RM Length L Ch R = 1,79,0,0,0
BEGIN DESCRIPTION:
UNT 173 IN CACR 1.0
END DESCRIPTION:
XS GIS Cut Line= 4
      3679812.96     10665451.56      3679951.85     10665855.21
      3680108.10     10665850.87      3680324.87     10665191.90
#Sta/Elev= 30
  4474.0  263.31  4493.7  257.28  4504.3  256.52  4515.0  252.54  4546.6  249.05
  4652.3  246.56  4800.4  248.04  4842.6  245.45  4879.2  246.10  4885.0  244.60
  4928.6  246.22  4978.7  245.41  4995.7  242.65  4998.4  242.15  5001.7  242.65
  5008.7  244.44  5018.7  244.76  5131.6  244.12  5203.0  246.92  5271.9  246.11
  5384.2  249.65  5495.3  249.59  5531.6  254.10  5584.3  258.22  5647.4  266.08
  5679.0  266.78  5685.2  269.61  5690.4  268.16  5710.6  273.25  5750.9  278.89
#Mann=4,-1,0
  4474.0    0.12       0  4995.7    0.07       0  5001.7    0.12       0
  5495.3    0.16       0
Bank Sta=4995.7,5001.7
Exp/Cntr=0.3,0.1

Chan Stop Cuts=-1