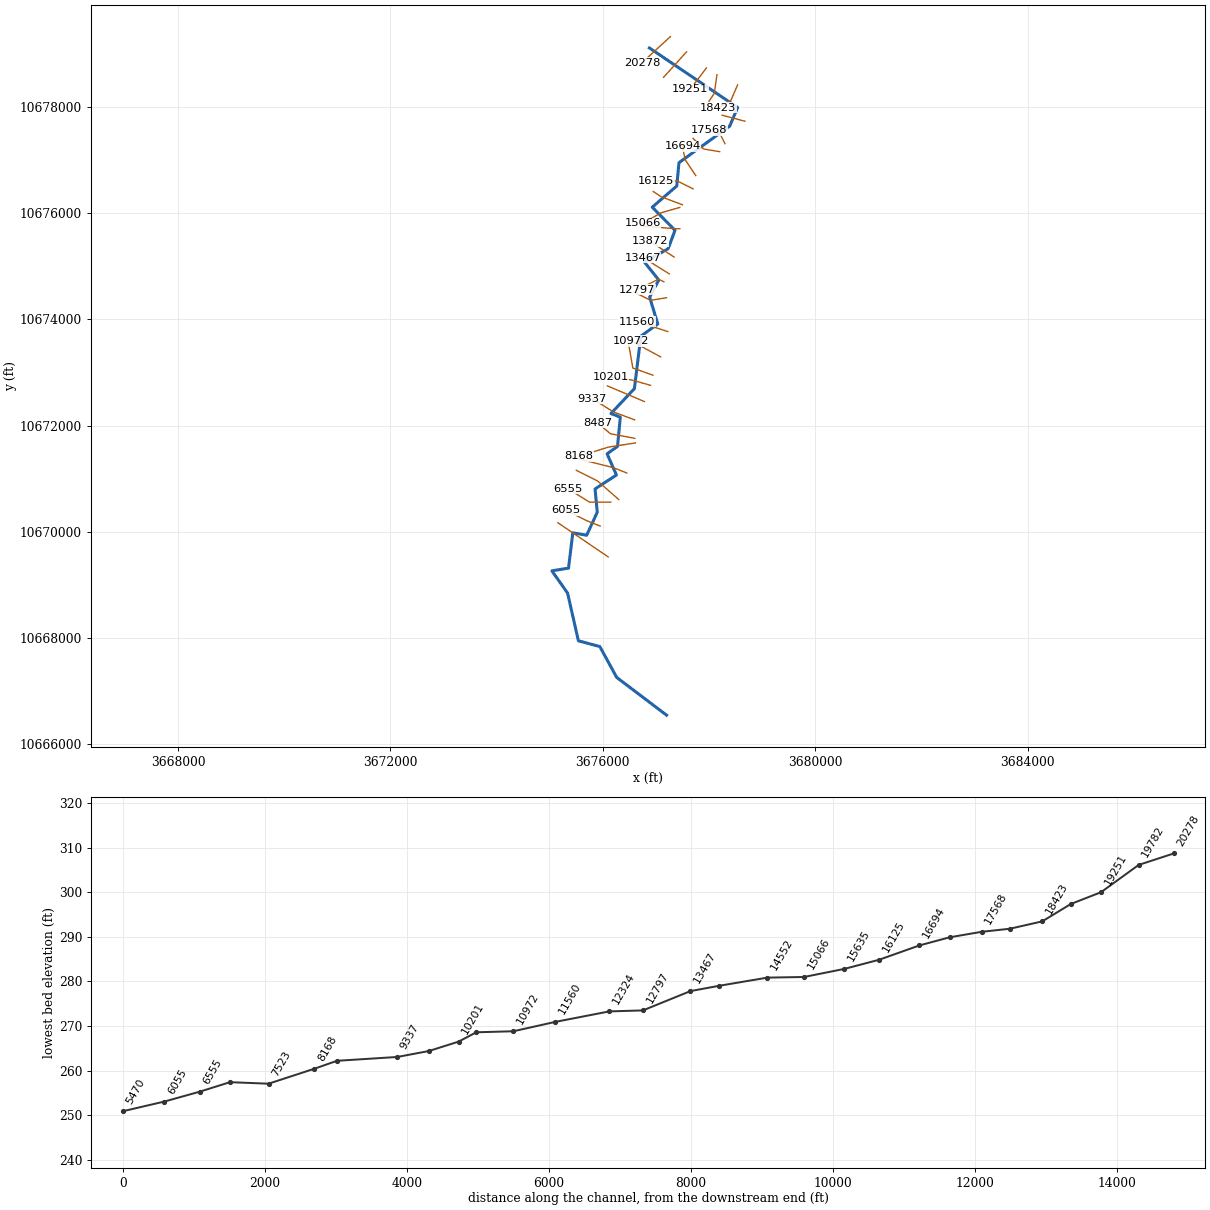
--- UNT 174 IN CACR.prj (project) ---

Proj Title=UNT 174 IN CACR Base Level Engineering
Current Plan=p01
Default Exp/Contr=0.3,0.1
English Units
Geom File=g01
Flow File=f01
Plan File=p01
BEGIN DESCRIPTION:
UNT 174 IN CACR
END DESCRIPTION:

--- UNT 174 IN CACR.p01 (plan) ---

Plan Title=Multiple Run
Short Identifier=Multiple
Geom File=g01
Flow File=f01
Subcritical Flow
K Sum by GR= 0
Std Step Tol= 0.01
Critical Tol= 0.01
Num of Std Step Trials= 20
Max Error Tol= 0.3
Flow Tol Ratio= 0.001
Split Flow NTrial= 30
Split Flow Tol= 0.02
Split Flow Ratio= 0.02
Log Output Level= 0
Friction Slope Method= 1
Unsteady Friction Slope Method= 2
Unsteady Bridges Friction Slope Method= 1
Parabolic Critical Depth
Global Vel Dist=  1 , 1 , 1
Global Log Level= 0
CheckData=True
Encroach Param= -1, 0, 0, 0
BEGIN DESCRIPTION:
Multiple Run
END DESCRIPTION:

--- UNT 174 IN CACR.f01 (steady flow) ---

Flow Title=Multiple
Number of Profiles=7
Profile Names=10-year,25-year,50-year,1pct_min,100-year,1pct_plu,500-year
River Rch & RM= UNT 174 IN CACR,Reach-1,20278
     363     473     560     488     659     892     917
River Rch & RM= UNT 174 IN CACR,Reach-1,16125
     489     646     772     677     915    1238    1293
River Rch & RM= UNT 174 IN CACR,Reach-1,15066
     742    1015    1241    1114    1507    2038    2232
River Rch & RM= UNT 174 IN CACR,Reach-1,10450
     790    1082    1325    1191    1610    2178    2389
River Rch & RM= UNT 174 IN CACR,Reach-1,7523
    1009    1396    1719    1552    2099    2839    3145
Boundary for River Rch & Prof#=UNT 174 IN CACR,Reach-1,1
Up Type=0
Dn Type=3
Dn Slope=0.005
Boundary for River Rch & Prof#=UNT 174 IN CACR,Reach-1,2
Up Type=0
Dn Type=3
Dn Slope=0.005
Boundary for River Rch & Prof#=UNT 174 IN CACR,Reach-1,3
Up Type=0
Dn Type=3
Dn Slope=0.005
Boundary for River Rch & Prof#=UNT 174 IN CACR,Reach-1,4
Up Type=0
Dn Type=3
Dn Slope=0.005
Boundary for River Rch & Prof#=UNT 174 IN CACR,Reach-1,5
Up Type=0
Dn Type=3
Dn Slope=0.005
Boundary for River Rch & Prof#=UNT 174 IN CACR,Reach-1,6
Up Type=0
Dn Type=3
Dn Slope=0.005
Boundary for River Rch & Prof#=UNT 174 IN CACR,Reach-1,7
Up Type=0
Dn Type=3
Dn Slope=0.005

--- UNT 174 IN CACR.g01 (geometry) ---

Geom Title=Existing Conditions

River Reach=UNT 174 IN CACR,Reach-1
Reach XY= 30
      3676877.12     10679113.14      3678538.75     10677991.00
      3678388.50     10677641.00      3677434.00     10676953.00
      3677392.00     10676514.00      3676930.50     10676115.00
      3677358.75     10675680.00      3677230.25     10675333.00
      3676784.25     10675080.00      3677053.50     10674744.00
      3676881.75     10674420.00      3677035.25     10673916.00
      3676716.50     10673687.00      3676594.25     10672698.00
      3676152.75     10672229.00      3676329.75     10672162.00
      3676276.25     10671611.00      3676080.25     10671470.00
      3676256.25     10671072.00      3675853.50     10670809.00
      3675895.00     10670371.00      3675696.00     10669938.00
      3675434.75     10669983.00      3675353.75     10669318.00
      3675040.75     10669267.00      3675336.25     10668848.00
      3675540.00     10667950.00      3675944.00     10667841.00
      3676260.75     10667261.00      3677199.50     10666550.00

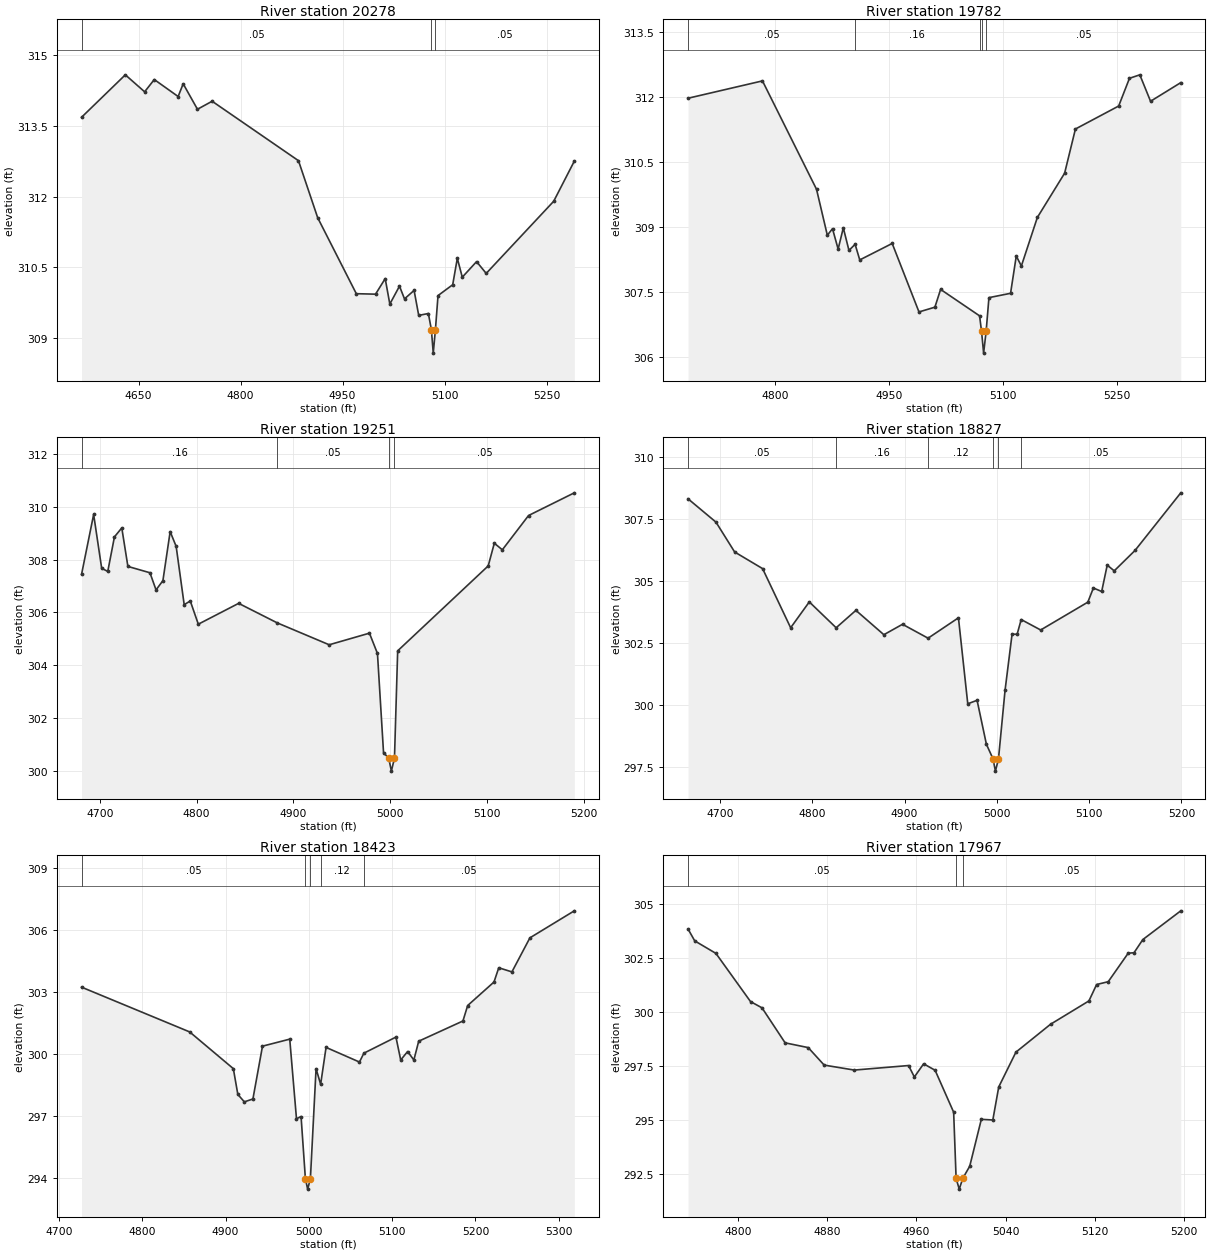
Type RM Length L Ch R = 1,20278,496,496,496
BEGIN DESCRIPTION:
UNT 174 IN CACR 40.0
END DESCRIPTION:
XS GIS Cut Line= 2
      3677273.38     10679327.57      3676739.55     10678837.15
#Sta/Elev= 30
  4566.0  313.68  4630.4  314.58  4658.8  314.22  4673.0  314.48  4708.1  314.12
  4715.5  314.39  4736.5  313.85  4758.1  314.02  4885.1  312.76  4913.4  311.55
  4970.2  309.94  4998.5  309.93  5012.7  310.26  5019.5  309.72  5033.7  310.10
  5041.1  309.83  5055.2  310.01  5062.0  309.48  5076.2  309.52  5080.6  309.18
  5083.4  308.68  5086.6  309.18  5090.4  309.90  5112.0  310.13  5118.8  310.69
  5126.1  310.29  5147.1  310.62  5161.3  310.37  5260.6  311.90  5290.9  312.75
#Mann=3,-1,0
  4566.0    0.05       0  5080.6    0.03       0  5086.6    0.05       0
Bank Sta=5080.6,5086.6
Exp/Cntr=0.3,0.1

Type RM Length L Ch R = 1,19782,531,531,531
BEGIN DESCRIPTION:
UNT 174 IN CACR 39.0
END DESCRIPTION:
XS GIS Cut Line= 2
      3677577.19     10679041.10      3677143.93     10678560.18
#Sta/Elev= 30
  4686.1  311.98  4783.9  312.38  4854.9  309.88  4869.1  308.82  4875.9  308.97
  4883.3  308.50  4890.1  308.99  4897.5  308.47  4905.6  308.61  4911.7  308.25
  4954.3  308.63  4989.5  307.05  5010.4  307.16  5017.9  307.57  5069.1  306.96
  5071.7  306.60  5074.4  306.10  5077.7  306.60  5081.4  307.38  5109.8  307.48
  5117.3  308.34  5124.0  308.11  5145.0  309.23  5180.8  310.25  5195.0  311.27
  5251.8  311.80  5266.0  312.44  5279.6  312.52  5293.7  311.91  5333.4  312.34
#Mann=5,-1,0
  4686.1    0.05       0  4905.6    0.16       0  5069.1    0.05       0
  5071.7    0.07       0  5077.7    0.05       0
Bank Sta=5071.7,5077.7
Exp/Cntr=0.3,0.1

Type RM Length L Ch R = 1,19251,424,424,424
BEGIN DESCRIPTION:
UNT 174 IN CACR 38.0
END DESCRIPTION:
XS GIS Cut Line= 2
      3677950.50     10678737.34      3677643.48     10678330.86
#Sta/Elev= 30
  4681.0  307.44  4693.5  309.71  4701.8  307.67  4708.1  307.55  4715.0  308.86
  4722.6  309.20  4728.9  307.74  4751.7  307.50  4758.0  306.85  4765.1  307.20
  4772.6  309.06  4778.8  308.50  4787.1  306.29  4793.4  306.43  4801.7  305.55
  4843.4  306.34  4883.3  305.60  4937.0  304.77  4978.6  305.21  4986.9  304.44
  4993.2  300.67  4998.5  300.48  5001.3  299.98  5004.5  300.48  5007.8  304.54
  5101.4  307.76  5107.7  308.62  5116.0  308.37  5143.1  309.67  5190.4  310.53
#Mann=4,-1,0
  4681.0    0.16       0  4883.3    0.05       0  4998.5    0.03       0
  5004.5    0.05       0
Bank Sta=4998.5,5004.5
Exp/Cntr=0.3,0.1

Type RM Length L Ch R = 1,18827,404,404,404
BEGIN DESCRIPTION:
UNT 174 IN CACR 37.0
END DESCRIPTION:
XS GIS Cut Line= 3
      3678149.61     10678610.23      3678099.61     10678260.19
      3677999.59     10678110.16
#Sta/Elev= 30
  4665.4  308.31  4695.7  307.37  4715.9  306.17  4746.2  305.50  4776.6  303.12
  4796.8  304.16  4825.9  303.12  4847.3  303.82  4877.6  302.84  4897.8  303.26
  4925.5  302.70  4958.4  303.52  4968.5  300.06  4978.6  300.20  4988.7  298.43
  4995.8  297.85  4998.5  297.35  5001.8  297.85  5008.9  300.60  5016.5  302.86
  5022.0  302.86  5026.4  303.45  5047.5  303.03  5098.6  304.15  5104.6  304.72
  5113.6  304.58  5119.6  305.64  5127.2  305.41  5149.7  306.23  5199.3  308.55
#Mann=6,-1,0
  4665.4    0.05       0  4825.9    0.16       0  4925.5    0.12       0
  4995.8    0.07       0  5001.8    0.12       0  5026.4    0.05       0
Bank Sta=4995.8,5001.8
Exp/Cntr=0.3,0.1

Type RM Length L Ch R = 1,18423,456,456,456
BEGIN DESCRIPTION:
UNT 174 IN CACR 36.0
END DESCRIPTION:
XS GIS Cut Line= 3
      3678538.34     10678419.45      3678410.73     10678125.16
      3678176.31     10677989.72
#Sta/Elev= 30
  4727.2  303.24  4857.0  301.07  4909.4  299.29  4914.8  298.04  4922.6  297.68
  4932.9  297.82  4944.4  300.38  4977.1  300.72  4985.2  296.86  4990.7  296.97
  4995.9  293.95  4998.6  293.45  5001.9  293.95  5008.7  299.29  5014.2  298.53
  5020.7  300.32  5060.8  299.61  5066.1  300.04  5104.6  300.82  5110.3  299.71
  5118.6  300.12  5126.1  299.71  5131.9  300.62  5185.0  301.60  5190.7  302.35
  5222.3  303.49  5228.0  304.18  5243.8  303.98  5265.4  305.63  5318.7  306.94
#Mann=5,-1,0
  4727.2    0.05       0  4995.9    0.03       0  5001.9    0.05       0
  5014.2    0.12       0  5066.1    0.05       0
Bank Sta=4995.9,5001.9
Exp/Cntr=0.3,0.1

Type RM Length L Ch R = 1,17967,399,399,399
BEGIN DESCRIPTION:
UNT 174 IN CACR 35.0
END DESCRIPTION:
XS GIS Cut Line= 2
      3678673.78     10677734.53      3678246.71     10677846.51
#Sta/Elev= 30
  4755.4  303.84  4761.4  303.29  4780.4  302.71  4811.4  300.48  4821.7  300.19
  4842.4  298.57  4863.1  298.35  4877.4  297.54  4904.4  297.31  4953.0  297.52
  4958.2  296.99  4966.5  297.60  4976.8  297.30  4993.4  295.36  4995.6  292.30
  4998.4  291.80  5001.6  292.30  5007.8  292.86  5018.2  295.03  5028.5  295.00
  5033.8  296.53  5049.2  298.14  5080.2  299.43  5114.6  300.51  5121.5  301.27
  5131.9  301.40  5149.8  302.72  5155.0  302.74  5162.9  303.35  5196.9  304.68
#Mann=3,-1,0
  4755.4    0.05       0  4995.6    0.03       0  5001.6    0.05       0
Bank Sta=4995.6,5001.6
Exp/Cntr=0.3,0.1

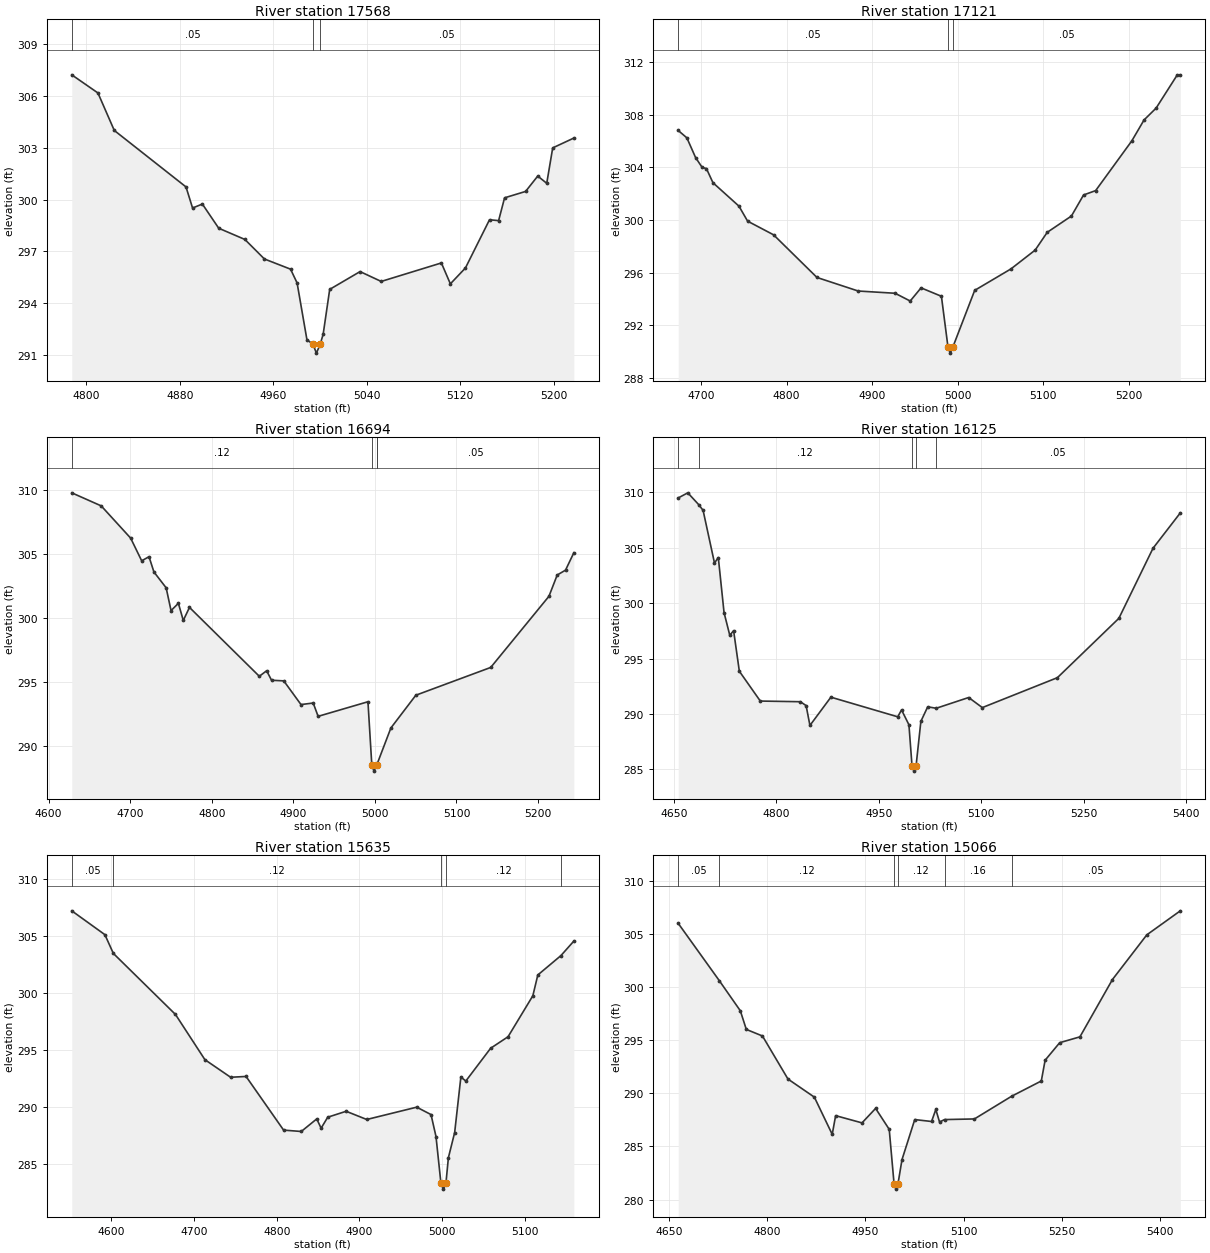
Type RM Length L Ch R = 1,17568,447,447,447
BEGIN DESCRIPTION:
UNT 174 IN CACR 34.0
END DESCRIPTION:
XS GIS Cut Line= 3
      3678299.62     10677310.17      3678199.61     10677510.19
      3677999.59     10677560.19
#Sta/Elev= 30
  4787.6  307.22  4810.0  306.17  4824.0  304.00  4885.4  300.73  4891.0  299.51
  4899.4  299.74  4913.4  298.34  4935.8  297.69  4952.5  296.56  4974.9  295.97
  4980.5  295.17  4988.9  291.89  4994.2  291.61  4997.0  291.11  5000.2  291.61
  5002.8  292.20  5008.4  294.80  5034.4  295.83  5052.5  295.26  5104.0  296.33
  5111.7  295.12  5124.6  296.04  5145.2  298.83  5153.0  298.78  5158.1  300.10
  5176.1  300.47  5186.5  301.36  5194.2  300.94  5199.3  302.99  5217.4  303.56
#Mann=3,-1,0
  4787.6    0.05       0  4994.2    0.03       0  5000.2    0.05       0
Bank Sta=4994.2,5000.2
Exp/Cntr=0.3,0.1

Type RM Length L Ch R = 1,17121,427,427,427
BEGIN DESCRIPTION:
UNT 174 IN CACR 33.0
END DESCRIPTION:
XS GIS Cut Line= 3
      3678199.62     10677160.19      3677899.61     10677210.19
      3677699.60     10677410.20
#Sta/Elev= 30
  4673.3  306.81  4683.4  306.25  4693.6  304.75  4701.2  304.01  4706.3  303.91
  4713.9  302.84  4744.3  301.06  4754.4  299.92  4784.8  298.88  4835.5  295.64
  4883.7  294.61  4926.8  294.44  4944.5  293.85  4957.2  294.85  4981.0  294.21
  4988.6  290.39  4991.3  289.89  4994.6  290.39  5019.9  294.66  5062.3  296.29
  5090.6  297.72  5104.7  299.07  5133.0  300.31  5147.2  301.91  5161.3  302.24
  5203.7  306.03  5217.9  307.61  5232.0  308.51  5256.8  311.04  5260.3  311.04
#Mann=3,-1,0
  4673.3    0.05       0  4988.6    0.03       0  4994.6    0.05       0
Bank Sta=4988.6,4994.6
Exp/Cntr=0.3,0.1

Type RM Length L Ch R = 1,16694,569,569,569
BEGIN DESCRIPTION:
UNT 174 IN CACR 32.0
END DESCRIPTION:
XS GIS Cut Line= 3
      3677749.63     10676710.16      3677549.61     10677010.19
      3677499.62     10677260.14
#Sta/Elev= 30
  4628.4  309.81  4664.5  308.79  4700.6  306.27  4714.1  304.50  4723.1  304.82
  4729.1  303.63  4744.1  302.39  4750.1  300.61  4759.1  301.18  4765.1  299.84
  4772.7  300.86  4858.3  295.48  4867.3  295.91  4873.3  295.17  4888.3  295.12
  4909.4  293.27  4924.4  293.39  4930.4  292.35  4991.5  293.49  4996.2  288.57
  4998.9  288.07  5002.2  288.57  5003.0  288.67  5019.6  291.44  5050.2  294.00
  5142.0  296.17  5213.4  301.73  5223.5  303.39  5233.7  303.77  5243.9  305.13
#Mann=4,-1,0
  4628.4    0.12       0  4996.2    0.07       0  5002.2    0.12       0
  5003.0    0.05       0
Bank Sta=4996.2,5002.2
Exp/Cntr=0.3,0.1

Type RM Length L Ch R = 1,16125,490,490,490
BEGIN DESCRIPTION:
UNT 174 IN CACR 31.0
END DESCRIPTION:
XS GIS Cut Line= 3
      3677699.64     10676460.17      3677399.61     10676610.19
      3676999.65     10676610.19
#Sta/Elev= 30
  4656.4  309.49  4670.4  309.95  4686.3  308.89  4692.8  308.37  4709.5  303.62
  4715.1  304.11  4723.5  299.15  4731.9  297.10  4737.5  297.52  4745.9  293.86
  4776.6  291.17  4835.3  291.11  4843.7  290.76  4849.3  288.97  4880.0  291.52
  4977.9  289.75  4983.5  290.37  4994.3  289.03  4998.8  285.35  5001.6  284.85
  5004.8  285.35  5011.8  289.34  5021.8  290.65  5034.3  290.52  5081.8  291.49
  5101.8  290.58  5211.8  293.28  5301.8  298.63  5351.8  304.95  5391.8  308.14
#Mann=5,-1,0
  4656.4    0.05       0  4686.3    0.12       0  4998.8    0.07       0
  5004.8    0.12       0  5034.3    0.05       0
Bank Sta=4998.8,5004.8
Exp/Cntr=0.3,0.1

Type RM Length L Ch R = 1,15635,569,569,569
BEGIN DESCRIPTION:
UNT 174 IN CACR 30.0
END DESCRIPTION:
XS GIS Cut Line= 3
      3677499.61     10676160.19      3677099.61     10676310.19
      3676949.59     10676410.20
#Sta/Elev= 30
  4552.0  307.18  4592.1  305.09  4602.3  303.45  4677.5  298.10  4713.1  294.14
  4744.2  292.60  4762.9  292.67  4808.3  287.97  4829.7  287.85  4848.4  288.95
  4853.7  288.14  4861.7  289.10  4884.0  289.62  4908.9  288.90  4969.4  289.98
  4986.7  289.33  4992.7  287.41  4998.7  283.30  5001.5  282.80  5004.7  283.30
  5007.7  285.55  5015.3  287.76  5022.8  292.62  5028.8  292.27  5058.8  295.14
  5079.9  296.15  5109.9  299.74  5115.9  301.56  5143.9  303.26  5159.5  304.53
#Mann=5,-1,0
  4552.0    0.05       0  4602.3    0.12       0  4998.7    0.07       0
  5004.7    0.12       0  5143.9    0.16       0
Bank Sta=4998.7,5004.7
Exp/Cntr=0.3,0.1

Type RM Length L Ch R = 1,15066,514,514,514
BEGIN DESCRIPTION:
UNT 174 IN CACR 29.0
END DESCRIPTION:
XS GIS Cut Line= 3
      3677449.65     10676110.20      3677099.61     10676010.19
      3676749.57     10675810.17
#Sta/Elev= 30
  4663.9  305.98  4726.7  300.59  4758.8  297.76  4767.9  296.01  4792.6  295.39
  4831.6  291.34  4871.9  289.64  4899.2  286.14  4904.4  287.90  4944.7  287.22
  4965.5  288.58  4986.3  286.61  4993.7  281.49  4996.5  280.99  4999.7  281.49
  5005.8  283.76  5025.3  287.53  5051.0  287.35  5057.5  288.48  5063.2  287.30
  5070.8  287.53  5116.5  287.59  5173.2  289.72  5218.7  291.16  5224.5  293.11
  5246.8  294.76  5277.7  295.31  5327.4  300.70  5379.9  304.90  5431.1  307.16
#Mann=6,-1,0
  4663.9    0.05       0  4726.7    0.12       0  4993.7    0.07       0
  4999.7    0.12       0  5070.8    0.16       0  5173.2    0.05       0
Bank Sta=4993.7,4999.7
Exp/Cntr=0.3,0.1

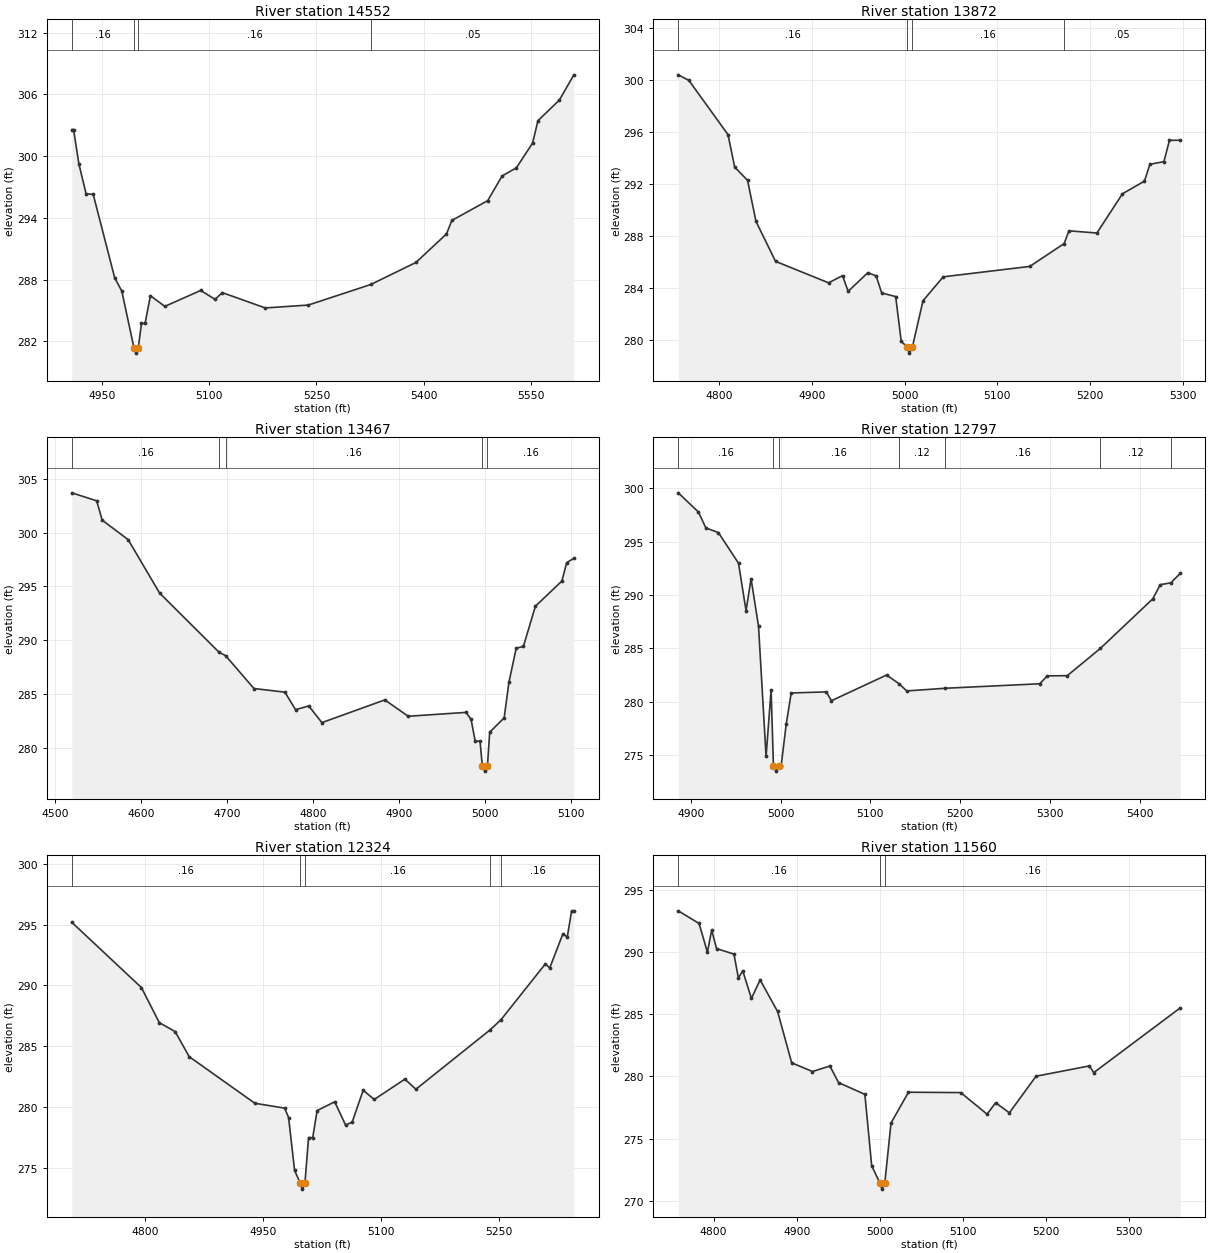
Type RM Length L Ch R = 1,14552,680,680,680
BEGIN DESCRIPTION:
UNT 174 IN CACR 28.0
END DESCRIPTION:
XS GIS Cut Line= 3
      3677449.62     10675710.19      3677349.61     10675710.19
      3676749.60     10675760.19
#Sta/Elev= 30
  4907.8  302.57  4910.3  302.57  4917.8  299.22  4927.8  296.34  4937.8  296.27
  4967.8  288.17  4977.8  286.87  4994.8  281.35  4997.6  280.85  5000.8  281.35
  5005.3  283.74  5010.3  283.74  5017.8  286.43  5037.9  285.39  5088.1  286.94
  5108.2  286.07  5118.2  286.73  5178.4  285.24  5238.6  285.52  5326.0  287.52
  5389.1  289.66  5431.8  292.43  5439.3  293.74  5489.5  295.67  5509.5  298.06
  5529.6  298.86  5552.2  301.26  5559.7  303.43  5589.8  305.45  5609.9  307.89
#Mann=4,-1,0
  4907.8    0.16       0  4994.8    0.07       0  5000.8    0.16       0
  5326.0    0.05       0
Bank Sta=4994.8,5000.8
Exp/Cntr=0.3,0.1

Type RM Length L Ch R = 1,13872,405,405,405
BEGIN DESCRIPTION:
UNT 174 IN CACR 27.0
END DESCRIPTION:
XS GIS Cut Line= 2
      3677340.54     10675176.42      3676887.43     10675473.28
#Sta/Elev= 30
  4755.8  300.43  4767.3  300.00  4809.5  295.83  4816.7  293.33  4830.6  292.31
  4839.7  289.15  4860.8  286.08  4918.0  284.43  4933.1  284.98  4939.1  283.77
  4960.2  285.20  4969.3  284.97  4975.3  283.65  4990.4  283.37  4996.4  279.92
  5002.5  279.52  5005.3  279.02  5008.5  279.52  5019.9  283.05  5041.7  284.89
  5135.1  285.69  5172.2  287.45  5177.3  288.43  5207.5  288.26  5235.1  291.28
  5258.8  292.25  5264.7  293.55  5279.8  293.75  5285.8  295.39  5297.5  295.40
#Mann=4,-1,0
  4755.8    0.16       0  5002.5    0.07       0  5008.5    0.16       0
  5172.2    0.05       0
Bank Sta=5002.5,5008.5
Exp/Cntr=0.3,0.1

Type RM Length L Ch R = 1,13467,670,670,670
BEGIN DESCRIPTION:
UNT 174 IN CACR 26.0
END DESCRIPTION:
XS GIS Cut Line= 3
      3677249.65     10674860.16      3676849.61     10675110.19
      3676749.65     10675160.17
#Sta/Elev= 30
  4519.4  303.70  4548.3  302.96  4554.8  301.16  4584.9  299.35  4621.5  294.38
  4690.6  288.88  4698.1  288.57  4731.1  285.51  4767.1  285.17  4779.5  283.54
  4794.8  283.89  4810.1  282.34  4883.2  284.45  4910.4  282.93  4977.6  283.29
  4983.5  282.63  4988.2  280.62  4993.9  280.62  4996.5  278.33  4999.3  277.83
  5002.5  278.33  5005.1  281.45  5021.9  282.78  5027.5  286.11  5035.9  289.25
  5044.3  289.43  5058.2  293.16  5089.0  295.50  5094.6  297.21  5102.9  297.61
#Mann=5,-1,0
  4519.4    0.16       0  4690.6    0.12       0  4698.1    0.16       0
  4996.5    0.07       0  5002.5    0.16       0
Bank Sta=4996.5,5002.5
Exp/Cntr=0.3,0.1

Type RM Length L Ch R = 1,12797,473,473,473
BEGIN DESCRIPTION:
UNT 174 IN CACR 25.0
END DESCRIPTION:
XS GIS Cut Line= 3
      3677149.61     10674710.19      3677049.61     10674760.19
      3676649.63     10674560.20
#Sta/Elev= 30
  4886.1  299.56  4908.5  297.77  4916.9  296.27  4930.8  295.84  4953.2  292.97
  4961.6  288.53  4967.2  291.51  4975.5  287.06  4983.9  274.87  4989.5  281.12
  4992.1  274.00  4994.9  273.50  4998.1  274.00  5000.7  274.00  5006.3  277.88
  5011.9  280.82  5051.0  280.92  5056.6  280.09  5118.1  282.50  5132.0  281.68
  5140.5  281.01  5183.3  281.26  5288.6  281.68  5297.0  282.42  5319.3  282.44
  5356.2  285.00  5414.4  289.63  5422.8  290.96  5434.5  291.13  5445.1  292.02
#Mann=7,-1,0
  4886.1    0.16       0  4992.1    0.07       0  4998.1    0.16       0
  5132.0    0.12       0  5183.3    0.16       0  5356.2    0.12       0
  5434.5    0.16       0
Bank Sta=4992.1,4998.1
Exp/Cntr=0.3,0.1

Type RM Length L Ch R = 1,12324,764,764,764
BEGIN DESCRIPTION:
UNT 174 IN CACR 24.0
END DESCRIPTION:
XS GIS Cut Line= 3
      3677199.59     10674410.19      3676899.61     10674360.19
      3676599.64     10674510.17
#Sta/Elev= 30
  4706.1  295.19  4794.8  289.83  4817.6  286.95  4837.9  286.21  4855.6  284.16
  4939.3  280.33  4977.3  279.93  4982.3  279.15  4989.9  274.81  4997.1  273.78
  4999.8  273.28  5003.1  273.78  5007.7  277.51  5013.0  277.51  5018.6  279.73
  5041.0  280.45  5054.9  278.53  5063.3  278.79  5077.3  281.40  5091.3  280.64
  5130.4  282.31  5144.4  281.48  5239.2  286.37  5252.8  287.19  5309.3  291.77
  5314.9  291.44  5331.7  294.25  5337.2  293.97  5342.8  296.13  5345.6  296.13
#Mann=5,-1,0
  4706.1    0.16       0  4997.1    0.07       0  5003.1    0.16       0
  5239.2    0.12       0  5252.8    0.16       0
Bank Sta=4997.1,5003.1
Exp/Cntr=0.3,0.1

Type RM Length L Ch R = 1,11560,588,588,588
BEGIN DESCRIPTION:
UNT 174 IN CACR 23.0
END DESCRIPTION:
XS GIS Cut Line= 2
      3677223.49     10673773.01      3676647.96     10673957.91
#Sta/Elev= 30
  4757.4  293.35  4782.5  292.33  4792.5  290.02  4797.7  291.80  4803.5  290.31
  4824.5  289.86  4829.8  287.94  4835.1  288.51  4845.5  286.29  4856.0  287.78
  4877.0  285.24  4894.0  281.10  4919.0  280.40  4940.0  280.84  4950.5  279.50
  4982.1  278.56  4990.3  272.81  5000.1  271.42  5002.8  270.92  5006.1  271.42
  5013.6  276.25  5034.6  278.73  5097.6  278.70  5129.2  276.96  5139.6  277.88
  5156.1  277.07  5188.2  280.02  5252.4  280.85  5257.7  280.31  5361.9  285.53
#Mann=3,-1,0
  4757.4    0.16       0  5000.1    0.07       0  5006.1    0.16       0
Bank Sta=5000.1,5006.1
Exp/Cntr=0.3,0.1

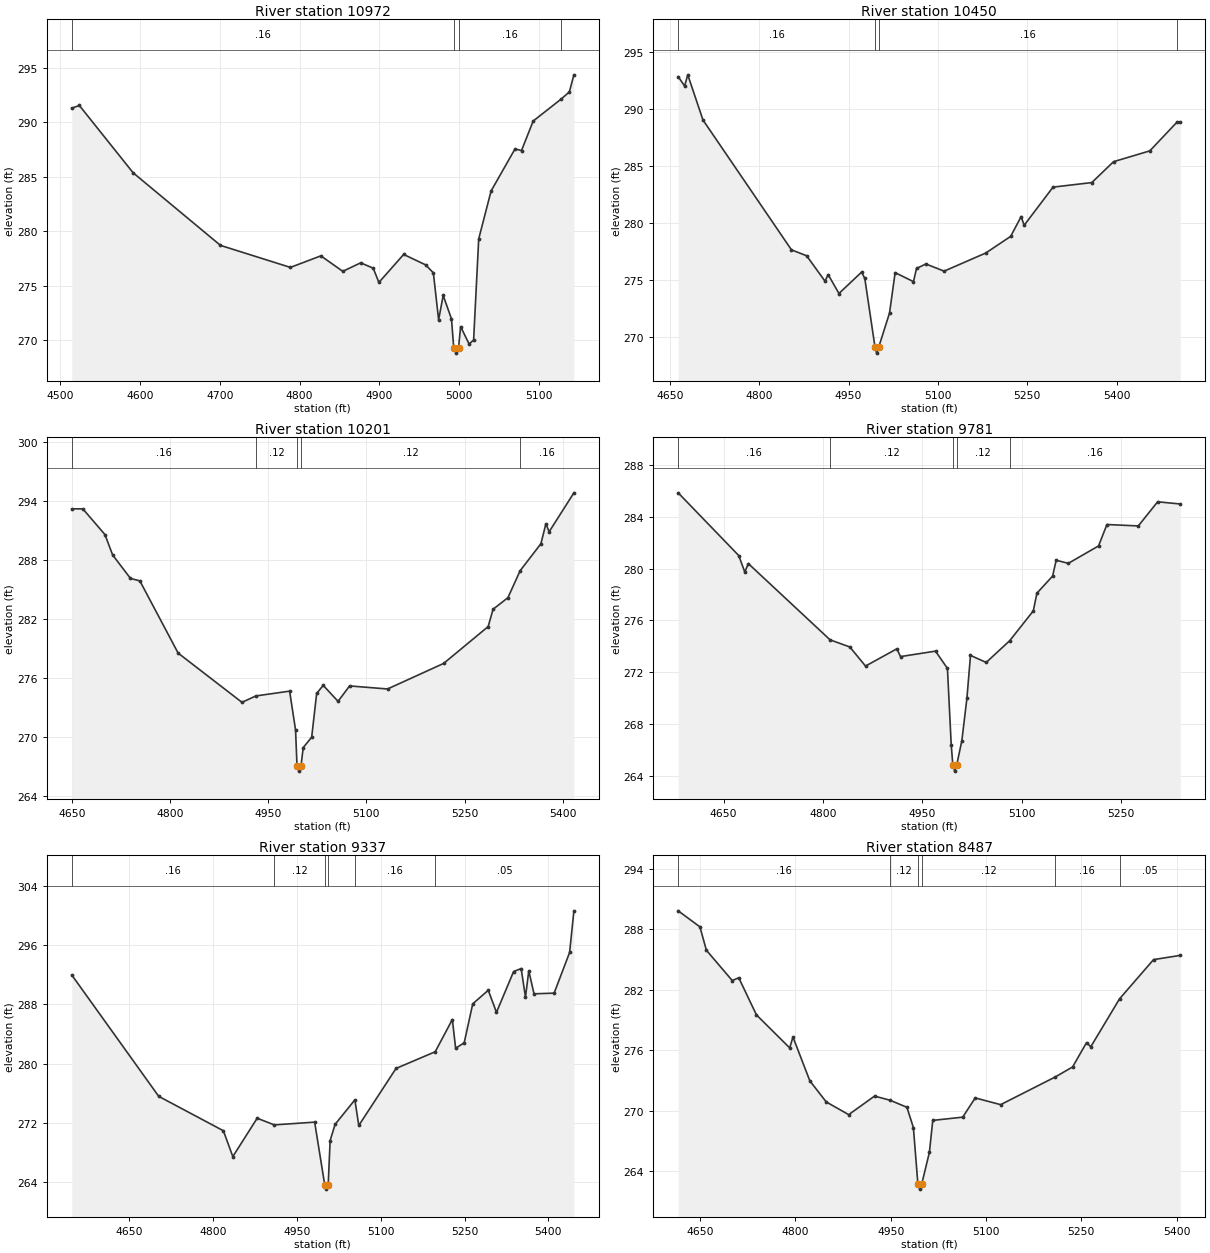
Type RM Length L Ch R = 1,10972,522,522,522
BEGIN DESCRIPTION:
UNT 174 IN CACR 22.0
END DESCRIPTION:
XS GIS Cut Line= 2
      3677088.00     10673296.48      3676534.70     10673595.21
#Sta/Elev= 30
  4514.7  291.29  4524.2  291.54  4591.5  285.37  4700.9  278.71  4788.5  276.69
  4826.6  277.75  4854.1  276.33  4876.5  277.11  4892.2  276.62  4899.3  275.31
  4930.3  277.88  4957.9  276.92  4967.5  276.19  4974.1  271.88  4979.8  274.12
  4990.2  271.97  4993.0  269.33  4995.7  268.83  4999.0  269.33  5001.7  271.26
  5012.2  269.67  5017.9  270.02  5024.3  279.31  5039.8  283.70  5069.7  287.55
  5077.9  287.41  5092.5  290.11  5127.2  292.11  5137.8  292.78  5143.5  294.35
#Mann=4,-1,0
  4514.7    0.16       0  4993.0    0.07       0  4999.0    0.16       0
  5127.2    0.05       0
Bank Sta=4993,4999
Exp/Cntr=0.3,0.1

Type RM Length L Ch R = 1,10450,249,249,249
BEGIN DESCRIPTION:
UNT 174 IN CACR 21.0
END DESCRIPTION:
XS GIS Cut Line= 3
      3676943.60     10672951.14      3676565.10     10673086.56
      3676488.71     10673520.59
#Sta/Elev= 30
  4664.1  292.85  4674.9  292.03  4680.2  293.01  4705.7  289.05  4854.2  277.66
  4879.7  277.14  4910.5  274.91  4915.8  275.49  4933.9  273.83  4972.0  275.71
  4977.3  275.15  4994.5  269.10  4997.2  268.60  5000.5  269.10  5018.8  272.12
  5028.2  275.66  5059.0  274.87  5064.1  276.03  5079.9  276.42  5110.4  275.79
  5180.3  277.38  5222.1  278.84  5239.7  280.58  5244.7  279.81  5293.2  283.16
  5358.3  283.56  5394.7  285.39  5455.6  286.34  5501.6  288.88  5506.8  288.87
#Mann=4,-1,0
  4664.1    0.16       0  4994.5    0.07       0  5000.5    0.16       0
  5501.6    0.05       0
Bank Sta=4994.5,5000.5
Exp/Cntr=0.3,0.1

Type RM Length L Ch R = 1,10201,420,420,420
BEGIN DESCRIPTION:
UNT 174 IN CACR 20.0
END DESCRIPTION:
XS GIS Cut Line= 3
      3676899.58     10672760.20      3676549.61     10672860.19
      3676149.60     10672910.19
#Sta/Elev= 30
  4649.9  293.20  4666.8  293.20  4700.6  290.58  4712.3  288.51  4739.6  286.12
  4753.9  285.87  4812.4  278.52  4909.9  273.51  4931.1  274.16  4982.7  274.65
  4991.8  270.69  4994.0  267.01  4996.7  266.51  5000.0  267.01  5003.5  268.91
  5016.4  269.96  5024.0  274.41  5034.0  275.24  5056.7  273.61  5074.3  275.18
  5132.3  274.87  5218.0  277.47  5286.0  281.22  5293.5  282.98  5316.2  284.16
  5334.9  286.91  5366.6  289.65  5374.2  291.68  5379.2  290.87  5417.0  294.83
#Mann=5,-1,0
  4649.9    0.16       0  4931.1    0.12       0  4994.0    0.07       0
  5000.0    0.12       0  5334.9    0.16       0
Bank Sta=4994,5000
Exp/Cntr=0.3,0.1

Type RM Length L Ch R = 1,9781,444,444,444
BEGIN DESCRIPTION:
UNT 174 IN CACR 19.0
END DESCRIPTION:
XS GIS Cut Line= 2
      3676783.83     10672454.63      3676085.97     10672749.74
#Sta/Elev= 30
  4581.6  285.83  4673.0  281.00  4682.1  279.73  4687.5  280.38  4810.8  274.51
  4840.6  273.96  4864.3  272.49  4911.6  273.82  4917.1  273.22  4969.9  273.64
  4987.9  272.31  4993.6  266.45  4996.0  264.90  4998.8  264.40  5002.0  264.90
  5009.6  266.73  5017.3  270.01  5022.7  273.31  5046.4  272.77  5081.8  274.44
  5117.5  276.74  5122.9  278.10  5146.6  279.42  5152.0  280.64  5170.3  280.40
  5215.9  281.74  5228.6  283.39  5275.9  283.28  5305.1  285.14  5339.3  284.97
#Mann=5,-1,0
  4581.6    0.16       0  4810.8    0.12       0  4996.0    0.07       0
  5002.0    0.12       0  5081.8    0.16       0
Bank Sta=4996,5002
Exp/Cntr=0.3,0.1

Type RM Length L Ch R = 1,9337,850,850,850
BEGIN DESCRIPTION:
UNT 174 IN CACR 18.0
END DESCRIPTION:
XS GIS Cut Line= 3
      3676599.57     10672110.20      3676199.61     10672260.19
      3675799.57     10672510.21
#Sta/Elev= 30
  4546.9  291.97  4702.6  275.59  4818.3  270.95  4835.2  267.46  4878.8  272.64
  4909.4  271.74  4981.7  272.11  4999.9  263.57  5002.7  263.07  5005.9  263.57
  5009.4  269.63  5018.3  271.81  5053.7  275.12  5060.7  271.66  5127.4  279.36
  5197.5  281.61  5228.2  285.96  5234.1  282.08  5249.4  282.82  5264.7  288.08
  5292.5  289.91  5307.2  286.93  5337.9  292.44  5351.4  292.84  5359.1  288.97
  5365.0  292.54  5374.4  289.43  5410.4  289.52  5438.1  295.01  5445.8  300.63
#Mann=6,-1,0
  4546.9    0.16       0  4909.4    0.12       0  4999.9    0.07       0
  5005.9    0.12       0  5053.7    0.16       0  5197.5    0.05       0
Bank Sta=4999.9,5005.9
Exp/Cntr=0.3,0.1

Type RM Length L Ch R = 1,8487,319,319,319
BEGIN DESCRIPTION:
UNT 174 IN CACR 17.0
END DESCRIPTION:
XS GIS Cut Line= 3
      3676603.25     10671761.92      3676143.22     10671848.72
      3675896.95     10672056.10
#Sta/Elev= 30
  4615.7  289.82  4649.9  288.23  4660.1  285.91  4700.8  282.90  4711.0  283.18
  4738.8  279.50  4791.2  276.22  4796.3  277.30  4822.9  272.95  4848.7  270.86
  4884.0  269.60  4924.7  271.44  4949.0  271.03  4975.6  270.33  4985.8  268.32
  4992.9  262.71  4995.7  262.21  4998.9  262.71  5011.0  265.86  5016.3  269.03
  5063.4  269.35  5083.1  271.26  5123.1  270.59  5208.8  273.33  5236.3  274.33
  5258.3  276.75  5264.9  276.33  5310.2  281.09  5363.7  284.98  5405.8  285.40
#Mann=6,-1,0
  4615.7    0.16       0  4949.0    0.12       0  4992.9    0.07       0
  4998.9    0.12       0  5208.8    0.16       0  5310.2    0.05       0
Bank Sta=4992.9,4998.9
Exp/Cntr=0.3,0.1

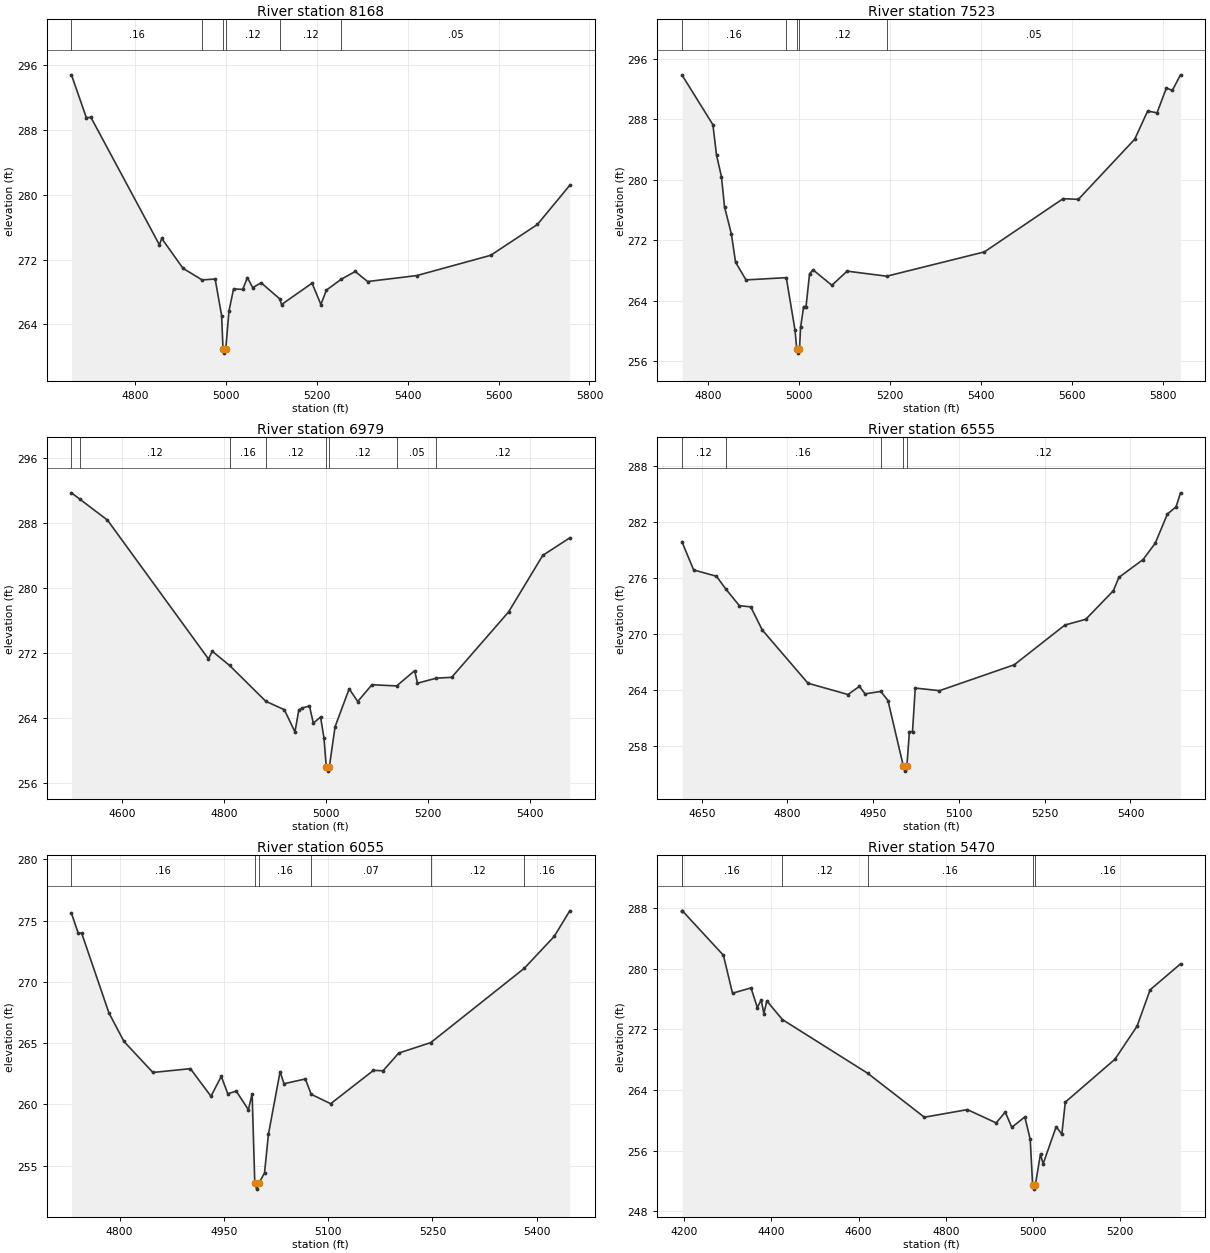
Type RM Length L Ch R = 1,8168,645,645,645
BEGIN DESCRIPTION:
UNT 174 IN CACR 16.0
END DESCRIPTION:
XS GIS Cut Line= 3
      3676611.98     10671675.11      3676108.06     10671597.80
      3675548.64     10671423.38
#Sta/Elev= 30
  4660.9  294.83  4693.6  289.54  4703.8  289.56  4854.3  273.82  4859.4  274.61
  4906.1  270.92  4948.1  269.48  4976.9  269.59  4991.1  265.08  4994.2  260.93
  4996.9  260.43  5000.2  260.93  5007.3  265.63  5017.4  268.38  5037.6  268.30
  5047.7  269.77  5059.5  268.53  5078.1  269.12  5119.1  267.13  5122.8  266.43
  5190.0  269.08  5209.4  266.44  5221.5  268.22  5254.6  269.58  5284.9  270.52
  5312.2  269.28  5420.5  270.02  5582.7  272.52  5685.5  276.33  5756.7  281.18
#Mann=6,-1,0
  4660.9    0.16       0  4948.1    0.12       0  4994.2    0.07       0
  5000.2    0.12       0  5119.1    0.12       0  5254.6    0.05       0
Bank Sta=4994.2,5000.2
Exp/Cntr=0.3,0.1

Type RM Length L Ch R = 1,7523,544,544,544
BEGIN DESCRIPTION:
UNT 174 IN CACR 15.0
END DESCRIPTION:
XS GIS Cut Line= 3
      3676449.65     10671110.17      3676199.61     10671210.19
      3675399.64     10671410.18
#Sta/Elev= 30
  4743.7  293.85  4811.1  287.31  4819.1  283.28  4829.9  280.43  4836.6  276.45
  4851.5  272.90  4860.9  269.11  4883.8  266.77  4972.2  267.07  4991.5  260.09
  4995.2  257.58  4997.9  257.08  5001.2  257.58  5003.6  260.48  5010.3  263.24
  5015.6  263.24  5023.3  267.58  5031.0  268.10  5072.3  266.06  5105.8  267.93
  5192.7  267.26  5407.3  270.48  5579.9  277.52  5613.4  277.43  5737.1  285.39
  5765.5  289.12  5786.1  288.88  5806.7  292.18  5819.6  291.84  5837.6  293.91
#Mann=5,-1,0
  4743.7    0.16       0  4972.2    0.12       0  4995.2    0.07       0
  5001.2    0.12       0  5192.7    0.05       0
Bank Sta=4995.2,5001.2
Exp/Cntr=0.3,0.1

Type RM Length L Ch R = 1,6979,424,424,424
BEGIN DESCRIPTION:
UNT 174 IN CACR 14.0
END DESCRIPTION:
XS GIS Cut Line= 3
      3676299.64     10670610.16      3675899.61     10670960.19
      3675499.57     10671160.21
#Sta/Elev= 30
  4500.2  291.72  4517.3  290.91  4570.9  288.36  4769.3  271.25  4776.9  272.19
  4810.9  270.44  4881.9  266.03  4918.3  264.99  4939.2  262.26  4946.8  264.95
  4953.4  265.20  4967.7  265.45  4975.3  263.34  4989.5  264.09  4996.2  261.51
  5000.7  257.92  5003.5  257.42  5006.7  257.92  5018.0  262.89  5045.7  267.57
  5062.5  266.00  5090.4  268.07  5138.9  267.92  5174.3  269.80  5179.9  268.26
  5217.1  268.88  5247.0  268.98  5358.8  277.04  5425.9  284.01  5479.0  286.17
#Mann=8,-1,0
  4500.2    0.16       0  4517.3    0.12       0  4810.9    0.16       0
  4881.9    0.12       0  5000.7    0.07       0  5006.7    0.12       0
  5138.9    0.05       0  5217.1    0.12       0
Bank Sta=5000.7,5006.7
Exp/Cntr=0.3,0.1

Type RM Length L Ch R = 1,6555,500,500,500
BEGIN DESCRIPTION:
UNT 174 IN CACR 13.0
END DESCRIPTION:
XS GIS Cut Line= 3
      3676149.60     10670560.19      3675749.61     10670560.19
      3675349.60     10670810.19
#Sta/Elev= 30
  4615.8  279.82  4635.8  276.86  4675.8  276.18  4692.0  274.82  4715.8  273.03
  4735.8  272.90  4755.8  270.43  4835.8  264.72  4905.8  263.51  4925.8  264.38
  4935.8  263.58  4963.3  263.84  4975.8  262.86  5002.8  255.80  5005.5  255.30
  5008.8  255.80  5013.3  259.53  5018.7  259.53  5023.5  264.20  5065.9  263.92
  5196.8  266.70  5285.2  270.95  5321.8  271.57  5370.2  274.64  5379.6  276.05
  5422.0  277.97  5443.3  279.72  5464.5  282.84  5479.8  283.63  5487.5  285.12
#Mann=5,-1,0
  4615.8    0.12       0  4692.0    0.16       0  4963.3    0.12       0
  5002.8    0.07       0  5008.8    0.12       0
Bank Sta=5002.8,5008.8
Exp/Cntr=0.3,0.1

Type RM Length L Ch R = 1,6055,585,585,585
BEGIN DESCRIPTION:
UNT 174 IN CACR 12.0
END DESCRIPTION:
XS GIS Cut Line= 3
      3675949.60     10670110.19      3675699.61     10670210.19
      3675299.58     10670410.20
#Sta/Elev= 30
  4730.9  275.59  4740.3  274.02  4745.7  273.95  4784.7  267.47  4806.3  265.14
  4848.0  262.60  4901.9  262.91  4931.5  260.66  4946.3  262.28  4955.7  260.86
  4967.8  261.08  4985.3  259.56  4990.7  260.86  4994.5  253.58  4997.2  253.08
  5000.5  253.58  5008.5  254.40  5014.1  257.55  5030.9  262.67  5036.5  261.68
  5067.2  262.07  5075.6  260.82  5103.6  260.05  5165.1  262.77  5179.0  262.74
  5201.4  264.18  5247.6  265.04  5381.8  271.09  5425.0  273.70  5447.4  275.79
#Mann=6,-1,0
  4730.9    0.16       0  4994.5    0.07       0  5000.5    0.16       0
  5075.6    0.07       0  5247.6    0.12       0  5381.8    0.16       0
Bank Sta=4994.5,5000.5
Exp/Cntr=0.3,0.1

Type RM Length L Ch R = 1,5470,327,327,327
BEGIN DESCRIPTION:
UNT 174 IN CACR 11.0
END DESCRIPTION:
XS GIS Cut Line= 2
      3676100.27     10669530.39      3675154.36     10670172.56
#Sta/Elev= 30
  4195.4  287.63  4195.9  287.63  4289.9  281.77  4310.9  276.76  4353.3  277.46
  4367.8  274.87  4376.7  275.87  4382.8  274.07  4389.6  275.75  4425.1  273.29
  4621.2  266.19  4751.0  260.40  4849.9  261.40  4915.7  259.65  4936.7  261.07
  4951.7  259.06  4981.5  260.44  4993.9  257.49  4999.5  251.41  5002.3  250.91
  5005.5  251.41  5017.5  255.56  5023.5  254.24  5053.4  259.14  5066.4  258.16
  5074.4  262.39  5188.2  268.04  5239.1  272.42  5269.0  277.21  5338.7  280.63
#Mann=6,-1,0
  4195.4    0.12       0  4195.9    0.16       0  4425.1    0.12       0
  4621.2    0.16       0  4999.5    0.07       0  5005.5    0.16       0
Bank Sta=4999.5,5005.5
Exp/Cntr=0.3,0.1