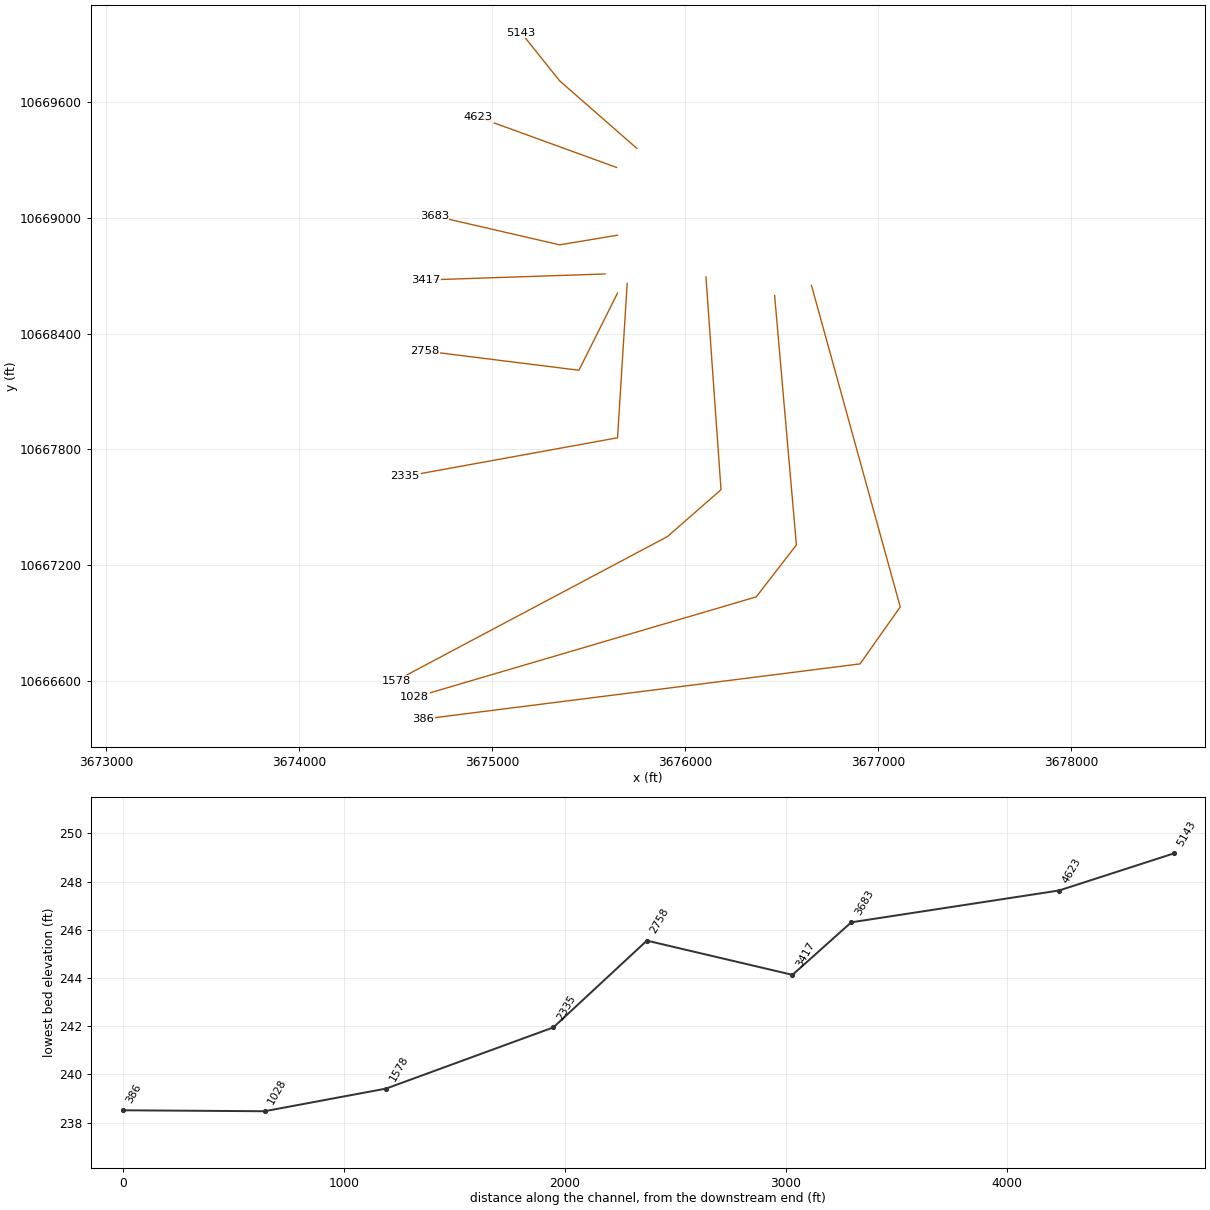
HEC-RAS study UNT 174 IN CACR.prj: UNT 174 IN CACR Base Level Engineering

--- UNT 174 IN CACR.g01 (geometry) --- (continued)

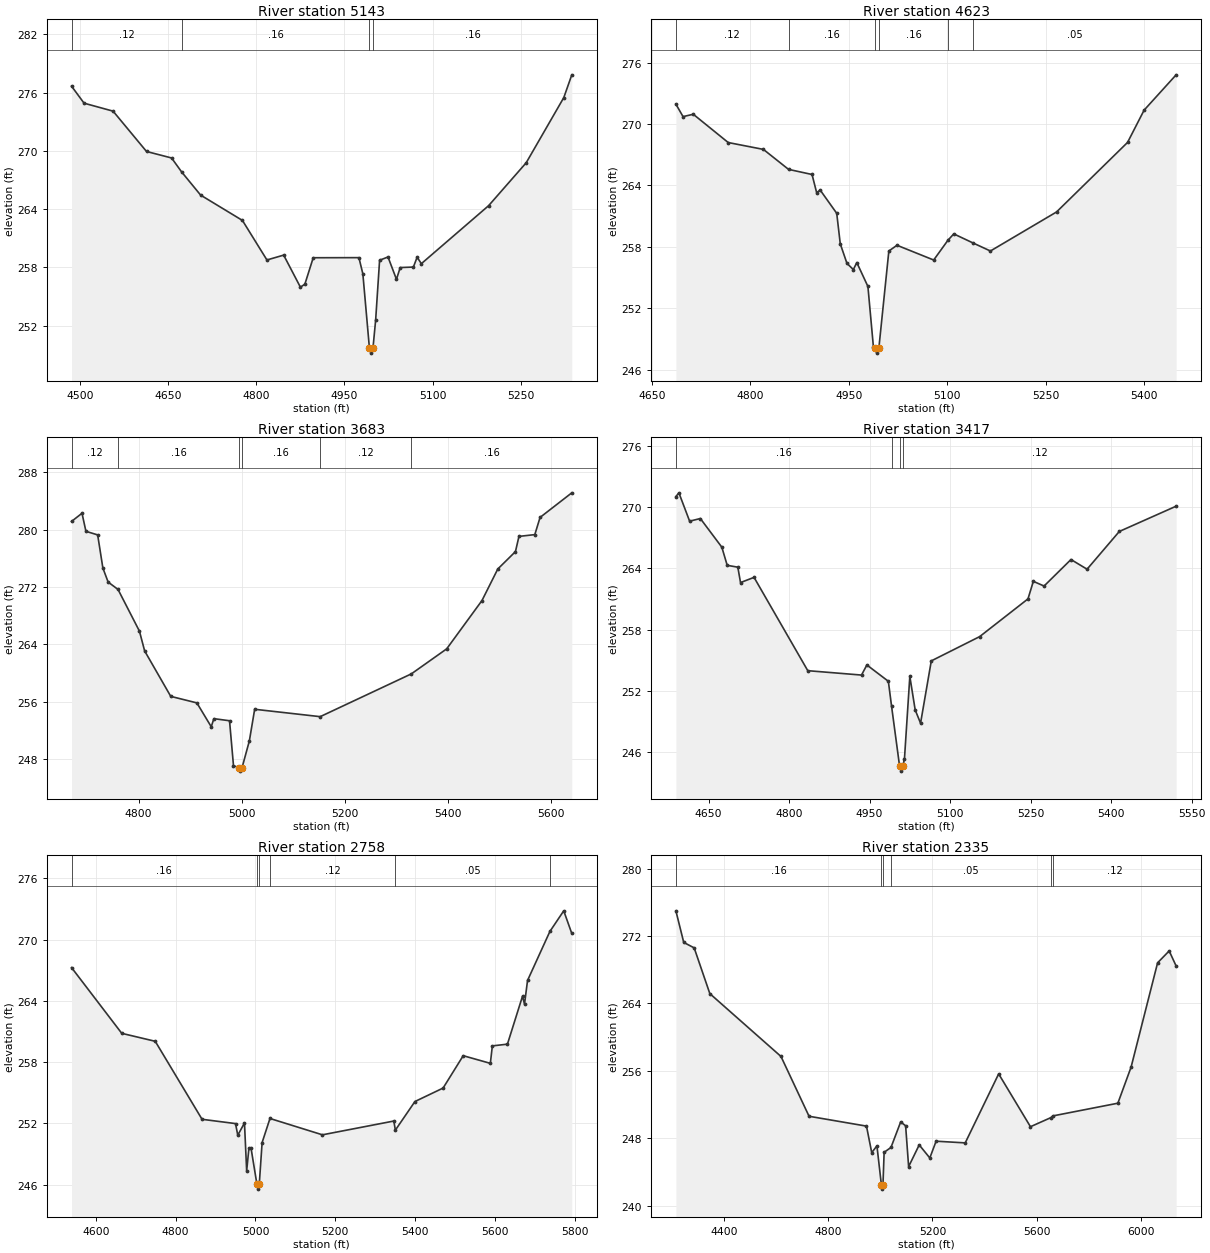
Type RM Length L Ch R = 1,5143,520,520,520
BEGIN DESCRIPTION:
UNT 174 IN CACR 10.0
END DESCRIPTION:
XS GIS Cut Line= 3
      3675749.58     10669360.21      3675349.61     10669710.19
      3675149.63     10669960.17
#Sta/Elev= 30
  4485.4  276.65  4506.7  274.90  4556.1  274.08  4613.0  269.93  4655.7  269.26
  4672.7  267.83  4705.1  265.44  4776.3  262.83  4818.0  258.76  4846.5  259.26
  4875.0  255.96  4882.6  256.27  4896.8  258.99  4974.6  259.00  4981.3  257.33
  4992.5  249.67  4995.3  249.17  4998.5  249.67  5003.1  252.59  5009.8  258.73
  5024.1  259.07  5038.5  256.77  5044.9  257.98  5067.3  258.03  5073.7  259.04
  5080.9  258.38  5195.4  264.35  5259.4  268.77  5323.4  275.48  5337.0  277.82
#Mann=4,-1,0
  4485.4    0.12       0  4672.7    0.16       0  4992.5    0.07       0
  4998.5    0.16       0
Bank Sta=4992.5,4998.5
Exp/Cntr=0.3,0.1

Type RM Length L Ch R = 1,4623,940,940,940
BEGIN DESCRIPTION:
UNT 174 IN CACR 8.0
END DESCRIPTION:
XS GIS Cut Line= 2
      3675644.50     10669261.31      3674928.37     10669521.71
#Sta/Elev= 30
  4686.7  271.94  4697.6  270.72  4713.2  270.95  4766.4  268.19  4820.0  267.52
  4858.3  265.57  4894.1  265.07  4901.1  263.30  4906.5  263.55  4931.7  261.28
  4937.1  258.30  4947.3  256.39  4957.0  255.79  4962.3  256.47  4979.2  254.14
  4987.6  248.22  4989.9  248.13  4992.7  247.63  4995.9  248.13  5011.1  257.60
  5023.5  258.16  5079.4  256.72  5101.1  258.65  5110.0  259.27  5139.5  258.38
  5165.8  257.60  5266.5  261.41  5374.7  268.20  5399.9  271.35  5448.7  274.80
#Mann=6,-1,0
  4686.7    0.12       0  4858.3    0.16       0  4989.9    0.07       0
  4995.9    0.16       0  5101.1    0.12       0  5139.5    0.05       0
Bank Sta=4989.9,4995.9
Exp/Cntr=0.3,0.1

Type RM Length L Ch R = 1,3683,266,266,266
BEGIN DESCRIPTION:
UNT 174 IN CACR 7.0
END DESCRIPTION:
XS GIS Cut Line= 3
      3675649.61     10668910.19      3675349.61     10668860.19
      3674699.63     10669010.18
#Sta/Elev= 30
  4669.8  281.15  4690.1  282.29  4697.7  279.77  4720.5  279.27  4730.6  274.65
  4740.8  272.69  4760.0  271.66  4801.6  265.84  4811.7  263.08  4862.4  256.74
  4913.1  255.83  4941.0  252.50  4946.1  253.63  4976.5  253.34  4984.2  247.06
  4994.9  246.81  4997.6  246.31  5000.9  246.81  5015.0  250.53  5025.3  254.94
  5152.5  253.91  5329.5  259.88  5398.1  263.37  5466.6  270.11  5497.3  274.51
  5531.6  276.94  5538.4  279.06  5569.2  279.31  5579.4  281.71  5641.0  285.14
#Mann=6,-1,0
  4669.8    0.12       0  4760.0    0.16       0  4994.9    0.07       0
  5000.9    0.16       0  5152.5    0.12       0  5329.5    0.16       0
Bank Sta=4994.9,5000.9
Exp/Cntr=0.3,0.1

Type RM Length L Ch R = 1,3417,659,659,659
BEGIN DESCRIPTION:
UNT 174 IN CACR 6.0
END DESCRIPTION:
XS GIS Cut Line= 2
      3675585.17     10668709.21      3674653.79     10668677.99
#Sta/Elev= 30
  4589.2  271.05  4594.8  271.42  4614.8  268.64  4634.8  268.90  4674.8  266.09
  4684.8  264.31  4704.6  264.13  4709.6  262.62  4734.8  263.13  4834.9  253.98
  4935.0  253.55  4945.0  254.54  4985.0  252.94  4991.0  250.49  5005.9  244.63
  5008.6  244.13  5011.9  244.63  5015.0  245.33  5025.0  253.42  5035.0  250.13
  5045.0  248.83  5065.0  254.94  5155.1  257.32  5245.1  261.02  5255.1  262.74
  5275.1  262.28  5325.2  264.88  5355.2  263.93  5415.2  267.63  5521.1  270.11
#Mann=4,-1,0
  4589.2    0.16       0  4991.0    0.12       0  5005.9    0.07       0
  5011.9    0.12       0
Bank Sta=5005.9,5011.9
Exp/Cntr=0.3,0.1

Type RM Length L Ch R = 1,2758,423,423,423
BEGIN DESCRIPTION:
UNT 174 IN CACR 5.0
END DESCRIPTION:
XS GIS Cut Line= 3
      3675649.62     10668610.21      3675449.61     10668210.19
      3674649.57     10668310.19
#Sta/Elev= 30
  4539.2  267.25  4665.0  260.81  4748.9  260.03  4866.2  252.39  4950.1  251.97
  4955.7  250.83  4972.5  252.03  4978.0  247.34  4983.6  249.55  4989.0  249.55
  5003.6  246.05  5006.3  245.55  5009.6  246.05  5016.7  250.11  5036.4  252.47
  5167.8  250.87  5346.7  252.22  5350.6  251.33  5399.6  254.13  5470.2  255.45
  5520.6  258.62  5588.6  257.87  5593.6  259.58  5631.4  259.75  5669.2  264.45
  5674.2  263.67  5681.8  265.99  5737.8  270.79  5772.5  272.81  5792.7  270.59
#Mann=6,-1,0
  4539.2    0.16       0  5003.6    0.07       0  5009.6    0.16       0
  5036.4    0.12       0  5350.6    0.05       0  5737.8    0.12       0
Bank Sta=5003.6,5009.6
Exp/Cntr=0.3,0.1

Type RM Length L Ch R = 1,2335,757,757,757
BEGIN DESCRIPTION:
UNT 174 IN CACR 4.0
END DESCRIPTION:
XS GIS Cut Line= 3
      3675699.61     10668660.21      3675649.61     10667860.19
      3674549.62     10667660.19
#Sta/Elev= 30
  4215.6  274.99  4245.7  271.24  4285.8  270.59  4345.9  265.16  4618.9  257.70
  4726.6  250.60  4947.0  249.43  4967.1  246.28  4987.1  247.09  5004.2  242.45
  5006.9  241.95  5010.2  242.45  5014.7  246.32  5041.0  246.90  5078.2  249.93
  5097.2  249.47  5108.7  244.62  5149.3  247.20  5190.0  245.65  5214.1  247.64
  5325.9  247.44  5454.2  255.63  5576.2  249.36  5654.6  250.44  5661.9  250.64
  5911.6  252.15  5962.4  256.44  6064.1  268.82  6108.5  270.23  6135.2  268.44
#Mann=6,-1,0
  4215.6    0.16       0  5004.2    0.07       0  5010.2    0.16       0
  5041.0    0.05       0  5654.6    0.07       0  5661.9    0.12       0
Bank Sta=5004.2,5010.2
Exp/Cntr=0.3,0.1

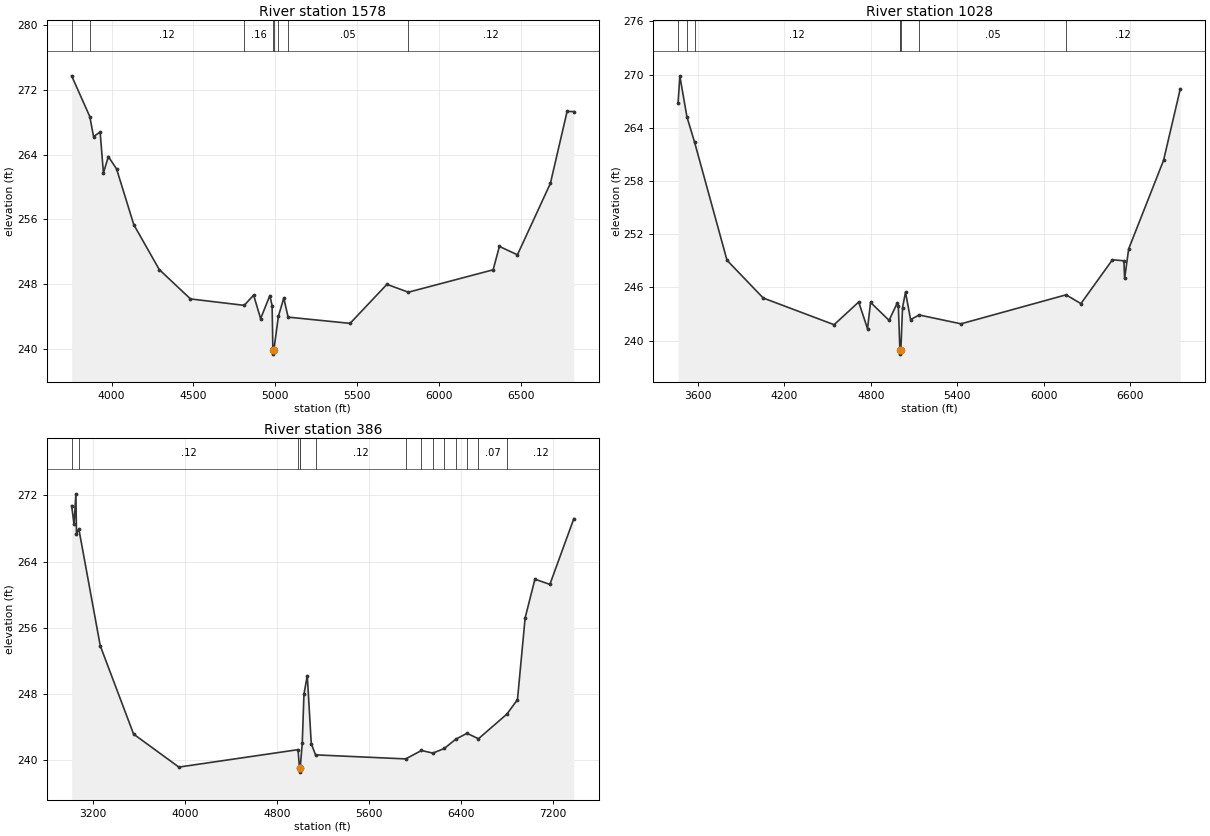
Type RM Length L Ch R = 1,1578,550,550,550
BEGIN DESCRIPTION:
UNT 174 IN CACR 3.0
END DESCRIPTION:
XS GIS Cut Line= 4
      3676107.78     10668693.60      3676185.90     10667591.16
      3675908.12     10667348.10      3674503.22     10666602.29
#Sta/Elev= 30
  3756.6  273.70  3867.5  268.67  3890.3  266.21  3930.4  266.78  3950.5  261.73
  3980.6  263.75  4030.7  262.23  4136.1  255.35  4291.3  249.83  4481.8  246.21
  4809.6  245.42  4867.2  246.68  4909.9  243.78  4965.9  246.62  4980.1  245.40
  4984.7  239.91  4987.5  239.41  4990.7  239.91  5018.5  244.09  5051.3  246.32
  5077.6  243.97  5455.9  243.20  5680.7  248.01  5811.3  247.04  6328.9  249.80
  6367.3  252.68  6477.2  251.65  6678.4  260.45  6780.3  269.31  6821.5  269.30
#Mann=8,-1,0
  3756.6    0.16       0  3867.5    0.12       0  4809.6    0.16       0
  4984.7    0.07       0  4990.7    0.16       0  5018.5    0.08       0
  5077.6    0.05       0  5811.3    0.12       0
Bank Sta=4984.7,4990.7
Exp/Cntr=0.3,0.1

Type RM Length L Ch R = 1,1028,642,642,642
BEGIN DESCRIPTION:
UNT 174 IN CACR 2.0
END DESCRIPTION:
XS GIS Cut Line= 4
      3676463.68     10668598.08      3676576.53     10667304.70
      3676368.19     10667035.60      3674598.08     10666514.98
#Sta/Elev= 30
  3463.5  266.83  3475.3  269.87  3524.7  265.24  3577.7  262.38  3802.7  249.06
  4054.0  244.80  4545.5  241.79  4716.1  244.35  4777.5  241.34  4798.4  244.31
  4926.9  242.28  4983.1  244.22  4991.2  243.91  5001.7  239.08  5002.7  238.97
  5005.5  238.47  5008.7  238.97  5020.2  243.72  5041.0  245.46  5076.3  242.36
  5134.9  242.89  5425.8  241.89  6154.6  245.16  6257.7  244.17  6476.5  249.12
  6555.7  249.00  6560.9  247.01  6589.0  250.34  6830.9  260.33  6947.2  268.41
#Mann=8,-1,0
  3463.5    0.12       0  3524.7    0.16       0  3577.7    0.12       0
  5001.7    0.05       0  5002.7    0.07       0  5008.7    0.05       0
  5134.9    0.05       0  6154.6    0.12       0
Bank Sta=5002.7,5008.7
Exp/Cntr=0.3,0.1

Type RM Length L Ch R = 1,386,0,0,0
BEGIN DESCRIPTION:
UNT 174 IN CACR 1.0
END DESCRIPTION:
XS GIS Cut Line= 4
      3676654.65     10668650.19      3677114.72     10666983.52
      3676906.39     10666688.38      3674642.68     10666402.16
#Sta/Elev= 30
  3011.4  270.76  3032.2  268.49  3048.3  272.19  3053.5  267.38  3073.9  267.94
  3260.4  253.80  3550.9  243.11  3945.1  239.12  4982.2  241.23  4995.1  239.01
  4997.8  238.51  5001.1  239.01  5019.0  241.98  5033.8  247.92  5062.7  250.20
  5097.5  241.96  5134.5  240.60  5919.3  240.11  6056.9  241.13  6156.1  240.81
  6255.4  241.37  6354.6  242.49  6453.9  243.21  6553.1  242.55  6801.0  245.54
  6892.6  247.28  6959.4  257.18  7044.6  261.86  7174.8  261.23  7383.4  269.19
#Mann=14,-1,0
  3011.4    0.16       0  3073.9    0.12       0  4982.2    0.05       0
  4995.1    0.04       0  5001.1    0.05       0  5134.5    0.12       0
  5919.3    0.05       0  6056.9    0.08       0  6156.1    0.05       0
  6255.4     0.1       0  6354.6    0.05       0  6453.9    0.12       0
  6553.1    0.07       0  6801.0    0.12       0
Bank Sta=4995.1,5001.1
Exp/Cntr=0.3,0.1

Chan Stop Cuts=-1