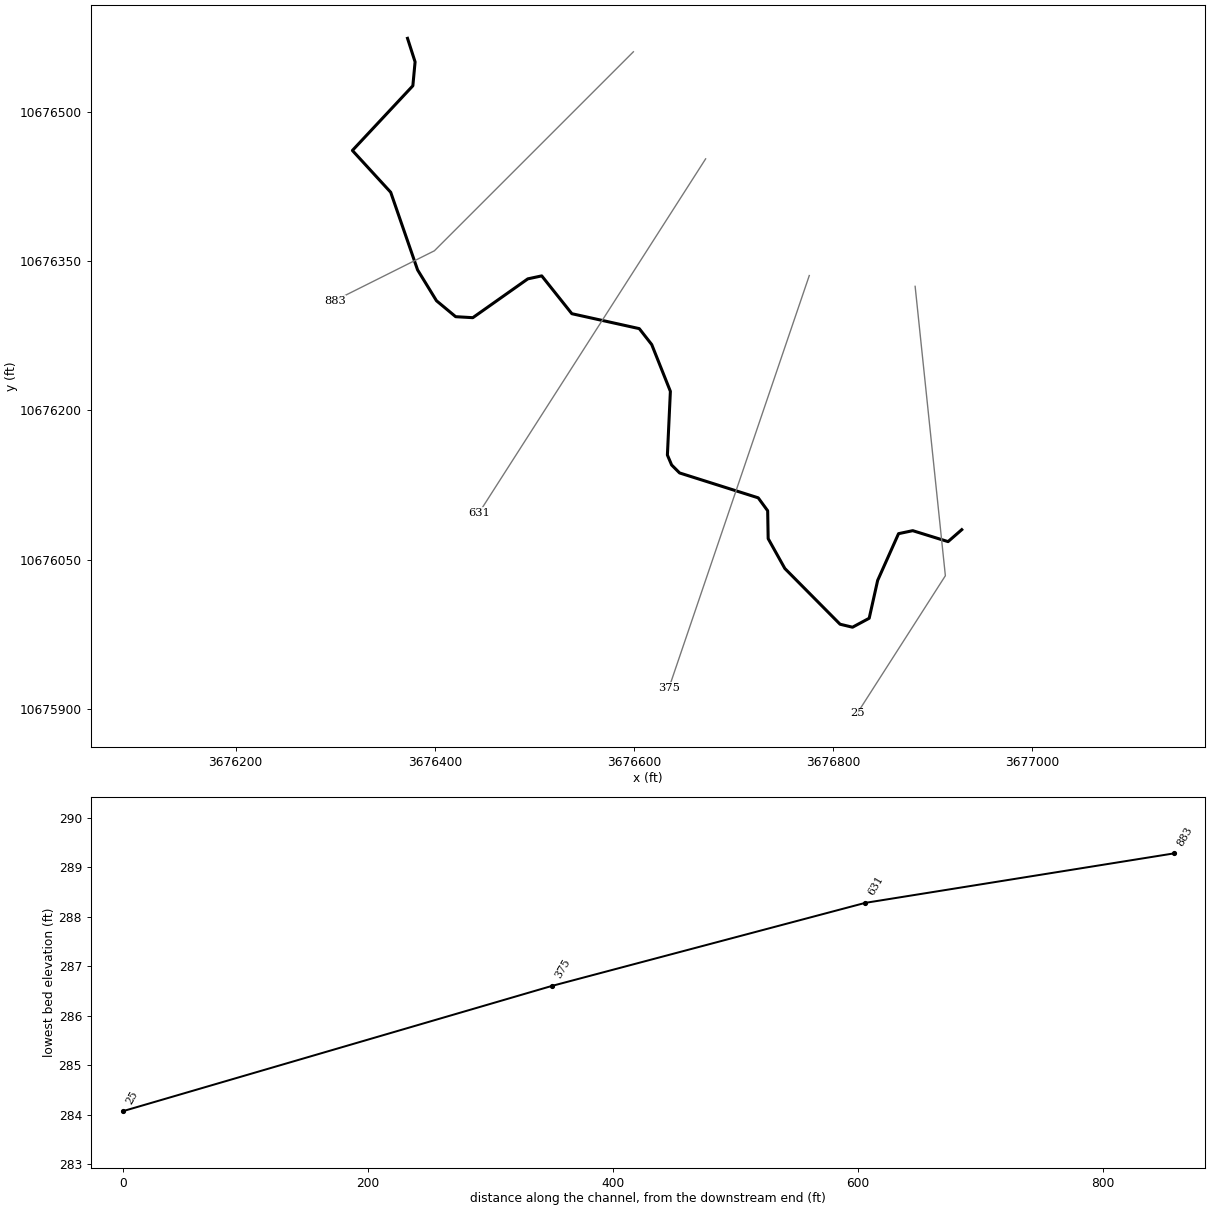
--- UNT 176 IN CACR.prj (project) ---

Proj Title=UNT 176 IN CACR Base Level Engineering
Current Plan=p01
Default Exp/Contr=0.3,0.1
English Units
Geom File=g01
Flow File=f01
Plan File=p01
BEGIN DESCRIPTION:
UNT 176 IN CACR
END DESCRIPTION:

--- UNT 176 IN CACR.p01 (plan) ---

Plan Title=Multiple Run
Short Identifier=Multiple
Geom File=g01
Flow File=f01
Subcritical Flow
K Sum by GR= 0
Std Step Tol= 0.01
Critical Tol= 0.01
Num of Std Step Trials= 20
Max Error Tol= 0.3
Flow Tol Ratio= 0.001
Split Flow NTrial= 30
Split Flow Tol= 0.02
Split Flow Ratio= 0.02
Log Output Level= 0
Friction Slope Method= 1
Unsteady Friction Slope Method= 2
Unsteady Bridges Friction Slope Method= 1
Parabolic Critical Depth
Global Vel Dist=  1 , 1 , 1
Global Log Level= 0
CheckData=True
Encroach Param= -1, 0, 0, 0
BEGIN DESCRIPTION:
Multiple Run
END DESCRIPTION:

--- UNT 176 IN CACR.f01 (steady flow) ---

Flow Title=Multiple
Number of Profiles=7
Profile Names=10-year,25-year,50-year,1pct_min,100-year,1pct_plu,500-year
River Rch & RM= UNT 176 IN CACR,Reach-1,883
     168     210     242     206     279     377     369
Boundary for River Rch & Prof#=UNT 176 IN CACR,Reach-1,1
Up Type=0
Dn Type=3
Dn Slope=0.005
Boundary for River Rch & Prof#=UNT 176 IN CACR,Reach-1,2
Up Type=0
Dn Type=3
Dn Slope=0.005
Boundary for River Rch & Prof#=UNT 176 IN CACR,Reach-1,3
Up Type=0
Dn Type=3
Dn Slope=0.005
Boundary for River Rch & Prof#=UNT 176 IN CACR,Reach-1,4
Up Type=0
Dn Type=3
Dn Slope=0.005
Boundary for River Rch & Prof#=UNT 176 IN CACR,Reach-1,5
Up Type=0
Dn Type=3
Dn Slope=0.005
Boundary for River Rch & Prof#=UNT 176 IN CACR,Reach-1,6
Up Type=0
Dn Type=3
Dn Slope=0.005
Boundary for River Rch & Prof#=UNT 176 IN CACR,Reach-1,7
Up Type=0
Dn Type=3
Dn Slope=0.005

--- UNT 176 IN CACR.g01 (geometry) ---

Geom Title=Existing Conditions

River Reach=UNT 176 IN CACR,Reach-1
Reach XY= 30
      3676372.64     10676573.67      3676380.25     10676550.00
      3676378.00     10676526.00      3676317.25     10676461.00
      3676355.75     10676419.00      3676382.75     10676341.00
      3676401.75     10676310.00      3676421.00     10676294.00
      3676438.25     10676293.00      3676493.50     10676332.00
      3676507.50     10676335.00      3676537.75     10676297.00
      3676605.50     10676282.00      3676618.00     10676266.00
      3676636.75     10676219.00      3676633.75     10676155.00
      3676638.00     10676145.00      3676646.00     10676137.00
      3676725.00     10676112.00      3676734.50     10676099.00
      3676735.00     10676071.00      3676751.75     10676041.00
      3676807.25     10675985.00      3676819.75     10675982.00
      3676836.50     10675991.00      3676845.00     10676029.00
      3676866.00     10676076.00      3676880.25     10676079.00
      3676915.75     10676068.00      3676929.50     10676080.00

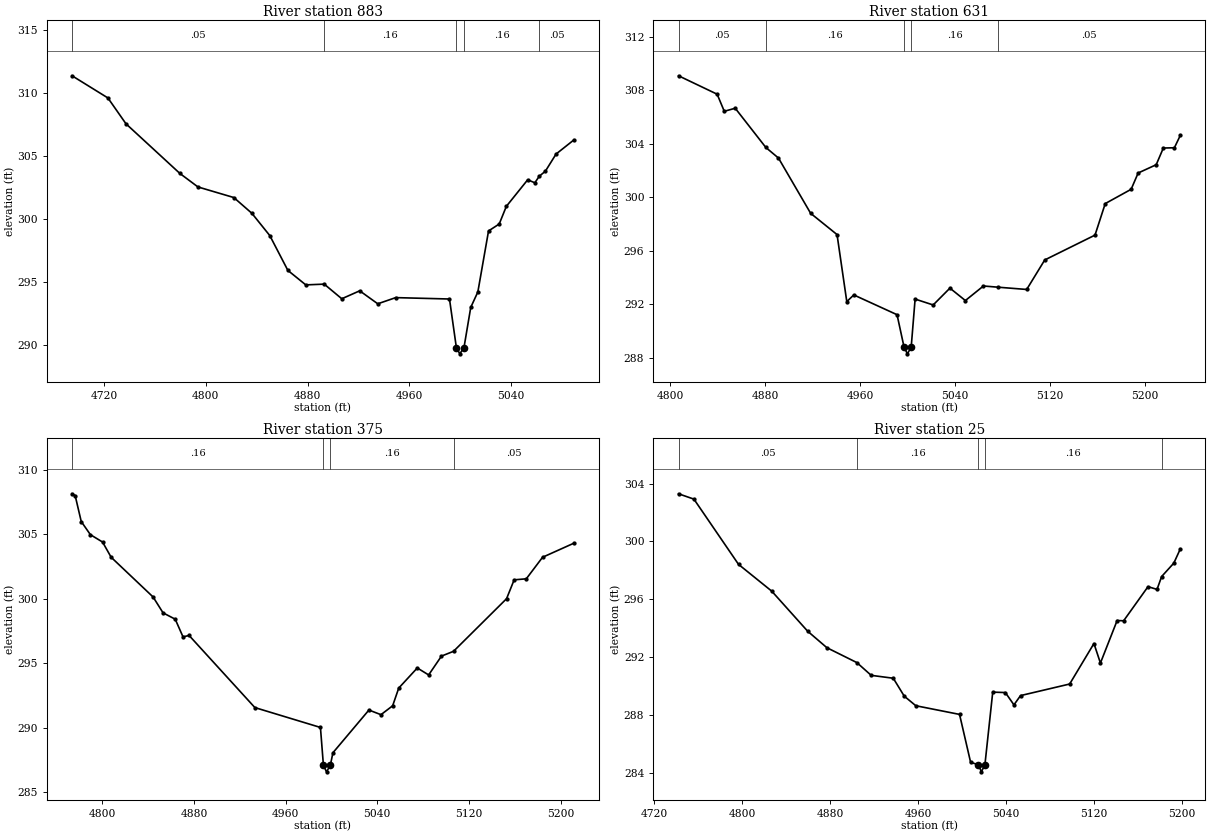
Type RM Length L Ch R = 1,883,252,252,252
BEGIN DESCRIPTION:
UNT 176 IN CACR 2.0
END DESCRIPTION:
XS GIS Cut Line= 3
      3676599.58     10676560.16      3676399.61     10676360.19
      3676299.61     10676310.19
#Sta/Elev= 30
  4694.8  311.34  4723.0  309.58  4737.2  307.53  4779.6  303.59  4793.8  302.52
  4822.0  301.68  4836.2  300.43  4850.3  298.66  4864.5  295.90  4878.6  294.75
  4893.1  294.81  4906.9  293.65  4921.0  294.28  4935.2  293.25  4949.3  293.74
  4991.6  293.63  4997.0  289.78  4999.7  289.28  5003.0  289.78  5008.3  292.96
  5013.9  294.19  5022.3  299.03  5030.7  299.58  5036.3  300.98  5053.1  303.09
  5058.7  302.85  5062.2  303.37  5067.0  303.77  5075.4  305.13  5089.4  306.25
#Mann=5,-1,0
  4694.8    0.05       0  4893.1    0.16       0  4997.0    0.07       0
  5003.0    0.16       0  5062.2    0.05       0
Bank Sta=4997,5003
Exp/Cntr=0.3,0.1

Type RM Length L Ch R = 1,631,256,256,256
BEGIN DESCRIPTION:
Mapping XS 4fdbd59c
END DESCRIPTION:
XS GIS Cut Line= 2
      3676672.16     10676452.57      3676444.46     10676096.92
#Sta/Elev= 30
  4807.2  309.10  4839.7  307.72  4845.7  306.44  4854.9  306.67  4880.7  303.73
  4891.3  302.94  4918.4  298.80  4940.6  297.21  4948.8  292.19  4954.7  292.69
  4991.1  291.21  4997.0  288.78  4999.8  288.28  5003.0  288.78  5006.3  292.38
  5021.5  291.94  5035.6  293.20  5048.6  292.27  5063.8  293.36  5076.1  293.27
  5100.2  293.10  5115.4  295.31  5157.7  297.17  5166.3  299.53  5188.1  300.60
  5194.0  301.82  5209.2  302.44  5215.2  303.69  5224.5  303.71  5229.5  304.64
#Mann=5,-1,0
  4807.2    0.05       0  4880.7    0.16       0  4997.0    0.07       0
  5003.0    0.16       0  5076.1    0.05       0
Bank Sta=4997,5003
Exp/Cntr=0.3,0.1

Type RM Length L Ch R = 1,375,350,350,350
BEGIN DESCRIPTION:
Mapping XS 83d2c5c3
END DESCRIPTION:
XS GIS Cut Line= 2
      3676776.31     10676335.34      3676635.27     10675920.89
#Sta/Elev= 30
  4773.7  308.15  4776.4  308.01  4781.7  306.00  4789.7  304.98  4800.3  304.41
  4807.8  303.23  4844.4  300.15  4853.1  298.92  4863.7  298.43  4870.5  297.06
  4875.8  297.17  4933.2  291.58  4990.4  290.04  4993.0  287.10  4995.7  286.60
  4999.0  287.10  5001.3  288.08  5032.7  291.39  5043.2  291.03  5053.4  291.72
  5058.7  293.09  5074.9  294.65  5084.8  294.11  5096.0  295.57  5106.5  295.94
  5152.8  300.02  5159.4  301.48  5170.0  301.56  5184.2  303.23  5211.5  304.32
#Mann=4,-1,0
  4773.7    0.16       0  4993.0    0.07       0  4999.0    0.16       0
  5106.5    0.05       0
Bank Sta=4993,4999
Exp/Cntr=0.3,0.1

Type RM Length L Ch R = 1,25,0,0,0
BEGIN DESCRIPTION:
UNT 176 IN CACR 1.0
END DESCRIPTION:
XS GIS Cut Line= 3
      3676882.66     10676324.50      3676913.04     10676033.73
      3676824.45     10675895.43
#Sta/Elev= 30
  4742.1  303.29  4756.1  302.92  4796.7  298.41  4826.9  296.56  4859.6  293.79
  4877.1  292.65  4904.4  291.62  4917.4  290.74  4937.5  290.54  4947.5  289.30
  4958.0  288.64  4997.8  288.04  5007.9  284.72  5014.9  284.57  5017.7  284.07
  5020.9  284.57  5028.0  289.58  5039.5  289.55  5047.3  288.70  5053.3  289.34
  5098.0  290.14  5120.1  292.94  5126.0  291.59  5141.2  294.53  5147.1  294.51
  5169.3  296.87  5177.5  296.68  5181.7  297.57  5192.8  298.50  5198.7  299.48
#Mann=5,-1,0
  4742.1    0.05       0  4904.4    0.16       0  5014.9    0.07       0
  5020.9    0.16       0  5181.7    0.05       0
Bank Sta=5014.9,5020.9
Exp/Cntr=0.3,0.1

Chan Stop Cuts=-1