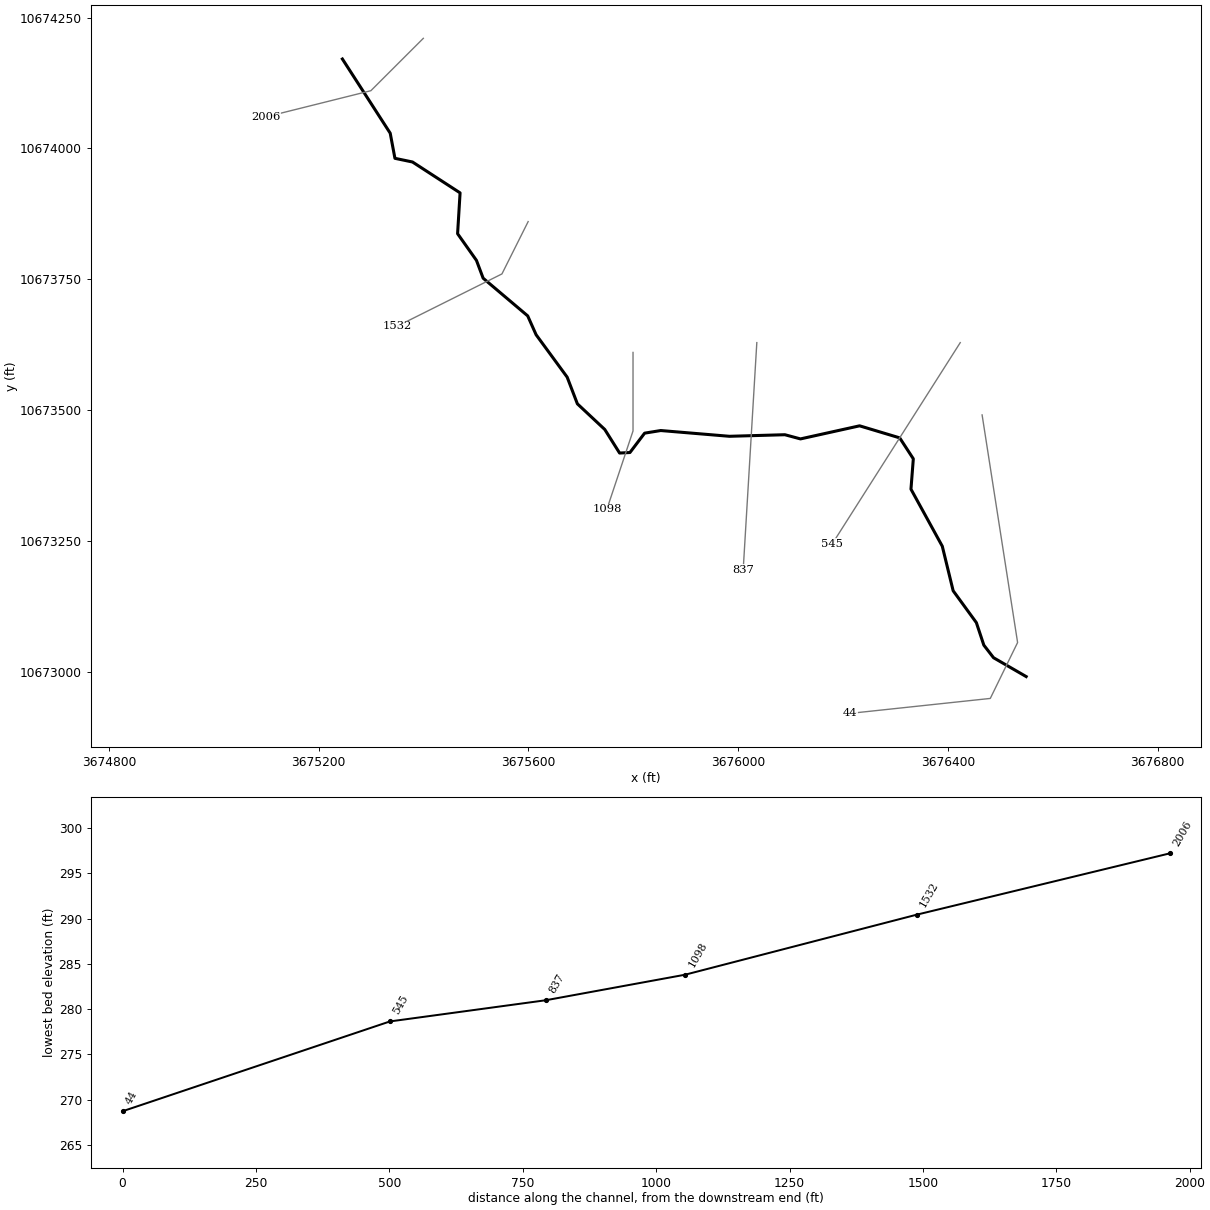
--- UNT 177 IN CACR.prj (project) ---

Proj Title=UNT 177 IN CACR Base Level Engineering
Current Plan=p01
Default Exp/Contr=0.3,0.1
English Units
Geom File=g01
Flow File=f01
Plan File=p01
BEGIN DESCRIPTION:
UNT 177 IN CACR
END DESCRIPTION:

--- UNT 177 IN CACR.p01 (plan) ---

Plan Title=Multiple Run
Short Identifier=Multiple
Geom File=g01
Flow File=f01
Subcritical Flow
K Sum by GR= 0
Std Step Tol= 0.01
Critical Tol= 0.01
Num of Std Step Trials= 20
Max Error Tol= 0.3
Flow Tol Ratio= 0.001
Split Flow NTrial= 30
Split Flow Tol= 0.02
Split Flow Ratio= 0.02
Log Output Level= 0
Friction Slope Method= 1
Unsteady Friction Slope Method= 2
Unsteady Bridges Friction Slope Method= 1
Parabolic Critical Depth
Global Vel Dist=  1 , 1 , 1
Global Log Level= 0
CheckData=True
Encroach Param= -1, 0, 0, 0
BEGIN DESCRIPTION:
Multiple Run
END DESCRIPTION:

--- UNT 177 IN CACR.f01 (steady flow) ---

Flow Title=Multiple
Number of Profiles=7
Profile Names=10-year,25-year,50-year,1pct_min,100-year,1pct_plu,500-year
River Rch & RM= UNT 177 IN CACR,Reach-1,2006
     146     181     207     176     238     322     313
River Rch & RM= UNT 177 IN CACR,Reach-1,44
     790    1082    1325    1191    1610    2178    2389
Boundary for River Rch & Prof#=UNT 177 IN CACR,Reach-1,1
Up Type=0
Dn Type=3
Dn Slope=0.005
Boundary for River Rch & Prof#=UNT 177 IN CACR,Reach-1,2
Up Type=0
Dn Type=3
Dn Slope=0.005
Boundary for River Rch & Prof#=UNT 177 IN CACR,Reach-1,3
Up Type=0
Dn Type=3
Dn Slope=0.005
Boundary for River Rch & Prof#=UNT 177 IN CACR,Reach-1,4
Up Type=0
Dn Type=3
Dn Slope=0.005
Boundary for River Rch & Prof#=UNT 177 IN CACR,Reach-1,5
Up Type=0
Dn Type=3
Dn Slope=0.005
Boundary for River Rch & Prof#=UNT 177 IN CACR,Reach-1,6
Up Type=0
Dn Type=3
Dn Slope=0.005
Boundary for River Rch & Prof#=UNT 177 IN CACR,Reach-1,7
Up Type=0
Dn Type=3
Dn Slope=0.005

--- UNT 177 IN CACR.g01 (geometry) ---

Geom Title=Existing Conditions

River Reach=UNT 177 IN CACR,Reach-1
Reach XY= 30
      3675245.28     10674170.74      3675336.50     10674029.00
      3675345.50     10673981.00      3675379.00     10673974.00
      3675469.75     10673915.00      3675465.00     10673837.00
      3675501.00     10673786.00      3675513.75     10673752.00
      3675598.75     10673680.00      3675614.75     10673644.00
      3675674.00     10673563.00      3675693.50     10673512.00
      3675745.75     10673463.00      3675774.00     10673418.00
      3675793.75     10673419.00      3675821.75     10673456.00
      3675852.50     10673461.00      3675983.50     10673450.00
      3676089.25     10673453.00      3676119.00     10673445.00
      3676231.75     10673470.00      3676308.25     10673447.00
      3676334.25     10673407.00      3676329.75     10673349.00
      3676389.50     10673240.00      3676410.24     10673154.88
      3676454.50     10673094.00      3676468.75     10673051.00
      3676487.25     10673027.00      3676549.50     10672991.00

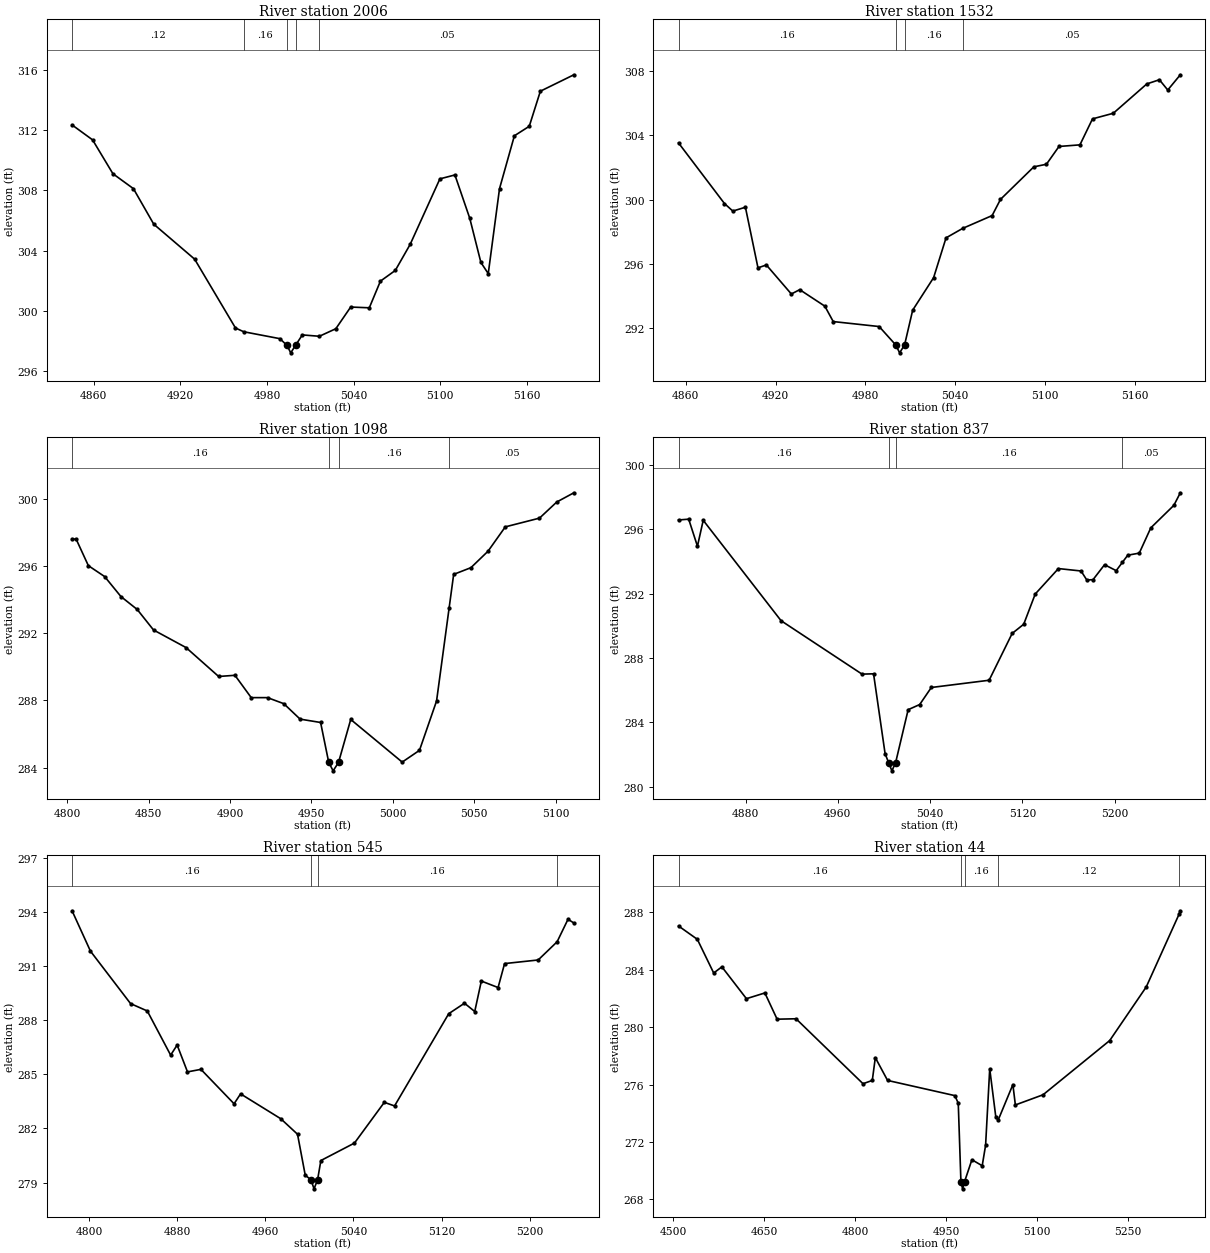
Type RM Length L Ch R = 1,2006,474,474,474
BEGIN DESCRIPTION:
UNT 177 IN CACR 4.0
END DESCRIPTION:
XS GIS Cut Line= 3
      3675399.64     10674210.22      3675299.61     10674110.19
      3675099.62     10674060.19
#Sta/Elev= 30
  4844.9  312.34  4859.1  311.35  4873.2  309.10  4887.4  308.11  4901.5  305.75
  4929.8  303.43  4958.1  298.86  4963.8  298.61  4988.9  298.15  4993.7  297.71
  4996.4  297.21  4999.7  297.71  5004.4  298.40  5016.2  298.31  5027.6  298.81
  5037.9  300.25  5050.8  300.20  5058.5  301.97  5068.8  302.68  5079.1  304.41
  5099.7  308.76  5110.1  309.02  5120.4  306.14  5128.1  303.21  5133.2  302.47
  5141.0  308.11  5151.3  311.62  5161.6  312.25  5169.3  314.58  5192.5  315.67
#Mann=5,-1,0
  4844.9    0.12       0  4963.8    0.16       0  4993.7    0.07       0
  4999.7    0.16       0  5016.2    0.05       0
Bank Sta=4993.7,4999.7
Exp/Cntr=0.3,0.1

Type RM Length L Ch R = 1,1532,434,434,434
BEGIN DESCRIPTION:
UNT 177 IN CACR 3.0
END DESCRIPTION:
XS GIS Cut Line= 3
      3675599.59     10673860.15      3675549.61     10673760.19
      3675349.58     10673660.17
#Sta/Elev= 30
  4855.1  303.53  4885.8  299.75  4891.4  299.28  4899.8  299.52  4908.2  295.74
  4913.8  295.92  4930.5  294.11  4936.1  294.38  4952.9  293.35  4958.5  292.39
  4989.2  292.08  5000.2  290.94  5002.9  290.44  5006.2  290.94  5011.6  293.10
  5025.6  295.13  5033.9  297.61  5045.0  298.20  5064.7  299.00  5070.3  300.01
  5092.6  302.04  5101.0  302.20  5109.4  303.31  5123.4  303.41  5131.8  305.03
  5145.7  305.38  5168.1  307.21  5176.5  307.47  5182.1  306.83  5190.5  307.78
#Mann=4,-1,0
  4855.1    0.16       0  5000.2    0.07       0  5006.2    0.16       0
  5045.0    0.05       0
Bank Sta=5000.2,5006.2
Exp/Cntr=0.3,0.1

Type RM Length L Ch R = 1,1098,261,261,261
BEGIN DESCRIPTION:
UNT 177 IN CACR 2.0
END DESCRIPTION:
XS GIS Cut Line= 3
      3675799.61     10673610.20      3675799.61     10673460.19
      3675749.62     10673310.21
#Sta/Elev= 30
  4803.0  297.61  4805.5  297.61  4813.0  296.03  4823.0  295.38  4833.0  294.19
  4843.0  293.42  4853.0  292.20  4873.0  291.15  4893.0  289.43  4903.0  289.50
  4913.0  288.17  4923.0  288.17  4933.0  287.81  4943.0  286.89  4955.6  286.69
  4960.6  284.31  4963.3  283.81  4966.6  284.31  4974.1  286.87  5005.7  284.33
  5016.3  285.03  5026.8  287.97  5034.5  293.50  5037.3  295.51  5047.9  295.91
  5058.4  296.89  5069.0  298.34  5090.0  298.86  5100.6  299.82  5111.1  300.37
#Mann=4,-1,0
  4803.0    0.16       0  4960.6    0.07       0  4966.6    0.16       0
  5034.5    0.05       0
Bank Sta=4960.6,4966.6
Exp/Cntr=0.3,0.1

Type RM Length L Ch R = 1,837,292,292,292
BEGIN DESCRIPTION:
Mapping XS d72f3ab5
END DESCRIPTION:
XS GIS Cut Line= 2
      3676035.74     10673628.96      3676009.74     10673194.64
#Sta/Elev= 30
  4821.9  296.58  4830.7  296.63  4838.3  294.95  4843.3  296.56  4910.8  290.32
  4981.0  287.00  4991.0  287.02  5001.0  282.06  5004.1  281.49  5006.9  280.99
  5010.1  281.49  5021.0  284.79  5031.0  285.11  5041.1  286.17  5091.2  286.62
  5111.2  289.53  5121.2  290.10  5131.2  291.98  5151.3  293.56  5170.9  293.41
  5175.9  292.85  5181.3  292.87  5191.3  293.80  5201.4  293.43  5206.7  293.94
  5211.4  294.39  5221.4  294.52  5231.4  296.09  5251.4  297.49  5257.0  298.27
#Mann=4,-1,0
  4821.9    0.16       0  5004.1    0.07       0  5010.1    0.16       0
  5206.7    0.05       0
Bank Sta=5004.1,5010.1
Exp/Cntr=0.3,0.1

Type RM Length L Ch R = 1,545,501,501,501
BEGIN DESCRIPTION:
Mapping XS a01f7033
END DESCRIPTION:
XS GIS Cut Line= 2
      3676423.76     10673628.92      3676179.50     10673244.33
#Sta/Elev= 30
  4784.5  294.08  4801.2  291.84  4837.6  288.93  4852.8  288.52  4874.0  286.07
  4879.9  286.63  4889.3  285.14  4901.5  285.28  4931.6  283.37  4937.5  283.92
  4974.0  282.54  4989.2  281.68  4996.2  279.41  5001.4  279.15  5004.2  278.65
  5007.4  279.15  5010.4  280.22  5040.9  281.19  5068.0  283.45  5077.3  283.25
  5126.5  288.37  5140.8  288.95  5150.1  288.49  5156.1  290.18  5171.3  289.82
  5177.2  291.15  5207.7  291.35  5224.9  292.36  5234.8  293.61  5240.1  293.40
#Mann=4,-1,0
  4784.5    0.16       0  5001.4    0.07       0  5007.4    0.16       0
  5224.9    0.05       0
Bank Sta=5001.4,5007.4
Exp/Cntr=0.3,0.1

Type RM Length L Ch R = 1,44,0,0,0
BEGIN DESCRIPTION:
UNT 177 IN CACR 1.0
END DESCRIPTION:
XS GIS Cut Line= 4
      3676465.44     10673490.86      3676533.14     10673056.01
      3676481.06     10672949.24      3676213.76     10672920.69
#Sta/Elev= 30
  4508.6  287.06  4539.6  286.13  4566.6  283.78  4580.1  284.21  4620.6  281.99
  4651.0  282.39  4671.2  280.56  4702.4  280.59  4812.9  276.06  4828.2  276.29
  4833.2  277.88  4853.4  276.29  4964.4  275.23  4970.0  274.70  4974.4  269.23
  4977.2  268.73  4980.4  269.23  4992.5  270.76  5009.5  270.34  5015.1  271.77
  5021.9  277.10  5032.0  273.72  5035.9  273.53  5060.1  276.00  5064.2  274.58
  5109.9  275.29  5219.8  279.07  5280.1  282.81  5334.1  287.87  5336.3  288.12
#Mann=5,-1,0
  4508.6    0.16       0  4974.4    0.07       0  4980.4    0.16       0
  5035.9    0.12       0  5334.1    0.16       0
Bank Sta=4974.4,4980.4
Exp/Cntr=0.3,0.1

Chan Stop Cuts=-1