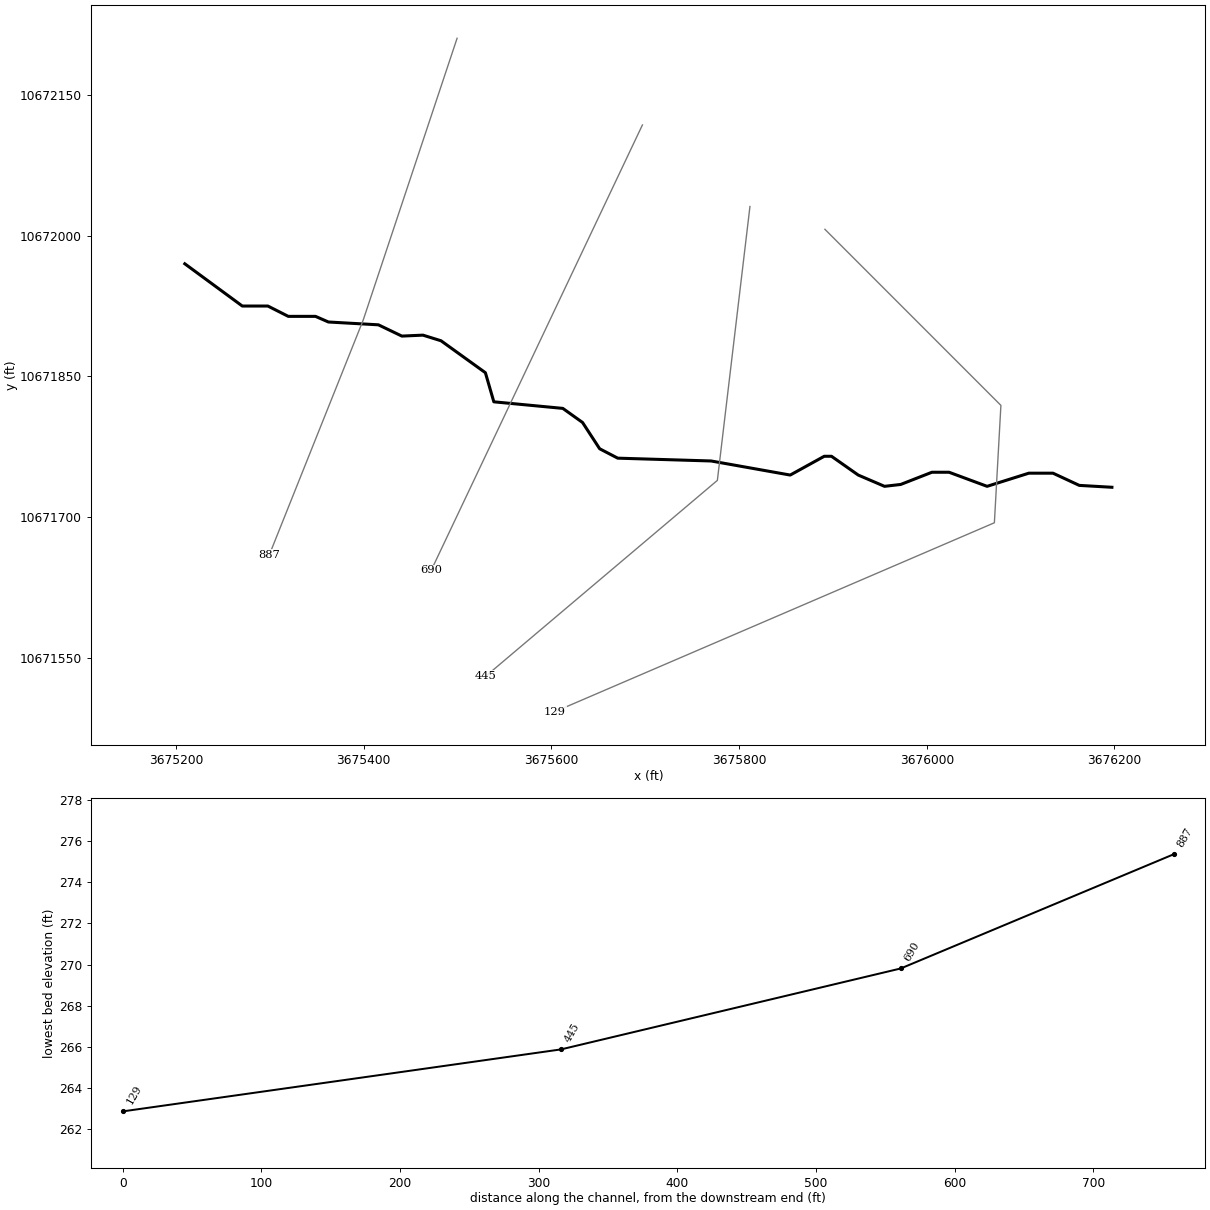
--- UNT 178 IN CACR.prj (project) ---

Proj Title=UNT 178 IN CACR Base Level Engineering
Current Plan=p01
Default Exp/Contr=0.3,0.1
English Units
Geom File=g01
Flow File=f01
Plan File=p01
BEGIN DESCRIPTION:
UNT 178 IN CACR
END DESCRIPTION:

--- UNT 178 IN CACR.p01 (plan) ---

Plan Title=Multiple Run
Short Identifier=Multiple
Geom File=g01
Flow File=f01
Subcritical Flow
K Sum by GR= 0
Std Step Tol= 0.01
Critical Tol= 0.01
Num of Std Step Trials= 20
Max Error Tol= 0.3
Flow Tol Ratio= 0.001
Split Flow NTrial= 30
Split Flow Tol= 0.02
Split Flow Ratio= 0.02
Log Output Level= 0
Friction Slope Method= 1
Unsteady Friction Slope Method= 2
Unsteady Bridges Friction Slope Method= 1
Parabolic Critical Depth
Global Vel Dist=  1 , 1 , 1
Global Log Level= 0
CheckData=True
Encroach Param= -1, 0, 0, 0
BEGIN DESCRIPTION:
Multiple Run
END DESCRIPTION:

--- UNT 178 IN CACR.f01 (steady flow) ---

Flow Title=Multiple
Number of Profiles=7
Profile Names=10-year,25-year,50-year,1pct_min,100-year,1pct_plu,500-year
River Rch & RM= UNT 178 IN CACR,Reach-1,887
     251     321     376     325     439     594     599
Boundary for River Rch & Prof#=UNT 178 IN CACR,Reach-1,1
Up Type=0
Dn Type=3
Dn Slope=0.005
Boundary for River Rch & Prof#=UNT 178 IN CACR,Reach-1,2
Up Type=0
Dn Type=3
Dn Slope=0.005
Boundary for River Rch & Prof#=UNT 178 IN CACR,Reach-1,3
Up Type=0
Dn Type=3
Dn Slope=0.005
Boundary for River Rch & Prof#=UNT 178 IN CACR,Reach-1,4
Up Type=0
Dn Type=3
Dn Slope=0.005
Boundary for River Rch & Prof#=UNT 178 IN CACR,Reach-1,5
Up Type=0
Dn Type=3
Dn Slope=0.005
Boundary for River Rch & Prof#=UNT 178 IN CACR,Reach-1,6
Up Type=0
Dn Type=3
Dn Slope=0.005
Boundary for River Rch & Prof#=UNT 178 IN CACR,Reach-1,7
Up Type=0
Dn Type=3
Dn Slope=0.005

--- UNT 178 IN CACR.g01 (geometry) ---

Geom Title=Existing Conditions

River Reach=UNT 178 IN CACR,Reach-1
Reach XY= 30
      3675209.50     10671970.00      3675270.75     10671925.00
      3675298.00     10671925.00      3675319.75     10671914.00
      3675348.75     10671914.00      3675362.50     10671908.00
      3675415.75     10671905.00      3675440.75     10671893.00
      3675463.25     10671894.00      3675482.50     10671888.00
      3675529.75     10671854.00      3675538.75     10671823.00
      3675612.25     10671816.00      3675633.25     10671801.00
      3675651.50     10671773.00      3675670.75     10671763.00
      3675770.25     10671760.00      3675854.50     10671745.00
      3675890.75     10671765.00      3675898.50     10671765.00
      3675927.00     10671745.00      3675955.00     10671733.00
      3675972.25     10671735.00      3676005.50     10671748.00
      3676023.75     10671748.00      3676064.25     10671733.00
      3676108.75     10671747.00      3676134.50     10671747.00
      3676162.50     10671734.00      3676197.25     10671732.00

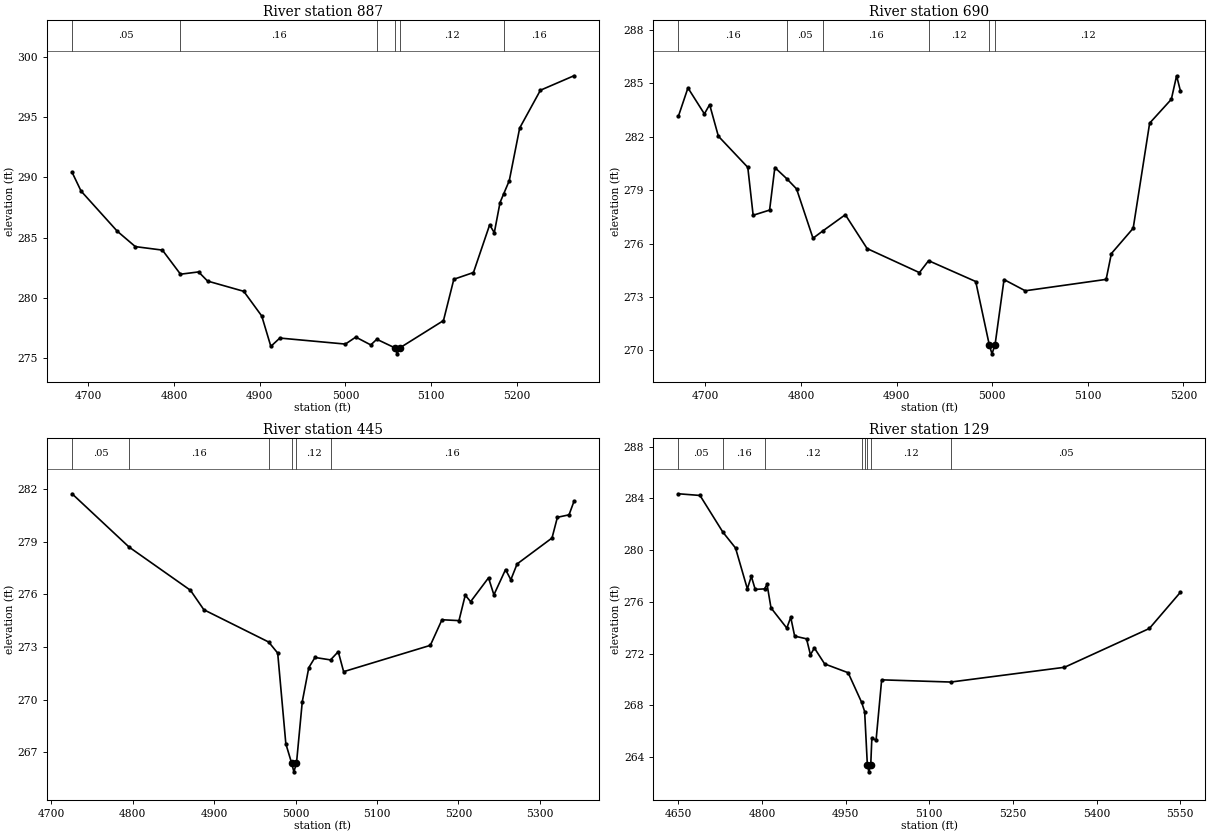
Type RM Length L Ch R = 1,887,197,197,197
BEGIN DESCRIPTION:
UNT 178 IN CACR 2.0
END DESCRIPTION:
XS GIS Cut Line= 3
      3675499.60     10672210.17      3675399.61     10671910.19
      3675299.60     10671660.15
#Sta/Elev= 30
  4681.0  290.43  4691.5  288.87  4733.7  285.54  4754.8  284.26  4786.4  283.97
  4807.5  281.97  4828.6  282.16  4839.1  281.40  4881.3  280.55  4902.3  278.50
  4912.9  275.98  4923.4  276.67  4999.9  276.17  5012.0  276.75  5029.5  276.10
  5036.5  276.57  5057.5  275.86  5060.2  275.36  5063.5  275.86  5114.3  278.12
  5126.4  281.55  5149.3  282.11  5168.2  286.07  5173.6  285.41  5180.3  287.92
  5184.4  288.61  5191.1  289.74  5203.2  294.10  5227.4  297.24  5266.5  298.44
#Mann=6,-1,0
  4681.0    0.05       0  4807.5    0.16       0  5036.5    0.12       0
  5057.5    0.07       0  5063.5    0.12       0  5184.4    0.16       0
Bank Sta=5057.5,5063.5
Exp/Cntr=0.3,0.1

Type RM Length L Ch R = 1,690,245,245,245
BEGIN DESCRIPTION:
Mapping XS 9139a197
END DESCRIPTION:
XS GIS Cut Line= 2
      3675697.05     10672117.84      3675472.05     10671643.61
#Sta/Elev= 30
  4671.8  283.16  4681.7  284.74  4698.9  283.28  4704.4  283.80  4713.5  282.03
  4744.3  280.28  4749.9  277.59  4767.1  277.88  4772.6  280.27  4785.1  279.64
  4795.3  279.07  4812.5  276.30  4822.8  276.71  4846.3  277.62  4869.1  275.72
  4923.8  274.37  4933.4  275.04  4982.7  273.87  4996.9  270.31  4999.7  269.81
  5002.9  270.31  5012.3  273.98  5034.5  273.35  5119.1  273.99  5124.6  275.44
  5147.4  276.86  5164.6  282.76  5187.3  284.10  5192.8  285.42  5196.7  284.59
#Mann=6,-1,0
  4671.8    0.16       0  4785.1    0.05       0  4822.8    0.16       0
  4933.4    0.12       0  4996.9    0.07       0  5002.9    0.12       0
Bank Sta=4996.9,5002.9
Exp/Cntr=0.3,0.1

Type RM Length L Ch R = 1,445,316,316,316
BEGIN DESCRIPTION:
Mapping XS 9ebfc2c9
END DESCRIPTION:
XS GIS Cut Line= 3
      3675811.62     10672030.99      3675776.90     10671739.34
      3675530.35     10671530.99
#Sta/Elev= 30
  4725.5  281.73  4795.6  278.69  4870.9  276.23  4887.4  275.12  4967.0  273.28
  4978.1  272.65  4988.1  267.48  4995.2  266.38  4998.0  265.88  5001.2  266.38
  5008.3  269.88  5016.3  271.82  5023.9  272.40  5043.0  272.26  5052.5  272.73
  5059.1  271.59  5165.6  273.09  5179.9  274.55  5200.8  274.50  5208.5  275.95
  5215.1  275.58  5237.1  276.94  5243.7  275.97  5258.0  277.41  5264.5  276.83
  5272.2  277.73  5315.1  279.21  5321.7  280.39  5336.0  280.53  5342.0  281.29
#Mann=6,-1,0
  4725.5    0.05       0  4795.6    0.16       0  4967.0    0.12       0
  4995.2    0.07       0  5001.2    0.12       0  5043.0    0.16       0
Bank Sta=4995.2,5001.2
Exp/Cntr=0.3,0.1

Type RM Length L Ch R = 1,129,0,0,0
BEGIN DESCRIPTION:
UNT 178 IN CACR 1.0
END DESCRIPTION:
XS GIS Cut Line= 4
      3675891.49     10672006.70      3676078.99     10671819.20
      3676072.04     10671694.20      3675603.97     10671493.10
#Sta/Elev= 30
  4650.2  284.36  4688.8  284.23  4729.9  281.39  4752.5  280.17  4773.7  277.01
  4780.8  277.98  4787.8  276.97  4804.5  277.01  4809.0  277.36  4816.1  275.54
  4844.4  273.98  4851.5  274.81  4858.5  273.36  4879.8  273.15  4886.8  271.92
  4893.9  272.44  4912.3  271.21  4954.4  270.53  4978.6  268.24  4984.0  267.53
  4988.9  263.37  4991.6  262.87  4994.9  263.37  4996.9  265.47  5004.5  265.32
  5014.5  269.98  5138.4  269.81  5342.3  270.95  5494.5  273.95  5550.0  276.74
#Mann=8,-1,0
  4650.2    0.05       0  4729.9    0.16       0  4804.5    0.12       0
  4978.6    0.16       0  4984.0    0.12       0  4988.9    0.07       0
  4994.9    0.12       0  5138.4    0.05       0
Bank Sta=4988.9,4994.9
Exp/Cntr=0.3,0.1

Chan Stop Cuts=-1