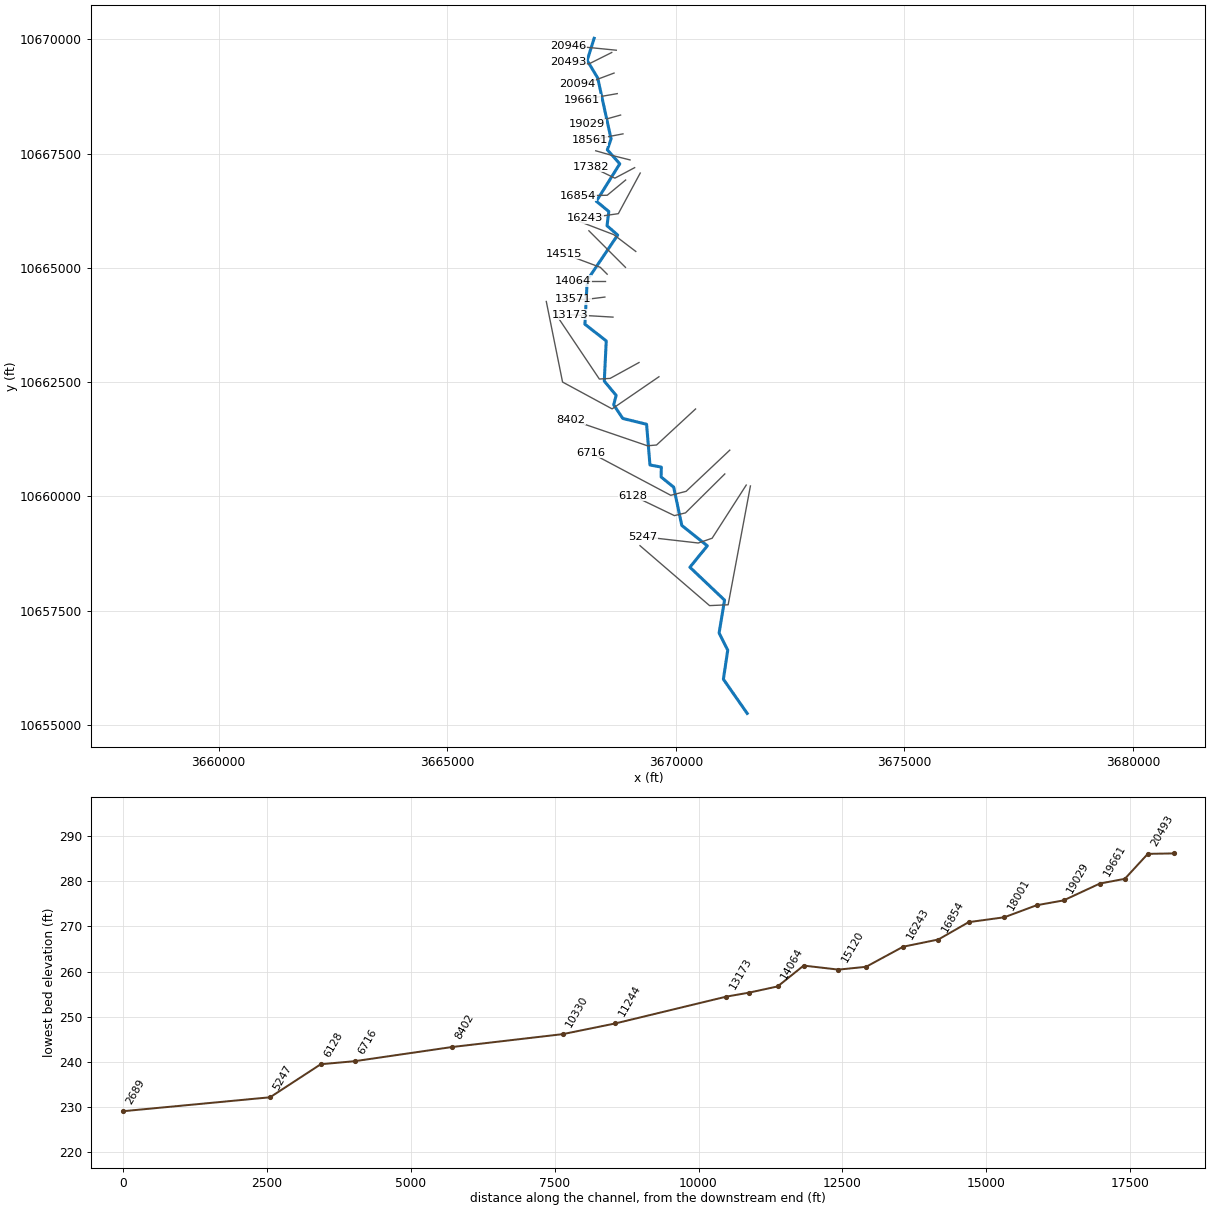
--- UNT 179 IN CACR.prj (project) ---

Proj Title=UNT 179 IN CACR Base Level Engineering
Current Plan=p01
Default Exp/Contr=0.3,0.1
English Units
Geom File=g01
Flow File=f01
Flow File=f02
Flow File=f03
Plan File=p01
Plan File=p02
Plan File=p03
BEGIN DESCRIPTION:
UNT 179 IN CACR
END DESCRIPTION:

--- UNT 179 IN CACR.p01 (plan) ---

Plan Title=Multiple Run
Short Identifier=Multiple
Geom File=g01
Flow File=f01
Subcritical Flow
K Sum by GR= 0
Std Step Tol= 0.01
Critical Tol= 0.01
Num of Std Step Trials= 20
Max Error Tol= 0.3
Flow Tol Ratio= 0.001
Split Flow NTrial= 30
Split Flow Tol= 0.02
Split Flow Ratio= 0.02
Log Output Level= 0
Friction Slope Method= 1
Unsteady Friction Slope Method= 2
Unsteady Bridges Friction Slope Method= 1
Parabolic Critical Depth
Global Vel Dist=  1 , 1 , 1
Global Log Level= 0
CheckData=True
Encroach Param= -1, 0, 0, 0
BEGIN DESCRIPTION:
Multiple Run
END DESCRIPTION:

--- UNT 179 IN CACR.p02 (plan) ---

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Plan Title=Floodway Run
Short Identifier=Floodway
Geom File=g01
Flow File=f02
Floodway Run

--- UNT 179 IN CACR.p03 (plan) ---

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Plan Title=100-Year Single
Short Identifier=100Year
Geom File=g01
Flow File=f03
100Year Run

--- UNT 179 IN CACR.f01 (steady flow) ---

Flow Title=Multiple
Number of Profiles=4
Profile Names=10-year,50-year,100-year,500-year
River Rch & RM= UNT 179 IN CACR,Reach-1,20946
     483     740     856    1137
River Rch & RM= UNT 179 IN CACR,Reach-1,19661
     711    1089    1260    1672
River Rch & RM= UNT 179 IN CACR,Reach-1,11244
     874    1338    1548    2054
Boundary for River Rch & Prof#=UNT 179 IN CACR,Reach-1,1
Up Type=0
Dn Type=3
Dn Slope=0.005
Boundary for River Rch & Prof#=UNT 179 IN CACR,Reach-1,2
Up Type=0
Dn Type=3
Dn Slope=0.005
Boundary for River Rch & Prof#=UNT 179 IN CACR,Reach-1,3
Up Type=0
Dn Type=3
Dn Slope=0.005
Boundary for River Rch & Prof#=UNT 179 IN CACR,Reach-1,4
Up Type=0
Dn Type=3
Dn Slope=0.005

--- UNT 179 IN CACR.f02 (steady flow) ---

Flow Title=Floodway
Number of Profiles=2
Profile Names=100-year,100-FW
River Rch & RM= UNT 179 IN CACR,Reach-1,20946
     856     856
River Rch & RM= UNT 179 IN CACR,Reach-1,19661
    1260    1260
River Rch & RM= UNT 179 IN CACR,Reach-1,11244
    1548    1548
Boundary for River Rch & Prof#=UNT 179 IN CACR,Reach-1,1
Up Type=0
Dn Type=3
Dn Slope=0.005
Boundary for River Rch & Prof#=UNT 179 IN CACR,Reach-1,2
Up Type=0
Dn Type=3
Dn Slope=0.005

--- UNT 179 IN CACR.f03 (steady flow) ---

Flow Title=100-year Single
Number of Profiles=1
Profile Names=100-year
River Rch & RM= UNT 179 IN CACR,Reach-1,20946
     856
River Rch & RM= UNT 179 IN CACR,Reach-1,19661
    1260
River Rch & RM= UNT 179 IN CACR,Reach-1,11244
    1548
Boundary for River Rch & Prof#=UNT 179 IN CACR,Reach-1,1
Up Type=0
Dn Type=3
Dn Slope=0.005

--- UNT 179 IN CACR.g01 (geometry) ---

Geom Title=Existing Conditions

River Reach=UNT 179 IN CACR,Reach-1
Reach XY= 30
      3668214.49     10670020.01      3668062.00     10669536.00
      3668292.25     10669153.00      3668584.75     10667820.00
      3668503.00     10667581.00      3668775.50     10667275.00
      3668262.50     10666456.00      3668535.25     10666233.00
      3668496.25     10665921.00      3668729.50     10665717.00
      3668063.00     10664729.00      3668012.75     10663766.00
      3668479.00     10663401.00      3668436.50     10662521.00
      3668695.75     10662209.00      3668642.50     10662002.00
      3668841.00     10661705.00      3669361.75     10661577.00
      3669435.50     10660687.00      3669684.25     10660640.00
      3669679.50     10660424.00      3669954.25     10660203.00
      3670132.36     10659363.69      3670690.83     10658918.72
      3670309.25     10658450.00      3671066.75     10657731.00
      3670948.25     10657010.00      3671137.25     10656636.00
      3671041.75     10656000.00      3671562.50     10655253.00

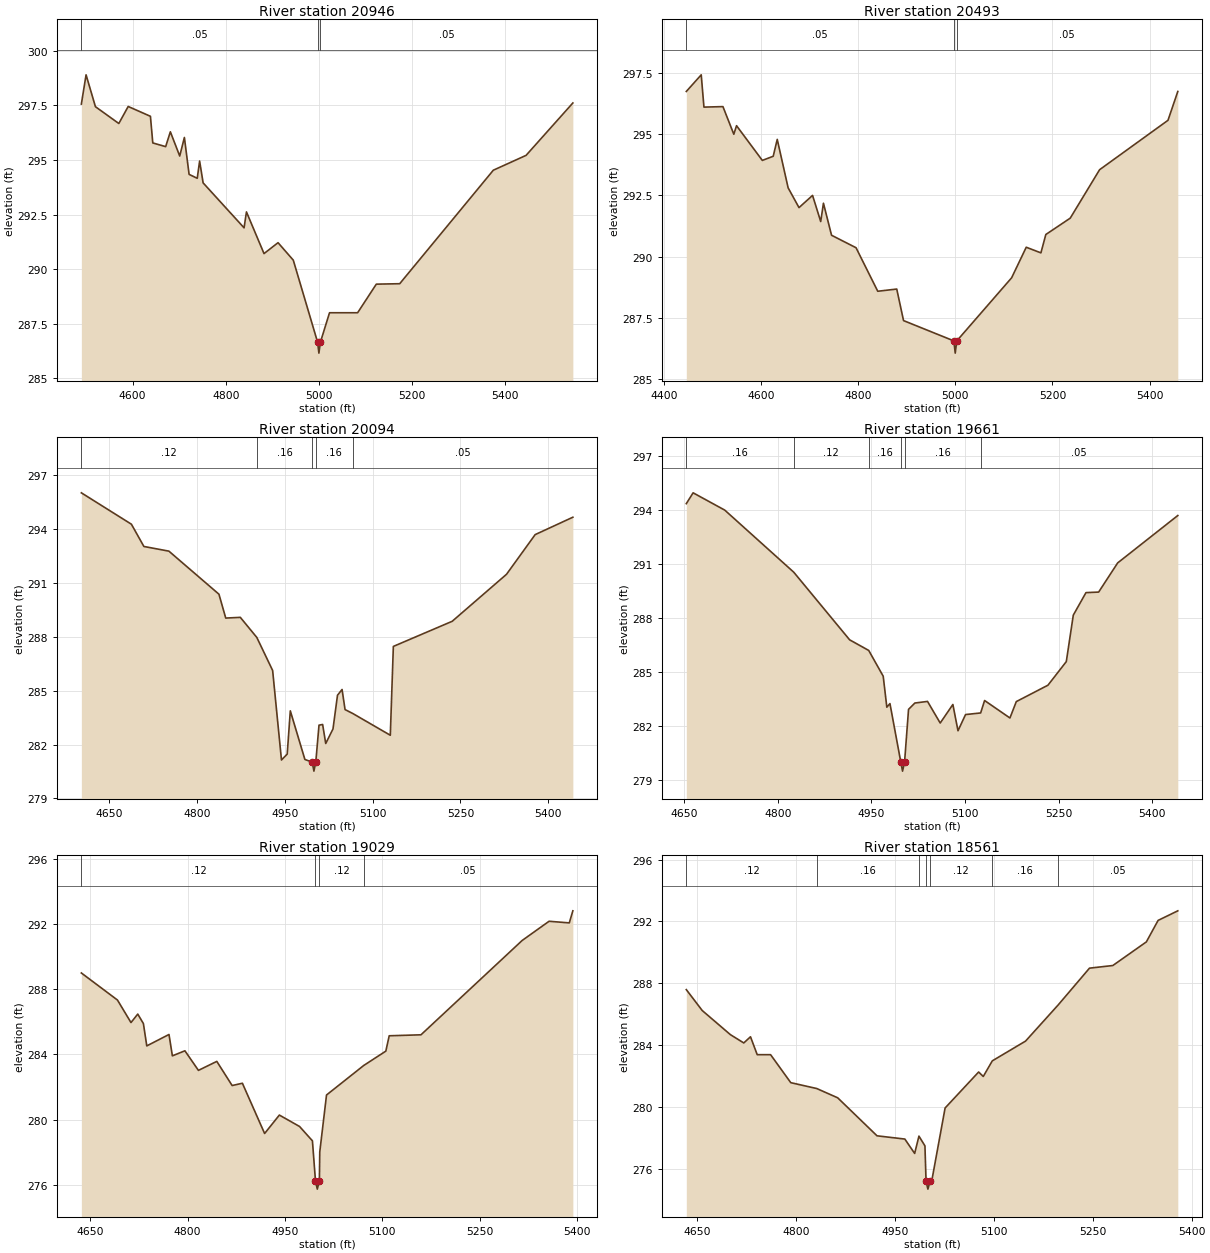
Type RM Length L Ch R = 1,20946,453,453,453
BEGIN DESCRIPTION:
UNT 179 IN CACR 26.0
END DESCRIPTION:
XS GIS Cut Line= 3
      3668699.62     10669760.19      3668199.61     10669810.19
      3667649.58     10669860.19
#Sta/Elev= 30
  4490.0  297.56  4500.1  298.90  4520.2  297.44  4570.4  296.67  4590.5  297.45
  4638.2  297.00  4643.3  295.78  4670.9  295.61  4681.0  296.29  4701.1  295.18
  4711.1  296.03  4721.2  294.34  4738.7  294.16  4743.8  294.95  4751.3  293.95
  4839.2  291.89  4844.3  292.62  4882.0  290.71  4912.1  291.21  4944.8  290.41
  4997.0  286.65  4999.8  286.15  5003.0  286.65  5022.6  288.00  5082.9  288.00
  5123.0  289.31  5173.2  289.33  5374.1  294.53  5444.4  295.21  5544.8  297.61
#Mann=3,-1,0
  4490.0    0.05       0  4997.0    0.03       0  5003.0    0.05       0
Bank Sta=4997,5003
Exp/Cntr=0.3,0.1

Type RM Length L Ch R = 1,20493,399,399,399
BEGIN DESCRIPTION:
UNT 179 IN CACR 25.0
END DESCRIPTION:
XS GIS Cut Line= 3
      3668599.58     10669710.18      3668099.61     10669460.19
      3667649.57     10669510.19
#Sta/Elev= 30
  4446.2  296.75  4476.9  297.43  4482.5  296.11  4521.6  296.13  4544.0  295.00
  4549.6  295.35  4602.7  293.93  4625.1  294.10  4633.4  294.79  4655.8  292.81
  4678.2  292.00  4706.1  292.50  4722.9  291.43  4728.5  292.18  4745.2  290.87
  4795.6  290.36  4840.3  288.58  4879.4  288.67  4893.4  287.38  4997.0  286.55
  4999.8  286.05  5003.0  286.55  5115.9  289.13  5146.0  290.38  5176.2  290.15
  5186.3  290.90  5236.6  291.57  5297.0  293.55  5437.8  295.57  5458.0  296.75
#Mann=3,-1,0
  4446.2    0.05       0  4997.0    0.03       0  5003.0    0.05       0
Bank Sta=4997,5003
Exp/Cntr=0.3,0.1

Type RM Length L Ch R = 1,20094,433,433,433
BEGIN DESCRIPTION:
UNT 179 IN CACR 24.0
END DESCRIPTION:
XS GIS Cut Line= 3
      3668649.63     10669260.20      3668249.61     10669110.19
      3667849.64     10669010.20
#Sta/Elev= 30
  4602.6  296.03  4688.1  294.28  4709.4  293.04  4752.1  292.78  4837.6  290.38
  4849.2  289.05  4874.1  289.09  4902.3  287.97  4929.3  286.13  4944.4  281.14
  4954.2  281.47  4959.5  283.88  4984.4  281.17  4997.0  281.02  4999.8  280.52
  5003.0  281.02  5008.5  283.08  5014.7  283.12  5020.0  282.06  5032.4  282.87
  5040.1  284.75  5047.9  285.07  5053.0  283.95  5066.3  283.73  5130.3  282.52
  5135.5  287.47  5236.0  288.87  5328.8  291.49  5377.7  293.70  5442.1  294.67
#Mann=5,-1,0
  4602.6    0.12       0  4902.3    0.16       0  4997.0    0.07       0
  5003.0    0.16       0  5066.3    0.05       0
Bank Sta=4997,5003
Exp/Cntr=0.3,0.1

Type RM Length L Ch R = 1,19661,632,632,632
BEGIN DESCRIPTION:
UNT 179 IN CACR 23.0
END DESCRIPTION:
XS GIS Cut Line= 2
      3668720.30     10668810.52      3667944.72     10668675.18
#Sta/Elev= 30
  4653.4  294.33  4664.3  294.93  4715.0  293.97  4825.6  290.52  4915.0  286.77
  4945.6  286.18  4968.8  284.75  4974.6  283.03  4979.6  283.23  4997.0  279.98
  4999.8  279.48  5003.0  279.98  5009.4  282.91  5019.5  283.26  5039.8  283.35
  5060.1  282.15  5080.4  283.18  5088.6  281.72  5100.7  282.62  5124.9  282.71
  5131.2  283.40  5171.8  282.43  5182.0  283.34  5232.7  284.25  5262.1  285.56
  5273.3  288.14  5293.6  289.39  5313.9  289.42  5344.4  291.04  5440.7  293.67
#Mann=6,-1,0
  4653.4    0.16       0  4825.6    0.12       0  4945.6    0.16       0
  4997.0    0.07       0  5003.0    0.16       0  5124.9    0.05       0
Bank Sta=4997,5003
Exp/Cntr=0.3,0.1

Type RM Length L Ch R = 1,19029,468,468,468
BEGIN DESCRIPTION:
UNT 179 IN CACR 22.0
END DESCRIPTION:
XS GIS Cut Line= 2
      3668793.19     10668341.76      3668064.34     10668138.73
#Sta/Elev= 30
  4636.6  288.99  4692.2  287.33  4713.0  285.95  4723.4  286.47  4732.1  285.89
  4737.3  284.52  4771.5  285.22  4776.7  283.91  4796.0  284.22  4816.8  283.02
  4845.1  283.57  4868.7  282.09  4884.5  282.23  4918.7  279.15  4941.4  280.28
  4972.5  279.58  4992.3  278.70  4997.0  276.24  4999.8  275.74  5003.0  276.24
  5003.6  278.02  5014.0  281.51  5071.3  283.32  5105.3  284.20  5110.5  285.14
  5159.4  285.20  5315.1  290.98  5356.6  292.16  5387.7  292.06  5393.2  292.80
#Mann=4,-1,0
  4636.6    0.12       0  4997.0    0.07       0  5003.0    0.12       0
  5071.3    0.05       0
Bank Sta=4997,5003
Exp/Cntr=0.3,0.1

Type RM Length L Ch R = 1,18561,560,560,560
BEGIN DESCRIPTION:
UNT 179 IN CACR 21.0
END DESCRIPTION:
XS GIS Cut Line= 2
      3668845.26     10667930.30      3668112.76     10667790.04
#Sta/Elev= 30
  4633.2  287.58  4657.3  286.23  4700.0  284.67  4720.4  284.13  4730.6  284.53
  4740.8  283.37  4761.1  283.37  4791.7  281.56  4831.1  281.18  4862.9  280.58
  4922.6  278.12  4964.8  277.91  4979.7  276.98  4986.2  278.10  4995.3  277.47
  4997.0  275.17  4999.8  274.67  5003.0  275.17  5005.5  275.17  5025.9  279.92
  5076.8  282.25  5083.8  281.96  5097.5  282.97  5148.0  284.25  5197.5  286.59
  5245.0  288.97  5280.4  289.14  5331.3  290.67  5349.1  292.06  5379.0  292.68
#Mann=7,-1,0
  4633.2    0.12       0  4831.1    0.16       0  4986.2    0.12       0
  4997.0    0.07       0  5003.0    0.12       0  5097.5    0.16       0
  5197.5    0.05       0
Bank Sta=4997,5003
Exp/Cntr=0.3,0.1

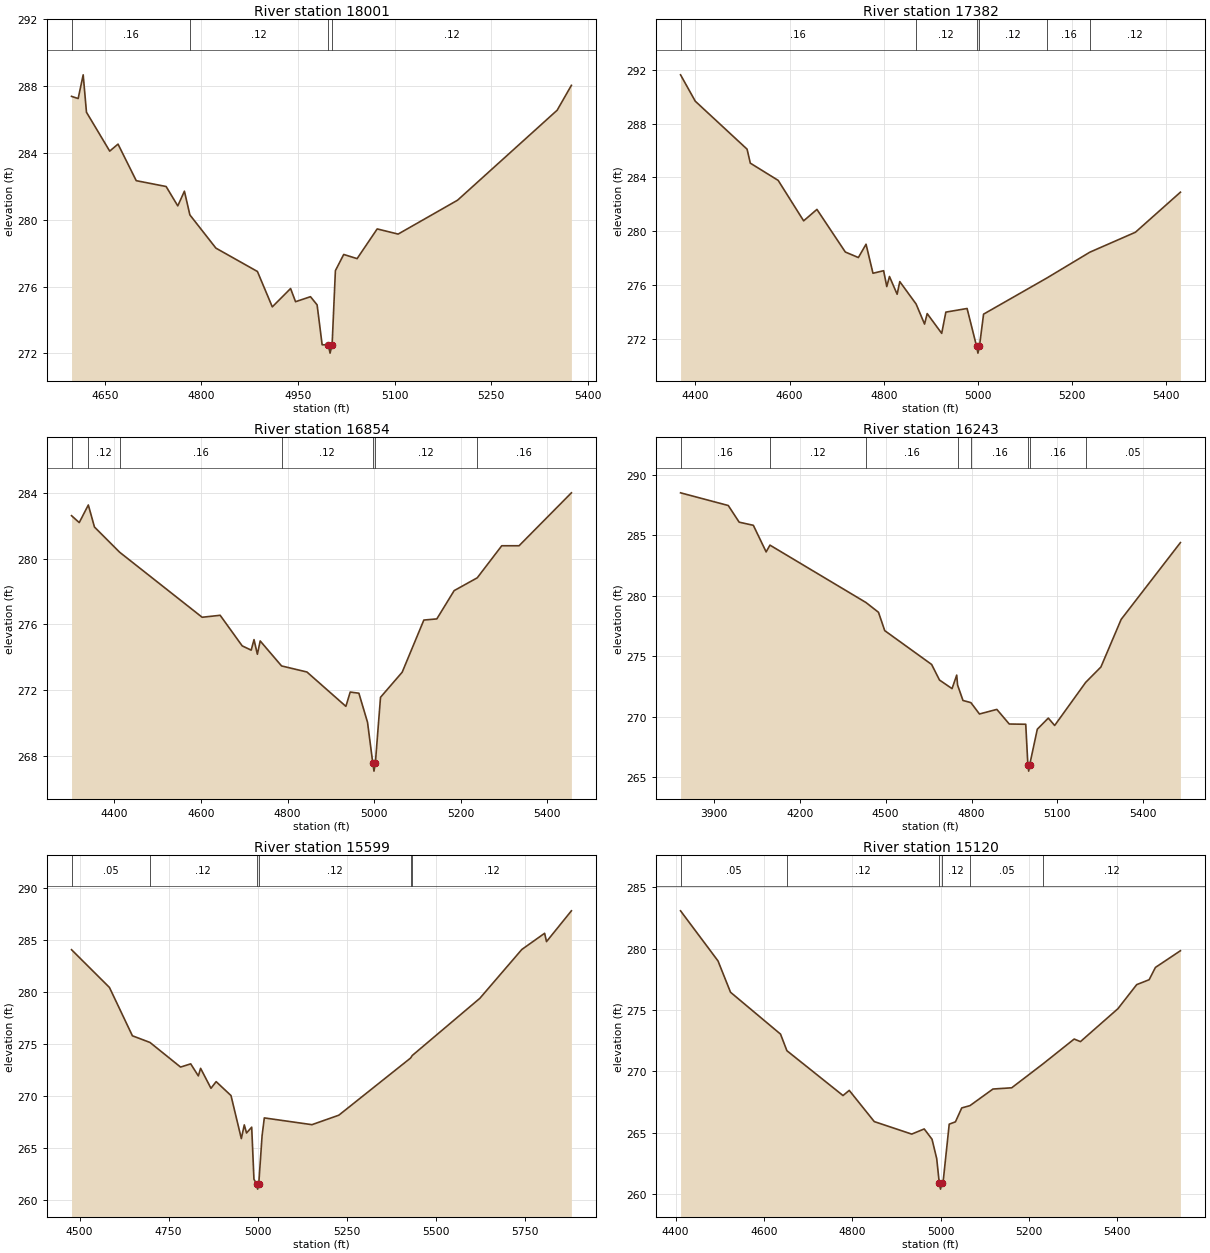
Type RM Length L Ch R = 1,18001,619,619,619
BEGIN DESCRIPTION:
UNT 179 IN CACR 20.0
END DESCRIPTION:
XS GIS Cut Line= 3
      3668999.64     10667360.18      3668599.61     10667460.19
      3668249.66     10667560.17
#Sta/Elev= 30
  4598.3  287.39  4608.6  287.26  4616.4  288.68  4621.5  286.44  4657.6  284.11
  4670.5  284.53  4698.8  282.34  4745.2  281.99  4763.3  280.83  4773.6  281.71
  4782.1  280.29  4822.5  278.30  4887.0  276.90  4910.1  274.78  4938.5  275.88
  4946.2  275.09  4969.4  275.39  4979.7  274.90  4987.5  272.51  4997.0  272.51
  4999.8  272.01  5003.0  272.51  5008.1  276.95  5021.0  277.92  5041.8  277.67
  5073.0  279.45  5105.5  279.14  5197.8  281.17  5352.5  286.56  5374.6  288.05
#Mann=4,-1,0
  4598.3    0.16       0  4782.1    0.12       0  4997.0    0.07       0
  5003.0    0.12       0
Bank Sta=4997,5003
Exp/Cntr=0.3,0.1

Type RM Length L Ch R = 1,17382,528,528,528
BEGIN DESCRIPTION:
UNT 179 IN CACR 19.0
END DESCRIPTION:
XS GIS Cut Line= 3
      3669100.49     10667190.73      3668668.17     10666961.55
      3668153.57     10667211.05
#Sta/Elev= 30
  4368.5  291.63  4399.7  289.67  4509.7  286.10  4516.6  285.06  4575.7  283.78
  4629.8  280.77  4658.0  281.62  4718.3  278.45  4746.0  278.04  4762.3  279.03
  4777.0  276.87  4799.6  277.06  4806.3  275.88  4812.0  276.63  4828.3  275.31
  4833.9  276.25  4868.6  274.58  4886.5  273.09  4892.1  273.87  4922.9  272.40
  4931.7  273.98  4976.8  274.25  4997.0  271.43  4999.8  270.93  5003.0  271.43
  5011.8  273.83  5146.3  276.52  5237.5  278.44  5334.1  279.92  5429.7  282.90
#Mann=6,-1,0
  4368.5    0.16       0  4868.6    0.12       0  4997.0    0.07       0
  5003.0    0.12       0  5146.3    0.16       0  5237.5    0.12       0
Bank Sta=4997,5003
Exp/Cntr=0.3,0.1

Type RM Length L Ch R = 1,16854,611,611,611
BEGIN DESCRIPTION:
UNT 179 IN CACR 18.0
END DESCRIPTION:
XS GIS Cut Line= 3
      3668903.47     10666920.59      3668500.71     10666587.27
      3667868.76     10666573.38
#Sta/Elev= 30
  4301.0  282.62  4318.8  282.20  4339.8  283.27  4354.0  281.93  4412.0  280.40
  4602.8  276.44  4644.4  276.56  4695.3  274.70  4716.1  274.44  4722.6  275.08
  4730.4  274.19  4736.9  275.00  4786.2  273.48  4844.9  273.11  4934.9  271.02
  4944.9  271.89  4964.9  271.82  4984.9  270.05  4997.0  267.58  4999.8  267.08
  5003.0  267.58  5014.9  271.57  5065.0  273.10  5115.0  276.27  5145.0  276.34
  5185.0  278.06  5238.4  278.84  5295.0  280.79  5335.0  280.79  5455.9  284.01
#Mann=7,-1,0
  4301.0    0.16       0  4339.8    0.12       0  4412.0    0.16       0
  4786.2    0.12       0  4997.0    0.07       0  5003.0    0.12       0
  5238.4    0.16       0
Bank Sta=4997,5003
Exp/Cntr=0.3,0.1

Type RM Length L Ch R = 1,16243,644,644,644
BEGIN DESCRIPTION:
UNT 179 IN CACR 17.0
END DESCRIPTION:
XS GIS Cut Line= 3
      3669222.94     10667073.41      3668743.76     10666184.50
      3668014.61     10666080.33
#Sta/Elev= 30
  3783.5  288.53  3950.2  287.48  3988.3  286.10  4037.8  285.84  4082.5  283.64
  4095.8  284.20  4431.2  279.45  4475.0  278.64  4496.9  277.12  4660.7  274.32
  4688.2  273.03  4732.0  272.32  4748.3  273.44  4751.3  272.62  4770.2  271.34
  4797.9  271.16  4827.8  270.22  4888.5  270.60  4931.9  269.39  4989.5  269.37
  4997.0  265.99  4999.8  265.49  5003.0  265.99  5029.9  268.96  5068.3  269.88
  5090.5  269.27  5199.0  272.84  5252.1  274.11  5322.8  278.05  5529.9  284.41
#Mann=8,-1,0
  3783.5    0.16       0  4095.8    0.12       0  4431.2    0.16       0
  4751.3    0.12       0  4797.9    0.16       0  4997.0    0.07       0
  5003.0    0.16       0  5199.0    0.05       0
Bank Sta=4997,5003
Exp/Cntr=0.3,0.1

Type RM Length L Ch R = 1,15599,479,479,479
BEGIN DESCRIPTION:
UNT 179 IN CACR 16.0
END DESCRIPTION:
XS GIS Cut Line= 3
      3669125.72     10665358.09      3668641.91     10665726.16
      3667899.60     10666010.19
#Sta/Elev= 30
  4477.6  284.07  4584.0  280.44  4648.4  275.79  4697.7  275.15  4783.6  272.78
  4812.0  273.09  4833.5  271.93  4839.8  272.66  4868.9  270.74  4883.4  271.38
  4925.1  270.04  4954.1  265.90  4962.4  267.22  4968.7  266.44  4983.2  267.00
  4989.5  261.99  4997.0  261.54  4999.8  261.04  5003.0  261.54  5012.3  266.17
  5018.6  267.89  5152.2  267.24  5227.6  268.15  5429.1  273.65  5433.6  273.89
  5623.3  279.39  5741.1  284.09  5805.2  285.65  5810.5  284.85  5880.3  287.81
#Mann=6,-1,0
  4477.6    0.05       0  4697.7    0.12       0  4997.0    0.07       0
  5003.0    0.12       0  5429.1    0.05       0  5433.6    0.12       0
Bank Sta=4997,5003
Exp/Cntr=0.3,0.1

Type RM Length L Ch R = 1,15120,605,605,605
BEGIN DESCRIPTION:
UNT 179 IN CACR 15.0
END DESCRIPTION:
XS GIS Cut Line= 3
      3668899.60     10665010.20      3668499.61     10665410.19
      3668099.58     10665810.22
#Sta/Elev= 30
  4411.4  283.08  4496.2  279.00  4524.5  276.45  4637.7  273.04  4652.1  271.69
  4779.1  268.04  4793.2  268.46  4849.8  265.92  4934.6  264.90  4962.9  265.32
  4980.6  264.48  4991.2  262.90  4997.0  260.92  4999.8  260.42  5003.0  260.92
  5005.4  260.92  5019.5  265.71  5033.6  265.90  5047.8  267.03  5066.5  267.22
  5118.5  268.57  5160.9  268.67  5231.1  270.60  5302.3  272.64  5316.5  272.43
  5401.3  275.11  5443.8  277.07  5472.0  277.47  5486.2  278.47  5542.8  279.83
#Mann=6,-1,0
  4411.4    0.05       0  4652.1    0.12       0  4997.0    0.07       0
  5003.0    0.12       0  5066.5    0.05       0  5231.1    0.12       0
Bank Sta=4997,5003
Exp/Cntr=0.3,0.1

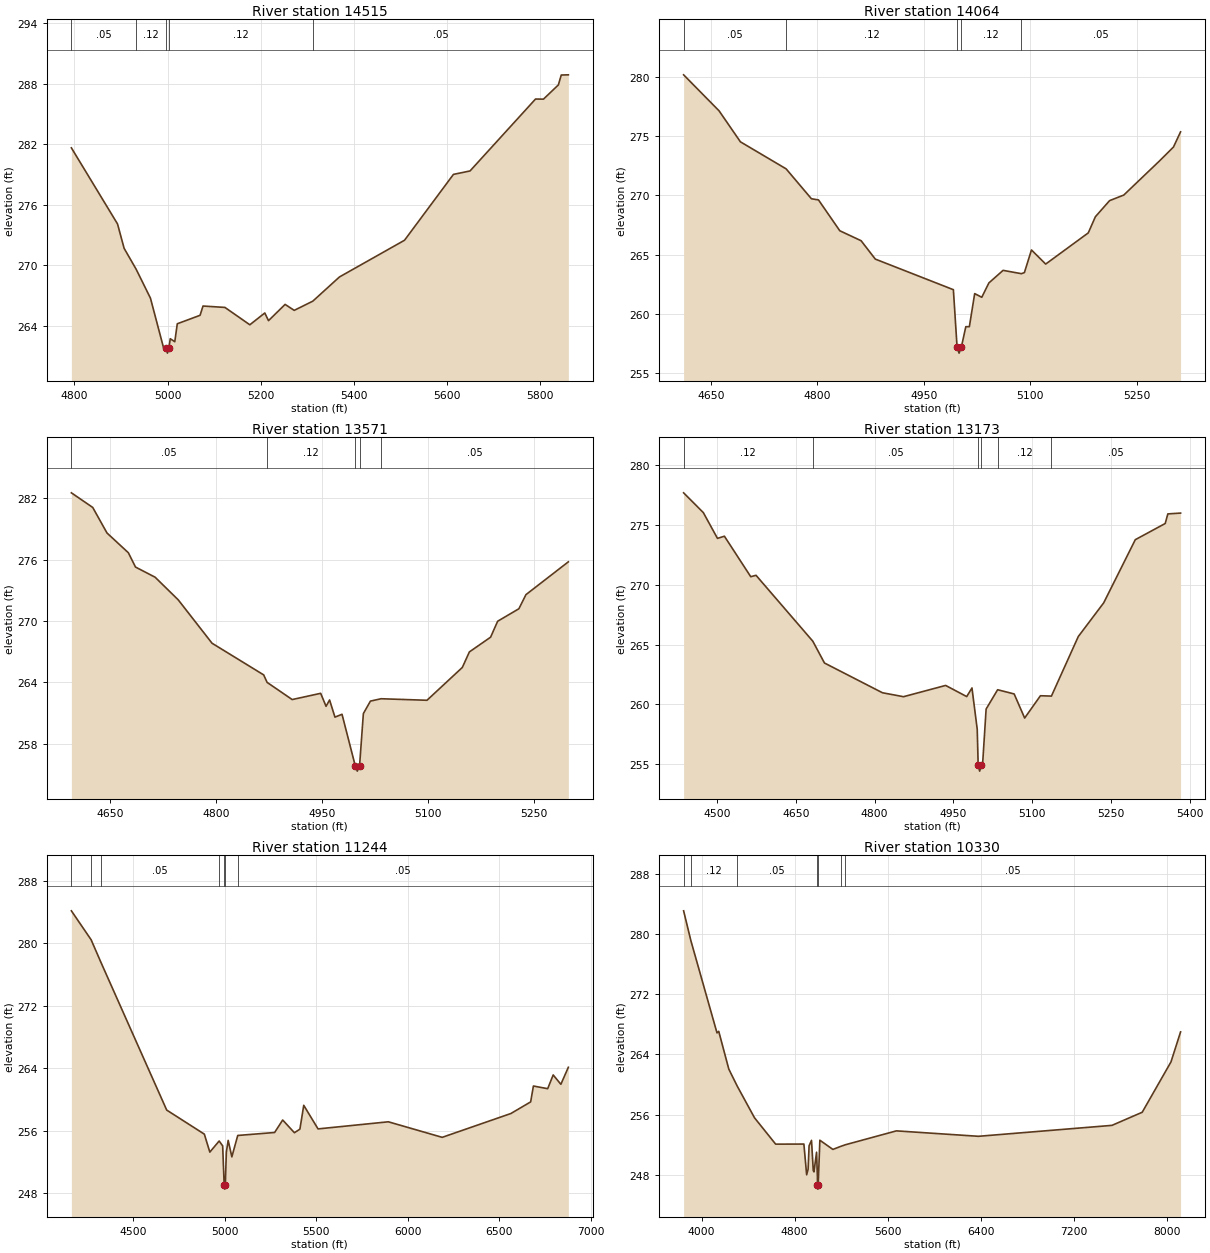
Type RM Length L Ch R = 1,14515,451,451,451
BEGIN DESCRIPTION:
UNT 179 IN CACR 14.0
END DESCRIPTION:
XS GIS Cut Line= 3
      3668499.62     10664860.17      3668349.61     10665010.19
      3667549.57     10665310.21
#Sta/Elev= 30
  4793.7  281.66  4892.7  274.12  4906.9  271.70  4932.9  269.61  4963.4  266.76
  4991.7  261.81  4997.0  261.81  4999.8  261.31  5003.0  261.81  5005.9  262.74
  5015.6  262.44  5021.0  264.22  5069.9  265.06  5076.2  265.98  5123.3  265.84
  5176.7  264.12  5208.8  265.29  5216.8  264.53  5252.4  266.14  5272.0  265.55
  5311.8  266.46  5369.0  268.86  5508.7  272.50  5613.7  279.03  5649.3  279.37
  5789.9  286.50  5806.9  286.49  5838.9  287.90  5845.1  288.88  5860.3  288.90
#Mann=5,-1,0
  4793.7    0.05       0  4932.9    0.12       0  4997.0    0.07       0
  5003.0    0.12       0  5311.8    0.05       0
Bank Sta=4997,5003
Exp/Cntr=0.3,0.1

Type RM Length L Ch R = 1,14064,493,493,493
BEGIN DESCRIPTION:
UNT 179 IN CACR 13.0
END DESCRIPTION:
XS GIS Cut Line= 3
      3668449.56     10664710.19      3668049.61     10664710.19
      3667749.56     10664710.19
#Sta/Elev= 30
  4611.8  280.17  4661.8  277.13  4691.8  274.52  4756.2  272.24  4791.8  269.72
  4801.8  269.62  4831.8  267.02  4861.8  266.18  4881.8  264.63  4991.8  262.05
  4997.0  257.20  4999.8  256.70  5003.0  257.20  5009.3  258.93  5014.3  258.93
  5021.8  261.72  5031.8  261.41  5041.8  262.62  5061.8  263.68  5087.6  263.40
  5091.8  263.49  5101.8  265.40  5121.8  264.21  5181.8  266.84  5191.8  268.20
  5211.8  269.56  5231.8  270.03  5281.8  272.89  5301.8  274.08  5311.8  275.36
#Mann=5,-1,0
  4611.8    0.05       0  4756.2    0.12       0  4997.0    0.07       0
  5003.0    0.12       0  5087.6    0.05       0
Bank Sta=4997,5003
Exp/Cntr=0.3,0.1

Type RM Length L Ch R = 1,13571,398,398,398
BEGIN DESCRIPTION:
UNT 179 IN CACR 12.0
END DESCRIPTION:
XS GIS Cut Line= 3
      3668449.60     10664360.19      3668049.61     10664310.19
      3667749.61     10664310.19
#Sta/Elev= 30
  4595.3  282.55  4625.5  281.12  4645.7  278.62  4675.9  276.69  4686.0  275.29
  4713.7  274.30  4746.5  272.08  4794.3  267.84  4867.4  264.74  4872.2  264.01
  4907.7  262.33  4948.0  262.94  4955.6  261.67  4960.6  262.29  4968.2  260.61
  4978.2  260.89  4997.0  255.83  4999.8  255.33  5003.0  255.83  5008.4  260.96
  5018.4  262.18  5033.5  262.41  5098.4  262.26  5148.4  265.47  5158.4  266.99
  5188.4  268.43  5198.4  269.99  5228.4  271.21  5238.4  272.59  5298.4  275.80
#Mann=5,-1,0
  4595.3    0.05       0  4872.2    0.12       0  4997.0    0.07       0
  5003.0    0.12       0  5033.5    0.05       0
Bank Sta=4997,5003
Exp/Cntr=0.3,0.1

Type RM Length L Ch R = 1,13173,1929,1929,1929
BEGIN DESCRIPTION:
UNT 179 IN CACR 11.0
END DESCRIPTION:
XS GIS Cut Line= 2
      3668627.09     10663921.30      3667683.62     10663976.80
#Sta/Elev= 30
  4436.8  277.66  4474.3  276.01  4501.2  273.86  4514.4  274.04  4564.5  270.66
  4574.5  270.78  4682.5  265.28  4704.7  263.46  4814.9  260.98  4855.0  260.65
  4935.1  261.59  4975.2  260.66  4985.2  261.38  4995.2  257.93  4997.0  254.94
  4999.8  254.44  5003.0  254.94  5005.3  254.94  5012.1  259.62  5034.0  261.23
  5065.4  260.88  5085.4  258.87  5115.4  260.73  5136.3  260.70  5187.4  265.67
  5235.7  268.48  5295.8  273.75  5352.7  275.10  5357.7  275.90  5381.9  275.97
#Mann=6,-1,0
  4436.8    0.12       0  4682.5    0.05       0  4997.0    0.03       0
  5003.0    0.05       0  5034.0    0.12       0  5136.3    0.05       0
Bank Sta=4997,5003
Exp/Cntr=0.3,0.1

Type RM Length L Ch R = 1,11244,914,914,914
BEGIN DESCRIPTION:
UNT 179 IN CACR 9.0
END DESCRIPTION:
XS GIS Cut Line= 4
      3669196.56     10662928.26      3668564.59     10662581.02
      3668328.48     10662567.13      3667349.40     10664025.34
#Sta/Elev= 30
  4162.5  284.13  4270.2  280.43  4323.0  277.58  4683.1  258.62  4888.6  255.54
  4918.6  253.24  4969.5  254.66  4988.7  254.04  4997.0  249.00  4999.8  248.50
  5003.0  249.00  5008.8  253.25  5018.8  254.74  5038.8  252.63  5071.0  255.37
  5272.4  255.75  5316.5  257.35  5380.5  255.72  5410.5  256.18  5431.5  259.23
  5509.5  256.21  5893.5  257.12  6187.6  255.13  6562.7  258.18  6670.7  259.67
  6685.7  261.70  6763.7  261.36  6793.7  263.12  6835.7  261.92  6876.5  264.10
#Mann=7,-1,0
  4162.5    0.05       0  4270.2    0.12       0  4323.0    0.05       0
  4969.5    0.12       0  4997.0    0.07       0  5003.0    0.12       0
  5071.0    0.05       0
Bank Sta=4997,5003
Exp/Cntr=0.3,0.1

Type RM Length L Ch R = 1,10330,1928,1928,1928
BEGIN DESCRIPTION:
UNT 179 IN CACR 8.0
END DESCRIPTION:
XS GIS Cut Line= 4
      3669632.09     10662617.12      3668607.78     10661913.99
      3667523.69     10662501.24      3667167.78     10664263.42
#Sta/Elev= 30
  3846.1  283.06  3908.4  279.11  4133.2  266.86  4148.1  267.07  4234.7  262.06
  4306.4  259.82  4456.0  255.59  4637.5  252.10  4880.3  252.11  4904.0  248.03
  4916.5  248.77  4925.0  251.88  4945.9  252.60  4960.8  248.62  4966.9  248.42
  4989.3  251.03  4996.7  247.70  4997.0  246.63  4999.8  246.13  5003.0  246.63
  5017.7  252.62  5129.6  251.40  5200.0  251.82  5237.6  252.02  5675.5  253.86
  6381.6  253.14  7529.2  254.59  7789.4  256.33  8036.8  263.01  8119.2  266.99
#Mann=7,-1,0
  3846.1    0.05       0  3908.4    0.12       0  4306.4    0.05       0
  4997.0    0.03       0  5003.0    0.05       0  5200.0    0.12       0
  5237.6    0.05       0
Bank Sta=4997,5003
Exp/Cntr=0.3,0.1

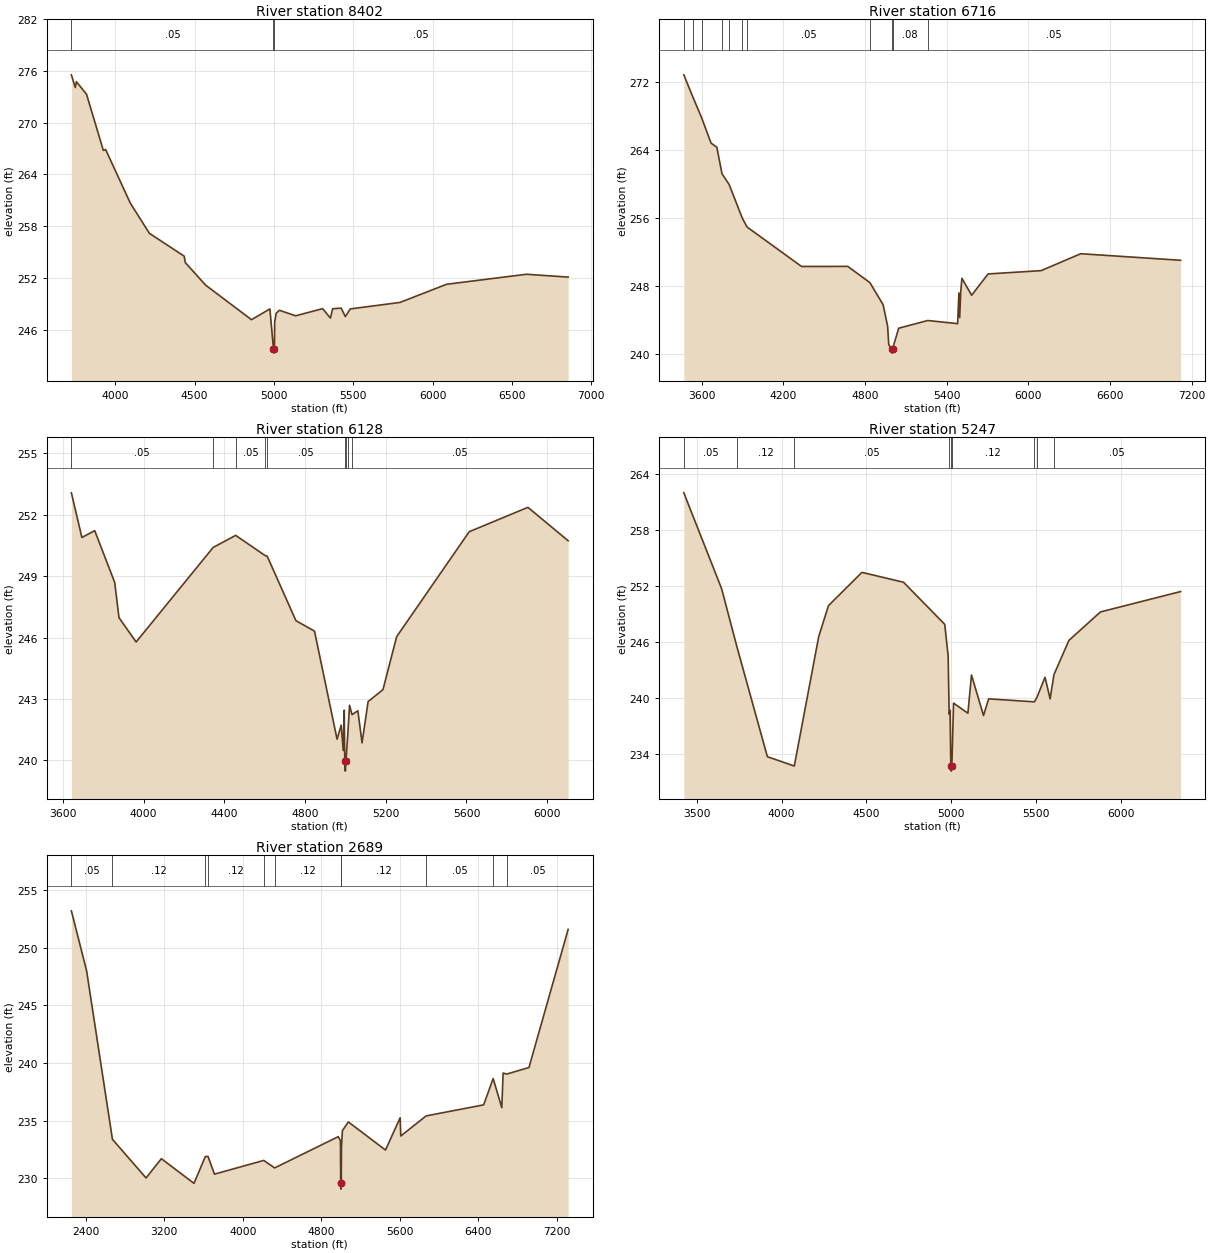
Type RM Length L Ch R = 1,8402,1686,1686,1686
BEGIN DESCRIPTION:
UNT 179 IN CACR 7.0
END DESCRIPTION:
XS GIS Cut Line= 4
      3670432.83     10661911.79      3669580.00     10661124.06
      3669380.35     10661106.70      3667704.97     10661679.63
#Sta/Elev= 30
  3722.8  275.56  3747.4  274.09  3754.4  274.76  3818.3  273.31  3924.4  266.79
  3938.5  266.90  4094.5  260.67  4214.7  257.17  4434.1  254.52  4440.9  253.78
  4568.5  251.17  4858.3  247.15  4974.5  248.40  4997.0  243.77  4999.8  243.27
  5003.0  243.77  5004.6  246.90  5014.6  247.91  5034.7  248.24  5136.9  247.60
  5306.9  248.43  5356.0  247.34  5370.3  248.42  5423.9  248.49  5450.0  247.51
  5481.3  248.40  5794.3  249.15  6089.0  251.26  6592.4  252.42  6854.8  252.09
#Mann=3,-1,0
  3722.8    0.05       0  4997.0    0.03       0  5003.0    0.05       0
Bank Sta=4997,5003
Exp/Cntr=0.3,0.1

Type RM Length L Ch R = 1,6716,588,588,588
BEGIN DESCRIPTION:
UNT 179 IN CACR 6.0
END DESCRIPTION:
XS GIS Cut Line= 4
      3671181.56     10661011.21      3670226.70     10660110.61
      3669890.33     10660023.80      3668132.53     10660956.96
#Sta/Elev= 30
  3469.3  272.90  3540.1  270.12  3600.6  267.83  3669.4  264.86  3711.9  264.38
  3749.6  261.27  3802.5  259.98  3898.7  256.04  3933.7  254.99  4334.5  250.34
  4674.0  250.35  4836.1  248.45  4933.8  245.84  4966.8  243.31  4975.1  241.14
  4997.0  240.64  4999.8  240.14  5003.0  240.64  5048.1  243.07  5261.3  243.98
  5481.1  243.61  5490.7  247.22  5496.4  244.33  5503.7  247.30  5512.7  248.95
  5584.3  246.95  5704.9  249.46  6095.0  249.85  6385.8  251.84  7119.4  251.07
#Mann=11,-1,0
  3469.3     0.1       0  3540.1    0.08       0  3600.6    0.05       0
  3749.6    0.08       0  3802.5    0.05       0  3898.7    0.08       0
  3933.7    0.05       0  4836.1    0.08       0  4997.0    0.07       0
  5003.0    0.08       0  5261.3    0.05       0
Bank Sta=4997,5003
Exp/Cntr=0.3,0.1

Type RM Length L Ch R = 1,6128,881,881,881
BEGIN DESCRIPTION:
UNT 179 IN CACR 5.0
END DESCRIPTION:
XS GIS Cut Line= 4
      3671073.05     10660490.38      3670213.68     10659639.69
      3669970.63     10659578.93      3669067.89     10660012.93
#Sta/Elev= 30
  3642.4  253.07  3694.5  250.89  3758.1  251.22  3857.1  248.69  3878.3  246.97
  3963.2  245.78  4344.8  250.40  4456.5  250.99  4601.6  250.01  4612.9  249.97
  4755.2  246.82  4847.1  246.31  4958.9  241.03  4979.5  241.72  4989.3  240.48
  4994.4  242.45  4997.0  239.97  4999.8  239.47  5003.0  239.97  5012.4  241.32
  5020.7  242.69  5032.9  242.23  5062.0  242.42  5082.6  240.85  5112.7  242.87
  5186.2  243.45  5254.1  246.04  5613.7  251.17  5904.5  252.36  6103.8  250.73
#Mann=9,-1,0
  3642.4    0.05       0  4344.8    0.08       0  4456.5    0.05       0
  4601.6    0.08       0  4612.9    0.05       0  4997.0    0.03       0
  5003.0    0.05       0  5012.4    0.12       0  5032.9    0.05       0
Bank Sta=4997,5003
Exp/Cntr=0.3,0.1

Type RM Length L Ch R = 1,5247,2558,2558,2558
BEGIN DESCRIPTION:
UNT 179 IN CACR 4.0
END DESCRIPTION:
XS GIS Cut Line= 4
      3671541.81     10660247.33      3670795.28     10659084.13
      3670491.46     10658979.97      3669276.20     10659118.85
#Sta/Elev= 30
  3424.0  262.03  3646.6  251.74  3736.9  245.50  3916.2  233.70  4074.9  232.70
  4218.8  246.60  4276.3  249.92  4473.2  253.49  4718.3  252.43  4961.2  247.91
  4981.3  244.49  4987.2  238.26  4989.0  238.40  4992.5  238.68  4997.0  232.65
  4999.8  232.15  5003.0  232.65  5013.0  239.45  5097.6  238.37  5118.7  242.47
  5189.6  238.12  5219.8  239.91  5489.2  239.59  5504.3  240.07  5551.9  242.23
  5582.1  239.91  5604.3  242.50  5692.8  246.19  5878.5  249.24  6350.5  251.43
#Mann=9,-1,0
  3424.0    0.05       0  3736.9    0.12       0  4074.9    0.05       0
  4989.0    0.12       0  4997.0    0.07       0  5003.0    0.12       0
  5489.2    0.05       0  5504.3    0.08       0  5604.3    0.05       0
Bank Sta=4997,5003
Exp/Cntr=0.3,0.1

Type RM Length L Ch R = 1,2689,0,0,0
BEGIN DESCRIPTION:
UNT 179 IN CACR 1.0
END DESCRIPTION:
XS GIS Cut Line= 4
      3671633.13     10660227.89      3671145.98     10657628.61
      3670739.73     10657610.38      3669217.68     10658921.66
#Sta/Elev= 30
  2253.8  253.20  2408.9  248.00  2672.1  233.38  3014.5  230.03  3170.4  231.70
  3502.9  229.56  3617.8  231.88  3645.2  231.90  3711.5  230.36  4213.5  231.55
  4324.5  230.90  4972.2  233.61  4994.8  233.26  4997.0  229.56  4999.8  229.06
  5003.0  229.56  5004.8  232.72  5014.8  234.13  5074.9  234.89  5453.6  232.45
  5602.8  235.25  5609.4  233.67  5867.1  235.41  6453.5  236.37  6550.4  238.65
  6638.3  236.12  6651.7  239.13  6688.3  239.04  6915.0  239.61  7314.0  251.59
#Mann=11,-1,0
  2253.8    0.05       0  2672.1    0.12       0  3617.8    0.07       0
  3645.2    0.12       0  4213.5    0.07       0  4324.5    0.12       0
  4997.0    0.07       0  5003.0    0.12       0  5867.1    0.05       0
  6550.4    0.08       0  6688.3    0.05       0
Bank Sta=4997,5003
Exp/Cntr=0.3,0.1

Chan Stop Cuts=-1