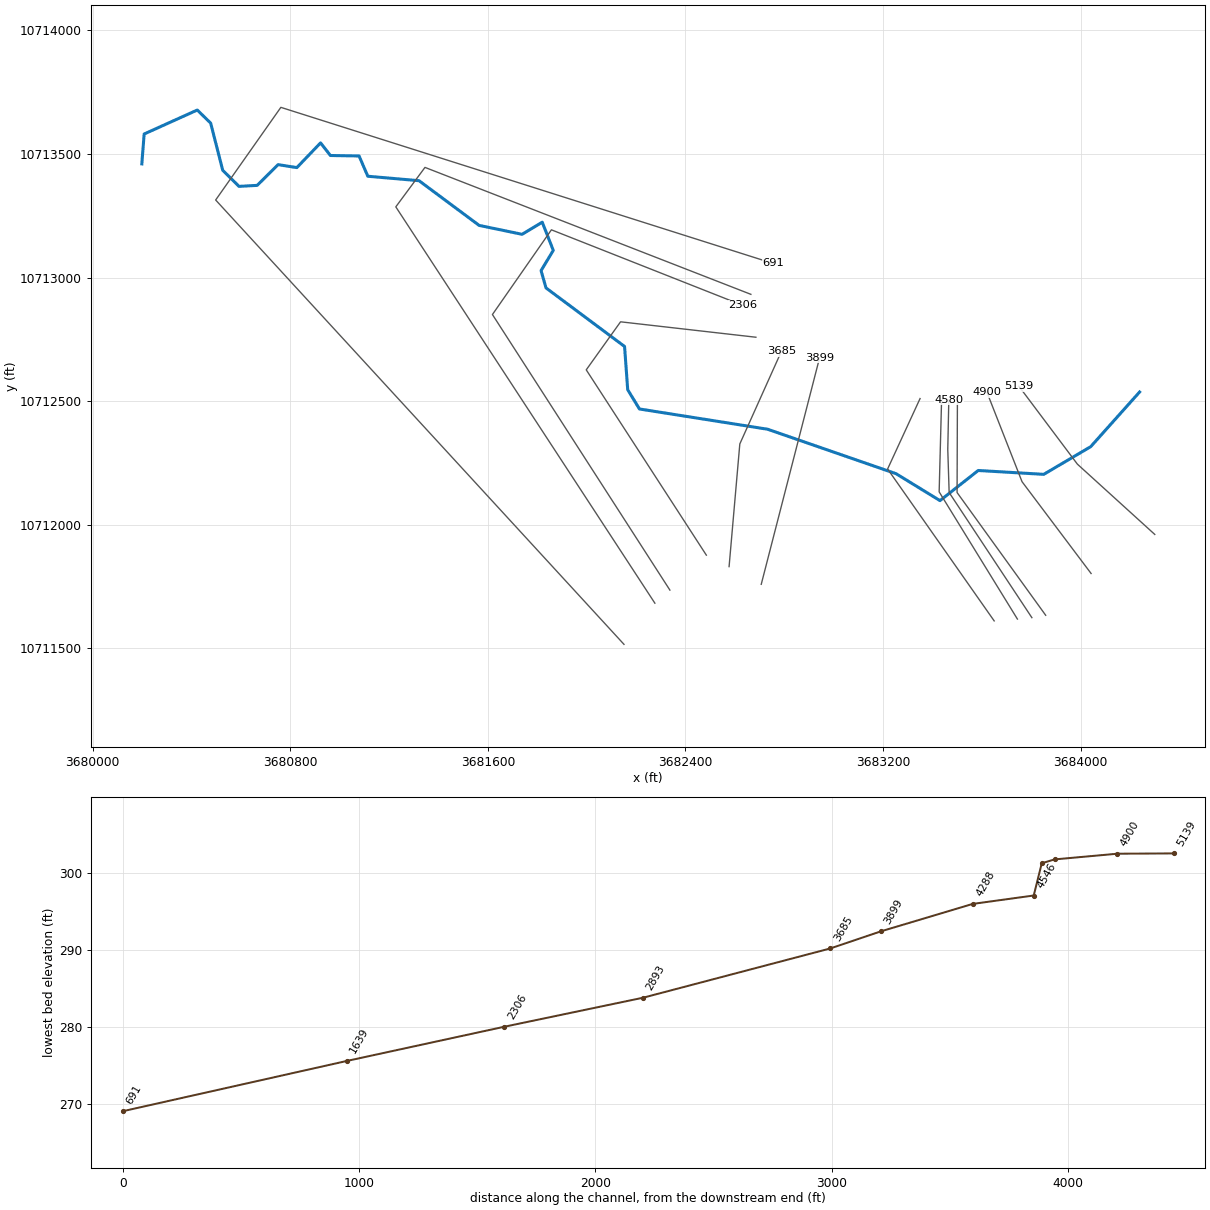
--- UNT 180 IN CACR.prj (project) ---

Proj Title=UNT 180 IN CACR Base Level Engineering
Current Plan=p01
Default Exp/Contr=0.3,0.1
English Units
Geom File=g01
Flow File=f01
Plan File=p01
BEGIN DESCRIPTION:
UNT 180 IN CACR
END DESCRIPTION:

--- UNT 180 IN CACR.p01 (plan) ---

Plan Title=Multiple Run
Short Identifier=Multiple
Geom File=g01
Flow File=f01
Subcritical Flow
K Sum by GR= 0
Std Step Tol= 0.01
Critical Tol= 0.01
Num of Std Step Trials= 20
Max Error Tol= 0.3
Flow Tol Ratio= 0.001
Split Flow NTrial= 30
Split Flow Tol= 0.02
Split Flow Ratio= 0.02
Log Output Level= 0
Friction Slope Method= 1
Unsteady Friction Slope Method= 2
Unsteady Bridges Friction Slope Method= 1
Parabolic Critical Depth
Global Vel Dist=  1 , 1 , 1
Global Log Level= 0
CheckData=True
Encroach Param= -1, 0, 0, 0
BEGIN DESCRIPTION:
Multiple Run
END DESCRIPTION:

--- UNT 180 IN CACR.f01 (steady flow) ---

Flow Title=Multiple
Number of Profiles=7
Profile Names=10-year,25-year,50-year,1pct_min,100-year,1pct_plu,500-year
River Rch & RM= UNT 180 IN CACR,Reach-1,5139
     198     250     290     247     334     452     446
Boundary for River Rch & Prof#=UNT 180 IN CACR,Reach-1,1
Up Type=0
Dn Type=3
Dn Slope=0.005
Boundary for River Rch & Prof#=UNT 180 IN CACR,Reach-1,2
Up Type=0
Dn Type=3
Dn Slope=0.005
Boundary for River Rch & Prof#=UNT 180 IN CACR,Reach-1,3
Up Type=0
Dn Type=3
Dn Slope=0.005
Boundary for River Rch & Prof#=UNT 180 IN CACR,Reach-1,4
Up Type=0
Dn Type=3
Dn Slope=0.005
Boundary for River Rch & Prof#=UNT 180 IN CACR,Reach-1,5
Up Type=0
Dn Type=3
Dn Slope=0.005
Boundary for River Rch & Prof#=UNT 180 IN CACR,Reach-1,6
Up Type=0
Dn Type=3
Dn Slope=0.005
Boundary for River Rch & Prof#=UNT 180 IN CACR,Reach-1,7
Up Type=0
Dn Type=3
Dn Slope=0.005

--- UNT 180 IN CACR.g01 (geometry) ---

Geom Title=Existing Conditions

River Reach=UNT 180 IN CACR,Reach-1
Reach XY= 30
      3684238.20     10712536.73      3684040.29     10712315.38
      3683850.18     10712203.40      3683585.00     10712219.00
      3683430.25     10712097.00      3683252.50     10712206.00
      3682732.50     10712386.00      3682213.75     10712468.00
      3682166.25     10712546.00      3682153.50     10712721.00
      3681835.50     10712958.00      3681815.50     10713028.00
      3681865.00     10713110.00      3681820.25     10713224.00
      3681738.75     10713175.00      3681565.00     10713211.00
      3681321.50     10713392.00      3681114.25     10713410.00
      3681079.00     10713492.00      3680963.00     10713494.00
      3680923.00     10713545.00      3680827.00     10713445.00
      3680751.00     10713457.00      3680666.50     10713373.00
      3680593.00     10713369.00      3680527.00     10713434.00
      3680478.25     10713625.00      3680424.00     10713678.00
      3680209.00     10713581.00      3680199.50     10713460.00

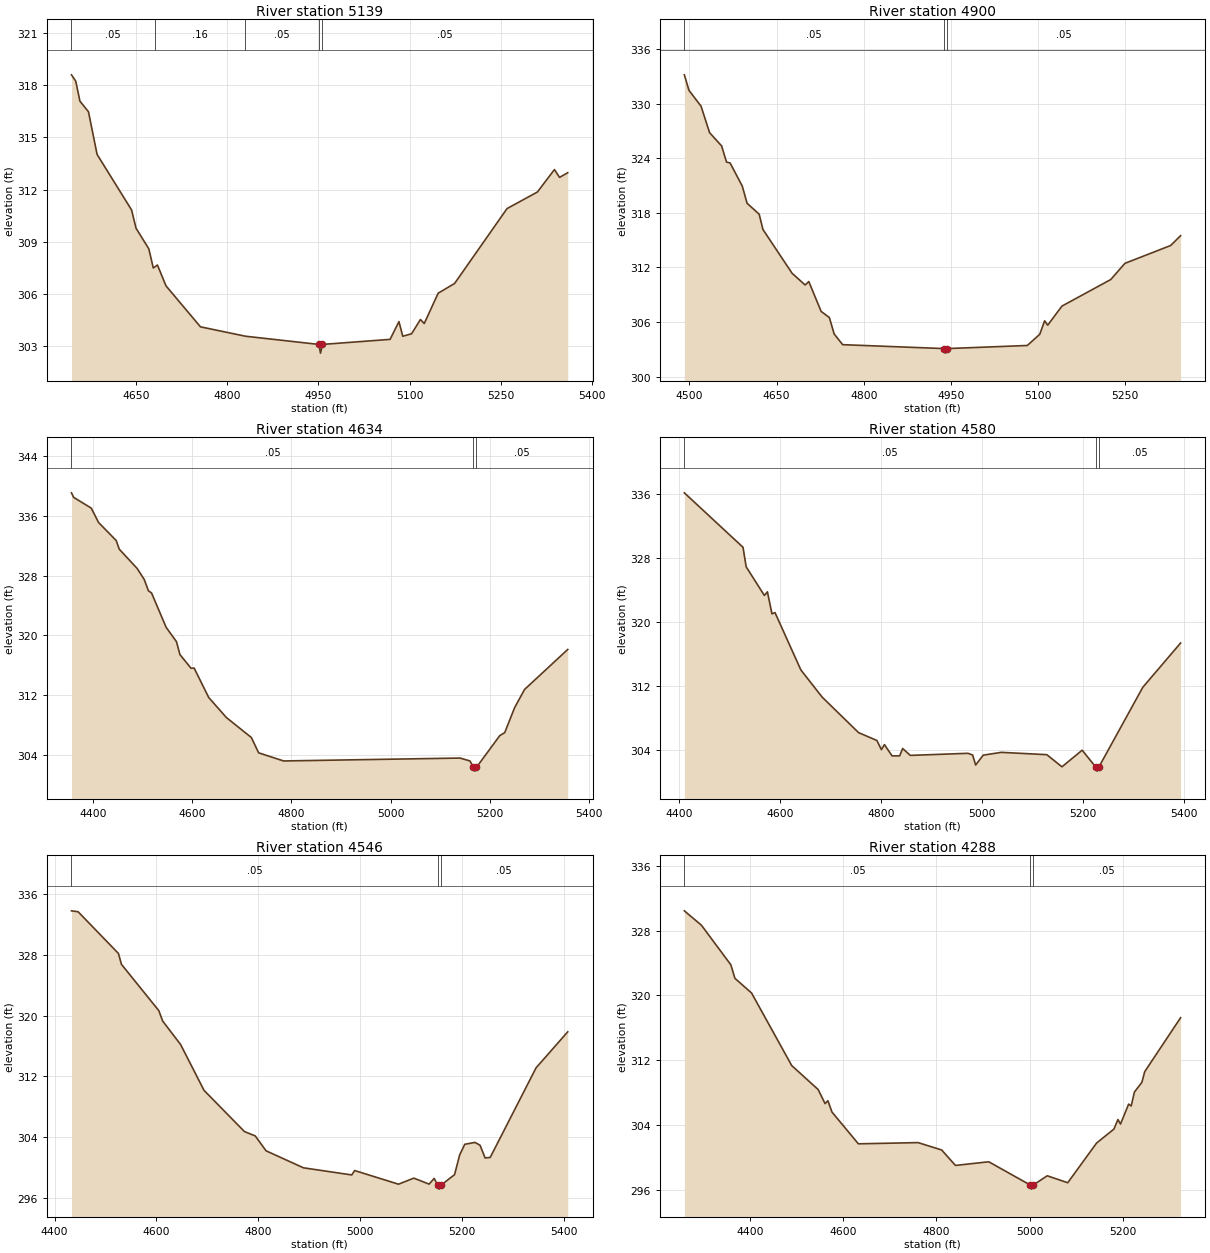
Type RM Length L Ch R = 1,5139,239,239,239
BEGIN DESCRIPTION:
UNT 180 IN CACR 6.0
END DESCRIPTION:
XS GIS Cut Line= 3
      3684299.61     10711960.19      3683986.48     10712244.60
      3683749.61     10712560.18
#Sta/Elev= 30
  4543.1  318.59  4550.2  318.22  4557.0  317.08  4571.1  316.47  4585.3  314.02
  4642.1  310.83  4649.5  309.78  4670.5  308.60  4677.9  307.50  4680.4  307.56
  4684.7  307.67  4698.9  306.47  4755.6  304.12  4829.8  303.58  4950.6  303.11
  4953.4  302.61  4956.6  303.11  5068.0  303.40  5082.6  304.42  5088.9  303.58
  5103.4  303.72  5118.0  304.54  5124.3  304.31  5147.2  306.05  5174.3  306.61
  5260.7  310.91  5310.7  311.86  5338.8  313.15  5347.2  312.70  5360.7  312.97
#Mann=5,-1,0
  4543.1    0.05       0  4680.4    0.16       0  4829.8    0.05       0
  4950.6   0.035       0  4956.6    0.05       0
Bank Sta=4950.6,4956.6
Exp/Cntr=0.3,0.1

Type RM Length L Ch R = 1,4900,266,266,266
BEGIN DESCRIPTION:
Mapping XS 33a7b879
END DESCRIPTION:
XS GIS Cut Line= 3
      3684041.90     10711802.07      3683762.36     10712173.64
      3683620.23     10712535.87
#Sta/Elev= 30
  4491.2  333.16  4499.2  331.45  4520.0  329.71  4534.6  326.81  4555.4  325.34
  4563.8  323.57  4570.0  323.47  4590.9  320.93  4599.2  319.04  4620.0  317.84
  4626.5  316.16  4676.6  311.35  4699.1  310.06  4705.4  310.44  4726.6  307.16
  4740.8  306.48  4749.1  304.67  4763.7  303.50  4937.7  303.07  4940.5  302.57
  4943.7  303.07  5081.4  303.41  5102.9  304.64  5111.3  306.12  5116.6  305.64
  5141.1  307.74  5225.1  310.66  5249.5  312.44  5328.2  314.40  5345.3  315.48
#Mann=3,-1,0
  4491.2    0.05       0  4937.7   0.033       0  4943.7    0.05       0
Bank Sta=4937.7,4943.7
Exp/Cntr=0.3,0.1

Type RM Length L Ch R = 1,4634,54,54,54
BEGIN DESCRIPTION:
UNT 180 IN CACR 5.0
END DESCRIPTION:
XS GIS Cut Line= 3
      3683858.05     10711632.98      3683499.43     10712129.75
      3683500.82     10712517.16
#Sta/Elev= 30
  4356.7  339.07  4361.0  338.47  4396.6  337.02  4411.3  335.10  4446.9  332.68
  4453.0  331.53  4488.9  328.96  4503.3  327.48  4511.9  325.95  4518.0  325.68
  4547.5  321.07  4568.3  319.15  4575.3  317.42  4597.8  315.59  4603.9  315.62
  4633.3  311.68  4668.9  309.00  4719.2  306.33  4733.9  304.28  4784.2  303.19
  5139.8  303.58  5159.8  303.19  5166.8  302.33  5169.6  301.83  5172.8  302.33
  5219.8  306.58  5229.8  306.98  5249.8  310.33  5269.8  312.76  5356.8  318.11
#Mann=3,-1,0
  4356.7    0.05       0  5166.8   0.033       0  5172.8    0.05       0
Bank Sta=5166.8,5172.8
Exp/Cntr=0.3,0.1

Type RM Length L Ch R = 1,4580,34,34,34
BEGIN DESCRIPTION:
Mapping XS c720a14c
END DESCRIPTION:
XS GIS Cut Line= 4
      3683802.19     10711623.27      3683467.34     10712129.75
      3683461.76     10712304.17      3683465.94     10712505.05
#Sta/Elev= 30
  4411.0  336.17  4527.2  329.35  4533.4  326.91  4569.5  323.32  4575.5  323.78
  4584.5  321.02  4590.5  321.18  4641.7  314.00  4683.8  310.60  4756.0  306.15
  4792.2  305.17  4801.2  304.02  4807.2  304.65  4822.3  303.24  4837.3  303.24
  4843.3  304.16  4858.4  303.30  4972.7  303.56  4981.8  303.35  4987.8  302.10
  5002.8  303.33  5038.6  303.68  5128.7  303.39  5158.7  301.87  5198.7  303.95
  5225.7  301.83  5228.4  301.33  5231.7  301.83  5318.7  311.82  5393.6  317.37
#Mann=3,-1,0
  4411.0    0.05       0  5225.7    0.03       0  5231.7    0.05       0
Bank Sta=5225.7,5231.7
Exp/Cntr=0.3,0.1

Type RM Length L Ch R = 1,4546,258,258,258
BEGIN DESCRIPTION:
Mapping XS 2cbaca5a
END DESCRIPTION:
XS GIS Cut Line= 3
      3683743.60     10711617.68      3683426.87     10712132.54
      3683436.64     10712502.33
#Sta/Elev= 30
  4433.2  333.83  4446.2  333.71  4525.4  328.21  4531.3  326.78  4604.7  320.67
  4612.3  319.30  4647.5  316.20  4693.5  310.16  4772.8  304.73  4794.1  304.15
  4815.3  302.19  4888.7  299.95  4983.4  299.01  4989.3  299.59  5075.3  297.79
  5105.4  298.59  5135.4  297.80  5145.4  298.55  5152.4  297.64  5155.1  297.14
  5158.4  297.64  5185.4  299.05  5195.4  301.65  5205.4  303.05  5225.4  303.30
  5235.4  302.93  5245.4  301.25  5255.4  301.32  5345.4  313.13  5407.6  317.88
#Mann=3,-1,0
  4433.2    0.05       0  5152.4    0.03       0  5158.4    0.05       0
Bank Sta=5152.4,5158.4
Exp/Cntr=0.3,0.1

Type RM Length L Ch R = 1,4288,389,389,389
BEGIN DESCRIPTION:
UNT 180 IN CACR 4.0
END DESCRIPTION:
XS GIS Cut Line= 3
      3683649.62     10711610.17      3683218.25     10712225.07
      3683349.59     10712510.15
#Sta/Elev= 30
  4259.2  330.45  4295.9  328.67  4359.0  323.78  4367.7  322.11  4403.5  320.29
  4489.7  311.32  4546.4  308.36  4561.2  306.62  4567.3  306.98  4576.0  305.58
  4632.7  301.65  4760.8  301.80  4811.4  300.89  4841.0  298.98  4912.5  299.43
  5001.8  296.55  5004.5  296.05  5007.8  296.55  5038.0  297.70  5082.0  296.84
  5143.8  301.74  5181.1  303.47  5189.7  304.65  5195.2  304.09  5212.7  306.56
  5218.2  306.33  5225.1  308.05  5241.1  309.25  5247.2  310.57  5324.2  317.24
#Mann=3,-1,0
  4259.2    0.05       0  5001.8    0.03       0  5007.8    0.05       0
Bank Sta=5001.8,5007.8
Exp/Cntr=0.3,0.1

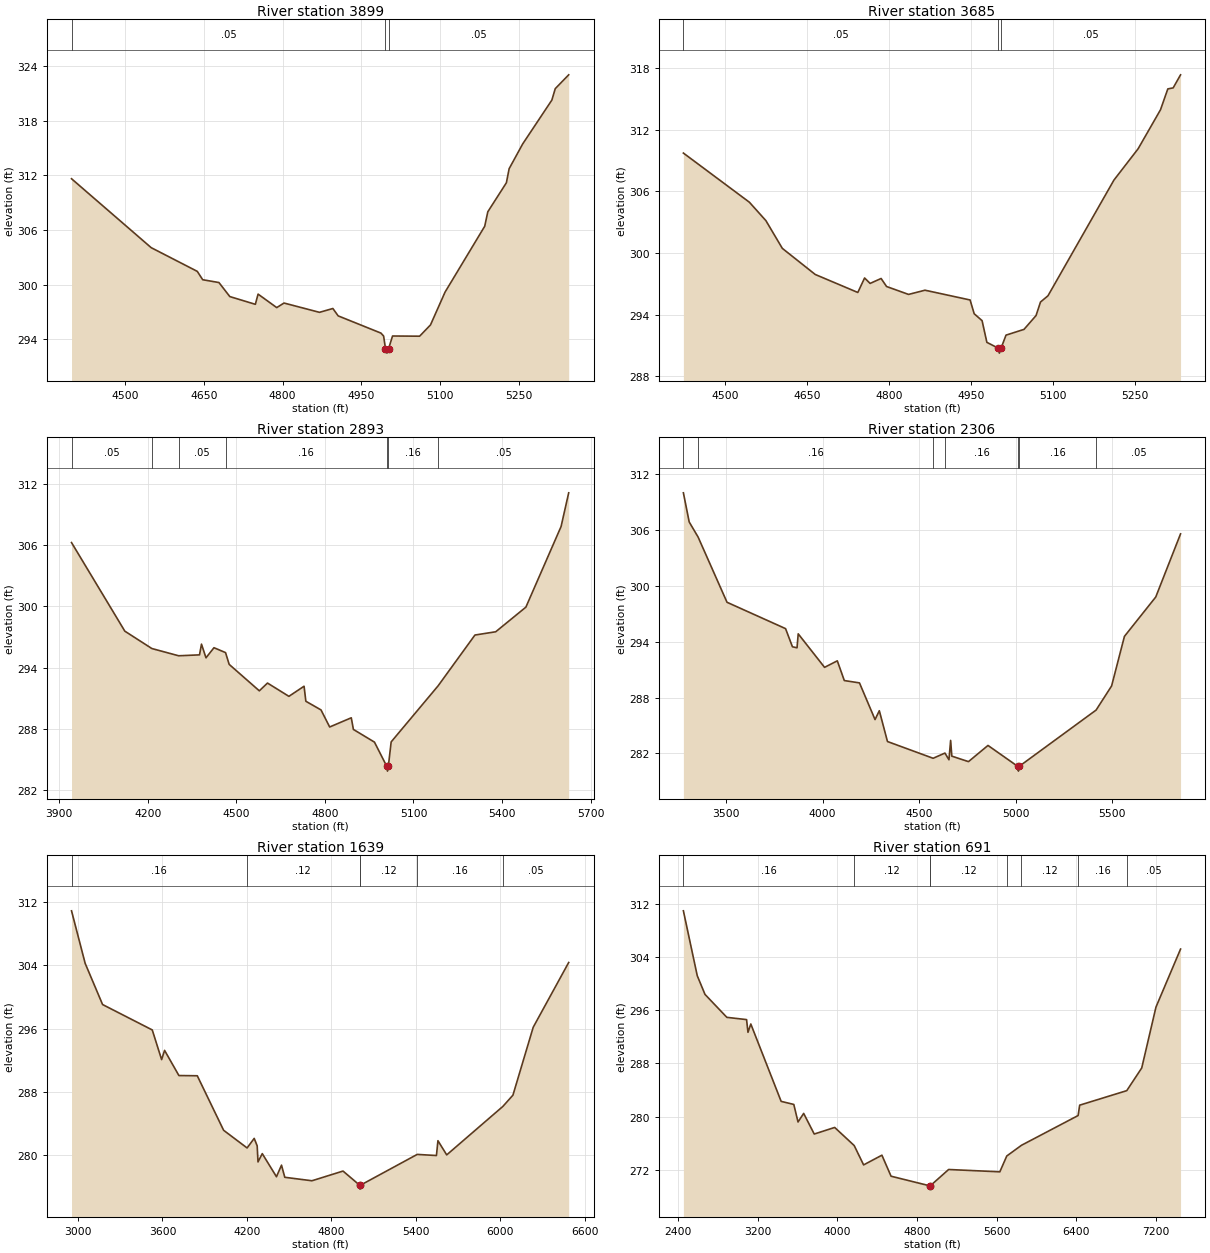
Type RM Length L Ch R = 1,3899,214,214,214
BEGIN DESCRIPTION:
Mapping XS 945f04ae
END DESCRIPTION:
XS GIS Cut Line= 2
      3682706.75     10711758.33      3682942.87     10712675.01
#Sta/Elev= 30
  4398.2  311.63  4549.9  304.06  4637.6  301.46  4648.0  300.54  4678.9  300.23
  4699.6  298.69  4748.2  297.84  4753.4  298.96  4788.9  297.48  4802.8  297.98
  4870.3  296.96  4895.8  297.38  4905.9  296.57  4987.3  294.68  4992.4  294.36
  4996.0  292.98  4998.8  292.48  5002.0  292.98  5009.4  294.36  5061.0  294.34
  5081.7  295.58  5109.4  299.18  5184.9  306.41  5190.8  308.00  5226.2  311.19
  5231.4  312.73  5257.2  315.45  5312.8  320.27  5319.2  321.52  5344.8  323.04
#Mann=3,-1,0
  4398.2    0.05       0  4996.0    0.03       0  5002.0    0.05       0
Bank Sta=4996,5002
Exp/Cntr=0.3,0.1

Type RM Length L Ch R = 1,3685,792,792,792
BEGIN DESCRIPTION:
Mapping XS 9660ec11
END DESCRIPTION:
XS GIS Cut Line= 3
      3682576.59     10711829.90      3682620.00     10712326.41
      3682788.41     10712701.43
#Sta/Elev= 30
  4423.8  309.72  4544.5  304.94  4574.7  303.15  4604.8  300.45  4665.0  297.91
  4742.9  296.16  4755.3  297.57  4765.4  297.04  4785.5  297.52  4795.5  296.74
  4835.7  295.97  4865.8  296.38  4948.3  295.43  4955.8  294.09  4970.2  293.42
  4979.0  291.31  4999.1  290.76  5001.9  290.26  5005.1  290.76  5014.0  292.01
  5046.9  292.57  5068.9  293.91  5077.1  295.23  5090.8  295.84  5211.4  307.09
  5255.7  310.14  5296.6  313.93  5310.0  315.96  5319.8  316.06  5333.3  317.33
#Mann=3,-1,0
  4423.8    0.05       0  4999.1    0.03       0  5005.1    0.05       0
Bank Sta=4999.1,5005.1
Exp/Cntr=0.3,0.1

Type RM Length L Ch R = 1,2893,587,587,587
BEGIN DESCRIPTION:
UNT 180 IN CACR 3.0
END DESCRIPTION:
XS GIS Cut Line= 4
      3682484.54     10711876.33      3681998.41     10712626.36
      3682137.30     10712820.80      3682685.21     10712758.38
#Sta/Elev= 30
  3941.6  306.23  4122.2  297.56  4213.7  295.86  4304.5  295.15  4375.2  295.24
  4381.9  296.29  4397.1  294.95  4424.2  295.94  4463.4  295.46  4475.6  294.31
  4577.8  291.72  4605.5  292.48  4678.0  291.18  4729.4  292.17  4735.4  290.70
  4786.8  289.85  4816.1  288.18  4889.3  289.08  4896.5  287.94  4967.8  286.70
  5009.0  284.36  5011.8  283.86  5015.0  284.36  5024.4  286.72  5183.5  292.21
  5308.2  297.18  5378.6  297.50  5480.8  299.91  5600.0  307.80  5625.8  311.10
#Mann=7,-1,0
  3941.6    0.05       0  4213.7    0.16       0  4304.5    0.05       0
  4463.4    0.16       0  5009.0    0.07       0  5015.0    0.16       0
  5183.5    0.05       0
Bank Sta=5009,5015
Exp/Cntr=0.3,0.1

Type RM Length L Ch R = 1,2306,667,667,667
BEGIN DESCRIPTION:
Mapping XS 85e6cbc8
END DESCRIPTION:
XS GIS Cut Line= 4
      3682337.00     10711734.84      3681618.69     10712850.28
      3681857.41     10713193.17      3682632.16     10712887.17
#Sta/Elev= 30
  3278.2  309.99  3308.3  306.86  3354.7  305.23  3504.4  298.23  3807.9  295.40
  3843.6  293.45  3867.4  293.34  3873.5  294.84  4010.1  291.24  4076.2  291.94
  4112.5  289.82  4191.1  289.57  4271.8  285.63  4294.0  286.58  4336.3  283.27
  4572.9  281.47  4634.2  282.03  4655.0  281.31  4663.7  283.39  4669.8  281.70
  4756.2  281.11  4857.4  282.85  5012.4  280.59  5015.2  280.09  5018.4  280.59
  5417.9  286.65  5498.2  289.24  5564.8  294.57  5727.2  298.80  5855.7  305.58
#Mann=7,-1,0
  3278.2    0.05       0  3354.7    0.16       0  4572.9    0.12       0
  4634.2    0.16       0  5012.4    0.07       0  5018.4    0.16       0
  5417.9    0.05       0
Bank Sta=5012.4,5018.4
Exp/Cntr=0.3,0.1

Type RM Length L Ch R = 1,1639,948,948,948
BEGIN DESCRIPTION:
UNT 180 IN CACR 2.0
END DESCRIPTION:
XS GIS Cut Line= 4
      3682276.21     10711681.89      3681227.58     10713286.08
      3681345.64     10713445.80      3682664.88     10712931.99
#Sta/Elev= 30
  2954.2  310.92  3051.1  304.26  3174.8  299.04  3527.6  295.82  3594.1  292.06
  3615.1  293.23  3716.8  290.04  3847.4  290.01  4034.4  283.10  4201.1  280.86
  4251.6  282.07  4272.7  281.13  4278.6  279.09  4308.9  280.14  4409.7  277.21
  4445.5  278.68  4468.8  277.14  4661.7  276.70  4882.3  277.93  5000.4  276.14
  5003.1  275.64  5006.4  276.14  5409.2  280.04  5545.8  279.90  5556.5  281.78
  5618.8  279.98  6018.0  286.13  6089.1  287.55  6233.1  296.16  6485.1  304.37
#Mann=6,-1,0
  2954.2    0.16       0  4201.1    0.12       0  5000.4    0.07       0
  5006.4    0.12       0  5409.2    0.16       0  6018.0    0.05       0
Bank Sta=5000.4,5006.4
Exp/Cntr=0.3,0.1

Type RM Length L Ch R = 1,691,0,0,0
BEGIN DESCRIPTION:
UNT 180 IN CACR 1.0
END DESCRIPTION:
XS GIS Cut Line= 4
      3682151.20     10711515.24      3680498.41     10713313.86
      3680762.30     10713688.86      3682755.00     10713057.03
#Sta/Elev= 30
  2455.1  310.94  2594.3  301.19  2672.0  298.38  2891.5  294.93  3089.4  294.59
  3103.6  292.68  3132.0  293.93  3436.6  282.30  3563.6  281.84  3606.1  279.20
  3662.8  280.49  3768.9  277.39  3974.2  278.38  4170.1  275.66  4264.6  272.75
  4448.3  274.21  4540.2  271.05  4928.0  269.61  4930.8  269.11  4934.0  269.61
  5118.3  272.06  5632.3  271.71  5702.0  274.09  5849.7  275.70  6418.2  280.17
  6434.0  281.73  6906.5  283.91  7057.0  287.32  7199.9  296.47  7446.8  305.19
#Mann=8,-1,0
  2455.1    0.16       0  4170.1    0.12       0  4928.0    0.07       0
  4934.0    0.12       0  5702.0    0.16       0  5849.7    0.12       0
  6418.2    0.16       0  6906.5    0.05       0
Bank Sta=4928,4934
Exp/Cntr=0.3,0.1

Chan Stop Cuts=-1