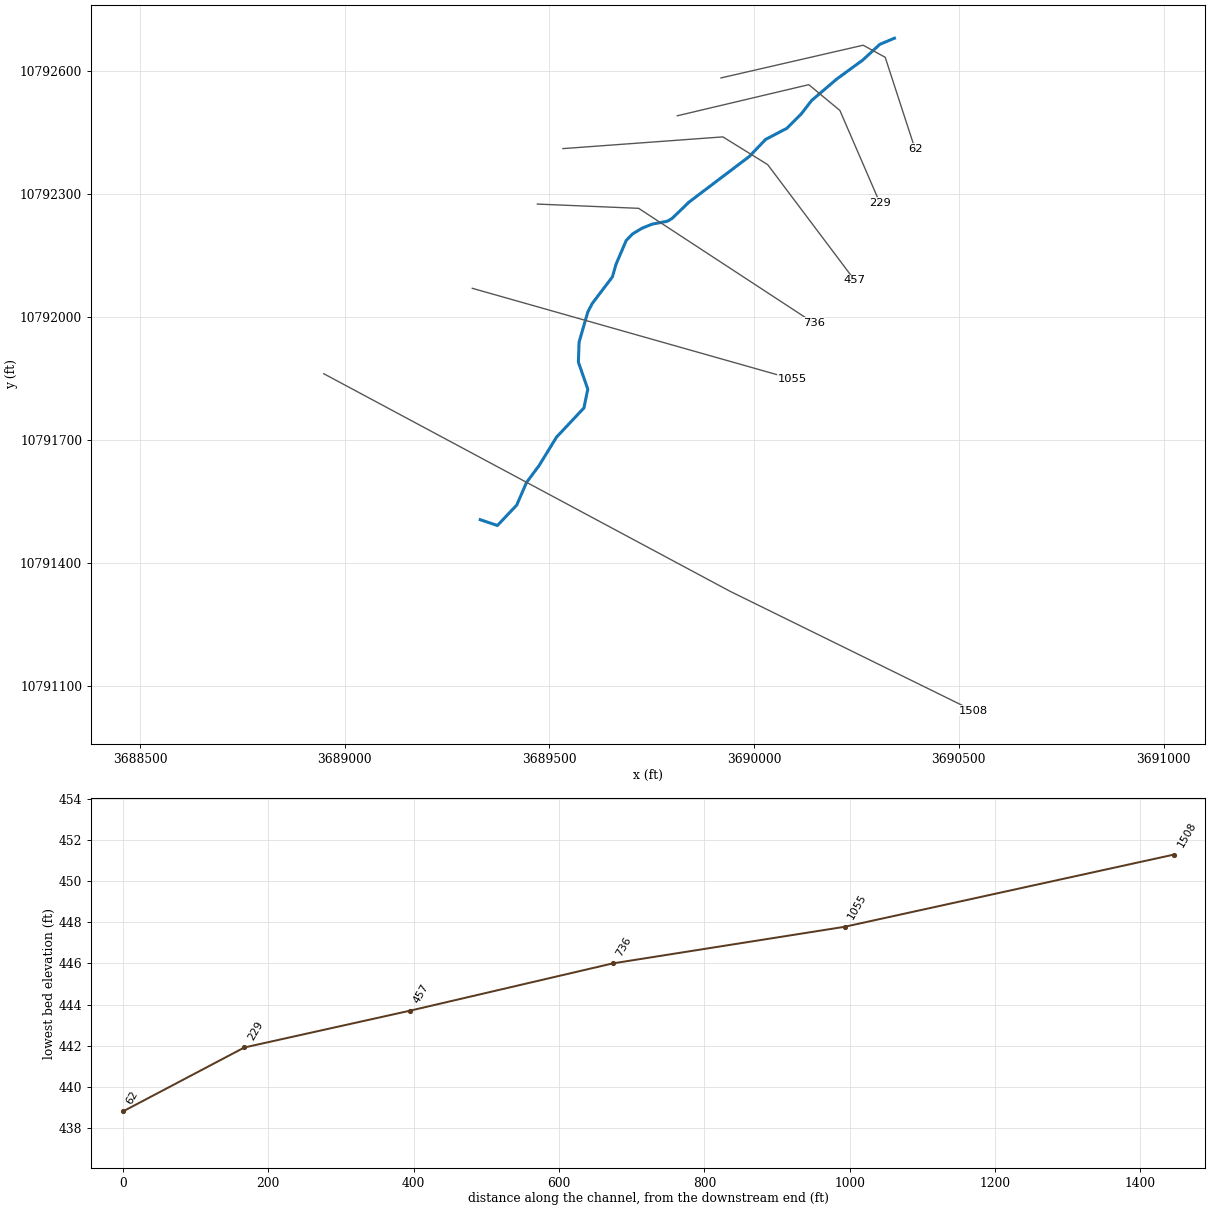
--- UNT 190 IN CACR.prj (project) ---

Proj Title=UNT 190 IN CACR Base Level Engineering
Current Plan=p01
Default Exp/Contr=0.3,0.1
English Units
Geom File=g01
Flow File=f01
Plan File=p01
Y Axis Title=Elevation
X Axis Title(PF)=Main Channel Distance
X Axis Title(XS)=Station
BEGIN DESCRIPTION:
UNT 190 IN CACR
END DESCRIPTION:
DSS Export Rating Curves= 0
DSS Export Rating Curve Sorted= 0
DSS Export Volume Flow Curves= 0
DXF OffsetX= 0
DXF OffsetY= 0
DXF ScaleX= 1
DXF ScaleY= 10

--- UNT 190 IN CACR.p01 (plan) ---

Plan Title=Multiple Run
Short Identifier=Multiple
Geom File=g01
Flow File=f01
Subcritical Flow
K Sum by GR= 0
Std Step Tol= 0.01
Critical Tol= 0.01
Num of Std Step Trials= 20
Max Error Tol= 0.3
Flow Tol Ratio= 0.001
Split Flow NTrial= 30
Split Flow Tol= 0.02
Split Flow Ratio= 0.02
Log Output Level= 0
Friction Slope Method= 1
Unsteady Friction Slope Method= 2
Unsteady Bridges Friction Slope Method= 1
Parabolic Critical Depth
Global Vel Dist=  1 , 1 , 1
Global Log Level= 0
CheckData=True
Encroach Param= -1, 0, 0, 0
BEGIN DESCRIPTION:
Multiple Run
END DESCRIPTION:

--- UNT 190 IN CACR.f01 (steady flow) ---

Flow Title=Multiple
Program Version=4.10
Number of Profiles= 7
Profile Names=10-year,25-year,50-year,1pct_min,100-year,1pct_plu,500-year
River Rch & RM=UNT 190 IN CACR,Reach-1         ,1508
     379     499     594     520     704     952     988
River Rch & RM=UNT 190 IN CACR,Reach-1         ,62
     959    1333    1648    1492    2018    2729    3035
Boundary for River Rch & Prof#=UNT 190 IN CACR,Reach-1         , 1
Up Type= 0
Dn Type= 3
Dn Slope=0.005
Boundary for River Rch & Prof#=UNT 190 IN CACR,Reach-1         , 2
Up Type= 0
Dn Type= 3
Dn Slope=0.005
Boundary for River Rch & Prof#=UNT 190 IN CACR,Reach-1         , 3
Up Type= 0
Dn Type= 3
Dn Slope=0.005
Boundary for River Rch & Prof#=UNT 190 IN CACR,Reach-1         , 4
Up Type= 0
Dn Type= 3
Dn Slope=0.005
Boundary for River Rch & Prof#=UNT 190 IN CACR,Reach-1         , 5
Up Type= 0
Dn Type= 3
Dn Slope=0.005
Boundary for River Rch & Prof#=UNT 190 IN CACR,Reach-1         , 6
Up Type= 0
Dn Type= 3
Dn Slope=0.005
Boundary for River Rch & Prof#=UNT 190 IN CACR,Reach-1         , 7
Up Type= 0
Dn Type= 3
Dn Slope=0.005
DSS Import GetInterval= 0
DSS Import GetPeak= 0
DSS Import FillOption= 0

--- UNT 190 IN CACR.g01 (geometry) ---

Geom Title=Existing Conditions
Program Version=4.10

River Reach=UNT 190 IN CACR ,Reach-1
Reach XY= 30
      3689330.97     10791505.28        3689373.       10791491.
      3689420.25       10791541.        3689444.       10791596.
       3689474.5       10791637.       3689517.5       10791707.
      3689584.25       10791778.      3689593.75       10791824.
      3689570.75       10791890.       3689572.5       10791939.
        3689594.       10792013.       3689604.5       10792033.
      3689653.75       10792098.      3689662.75       10792129.
       3689687.5       10792187.        3689703.       10792203.
      3689726.25       10792217.        3689751.       10792227.
        3689788.       10792234.      3689799.75       10792241.
      3689841.25       10792281.        3689988.       10792392.
      3690028.25       10792434.        3690080.       10792461.
        3690115.       10792496.       3690140.5       10792529.
       3690201.5       10792581.      3690265.75       10792628.
        3690307.       10792666.      3690342.75       10792681.

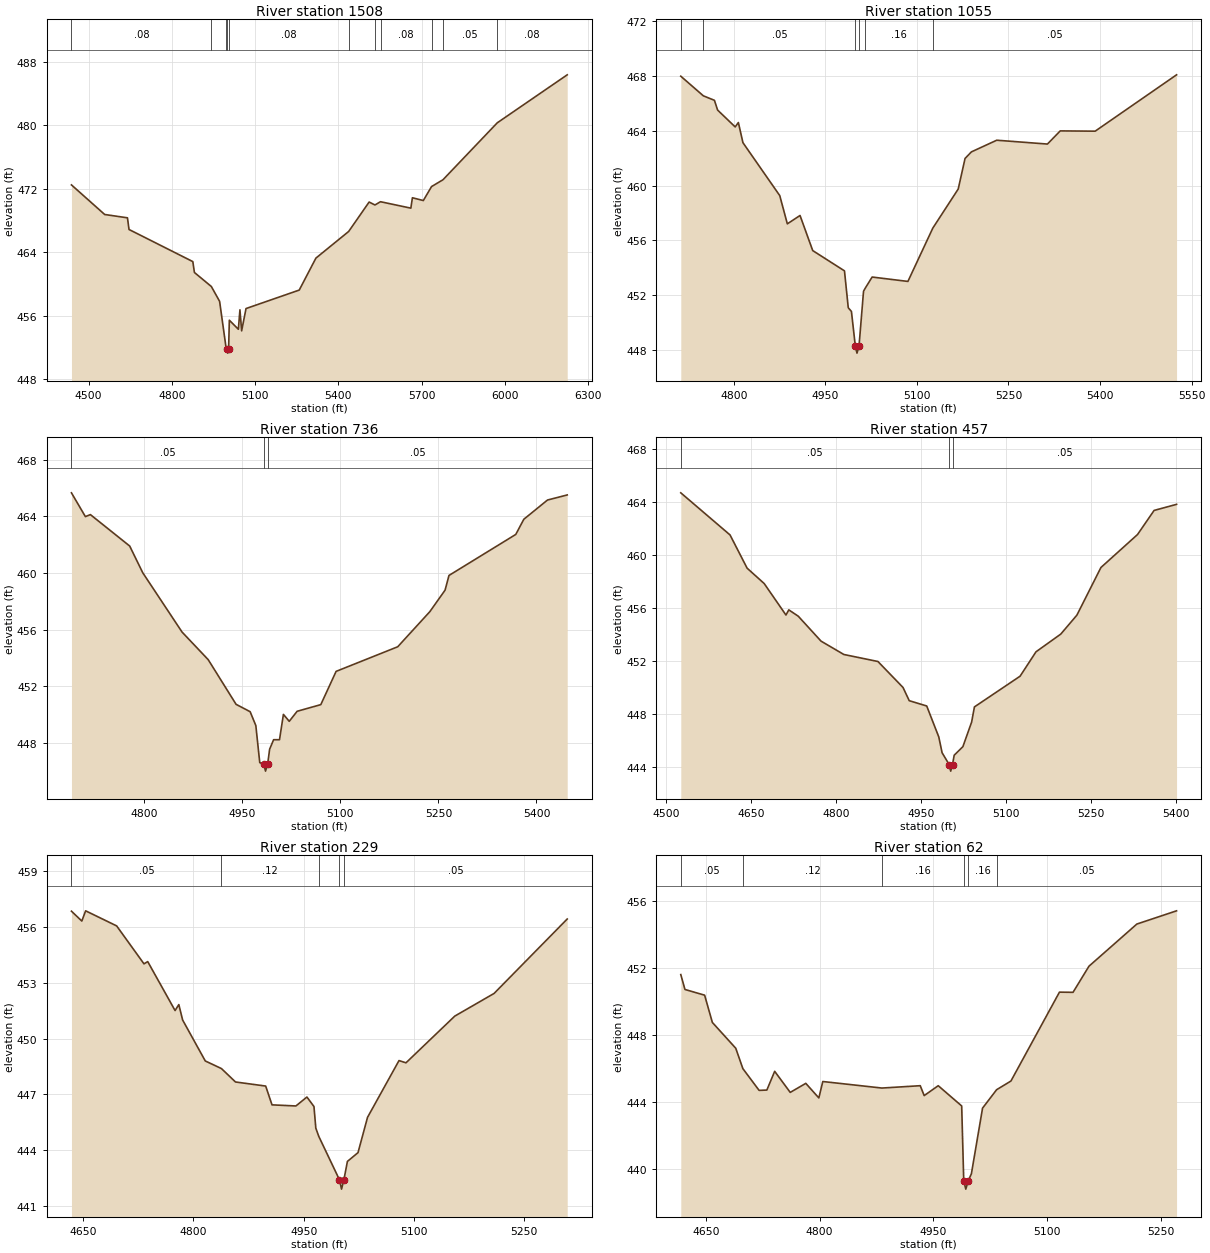
Type RM Length L Ch R = 1 ,1508    ,453,453,453
BEGIN DESCRIPTION:
Mapping XS bc94c362
END DESCRIPTION:
XS GIS Cut Line= 3
      3688948.88     10791861.68      3689941.05     10791330.44
      3690534.75      10791038.8
#Sta/Elev= 30
    4438   472.5  4557.8  468.77  4639.9  468.35  4645.5  466.88  4875.5  462.83
  4881.2  461.46  4942.2  459.69    4972  457.82  4995.7  451.87  4998.4  451.79
  5001.2  451.29  5004.4  451.79  5007.1  455.44  5039.6   454.3  5045.3  456.75
  5051.4   454.1  5067.2  456.91    5259  459.24  5319.1  463.27  5437.2  466.63
  5510.9  470.34  5531.9  469.97  5551.9  470.38  5661.3  469.57  5666.9  470.88
  5706.3  470.53  5735.9  472.29  5777.1  473.15  5972.8  480.33  6224.9  486.38
#Mann= 11 ,-1 , 0
    4438     .08       0  4942.2     .05       0  4995.7     .08       0
  4998.4     .07       0  5004.4     .08       0  5437.2     .05       0
  5531.9      .1       0  5551.9     .08       0  5735.9      .1       0
  5777.1     .05       0  5972.8     .08       0
Bank Sta=4998.4,5004.4
XS Rating Curve= 0 ,0
Exp/Cntr=0.3,0.1

Type RM Length L Ch R = 1 ,1055    ,319,319,319
BEGIN DESCRIPTION:
Mapping XS 269f6858
END DESCRIPTION:
XS GIS Cut Line= 2
      3689311.68     10792070.25      3690092.93     10791848.89
#Sta/Elev= 30
  4713.3  467.98  4750.2  466.55  4768.4  466.22  4773.6  465.51  4802.4  464.28
  4807.6   464.6  4815.1  463.13  4875.4  459.27  4887.8  457.21  4908.6  457.82
  4929.4  455.26  4981.4  453.78  4987.6  451.09  4992.8  450.82  4999.2  448.28
  5001.9  447.78  5005.2  448.28  5012.6  452.29  5015.3  452.51  5026.7  453.33
  5085.3  453.01  5126.1   456.9  5167.7  459.75  5178.9  461.98  5189.3  462.46
  5230.8  463.31  5313.8  463.03  5334.8  463.99    5392  463.97  5525.3  468.08
#Mann= 6 ,-1 , 0
  4713.3     .08       0  4750.2     .05       0  4999.2     .04       0
  5005.2     .05       0  5015.3     .16       0  5126.1     .05       0
Bank Sta=4999.2,5005.2
XS Rating Curve= 0 ,0
Exp/Cntr=0.3,0.1

Type RM Length L Ch R = 1 ,736     ,279,279,279
BEGIN DESCRIPTION:
Mapping XS 69abef44
END DESCRIPTION:
XS GIS Cut Line= 3
      3689470.61     10792275.97      3689717.96     10792265.55
      3690145.45     10791985.74
#Sta/Elev= 30
  4688.6  465.67  4709.9  463.99  4717.6  464.13  4777.7  461.91  4797.7  460.02
  4857.8  455.83  4897.8  453.88  4940.5  450.72    4962   450.2  4970.7  449.22
  4976.7   446.6  4982.8   446.5  4985.5     446  4988.8   446.5  4991.8  447.55
  4997.9  448.22  5006.9  448.22  5012.9  450.01  5021.8  449.52  5033.9  450.23
  5070.1   450.7  5093.5  453.05  5187.8  454.79  5236.9  457.27  5260.2  458.79
  5266.2  459.83  5368.4  462.73  5380.7   463.8  5416.9  465.16  5447.1  465.52
#Mann= 3 ,-1 , 0
  4688.6     .05       0  4982.8     .03       0  4988.8     .05       0
Bank Sta=4982.8,4988.8
XS Rating Curve= 0 ,0
Exp/Cntr=0.3,0.1

Type RM Length L Ch R = 1 ,457     ,228,228,228
BEGIN DESCRIPTION:
Mapping XS 4fca559d
END DESCRIPTION:
XS GIS Cut Line= 4
      3689533.03     10792411.38      3689923.69     10792440.03
      3690033.06     10792372.32      3690245.61     10792089.79
#Sta/Elev= 30
  4526.5  464.72  4613.3  461.54  4643.4  459.03  4673.5  457.87  4711.9  455.49
  4716.9  455.88  4733.6   455.4  4773.7  453.52  4813.9  452.51    4874  451.98
  4918.2  450.02  4929.2  449.02    4960  448.62  4981.3  446.28  4987.1  445.09
  4999.5   444.2  5002.3   443.7  5005.5   444.2  5008.4   444.9  5023.8  445.55
  5039.2  447.41  5044.1  448.55  5124.6  450.87  5152.6  452.71  5196.3  454.05
  5224.7  455.48  5267.1  459.08  5331.6  461.57  5360.8  463.39  5400.4  463.85
#Mann= 3 ,-1 , 0
  4526.5     .05       0  4999.5     .03       0  5005.5     .05       0
Bank Sta=4999.5,5005.5
XS Rating Curve= 0 ,0
Exp/Cntr=0.3,0.1

Type RM Length L Ch R = 1 ,229     ,167,167,167
BEGIN DESCRIPTION:
UNT 190 IN CACR 2.0
END DESCRIPTION:
XS GIS Cut Line= 4
      3689812.36     10792491.58      3690133.51     10792567.53
      3690209.46     10792504.59      3690307.13     10792278.86
#Sta/Elev= 30
    4634  456.85  4648.1  456.32  4653.3  456.87  4695.5  456.06  4732.7  454.02
  4737.8  454.14    4775  451.51  4780.1  451.83  4785.3     451  4816.1   448.8
  4838.1  448.39  4857.2  447.67  4898.3  447.45  4906.9  446.44  4939.4  446.38
  4954.4  446.86    4964  446.35  4966.5  445.19  4970.5  444.75  4998.7  442.41
  5001.5  441.91  5004.7  442.41  5009.5   443.4  5023.9  443.87  5036.9  445.77
  5079.7  448.82  5089.2   448.7  5155.6  451.21  5209.1  452.43  5308.6  456.43
#Mann= 5 ,-1 , 0
    4634     .05       0  4838.1     .12       0  4970.5     .05       0
  4998.7     .03       0  5004.7     .05       0
Bank Sta=4998.7,5004.7
XS Rating Curve= 0 ,0
Exp/Cntr=0.3,0.1

Type RM Length L Ch R = 1 ,62      ,0,0,0
BEGIN DESCRIPTION:
UNT 190 IN CACR 1.0
END DESCRIPTION:
XS GIS Cut Line= 4
      3689919.06     10792584.01      3690266.32     10792663.88
      3690320.14     10792634.37      3690393.04     10792410.44
#Sta/Elev= 30
  4617.1  451.62  4622.6  450.73  4648.5  450.39  4658.7  448.76  4689.5  447.22
  4698.9     446  4720.3   444.7  4730.5  444.72  4740.8  445.84  4761.3  444.58
  4781.8  445.12    4799  444.25  4804.2  445.23  4882.1  444.84  4932.6  444.98
  4937.8  444.39  4956.3  444.98  4987.2  443.77  4989.9   439.3  4992.6   438.8
  4995.9   439.3    5000  439.72  5014.7  443.64  5033.2  444.74  5052.1  445.26
    5116  450.57  5133.9  450.56  5154.9  452.12    5218  454.64  5270.3  455.43
#Mann= 6 ,-1 , 0
  4617.1     .05       0  4698.9     .12       0  4882.1     .16       0
  4989.9     .07       0  4995.9     .16       0  5033.2     .05       0
Bank Sta=4989.9,4995.9
XS Rating Curve= 0 ,0
Exp/Cntr=0.3,0.1

Chan Stop Cuts=-1
Use User Specified Reach Order=0
Composite Channel Slope=5