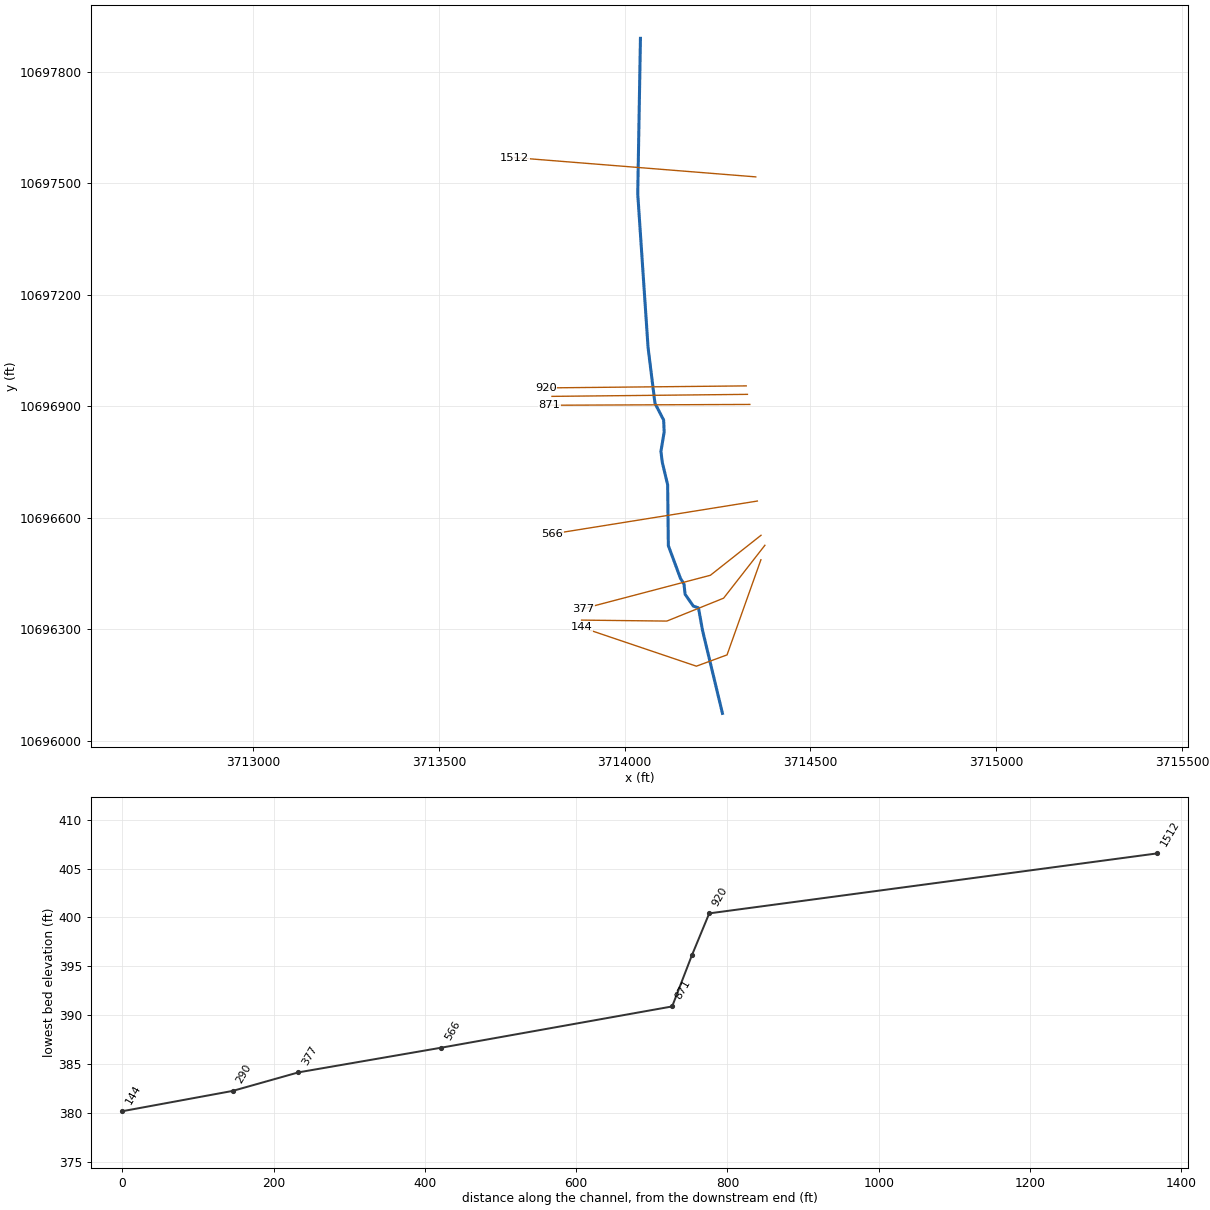
--- UNT 191 IN CACR.prj (project) ---

Proj Title=UNT 191 IN CACR Base Level Engineering
Current Plan=p01
Default Exp/Contr=0.3,0.1
English Units
Geom File=g01
Flow File=f01
Plan File=p01
BEGIN DESCRIPTION:
UNT 191 IN CACR
END DESCRIPTION:

--- UNT 191 IN CACR.p01 (plan) ---

Plan Title=Multiple Run
Short Identifier=Multiple
Geom File=g01
Flow File=f01
Subcritical Flow
K Sum by GR= 0
Std Step Tol= 0.01
Critical Tol= 0.01
Num of Std Step Trials= 20
Max Error Tol= 0.3
Flow Tol Ratio= 0.001
Split Flow NTrial= 30
Split Flow Tol= 0.02
Split Flow Ratio= 0.02
Log Output Level= 0
Friction Slope Method= 1
Unsteady Friction Slope Method= 2
Unsteady Bridges Friction Slope Method= 1
Parabolic Critical Depth
Global Vel Dist=  1 , 1 , 1
Global Log Level= 0
CheckData=True
Encroach Param= -1, 0, 0, 0
BEGIN DESCRIPTION:
Multiple Run
END DESCRIPTION:

--- UNT 191 IN CACR.f01 (steady flow) ---

Flow Title=Multiple
Number of Profiles=7
Profile Names=10-year,25-year,50-year,1pct_min,100-year,1pct_plu,500-year
River Rch & RM= UNT 191 IN CACR,Reach-1,1512
      88     115     136      93     157     222     209
Boundary for River Rch & Prof#=UNT 191 IN CACR,Reach-1,1
Up Type=0
Dn Type=3
Dn Slope=0.005
Boundary for River Rch & Prof#=UNT 191 IN CACR,Reach-1,2
Up Type=0
Dn Type=3
Dn Slope=0.005
Boundary for River Rch & Prof#=UNT 191 IN CACR,Reach-1,3
Up Type=0
Dn Type=3
Dn Slope=0.005
Boundary for River Rch & Prof#=UNT 191 IN CACR,Reach-1,4
Up Type=0
Dn Type=3
Dn Slope=0.005
Boundary for River Rch & Prof#=UNT 191 IN CACR,Reach-1,5
Up Type=0
Dn Type=3
Dn Slope=0.005
Boundary for River Rch & Prof#=UNT 191 IN CACR,Reach-1,6
Up Type=0
Dn Type=3
Dn Slope=0.005
Boundary for River Rch & Prof#=UNT 191 IN CACR,Reach-1,7
Up Type=0
Dn Type=3
Dn Slope=0.005

--- UNT 191 IN CACR.g01 (geometry) ---

Geom Title=Existing Conditions

River Reach=UNT 191 IN CACR,Reach-1
Reach XY= 17
      3714042.54     10697889.71      3714035.25     10697471.00
      3714063.00     10697058.00      3714081.64     10696907.42
      3714104.97     10696862.43      3714106.36     10696830.49
      3714097.64     10696778.18      3714101.25     10696749.00
      3714115.75     10696688.00      3714117.62     10696524.46
      3714150.11     10696436.74      3714159.83     10696420.76
      3714162.61     10696393.68      3714184.83     10696361.74
      3714198.72     10696356.88      3714209.68     10696295.96
      3714263.25     10696073.00

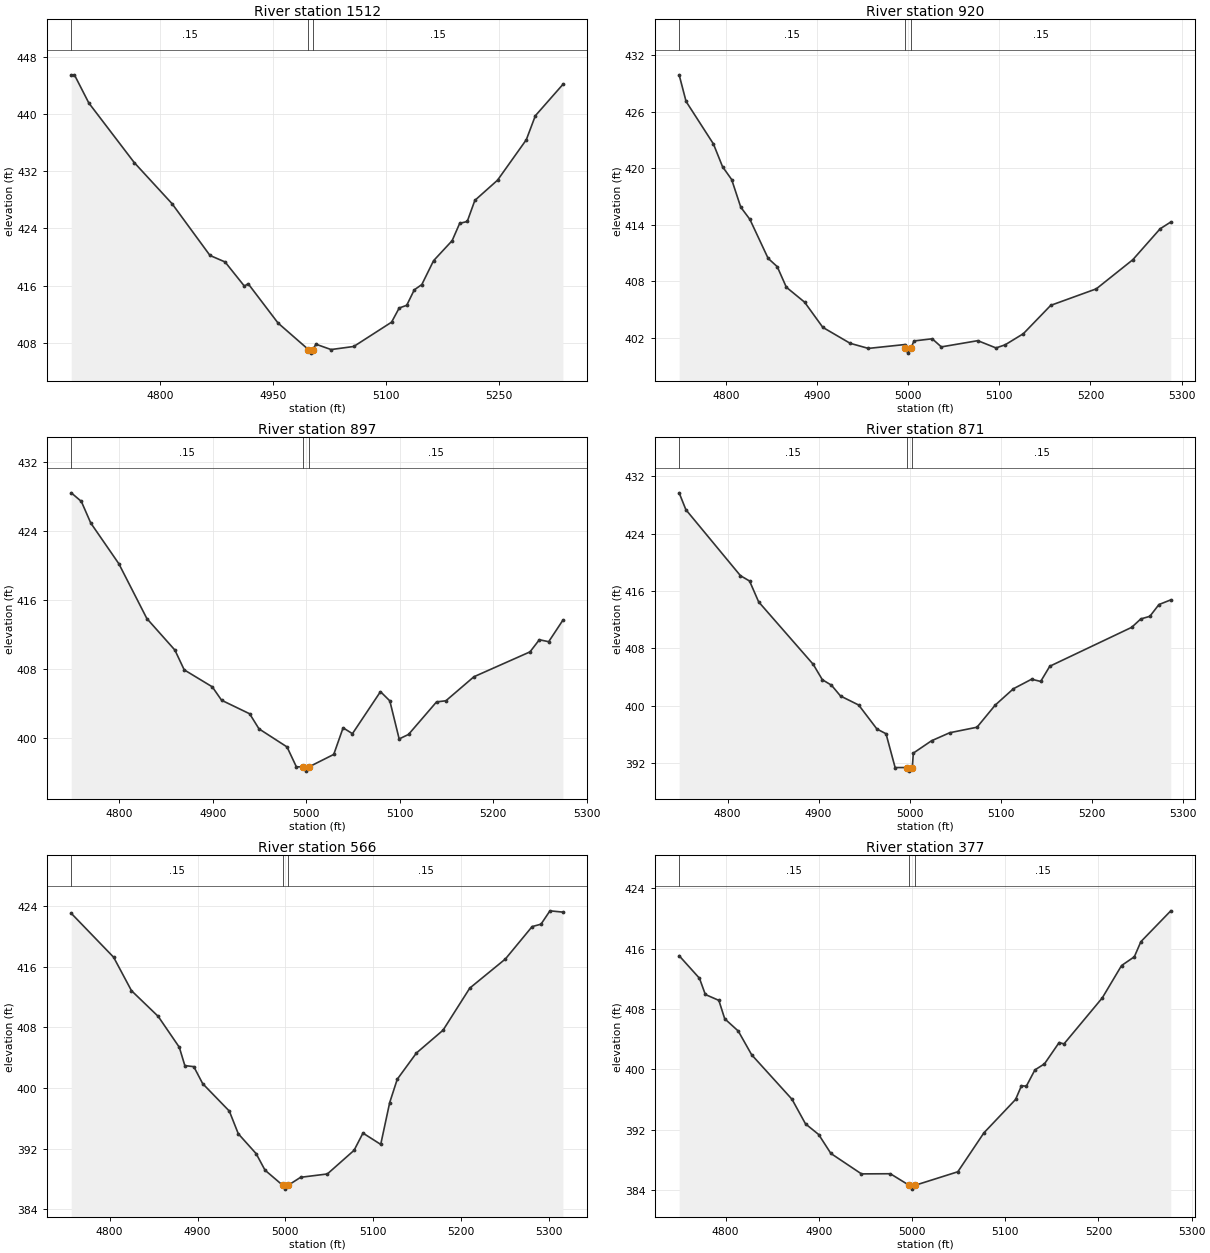
Type RM Length L Ch R = 1,1512,592,592,592
BEGIN DESCRIPTION:
UNT 191 IN CACR 1.0
END DESCRIPTION:
XS GIS Cut Line= 2
      3714352.88     10697516.85      3713703.25     10697568.82
#Sta/Elev= 30
  4682.6  445.47  4686.8  445.47  4705.9  441.53  4766.1  433.20  4816.3  427.44
  4866.5  420.21  4886.5  419.30  4912.1  415.92  4917.1  416.26  4956.7  410.76
  4997.0  407.05  4999.8  406.55  5003.0  407.05  5006.9  407.80  5027.0  407.05
  5057.1  407.48  5107.2  410.88  5117.3  412.86  5127.3  413.24  5137.3  415.40
  5147.3  416.14  5162.9  419.48  5187.5  422.28  5197.5  424.70  5207.5  424.96
  5217.6  427.91  5247.7  430.74  5285.8  436.39  5297.8  439.75  5334.3  444.13
#Mann=3,-1,0
  4682.6    0.15       0  4997.0    0.05       0  5003.0    0.15       0
Bank Sta=4997,5003
Exp/Cntr=0.3,0.1

Type RM Length L Ch R = 1,920,23,23,23
BEGIN DESCRIPTION:
Mapping XS 6103628c
END DESCRIPTION:
XS GIS Cut Line= 2
      3714327.23     10696954.35      3713787.96     10696948.93
#Sta/Elev= 30
  4748.9  429.89  4756.5  427.07  4786.5  422.57  4796.5  420.16  4806.5  418.80
  4816.5  415.87  4826.5  414.58  4846.5  410.45  4856.5  409.57  4866.5  407.39
  4886.5  405.81  4906.5  403.14  4936.5  401.45  4956.5  400.91  4996.5  401.32
  4997.0  400.91  4999.8  400.41  5003.0  400.91  5006.5  401.70  5026.5  401.93
  5036.5  401.07  5076.5  401.73  5096.5  400.96  5106.5  401.29  5126.5  402.47
  5156.5  405.47  5206.5  407.22  5246.5  410.30  5276.5  413.58  5288.2  414.30
#Mann=3,-1,0
  4748.9    0.15       0  4997.0    0.05       0  5003.0    0.15       0
Bank Sta=4997,5003
Exp/Cntr=0.3,0.1

Type RM Length L Ch R = 1,897,26,26,26
BEGIN DESCRIPTION:
Mapping XS ff426bb0
END DESCRIPTION:
XS GIS Cut Line= 2
      3714330.46     10696931.57      3713804.39     10696926.14
#Sta/Elev= 30
  4748.5  428.42  4759.3  427.42  4769.4  424.91  4799.4  420.19  4829.4  413.82
  4859.4  410.16  4869.4  407.86  4899.4  405.89  4909.4  404.33  4939.4  402.76
  4949.4  401.01  4979.4  398.91  4989.4  396.60  4997.0  396.60  4999.8  396.10
  5003.0  396.60  5029.4  398.04  5039.4  401.13  5049.4  400.45  5079.4  405.33
  5089.4  404.26  5099.4  399.84  5109.4  400.36  5139.4  404.14  5149.4  404.27
  5179.4  407.06  5239.4  409.95  5249.4  411.36  5259.4  411.13  5274.6  413.63
#Mann=3,-1,0
  4748.5    0.15       0  4997.0    0.05       0  5003.0    0.15       0
Bank Sta=4997,5003
Exp/Cntr=0.3,0.1

Type RM Length L Ch R = 1,871,305,305,305
BEGIN DESCRIPTION:
Mapping XS 2d934f1f
END DESCRIPTION:
XS GIS Cut Line= 2
      3714337.01     10696904.44      3713796.61     10696902.27
#Sta/Elev= 30
  4746.7  429.67  4754.1  427.32  4814.1  418.12  4824.1  417.38  4834.1  414.47
  4894.1  405.76  4904.1  403.62  4914.1  402.86  4924.1  401.35  4944.1  400.09
  4964.1  396.75  4974.1  396.09  4984.1  391.38  4997.0  391.38  4999.8  390.88
  5003.0  391.38  5004.1  393.39  5024.1  395.11  5044.1  396.23  5074.1  397.00
  5094.1  400.08  5114.1  402.36  5134.1  403.69  5144.1  403.38  5154.1  405.50
  5244.1  410.92  5254.1  412.09  5264.1  412.46  5274.1  414.10  5287.1  414.75
#Mann=3,-1,0
  4746.7    0.15       0  4997.0    0.05       0  5003.0    0.15       0
Bank Sta=4997,5003
Exp/Cntr=0.3,0.1

Type RM Length L Ch R = 1,566,189,189,189
BEGIN DESCRIPTION:
Mapping XS fafc0b7a
END DESCRIPTION:
XS GIS Cut Line= 2
      3714357.21     10696644.46      3713805.07     10696555.91
#Sta/Elev= 30
  4756.4  423.03  4804.6  417.24  4824.9  412.83  4855.3  409.44  4879.3  405.37
  4885.6  402.95  4895.8  402.81  4905.9  400.57  4936.2  396.95  4946.4  393.96
  4966.7  391.34  4976.8  389.16  4997.0  387.16  4999.8  386.66  5003.0  387.16
  5017.3  388.22  5047.7  388.66  5078.1  391.78  5088.2  394.05  5108.4  392.56
  5118.6  398.07  5127.2  401.15  5149.0  404.61  5179.3  407.62  5209.7  413.17
  5250.2  417.01  5280.6  421.28  5290.7  421.60  5300.9  423.36  5315.6  423.19
#Mann=3,-1,0
  4756.4    0.15       0  4997.0    0.05       0  5003.0    0.15       0
Bank Sta=4997,5003
Exp/Cntr=0.3,0.1

Type RM Length L Ch R = 1,377,87,87,87
BEGIN DESCRIPTION:
Mapping XS 9bdf143f
END DESCRIPTION:
XS GIS Cut Line= 3
      3714367.07     10696552.33      3714230.75     10696444.66
      3713888.57     10696354.79
#Sta/Elev= 30
  4750.1  415.07  4771.9  412.08  4778.2  409.93  4792.7  409.15  4799.0  406.71
  4813.5  405.09  4827.9  401.94  4871.2  396.04  4885.7  392.78  4899.8  391.37
  4912.9  388.86  4945.7  386.15  4976.7  386.17  4997.0  384.63  4999.8  384.13
  5003.0  384.63  5049.1  386.43  5077.1  391.59  5111.1  396.02  5117.4  397.84
  5122.6  397.77  5131.8  399.93  5142.1  400.74  5157.8  403.56  5163.0  403.38
  5204.1  409.48  5224.8  413.77  5238.5  414.93  5245.5  416.93  5277.6  421.02
#Mann=3,-1,0
  4750.1    0.15       0  4997.0    0.05       0  5003.0    0.15       0
Bank Sta=4997,5003
Exp/Cntr=0.3,0.1

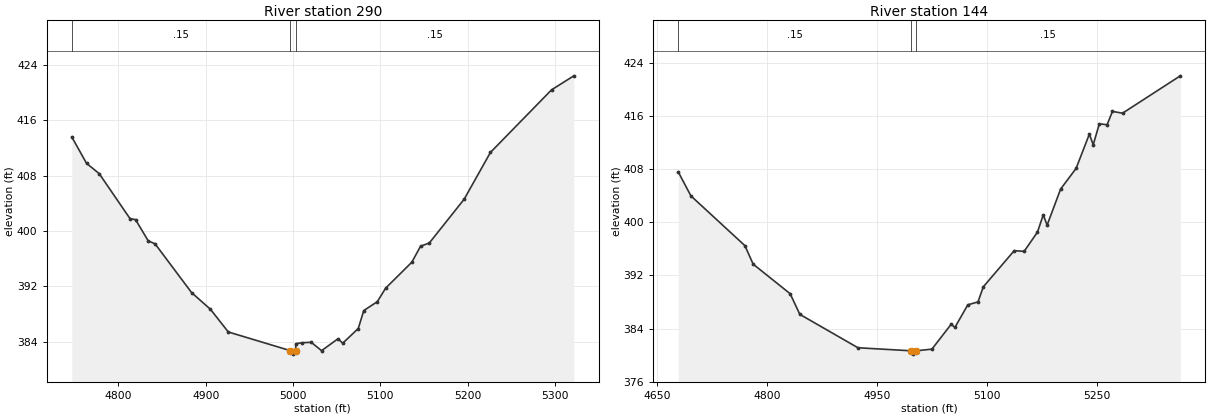
Type RM Length L Ch R = 1,290,146,146,146
BEGIN DESCRIPTION:
Mapping XS 9e86a447
END DESCRIPTION:
XS GIS Cut Line= 4
      3714377.45     10696525.38      3714266.34     10696383.03
      3714113.57     10696321.40      3713884.10     10696323.99
#Sta/Elev= 30
  4746.7  413.59  4763.6  409.78  4778.1  408.29  4813.4  401.79  4819.7  401.65
  4834.2  398.59  4842.1  398.15  4883.9  391.11  4905.5  388.70  4925.9  385.43
  4997.0  382.73  4999.8  382.23  5003.0  382.73  5003.2  383.73  5010.0  383.87
  5020.8  383.94  5032.7  382.73  5051.5  384.45  5056.9  383.81  5074.7  385.93
  5081.0  388.52  5096.5  389.80  5106.0  391.75  5136.0  395.50  5146.0  397.81
  5156.0  398.27  5196.0  404.61  5226.0  411.35  5296.0  420.39  5321.5  422.41
#Mann=3,-1,0
  4746.7    0.15       0  4997.0    0.05       0  5003.0    0.15       0
Bank Sta=4997,5003
Exp/Cntr=0.3,0.1

Type RM Length L Ch R = 1,144,0,0,0
BEGIN DESCRIPTION:
UNT 191 IN CACR 2.0
END DESCRIPTION:
XS GIS Cut Line= 4
      3714366.73     10696486.45      3714275.60     10696230.39
      3714193.13     10696200.01      3713884.94     10696304.19
#Sta/Elev= 30
  4679.1  407.61  4696.4  403.99  4770.1  396.49  4781.3  393.71  4831.8  389.25
  4845.0  386.14  4924.3  381.11  4997.0  380.65  4999.8  380.15  5003.0  380.65
  5025.2  380.90  5051.4  384.64  5056.6  384.18  5074.2  387.58  5088.1  388.02
  5095.3  390.29  5137.5  395.74  5151.0  395.63  5169.2  398.53  5177.1  401.13
  5182.4  399.59  5200.8  405.02  5221.9  408.13  5240.0  413.29  5245.3  411.70
  5253.6  414.85  5264.2  414.71  5271.5  416.72  5285.3  416.45  5364.1  422.08
#Mann=3,-1,0
  4679.1    0.15       0  4997.0    0.05       0  5003.0    0.15       0
Bank Sta=4997,5003
Exp/Cntr=0.3,0.1

Chan Stop Cuts=-1