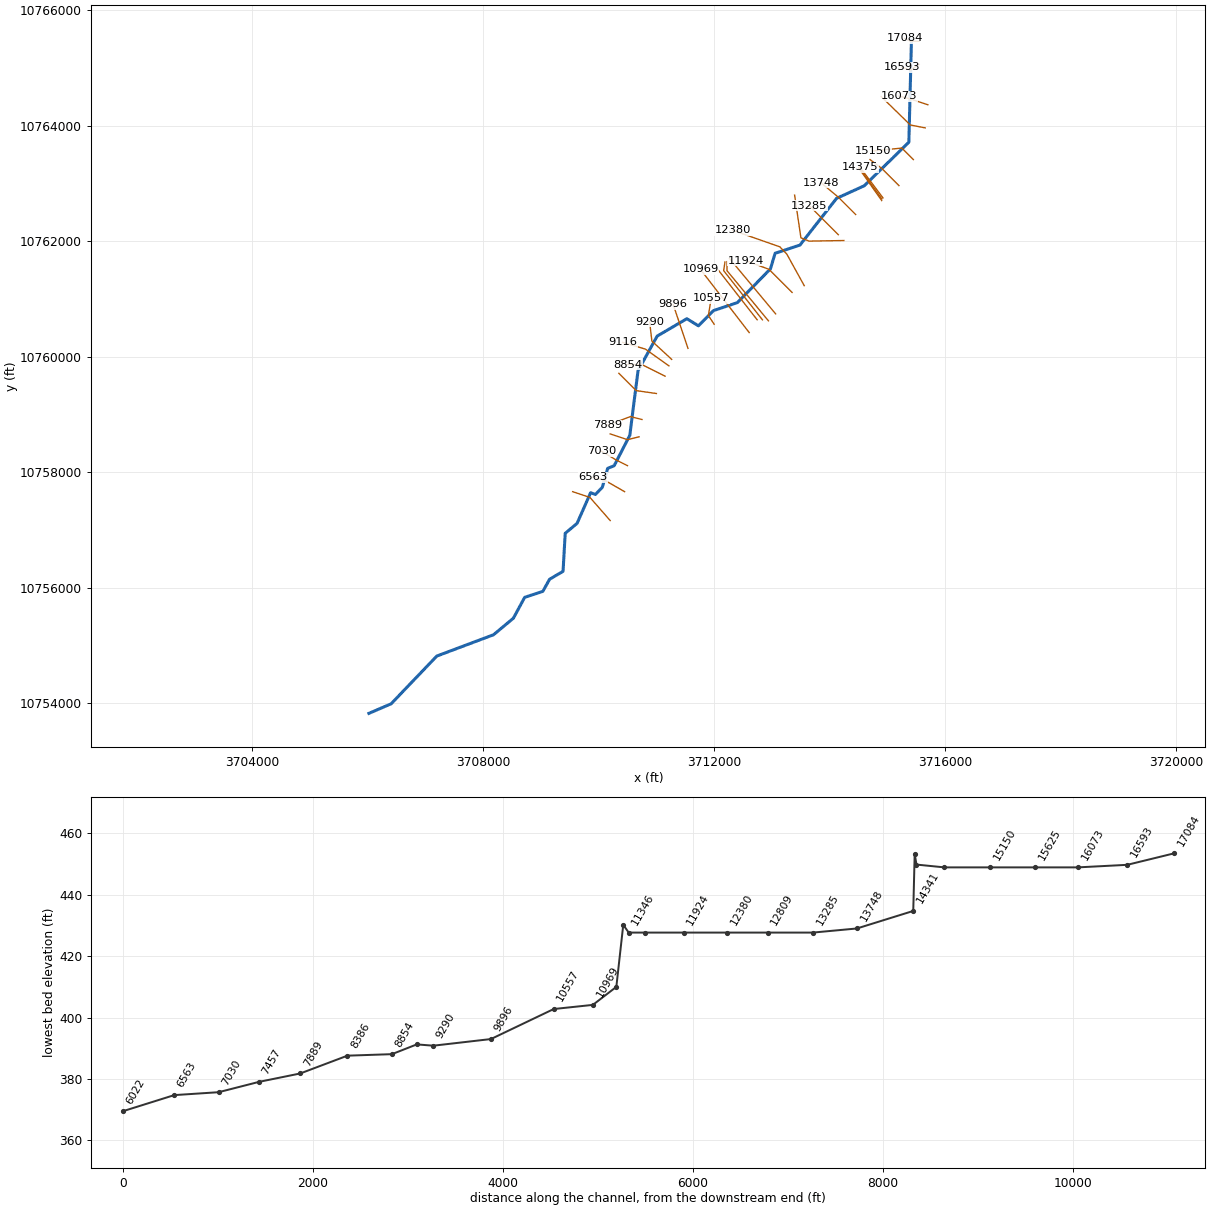
--- WIRE BRANCH.prj (project) ---

Proj Title=WIRE BRANCH Base Level Engineering
Current Plan=p01
Default Exp/Contr=0.3,0.1
English Units
Geom File=g01
Flow File=f01
Plan File=p01
Y Axis Title=Elevation
X Axis Title(PF)=Main Channel Distance
X Axis Title(XS)=Station
BEGIN DESCRIPTION:
WIRE BRANCH
END DESCRIPTION:
DSS Export Rating Curves= 0
DSS Export Rating Curve Sorted= 0
DSS Export Volume Flow Curves= 0
DXF OffsetX= 0
DXF OffsetY= 0
DXF ScaleX= 1
DXF ScaleY= 10

--- WIRE BRANCH.p01 (plan) ---

Plan Title=Multiple Run
Short Identifier=Multiple
Geom File=g01
Flow File=f01
Subcritical Flow
K Sum by GR= 0
Std Step Tol= 0.01
Critical Tol= 0.01
Num of Std Step Trials= 20
Max Error Tol= 0.3
Flow Tol Ratio= 0.001
Split Flow NTrial= 30
Split Flow Tol= 0.02
Split Flow Ratio= 0.02
Log Output Level= 0
Friction Slope Method= 1
Unsteady Friction Slope Method= 2
Unsteady Bridges Friction Slope Method= 1
Parabolic Critical Depth
Global Vel Dist=  1 , 1 , 1
Global Log Level= 0
CheckData=True
Encroach Param= -1, 0, 0, 0
BEGIN DESCRIPTION:
Multiple Run
END DESCRIPTION:

--- WIRE BRANCH.f01 (steady flow) ---

Flow Title=Multiple
Number of Profiles=7
Profile Names=10-year,25-year,50-year,1pct_min,100-year,1pct_plu,500-year
River Rch & RM= WIRE BRANCH,Reach-1,17084
     364     475     564     491     664     898     922
River Rch & RM= WIRE BRANCH,Reach-1,12380
     474     628     753     662     896    1211    1269
River Rch & RM= WIRE BRANCH,Reach-1,11924
     735    1002    1224    1095    1482    2004    2176
River Rch & RM= WIRE BRANCH,Reach-1,9116
    1040    1446    1789    1621    2192    2964    3298
River Rch & RM= WIRE BRANCH,Reach-1,5564
    1230    1720    2135    1938    2621    3545    3963
Boundary for River Rch & Prof#=WIRE BRANCH,Reach-1,1
Up Type=0
Dn Type=3
Dn Slope=0.005
Boundary for River Rch & Prof#=WIRE BRANCH,Reach-1,2
Up Type=0
Dn Type=3
Dn Slope=0.005
Boundary for River Rch & Prof#=WIRE BRANCH,Reach-1,3
Up Type=0
Dn Type=3
Dn Slope=0.005
Boundary for River Rch & Prof#=WIRE BRANCH,Reach-1,4
Up Type=0
Dn Type=3
Dn Slope=0.005
Boundary for River Rch & Prof#=WIRE BRANCH,Reach-1,5
Up Type=0
Dn Type=3
Dn Slope=0.005
Boundary for River Rch & Prof#=WIRE BRANCH,Reach-1,6
Up Type=0
Dn Type=3
Dn Slope=0.005
Boundary for River Rch & Prof#=WIRE BRANCH,Reach-1,7
Up Type=0
Dn Type=3
Dn Slope=0.005

--- WIRE BRANCH.g01 (geometry) ---

Geom Title=Existing Conditions
Program Version=4.10

River Reach=WIRE BRANCH     ,Reach-1
Reach XY= 30
       3715416.3     10765478.96       3715371.5       10763712.
        3714599.       10762957.       3714119.5       10762739.
       3713485.5       10761930.      3713055.25       10761788.
       3712974.5       10761518.      3712401.75       10760934.
        3711987.       10760795.      3711728.25       10760532.
       3711526.5       10760655.        3711013.       10760354.
       3710681.5       10759755.      3710539.25       10758636.
      3710268.75       10758110.        3710155.       10758063.
        3710064.       10757737.      3709944.25       10757612.
      3709860.25       10757642.        3709626.       10757111.
      3709420.75       10756939.      3709383.25       10756281.
        3709150.       10756143.      3709033.25       10755934.
       3708718.5       10755830.      3708523.75       10755469.
      3708178.75       10755182.      3707197.36     10754813.62
       3706406.5       10753987.      3706021.25       10753821.

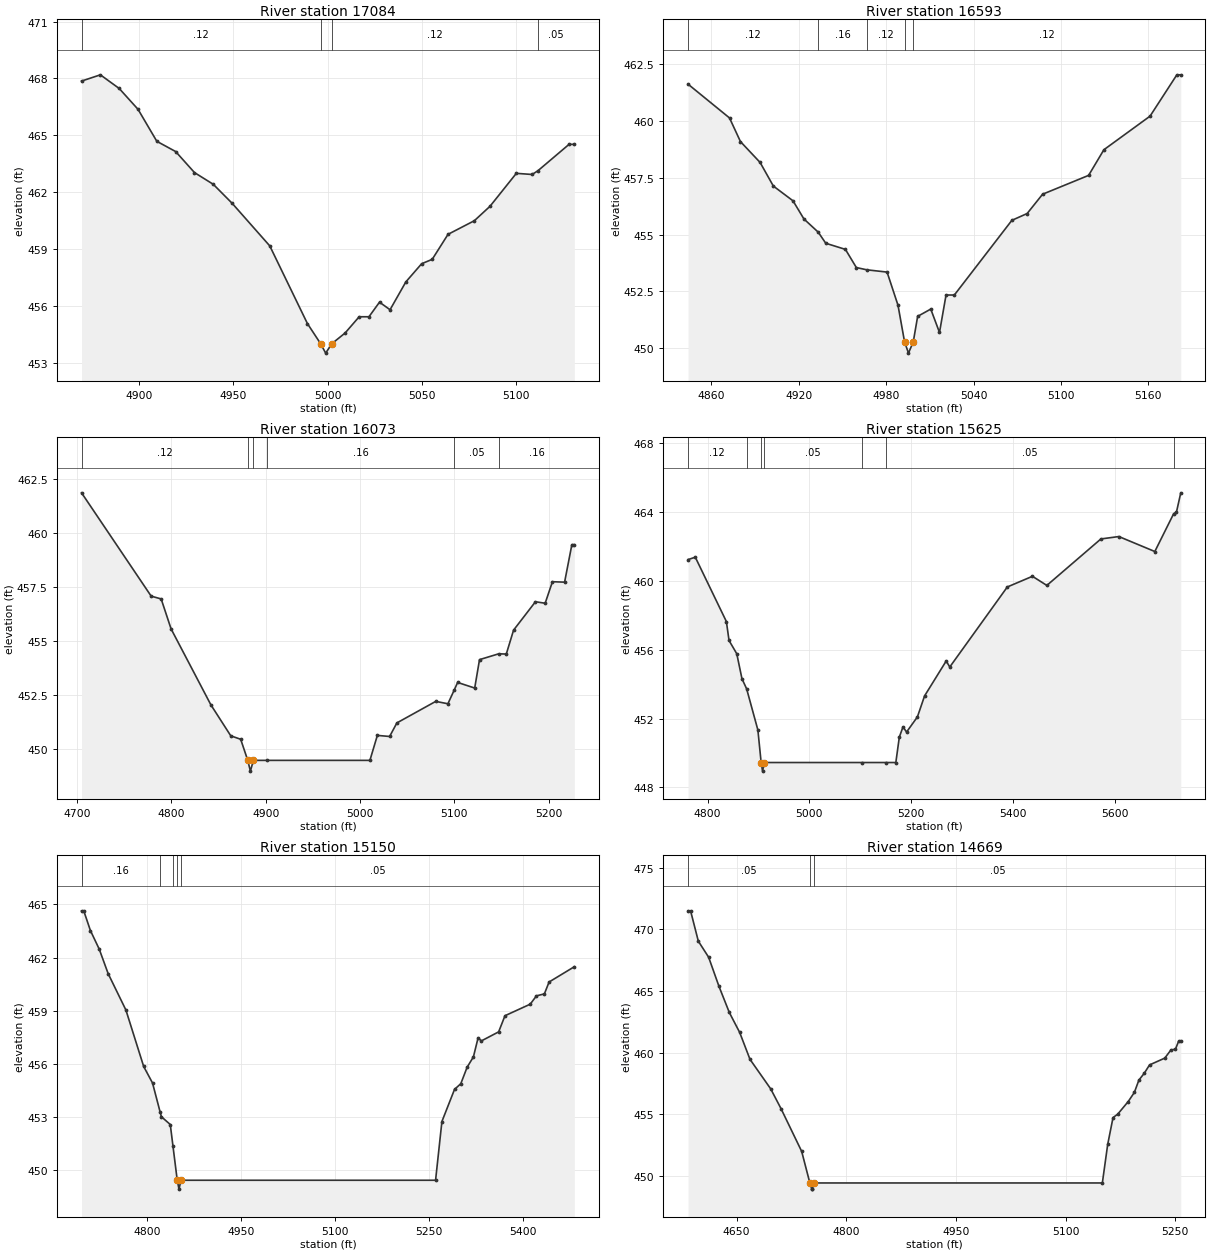
Type RM Length L Ch R = 1 ,17084   ,491,491,491
BEGIN DESCRIPTION:
WIRE BRANCH 35.0
END DESCRIPTION:
XS GIS Cut Line= 3
      3715549.56     10765460.19      3715399.61     10765460.19
      3715299.57     10765510.21
#Sta/Elev= 30
  4869.3  467.86  4879.3  468.19  4889.3  467.47  4899.3  466.37  4909.3  464.68
  4919.3  464.14  4929.3  463.03  4939.3  462.41  4949.3  461.41  4969.3  459.16
  4989.3  455.06  4996.3     454    4999   453.5  5002.3     454  5009.3  454.56
  5016.8  455.42    5022  455.42  5027.6  456.19  5033.2  455.79  5041.6  457.26
    5050  458.22  5055.6  458.45    5064  459.77    5078  460.49  5086.3  461.25
  5100.3  462.99  5108.7  462.93  5111.8  463.13  5128.3  464.52  5131.1  464.52
#Mann= 4 ,-1 , 0
  4869.3     .12       0  4996.3     .07       0  5002.3     .12       0
  5111.8     .05       0
Bank Sta=4996.3,5002.3
XS Rating Curve= 0 ,0
Exp/Cntr=0.3,0.1

Type RM Length L Ch R = 1 ,16593   ,520,520,520
BEGIN DESCRIPTION:
WIRE BRANCH 34.0
END DESCRIPTION:
XS GIS Cut Line= 3
      3715549.58     10765060.17      3715399.61     10764960.19
      3715249.57      10765010.2
#Sta/Elev= 30
  4843.9  461.63  4872.4  460.14  4879.9   459.1  4893.4  458.18  4902.5  457.14
    4916  456.49  4923.5  455.69  4933.3  455.11  4938.5  454.62    4952  454.35
  4959.5  453.55  4966.7  453.45  4980.6  453.35  4988.1  451.89  4992.6  450.28
  4995.3  449.78  4998.6  450.28  5001.6   451.4  5010.6  451.72  5016.6  450.69
  5021.1  452.34  5026.8  452.34  5066.3  455.63  5076.8  455.93  5087.4  456.78
    5119  457.61  5129.5  458.74  5161.2  460.22  5179.6  462.04  5182.3  462.04
#Mann= 5 ,-1 , 0
  4843.9     .12       0  4933.3     .16       0  4966.7     .12       0
  4992.6     .07       0  4998.6     .12       0
Bank Sta=4992.6,4998.6
XS Rating Curve= 0 ,0
Exp/Cntr=0.3,0.1

Type RM Length L Ch R = 1 ,16073   ,448,448,448
BEGIN DESCRIPTION:
WIRE BRANCH 33.0
END DESCRIPTION:
XS GIS Cut Line= 3
      3715699.65     10764360.18      3715399.61     10764460.19
      3715199.63     10764510.18
#Sta/Elev= 30
  4704.8  461.88  4778.6  457.08  4789.2  456.95  4799.7  455.56  4841.9  452.03
    4863  450.59  4873.5  450.43    4881  449.45  4883.8  448.95    4887  449.45
  4901.4  449.45  5010.5  449.45  5018.4  450.61  5031.4  450.56  5039.1  451.19
  5080.3  452.19  5093.2  452.08  5099.7   452.7  5103.5  453.07  5121.6  452.81
  5126.7  454.13    5147   454.4  5155.1  454.39  5162.8   455.5    5186  456.82
  5196.3  456.75    5204  457.75  5216.9  457.73  5224.6  459.47  5227.2  459.47
#Mann= 6 ,-1 , 0
  4704.8     .12       0    4881     .07       0    4887     .12       0
  4901.4     .16       0  5099.7     .05       0    5147     .16       0
Bank Sta=4881,4887
XS Rating Curve= 0 ,0
Exp/Cntr=0.3,0.1

Type RM Length L Ch R = 1 ,15625   ,475,475,475
BEGIN DESCRIPTION:
Mapping XS a5b21979
END DESCRIPTION:
XS GIS Cut Line= 3
       3715653.6     10763959.75      3715397.52     10764009.66
      3714890.78     10764503.39
#Sta/Elev= 30
  4761.5  461.24  4775.8  461.38  4836.9  457.64  4842.1  456.54  4857.3  455.77
  4867.5  454.32  4876.7  453.73  4898.8  451.34  4905.2  449.45    4908  448.95
  4911.2  449.45  5103.8  449.45  5151.5  449.45  5169.9  449.45  5176.8  450.93
    5184  451.52    5191  451.22  5212.3   452.1  5226.4  453.32  5268.9  455.35
  5275.9     455    5389  459.65  5438.4  460.27  5466.7  459.74  5572.9  462.44
  5608.2  462.58  5678.9  461.71  5715.8   463.9  5721.4     464  5729.9  465.12
#Mann= 7 ,-1 , 0
  4761.5     .12       0  4876.7     .05       0  4905.2    .033       0
  4911.2     .05       0  5103.8     .16       0  5151.5     .05       0
  5715.8     .16       0
Bank Sta=4905.2,4911.2
XS Rating Curve= 0 ,0
Exp/Cntr=0.3,0.1

Type RM Length L Ch R = 1 ,15150   ,481,481,481
BEGIN DESCRIPTION:
WIRE BRANCH 31.0
END DESCRIPTION:
XS GIS Cut Line= 3
      3715449.58     10763410.21      3715249.61     10763610.19
      3714749.61     10763560.19
#Sta/Elev= 30
    4696  464.63  4699.5  464.63  4710.1  463.52  4724.2  462.47  4738.4  461.09
  4766.7  459.04    4795  455.86  4809.1  454.93  4821.1  453.31  4823.2  453.03
  4837.4  452.59  4841.7  451.37  4848.5  449.45  4851.3  448.95  4854.5  449.45
  5260.2  449.45  5270.3  452.76  5290.4  454.57  5300.4  454.89  5310.5  455.82
  5320.5   456.4    5328  457.48  5333.1   457.3  5360.7  457.81  5370.8  458.72
    5411  459.37    5421  459.84  5433.6  459.95  5441.1  460.62  5481.3  461.48
#Mann= 5 ,-1 , 0
    4696     .16       0  4821.1      .1       0  4841.7     .05       0
  4848.5    .033       0  4854.5     .05       0
Bank Sta=4848.5,4854.5
XS Rating Curve= 0 ,0
Exp/Cntr=0.3,0.1

Type RM Length L Ch R = 1 ,14669   ,294,294,294
BEGIN DESCRIPTION:
WIRE BRANCH 30.0
END DESCRIPTION:
XS GIS Cut Line= 3
      3715199.58     10762960.22      3714899.61     10763260.19
      3714699.62     10763410.18
#Sta/Elev= 29
  4583.5  471.51    4587  471.51  4597.6  469.05  4611.7  467.75  4625.9  465.38
    4640  463.27  4654.2  461.65  4668.3  459.47  4696.6  457.08  4710.7  455.48
    4739  452.01  4750.2  449.45  4752.9  448.95  4753.4  448.95  4756.2  449.45
  5150.4  449.45  5157.7  452.57    5165  454.75  5171.3  455.02  5185.8  456.05
  5194.2  456.79  5200.4  457.79  5207.7  458.34    5215  459.02  5235.8  459.57
  5244.2  460.23  5250.4  460.29  5254.6  460.92  5257.7  460.92
#Mann= 3 ,-1 , 0
  4583.5     .05       0  4750.2    .033       0  4756.2     .05       0
Bank Sta=4750.2,4756.2
XS Rating Curve= 0 ,0
Exp/Cntr=0.3,0.1

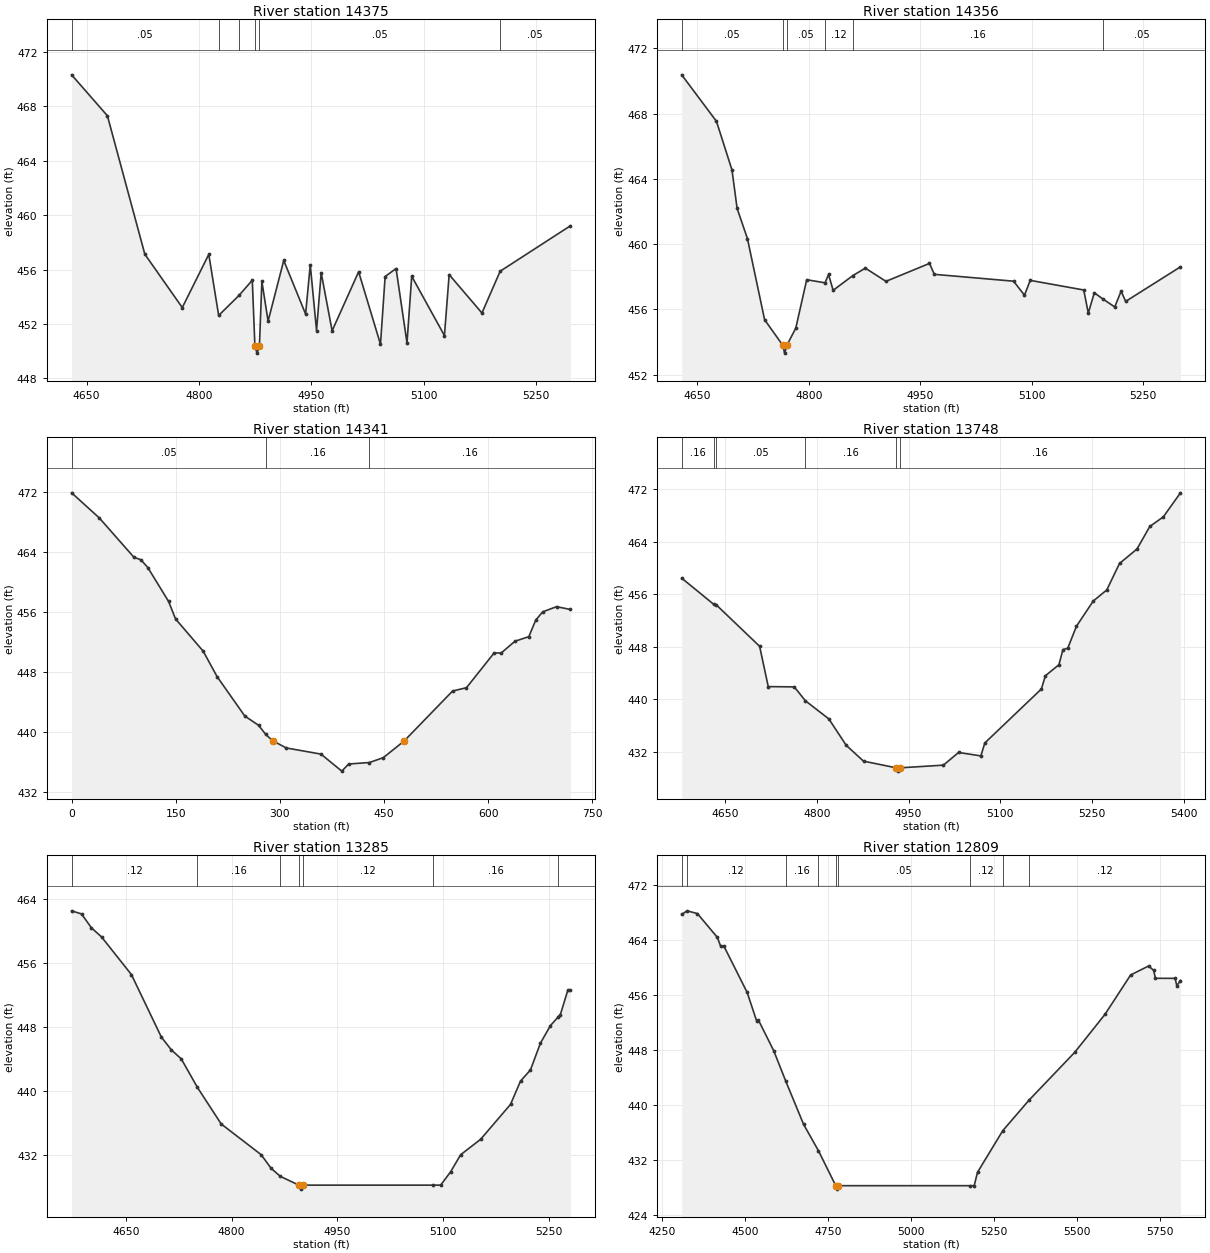
Type RM Length L Ch R = 1 ,14375   ,19,19,19
BEGIN DESCRIPTION:
Mapping XS cd0879ab
END DESCRIPTION:
XS GIS Cut Line= 2
      3714923.25     10762746.97      3714524.29     10763280.37
#Sta/Elev= 30
  4629.9  470.32  4677.7  467.31  4727.7  457.13  4777.7  453.21  4813.1  457.12
  4826.3  452.63  4853.6  454.11  4871.2  455.22  4874.7  450.36  4877.5  449.86
  4880.7  450.36    4884  455.13  4892.3  452.21  4913.2  456.67  4942.4  452.73
  4948.6  456.35    4957  451.52  4963.2  455.77  4977.8   451.5  5013.2  455.84
  5042.4  450.51  5048.6  455.49  5063.2  456.08  5077.8  450.61  5084.1  455.51
  5127.8  451.15  5134.1  455.63  5177.9  452.81  5202.2  455.88    5296  459.22
#Mann= 6 ,-1 , 0
  4629.9     .05       0  4826.3      .1       0  4853.6     .05       0
  4874.7     .07       0  4880.7     .05       0  5202.2     .05       0
Bank Sta=4874.7,4880.7
XS Rating Curve= 0 ,0
Exp/Cntr=0.3,0.1

Type RM Length L Ch R = 1 ,14356   ,15,15,15
BEGIN DESCRIPTION:
Mapping XS 955d1a7a
END DESCRIPTION:
XS GIS Cut Line= 2
       3714903.7     10762729.64      3714510.94      10763274.3
#Sta/Elev= 30
  4628.8  470.38  4675.6  467.53  4696.5  464.55  4703.4  462.19  4717.3  460.34
  4740.4  455.37  4764.6  453.82  4767.4  453.32  4770.6  453.82  4782.4  454.85
  4797.1  457.82  4821.8  457.63  4826.5  458.14  4832.7  457.17  4859.1  458.07
  4876.1  458.53  4903.8  457.72  4962.4  458.82  4968.9  458.15  5075.6  457.73
  5090.3  456.87    5098  457.78  5170.1  457.19  5176.2  455.77  5184.3  457.02
  5195.5  456.65  5211.8  456.15  5220.4  457.12  5226.5  456.49  5300.3  458.61
#Mann= 6 ,-1 , 0
  4628.8     .05       0  4764.6     .07       0  4770.6     .05       0
  4821.8     .12       0  4859.1     .16       0  5195.5     .05       0
Bank Sta=4764.6,4770.6
XS Rating Curve= 0 ,0
Exp/Cntr=0.3,0.1

Type RM Length L Ch R = 1 ,14341   ,593,593,593
BEGIN DESCRIPTION:
WIRE BRANCH 29.0
END DESCRIPTION:
XS GIS Cut Line= 2
      3714901.58     10762701.36      3714502.41     10763265.41
#Sta/Elev= 30
       0  471.89   39.92  468.54   89.81  463.29   99.79  462.96  109.77  461.92
  139.71   457.4  149.69  455.07   189.6  450.76  209.56  447.37  249.48  442.11
  269.44  440.87  279.42  439.68  289.39  438.82  309.35  437.85  359.25  437.03
  389.19  434.76  399.17  435.71   429.1  435.91  449.06  436.56     479  438.78
  548.85  445.45  568.81  445.89  608.73  450.54  618.71  450.51  638.66  452.09
  658.62   452.7   668.6  454.91  678.58  456.01  698.54   456.7   718.5  456.33
#Mann= 3 ,-1 , 0
       0     .05       0  279.42     .16       0   429.1     .16       0
Bank Sta=289.39,479
XS Rating Curve= 0 ,0
Exp/Cntr=0.3,0.1

Type RM Length L Ch R = 1 ,13748   ,463,463,463
BEGIN DESCRIPTION:
WIRE BRANCH 28.0
END DESCRIPTION:
XS GIS Cut Line= 3
      3714449.62     10762460.18      3714149.61     10762760.19
       3713849.6      10763010.2
#Sta/Elev= 30
  4579.4  458.44  4631.5  454.47  4635.9  454.37  4706.7  448.06  4720.8  441.92
  4763.3  441.88  4781.5  439.76  4819.8     437  4848.1  432.99  4876.4  430.57
    4930  429.55  4932.7  429.05    4936  429.55  5006.9  429.96  5031.7  431.89
  5068.1  431.37  5074.6  433.34    5167  441.56  5173.5  443.57  5195.7  445.26
  5202.2  447.56    5210  447.75  5224.3  451.12  5251.7  454.95  5273.8  456.64
  5294.6  460.67  5323.2  462.88  5344.1  466.31  5366.2  467.77  5394.2  471.43
#Mann= 6 ,-1 , 0
  4579.4     .16       0  4631.5     .12       0  4635.9     .05       0
  4781.5     .16       0    4930     .07       0    4936     .16       0
Bank Sta=4930,4936
XS Rating Curve= 0 ,0
Exp/Cntr=0.3,0.1

Type RM Length L Ch R = 1 ,13285   ,476,476,476
BEGIN DESCRIPTION:
WIRE BRANCH 27.0
END DESCRIPTION:
XS GIS Cut Line= 3
      3714149.58     10762110.21      3713849.61     10762410.19
      3713649.59     10762610.21
#Sta/Elev= 30
  4573.2  462.53  4587.3  462.14  4601.4  460.39  4615.6  459.27    4658  454.55
  4700.4  446.74  4714.6  445.13  4728.7     444  4751.6  440.43  4785.3  435.86
  4841.9  432.02    4856  430.32  4869.2   429.3  4895.4  428.21  4898.2  427.71
  4901.4  428.21    5086  428.21  5096.4  428.21  5110.6  429.89  5124.7  432.01
    5153  433.94  5195.4  438.31  5209.6  441.23  5223.7  442.62  5237.8  445.97
    5252  448.17  5262.5   449.2  5266.1  449.55  5276.7  452.61  5280.3  452.61
#Mann= 7 ,-1 , 0
  4573.2     .12       0  4751.6     .16       0  4869.2     .05       0
  4895.4    .033       0  4901.4     .12       0    5086     .16       0
  5262.5     .12       0
Bank Sta=4895.4,4901.4
XS Rating Curve= 0 ,0
Exp/Cntr=0.3,0.1

Type RM Length L Ch R = 1 ,12809   ,429,429,429
BEGIN DESCRIPTION:
WIRE BRANCH 26.0
END DESCRIPTION:
XS GIS Cut Line= 4
      3714246.98     10762009.14      3713642.84     10761998.72
      3713502.22     10762056.02      3713392.87     10762795.39
#Sta/Elev= 30
  4308.4  467.68  4324.7   468.2  4355.8   467.8  4415.8  464.34  4425.8  463.06
  4435.8  463.05  4505.8  456.32  4534.2   452.2  4539.2  452.35  4585.8  447.85
  4621.6  443.48  4675.8  437.14  4720.5  433.31  4772.8  428.21  4775.6  427.71
  4778.8  428.21  5176.8  428.21    5190  428.21  5200.1  430.16  5276.3  436.22
  5355.7  440.67  5493.3  447.62  5584.2  453.13  5661.7  458.87  5715.7  460.17
  5731.2  459.53  5736.3  458.38  5795.7  458.38  5800.8   457.3  5811.9  458.06
#Mann= 9 ,-1 , 0
  4308.4     .05       0  4324.7     .12       0  4621.6     .16       0
  4720.5     .05       0  4772.8    .033       0  4778.8     .05       0
  5176.8     .12       0  5276.3     .16       0  5355.7     .12       0
Bank Sta=4772.8,4778.8
XS Rating Curve= 0 ,0
Exp/Cntr=0.3,0.1

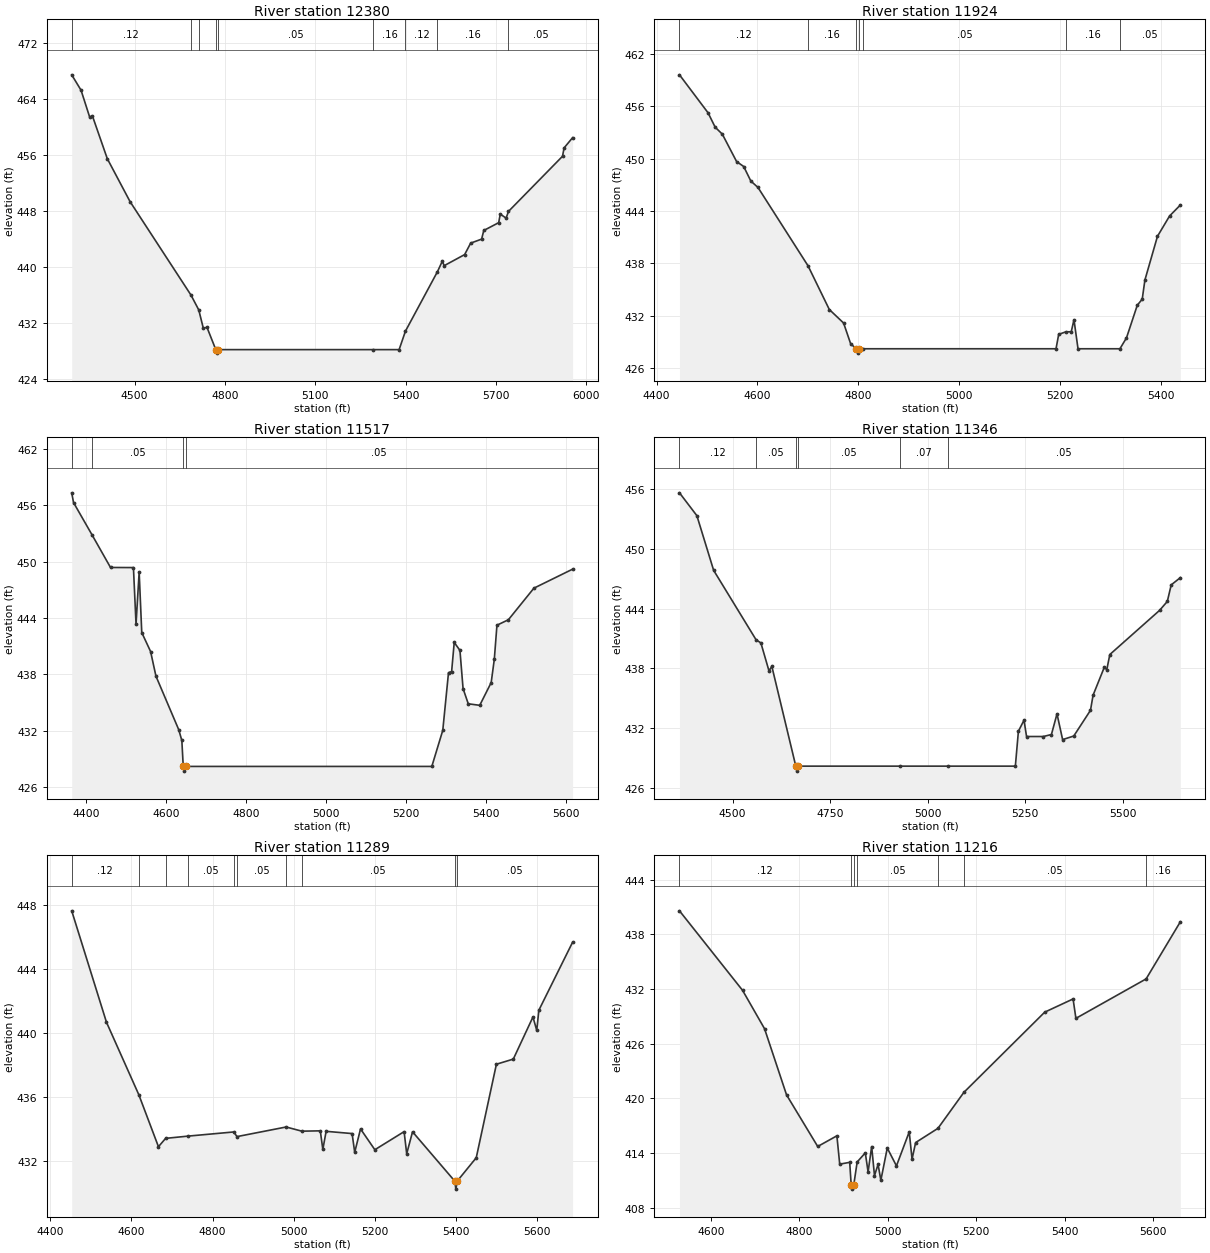
Type RM Length L Ch R = 1 ,12380   ,456,456,456
BEGIN DESCRIPTION:
WIRE BRANCH 25.0
END DESCRIPTION:
XS GIS Cut Line= 4
      3713559.51     10761227.89      3713257.42     10761774.77
      3713137.63     10761899.77      3712321.37     10762185.72
#Sta/Elev= 30
  4291.1  467.48  4322.1  465.28  4350.8  461.43  4359.9   461.6  4409.2   455.5
  4484.8  449.36  4687.1     436  4712.9  433.88  4727.8   431.3  4740.3  431.38
  4769.4  428.21  4772.1  427.71  4775.4  428.21  5292.8  428.21    5378  428.21
  5399.1  430.86  5505.4  439.36  5521.3  440.84  5527.7  440.21  5595.5  441.79
  5615.5  443.43  5651.8     444  5659.1  445.24  5708.5  446.35  5713.8  447.58
  5733.2     447    5741  447.96  5920.4  455.84  5925.7  457.04  5953.9   458.5
#Mann= 9 ,-1 , 0
  4291.1     .12       0  4687.1     .16       0  4712.9     .05       0
  4769.4    .033       0  4775.4     .05       0  5292.8     .16       0
  5399.1     .12       0  5505.4     .16       0    5741     .05       0
Bank Sta=4769.4,4775.4
XS Rating Curve= 0 ,0
Exp/Cntr=0.3,0.1

Type RM Length L Ch R = 1 ,11924   ,407,407,407
BEGIN DESCRIPTION:
WIRE BRANCH 24.0
END DESCRIPTION:
XS GIS Cut Line= 3
      3713349.62     10761110.18      3712949.61     10761510.19
      3712549.61     10761660.19
#Sta/Elev= 30
  4445.4  459.61    4502  455.26  4516.1  453.61  4530.3  452.81  4558.6  449.67
  4572.7   449.1  4586.8  447.44    4601   446.7  4700.2  437.72  4742.4  432.71
  4770.7  431.16  4784.8  428.77    4796  428.21  4798.7  427.71    4802  428.21
  4809.7  428.21  5191.8  428.21  5197.1  429.86  5211.2  430.15    5222  430.16
  5227.4  431.54  5235.4  428.21  5318.5  428.21  5331.5  429.46  5352.9   433.2
  5362.7   433.9    5368  436.09  5392.9   441.1  5416.9  443.43  5438.3  444.69
#Mann= 7 ,-1 , 0
  4445.4     .12       0  4700.2     .16       0    4796    .033       0
    4802     .16       0  4809.7     .05       0  5211.2     .16       0
  5318.5     .05       0
Bank Sta=4796,4802
XS Rating Curve= 0 ,0
Exp/Cntr=0.3,0.1

Type RM Length L Ch R = 1 ,11517   ,171,171,171
BEGIN DESCRIPTION:
WIRE BRANCH 23.0
END DESCRIPTION:
XS GIS Cut Line= 2
      3713064.71     10760738.31      3712263.65     10761700.63
#Sta/Elev= 30
  4364.1  457.31  4368.7  456.27  4414.9  452.84  4461.1  449.37  4518.4  449.36
  4524.9  443.34  4532.7  448.89  4539.2  442.45  4561.3  440.43  4574.7  437.81
  4631.6  432.12  4639.4  430.97  4642.9  428.21  4645.7  427.71  4648.9  428.21
  5264.3  428.21  5291.7  432.05    5306  438.18  5313.8   438.3  5320.3   441.4
  5334.6  440.55  5342.4  436.49  5355.4  434.87  5384.1  434.71  5412.7  437.13
  5420.5   439.6  5427.1  443.23  5455.7  443.81  5519.5  447.17  5616.2  449.19
#Mann= 4 ,-1 , 0
  4364.1     .12       0  4414.9     .05       0  4642.9    .033       0
  4648.9     .05       0
Bank Sta=4642.9,4648.9
XS Rating Curve= 0 ,0
Exp/Cntr=0.3,0.1

Type RM Length L Ch R = 1 ,11346   ,57,57,57
BEGIN DESCRIPTION:
Mapping XS bc94c489
END DESCRIPTION:
XS GIS Cut Line= 3
      3712940.38     10760617.63      3712221.62     10761487.43
      3712221.62     10761643.69
#Sta/Elev= 30
  4363.6  455.61  4408.2  453.32  4451.2  447.84    4560  440.88  4572.4  440.56
  4593.2  437.75  4600.4  438.22  4661.9  428.21  4664.6  427.71  4667.9  428.21
  4929.6  428.21  5052.8  428.21    5225  428.21  5232.8  431.71  5247.2  432.82
  5253.7  431.18  5296.7  431.18  5317.5  431.38  5331.8  433.45  5346.2  430.87
  5374.8  431.23  5417.7  433.81  5424.3  435.32    5453  438.11  5459.5  437.89
  5467.3   439.4  5594.7  443.82  5614.7  444.72  5624.7  446.38  5648.2  447.11
#Mann= 6 ,-1 , 0
  4363.6     .12       0    4560     .05       0  4661.9     .07       0
  4667.9     .05       0  4929.6     .07       0  5052.8     .05       0
Bank Sta=4661.9,4667.9
XS Rating Curve= 0 ,0
Exp/Cntr=0.3,0.1

Type RM Length L Ch R = 1 ,11289   ,73,73,73
BEGIN DESCRIPTION:
Mapping XS 0261191a
END DESCRIPTION:
XS GIS Cut Line= 3
      3712836.18      10760635.9      3712164.33     10761487.43
      3712187.51     10761636.78
#Sta/Elev= 30
  4452.5  447.62  4538.3  440.66    4618  436.14  4666.5  432.89  4684.2  433.41
  4739.2  433.55  4852.2  433.81  4860.3  433.52  4981.5  434.12  5020.3  433.86
  5065.8  433.88  5072.1  432.72  5080.2  433.85  5144.3  433.71  5150.7  432.54
  5165.1     434  5200.4   432.7  5272.6  433.83    5279  432.45  5293.4  433.82
  5397.6  430.74  5400.3  430.24  5403.6  430.74  5450.6   432.2  5500.3  438.04
    5542  438.36  5590.5  440.99  5599.9  440.15    5605  441.41  5688.3  445.66
#Mann= 10 ,-1 , 0
  4452.5     .12       0    4618     .05       0  4684.2     .12       0
  4739.2     .05       0  4852.2     .12       0  4860.3     .05       0
  4981.5     .07       0  5020.3     .05       0  5397.6     .07       0
  5403.6     .05       0
Bank Sta=5397.6,5403.6
XS Rating Curve= 0 ,0
Exp/Cntr=0.3,0.1

Type RM Length L Ch R = 1 ,11216   ,247,247,247
BEGIN DESCRIPTION:
Mapping XS 557cc8b2
END DESCRIPTION:
XS GIS Cut Line= 2
      3712745.05     10760635.88      3712047.17     10761529.07
#Sta/Elev= 30
  4528.6  440.57  4671.4  431.84  4721.1  427.63  4770.9  420.37  4841.4  414.71
  4884.8  415.88  4891.2  412.77  4913.8  412.97  4917.1  410.53  4919.9  410.03
  4923.1  410.53  4930.7  413.01  4949.1  414.01  4955.4  411.92  4963.5   414.7
  4969.9  411.51    4978  412.75  4984.3     411  4998.8  414.54  5019.6  412.58
  5048.5  416.31  5054.9  413.32    5063  415.14  5113.5   416.7  5172.2  420.65
  5355.1  429.45  5419.3   430.9  5425.7  428.77  5584.6   433.1  5662.1  439.37
#Mann= 7 ,-1 , 0
  4528.6     .12       0  4917.1     .03       0  4923.1     .12       0
  4930.7     .05       0  5113.5     .12       0  5172.2     .05       0
  5584.6     .16       0
Bank Sta=4917.1,4923.1
XS Rating Curve= 0 ,0
Exp/Cntr=0.3,0.1

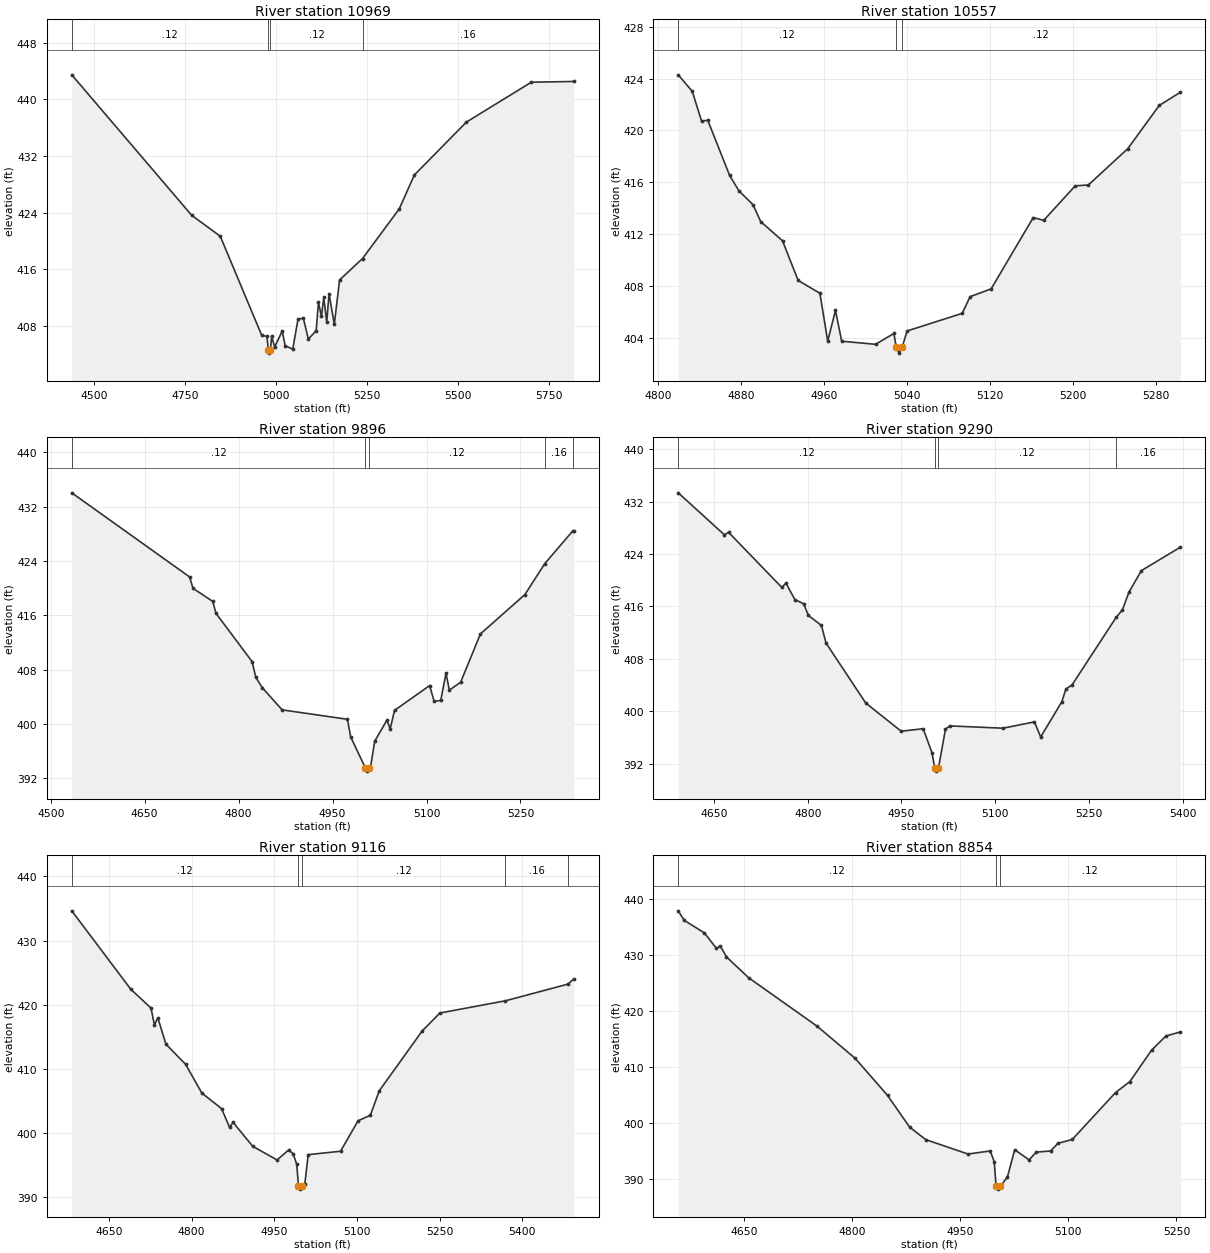
Type RM Length L Ch R = 1 ,10969   ,412,412,412
BEGIN DESCRIPTION:
WIRE BRANCH 22.0
END DESCRIPTION:
XS GIS Cut Line= 2
       3712606.4     10760415.37      3711763.61     10761507.87
#Sta/Elev= 30
  4438.2  443.47  4767.5  423.64  4846.3  420.67  4960.4  406.65  4974.7  406.53
  4978.2  404.66    4981  404.16  4984.2  404.66  4987.5  406.58  4995.7  405.02
  5016.5  407.28  5024.7  405.21  5045.5  404.72    5060  408.95  5074.5  409.12
  5088.4  406.14  5109.9  407.35  5116.2  411.32  5124.4  409.35  5130.7  412.04
  5138.9  408.52  5145.2  412.56  5159.7  408.21  5174.2   414.5  5237.3  417.52
  5338.1  424.53  5379.8  429.33  5522.9   436.8  5701.3  442.43    5818  442.53
#Mann= 4 ,-1 , 0
  4438.2     .12       0  4978.2     .07       0  4984.2     .12       0
  5237.3     .16       0
Bank Sta=4978.2,4984.2
XS Rating Curve= 0 ,0
Exp/Cntr=0.3,0.1

Type RM Length L Ch R = 1 ,10557   ,661,661,661
BEGIN DESCRIPTION:
WIRE BRANCH 21.0
END DESCRIPTION:
XS GIS Cut Line= 3
       3711999.6     10760560.21      3711899.61     10760710.19
      3711949.61      10761010.2
#Sta/Elev= 30
  4819.2  424.29  4832.7  423.02  4841.7  420.72  4847.7  420.78  4868.8  416.52
  4877.8  415.33  4891.3  414.27  4898.8  412.96  4919.8  411.48  4934.9  408.42
  4955.9  407.43  4963.4  403.73  4970.9  406.11  4976.9  403.73  5009.6  403.49
  5027.3  404.33  5029.4  403.31  5032.2  402.81  5035.4  403.31    5040  404.52
  5093.2  405.88  5100.8  407.17  5121.1  407.77  5161.7  413.27  5171.8  413.06
  5202.2  415.72  5214.9  415.79  5252.9  418.59  5283.3  421.93  5303.6  422.94
#Mann= 3 ,-1 , 0
  4819.2     .12       0  5029.4     .07       0  5035.4     .12       0
Bank Sta=5029.4,5035.4
XS Rating Curve= 0 ,0
Exp/Cntr=0.3,0.1

Type RM Length L Ch R = 1 ,9896    ,606,606,606
BEGIN DESCRIPTION:
WIRE BRANCH 20.0
END DESCRIPTION:
XS GIS Cut Line= 2
       3711546.5     10760141.91      3711290.41     10760901.51
#Sta/Elev= 30
  4533.6  434.05  4721.7  421.65  4727.2  419.97  4758.6  418.05  4763.9  416.28
  4821.6  409.16  4827.3  406.88  4837.8  405.32  4869.5  402.06  4973.7  400.67
    4979  398.05  5002.2  393.53    5005  393.03  5008.2  393.53  5010.5  393.55
  5017.2  397.43  5036.7  400.53    5042  399.27  5048.9  401.98  5104.9  405.64
  5112.2  403.31  5122.7  403.45  5131.1  407.48  5136.4  404.97  5154.4  406.13
  5186.1  413.26  5257.1  419.06  5288.8  423.62  5333.5  428.43  5335.2  428.43
#Mann= 5 ,-1 , 0
  4533.6     .12       0  5002.2     .07       0  5008.2     .12       0
  5288.8     .16       0  5333.5     .05       0
Bank Sta=5002.2,5008.2
XS Rating Curve= 0 ,0
Exp/Cntr=0.3,0.1

Type RM Length L Ch R = 1 ,9290    ,174,174,174
BEGIN DESCRIPTION:
WIRE BRANCH 19.0
END DESCRIPTION:
XS GIS Cut Line= 3
      3711264.33     10759951.01      3710921.49     10760267.82
      3710882.42     10760602.04
#Sta/Elev= 30
  4592.8  433.33  4666.6  426.93  4673.4   427.3  4758.4  418.91  4765.2  419.53
  4779.4  417.05  4793.6   416.4  4800.9  414.64  4821.9  413.09  4829.3   410.4
  4892.8  401.26  4949.5  396.96  4984.7  397.34  4998.8  393.67  5003.2  391.37
    5006  390.87  5009.2  391.37  5020.4  397.28  5027.2  397.77  5112.3  397.42
  5162.7  398.38  5172.7  396.08  5206.5  401.45    5213  403.38  5223.1  404.05
  5293.3  414.31  5303.6  415.49  5313.7  418.13  5333.8  421.46  5396.1  425.03
#Mann= 4 ,-1 , 0
  4592.8     .12       0  5003.2     .07       0  5009.2     .12       0
  5293.3     .16       0
Bank Sta=5003.2,5009.2
XS Rating Curve= 0 ,0
Exp/Cntr=0.3,0.1

Type RM Length L Ch R = 1 ,9116    ,262,262,262
BEGIN DESCRIPTION:
WIRE BRANCH 18.0
END DESCRIPTION:
XS GIS Cut Line= 3
      3711216.66     10759838.11      3710808.64     10760128.93
      3710415.73     10760245.51
#Sta/Elev= 30
  4582.7  434.65  4689.6  422.45  4726.4   419.5  4732.7  416.87  4738.8  417.98
  4753.5  413.88  4789.2  410.74  4818.7  406.26  4854.4  403.84  4869.1   400.9
  4875.3   401.7  4910.9  397.97  4955.2  395.83  4976.1  397.39  4984.3   396.8
  4990.8  395.17    4994  391.79  4996.7  391.29    5000  391.79  5005.6  392.16
  5011.7  396.66  5070.3  397.19  5102.1  401.93  5124.5  402.81  5140.5   406.6
  5218.3  415.92  5250.6  418.73  5369.3  420.63  5482.8  423.23  5493.6  424.04
#Mann= 5 ,-1 , 0
  4582.7     .12       0    4994     .07       0    5000     .12       0
  5369.3     .16       0  5482.8     .12       0
Bank Sta=4994,5000
XS Rating Curve= 0 ,0
Exp/Cntr=0.3,0.1

Type RM Length L Ch R = 1 ,8854    ,468,468,468
BEGIN DESCRIPTION:
WIRE BRANCH 17.0
END DESCRIPTION:
XS GIS Cut Line= 3
      3711149.57     10759660.21      3710749.61     10759860.19
      3710499.58     10759860.19
#Sta/Elev= 30
  4558.2  437.91  4566.5  436.21  4594.5  433.96  4611.3  431.19  4616.8  431.57
  4625.2  429.67    4656  425.93    4751  417.27  4804.1  411.49  4848.8  404.89
  4879.6  399.19  4901.9  396.97  4960.6  394.39  4991.4  394.94    4997  393.05
  4999.6  388.61  5002.3  388.11  5005.6  388.61  5015.4  390.31  5025.4  395.16
  5045.4  393.35  5055.4  394.73  5075.4  394.94  5085.4   396.3  5105.4     397
  5165.4  405.38  5185.4  407.36  5215.4  412.96  5235.4  415.52  5255.4  416.23
#Mann= 3 ,-1 , 0
  4558.2     .12       0  4999.6     .07       0  5005.6     .12       0
Bank Sta=4999.6,5005.6
XS Rating Curve= 0 ,0
Exp/Cntr=0.3,0.1

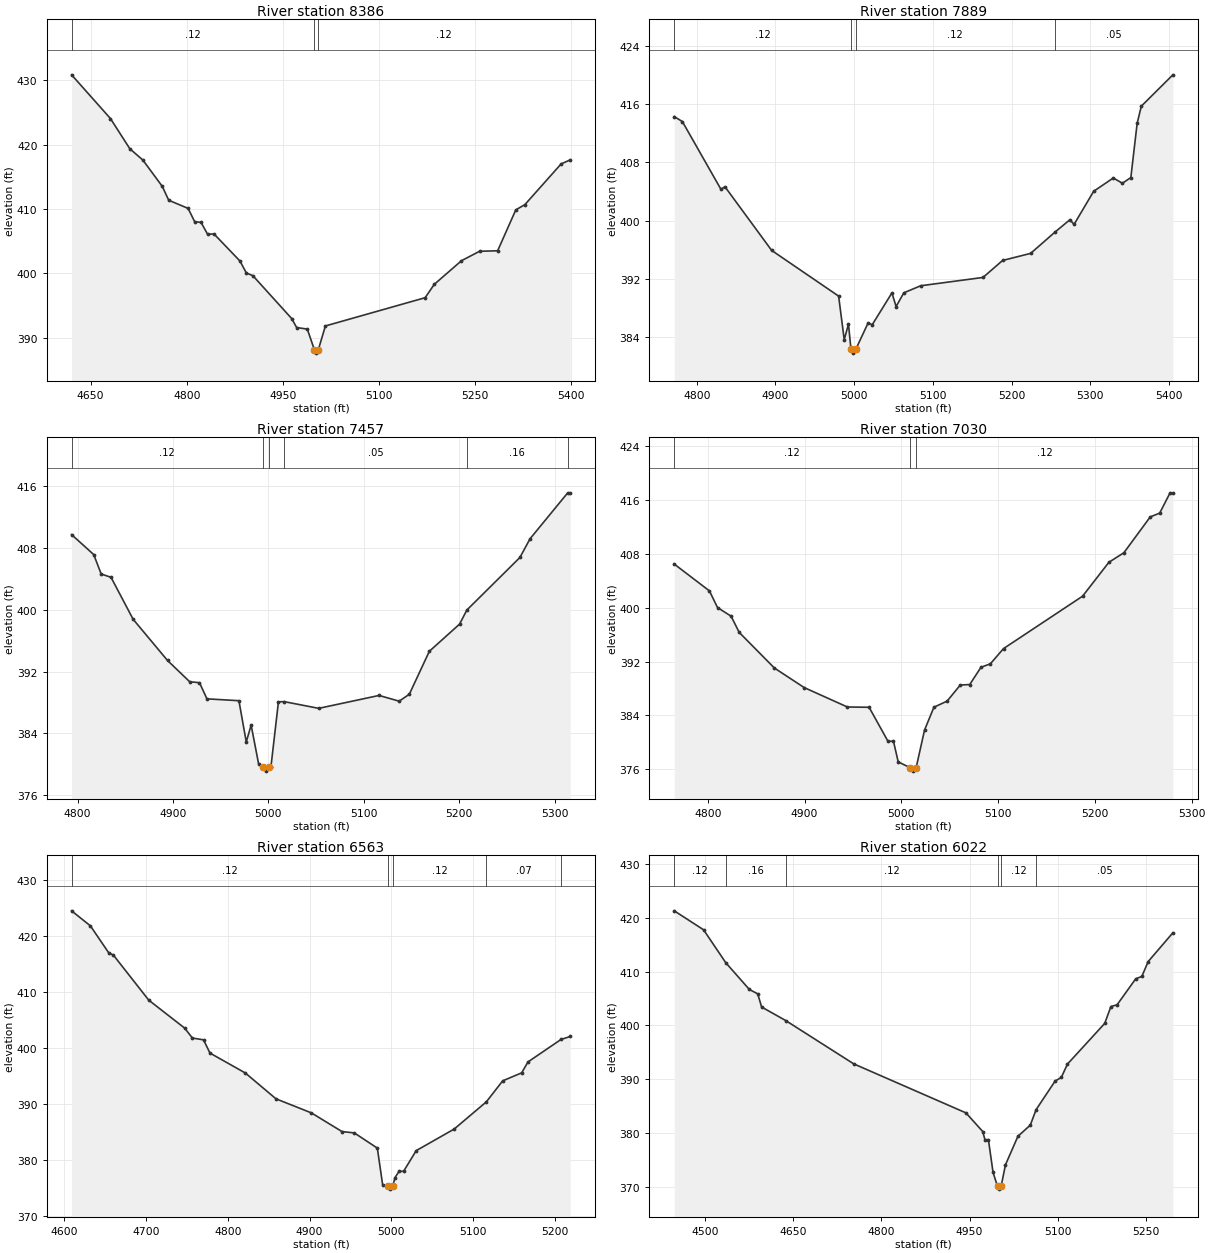
Type RM Length L Ch R = 1 ,8386    ,497,497,497
BEGIN DESCRIPTION:
WIRE BRANCH 16.0
END DESCRIPTION:
XS GIS Cut Line= 3
      3710999.57     10759360.19      3710649.61     10759410.19
       3710349.6      10759710.2
#Sta/Elev= 30
  4620.3  430.85  4680.9  424.06  4711.2  419.36  4731.4  417.62  4761.7  413.53
  4771.8  411.37  4802.1   410.1  4812.2  408.05  4822.3  407.92  4832.4  406.09
  4842.5  406.13  4882.9  401.93    4893  400.06  4903.1  399.65  4963.7  392.98
  4971.3   391.6    4988  391.35  4999.1  388.12  5001.9  387.62  5005.1  388.12
  5016.2  391.84  5171.8  396.23    5186   398.3  5228.4  401.97  5256.7  403.44
  5284.9  403.52  5313.2  409.87  5327.4  410.69  5383.9  417.01  5398.1  417.64
#Mann= 3 ,-1 , 0
  4620.3     .12       0  4999.1     .07       0  5005.1     .12       0
Bank Sta=4999.1,5005.1
XS Rating Curve= 0 ,0
Exp/Cntr=0.3,0.1

Type RM Length L Ch R = 1 ,7889    ,432,432,432
BEGIN DESCRIPTION:
WIRE BRANCH 15.0
END DESCRIPTION:
XS GIS Cut Line= 3
      3710749.61     10758910.19      3710549.61     10758960.19
      3710149.57     10758810.17
#Sta/Elev= 30
  4771.5  414.26  4781.8  413.58  4830.8  404.29  4835.9  404.64  4895.2  395.91
  4980.3  389.64  4987.4  383.67  4992.8  385.79    4996  382.32  4998.8  381.82
    5002  382.32  5017.7  385.95    5023  385.72    5048  390.08  5053.3  388.21
  5063.1  390.09  5084.5  391.06  5163.7   392.2  5188.6  394.53  5224.2   395.5
  5254.6  398.37    5274  400.11  5279.4  399.48  5304.3  404.02  5329.2  405.84
  5340.8  405.12  5351.5   405.9  5359.5  413.33  5364.8  415.69  5404.9  419.99
#Mann= 4 ,-1 , 0
  4771.5     .12       0    4996     .07       0    5002     .12       0
  5254.6     .05       0
Bank Sta=4996,5002
XS Rating Curve= 0 ,0
Exp/Cntr=0.3,0.1

Type RM Length L Ch R = 1 ,7457    ,427,427,427
BEGIN DESCRIPTION:
WIRE BRANCH 14.0
END DESCRIPTION:
XS GIS Cut Line= 3
      3710699.64      10758610.2      3710499.61     10758560.19
      3710199.62     10758660.18
#Sta/Elev= 30
  4793.8  409.73    4817  407.14  4824.8  404.63  4835.1   404.2  4858.3  398.76
  4894.3  393.43  4917.5  390.68  4927.8  390.55  4935.6  388.46  4969.1  388.22
  4976.8  382.88  4981.9  385.06  4989.7  380.06  4994.4   379.6  4997.2   379.1
  5000.4   379.6  5002.6   379.6  5010.5  388.07  5016.5   388.1  5052.7  387.23
  5115.9   388.9    5137  388.16  5147.6  389.05  5168.6  394.62  5200.3  398.14
  5207.9  399.96  5263.5  406.77  5274.1  409.19  5313.6  415.14  5316.2  415.14
#Mann= 6 ,-1 , 0
  4793.8     .12       0  4994.4     .07       0  5000.4     .12       0
  5016.5     .05       0  5207.9     .16       0  5313.6     .12       0
Bank Sta=4994.4,5000.4
XS Rating Curve= 0 ,0
Exp/Cntr=0.3,0.1

Type RM Length L Ch R = 1 ,7030    ,467,467,467
BEGIN DESCRIPTION:
WIRE BRANCH 13.0
END DESCRIPTION:
XS GIS Cut Line= 3
      3710499.62     10758110.18      3710299.61     10758210.19
      3710049.58     10758360.21
#Sta/Elev= 30
  4765.4  406.49  4801.7  402.51  4810.1  400.03  4824.1  398.75  4832.5  396.34
  4868.8  391.05  4899.6  388.14  4944.3  385.25  4966.7  385.21  4986.2  380.16
  4991.9  380.16  4996.8  377.09  5009.3  376.22  5012.1  375.72  5015.3  376.22
    5024  381.82  5033.7  385.22  5047.3  386.12  5060.9  388.51  5070.7  388.59
  5082.3  391.15    5092  391.67  5105.6  393.93  5187.3  401.72  5214.5  406.76
    5230  408.18  5257.2   413.5    5267  414.07  5277.7  417.08  5280.6  417.08
#Mann= 3 ,-1 , 0
  4765.4     .12       0  5009.3     .07       0  5015.3     .12       0
Bank Sta=5009.3,5015.3
XS Rating Curve= 0 ,0
Exp/Cntr=0.3,0.1

Type RM Length L Ch R = 1 ,6563    ,541,541,541
BEGIN DESCRIPTION:
WIRE BRANCH 12.0
END DESCRIPTION:
XS GIS Cut Line= 3
       3710449.6      10757660.2      3710099.61     10757860.19
      3709899.56      10757910.2
#Sta/Elev= 30
  4609.2  424.52  4632.2  421.83  4654.5  417.03  4660.3   416.6  4703.5  408.55
  4747.4  403.55  4756.8  401.78  4770.4  401.46  4778.3  399.09  4821.5  395.53
    4859  390.91  4902.2   388.4  4939.6  385.06  4954.7  384.82  4982.8   382.1
  4989.3  375.55  4995.6  375.27  4998.4  374.77  5001.6  375.27  5004.4  376.84
  5009.4  377.96  5014.9  377.96  5030.3  381.65  5076.7  385.51    5116  390.37
    5136  394.13  5159.2  395.56  5166.9  397.51  5207.2  401.52  5218.5  402.06
#Mann= 5 ,-1 , 0
  4609.2     .12       0  4995.6     .07       0  5001.6     .12       0
    5116     .07       0  5207.2     .12       0
Bank Sta=4995.6,5001.6
XS Rating Curve= 0 ,0
Exp/Cntr=0.3,0.1

Type RM Length L Ch R = 1 ,6022    ,458,458,458
BEGIN DESCRIPTION:
WIRE BRANCH 11.0
END DESCRIPTION:
XS GIS Cut Line= 3
      3710199.61     10757160.19      3709849.61     10757560.19
      3709549.64     10757660.18
#Sta/Elev= 30
  4447.9  421.35  4497.7  417.82  4535.6  411.67  4575.6   406.7  4589.8  405.89
  4596.4  403.44  4637.3  400.92    4753  392.85  4943.8  383.72  4972.3  380.25
  4976.1  378.72    4982  378.72  4989.9  372.62  4997.5  370.02  5000.2  369.52
  5003.5  370.02    5011  374.05  5032.1  379.35  5053.2  381.44  5063.1  384.33
  5095.4  389.65  5105.9  390.32  5116.4  392.81  5179.7  400.38  5190.2  403.51
  5200.8  403.86  5232.4  408.69  5242.9  409.14  5253.5  411.89  5295.6  417.26
#Mann= 6 ,-1 , 0
  4447.9     .12       0  4535.6     .16       0  4637.3     .12       0
  4997.5     .07       0  5003.5     .12       0  5063.1     .05       0
Bank Sta=4997.5,5003.5
XS Rating Curve= 0 ,0
Exp/Cntr=0.3,0.1