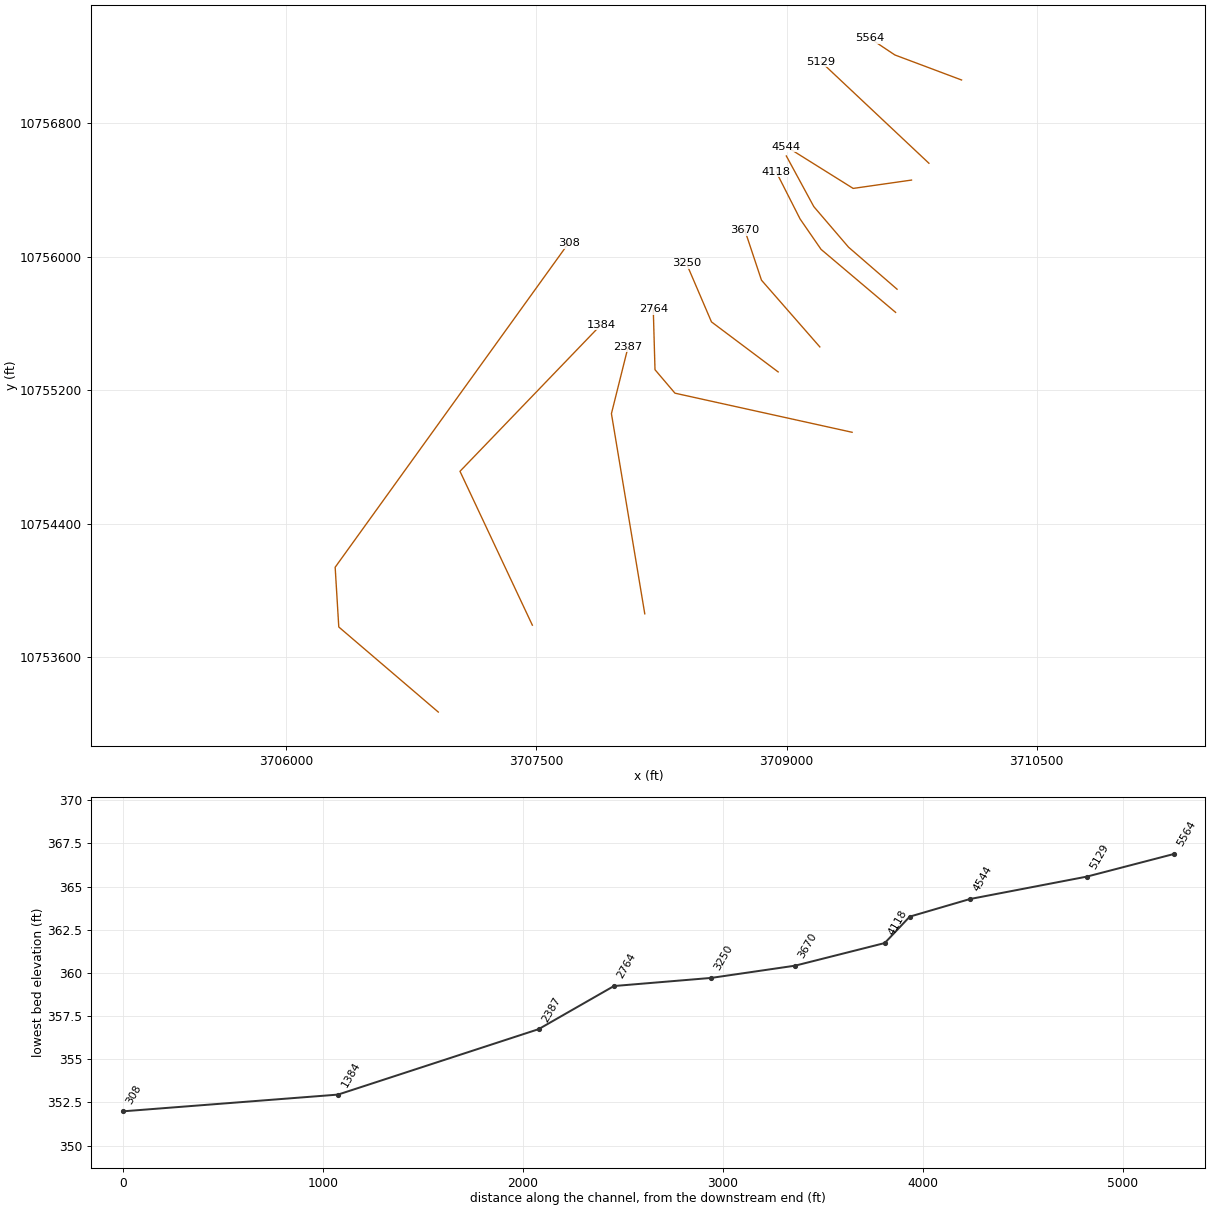
HEC-RAS study WIRE BRANCH.prj: WIRE BRANCH Base Level Engineering

--- WIRE BRANCH.g01 (geometry) --- (continued)

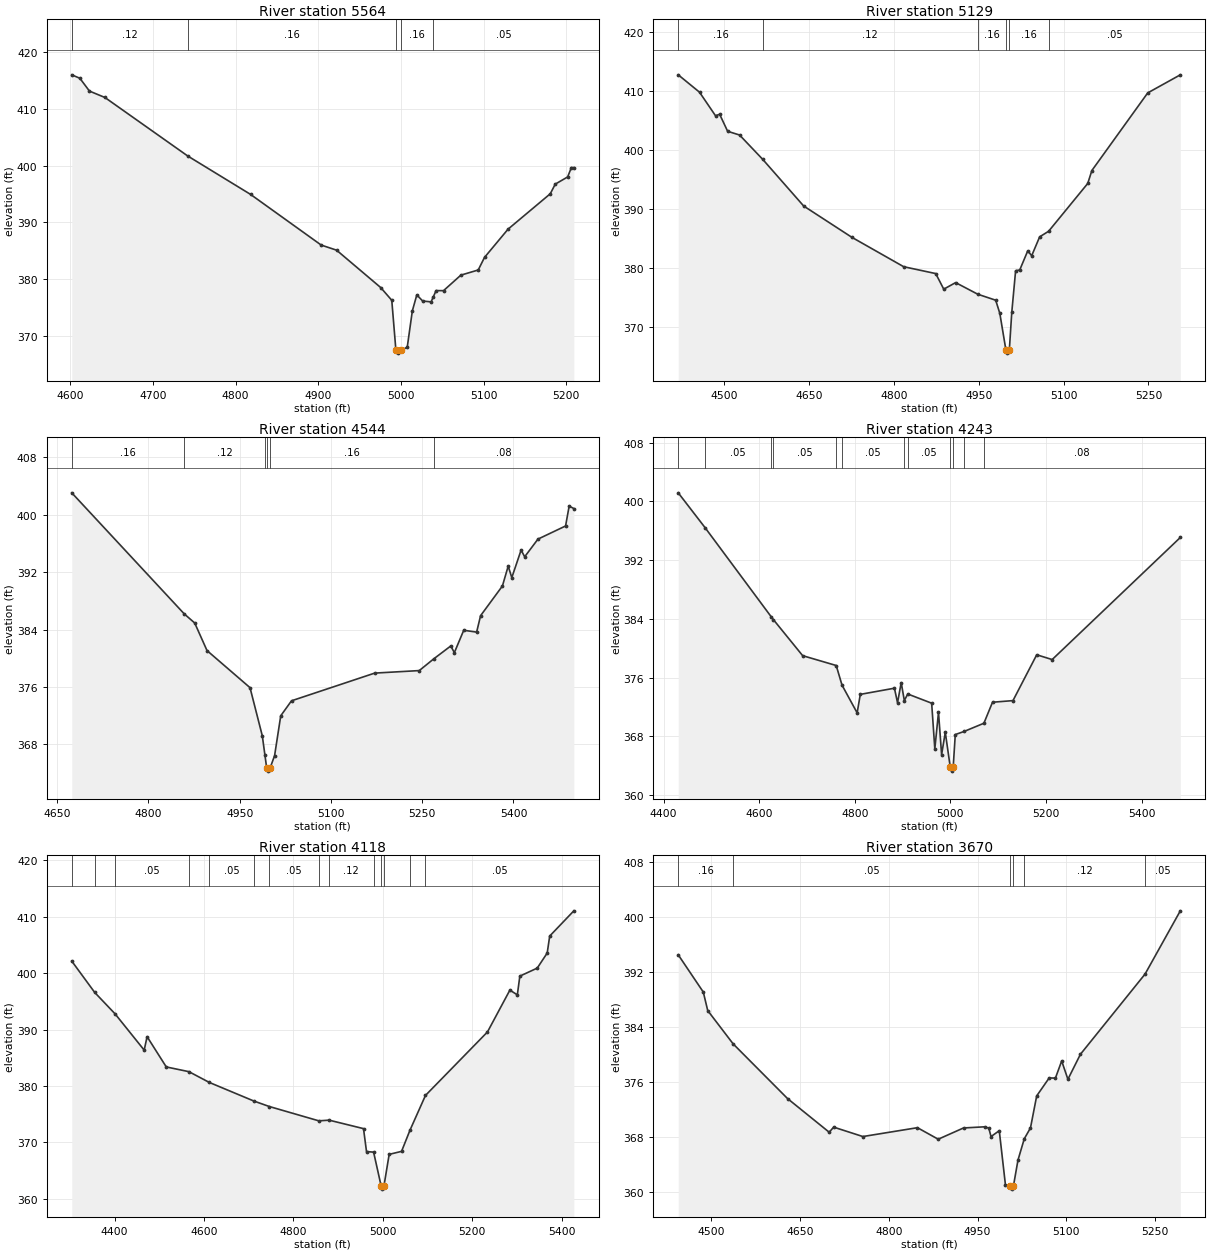
Type RM Length L Ch R = 1 ,5564    ,435,435,435
BEGIN DESCRIPTION:
WIRE BRANCH 10.0
END DESCRIPTION:
XS GIS Cut Line= 3
      3710049.65     10757060.17      3709649.61     10757210.19
      3709499.63     10757310.18
#Sta/Elev= 30
  4601.7  416.03  4611.5  415.42  4623.1  413.16  4641.8  412.03    4742   401.7
    4818  394.92  4903.5  385.97  4922.1  385.07  4975.5  378.47  4988.9  376.22
  4993.9  367.39  4996.7  366.89  4999.9  367.39  5007.6  367.92  5013.8  374.36
  5019.2  377.17  5026.3  376.09  5036.5  375.94  5038.9  376.74  5042.5  377.93
  5051.5  377.92  5072.5  380.66  5093.5  381.57  5101.1  383.79  5129.6  388.78
  5180.7  395.03  5186.7  396.73  5201.7     398  5206.2  399.65  5209.2  399.65
#Mann= 5 ,-1 , 0
  4601.7     .12       0    4742     .16       0  4993.9     .07       0
  4999.9     .16       0  5038.9     .05       0
Bank Sta=4993.9,4999.9
XS Rating Curve= 0 ,0
Exp/Cntr=0.3,0.1

Type RM Length L Ch R = 1 ,5129    ,585,585,585
BEGIN DESCRIPTION:
WIRE BRANCH 9.0
END DESCRIPTION:
XS GIS Cut Line= 2
      3709853.81     10756561.19       3709207.1     10757168.84
#Sta/Elev= 30
    4419   412.7  4456.6  409.76  4484.9  405.77  4492.2  406.02  4506.3  403.14
  4527.4  402.51  4568.3  398.39  4640.7  390.49  4725.7   385.2  4817.5  380.21
  4874.1  379.05  4888.3  376.41  4909.3  377.52  4948.5  375.55  4980.1  374.54
  4987.4  372.31  4998.2  366.08  5000.9  365.58  5004.2  366.08  5008.5  372.47
  5015.3  379.53  5022.6  379.66  5036.8  382.91  5043.7  382.07  5057.8  385.27
  5073.6  386.21  5142.8  394.31  5150.1   396.5  5248.8  409.64  5306.4   412.7
#Mann= 6 ,-1 , 0
    4419     .16       0  4568.3     .12       0  4948.5     .16       0
  4998.2     .07       0  5004.2     .16       0  5073.6     .05       0
Bank Sta=4998.2,5004.2
XS Rating Curve= 0 ,0
Exp/Cntr=0.3,0.1

Type RM Length L Ch R = 1 ,4544    ,301,301,301
BEGIN DESCRIPTION:
WIRE BRANCH 8.0
END DESCRIPTION:
XS GIS Cut Line= 3
      3709749.63     10756460.19      3709399.61     10756410.19
      3708999.59      10756660.2
#Sta/Elev= 30
  4673.9  403.06  4858.9  386.18    4876  384.92  4896.2  381.08  4966.9  375.91
  4987.1   369.2  4991.4  366.52  4994.2  364.78  4996.9  364.28  5000.2  364.78
  5007.3  366.44  5017.4  371.99  5035.1  374.08  5171.9  377.94  5245.1  378.29
  5268.7  379.91  5296.9  381.72  5302.8  380.79  5318.2  383.91  5339.4  383.65
  5345.9  385.94  5381.8  390.08  5391.3  392.85  5397.2  391.24  5412.5  395.08
  5418.4  394.15  5440.2  396.61  5485.6  398.44  5491.5  401.21  5499.2  400.87
#Mann= 6 ,-1 , 0
  4673.9     .16       0  4858.9     .12       0  4991.4     .16       0
  4994.2     .07       0  5000.2     .16       0  5268.7     .08       0
Bank Sta=4994.2,5000.2
XS Rating Curve= 0 ,0
Exp/Cntr=0.3,0.1

Type RM Length L Ch R = 1 ,4243    ,125,125,125
BEGIN DESCRIPTION:
Mapping XS 167e9e53
END DESCRIPTION:
XS GIS Cut Line= 4
      3709662.79     10755806.03      3709372.01     10756057.75
      3709163.67     10756300.81      3708998.76      10756604.6
#Sta/Elev= 30
  4430.6  401.15  4486.6  396.42  4625.6  384.23  4629.9  383.87  4690.9  378.98
  4761.1  377.64  4773.3  374.96  4804.9  371.19  4811.5  373.71  4882.9  374.55
  4889.4  372.57  4897.1  375.31  4903.6  372.87  4910.8  373.76  4960.8  372.51
  4967.4  366.28  4975.1  371.27  4981.6   365.5  4989.3  368.55  4999.8  363.76
  5002.6  363.26  5005.8  363.76  5010.2  368.24  5028.6  368.66  5070.1  369.78
  5088.1  372.64  5130.9  372.86  5180.6   379.1  5212.9  378.45    5481  395.07
#Mann= 12 ,-1 , 0
  4430.6     .08       0  4486.6     .05       0  4625.6     .08       0
  4629.9     .05       0  4761.1     .08       0  4773.3     .05       0
  4903.6     .12       0  4910.8     .05       0  4999.8     .04       0
  5005.8     .05       0  5028.6     .16       0  5070.1     .08       0
Bank Sta=4999.8,5005.8
XS Rating Curve= 0 ,0
Exp/Cntr=0.3,0.1

Type RM Length L Ch R = 1 ,4118    ,448,448,448
BEGIN DESCRIPTION:
WIRE BRANCH 7.0
END DESCRIPTION:
XS GIS Cut Line= 4
      3709654.16      10755667.1      3709207.08     10756044.73
      3709081.21     10756227.02        3708938.      10756509.1
#Sta/Elev= 30
  4304.1  402.13  4355.4  396.58  4400.9  392.79  4466.1  386.36  4472.6  388.74
  4515.5  383.38  4566.2  382.54  4611.9  380.63  4711.4  377.34  4745.9  376.37
  4856.7  373.83  4879.8  373.95  4956.7  372.45  4963.4  368.39  4979.3  368.28
  4996.3  362.23    4999  361.73  5002.3  362.23  5014.1  367.89  5041.8  368.42
  5060.8   372.2  5095.3  378.33    5234  389.58  5284.1  396.99  5300.8  396.15
  5306.4  399.47  5345.3  400.89  5367.6  403.56  5373.2  406.57  5427.2  411.04
#Mann= 14 ,-1 , 0
  4304.1     .05       0  4355.4     .08       0  4400.9     .05       0
  4566.2     .08       0  4611.9     .05       0  4711.4     .08       0
  4745.9     .05       0  4856.7     .08       0  4879.8     .12       0
  4979.3     .08       0  4996.3     .07       0  5002.3     .08       0
  5060.8     .16       0  5095.3     .05       0
Bank Sta=4996.3,5002.3
XS Rating Curve= 0 ,0
Exp/Cntr=0.3,0.1

Type RM Length L Ch R = 1 ,3670    ,420,420,420
BEGIN DESCRIPTION:
WIRE BRANCH 6.0
END DESCRIPTION:
XS GIS Cut Line= 3
      3709199.62     10755460.17      3708849.61     10755860.19
      3708749.59     10756160.23
#Sta/Elev= 30
  4444.5  394.55  4486.8  389.13  4494.3  386.43  4537.2  381.58  4629.1  373.61
  4699.4  368.71    4707  369.45  4756.3  368.08  4848.4  369.37  4883.5  367.69
  4926.2  369.33  4962.3   369.5  4968.9   369.3  4972.7  368.08  4986.6  368.93
  4997.1  360.97  5004.6  360.92  5007.4  360.42  5010.6  360.92  5018.2  364.65
  5028.8  367.75  5039.3  369.34  5049.8     374  5070.9  376.62  5081.4  376.59
    5092  379.09  5102.5  376.42  5123.6  380.06  5232.8  391.75  5292.3  400.96
#Mann= 6 ,-1 , 0
  4444.5     .16       0  4537.2     .05       0  5004.6     .03       0
  5010.6     .05       0  5028.8     .12       0  5232.8     .05       0
Bank Sta=5004.6,5010.6
XS Rating Curve= 0 ,0
Exp/Cntr=0.3,0.1

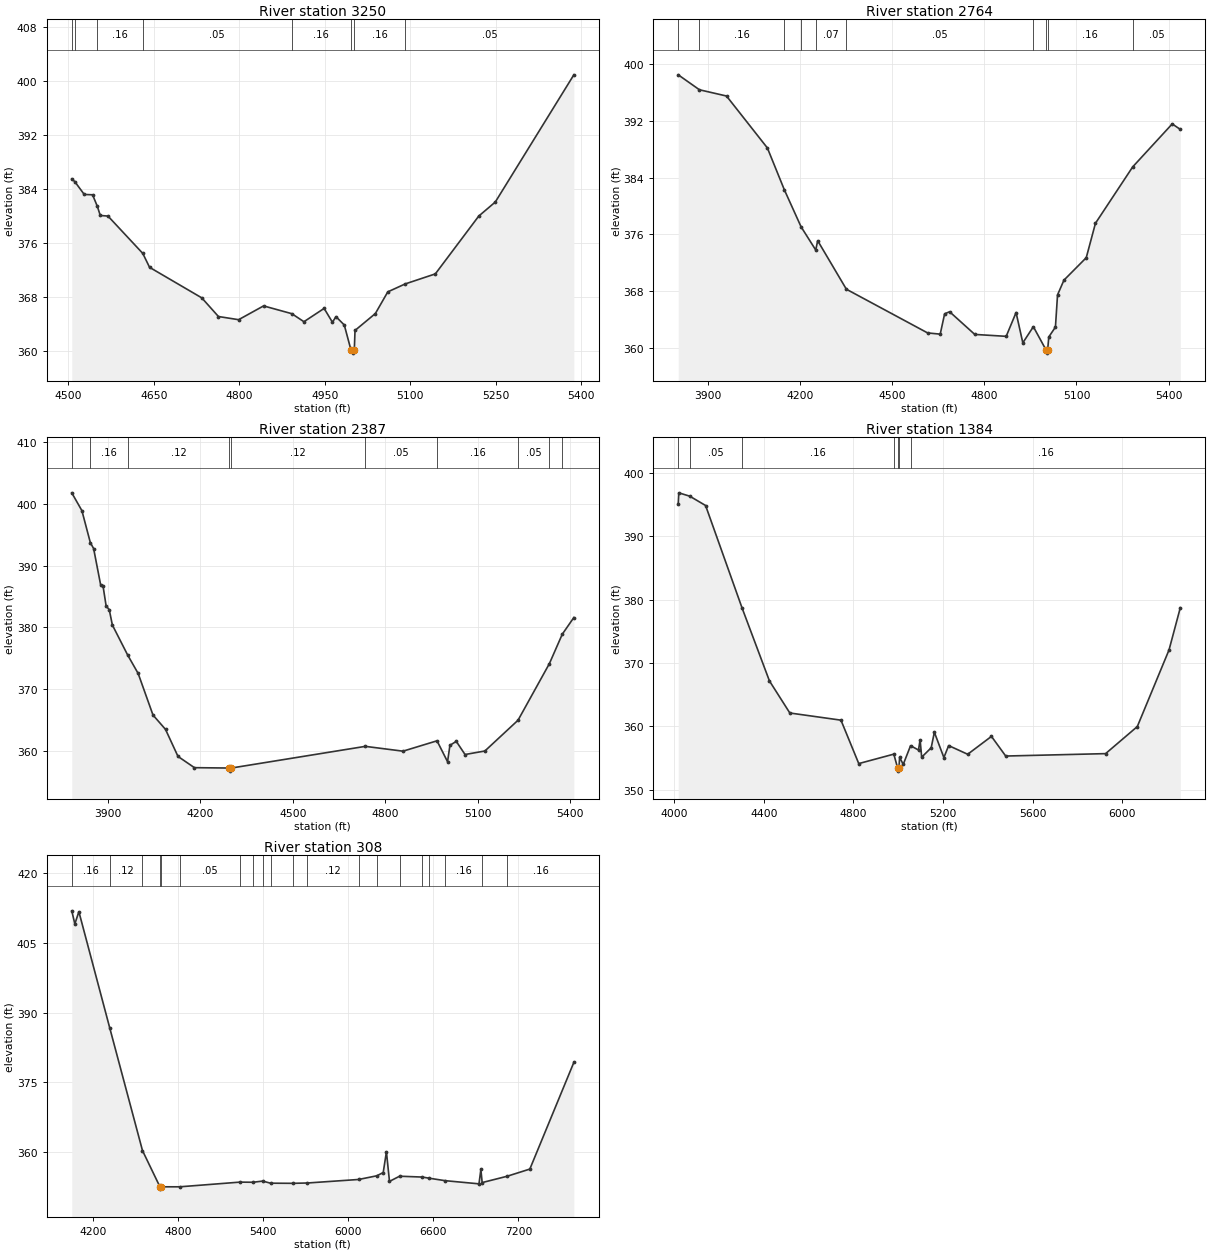
Type RM Length L Ch R = 1 ,3250    ,486,486,486
BEGIN DESCRIPTION:
WIRE BRANCH 5.0
END DESCRIPTION:
XS GIS Cut Line= 3
      3708949.61     10755310.19      3708549.61     10755610.19
      3708399.61      10755960.2
#Sta/Elev= 30
  4505.9   385.5  4511.2   385.1  4527.8   383.2  4542.4  383.15  4550.8  381.43
  4555.9  380.09  4569.4     380  4630.5  374.47  4642.4  372.41    4734  367.89
  4763.2  365.13  4798.6  364.66  4842.4   366.7  4891.9  365.55  4913.2  364.36
  4948.6  366.33  4963.2  364.28  4969.4  365.11    4984  363.87  4995.6  360.21
  4998.4  359.71  5001.6  360.21  5002.8  363.07  5038.5  365.57  5060.3  368.78
    5091  369.96  5143.7  371.44  5219.9     380  5248.9  382.08  5386.7  400.91
#Mann= 8 ,-1 , 0
  4505.9     .16       0  4511.2     .05       0  4550.8     .16       0
  4630.5     .05       0  4891.9     .16       0  4995.6     .07       0
  5001.6     .16       0    5091     .05       0
Bank Sta=4995.6,5001.6
XS Rating Curve= 0 ,0
Exp/Cntr=0.3,0.1

Type RM Length L Ch R = 1 ,2764    ,377,377,377
BEGIN DESCRIPTION:
WIRE BRANCH 4.0
END DESCRIPTION:
XS GIS Cut Line= 4
      3709393.26     10754948.38      3708330.77     10755182.75
      3708210.98     10755323.38      3708200.61     10755686.57
#Sta/Elev= 30
  3802.3  398.52  3871.4  396.41  3959.6  395.53  4092.8   388.2  4148.1  382.29
  4202.6  377.07  4250.4  373.79  4256.7  375.11  4350.2  368.26    4615  362.09
    4656  361.92  4670.4  364.79  4686.7  365.08  4768.6  361.88    4871  361.61
  4903.2  364.97  4925.2  360.69  4959.5  362.97  5000.2  359.74  5002.9  359.24
  5006.2  359.74  5009.8  361.52  5031.5  362.92  5038.3  367.46  5059.2  369.54
  5131.9  372.71  5161.9  377.57  5283.3  385.53    5412  391.59  5438.4  390.82
#Mann= 10 ,-1 , 0
  3802.3     .05       0  3871.4     .16       0  4148.1     .05       0
  4202.6     .16       0  4250.4     .07       0  4350.2     .05       0
  4959.5     .16       0  5000.2     .07       0  5006.2     .16       0
  5283.3     .05       0
Bank Sta=5000.2,5006.2
XS Rating Curve= 0 ,0
Exp/Cntr=0.3,0.1

Type RM Length L Ch R = 1 ,2387    ,1003,1003,1003
BEGIN DESCRIPTION:
WIRE BRANCH 3.0
END DESCRIPTION:
XS GIS Cut Line= 3
       3708149.6     10753860.24      3707949.61     10755060.19
      3708049.61     10755460.17
#Sta/Elev= 30
  3782.9   401.8  3815.8  398.91  3843.1  393.74  3853.8  392.78  3876.6  386.89
  3884.2  386.76  3894.4  383.47  3904.5  382.88  3914.6   380.4  3964.3  375.53
  3998.3  372.55  4046.4  365.82    4087   363.5  4127.5  359.12  4180.8   357.3
  4294.4  357.24  4297.1  356.74  4300.4  357.24  4735.2  360.75  4857.5  359.97
  4967.8  361.65    5002  358.26  5009.7  360.92  5030.3  361.56  5058.7  359.43
  5123.1     360  5230.6  364.98  5332.3  374.14  5374.2  378.91  5411.7  381.61
#Mann= 10 ,-1 , 0
  3782.9     .05       0  3843.1     .16       0  3964.3     .12       0
  4294.4     .07       0  4300.4     .12       0  4735.2     .05       0
  4967.8     .16       0  5230.6     .05       0  5332.3     .16       0
  5374.2     .05       0
Bank Sta=4294.4,4300.4
XS Rating Curve= 0 ,0
Exp/Cntr=0.3,0.1

Type RM Length L Ch R = 1 ,1384    ,1076,1076,1076
BEGIN DESCRIPTION:
WIRE BRANCH 2.0
END DESCRIPTION:
XS GIS Cut Line= 3
      3707475.32      10753792.1      3707041.28     10754714.44
      3707887.62     10755593.33
#Sta/Elev= 30
  4018.8  395.09  4021.3  396.85  4070.2  396.32  4140.8  394.85  4303.3  378.71
  4425.6  367.18  4516.6  362.12  4744.6  360.99    4824  354.14  4980.4  355.63
  4997.3  353.45  5000.1  352.95  5003.3  353.45  5006.3  355.12  5022.4  354.01
  5055.1  356.96  5090.5  356.28  5097.7   357.9  5104.6  355.15  5147.1  356.63
  5161.2  359.09  5203.7  355.09    5225  356.98  5309.9  355.61  5415.9  358.43
  5479.5  355.33    5925  355.71  6066.5  359.98    6208  372.07  6258.3  378.73
#Mann= 7 ,-1 , 0
  4018.8     .16       0  4070.2     .05       0  4303.3     .16       0
  4980.4     .12       0  4997.3     .07       0  5003.3     .12       0
  5055.1     .16       0
Bank Sta=4997.3,5003.3
XS Rating Curve= 0 ,0
Exp/Cntr=0.3,0.1

Type RM Length L Ch R = 1 ,308     ,0,0,0
BEGIN DESCRIPTION:
WIRE BRANCH 1.0
END DESCRIPTION:
XS GIS Cut Line= 4
      3706911.09     10753271.27      3706314.28     10753781.28
      3706292.58     10754139.35      3707692.34     10756081.65
#Sta/Elev= 30
  4052.9  411.93  4074.5  409.11    4103  411.74  4321.3  386.61  4551.2  360.28
  4674.2  352.48  4676.9  351.98  4680.2  352.48  4814.2  352.48  5237.8  353.49
    5329  353.46  5398.5  353.71  5453.3  353.26  5610.6  353.23  5712.8   353.3
  6074.7  354.06    6202  354.85  6247.5  355.55  6270.1  360.02  6291.7  353.65
  6362.7  354.76  6523.4  354.58  6571.8  354.33  6684.1   353.8  6922.4  353.12
  6935.7  356.22  6944.7  353.39  7120.4  354.75  7280.7   356.3  7590.8  379.28
#Mann= 20 ,-1 , 0
  4052.9     .16       0  4321.3     .12       0  4551.2     .16       0
  4674.2    .033       0  4680.2     .16       0  4814.2     .05       0
  5237.8     .16       0    5329     .07       0  5398.5     .12       0
  5453.3     .07       0  5610.6     .05       0  5712.8     .12       0
  6074.7     .05       0    6202     .05       0  6362.7     .05       0
  6523.4     .16       0  6571.8     .05       0  6684.1     .16       0
  6944.7     .05       0  7120.4     .16       0
Bank Sta=4674.2,4680.2
XS Rating Curve= 0 ,0
Exp/Cntr=0.3,0.1

Chan Stop Cuts=-1
Use User Specified Reach Order=0
Composite Channel Slope=5