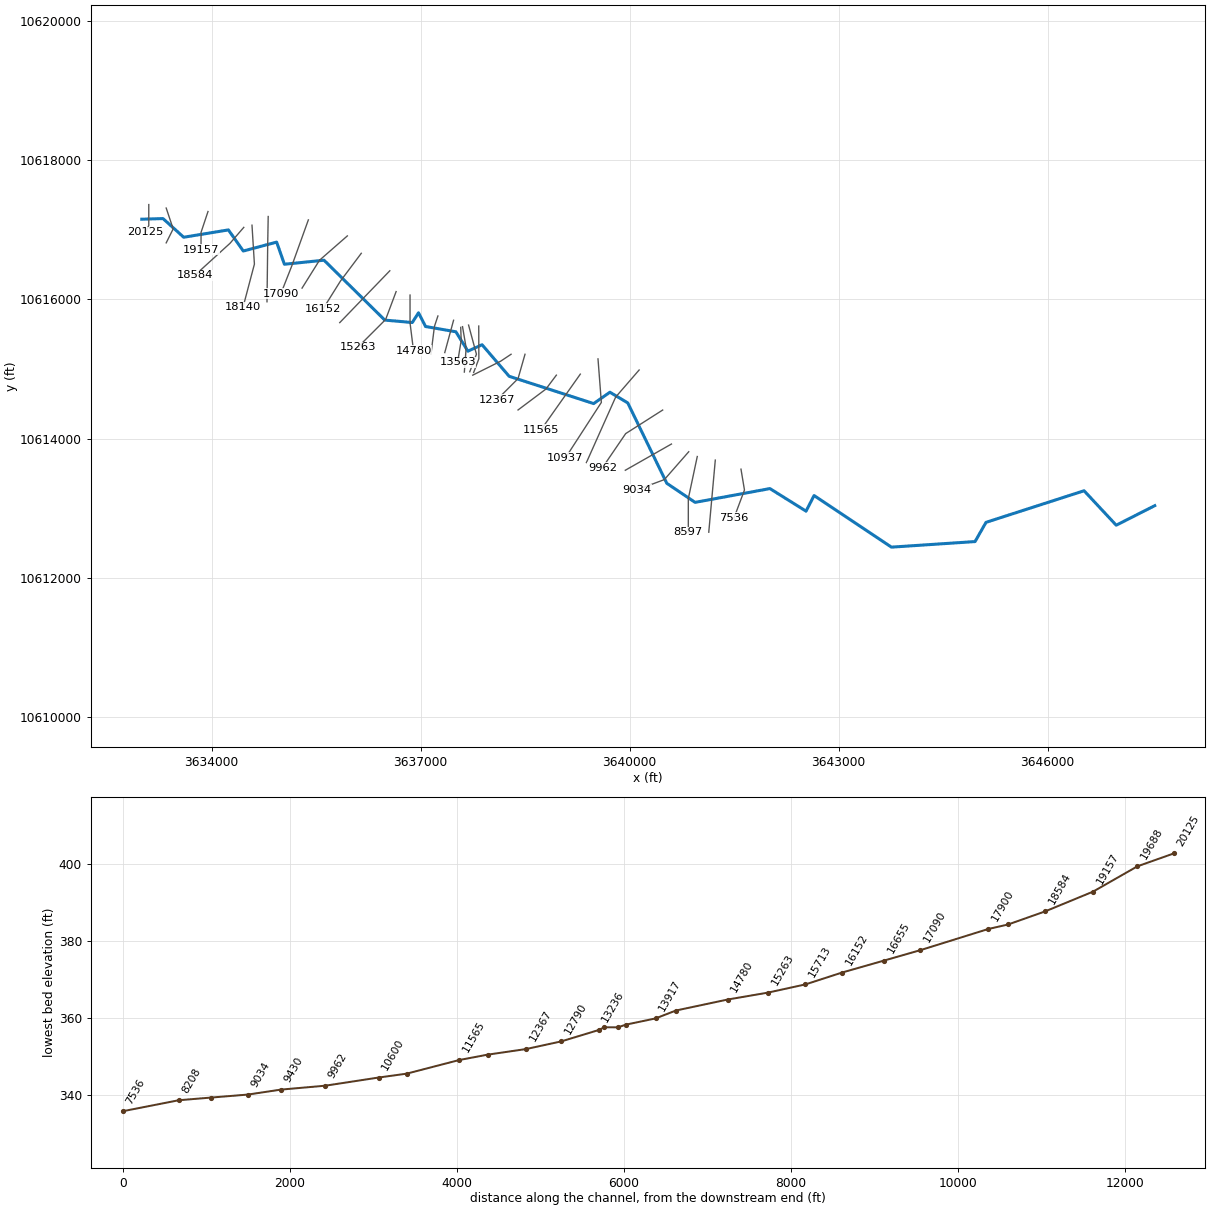
--- BATSMITH CREEK.prj (project) ---

Proj Title=BATSMITH CREEK Base Level Engineering
Current Plan=p01
Default Exp/Contr=0.3,0.1
English Units
Geom File=g01
Flow File=f01
Plan File=p01
Y Axis Title=Elevation
X Axis Title(PF)=Main Channel Distance
X Axis Title(XS)=Station
BEGIN DESCRIPTION:
BATSMITH CREEK
END DESCRIPTION:
DSS Export Rating Curves= 0
DSS Export Rating Curve Sorted= 0
DSS Export Volume Flow Curves= 0
DXF OffsetX= 0
DXF OffsetY= 0
DXF ScaleX= 1
DXF ScaleY= 10

--- BATSMITH CREEK.p01 (plan) ---

Plan Title=Multiple Run
Short Identifier=Multiple
Geom File=g01
Flow File=f01
Subcritical Flow
K Sum by GR= 0
Std Step Tol= 0.01
Critical Tol= 0.01
Num of Std Step Trials= 20
Max Error Tol= 0.3
Flow Tol Ratio= 0.001
Split Flow NTrial= 30
Split Flow Tol= 0.02
Split Flow Ratio= 0.02
Log Output Level= 0
Friction Slope Method= 1
Unsteady Friction Slope Method= 2
Unsteady Bridges Friction Slope Method= 1
Parabolic Critical Depth
Global Vel Dist=  1 , 1 , 1
Global Log Level= 0
CheckData=True
Encroach Param= -1, 0, 0, 0
BEGIN DESCRIPTION:
Multiple Run
END DESCRIPTION:

--- BATSMITH CREEK.f01 (steady flow) ---

Flow Title=Multiple
Program Version=4.10
Number of Profiles= 7
Profile Names=10-year,25-year,50-year,1pct_min,100-year,1pct_plu,500-year
River Rch & RM=BATSMITH CREEK,Reach-1         ,20125
    2072    2993    3792    3505    4740    6411    7384
River Rch & RM=BATSMITH CREEK,Reach-1         ,17090
    2467    3569    4526    4181    5655    7647    8801
River Rch & RM=BATSMITH CREEK,Reach-1         ,8597
    3037    4423    5635    5225    7066    9556   11090
Boundary for River Rch & Prof#=BATSMITH CREEK,Reach-1         , 1
Up Type= 0
Dn Type= 3
Dn Slope=0.004
Boundary for River Rch & Prof#=BATSMITH CREEK,Reach-1         , 2
Up Type= 0
Dn Type= 3
Dn Slope=0.004
Boundary for River Rch & Prof#=BATSMITH CREEK,Reach-1         , 3
Up Type= 0
Dn Type= 3
Dn Slope=0.004
Boundary for River Rch & Prof#=BATSMITH CREEK,Reach-1         , 4
Up Type= 0
Dn Type= 3
Dn Slope=0.004
Boundary for River Rch & Prof#=BATSMITH CREEK,Reach-1         , 5
Up Type= 0
Dn Type= 3
Dn Slope=0.004
Boundary for River Rch & Prof#=BATSMITH CREEK,Reach-1         , 6
Up Type= 0
Dn Type= 3
Dn Slope=0.004
Boundary for River Rch & Prof#=BATSMITH CREEK,Reach-1         , 7
Up Type= 0
Dn Type= 3
Dn Slope=0.004
DSS Import GetInterval= 0
DSS Import GetPeak= 0
DSS Import FillOption= 0

--- BATSMITH CREEK.g01 (geometry) ---

Geom Title=Existing Conditions
Program Version=4.10

River Reach=BATSMITH CREEK  ,Reach-1
Reach XY= 30
      3632999.61       10617150.      3633303.75       10617159.
       3633600.5       10616891.       3634242.5       10616996.
       3634456.5       10616693.      3634934.75       10616821.
      3635046.25       10616503.      3635614.75       10616561.
      3636487.25       10615701.      3636882.25       10615666.
      3636970.75       10615806.      3637072.25       10615609.
      3637507.25       10615533.      3637680.25       10615255.
       3637883.5       10615347.       3638271.5       10614894.
        3639485.       10614502.      3639718.75       10614665.
       3639974.5       10614512.      3640534.75       10613357.
      3640940.75       10613083.        3642015.       10613281.
      3642533.25       10612957.        3642649.       10613181.
        3643759.       10612440.       3644959.5       10612520.
       3645116.5       10612796.      3646524.25       10613250.
      3646985.25       10612755.      3647538.75       10613036.

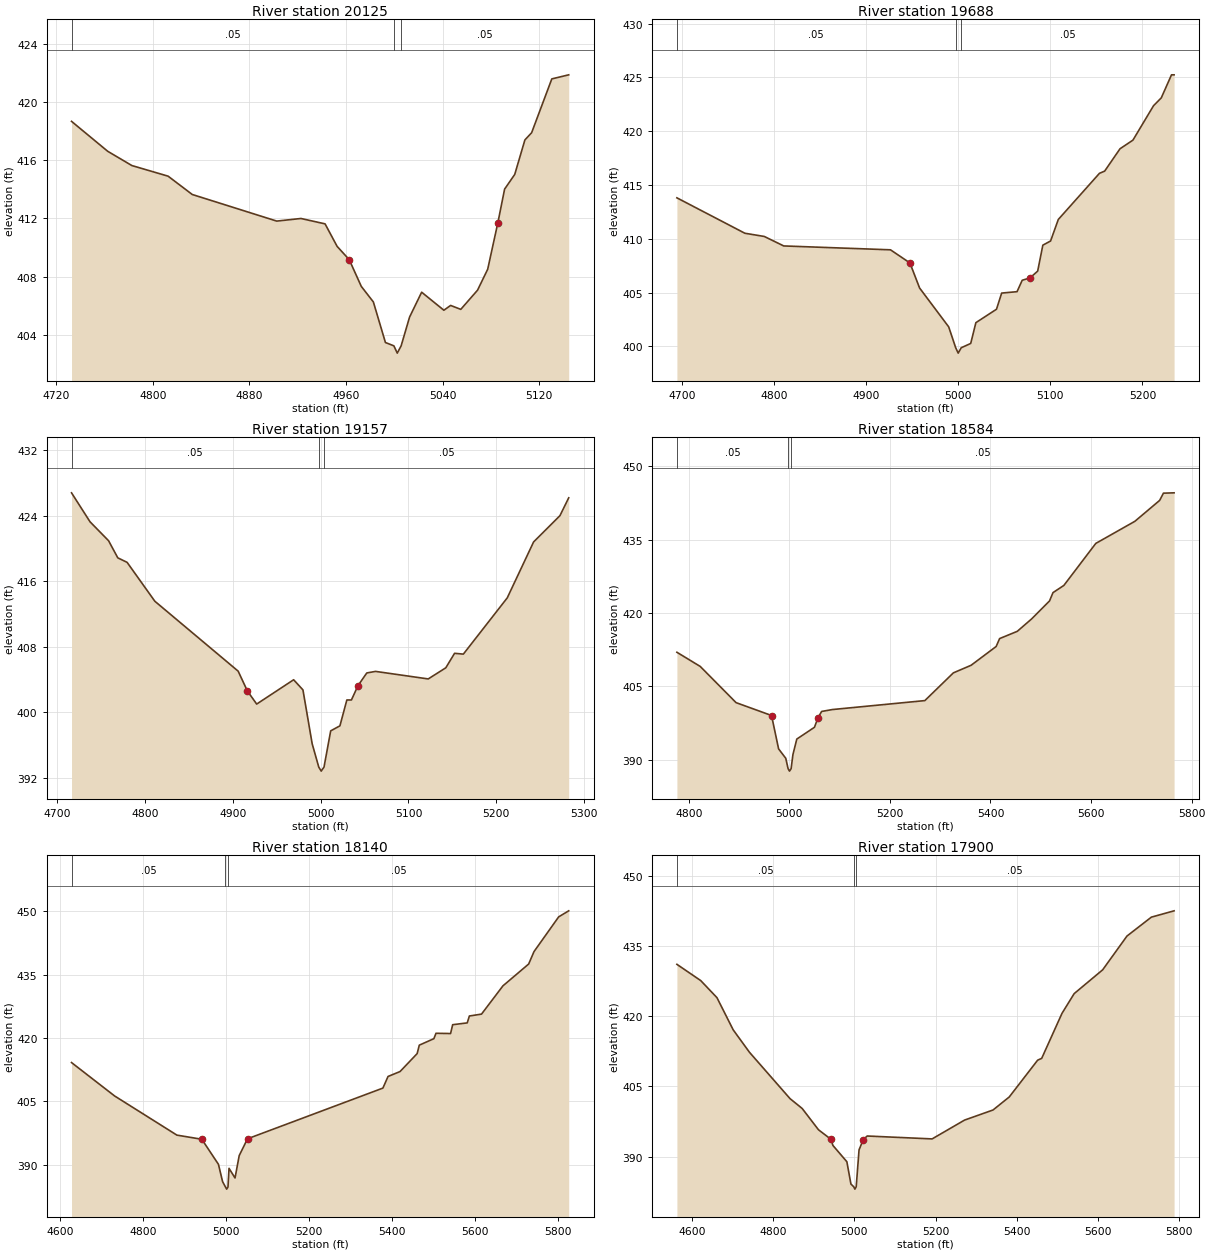
Type RM Length L Ch R = 1 ,20125   ,437,437,437
BEGIN DESCRIPTION:
BATSMITH CREEK 42.0
END DESCRIPTION:
XS GIS Cut Line= 3
      3633099.61      10617360.2      3633099.61     10617060.19
      3633049.61      10616960.2
#Sta/Elev= 30
  4732.6  418.68  4762.6  416.62  4782.6  415.64  4812.6  414.91  4832.6  413.65
  4902.6  411.82  4922.6     412  4942.6  411.63  4952.6  410.08  4962.6  409.17
  4972.6  407.33  4982.6  406.26  4992.6  403.47  4999.6  403.24  5002.4  402.74
  5005.6  403.24  5012.6  405.22  5022.6  406.93    5041  405.69  5046.6  406.02
    5055  405.75  5068.9  407.07  5077.3  408.51  5085.7   411.7  5091.3  414.02
  5099.7  415.03  5108.1   417.4  5113.7   417.9  5130.4   421.6  5144.4  421.88
#Mann= 3 ,-1 , 0
  4732.6     .05       0  4999.6     .03       0  5005.6     .05       0
Bank Sta=4962.6,5085.7
XS Rating Curve= 0 ,0
Exp/Cntr=0.3,0.1

Type RM Length L Ch R = 1 ,19688   ,531,531,531
BEGIN DESCRIPTION:
BATSMITH CREEK 41.0
END DESCRIPTION:
XS GIS Cut Line= 3
      3633349.61     10617310.19      3633449.61     10617010.19
      3633349.62     10616810.22
#Sta/Elev= 30
  4694.6  413.81  4768.4  410.52  4789.5  410.22  4810.6  409.34  4926.5  408.98
  4947.6  407.76  4958.1  405.43  4989.7  401.82  4997.3  399.88    5000  399.38
  5003.3  399.88  5013.6  400.28  5019.2  402.21  5041.6  403.46  5047.2  404.96
  5063.9  405.09  5069.5  406.15  5077.9  406.37  5086.3     407  5091.9  409.41
  5100.3   409.8  5108.7   411.8  5153.4  416.09    5159  416.29  5175.7  418.37
  5189.7  419.17  5212.1  422.37  5220.5   423.1  5231.6  425.24  5234.4  425.24
#Mann= 3 ,-1 , 0
  4694.6     .05       0  4997.3     .03       0  5003.3     .05       0
Bank Sta=4947.6,5077.9
XS Rating Curve= 0 ,0
Exp/Cntr=0.3,0.1

Type RM Length L Ch R = 1 ,19157   ,573,573,573
BEGIN DESCRIPTION:
BATSMITH CREEK 40.0
END DESCRIPTION:
XS GIS Cut Line= 3
      3633949.62     10617260.23      3633849.61     10616960.19
      3633849.61     10616710.16
#Sta/Elev= 30
  4716.2  426.79  4737.3  423.25  4758.4  420.94  4768.9  418.85  4779.5   418.3
  4811.1  413.55    4906  405.01  4916.5  402.59  4927.1  400.99  4969.2  403.96
  4979.8  402.72  4990.3  396.14  4997.8   393.3  5000.6   392.8  5003.8   393.3
  5011.4  397.72  5021.9  398.33  5029.8  401.49    5035  401.49  5042.5  403.24
  5052.5  404.79  5062.5  404.98  5122.5  404.06  5142.5  405.42  5152.5  407.19
  5162.5  407.09  5212.5  413.96  5242.5  420.79  5272.5     424  5282.5  426.18
#Mann= 3 ,-1 , 0
  4716.2     .05       0  4997.8     .03       0  5003.8     .05       0
Bank Sta=4916.5,5042.5
XS Rating Curve= 0 ,0
Exp/Cntr=0.3,0.1

Type RM Length L Ch R = 1 ,18584   ,444,444,444
BEGIN DESCRIPTION:
BATSMITH CREEK 39.0
END DESCRIPTION:
XS GIS Cut Line= 3
      3634462.99     10617032.63      3634265.06     10616803.45
       3633758.1     10616341.63
#Sta/Elev= 30
  4776.5  411.99  4822.9  409.09  4894.2  401.68  4964.7  399.05  4978.7  392.23
    4993  390.29  4997.6  388.17  5000.4  387.67  5003.6  388.17  5007.2  391.05
  5014.9  394.23    5050  396.64  5057.2  398.63  5064.3  399.88  5085.8  400.27
  5269.5   402.1  5326.3  407.78  5361.4  409.32  5411.3  413.17  5418.2  414.79
  5453.3  416.27  5481.7   418.8  5517.5   422.5  5524.3  424.19  5545.9  425.66
  5609.4  434.26  5687.1  438.78  5736.4  443.06  5743.9  444.54  5765.1  444.61
#Mann= 3 ,-1 , 0
  4776.5     .05       0  4997.6     .03       0  5003.6     .05       0
Bank Sta=4964.7,5057.2
XS Rating Curve= 0 ,0
Exp/Cntr=0.3,0.1

Type RM Length L Ch R = 1 ,18140   ,240,240,240
BEGIN DESCRIPTION:
BATSMITH CREEK 38.0
END DESCRIPTION:
XS GIS Cut Line= 3
      3634581.03     10617063.87      3634615.75     10616504.84
      3634452.57     10615886.83
#Sta/Elev= 30
  4627.5  414.21  4731.4  406.31  4881.7  397.04  4941.8  396.06  4981.9  390.13
  4991.9  386.03  4998.9  384.76  5001.7  384.26  5004.9  384.76  5007.4  389.18
  5021.9   386.9    5032   392.2    5052  396.17  5378.6  408.17    5391  410.92
    5420  412.09  5461.2  416.33  5466.4  418.33  5501.5  419.86  5506.7  421.14
  5541.8  421.08  5546.9  423.17    5582   423.6  5587.2  425.23  5616.5  425.68
  5668.2  432.37  5730.2  437.53  5743.1  440.47  5802.6  448.69  5826.8  450.12
#Mann= 3 ,-1 , 0
  4627.5     .05       0  4998.9     .03       0  5004.9     .05       0
Bank Sta=4941.8,5052
XS Rating Curve= 0 ,0
Exp/Cntr=0.3,0.1

Type RM Length L Ch R = 1 ,17900   ,810,810,810
BEGIN DESCRIPTION:
BATSMITH CREEK 37.0
END DESCRIPTION:
XS GIS Cut Line= 3
      3634813.67     10617188.83      3634806.73     10616803.45
      3634796.32     10615964.16
#Sta/Elev= 30
  4562.8  431.06  4621.5  427.59  4661.5  423.94  4701.5  417.07  4741.5  412.29
  4841.5  402.39  4871.5  400.28  4911.5  395.75  4941.5  393.76  4947.4  392.37
  4981.5  388.92  4991.5  384.16  4998.5  383.57  5001.3  383.07  5004.5  383.57
  5011.5  391.44  5021.5  393.57  5031.5  394.41  5191.5  393.79  5271.5  397.81
  5341.5  399.96  5381.5  402.74  5451.5   410.6  5461.5  410.99  5511.5   420.6
  5541.5  424.81  5611.6  429.88  5671.6   437.1  5731.6  441.13  5787.6  442.48
#Mann= 3 ,-1 , 0
  4562.8     .05       0  4998.5     .03       0  5004.5     .05       0
Bank Sta=4941.5,5021.5
XS Rating Curve= 0 ,0
Exp/Cntr=0.3,0.1

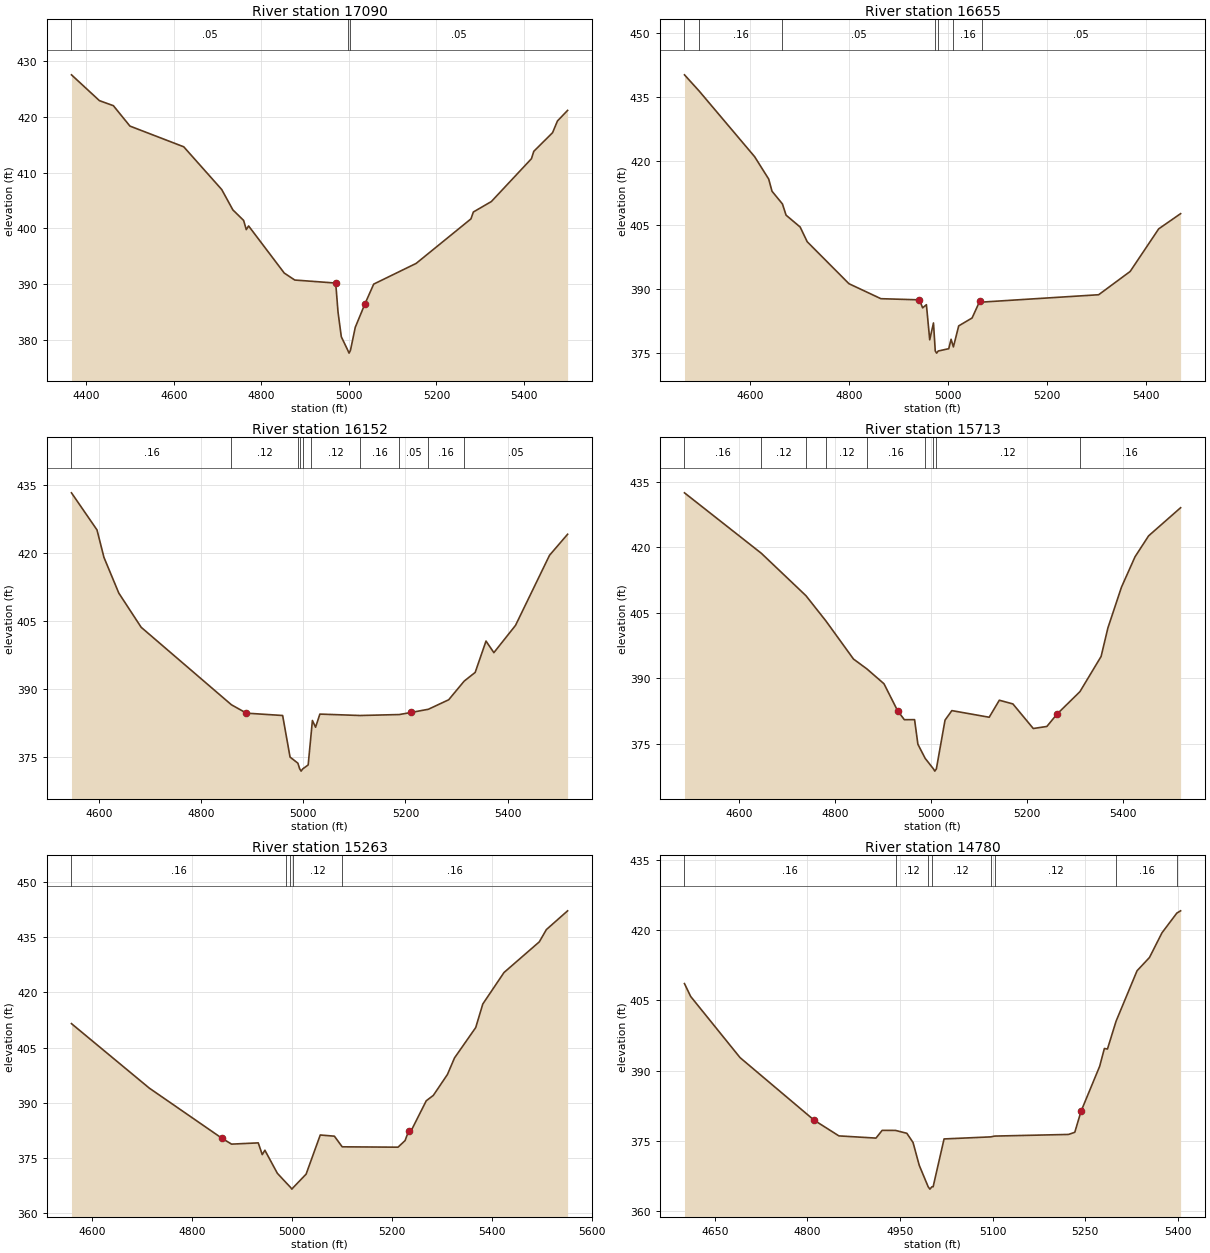
Type RM Length L Ch R = 1 ,17090   ,435,435,435
BEGIN DESCRIPTION:
BATSMITH CREEK 36.0
END DESCRIPTION:
XS GIS Cut Line= 3
      3635390.07     10617140.28      3635153.95       10616484.
       3634994.4      10616078.2
#Sta/Elev= 30
  4366.2  427.59  4430.1  422.95  4461.9  422.05  4499.8  418.38  4622.7  414.66
  4709.5  406.98  4734.9  403.33  4759.5  401.43  4765.6  399.78  4770.9  400.44
  4852.4  391.97  4876.4  390.72  4969.9  390.18  4975.2  384.97  4982.7  380.53
  4997.6  378.09  5000.4  377.59  5003.6  378.09  5014.6  382.23  5036.7  386.44
  5056.7  389.99  5153.7  393.71  5278.9  401.71  5284.3  402.94  5325.6  404.83
  5417.1  412.52  5422.4  413.84  5465.3  417.19  5476.6  419.31  5499.7   421.2
#Mann= 3 ,-1 , 0
  4366.2     .05       0  4997.6     .03       0  5003.6     .05       0
Bank Sta=4969.9,5036.7
XS Rating Curve= 0 ,0
Exp/Cntr=0.3,0.1

Type RM Length L Ch R = 1 ,16655   ,503,503,503
BEGIN DESCRIPTION:
BATSMITH CREEK 35.0
END DESCRIPTION:
XS GIS Cut Line= 3
      3635949.58     10616910.16      3635549.61     10616560.19
      3635299.59     10616160.16
#Sta/Elev= 30
  4467.4  440.27  4497.1  436.46  4609.3  421.03  4637.7  415.78  4644.4  412.92
  4665.5  409.93  4672.8   407.3  4701.3  404.51  4715.6  401.05    4800  391.19
  4864.6  387.67  4942.4   387.4    4949  385.52  4956.6  386.26  4963.3  378.01
  4970.9  381.97  4974.5  375.38  4977.3  374.88  4980.5  375.38  5001.8  375.92
  5006.5  378.14  5011.2  376.34  5021.9  381.28    5049  383.14  5064.3  387.06
  5068.7  386.87  5304.9   388.6  5368.6  394.07  5426.3  404.08  5470.6  407.65
#Mann= 7 ,-1 , 0
  4467.4     .05       0  4497.1     .16       0  4665.5     .05       0
  4974.5     .03       0  4980.5     .05       0  5011.2     .16       0
  5068.7     .05       0
Bank Sta=4942.4,5064.3
XS Rating Curve= 0 ,0
Exp/Cntr=0.3,0.1

Type RM Length L Ch R = 1 ,16152   ,439,439,439
BEGIN DESCRIPTION:
BATSMITH CREEK 34.0
END DESCRIPTION:
XS GIS Cut Line= 3
      3636149.62      10616660.2      3635849.61     10616260.19
      3635599.62      10615860.2
#Sta/Elev= 30
    4546  433.31    4596  425.11  4609.6  419.04  4638.7  411.14  4682.5  403.58
  4859.3  386.44  4888.7  384.59  4959.6  384.07  4974.1  374.88  4989.4  373.53
    4993  372.27  4995.8  371.77    4999  372.27  5009.6  373.14    5016  380.72
  5017.9  382.97  5024.1  381.48  5032.5  384.38  5111.4  384.07    5188  384.28
  5211.7  384.75    5245  385.45  5284.8  387.55  5315.1  391.67  5336.7   393.6
  5357.9  400.53  5373.3  397.97  5415.7     404  5482.3   419.5  5517.7  424.15
#Mann= 10 ,-1 , 0
    4546     .16       0  4859.3     .12       0  4989.4     .16       0
    4993     .07       0    4999     .16       0    5016     .12       0
  5111.4     .16       0    5188     .05       0    5245     .16       0
  5315.1     .05       0
Bank Sta=4888.7,5211.7
XS Rating Curve= 0 ,0
Exp/Cntr=0.3,0.1

Type RM Length L Ch R = 1 ,15713   ,450,450,450
BEGIN DESCRIPTION:
BATSMITH CREEK 33.0
END DESCRIPTION:
XS GIS Cut Line= 2
      3636559.03     10616409.12      3635840.66     10615664.72
#Sta/Elev= 30
  4485.4  432.42  4645.7  418.57  4738.7  408.86  4780.3  403.08  4837.8  394.35
  4865.9  392.08  4901.4  388.69  4929.7  382.54  4943.8  380.46  4965.2  380.47
  4972.1  374.84  4987.2  371.62  5004.6  369.18  5007.4  368.68  5010.6  369.18
  5028.7  380.36  5042.9  382.54  5120.8  381.02  5141.9  384.92  5170.2  384.07
  5212.7  378.44    5241  378.91  5262.2  381.74  5309.9  386.87  5354.1  394.94
  5368.3  401.48  5396.6  410.82  5424.9  417.78  5453.2  422.57  5519.9  429.01
#Mann= 9 ,-1 , 0
  4485.4     .16       0  4645.7     .12       0  4738.7     .16       0
  4780.3     .12       0  4865.9     .16       0  4987.2     .12       0
  5004.6     .07       0  5010.6     .12       0  5309.9     .16       0
Bank Sta=4929.7,5262.2
XS Rating Curve= 0 ,0
Exp/Cntr=0.3,0.1

Type RM Length L Ch R = 1 ,15263   ,483,483,483
BEGIN DESCRIPTION:
BATSMITH CREEK 32.0
END DESCRIPTION:
XS GIS Cut Line= 3
       3636649.6     10616110.17      3636499.61     10615710.19
      3636099.58     10615310.16
#Sta/Elev= 30
  4558.8  411.52  4714.5     394  4860.5  380.31  4879.2  378.77  4932.6  379.11
  4940.6  375.92  4945.9  377.11  4970.8  370.85  4987.3  368.44  4997.1  367.04
  4999.9  366.54  5003.1  367.04  5028.4  370.62  5056.7  381.25    5085  380.93
  5100.6  378.04  5212.3  377.94  5226.4  379.73  5233.5   382.3  5240.5  382.92
  5268.8  390.55    5283  392.02  5311.2   397.7  5325.4  402.21  5367.8  410.45
    5382  416.86  5424.4  425.41  5495.1  433.75  5509.2  437.08  5551.7  442.18
#Mann= 5 ,-1 , 0
  4558.8     .16       0  4987.3     .12       0  4997.1     .07       0
  5003.1     .12       0  5100.6     .16       0
Bank Sta=4860.5,5233.5
XS Rating Curve= 0 ,0
Exp/Cntr=0.3,0.1

Type RM Length L Ch R = 1 ,14780   ,618,618,618
BEGIN DESCRIPTION:
BATSMITH CREEK 31.0
END DESCRIPTION:
XS GIS Cut Line= 3
      3636849.61     10616060.21      3636849.61     10615660.19
      3636899.61     10615260.22
#Sta/Elev= 30
  4601.1   408.6  4611.1  405.86  4691.1   392.8  4811.1  379.44  4851.1   376.1
  4911.1  375.63  4921.1  377.28  4942.7  377.27  4961.1  376.65  4971.1  374.69
  4981.1  369.83  4995.6  365.24  4998.4  364.74  5001.6  365.24  5003.6  365.24
  5021.3  375.45  5096.8  375.89  5103.3  376.06  5222.8  376.41  5232.9  376.87
    5243  381.34  5273.2  390.96  5280.8  394.75  5285.8  394.64  5299.7  400.56
  5333.7  411.34  5353.8  414.17    5374  419.43  5398.1  423.65  5404.2  424.13
#Mann= 8 ,-1 , 0
  4601.1     .16       0  4942.7     .12       0  4995.6     .07       0
  5001.6     .12       0  5096.8     .16       0  5103.3     .12       0
  5299.7     .16       0  5398.1     .05       0
Bank Sta=4811.1,5243
XS Rating Curve= 0 ,0
Exp/Cntr=0.3,0.1

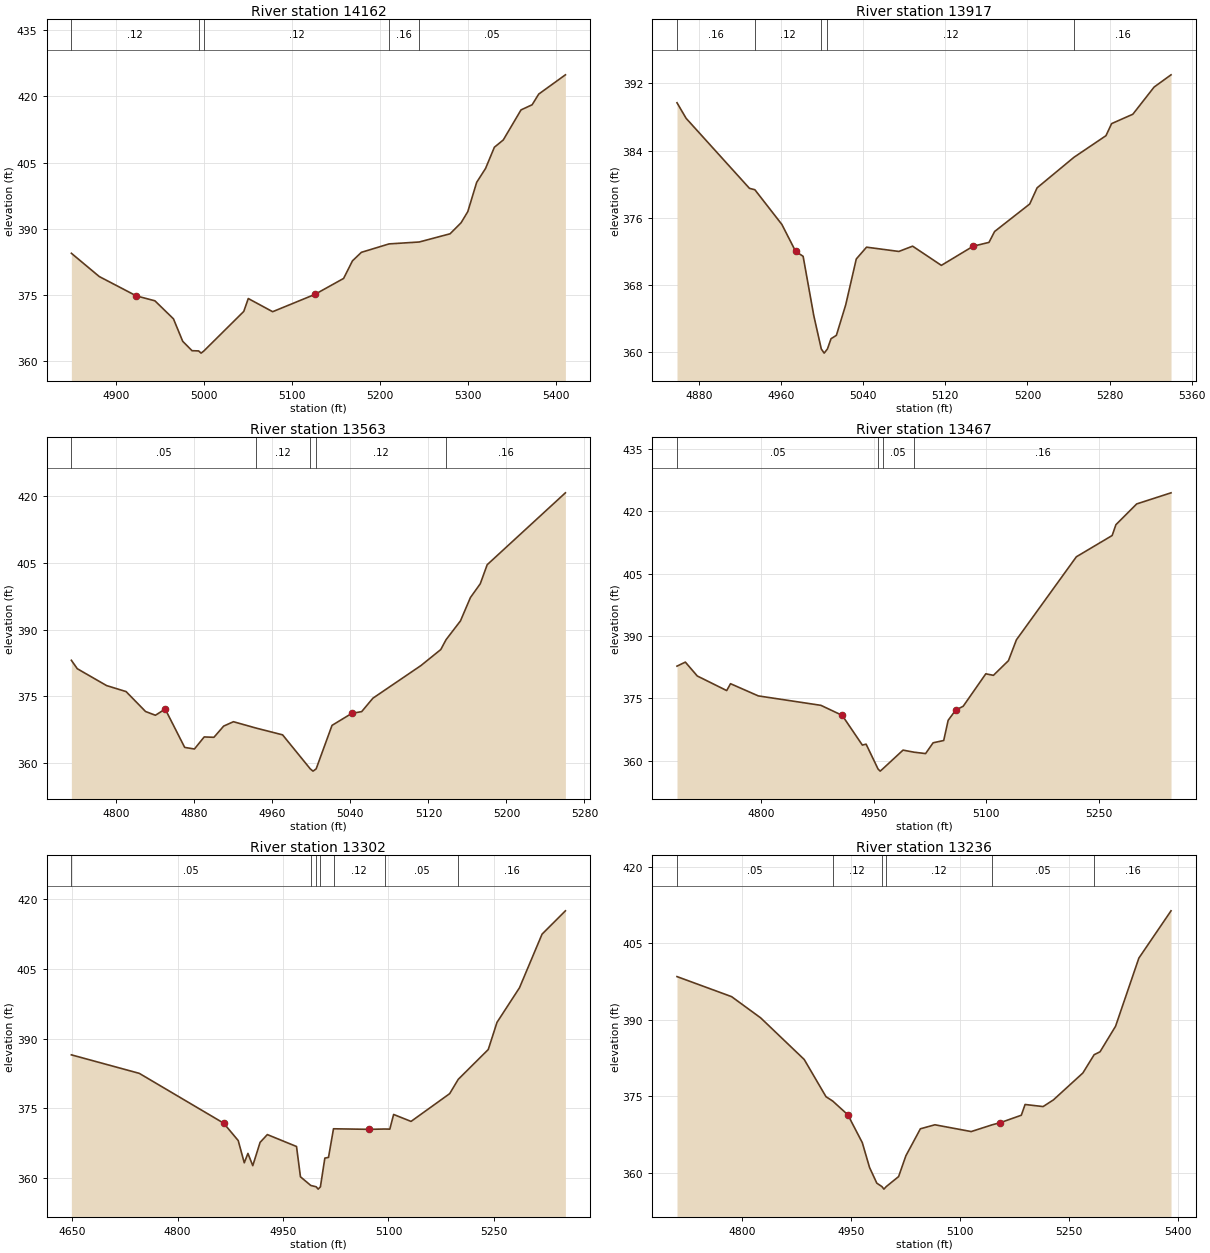
Type RM Length L Ch R = 1 ,14162   ,245,245,245
BEGIN DESCRIPTION:
BATSMITH CREEK 30.0
END DESCRIPTION:
XS GIS Cut Line= 3
      3637249.62     10615760.22      3637199.61     10615610.19
       3637149.6     10615210.15
#Sta/Elev= 30
  4849.4   384.5  4881.1  379.23  4923.2  374.85  4944.3  373.74  4965.4  369.65
  4975.9  364.57  4986.5  362.44    4994  362.39  4996.8  361.89    5000  362.39
  5045.3  371.34  5050.4  374.25  5078.1  371.27    5126  375.18  5158.7   378.8
  5168.8  382.79  5178.9  384.71  5210.4  386.62  5244.6  387.05  5279.7  388.91
  5292.2  391.41  5299.8  393.93  5309.9  400.56    5320  403.71    5330   408.5
  5340.1  410.15  5360.3  416.96  5372.9  418.12  5380.4  420.54  5410.7   424.9
#Mann= 5 ,-1 , 0
  4849.4     .12       0    4994     .07       0    5000     .12       0
  5210.4     .16       0  5244.6     .05       0
Bank Sta=4923.2,5126
XS Rating Curve= 0 ,0
Exp/Cntr=0.3,0.1

Type RM Length L Ch R = 1 ,13917   ,354,354,354
BEGIN DESCRIPTION:
BATSMITH CREEK 29.0
END DESCRIPTION:
XS GIS Cut Line= 2
      3637474.41     10615698.78      3637347.89      10615234.3
#Sta/Elev= 30
  4858.5   389.7  4867.4  387.84  4929.1  379.49  4934.4  379.32  4960.7  375.18
  4974.1  371.97  4981.4  371.38  4991.8   364.3  4999.1  360.33  5001.9  359.83
  5005.1  360.33  5008.6  361.55  5013.8  361.95  5022.9  365.59  5033.2  371.06
  5043.2  372.47  5074.7  371.96  5088.1  372.59  5116.1   370.3  5147.2  372.59
  5162.5  373.04    5168  374.34  5202.2  377.62  5209.4  379.55  5245.3  383.19
  5276.5  385.77    5282  387.21  5302.7  388.33  5323.4  391.57  5339.9  393.03
#Mann= 5 ,-1 , 0
  4858.5     .16       0  4934.4     .12       0  4999.1     .07       0
  5005.1     .12       0  5245.3     .16       0
Bank Sta=4974.1,5147.2
XS Rating Curve= 0 ,0
Exp/Cntr=0.3,0.1

Type RM Length L Ch R = 1 ,13563   ,96,96,96
BEGIN DESCRIPTION:
Mapping XS ecd5a18d
END DESCRIPTION:
XS GIS Cut Line= 3
      3637576.83     10615596.28      3637583.77     10615408.81
      3637531.89     10615094.06
#Sta/Elev= 30
  4753.9  383.12    4760  381.22    4790  377.44    4810  376.09    4830  371.61
  4840.1  370.77  4850.1  372.17  4870.1  363.55  4880.1  363.19  4890.1   365.9
  4900.1  365.82  4910.1  368.34  4920.1  369.32    4943  367.91  4970.5  366.37
  4998.9  358.72  5001.7  358.22  5004.9  358.72  5021.2   368.5  5041.5   371.2
  5051.6  371.59  5063.1   374.6  5112.4  381.94  5132.7  385.53  5138.1  387.74
  5152.9  391.97  5163.1  397.21  5173.2  400.31  5180.3  404.59  5260.5  420.74
#Mann= 5 ,-1 , 0
  4753.9     .05       0    4943     .12       0  4998.9     .07       0
  5004.9     .12       0  5138.1     .16       0
Bank Sta=4850.1,5041.5
XS Rating Curve= 0 ,0
Exp/Cntr=0.3,0.1

Type RM Length L Ch R = 1 ,13467   ,165,165,165
BEGIN DESCRIPTION:
BATSMITH CREEK 28.0
END DESCRIPTION:
XS GIS Cut Line= 4
      3637602.86     10615606.77      3637649.74     10615332.42
      3637651.48     10615256.03      3637628.96     10614954.61
#Sta/Elev= 30
  4688.5  382.75  4699.6  383.72  4715.5  380.38  4754.6  376.88  4759.7  378.53
  4796.6   375.6  4879.9  373.33  4908.2  370.92    4935  363.78    4940     364
  4955.9  358.02  4958.7  357.52  4961.9  358.02  4989.1  362.57  5003.7  362.07
  5019.1  361.74  5029.1  364.33  5043.2  364.88  5049.1  369.73  5059.1  372.18
  5069.1  373.11  5099.2  380.91  5109.3  380.54  5129.3  384.07  5139.9  389.08
  5219.6  409.03  5267.2  414.14  5272.2  416.74  5299.8  421.73  5345.5   424.4
#Mann= 4 ,-1 , 0
  4688.5     .05       0  4955.9     .04       0  4961.9     .05       0
  5003.7     .16       0
Bank Sta=4908.2,5059.1
XS Rating Curve= 0 ,0
Exp/Cntr=0.3,0.1

Type RM Length L Ch R = 1 ,13302   ,66,66,66
BEGIN DESCRIPTION:
Mapping XS 660ea902
END DESCRIPTION:
XS GIS Cut Line= 3
      3637689.67     10615629.32      3637802.52      10615210.9
      3637707.04     10614959.17
#Sta/Elev= 30
    4649  386.48  4745.6  382.49  4865.6  371.75  4886.3     368  4894.9  363.21
  4900.1  365.23    4907  362.59  4917.4  367.61  4927.7  369.29  4969.2  366.72
  4974.8  360.19  4989.5  358.32  4997.2  358.03    5000  357.53  5003.2  358.03
  5009.5  364.22  5014.7  364.37  5021.8  370.54  5072.8  370.42  5095.1  370.49
  5101.9  370.46  5107.3  373.63  5132.1  372.13    5187  378.11  5199.2   381.2
  5241.9  387.63  5254.3  393.48  5286.3  400.94  5318.4   412.5  5351.6  417.53
#Mann= 7 ,-1 , 0
    4649     .05       0  4989.5     .08       0  4997.2     .07       0
  5003.2     .08       0  5021.8     .12       0  5095.1     .05       0
  5199.2     .16       0
Bank Sta=4865.6,5072.8
XS Rating Curve= 0 ,0
Exp/Cntr=0.3,0.1

Type RM Length L Ch R = 1 ,13236   ,446,446,446
BEGIN DESCRIPTION:
Mapping XS 4f970281
END DESCRIPTION:
XS GIS Cut Line= 3
      3637835.51     10615615.42      3637837.24     10615144.92
      3637762.59     10614948.74
#Sta/Elev= 30
  4710.6  398.49  4785.8  394.56  4825.8   390.4  4885.8  382.24  4915.8  374.94
  4925.1  374.08  4945.8   371.4  4965.8  365.93  4975.8  361.05  4985.8  357.98
  4992.8  357.31  4995.6  356.81  4998.8  357.31  5015.8  359.27  5025.8  363.34
  5045.8  368.64  5065.8  369.43  5115.8   368.1  5144.8  369.43  5155.8  369.84
  5184.8   371.3    5190  373.41  5214.8     373    5229  374.31  5269.6  379.59
  5285.1  383.17  5293.2  383.74  5314.6  388.75  5346.7  402.12    5391  411.39
#Mann= 6 ,-1 , 0
  4710.6     .05       0  4925.1     .12       0  4992.8     .07       0
  4998.8     .12       0  5144.8     .05       0  5285.1     .16       0
Bank Sta=4945.8,5155.8
XS Rating Curve= 0 ,0
Exp/Cntr=0.3,0.1

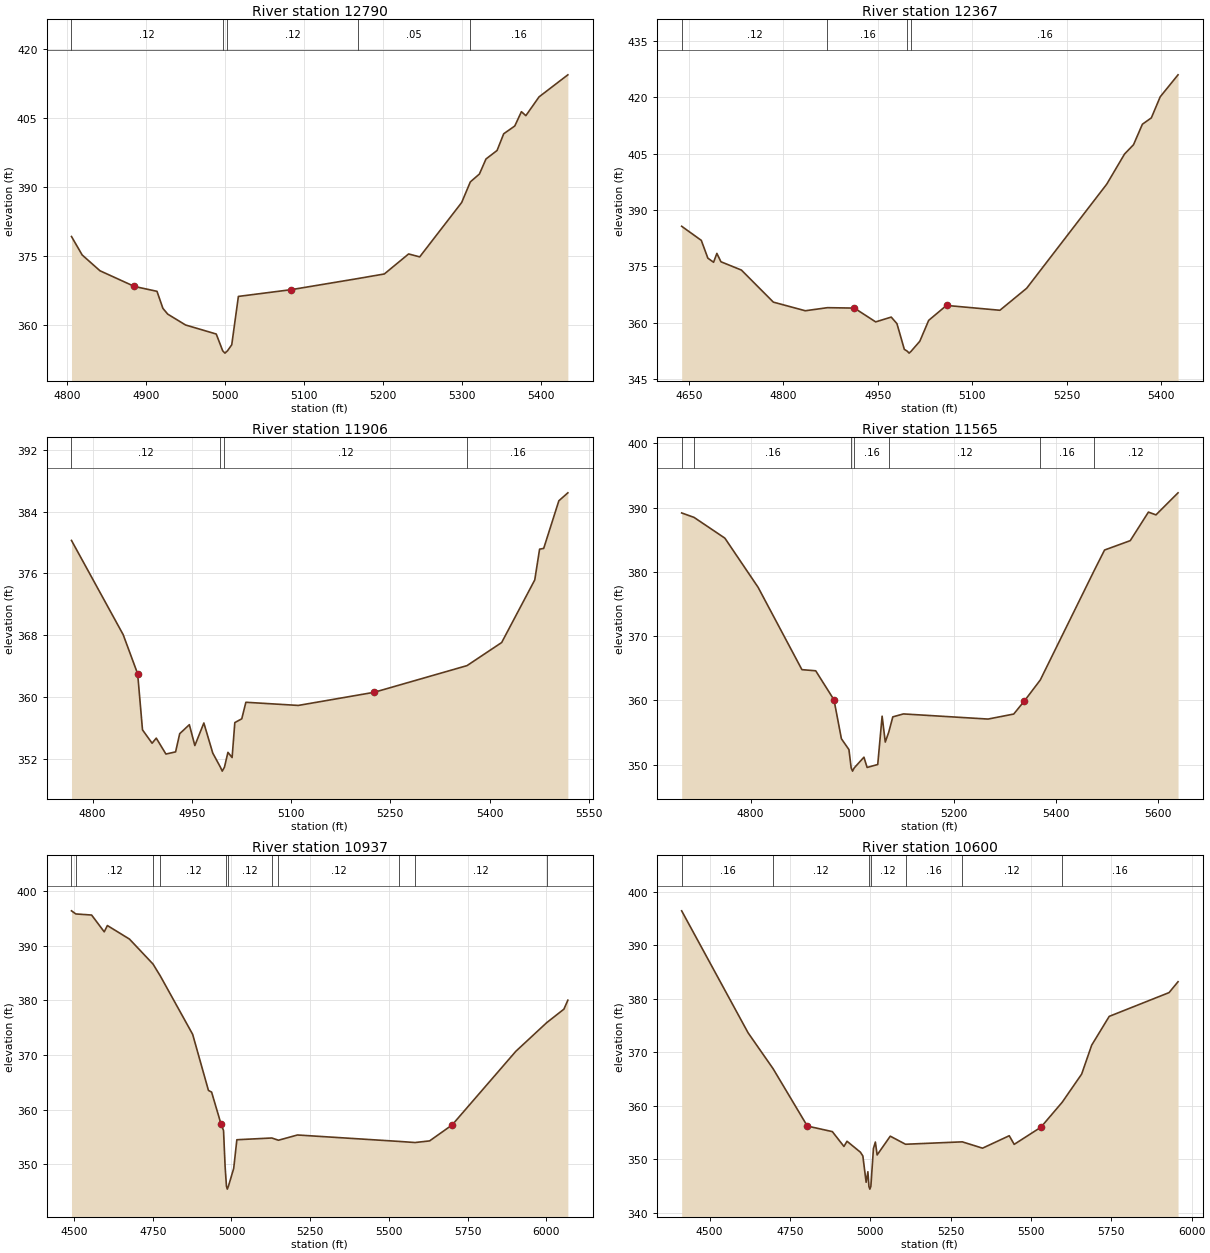
Type RM Length L Ch R = 1 ,12790   ,423,423,423
BEGIN DESCRIPTION:
BATSMITH CREEK 27.0
END DESCRIPTION:
XS GIS Cut Line= 3
      3638299.59     10615210.17      3638149.61     10615110.19
      3637749.58     10614910.17
#Sta/Elev= 30
  4805.9  379.27  4819.4  375.25  4841.9  371.81  4885.5  368.39    4914  367.33
  4921.5  363.61  4927.6  362.36  4950.1     360  4988.9  358.03  4997.1  354.37
  4999.9  353.87  5003.1  354.37  5008.5  355.69  5016.9  366.22    5084   367.7
  5168.3  370.12  5201.4  371.11  5232.1  375.47  5246.1  374.83  5299.2  386.68
  5310.1  391.16  5321.6  392.88  5329.9  396.15  5343.9     398  5352.3  401.64
  5366.3  403.34  5374.7  406.45  5380.3  405.59    5397  409.68  5433.4  414.48
#Mann= 5 ,-1 , 0
  4805.9     .12       0  4997.1     .07       0  5003.1     .12       0
  5168.3     .05       0  5310.1     .16       0
Bank Sta=4885.5,5084
XS Rating Curve= 0 ,0
Exp/Cntr=0.3,0.1

Type RM Length L Ch R = 1 ,12367   ,461,461,461
BEGIN DESCRIPTION:
BATSMITH CREEK 26.0
END DESCRIPTION:
XS GIS Cut Line= 3
      3638499.61      10615210.2      3638399.61     10614860.19
       3638099.6     10614560.18
#Sta/Elev= 30
  4638.6  385.67  4669.8  381.91  4680.2  377.17  4689.3  376.08  4694.5  378.44
    4701  376.21  4733.5     374  4784.2  365.46  4834.9  363.16  4870.2  363.98
  4912.9  363.87  4946.7  360.19  4971.4  361.47  4980.5  359.73  4992.2  352.88
    4997  352.37  4999.8  351.87    5003  352.37  5016.8  355.03  5030.9   360.6
  5059.2  364.58    5144  363.29  5186.5  369.15  5313.7   396.9    5342  404.93
  5356.2   407.4  5370.3  412.86  5384.5  414.55  5398.6  420.17  5426.9  426.02
#Mann= 4 ,-1 , 0
  4638.6     .12       0  4870.2     .16       0    4997     .07       0
    5003     .16       0
Bank Sta=4912.9,5059.2
XS Rating Curve= 0 ,0
Exp/Cntr=0.3,0.1

Type RM Length L Ch R = 1 ,11906   ,341,341,341
BEGIN DESCRIPTION:
BATSMITH CREEK 25.0
END DESCRIPTION:
XS GIS Cut Line= 3
      3638949.59     10614910.16      3638799.61     10614710.19
      3638399.58     10614410.17
#Sta/Elev= 30
  4768.2  380.26  4846.3  368.07  4868.2     363  4875.5  355.75    4890  354.02
  4896.3  354.68  4910.9  352.62  4925.5   352.9  4931.7  355.25  4946.3  356.42
  4954.6  353.72  4968.2  356.64  4981.7  352.74  4993.3  350.91    4996  350.41
  4999.3  350.91  5004.6  352.84  5010.9  352.17    5015  356.69  5025.5  357.18
  5031.7  359.32  5110.9  358.91  5225.5  360.61  5365.8  364.06  5418.2  367.05
  5468.2  375.15  5475.5  379.13  5481.7  379.23  5504.6  385.39  5518.2  386.42
#Mann= 4 ,-1 , 0
  4768.2     .12       0  4993.3     .07       0  4999.3     .12       0
  5365.8     .16       0
Bank Sta=4868.2,5225.5
XS Rating Curve= 0 ,0
Exp/Cntr=0.3,0.1

Type RM Length L Ch R = 1 ,11565   ,628,628,628
BEGIN DESCRIPTION:
BATSMITH CREEK 24.0
END DESCRIPTION:
XS GIS Cut Line= 2
       3639293.4     10614924.75      3638730.91     10614127.88
#Sta/Elev= 30
  4664.7  389.18    4689  388.49  4749.6  385.26  4814.9  377.61    4901   364.8
  4928.1  364.62    4964  360.11  4978.6  354.05  4993.4  352.36  4997.8  349.51
  5000.5  349.01  5003.8  349.51  5022.9  351.18  5029.1  349.58    5050  350.04
  5058.6  357.56  5064.8  353.53  5071.7  355.09  5079.6  357.45  5100.5  357.91
  5266.7  357.11  5317.2  357.89  5338.1  359.92  5369.4  363.19  5475.1  380.18
  5495.7  383.41  5546.2  384.87  5581.9  389.31  5596.7  388.88  5640.1  392.31
#Mann= 7 ,-1 , 0
  4664.7     .12       0    4689     .16       0  4997.8     .07       0
  5003.8     .16       0  5071.7     .12       0  5369.4     .16       0
  5475.1     .12       0
Bank Sta=4964,5338.1
XS Rating Curve= 0 ,0
Exp/Cntr=0.3,0.1

Type RM Length L Ch R = 1 ,10937   ,337,337,337
BEGIN DESCRIPTION:
BATSMITH CREEK 23.0
END DESCRIPTION:
XS GIS Cut Line= 3
      3639547.32     10615143.88      3639595.47     10614518.48
      3639079.85      10613721.6
#Sta/Elev= 30
  4491.9  396.36  4505.6  395.79  4555.8  395.59  4595.9  392.52  4605.9  393.67
  4676.1  391.19  4750.8  386.63  4774.2  384.43  4876.7  373.78  4926.9  363.52
  4936.9  363.21    4967  357.34  4974.8  356.19  4979.8   349.6  4984.1  345.97
  4986.8  345.47  4990.1  345.97  5007.1  349.26  5017.1   354.5  5128.1  354.82
  5149.2  354.41  5209.6  355.37  5533.5  354.19  5582.9  353.99  5629.3  354.29
  5700.7   357.2  5903.2  370.68  6001.3  375.92  6055.8  378.38  6068.3  380.02
#Mann= 11 ,-1 , 0
  4491.9     .16       0  4505.6     .12       0  4750.8     .16       0
  4774.2     .12       0  4984.1     .07       0  4990.1     .12       0
  5128.1     .16       0  5149.2     .12       0  5533.5     .16       0
  5582.9     .12       0  6001.3     .16       0
Bank Sta=4967,5700.7
XS Rating Curve= 0 ,0
Exp/Cntr=0.3,0.1

Type RM Length L Ch R = 1 ,10600   ,638,638,638
BEGIN DESCRIPTION:
BATSMITH CREEK 22.0
END DESCRIPTION:
XS GIS Cut Line= 3
       3640137.6     10614984.15       3639800.8     10614595.26
      3639380.85     10613654.72
#Sta/Elev= 30
  4413.2  396.43  4619.9  373.65  4697.8  366.94  4804.2  356.24    4882   355.2
  4918.2  352.43  4927.7   353.4  4969.5  351.35    4977  350.65  4987.2  345.74
  4992.7  347.71  4995.9  344.96  4998.7  344.46  5001.9  344.96  5009.9  352.05
  5015.9  353.25  5021.4  350.84  5062.3  354.35  5109.7  352.84  5286.4  353.29
  5349.4  352.11  5432.5  354.43  5447.9  352.82  5530.8  356.01  5597.2  360.68
  5657.8  365.94  5688.9  371.33  5743.6  376.72  5929.8  381.16  5957.7  383.19
#Mann= 7 ,-1 , 0
  4413.2     .16       0  4697.8     .12       0  4995.9     .07       0
  5001.9     .12       0  5109.7     .16       0  5286.4     .12       0
  5597.2     .16       0
Bank Sta=4804.2,5530.8
XS Rating Curve= 0 ,0
Exp/Cntr=0.3,0.1

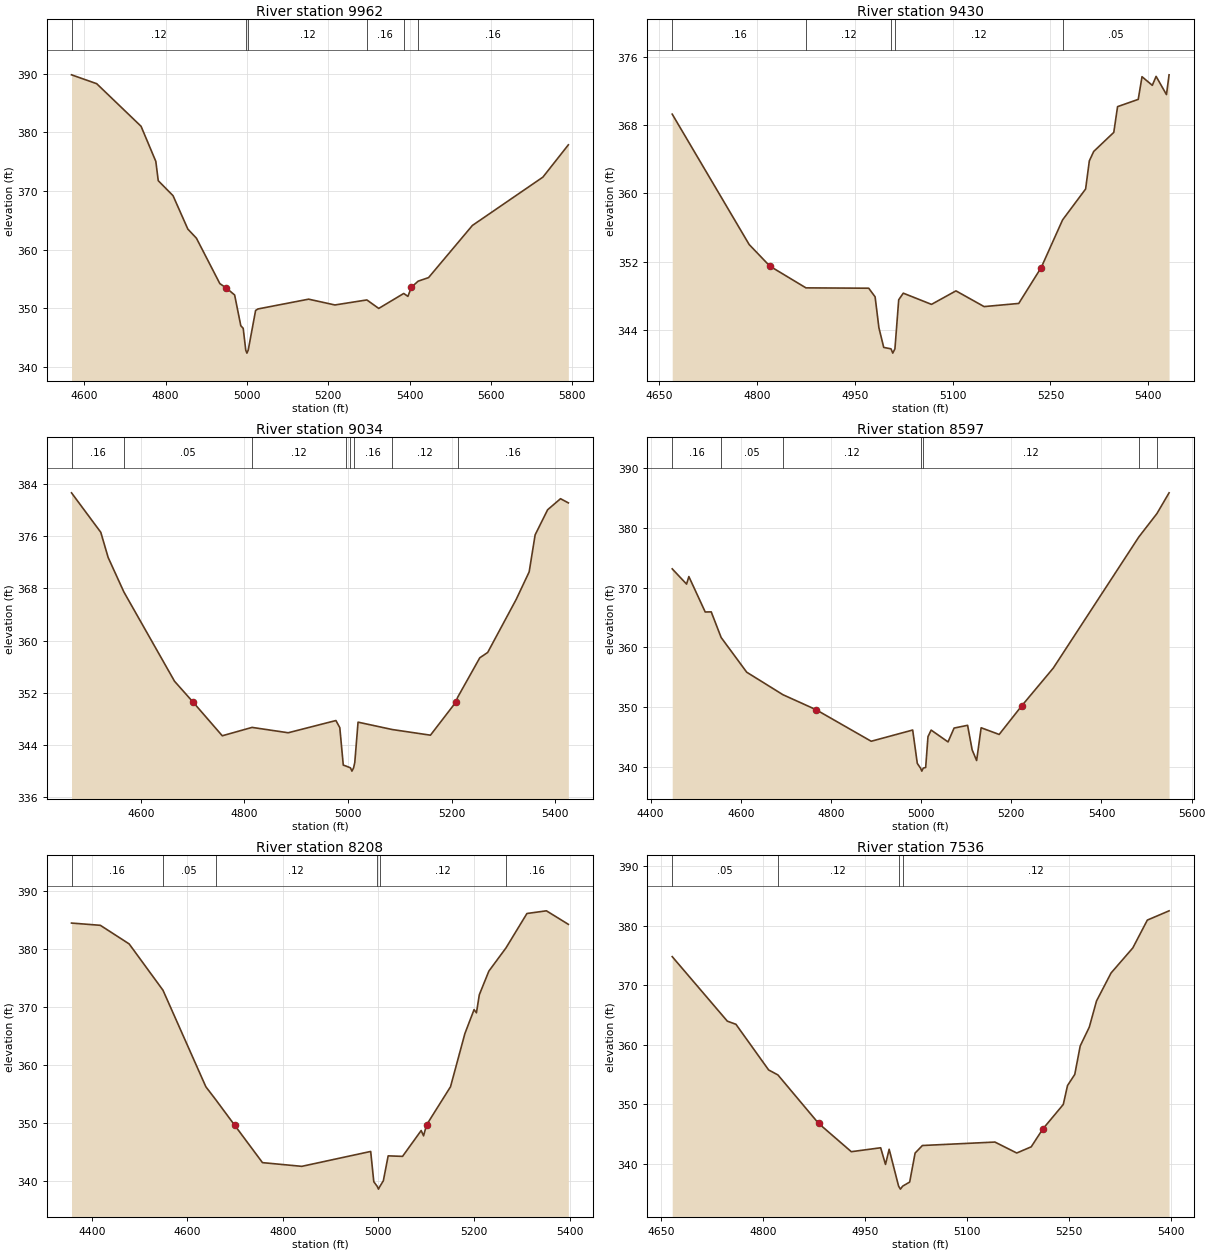
Type RM Length L Ch R = 1 ,9962    ,532,532,532
BEGIN DESCRIPTION:
BATSMITH CREEK 21.0
END DESCRIPTION:
XS GIS Cut Line= 3
      3640475.71     10614409.12      3639944.43     10614070.56
      3639611.08     10613580.95
#Sta/Elev= 30
  4568.5  389.84  4630.4  388.33  4739.6  381.06  4775.9  375.07  4781.9  371.77
  4818.3  369.21  4854.7  363.51  4875.8  361.96  4933.4  354.21  4948.6  353.49
  4969.8  352.27    4985  347.02  4990.9  346.57  4997.2  342.84    5000  342.34
  5003.2  342.84  5021.4  349.62  5027.3  349.88  5151.8  351.55  5216.5  350.56
  5295.1  351.42  5324.3  349.97  5385.8  352.52  5396.1  352.03  5404.6  353.58
  5421.2  354.62  5446.9  355.23  5554.7  364.13  5728.2  372.38  5790.8  377.89
#Mann= 6 ,-1 , 0
  4568.5     .12       0  4997.2     .07       0  5003.2     .12       0
  5295.1     .16       0  5385.8     .12       0  5421.2     .16       0
Bank Sta=4948.6,5404.6
XS Rating Curve= 0 ,0
Exp/Cntr=0.3,0.1

Type RM Length L Ch R = 1 ,9430    ,396,396,396
BEGIN DESCRIPTION:
BATSMITH CREEK 20.0
END DESCRIPTION:
XS GIS Cut Line= 2
      3640601.62     10613921.01      3639939.13     10613544.31
#Sta/Elev= 30
  4669.8  369.26  4787.8  354.02  4819.6  351.49  4874.9  348.95  4971.2  348.91
    4981   347.9  4986.8   344.3  4994.2  341.99  5005.4  341.82  5008.1  341.32
  5011.4  341.82  5017.2  347.56  5024.2  348.33  5067.5  347.02    5105   348.6
  5148.2  346.76  5201.3  347.13  5235.8  351.33  5268.5  356.89  5303.9  360.51
  5309.6   363.8  5316.3   364.9  5347.1  367.13  5352.9  370.14  5384.6  370.99
  5390.4  373.64  5406.2  372.63    5412  373.68  5427.9  371.55  5431.9  373.86
#Mann= 5 ,-1 , 0
  4669.8     .16       0  4874.9     .12       0  5005.4     .07       0
  5011.4     .12       0  5268.5     .05       0
Bank Sta=4819.6,5235.8
XS Rating Curve= 0 ,0
Exp/Cntr=0.3,0.1

Type RM Length L Ch R = 1 ,9034    ,437,437,437
BEGIN DESCRIPTION:
BATSMITH CREEK 19.0
END DESCRIPTION:
XS GIS Cut Line= 3
      3640849.61     10613810.19      3640499.61     10613410.19
      3640099.62     10613260.19
#Sta/Elev= 30
  4466.3  382.61  4522.8  376.57    4537  372.72  4567.3  367.45  4665.1  353.78
  4700.3  350.64  4757.2  345.44  4814.7  346.72  4884.4   345.9  4976.5  347.77
    4984  346.68  4990.7  340.95  4996.5  340.79  5004.6  340.53  5007.4  340.03
  5010.6  340.53  5012.9  341.35  5019.2  347.52  5085.5  346.39  5158.9  345.53
  5208.7  350.66  5211.2   351.3  5254.1  357.37  5269.3  358.18  5324.4  366.31
  5349.4  370.52  5360.9  376.18    5385  380.02  5409.9  381.71    5425  381.07
#Mann= 8 ,-1 , 0
  4466.3     .16       0  4567.3     .05       0  4814.7     .12       0
  4996.5     .16       0  5004.6     .07       0  5010.6     .16       0
  5085.5     .12       0  5211.2     .16       0
Bank Sta=4700.3,5208.7
XS Rating Curve= 0 ,0
Exp/Cntr=0.3,0.1

Type RM Length L Ch R = 1 ,8597    ,389,389,389
BEGIN DESCRIPTION:
BATSMITH CREEK 18.0
END DESCRIPTION:
XS GIS Cut Line= 3
      3640972.19      10613741.8      3640843.73     10613137.67
      3640843.73     10612653.41
#Sta/Elev= 30
    4448  373.12  4479.8  370.57  4484.9  371.83  4521.2   365.9  4534.5  365.92
  4556.5  361.63  4613.2  355.82  4693.6  352.05  4766.6  349.56  4889.3  344.26
  4981.3  346.14  4991.5  340.56  4998.7  339.76  5001.5  339.26  5004.7  339.76
  5010.1  339.87  5015.2  345.02  5022.2  346.13  5059.7  344.15  5073.1  346.47
  5103.1  346.93  5113.1  342.84  5123.1  341.03  5133.1  346.52  5173.1   345.4
  5223.1  350.19  5293.1  356.51  5482.8  378.46  5522.9  382.37  5549.9  385.85
#Mann= 7 ,-1 , 0
    4448     .16       0  4556.5     .05       0  4693.6     .12       0
  4998.7     .07       0  5004.7     .12       0  5482.8     .16       0
  5522.9     .12       0
Bank Sta=4766.6,5223.1
XS Rating Curve= 0 ,0
Exp/Cntr=0.3,0.1

Type RM Length L Ch R = 1 ,8208    ,672,672,672
BEGIN DESCRIPTION:
BATSMITH CREEK 17.0
END DESCRIPTION:
XS GIS Cut Line= 2
      3641230.89     10613690.38      3641137.19     10612654.51
#Sta/Elev= 30
  4357.5  384.46  4417.9  384.07  4478.2  380.86    4549  372.87  4638.8  356.21
  4659.1  354.03  4699.1  349.58  4757.3  343.13  4839.6  342.49  4983.8  345.06
  4990.3  339.84  4997.3  339.06  5000.1  338.56  5003.3  339.06  5010.3     340
  5020.4   344.3  5050.5  344.21  5089.5  348.67  5094.5  347.75  5100.7  349.63
  5150.9  356.22    5181  365.39  5200.2  369.53  5205.2  368.98  5211.2  372.09
  5231.2  376.17  5267.1  380.18  5310.9  386.11  5351.7  386.57  5397.6  384.24
#Mann= 6 ,-1 , 0
  4357.5     .16       0    4549     .05       0  4659.1     .12       0
  4997.3     .07       0  5003.3     .12       0  5267.1     .16       0
Bank Sta=4699.1,5100.7
XS Rating Curve= 0 ,0
Exp/Cntr=0.3,0.1

Type RM Length L Ch R = 1 ,7536    ,295,295,295
BEGIN DESCRIPTION:
BATSMITH CREEK 16.0
END DESCRIPTION:
XS GIS Cut Line= 3
      3641599.61     10613560.19      3641649.61     10613260.19
      3641499.62     10612860.22
#Sta/Elev= 30
  4666.2  374.77  4747.3  363.93    4760   363.4  4808.1  355.73  4821.8  354.89
  4881.6  346.75  4929.8  341.99    4973  342.65  4980.1  339.85  4985.5   342.4
  4999.4   336.2  5002.1   335.7  5005.4   336.2  5015.7  336.89  5023.7  341.76
  5034.4  343.03  5141.2  343.61  5173.3  341.77  5194.6  342.81  5211.5  345.78
  5241.8  349.93    5248   353.1  5258.7  354.98  5266.7  359.76  5280.1  362.93
  5290.7  367.32  5312.1  372.02  5344.1  376.23  5365.5  380.91  5397.5  382.47
#Mann= 4 ,-1 , 0
  4666.2     .05       0  4821.8     .12       0  4999.4     .07       0
  5005.4     .12       0
Bank Sta=4881.6,5211.5
XS Rating Curve= 0 ,0
Exp/Cntr=0.3,0.1