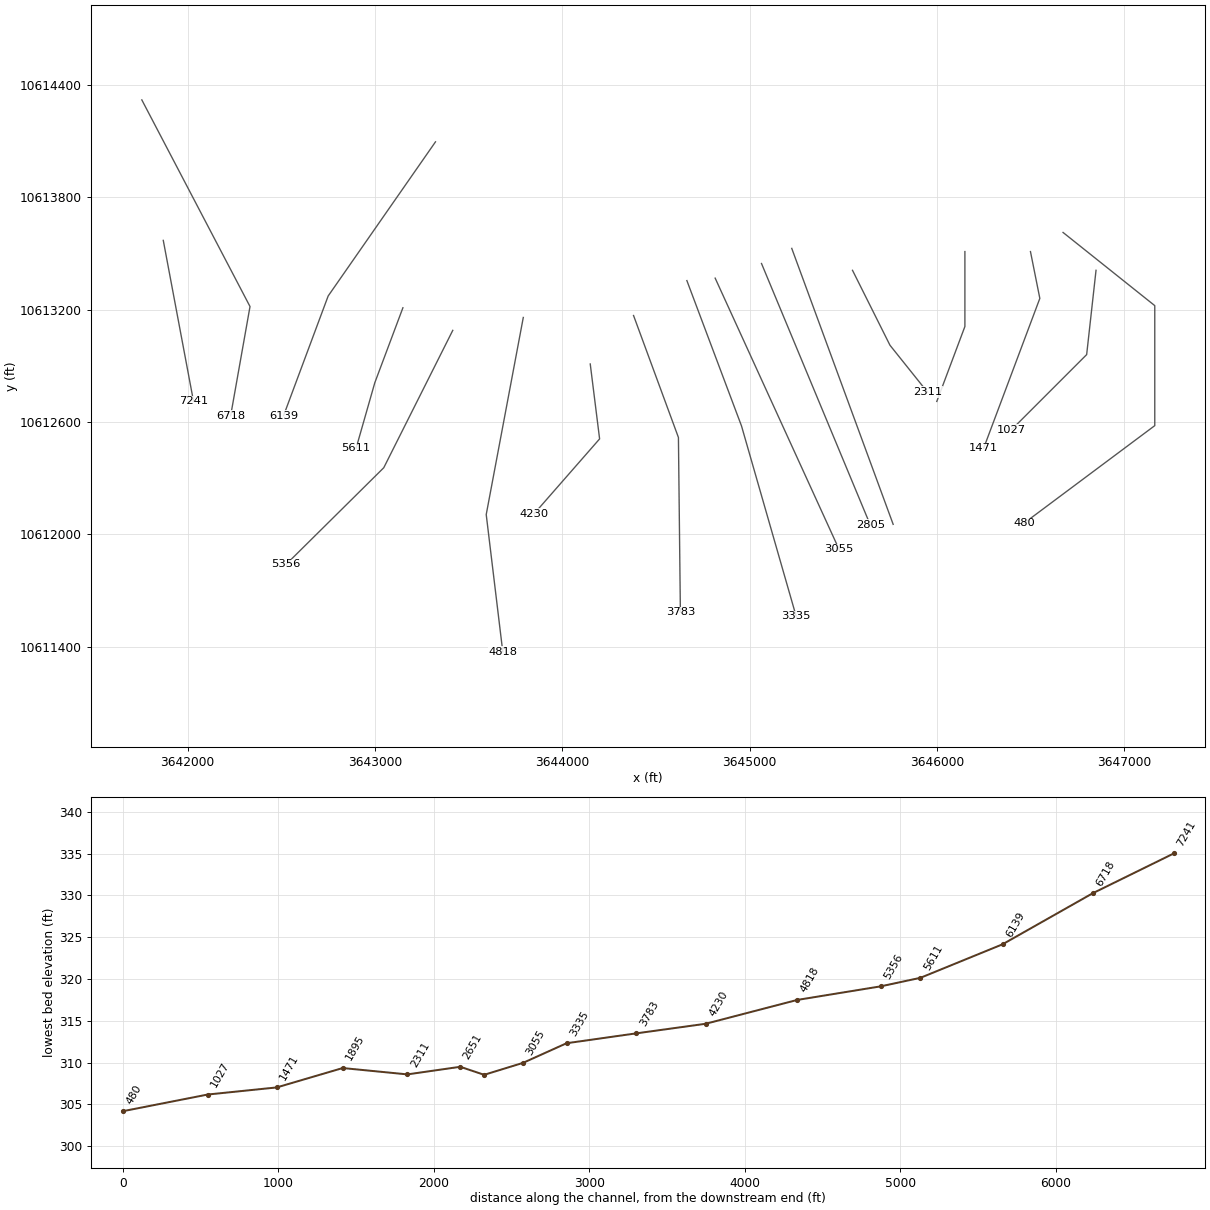
HEC-RAS study BATSMITH CREEK.prj: BATSMITH CREEK Base Level Engineering

--- BATSMITH CREEK.g01 (geometry) --- (continued)

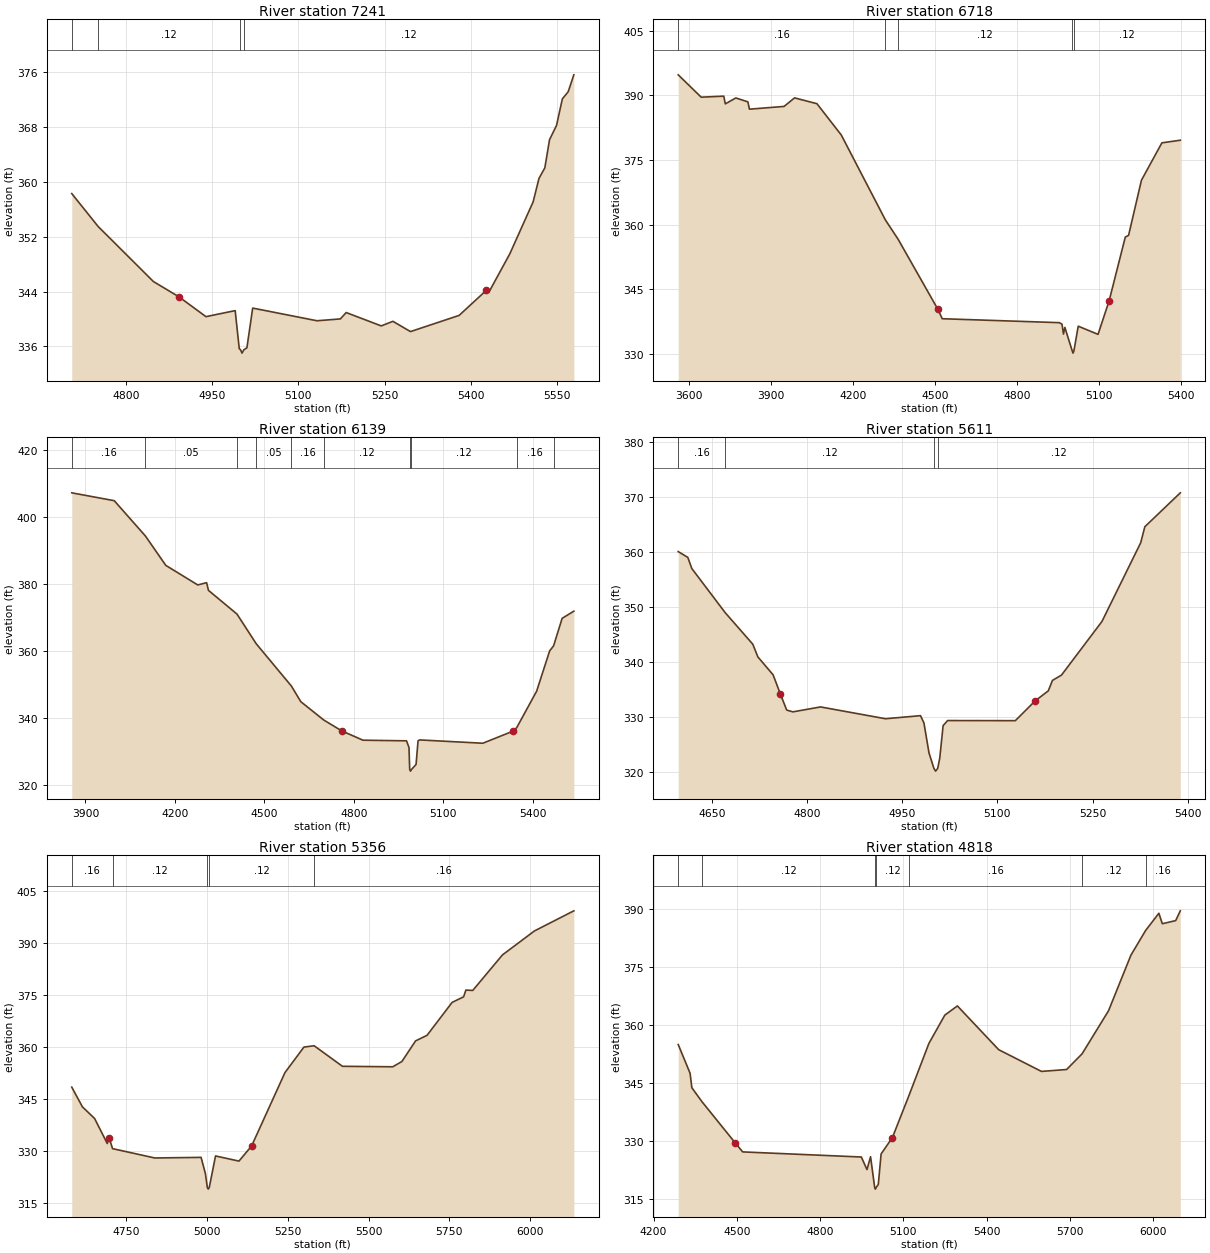
Type RM Length L Ch R = 1 ,7241    ,523,523,523
BEGIN DESCRIPTION:
BATSMITH CREEK 15.0
END DESCRIPTION:
XS GIS Cut Line= 2
      3641870.38     10613569.91      3642031.84     10612710.55
#Sta/Elev= 30
  4705.3   358.3  4751.1  353.51  4847.5  345.47    4892  343.24    4939  340.35
  4989.9  341.23    4997  335.68  4999.1  335.53  5001.8  335.03  5005.1  335.53
  5010.3   335.8  5020.4   341.6  5132.4  339.75  5173.1  340.02  5183.2  340.95
  5244.3     339  5264.6  339.67  5295.2  338.17  5379.9  340.53  5427.3  344.19
  5432.4  344.02  5468.1   349.5  5508.8  357.09    5519  360.51  5529.2  362.06
  5537.4  366.17  5549.5  368.23  5559.7  372.11  5569.9  373.16  5579.7  375.62
#Mann= 4 ,-1 , 0
  4705.3     .16       0  4751.1     .12       0  4999.1     .07       0
  5005.1     .12       0
Bank Sta=4892,5427.3
XS Rating Curve= 0 ,0
Exp/Cntr=0.3,0.1

Type RM Length L Ch R = 1 ,6718    ,579,579,579
BEGIN DESCRIPTION:
BATSMITH CREEK 14.0
END DESCRIPTION:
XS GIS Cut Line= 3
      3641755.82     10614319.88      3642333.41     10613216.76
      3642230.01     10612633.84
#Sta/Elev= 30
  3561.2  394.73  3645.2  389.55  3727.8  389.79  3733.4     388  3771.9  389.37
  3816.1  388.47  3821.7  386.77  3948.5  387.41  3986.9  389.39  4068.8  388.04
  4157.8  380.79  4319.3   361.1    4366  356.62  4510.9  340.45  4527.3  338.22
  4955.2  337.31  4965.4  336.98  4970.9  334.67    4976  336.21    5003  330.75
  5005.8  330.25    5009  330.75  5024.9  336.49  5097.4   334.6    5138  342.38
  5197.1  357.14  5209.1  357.53  5256.2  370.31    5331  378.97  5398.4  379.58
#Mann= 5 ,-1 , 0
  3561.2     .16       0  4319.3     .05       0    4366     .12       0
    5003     .07       0    5009     .12       0
Bank Sta=4510.9,5138
XS Rating Curve= 0 ,0
Exp/Cntr=0.3,0.1

Type RM Length L Ch R = 1 ,6139    ,528,528,528
BEGIN DESCRIPTION:
BATSMITH CREEK 13.0
END DESCRIPTION:
XS GIS Cut Line= 3
       3643323.5     10614095.94      3642750.59     10613273.04
      3642512.54     10612634.14
#Sta/Elev= 30
  3854.1  407.18  3996.7  404.83  4101.4  394.28  4169.5  385.54  4276.8   379.7
  4306.5  380.37  4312.6  378.09  4408.4  371.01  4472.9  362.16    4591  349.53
  4622.4  344.88  4699.2  339.42  4759.5  336.18    4831  333.38  4977.2  333.19
  4985.5  331.21  4987.9  324.65  4990.6  324.15  4993.9  324.65  5009.2  326.13
  5015.9   333.2  5021.2  333.46  5233.3  332.47  5333.4  336.04  5346.9  337.11
  5413.8  348.01  5457.4  360.01  5470.5   361.5  5499.4  369.74  5538.6  371.87
#Mann= 10 ,-1 , 0
  3854.1     .16       0  4101.4     .05       0  4408.4     .16       0
  4472.9     .05       0    4591     .16       0  4699.2     .12       0
  4987.9     .07       0  4993.9     .12       0  5346.9     .16       0
  5470.5     .05       0
Bank Sta=4759.5,5333.4
XS Rating Curve= 0 ,0
Exp/Cntr=0.3,0.1

Type RM Length L Ch R = 1 ,5611    ,255,255,255
BEGIN DESCRIPTION:
BATSMITH CREEK 12.0
END DESCRIPTION:
XS GIS Cut Line= 3
      3643149.61      10613210.2      3642999.61     10612810.19
      3642899.61     10612460.21
#Sta/Elev= 30
    4597  360.08  4612.1  359.02  4618.4     357    4671  348.97  4714.5  343.23
  4722.5  340.92  4746.5  337.66  4758.1  334.13  4767.9  331.25  4777.7  330.92
  4821.3  331.82  4923.6  329.67  4978.8  330.23  4984.2   328.9  4992.2  323.44
  4999.9  320.64  5002.6  320.14  5005.9  320.64  5009.1  322.48  5014.4  328.41
  5021.5  329.34  5128.2  329.32  5159.4  332.91  5180.2  334.75  5186.7  336.64
    5201  337.62  5264.7  347.36  5325.8  361.69  5332.3   364.6  5388.2  370.77
#Mann= 4 ,-1 , 0
    4597     .16       0    4671     .12       0  4999.9     .07       0
  5005.9     .12       0
Bank Sta=4758.1,5159.4
XS Rating Curve= 0 ,0
Exp/Cntr=0.3,0.1

Type RM Length L Ch R = 1 ,5356    ,538,538,538
BEGIN DESCRIPTION:
BATSMITH CREEK 11.0
END DESCRIPTION:
XS GIS Cut Line= 3
      3643415.77     10613089.59      3643047.47     10612356.37
      3642526.65     10611840.76
#Sta/Elev= 30
  4581.8  348.51  4614.7  342.84  4652.5  339.47  4691.6  332.27  4697.2  333.96
    4708  330.79  4838.5   328.1  4981.9  328.27  4995.2  323.63  5001.2  319.62
    5004  319.12  5007.2  319.62  5026.6  328.68  5099.1   327.2  5138.2  331.55
  5241.4   352.7  5300.1  360.06  5331.7  360.44  5419.3  354.52  5574.9  354.38
  5603.2   355.9  5645.6  361.85  5680.9  363.44  5758.7  372.95  5794.1  374.54
  5801.2  376.49  5822.4  376.38  5914.3  386.62  6013.3  393.53  6135.2  399.33
#Mann= 5 ,-1 , 0
  4581.8     .16       0    4708     .12       0  5001.2     .07       0
  5007.2     .12       0  5331.7     .16       0
Bank Sta=4697.2,5138.2
XS Rating Curve= 0 ,0
Exp/Cntr=0.3,0.1

Type RM Length L Ch R = 1 ,4818    ,588,588,588
BEGIN DESCRIPTION:
BATSMITH CREEK 10.0
END DESCRIPTION:
XS GIS Cut Line= 3
      3643792.25     10613158.42      3643594.34     10612106.37
      3643682.69     10611373.58
#Sta/Elev= 30
  4288.8  354.86  4331.5  347.43  4337.9  343.69  4374.9  340.03    4494  329.45
    4521  327.11  4948.4  325.79  4968.7  322.54  4981.6  325.86  4996.3  317.99
    4999  317.49  5002.3  317.99  5009.5  318.69  5019.6  326.58  5060.3  330.82
  5119.8  341.65  5191.6  355.12  5249.1  362.46  5294.4  364.83  5443.1  353.53
  5597.2  347.91  5687.8   348.4  5743.6  352.46  5838.9  363.59  5919.5  377.95
  5972.6  384.35  6020.2  388.78  6032.6  386.08  6080.7  386.88  6097.4  389.41
#Mann= 7 ,-1 , 0
  4288.8     .16       0  4374.9     .12       0  4996.3     .07       0
  5002.3     .12       0  5119.8     .16       0  5743.6     .12       0
  5972.6     .16       0
Bank Sta=4494,5060.3
XS Rating Curve= 0 ,0
Exp/Cntr=0.3,0.1

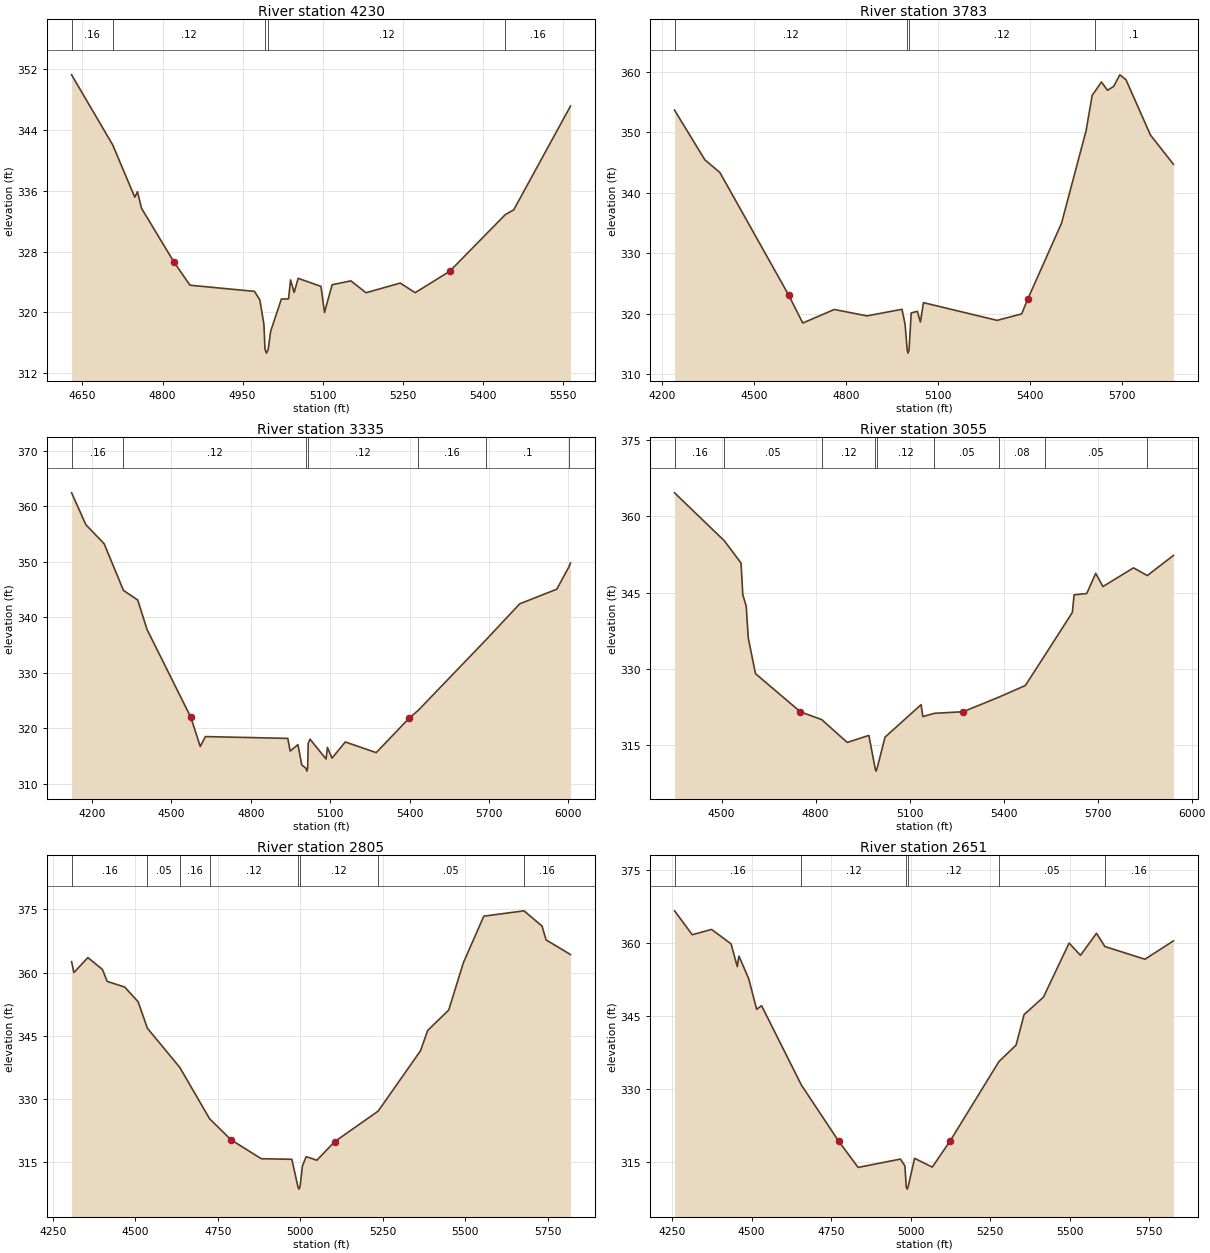
Type RM Length L Ch R = 1 ,4230    ,447,447,447
BEGIN DESCRIPTION:
BATSMITH CREEK 9.0
END DESCRIPTION:
XS GIS Cut Line= 3
      3644149.61     10612910.18      3644199.61     10612510.19
      3643849.62      10612110.2
#Sta/Elev= 30
  4629.7  351.23  4706.6  342.03  4748.1  335.14  4753.1  335.86  4760.7  333.68
  4821.2  326.65  4851.4  323.57  4972.3  322.76  4982.4  321.63    4990  318.41
    4992  315.14  4994.8  314.64    4998  315.14  5002.6  317.52  5022.7  321.75
  5036.1  321.77  5039.9  324.26  5046.6  322.62  5054.2  324.48  5096.9  323.41
  5103.5  319.99  5117.7  323.63  5152.9  324.14  5181.3  322.58  5245.4  323.85
  5273.4  322.59  5337.9  325.39    5442  332.84    5458  333.48  5564.3  347.12
#Mann= 5 ,-1 , 0
  4629.7     .16       0  4706.6     .12       0    4992     .07       0
    4998     .12       0    5442     .16       0
Bank Sta=4821.2,5337.9
XS Rating Curve= 0 ,0
Exp/Cntr=0.3,0.1

Type RM Length L Ch R = 1 ,3783    ,448,448,448
BEGIN DESCRIPTION:
BATSMITH CREEK 8.0
END DESCRIPTION:
XS GIS Cut Line= 3
      3644380.81     10613168.86      3644620.38     10612517.83
       3644630.8      10611585.5
#Sta/Elev= 30
  4241.6  353.69  4340.4  345.47  4389.4  343.37  4613.1  323.14  4659.5  318.47
  4762.3  320.71  4868.9  319.65    4983  320.74    4993  318.28    5000  313.99
  5002.7  313.49    5006  313.99    5013  320.13    5033  320.41    5043  318.64
    5053  321.84    5293  318.91    5373  319.98    5393  322.44    5503  334.98
    5583  350.28    5603  356.16  5612.3  356.81    5633  358.35    5653  356.97
    5673  357.62    5693  359.53    5713  358.73    5793  349.56  5867.7  344.74
#Mann= 4 ,-1 , 0
  4241.6     .12       0    5000     .07       0    5006     .12       0
  5612.3      .1       0
Bank Sta=4613.1,5393
XS Rating Curve= 0 ,0
Exp/Cntr=0.3,0.1

Type RM Length L Ch R = 1 ,3335    ,280,280,280
BEGIN DESCRIPTION:
Mapping XS 43ef6bcb
END DESCRIPTION:
XS GIS Cut Line= 3
      3644665.47     10613355.25      3644957.12     10612579.25
      3645248.57     10611564.37
#Sta/Elev= 30
  4123.1   362.4    4177  356.66    4246  353.24  4319.1  344.83  4372.7  343.12
  4408.3  337.79  4573.6  321.99  4609.2  316.74  4628.8  318.53    4940   318.2
  4948.9  315.92  4978.2  317.08  4992.7  313.43  5008.9  312.81  5011.6  312.31
  5014.9  312.81  5017.1  317.31  5023.9  318.06  5084.5  314.49  5089.7  316.57
  5107.2  314.66  5157.2  317.56    5274  315.64  5398.5  321.84  5432.6  323.24
  5688.4  335.92  5816.2  342.42  5956.3  345.06  6001.3     349    6008  349.76
#Mann= 7 ,-1 , 0
  4123.1     .16       0  4319.1     .12       0  5008.9     .07       0
  5014.9     .12       0  5432.6     .16       0  5688.4      .1       0
  6001.3     .07       0
Bank Sta=4573.6,5398.5
XS Rating Curve= 0 ,0
Exp/Cntr=0.3,0.1

Type RM Length L Ch R = 1 ,3055    ,250,250,250
BEGIN DESCRIPTION:
BATSMITH CREEK 7.0
END DESCRIPTION:
XS GIS Cut Line= 2
      3644816.49     10613368.32      3645477.97     10611920.36
#Sta/Elev= 30
  4349.9  364.56  4508.8  355.15  4562.1  350.79  4567.7  344.58  4578.7  342.29
  4585.1  336.09  4608.1  329.09  4751.8  321.58  4819.4  320.07    4901  315.59
    4970  316.97  4990.1  310.46  4992.8  309.96  4996.1  310.46  5021.6  316.63
  5136.7     323  5142.2  320.67  5179.1   321.3  5271.3  321.62  5384.2  324.46
  5469.2  326.75  5532.5  332.77  5619.3   341.1  5624.8  344.54  5665.3  344.81
  5693.8  348.76  5716.9  346.17  5814.5  349.84  5858.5  348.33  5941.8  352.28
#Mann= 9 ,-1 , 0
  4349.9     .16       0  4508.8     .05       0  4819.4     .12       0
  4990.1     .07       0  4996.1     .12       0  5179.1     .05       0
  5384.2     .08       0  5532.5     .05       0  5858.5      .1       0
Bank Sta=4751.8,5271.3
XS Rating Curve= 0 ,0
Exp/Cntr=0.3,0.1

Type RM Length L Ch R = 1 ,2805    ,154,154,154
BEGIN DESCRIPTION:
BATSMITH CREEK 6.0
END DESCRIPTION:
XS GIS Cut Line= 2
       3645063.9     10613446.42      3645644.62     10612050.61
#Sta/Elev= 30
  4306.9  362.58  4313.9  359.99  4356.2  363.56  4400.3  360.73  4414.7  357.89
  4467.8  356.55  4508.6  353.03  4536.6  346.76  4634.7  337.46  4725.1  325.25
  4790.2  320.24  4881.9  315.75  4974.3  315.62    4993  309.03  4995.8  308.53
    4999  309.03  5006.5  314.06  5017.7  316.24  5050.2   315.4  5104.3  319.82
    5236  327.07  5364.3  341.42  5385.9  346.23  5449.8  351.09  5494.2  362.35
  5556.1  373.39  5677.8  374.66  5732.5  371.05  5744.7  367.76  5818.7  364.28
#Mann= 8 ,-1 , 0
  4306.9     .16       0  4536.6     .05       0  4634.7     .16       0
  4725.1     .12       0    4993     .07       0    4999     .12       0
    5236     .05       0  5677.8     .16       0
Bank Sta=4790.2,5104.3
XS Rating Curve= 0 ,0
Exp/Cntr=0.3,0.1

Type RM Length L Ch R = 1 ,2651    ,340,340,340
BEGIN DESCRIPTION:
Mapping XS 402dd50c
END DESCRIPTION:
XS GIS Cut Line= 2
      3645225.36     10613527.15      3645766.67     10612054.16
#Sta/Elev= 30
  4257.5  366.68  4313.1  361.77    4374  362.86  4435.4  359.88  4454.8  355.23
  4460.1  357.37  4490.6  352.77  4515.8  346.44  4531.3  347.18  4656.4  330.89
  4774.1  319.31    4835  313.95  4968.1  315.67  4982.1  314.25  4986.4  309.99
  4989.1  309.49  4992.4  309.99  5012.5  315.82  5068.2  314.02  5123.8  319.32
  5277.9   335.7  5331.8  339.08    5357  345.35  5417.9  348.94  5498.7  360.05
  5534.5  357.54  5584.8  362.07  5611.3  359.34  5737.2  356.73  5826.8   360.5
#Mann= 6 ,-1 , 0
  4257.5     .16       0  4656.4     .12       0  4986.4     .07       0
  4992.4     .12       0  5277.9     .05       0  5611.3     .16       0
Bank Sta=4774.1,5123.8
XS Rating Curve= 0 ,0
Exp/Cntr=0.3,0.1

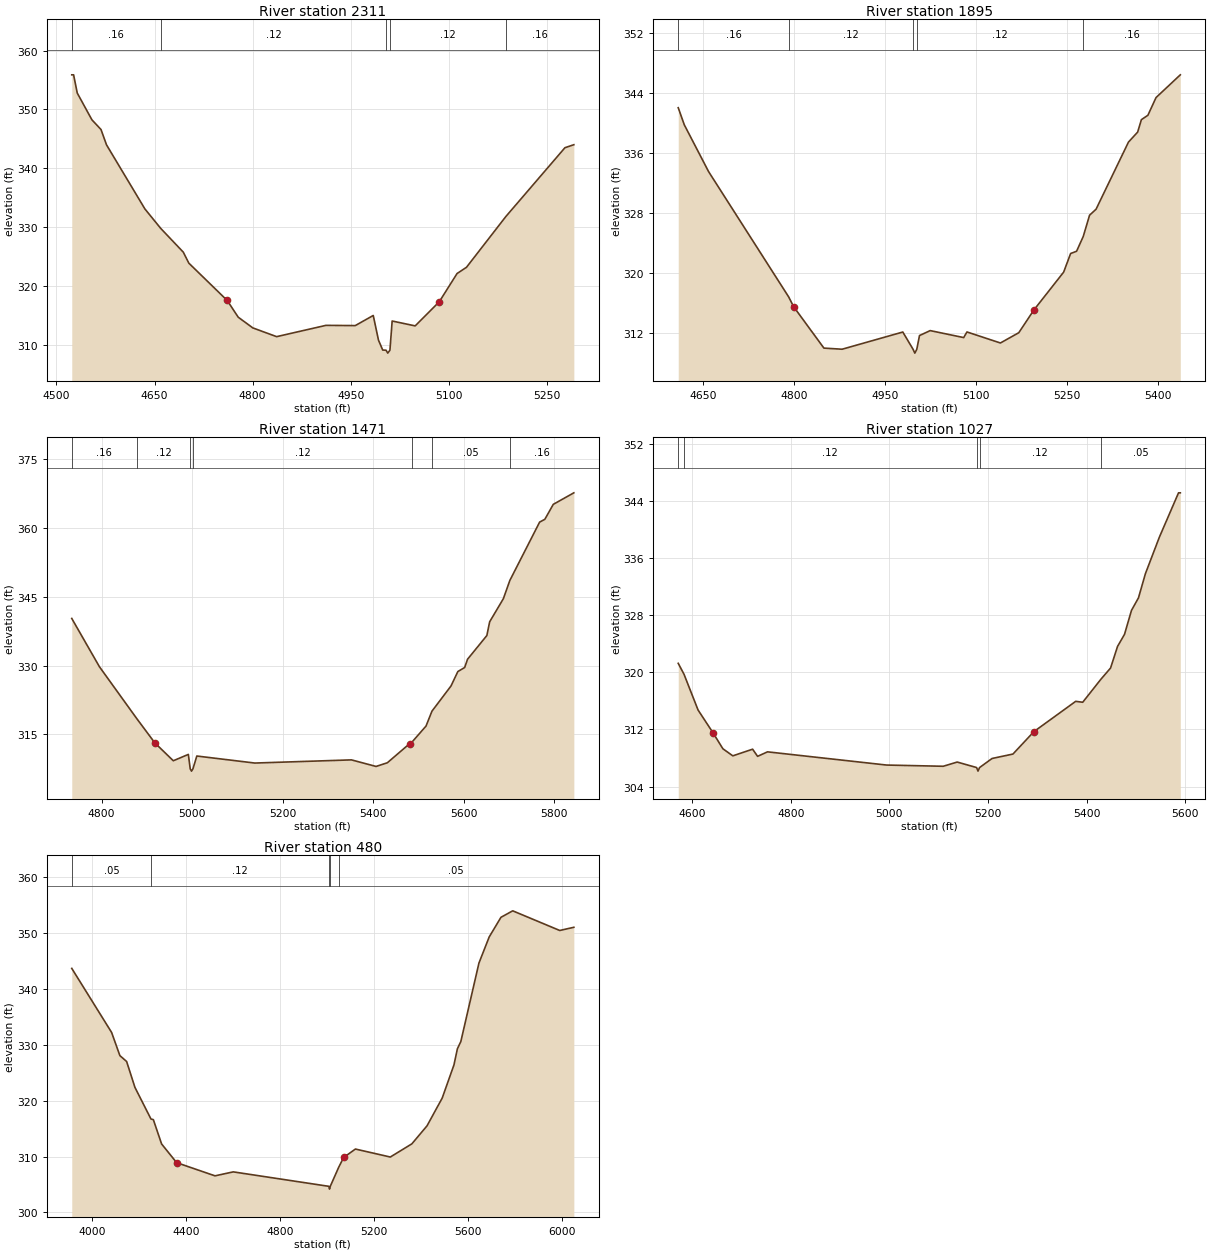
Type RM Length L Ch R = 1 ,2311    ,416,416,416
BEGIN DESCRIPTION:
BATSMITH CREEK 5.0
END DESCRIPTION:
XS GIS Cut Line= 3
       3645549.6     10613410.21      3645749.61     10613010.19
      3645949.61     10612760.18
#Sta/Elev= 30
  4523.5  355.89  4526.3  355.89  4531.9  352.79  4554.3  348.24  4568.2  346.59
  4576.6  343.99  4635.3  333.09  4659.5  329.78    4694  325.74  4702.4  323.88
  4761.1  317.53  4777.9  314.69  4800.2  312.87  4836.6  311.38    4912   313.3
  4956.8  313.26  4984.3  314.98  4992.3  310.79  4998.8   309.1  5003.8  309.08
  5006.5  308.58  5009.8  309.08  5013.2  314.04  5048.4  313.21  5085.2  317.31
  5112.4  322.11  5126.8  323.17  5186.9  331.79  5277.3   343.5  5290.9  344.01
#Mann= 5 ,-1 , 0
  4523.5     .16       0  4659.5     .12       0  5003.8     .07       0
  5009.8     .12       0  5186.9     .16       0
Bank Sta=4761.1,5085.2
XS Rating Curve= 0 ,0
Exp/Cntr=0.3,0.1

Type RM Length L Ch R = 1 ,1895    ,424,424,424
BEGIN DESCRIPTION:
BATSMITH CREEK 4.0
END DESCRIPTION:
XS GIS Cut Line= 3
      3646149.61     10613510.19      3646149.61     10613110.19
      3645999.61     10612710.19
#Sta/Elev= 30
  4609.3  342.03  4619.3  339.75  4659.3  333.52  4791.4  316.81  4799.3  315.54
  4849.3  310.01  4879.3  309.86  4979.3  312.15  4996.3  309.84  4999.1  309.34
  5002.3  309.84  5006.8  311.68  5024.4  312.34  5079.6  311.41    5085  312.16
  5140.1  310.69  5170.4  312.06  5195.3  315.09  5244.3  320.13  5255.8  322.61
  5265.6  322.91  5276.5  324.86    5287  327.71  5297.7  328.51  5351.1  337.45
  5366.2  338.78  5372.4  340.44  5383.1  341.02  5396.5  343.38  5436.5  346.41
#Mann= 5 ,-1 , 0
  4609.3     .16       0  4791.4     .12       0  4996.3     .07       0
  5002.3     .12       0  5276.5     .16       0
Bank Sta=4799.3,5195.3
XS Rating Curve= 0 ,0
Exp/Cntr=0.3,0.1

Type RM Length L Ch R = 1 ,1471    ,444,444,444
BEGIN DESCRIPTION:
BATSMITH CREEK 3.0
END DESCRIPTION:
XS GIS Cut Line= 3
      3646499.62     10613510.16      3646549.61     10613260.19
      3646249.62     10612460.21
#Sta/Elev= 30
  4734.2  340.28  4795.4  329.75  4877.7  318.48  4917.7  313.18  4958.5  309.28
  4991.8  310.66  4995.9  307.52  4998.7  307.02  5001.9  307.52  5010.5  310.31
  5138.6  308.78  5352.2  309.47  5406.5  308.04  5431.4  308.84  5480.4  312.98
  5485.6  313.31  5516.9  316.84    5530  320.08  5572.1  325.57  5587.2  328.71
  5602.3   329.6  5608.6  331.39  5651.3  336.56  5657.5  339.55  5687.8  344.59
  5702.1  348.56  5767.9  361.27  5779.4  361.88  5798.1  365.14  5843.5  367.65
#Mann= 7 ,-1 , 0
  4734.2     .16       0  4877.7     .12       0  4995.9     .07       0
  5001.9     .12       0  5485.6     .16       0    5530     .05       0
  5702.1     .16       0
Bank Sta=4917.7,5480.4
XS Rating Curve= 0 ,0
Exp/Cntr=0.3,0.1

Type RM Length L Ch R = 1 ,1027    ,547,547,547
BEGIN DESCRIPTION:
BATSMITH CREEK 2.0
END DESCRIPTION:
XS GIS Cut Line= 3
      3646849.61     10613410.19      3646799.61     10612960.19
      3646399.58     10612560.16
#Sta/Elev= 30
  4571.6  321.26  4583.4  319.72  4611.8  314.73    4642  311.55  4662.2   309.3
  4682.3  308.31  4722.5  309.24  4732.6  308.24  4752.7  308.87  4994.2  307.02
  5109.2  306.85  5137.5  307.44  5176.9  306.67  5179.7  306.17  5182.9  306.67
  5208.2  307.94  5250.6  308.56  5293.1   311.7  5377.9  315.94  5392.1  315.81
  5429.1  319.04  5448.6   320.6  5462.8  323.63  5476.9  325.32  5491.1  328.68
  5505.2  330.42  5519.3  333.81  5547.6  338.92  5586.5  345.13  5590.1  345.13
#Mann= 5 ,-1 , 0
  4571.6     .05       0  4583.4     .12       0  5176.9     .07       0
  5182.9     .12       0  5429.1     .05       0
Bank Sta=4642,5293.1
XS Rating Curve= 0 ,0
Exp/Cntr=0.3,0.1

Type RM Length L Ch R = 1 ,480     ,0,0,0
BEGIN DESCRIPTION:
BATSMITH CREEK 1.0
END DESCRIPTION:
XS GIS Cut Line= 4
      3646673.62     10613612.21      3647163.18      10613221.6
      3647163.18     10612580.98      3646465.23     10612060.12
#Sta/Elev= 30
  3912.1  343.71  4081.7  332.24  4116.9  328.09  4145.7  327.03    4181   322.4
  4249.3  316.73  4259.4  316.62  4294.6  312.26  4358.7  308.91    4522  306.55
  4599.8  307.26  5006.8  304.67  5009.6  304.17  5012.8  304.67  5048.7  308.09
  5069.8  309.84  5119.8  311.35  5268.4  309.92  5360.2  312.28  5424.8  315.51
  5489.4  320.48  5539.5  326.43  5554.1  329.31  5568.7  330.61  5645.8  344.66
  5689.6  349.35  5739.6  352.86  5789.6  354.02  5989.8   350.5  6049.9  351.07
#Mann= 5 ,-1 , 0
  3912.1     .05       0  4249.3     .12       0  5006.8     .07       0
  5012.8     .12       0  5048.7     .05       0
Bank Sta=4358.7,5069.8
XS Rating Curve= 0 ,0
Exp/Cntr=0.3,0.1

Chan Stop Cuts=-1
Use User Specified Reach Order=0
Composite Channel Slope=5