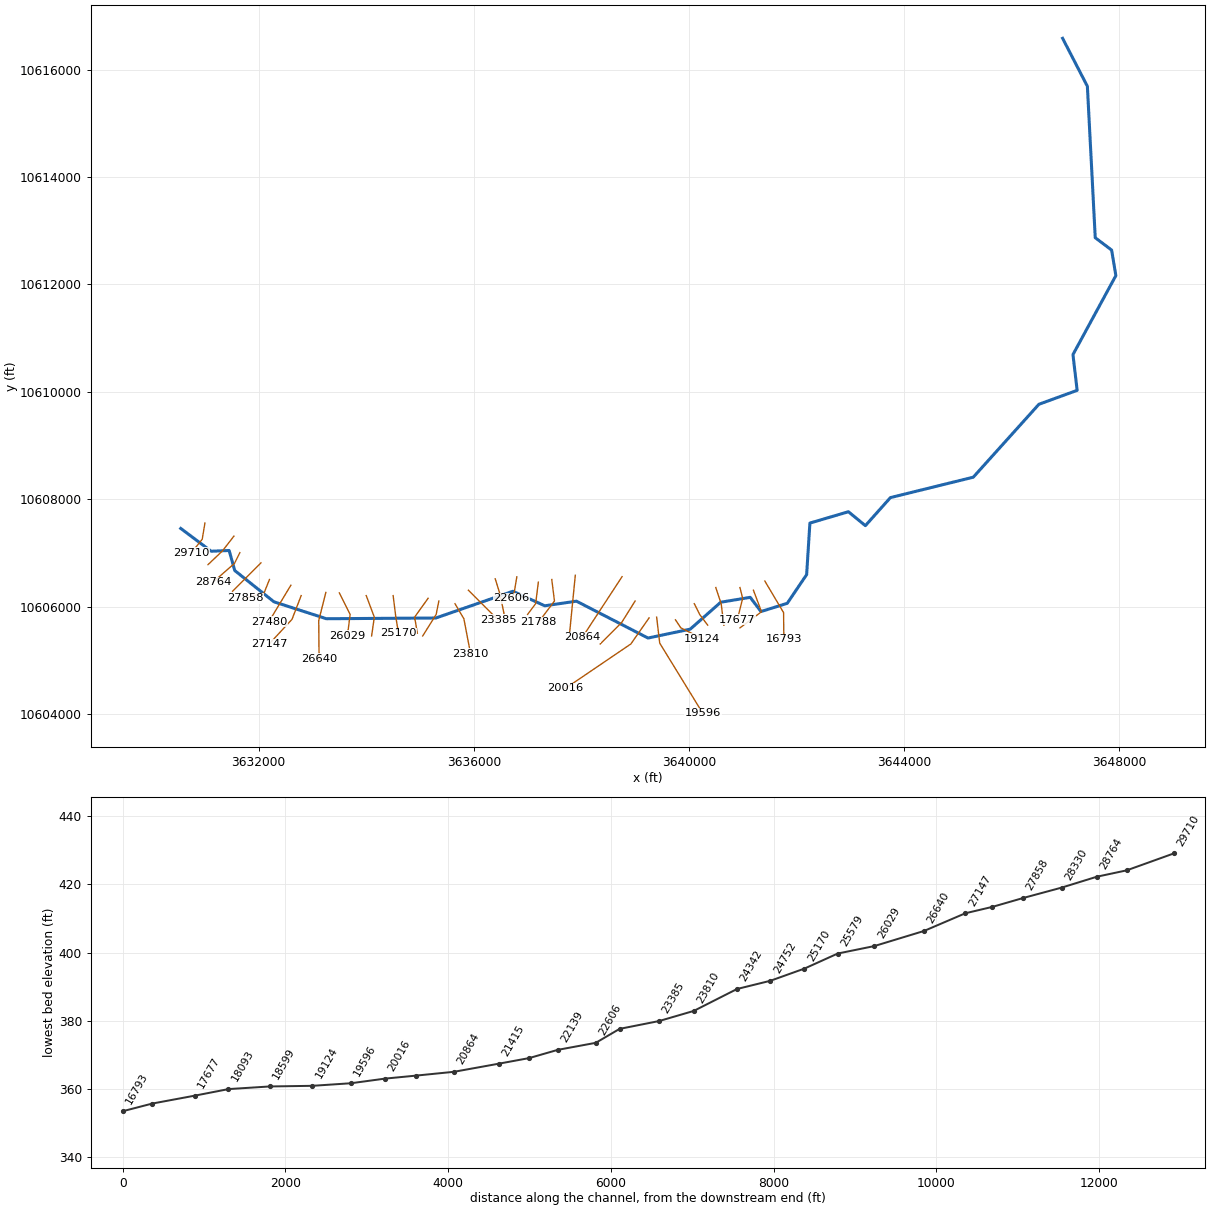
--- BRINKLEY CREEK.prj (project) ---

Proj Title=BRINKLEY CREEK Base Level Engineering
Current Plan=p01
Default Exp/Contr=0.3,0.1
English Units
Geom File=g01
Flow File=f01
Plan File=p01
Y Axis Title=Elevation
X Axis Title(PF)=Main Channel Distance
X Axis Title(XS)=Station
BEGIN DESCRIPTION:
BRINKLEY CREEK
END DESCRIPTION:
DSS File=dss
DSS Export Rating Curves= 0
DSS Export Rating Curve Sorted= 0
DSS Export Volume Flow Curves= 0
DXF OffsetX= 0
DXF OffsetY= 0
DXF ScaleX= 1
DXF ScaleY= 10

--- BRINKLEY CREEK.p01 (plan) ---

Plan Title=Multiple Run
Program Version=4.10
Short Identifier=Multiple Run
Geom File=g01
Flow File=f01
Subcritical Flow
K Sum by GR= 0
Std Step Tol= 0.01
Critical Tol= 0.01
Num of Std Step Trials= 20
Max Error Tol= 0.3
Flow Tol Ratio= 0.001
Split Flow NTrial= 30
Split Flow Tol= 0.02
Split Flow Ratio= 0.02
Log Output Level= 0
Friction Slope Method= 1
Unsteady Friction Slope Method= 2
Unsteady Bridges Friction Slope Method= 1
Parabolic Critical Depth
Global Vel Dist= 1 , 1 , 1
Global Log Level= 0
CheckData=True
Encroach Param=-1 ,0,0, 0
BEGIN DESCRIPTION:
Multiple Run
END DESCRIPTION:
Computation Interval=1HOUR
Output Interval=1HOUR
Run HTab= 0
Run UNet= 0
Run PostProcess= 0
Run WQNet= 0
UNET Theta= 1
UNET Theta Warmup= 1
UNET ZTol= 0.02
UNET ZSATol= 0.05
UNET MxIter= 20
UNET MaxInSteps= 0
UNET DtIC= 0
UNET DtMin= 0
UNET MaxCRTS= 20
UNET WFStab= 2
UNET SFStab= 1
UNET WFX= 1
UNET SFX= 1
UNET DSS MLevel= 4
UNET DZMax Abort= 100
UNET Convert EG Bridges= 0
UNET Use Existing IB Tables=-1
UNET Froude Reduction=False
UNET Froude Limit= 1
UNET Froude Power= 10
UNET Time Slicing=0,0, 5
UNET Junction Losses=0
Instantaneous Interval=1HOUR
DSS File=dss
Write IC File= 0
Write IC File at Sim End=0
Echo Input=False
Echo Parameters=False
Echo Output=False
Write Detailed= 0
WQ AD Non Conservative
WQ ULTIMATE=-1
WQ Max Comp Step=1HOUR
WQ Output Interval=15MIN
WQ Output Selected Increments= 0
WQ Output face flow=0
WQ Output face velocity=0
WQ Output face area=0
WQ Output face dispersion=0
WQ Output cell volume=0
WQ Output cell surface area=0
WQ Output cell continuity=0
WQ Output cumulative cell continuity=0
WQ Output face conc=0
WQ Output face dconc_dx=0
WQ Output face courant=0
WQ Output face peclet=0
WQ Output face adv mass=0
WQ Output face disp mass=0
WQ Output cell mass=0
WQ Output cell source sink temp=0
WQ Output cell source sink nsm=0
WQ Output MaxMinRange=-1
WQ Daily Max Min Mean=-1
WQ Daily Range=0
WQ Daily Time=0
WQ Create Restart=0
WQ Fixed Restart=0
WQ System Summary=0
WQ Use Fixed Temperature=0
Sorting and Armoring Iterations= 10
XS Update Threshold= 0.02
Hydraulics Update Threshold= 0.02
Energy Slope Method= 1
Volume Change Method= 0
XS Weighting Method= 0
Number of US Weighted Cross Sections= 1
Number of DS Weighted Cross Sections= 1
Upstream XS Weight=0.25
Main XS Weight=0.5
Downstream XS Weight=0.25
Number of DS XS's Weighted with US Boundary= 1
Upstream Boundary Weight= 1
Weight of XSs Associated with US Boundary= 0
Number of US XS's Weighted with DS Boundary= 1
Downstream Boundary Weight= 0.5
Weight of XSs Associated with DS Boundary= 0.5
Sediment Output Level= 4
Mass or Volume Output= 0
Output Increment Type= 1
Profile and TS Output Increment= 10
XS Output Flag= 0
XS Output Increment= 10
Disregard all LS=0
Disregard all Conn=0
Disregard all Breaches=0
Disregard all Pumps=0

--- BRINKLEY CREEK.f01 (steady flow) ---

Flow Title=Multiple
Program Version=4.10
Number of Profiles= 7
Profile Names=10-year,25-year,50-year,1pct_min,100-year,1pct_plu,500-year
River Rch & RM=BRINKLEY CREEK,Reach-1         ,29710
    1657    2330    2898    2627    3552    4804    5322
River Rch & RM=BRINKLEY CREEK,Reach-1         ,23385
    2430    3486    4394    4032    5452    7373    8373
River Rch & RM=BRINKLEY CREEK,Reach-1         ,18599
    2777    4005    5067    4664    6308    8531    9750
River Rch & RM=BRINKLEY CREEK,Reach-1         ,15746
    3129    4532    5749    5303    7171    9699   11133
River Rch & RM=BRINKLEY CREEK,Reach-1         ,13489
    3356    4876    6201    5736    7757   10490   12112
River Rch & RM=BRINKLEY CREEK,Reach-1         ,9477
    3286    4768    6059    5604    7579   10250   11852
River Rch & RM=BRINKLEY CREEK,Reach-1         ,4095
    4877    7181    9216    8599   11629   15727   18501
Boundary for River Rch & Prof#=BRINKLEY CREEK,Reach-1         , 1
Up Type= 0
Dn Type= 3
Dn Slope=0.019
Boundary for River Rch & Prof#=BRINKLEY CREEK,Reach-1         , 2
Up Type= 0
Dn Type= 3
Dn Slope=0.019
Boundary for River Rch & Prof#=BRINKLEY CREEK,Reach-1         , 3
Up Type= 0
Dn Type= 3
Dn Slope=0.019
Boundary for River Rch & Prof#=BRINKLEY CREEK,Reach-1         , 4
Up Type= 0
Dn Type= 3
Dn Slope=0.019
Boundary for River Rch & Prof#=BRINKLEY CREEK,Reach-1         , 5
Up Type= 0
Dn Type= 3
Dn Slope=0.019
Boundary for River Rch & Prof#=BRINKLEY CREEK,Reach-1         , 6
Up Type= 0
Dn Type= 3
Dn Slope=0.019
Boundary for River Rch & Prof#=BRINKLEY CREEK,Reach-1         , 7
Up Type= 0
Dn Type= 3
Dn Slope=0.019
DSS Import GetInterval= 0
DSS Import GetPeak= 0
DSS Import FillOption= 0

--- BRINKLEY CREEK.g01 (geometry) ---

Geom Title=Existing Conditions
Program Version=4.10

River Reach=BRINKLEY CREEK  ,Reach-1
Reach XY= 30
      3630549.61     10607460.19      3631116.75       10607036.
      3631449.75       10607050.      3631554.25       10606677.
      3632283.25       10606095.       3633258.5       10605780.
       3635294.5       10605794.        3636726.       10606291.
      3637319.25       10606021.      3637908.25       10606107.
      3639239.25       10605421.      3640024.25       10605586.
      3640591.25       10606087.        3641140.       10606178.
      3641340.25       10605914.       3641828.5       10606067.
        3642189.       10606601.       3642249.5       10607560.
        3642966.       10607771.       3643281.5       10607512.
        3643747.       10608034.        3645288.       10608414.
      3646507.75       10609770.       3647219.5       10610030.
      3647141.25       10610695.      3647939.25       10612165.
       3647860.5       10612640.        3647556.       10612870.
       3647409.5       10615688.        3646949.       10616580.

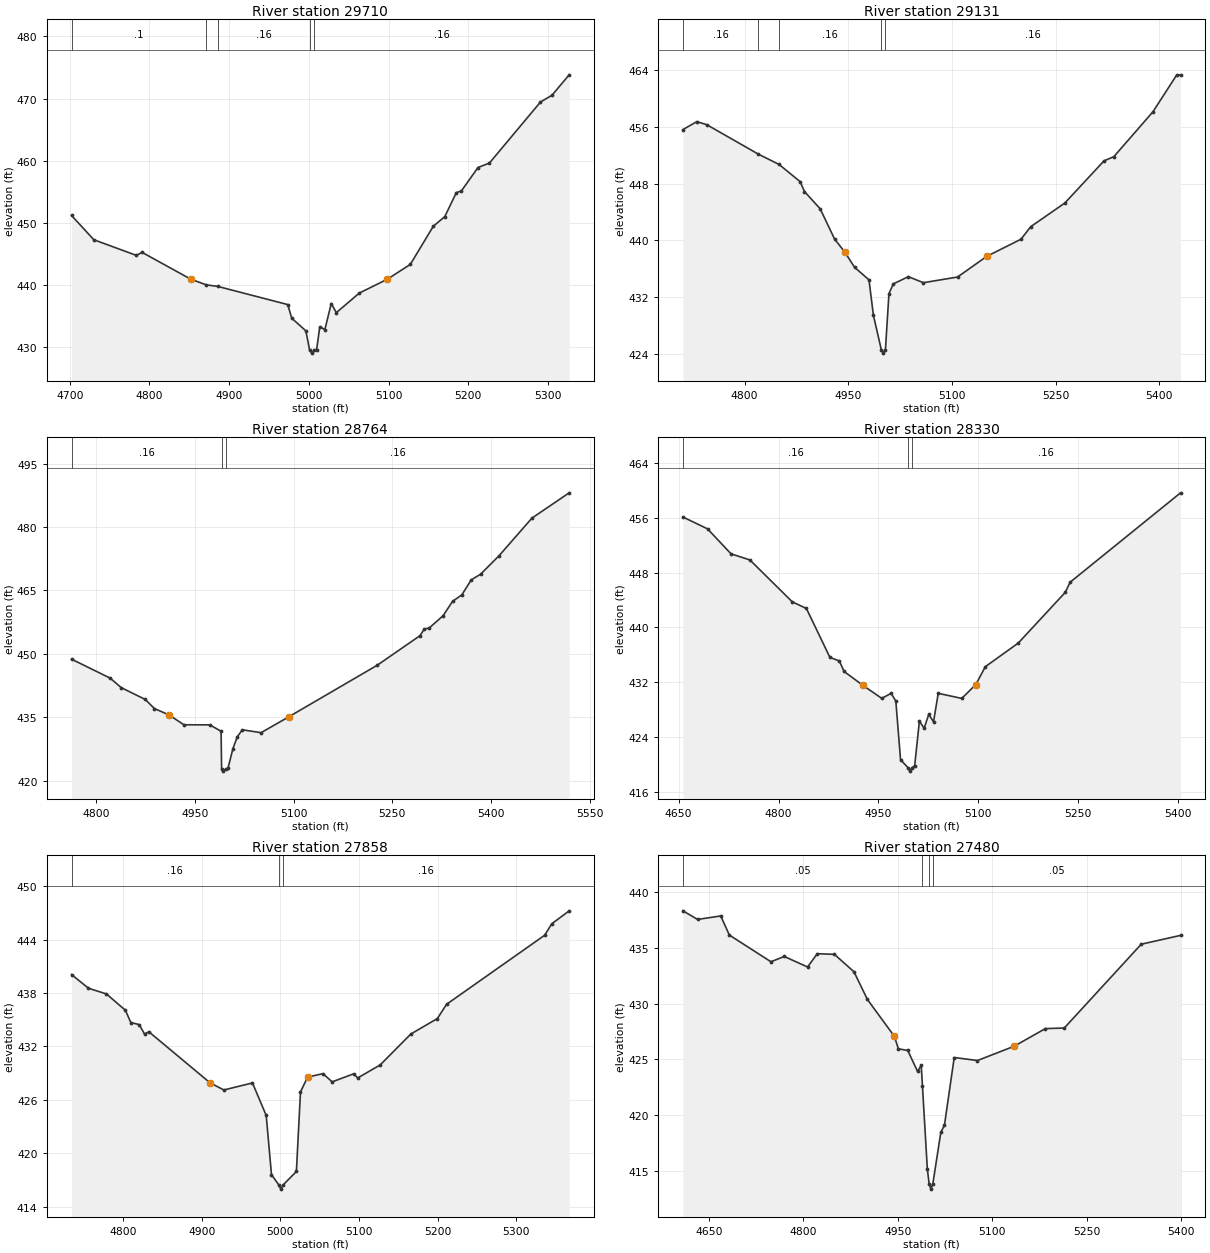
Type RM Length L Ch R = 1 ,29710   ,579,579,579
BEGIN DESCRIPTION:
BRINKLEY CREEK 61.0
END DESCRIPTION:
XS GIS Cut Line= 3
      3630999.62     10607560.23      3630949.61     10607260.19
      3630749.63     10607010.21
#Sta/Elev= 30
  4702.3  451.19  4730.2  447.29  4783.4  444.78    4791  445.24  4851.9  440.94
  4871.3  440.03  4885.4  439.79  4973.5  436.86  4978.6  434.66  4996.3  432.63
  5000.9  429.55  5003.7  429.05  5006.9  429.55  5009.7  429.55  5013.7  433.29
  5020.1  432.84  5028.1  437.03  5034.5  435.56  5063.3  438.71  5098.5  440.94
  5127.3  443.32  5156.1  449.45  5170.6  451.02    5185  454.86  5191.4  455.14
  5212.2   458.9  5226.6  459.63  5290.6  469.44    5305  470.52  5326.6  473.81
#Mann= 5 ,-1 , 0
  4702.3      .1       0  4871.3     .05       0  4885.4     .16       0
  5000.9     .07       0  5006.9     .16       0
Bank Sta=4851.9,5098.5
XS Rating Curve= 0 ,0
Exp/Cntr=0.3,0.1

Type RM Length L Ch R = 1 ,29131   ,367,367,367
BEGIN DESCRIPTION:
BRINKLEY CREEK 60.0
END DESCRIPTION:
XS GIS Cut Line= 3
      3631539.42     10607318.01      3631324.14     10607040.23
      3631056.75     10606786.73
#Sta/Elev= 30
  4710.8  455.61    4731  456.73  4745.5  456.29  4819.7  452.16    4850  450.69
  4880.4  448.27  4886.7  446.87  4909.4  444.44  4930.2  440.18  4944.7  438.38
  4959.1   436.2    4980  434.42  4986.4  429.42  4997.8  424.59  5000.5  424.09
  5003.8  424.59  5008.9  432.49  5015.3  433.86    5037  434.87  5058.7  434.02
  5108.1  434.82  5150.5  437.74  5199.9  440.15    5214  441.92  5263.4  445.26
    5320   451.2  5334.2  451.79  5390.8  458.12  5425.3  463.33  5430.7  463.33
#Mann= 5 ,-1 , 0
  4710.8     .16       0  4819.7      .1       0    4850     .16       0
  4997.8     .07       0  5003.8     .16       0
Bank Sta=4944.7,5150.5
XS Rating Curve= 0 ,0
Exp/Cntr=0.3,0.1

Type RM Length L Ch R = 1 ,28764   ,434,434,434
BEGIN DESCRIPTION:
BRINKLEY CREEK 59.0
END DESCRIPTION:
XS GIS Cut Line= 3
      3631649.59     10607010.15      3631549.61     10606810.19
      3631149.59     10606460.17
#Sta/Elev= 30
  4763.2  448.72  4821.9  444.22  4838.6  441.98    4875  439.19  4888.9  437.04
  4911.3   435.5  4933.7  433.19  4972.8  433.17  4990.1  431.67  4990.9  422.72
  4993.6  422.22  4996.9  422.72  5000.5  422.86  5008.1  427.57  5014.8  430.38
  5022.4     432  5050.8  431.32  5093.1   435.1  5227.4  447.32  5291.9  454.28
  5298.6  455.87  5305.7  456.07    5327  459.01  5341.3  462.39  5355.5  463.96
  5369.7  467.49    5384  468.85    5412  473.22  5461.8  482.11  5518.3  488.09
#Mann= 3 ,-1 , 0
  4763.2     .16       0  4990.9     .07       0  4996.9     .16       0
Bank Sta=4911.3,5093.1
XS Rating Curve= 0 ,0
Exp/Cntr=0.3,0.1

Type RM Length L Ch R = 1 ,28330   ,472,472,472
BEGIN DESCRIPTION:
BRINKLEY CREEK 58.0
END DESCRIPTION:
XS GIS Cut Line= 2
      3632042.06     10606820.06      3631513.57     10606291.56
#Sta/Elev= 30
  4656.4  456.13  4693.4   454.4  4728.7  450.75    4757  449.86  4820.7  443.74
  4841.9  442.77  4877.2  435.63  4891.4  435.11  4898.5  433.57  4926.7  431.55
    4955  429.65  4969.2  430.38  4976.2  429.25  4983.3  420.69  4994.5  419.52
  4997.2  419.02  5000.5  419.52  5004.5   419.8  5011.6  426.33  5018.7  425.27
  5025.7  427.32  5032.8  426.21  5039.9  430.38  5075.2  429.64  5096.4  431.67
  5110.6  434.27  5160.1  437.72  5230.8  445.14  5237.9   446.6  5403.8  459.66
#Mann= 3 ,-1 , 0
  4656.4     .16       0  4994.5     .07       0  5000.5     .16       0
Bank Sta=4926.7,5096.4
XS Rating Curve= 0 ,0
Exp/Cntr=0.3,0.1

Type RM Length L Ch R = 1 ,27858   ,378,378,378
BEGIN DESCRIPTION:
BRINKLEY CREEK 57.0
END DESCRIPTION:
XS GIS Cut Line= 3
       3632199.6     10606510.17      3632099.61     10606260.19
      3631749.65      10606160.2
#Sta/Elev= 30
  4734.3  440.07  4755.8  438.53  4778.7  437.89  4802.9  436.05  4809.7  434.68
  4820.4  434.45  4827.2  433.38  4832.6  433.65  4910.6  427.91  4928.1  427.11
  4964.5   427.9    4982  424.25  4988.7  417.61  4997.8  416.48  5000.6  415.98
  5003.8  416.48  5020.4  417.96  5025.6  426.89  5034.7  428.56  5054.2  428.94
  5065.9  428.02  5093.2  428.92  5098.4  428.46    5127  429.92    5166  433.39
  5199.8  435.13  5211.5  436.73  5336.3  444.48  5345.4  445.77  5367.5  447.22
#Mann= 3 ,-1 , 0
  4734.3     .16       0  4997.8     .07       0  5003.8     .16       0
Bank Sta=4910.6,5034.7
XS Rating Curve= 0 ,0
Exp/Cntr=0.3,0.1

Type RM Length L Ch R = 1 ,27480   ,333,333,333
BEGIN DESCRIPTION:
BRINKLEY CREEK 56.0
END DESCRIPTION:
XS GIS Cut Line= 2
      3632597.64     10606403.41      3632189.65     10605726.33
#Sta/Elev= 30
  4608.7  438.31    4632  437.54  4668.8  437.85  4682.5  436.14  4748.5  433.75
  4769.8  434.22  4806.7  433.28  4822.2  434.47  4849.4  434.41  4880.5  432.85
  4901.8  430.37  4944.6  427.07    4951  425.95  4965.9   425.8  4981.5  423.92
  4987.3  424.48  4989.2  422.66    4997  415.18  4999.8  413.88  5002.6  413.38
  5005.8  413.88  5018.4  418.46  5024.2  419.11  5039.7  425.17  5076.6   424.9
  5134.9  426.18  5184.5  427.76  5214.5  427.81  5336.8  435.32  5399.2  436.11
#Mann= 4 ,-1 , 0
  4608.7     .05       0  4989.2     .16       0  4999.8     .07       0
  5005.8     .05       0
Bank Sta=4944.6,5134.9
XS Rating Curve= 0 ,0
Exp/Cntr=0.3,0.1

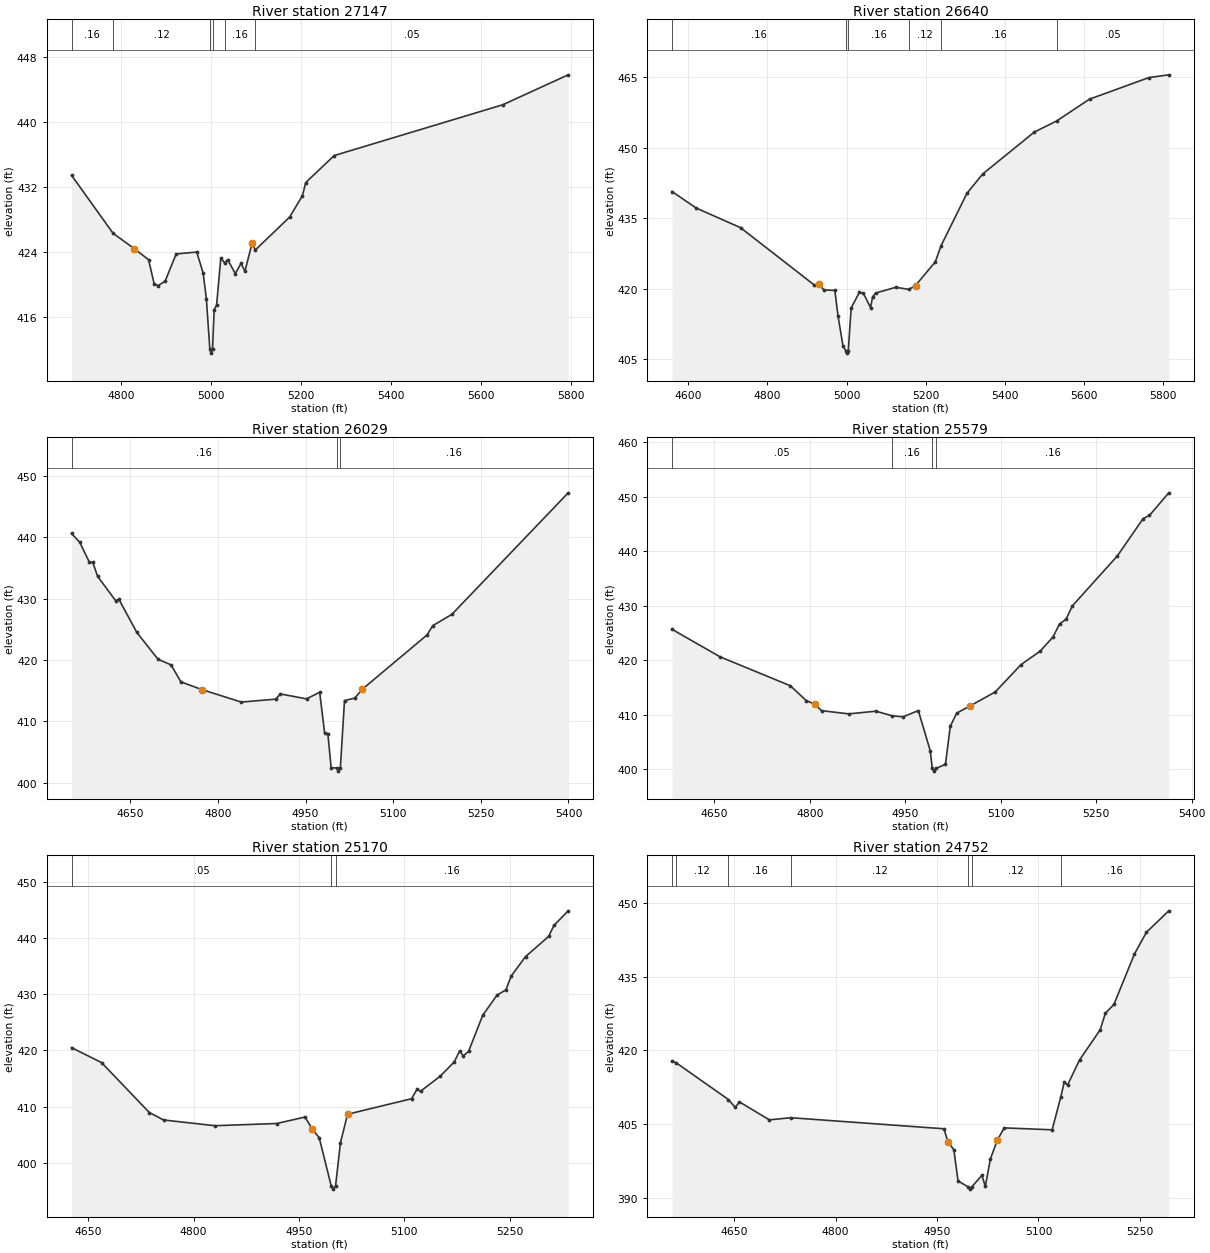
Type RM Length L Ch R = 1 ,27147   ,507,507,507
BEGIN DESCRIPTION:
BRINKLEY CREEK 55.0
END DESCRIPTION:
XS GIS Cut Line= 3
      3632789.42     10606210.38      3632619.28      10605769.4
      3632189.19     10605304.63
#Sta/Elev= 30
  4688.7  433.43  4781.3  426.27  4828.2  424.39  4860.4  423.01  4872.6  420.07
  4881.8  419.82  4897.2  420.38  4921.8  423.73  4967.6  423.96  4981.8  421.37
    4989  418.21  4996.7     412  4999.5   411.5  5002.7     412  5006.4  416.87
  5011.7  417.39  5021.2  423.25  5029.5  422.61  5036.3  423.04  5053.3  421.31
  5066.3  422.57  5074.8  421.59  5090.9  425.08  5097.8  424.21  5174.5  428.28
  5202.8   430.9  5210.2  432.53  5273.7  435.86    5649  442.12  5794.6  445.81
#Mann= 6 ,-1 , 0
  4688.7     .16       0  4781.3     .12       0  4996.7     .07       0
  5002.7     .12       0  5029.5     .16       0  5097.8     .05       0
Bank Sta=4828.2,5090.9
XS Rating Curve= 0 ,0
Exp/Cntr=0.3,0.1

Type RM Length L Ch R = 1 ,26640   ,611,611,611
BEGIN DESCRIPTION:
BRINKLEY CREEK 54.0
END DESCRIPTION:
XS GIS Cut Line= 3
      3633247.76     10606269.41      3633115.81      10605745.1
      3633122.75     10605029.79
#Sta/Elev= 30
  4558.7  440.69  4619.8  437.18  4731.8  433.01  4918.8  420.78  4929.1  421.06
  4942.5  419.76  4970.4  419.66  4978.4  414.21    4991  407.83  4998.3  406.82
  5001.1  406.32  5004.3  406.82  5011.6  415.93  5032.2  419.22  5042.5  419.06
  5060.7     416  5065.8  418.27  5073.5   419.1  5124.3  420.32  5157.7  419.88
  5174.3   420.7  5224.3  425.73  5239.2  429.21  5304.3  440.31  5344.3  444.43
  5474.3  453.32  5530.9  455.69  5614.3  460.34  5764.3  464.93  5814.7  465.52
#Mann= 6 ,-1 , 0
  4558.7     .16       0  4998.3     .07       0  5004.3     .16       0
  5157.7     .12       0  5239.2     .16       0  5530.9     .05       0
Bank Sta=4929.1,5174.3
XS Rating Curve= 0 ,0
Exp/Cntr=0.3,0.1

Type RM Length L Ch R = 1 ,26029   ,450,450,450
BEGIN DESCRIPTION:
BRINKLEY CREEK 53.0
END DESCRIPTION:
XS GIS Cut Line= 3
      3633499.59     10606260.22      3633699.61     10605860.19
       3633649.6     10605460.15
#Sta/Elev= 30
  4549.2  440.63  4563.2  439.21    4580  435.91  4585.6  435.91    4594  433.63
  4624.7  429.69  4630.3  429.91    4661  424.51  4697.4  420.12  4719.7  419.21
  4736.5  416.44  4772.8  415.17  4839.9  413.15  4898.6  413.62    4907  414.47
  4951.7  413.67  4974.1  414.75  4982.5  408.15  4988.1  408.01  4993.7  402.46
  5003.5  402.39  5006.3  401.89  5009.5  402.39  5016.6  413.39  5034.2   413.8
  5046.8  415.22  5157.7  424.07  5167.8  425.61  5200.5  427.45  5399.6  447.26
#Mann= 3 ,-1 , 0
  4549.2     .16       0  5003.5     .07       0  5009.5     .16       0
Bank Sta=4772.8,5046.8
XS Rating Curve= 0 ,0
Exp/Cntr=0.3,0.1

Type RM Length L Ch R = 1 ,25579   ,409,409,409
BEGIN DESCRIPTION:
BRINKLEY CREEK 52.0
END DESCRIPTION:
XS GIS Cut Line= 3
      3633999.62     10606210.17      3634149.61     10605810.19
      3634099.61     10605460.22
#Sta/Elev= 30
  4583.3   425.7  4658.9  420.65  4769.3  415.35  4794.2  412.63  4807.6  411.99
  4818.2  410.79    4861   410.2  4903.7  410.69    4929  409.85  4946.4  409.66
  4970.4   410.8  4989.1  403.44  4992.3   400.2  4995.1   399.7  4998.3   400.2
    5013  400.95  5020.6  407.92  5030.7  410.34  5050.9   411.6  5091.3  414.22
  5131.7  419.22    5162  421.71  5182.2  424.32  5192.3  426.69  5202.4  427.53
  5212.5     430  5283.2  439.16  5323.6  445.98  5333.7   446.6    5364  450.73
#Mann= 4 ,-1 , 0
  4583.3     .05       0    4929     .16       0  4992.3     .07       0
  4998.3     .16       0
Bank Sta=4807.6,5050.9
XS Rating Curve= 0 ,0
Exp/Cntr=0.3,0.1

Type RM Length L Ch R = 1 ,25170   ,418,418,418
BEGIN DESCRIPTION:
BRINKLEY CREEK 51.0
END DESCRIPTION:
XS GIS Cut Line= 3
      3634499.61     10606210.16      3634549.61     10605810.19
       3634599.6     10605510.22
#Sta/Elev= 30
  4626.1   420.5  4668.9  417.83  4736.9  408.94  4757.1  407.61  4830.2  406.59
  4918.3  406.98  4958.6  408.13  4968.7  406.02  4978.8  404.44    4996  395.79
  4998.7  395.29    5002  395.79    5009  403.52  5019.1  408.63  5110.3   411.4
  5117.9  413.06    5123  412.73  5150.8  415.38  5171.1  417.96  5178.7  419.91
  5183.8  419.03  5191.4  419.81  5211.7  426.29  5231.9  429.83  5244.6   430.8
  5252.2  433.26  5272.5  436.71  5305.4   440.3  5313.1  442.29  5333.3  444.87
#Mann= 3 ,-1 , 0
  4626.1     .05       0    4996     .07       0    5002     .16       0
Bank Sta=4968.7,5019.1
XS Rating Curve= 0 ,0
Exp/Cntr=0.3,0.1

Type RM Length L Ch R = 1 ,24752   ,410,410,410
BEGIN DESCRIPTION:
BRINKLEY CREEK 50.0
END DESCRIPTION:
XS GIS Cut Line= 3
      3635149.63     10606160.22      3634899.61     10605810.19
      3634949.61     10605510.18
#Sta/Elev= 30
  4558.3  417.84    4564  417.48  4641.6  409.97  4651.7  408.36  4657.9  409.48
  4702.1  405.83  4734.1  406.26  4960.2  404.01  4966.3  401.31  4974.9  399.75
  4981.1  393.38  4995.6  392.22  4998.3  391.72  5001.6  392.22  5016.3  394.51
  5021.4  392.31    5029  397.89  5039.1  401.67  5049.3  404.19  5120.2   403.8
  5132.9  410.43    5138  413.47  5143.1  412.95  5160.8  418.04  5191.2  424.16
  5198.8  427.51  5211.5  429.32  5241.9  439.61  5259.6  444.02  5292.6  448.39
#Mann= 7 ,-1 , 0
  4558.3     .16       0    4564     .12       0  4641.6     .16       0
  4734.1     .12       0  4995.6     .07       0  5001.6     .12       0
  5132.9     .16       0
Bank Sta=4966.3,5039.1
XS Rating Curve= 0 ,0
Exp/Cntr=0.3,0.1

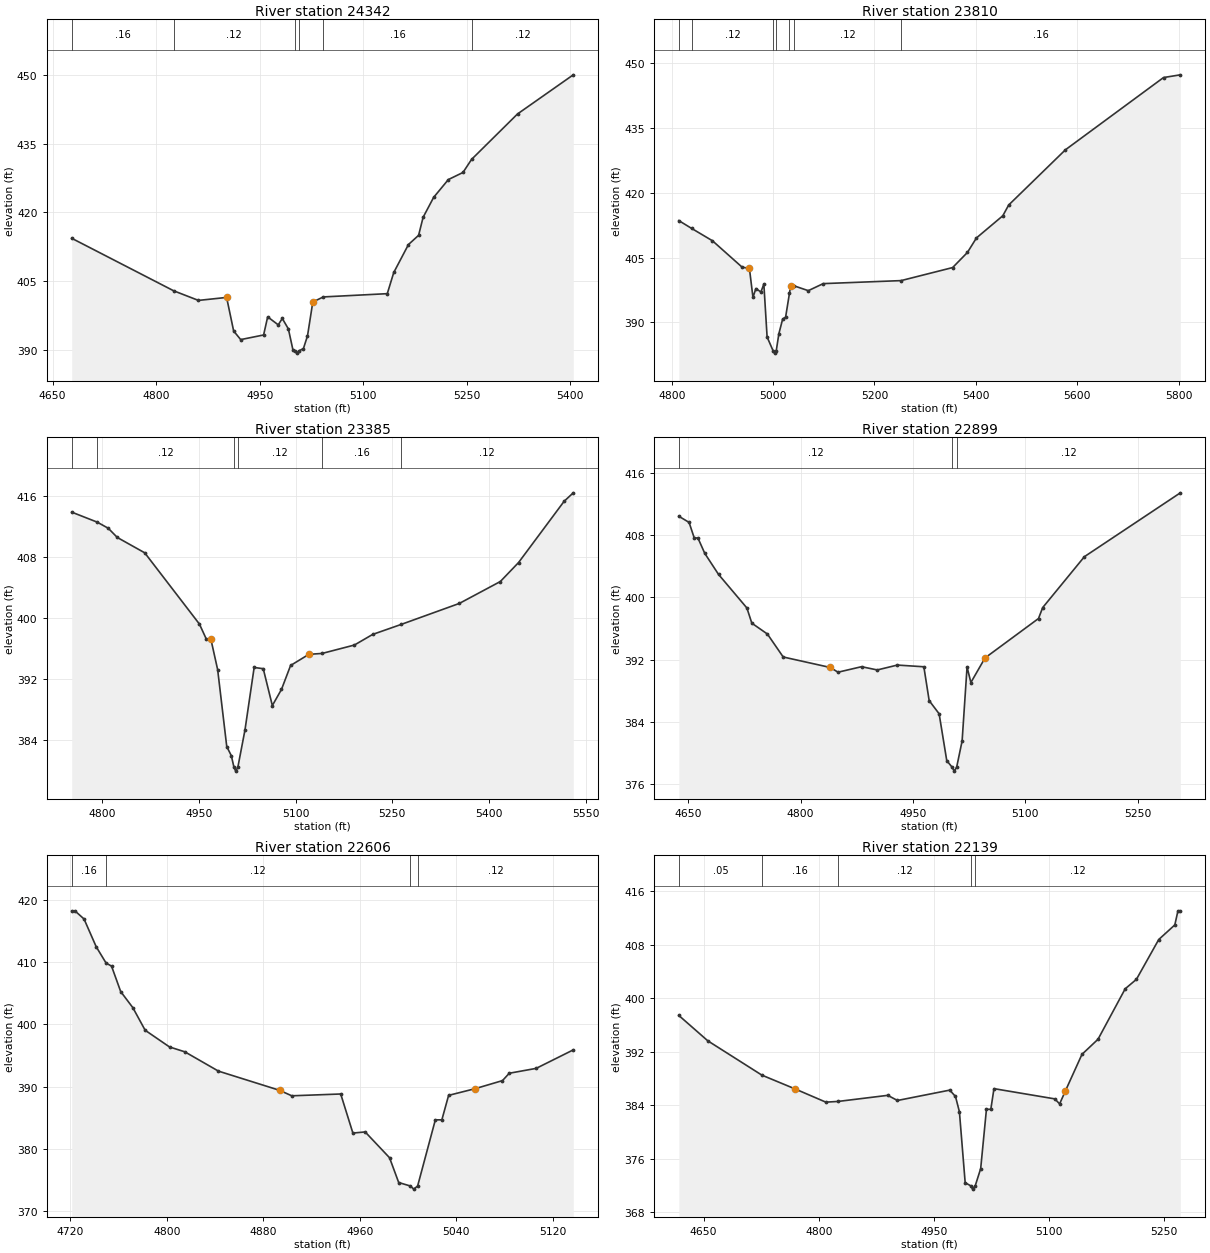
Type RM Length L Ch R = 1 ,24342   ,532,532,532
BEGIN DESCRIPTION:
BRINKLEY CREEK 49.0
END DESCRIPTION:
XS GIS Cut Line= 3
      3635349.61      10606110.2      3635299.61     10605860.19
      3635049.59     10605460.16
#Sta/Elev= 30
  4677.7  414.36  4825.5   402.9  4861.3  400.81  4902.1  401.46  4912.3  394.14
  4922.5  392.26  4955.7  393.27  4961.6  397.22  4976.9  395.48  4982.8  396.87
  4991.6  394.59  4998.1  390.09    5001  389.81  5003.8  389.31    5007  389.81
  5013.4  390.31  5019.3  393.06    5027  400.46  5042.2  401.57  5134.9  402.28
  5144.3   406.9  5165.6     413  5180.3  415.01  5186.8  418.93  5202.1  423.29
  5223.4  427.17  5244.6  428.72  5257.1  431.58  5323.6  441.48  5404.4  450.02
#Mann= 6 ,-1 , 0
  4677.7     .16       0  4825.5     .12       0    5001     .07       0
    5007     .12       0  5042.2     .16       0  5257.1     .12       0
Bank Sta=4902.1,5027
XS Rating Curve= 0 ,0
Exp/Cntr=0.3,0.1

Type RM Length L Ch R = 1 ,23810   ,425,425,425
BEGIN DESCRIPTION:
BRINKLEY CREEK 48.0
END DESCRIPTION:
XS GIS Cut Line= 3
      3635649.61     10606060.18       3635814.8      10605780.3
       3635939.8     10605127.55
#Sta/Elev= 30
    4814  413.56  4839.2  411.76  4880.4  408.89  4938.9  402.78  4953.3   402.5
  4960.3  395.78  4966.1  397.83    4976  397.03  4981.8  398.87  4988.2  386.62
  5000.2  383.38    5003  382.88  5006.2  383.38  5011.4  387.35  5018.9  390.78
  5024.7   391.2  5032.3  396.72  5034.5  398.32  5041.6  398.45  5069.5  397.34
  5098.9  398.97  5252.6  399.67  5354.3  402.69  5383.5  406.19  5401.3  409.55
  5453.3  414.68  5464.9  417.17  5576.9  429.96  5770.4  446.68  5803.6  447.31
#Mann= 7 ,-1 , 0
    4814     .16       0  4839.2     .12       0  5000.2     .07       0
  5006.2     .12       0  5032.3     .16       0  5041.6     .12       0
  5252.6     .16       0
Bank Sta=4953.3,5034.5
XS Rating Curve= 0 ,0
Exp/Cntr=0.3,0.1

Type RM Length L Ch R = 1 ,23385   ,486,486,486
BEGIN DESCRIPTION:
BRINKLEY CREEK 47.0
END DESCRIPTION:
XS GIS Cut Line= 3
      3635899.59      10606310.2      3636049.61     10606160.19
      3636449.58     10605760.22
#Sta/Elev= 30
  4752.8  413.85  4792.3  412.54  4809.4  411.74  4823.5  410.53    4866  408.52
  4950.8  399.19  4961.4  397.24  4968.5  397.24  4979.1  393.21  4993.2  383.14
  5000.3  381.94  5004.4  380.42  5007.1  379.92  5010.4  380.42  5021.5  385.33
  5035.7   393.5  5049.8  393.34  5063.9  388.51  5078.1  390.63  5092.2  393.76
  5120.5  395.22  5141.1  395.34  5191.2  396.44  5219.5  397.83  5263.4  399.13
  5353.9  401.89  5417.5  404.76  5445.8  407.25  5516.5  415.28  5530.6  416.38
#Mann= 6 ,-1 , 0
  4752.8     .16       0  4792.3     .12       0  5004.4     .07       0
  5010.4     .12       0  5141.1     .16       0  5263.4     .12       0
Bank Sta=4968.5,5120.5
XS Rating Curve= 0 ,0
Exp/Cntr=0.3,0.1

Type RM Length L Ch R = 1 ,22899   ,293,293,293
BEGIN DESCRIPTION:
BRINKLEY CREEK 46.0
END DESCRIPTION:
XS GIS Cut Line= 3
      3636398.15     10606523.32      3636488.41     10606231.69
      3636561.21     10605874.62
#Sta/Elev= 30
  4637.3  410.47    4651  409.68  4657.7  407.73    4663  407.63    4672  405.68
  4690.3  402.98  4728.2  398.65  4734.8  396.69  4755.6  395.29  4776.7  392.33
  4839.5  390.98  4849.9  390.37  4881.3  391.08  4902.3  390.66  4929.1  391.29
  4964.5  391.07  4971.6  386.71  4984.9  385.01  4995.1  378.97  5002.3  378.12
  5005.1  377.62  5008.3  378.12  5015.6  381.51  5022.2  391.05  5027.3  389.04
  5046.2  392.21  5117.6  397.29  5123.2   398.7  5178.9  405.26    5307  413.49
#Mann= 3 ,-1 , 0
  4637.3     .12       0  5002.3     .07       0  5008.3     .12       0
Bank Sta=4839.5,5046.2
XS Rating Curve= 0 ,0
Exp/Cntr=0.3,0.1

Type RM Length L Ch R = 1 ,22606   ,467,467,467
BEGIN DESCRIPTION:
BRINKLEY CREEK 45.0
END DESCRIPTION:
XS GIS Cut Line= 3
      3636799.62     10606560.23      3636749.61     10606260.19
       3636699.6     10606160.17
#Sta/Elev= 30
  4721.2   418.2  4723.8   418.2  4731.4  416.89  4741.5  412.43  4749.7  409.81
  4754.2  409.33  4761.8  405.24  4771.9  402.65  4782.1  399.03  4802.3  396.35
    4815  395.57  4842.9  392.47  4893.6  389.39  4903.7  388.51  4944.3   388.8
  4954.4  382.53  4964.6  382.71  4984.8  378.57  4992.4  374.59  5002.1  374.03
  5004.9  373.53  5008.1  374.03  5022.8  384.65  5028.2  384.65  5033.8  388.58
  5056.1  389.67  5078.5  390.95  5084.1  392.13  5106.4  392.91  5137.2  395.88
#Mann= 4 ,-1 , 0
  4721.2     .16       0  4749.7     .12       0  5002.1     .07       0
  5008.1     .12       0
Bank Sta=4893.6,5056.1
XS Rating Curve= 0 ,0
Exp/Cntr=0.3,0.1

Type RM Length L Ch R = 1 ,22139   ,351,351,351
BEGIN DESCRIPTION:
BRINKLEY CREEK 44.0
END DESCRIPTION:
XS GIS Cut Line= 3
      3637199.61     10606460.22      3637149.61     10606060.19
      3636999.64     10605860.23
#Sta/Elev= 30
  4617.7  397.45  4655.5  393.65  4725.9  388.52  4768.9  386.47  4809.2  384.48
  4825.3  384.59  4889.8   385.5  4902.4  384.73  4970.5  386.28    4978  385.33
  4983.1  383.04  4990.6  372.44  4997.7  371.97  5000.4  371.47  5003.7  371.97
  5010.8  374.54  5018.3  383.41    5024  383.41  5028.1   386.5  5107.3  384.97
  5113.6  384.22  5120.8  386.08  5142.7  391.63  5163.6  393.89    5199  401.44
  5213.6  402.85  5242.7  408.81  5263.6  410.99  5267.7   413.1  5270.8   413.1
#Mann= 5 ,-1 , 0
  4617.7     .05       0  4725.9     .16       0  4825.3     .12       0
  4997.7     .07       0  5003.7     .12       0
Bank Sta=4768.9,5120.8
XS Rating Curve= 0 ,0
Exp/Cntr=0.3,0.1

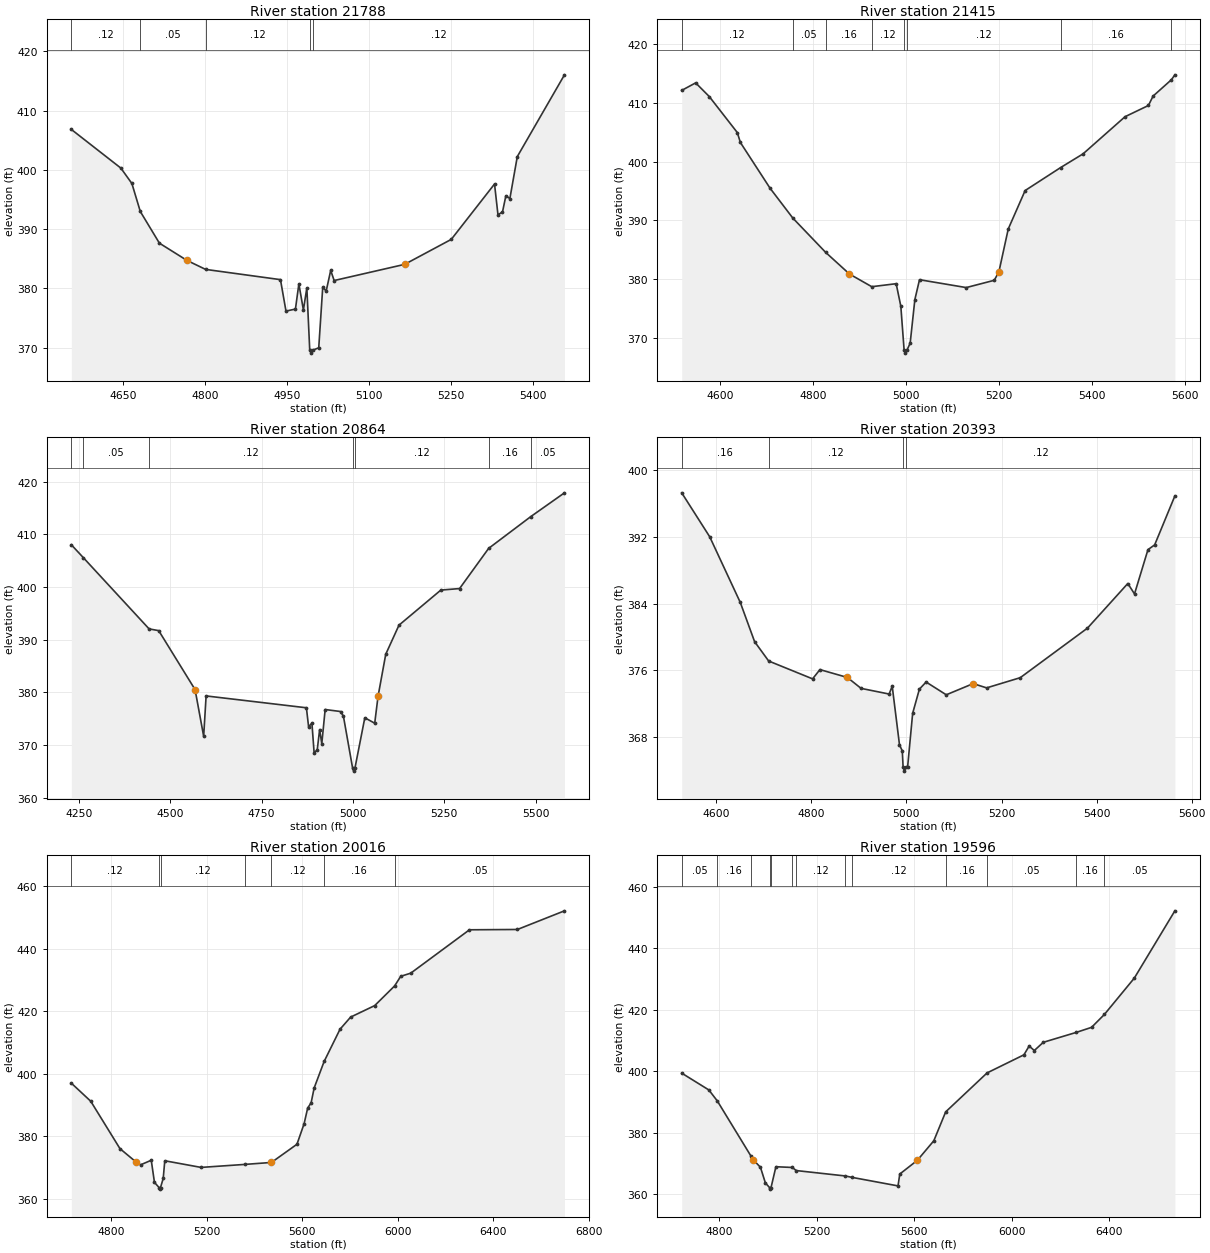
Type RM Length L Ch R = 1 ,21788   ,373,373,373
BEGIN DESCRIPTION:
BRINKLEY CREEK 43.0
END DESCRIPTION:
XS GIS Cut Line= 3
      3637449.61     10606510.21      3637499.61     10606110.19
      3637199.63     10605710.22
#Sta/Elev= 30
  4555.4  406.84  4646.1  400.31  4666.3  397.71  4681.7  392.98  4716.7  387.63
  4767.1  384.72  4801.3   383.2  4938.4  381.47  4948.5  376.16  4965.8   376.5
  4972.1  380.75  4980.4  376.35  4986.7  380.09    4992  369.56  4994.7  369.06
    4998  369.56  5008.5  369.97  5015.8  380.19  5022.1  379.54  5030.4  383.03
  5036.7  381.32  5165.8  384.05  5251.2  388.27  5330.4  397.62  5336.7  392.43
    5345   392.9  5351.2  395.64  5358.5  395.16  5372.1  402.25  5458.5  416.06
#Mann= 5 ,-1 , 0
  4555.4     .12       0  4681.7     .05       0  4801.3     .12       0
    4992     .07       0    4998     .12       0
Bank Sta=4767.1,5165.8
XS Rating Curve= 0 ,0
Exp/Cntr=0.3,0.1

Type RM Length L Ch R = 1 ,21415   ,551,551,551
BEGIN DESCRIPTION:
BRINKLEY CREEK 42.0
END DESCRIPTION:
XS GIS Cut Line= 2
      3637887.14     10606589.23      3637783.14     10605533.54
#Sta/Elev= 30
  4517.6  412.15  4547.6  413.43  4576.9   411.1  4637.2  404.97  4643.8  403.28
  4707.6   395.5  4756.6  390.41  4827.4  384.56  4878.4  380.89  4926.4  378.73
  4978.9  379.24  4988.9  375.41    4996  367.92  4998.7  367.42    5002  367.92
    5009  369.11  5019.1  376.54  5029.1  379.92  5129.6  378.58  5189.9  379.82
  5199.9  381.27    5220  388.56  5256.3   395.1  5332.4     399  5380.8  401.34
  5471.2  407.67  5521.5  409.58  5531.5  411.18  5570.9  413.96  5578.4   414.8
#Mann= 8 ,-1 , 0
  4517.6     .12       0  4756.6     .05       0  4827.4     .16       0
  4926.4     .12       0    4996     .07       0    5002     .12       0
  5332.4     .16       0  5570.9     .05       0
Bank Sta=4878.4,5199.9
XS Rating Curve= 0 ,0
Exp/Cntr=0.3,0.1

Type RM Length L Ch R = 1 ,20864   ,471,471,471
BEGIN DESCRIPTION:
BRINKLEY CREEK 41.0
END DESCRIPTION:
XS GIS Cut Line= 2
      3638756.94     10606563.15      3638018.11      10605434.1
#Sta/Elev= 30
  4229.4  408.03  4262.1  405.59  4442.2  392.05  4468.5  391.72    4568  380.52
  4591.5  371.66  4598.2  379.32  4872.6  377.07  4878.6  373.46  4887.7  374.15
  4893.7  368.52  4902.2  369.07  4908.8  372.93  4914.7  370.25  4923.9  376.74
    4966  376.36  4973.9  375.46  4999.2  365.54    5002  365.04  5005.2  365.54
  5032.4  375.17  5059.5  374.14  5068.6  379.23  5089.7  387.24  5125.9  392.76
  5240.4  399.42  5291.7  399.71  5371.2  407.34  5486.8  413.39  5578.7  417.89
#Mann= 7 ,-1 , 0
  4229.4     .16       0  4262.1     .05       0  4442.2     .12       0
  4999.2     .07       0  5005.2     .12       0  5371.2     .16       0
  5486.8     .05       0
Bank Sta=4568,5068.6
XS Rating Curve= 0 ,0
Exp/Cntr=0.3,0.1

Type RM Length L Ch R = 1 ,20393   ,377,377,377
BEGIN DESCRIPTION:
BRINKLEY CREEK 40.0
END DESCRIPTION:
XS GIS Cut Line= 3
       3638999.6     10606110.17      3638749.61     10605710.19
      3638349.58     10605310.16
#Sta/Elev= 30
  4527.3  397.27  4586.2     392  4650.5  384.13  4680.6  379.43  4710.2  377.11
  4802.6  374.97    4818  376.08  4875.7  375.14  4904.6  373.83  4963.6  373.15
  4970.1  374.09  4985.4  367.07  4991.3  366.33    4993  364.41  4995.8  363.91
    4999  364.41  5002.5  364.41  5013.1  370.84  5027.3  373.74  5041.4  374.59
  5083.8  373.06  5140.4   374.4  5168.7  373.89  5239.4  375.11  5380.8  381.05
  5465.7   386.4  5479.8  385.15  5508.1  390.46  5522.2  391.03  5564.7   396.9
#Mann= 4 ,-1 , 0
  4527.3     .16       0  4710.2     .12       0    4993     .07       0
    4999     .12       0
Bank Sta=4875.7,5140.4
XS Rating Curve= 0 ,0
Exp/Cntr=0.3,0.1

Type RM Length L Ch R = 1 ,20016   ,420,420,420
BEGIN DESCRIPTION:
BRINKLEY CREEK 39.0
END DESCRIPTION:
XS GIS Cut Line= 3
       3639258.9     10605795.16      3638920.35     10605310.78
      3637703.12     10604483.69
#Sta/Elev= 30
  4634.3  396.96  4715.6  391.16  4837.7     376  4903.1  371.84  4924.1  370.82
  4968.6  372.28    4982  365.21  5001.3  363.54  5004.1  363.04  5007.3  363.54
  5018.6  366.45  5025.2  372.12    5177  369.99  5361.7  370.96  5471.4  371.58
    5578   377.4  5607.9  383.97  5622.9     389  5637.2  390.65  5649.9   395.4
  5691.6  403.89  5758.1  414.21  5802.5   418.1  5903.2  421.78  5986.4  428.07
    6012  431.15    6054  432.16  6299.5  446.04  6500.1  446.14  6696.9  452.11
#Mann= 7 ,-1 , 0
  4634.3     .12       0  5001.3     .07       0  5007.3     .12       0
  5361.7     .16       0  5471.4     .12       0  5691.6     .16       0
  5986.4     .05       0
Bank Sta=4903.1,5471.4
XS Rating Curve= 0 ,0
Exp/Cntr=0.3,0.1

Type RM Length L Ch R = 1 ,19596   ,472,472,472
BEGIN DESCRIPTION:
BRINKLEY CREEK 38.0
END DESCRIPTION:
XS GIS Cut Line= 3
      3639399.52     10605810.76      3639456.81      10605326.4
      3640258.91     10604019.08
#Sta/Elev= 30
  4646.8  399.43  4758.1  393.95  4792.7  390.38  4930.5  372.45  4939.4   371.3
  4969.6  368.77  4989.7  363.71  5006.9  362.18  5009.6  361.68  5012.9  362.18
  5032.9  368.97  5100.1  368.73  5116.4  367.72  5317.9  365.96    5344  365.52
  5533.4  362.73  5540.7  366.59  5612.7  371.06  5680.2  377.42  5728.8  386.82
  5898.5   399.5  6049.6  405.39  6070.9  408.24  6092.2  406.79  6128.9  409.46
  6263.9  412.68  6326.8  414.33  6379.3  418.52    6502  430.35  6668.3  452.25
#Mann= 13 ,-1 , 0
  4646.8     .05       0  4792.7     .16       0  4930.5     .12       0
  5006.9     .07       0  5012.9     .12       0  5100.1     .16       0
  5116.4     .12       0  5317.9     .16       0    5344     .12       0
  5728.8     .16       0  5898.5     .05       0  6263.9     .16       0
  6379.3     .05       0
Bank Sta=4939.4,5612.7
XS Rating Curve= 0 ,0
Exp/Cntr=0.3,0.1

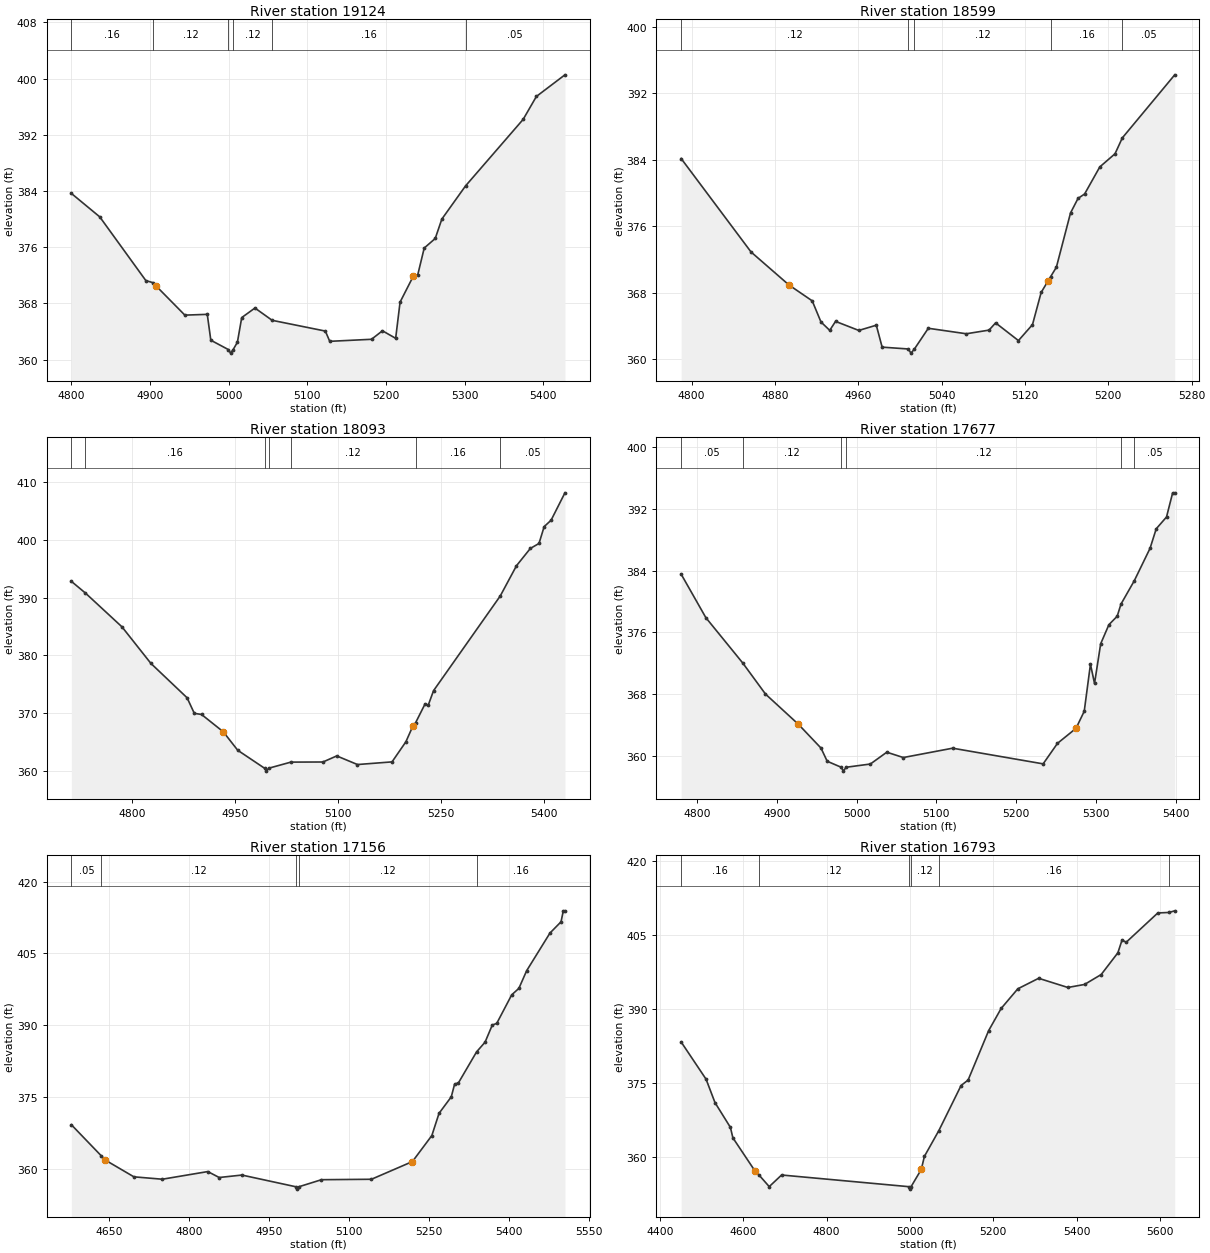
Type RM Length L Ch R = 1 ,19124   ,525,525,525
BEGIN DESCRIPTION:
BRINKLEY CREEK 37.0
END DESCRIPTION:
XS GIS Cut Line= 3
      3639749.59     10605760.22      3639849.61     10605610.19
      3640249.59      10605410.2
#Sta/Elev= 30
  4799.9  383.67    4836  380.33  4894.6  371.26  4903.3  370.97  4908.1  370.44
  4944.2  366.34  4972.7  366.45  4977.2  362.77  4999.6  361.43  5002.3  360.93
  5005.6  361.43    5011  362.48  5016.5  365.99  5033.3  367.35  5055.2   365.6
  5122.8  364.07  5128.4  362.61  5181.5   362.9  5195.4  364.11  5212.2  363.04
  5217.8  368.19  5234.6  371.88  5240.2  372.04  5248.5  375.89  5262.5  377.25
  5270.9  380.01    5301  384.73  5374.3  394.21  5391.1  397.47  5427.4  400.55
#Mann= 6 ,-1 , 0
  4799.9     .16       0  4903.3     .12       0  4999.6     .07       0
  5005.6     .12       0  5055.2     .16       0    5301     .05       0
Bank Sta=4908.1,5234.6
XS Rating Curve= 0 ,0
Exp/Cntr=0.3,0.1

Type RM Length L Ch R = 1 ,18599   ,506,506,506
BEGIN DESCRIPTION:
BRINKLEY CREEK 36.0
END DESCRIPTION:
XS GIS Cut Line= 3
      3640099.59     10606060.23      3640199.61     10605860.19
      3640349.64     10605660.15
#Sta/Elev= 30
    4790  384.16  4857.1  372.91  4893.5  368.94  4915.8  367.03  4924.2  364.49
  4932.6  363.48  4938.2  364.56  4960.5  363.47  4977.3   364.1  4982.9  361.46
  5007.9  361.24  5010.6  360.74  5013.9  361.24  5027.2  363.73  5063.7  363.07
  5085.5  363.51  5091.8  364.38  5113.7  362.25  5127.2  364.17  5135.5  368.04
  5141.8  369.36  5144.5  369.92  5150.1  371.07  5163.7  377.61  5170.9  379.36
  5177.2  379.89  5191.8  383.15  5206.4  384.73  5213.4  386.64  5263.7  394.23
#Mann= 5 ,-1 , 0
    4790     .12       0  5007.9     .07       0  5013.9     .12       0
  5144.5     .16       0  5213.4     .05       0
Bank Sta=4893.5,5141.8
XS Rating Curve= 0 ,0
Exp/Cntr=0.3,0.1

Type RM Length L Ch R = 1 ,18093   ,416,416,416
BEGIN DESCRIPTION:
BRINKLEY CREEK 35.0
END DESCRIPTION:
XS GIS Cut Line= 3
       3640499.6     10606360.23      3640599.61     10606060.19
      3640649.61     10605660.17
#Sta/Elev= 30
  4711.7  392.81  4732.3  390.77  4785.5  384.93  4827.7   378.6  4880.4  372.66
  4890.9  369.97  4901.5  369.77  4933.1  366.78  4954.2  363.58  4993.3  360.47
  4996.1  359.97  4999.3  360.47  5031.7  361.53  5078.4  361.55  5098.5   362.6
  5128.7  361.11  5179.1  361.57  5199.3  365.05  5209.4  367.75  5213.6  368.38
    5227  371.54    5232  371.42  5239.6  373.89  5336.8  390.27  5360.5  395.51
  5380.7   398.5  5393.3  399.36  5400.8  402.27  5410.9  403.38  5431.1  408.12
#Mann= 7 ,-1 , 0
  4711.7     .05       0  4732.3     .16       0  4993.3     .07       0
  4999.3     .16       0  5031.7     .12       0  5213.6     .16       0
  5336.8     .05       0
Bank Sta=4933.1,5209.4
XS Rating Curve= 0 ,0
Exp/Cntr=0.3,0.1

Type RM Length L Ch R = 1 ,17677   ,521,521,521
BEGIN DESCRIPTION:
BRINKLEY CREEK 34.0
END DESCRIPTION:
XS GIS Cut Line= 3
       3640949.6     10606360.23      3640999.61     10606160.19
      3640899.61      10605760.2
#Sta/Elev= 30
  4780.2  383.55  4811.2  377.91  4857.5  372.03  4885.9  368.02  4927.1  364.11
  4955.5  361.02  4963.2  359.32  4980.8  358.54  4983.6  358.04  4986.8  358.54
  5017.3  358.96  5037.9  360.49  5058.6   359.8  5120.4  361.01  5233.8  358.98
  5251.8  361.64    5275  363.58  5285.3  365.79  5293.1  371.89  5298.2  369.39
  5305.9  374.53  5316.2     377  5326.6   378.1  5331.4  379.68    5348  382.69
  5367.8   386.9  5375.5  389.42  5388.4  390.95  5396.1  394.08  5398.7  394.08
#Mann= 6 ,-1 , 0
  4780.2     .05       0  4857.5     .12       0  4980.8     .07       0
  4986.8     .12       0  5331.4     .16       0    5348     .05       0
Bank Sta=4927.1,5275
XS Rating Curve= 0 ,0
Exp/Cntr=0.3,0.1

Type RM Length L Ch R = 1 ,17156   ,363,363,363
BEGIN DESCRIPTION:
BRINKLEY CREEK 33.0
END DESCRIPTION:
XS GIS Cut Line= 3
      3641199.61     10606310.19      3641349.61     10605910.19
      3640949.61     10605610.19
#Sta/Elev= 30
  4578.5  369.19  4634.9  362.67  4642.6  361.78    4696   358.3  4749.4   357.8
  4834.8   359.4  4856.2  358.16  4898.9  358.67    5000  356.23  5002.8  355.73
    5006  356.23  5048.4   357.7  5142.2  357.79  5219.2  361.49  5255.7  366.93
  5269.2  371.57  5292.2  375.02  5298.4  377.65  5305.7  377.95  5339.7  384.41
  5355.7  386.45  5369.2  390.02  5377.6  390.37  5405.7  396.33  5419.2  397.69
  5433.8  401.38  5477.6  409.25  5498.4   411.6  5502.6  413.89  5505.7  413.89
#Mann= 5 ,-1 , 0
  4578.5     .05       0  4634.9     .12       0    5000     .07       0
    5006     .12       0  5339.7     .16       0
Bank Sta=4642.6,5219.2
XS Rating Curve= 0 ,0
Exp/Cntr=0.3,0.1

Type RM Length L Ch R = 1 ,16793   ,517,517,517
BEGIN DESCRIPTION:
BRINKLEY CREEK 32.0
END DESCRIPTION:
XS GIS Cut Line= 3
      3641411.21     10606481.82      3641760.63     10605893.68
      3641764.95     10605393.81
#Sta/Elev= 30
  4451.2  383.28    4511  375.74  4532.4     371  4569.4  365.98  4575.3  363.87
  4627.6  357.25    4639  356.24  4662.5  353.99  4692.2  356.34  4996.8  353.98
  4999.5  353.48  5002.8  353.98  5027.3  357.48  5034.7  360.11  5069.5  365.35
  5122.7  374.46  5139.6  375.57  5188.8  385.57  5218.8  390.06  5258.8  394.04
  5308.8  396.17  5378.8  394.31  5418.8  394.92  5458.8  396.93  5498.8  401.33
  5508.8  403.91  5518.8  403.47  5594.6   409.4  5621.3   409.5  5635.2  409.83
#Mann= 6 ,-1 , 0
  4451.2     .16       0    4639     .12       0  4996.8     .07       0
  5002.8     .12       0  5069.5     .16       0  5621.3     .05       0
Bank Sta=4627.6,5027.3
XS Rating Curve= 0 ,0
Exp/Cntr=0.3,0.1