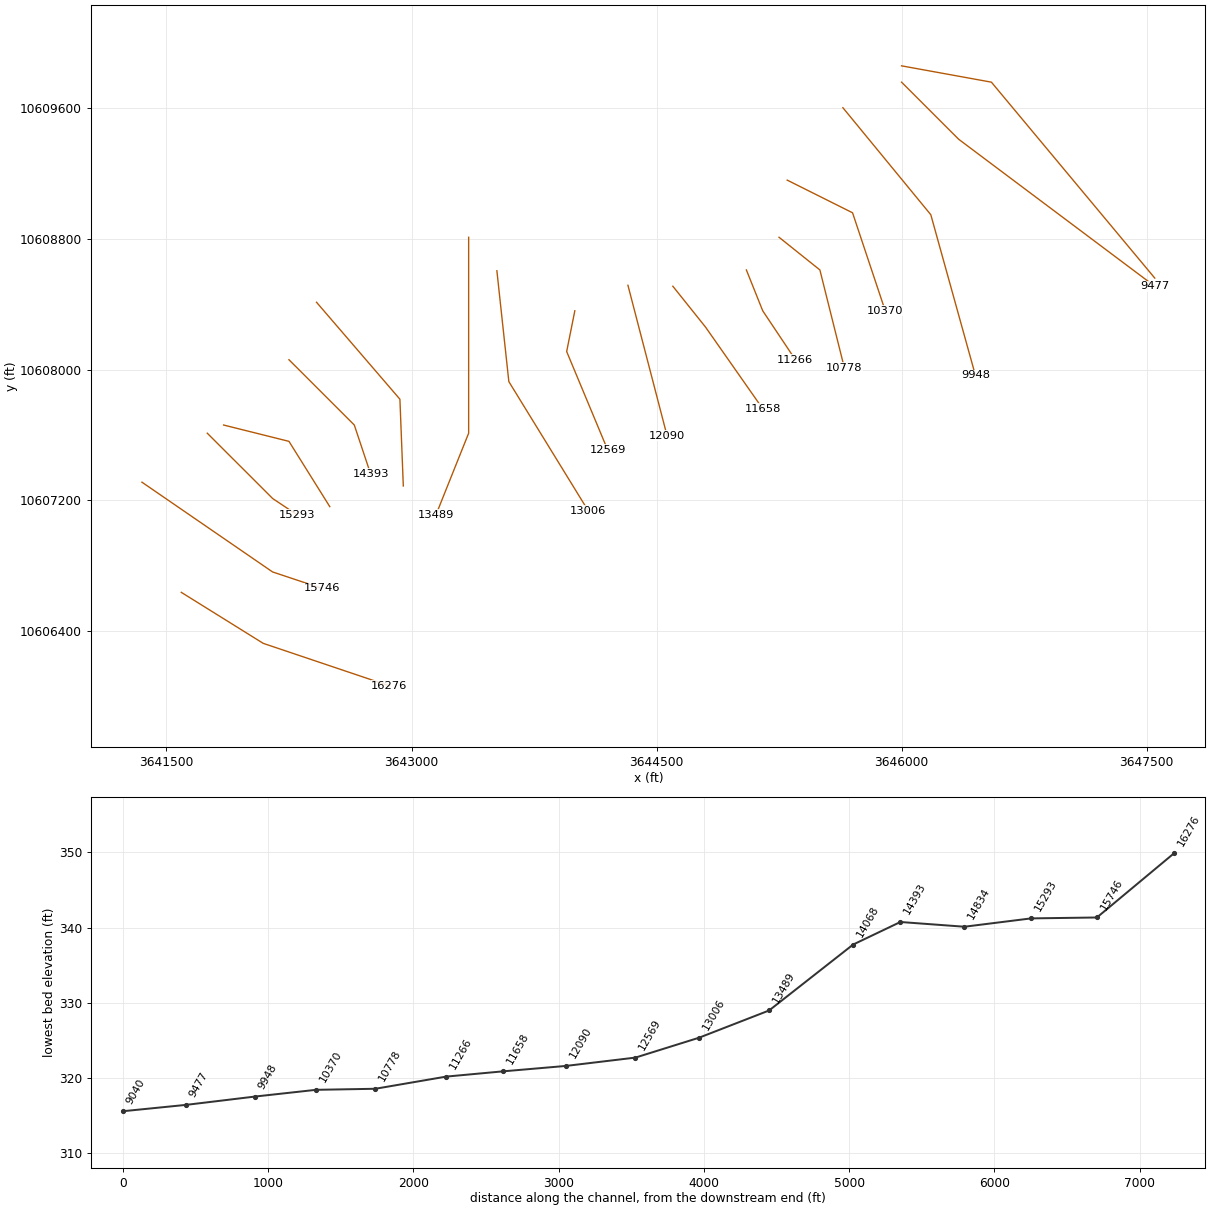
HEC-RAS study BRINKLEY CREEK.prj: BRINKLEY CREEK Base Level Engineering

--- BRINKLEY CREEK.g01 (geometry) --- (continued)

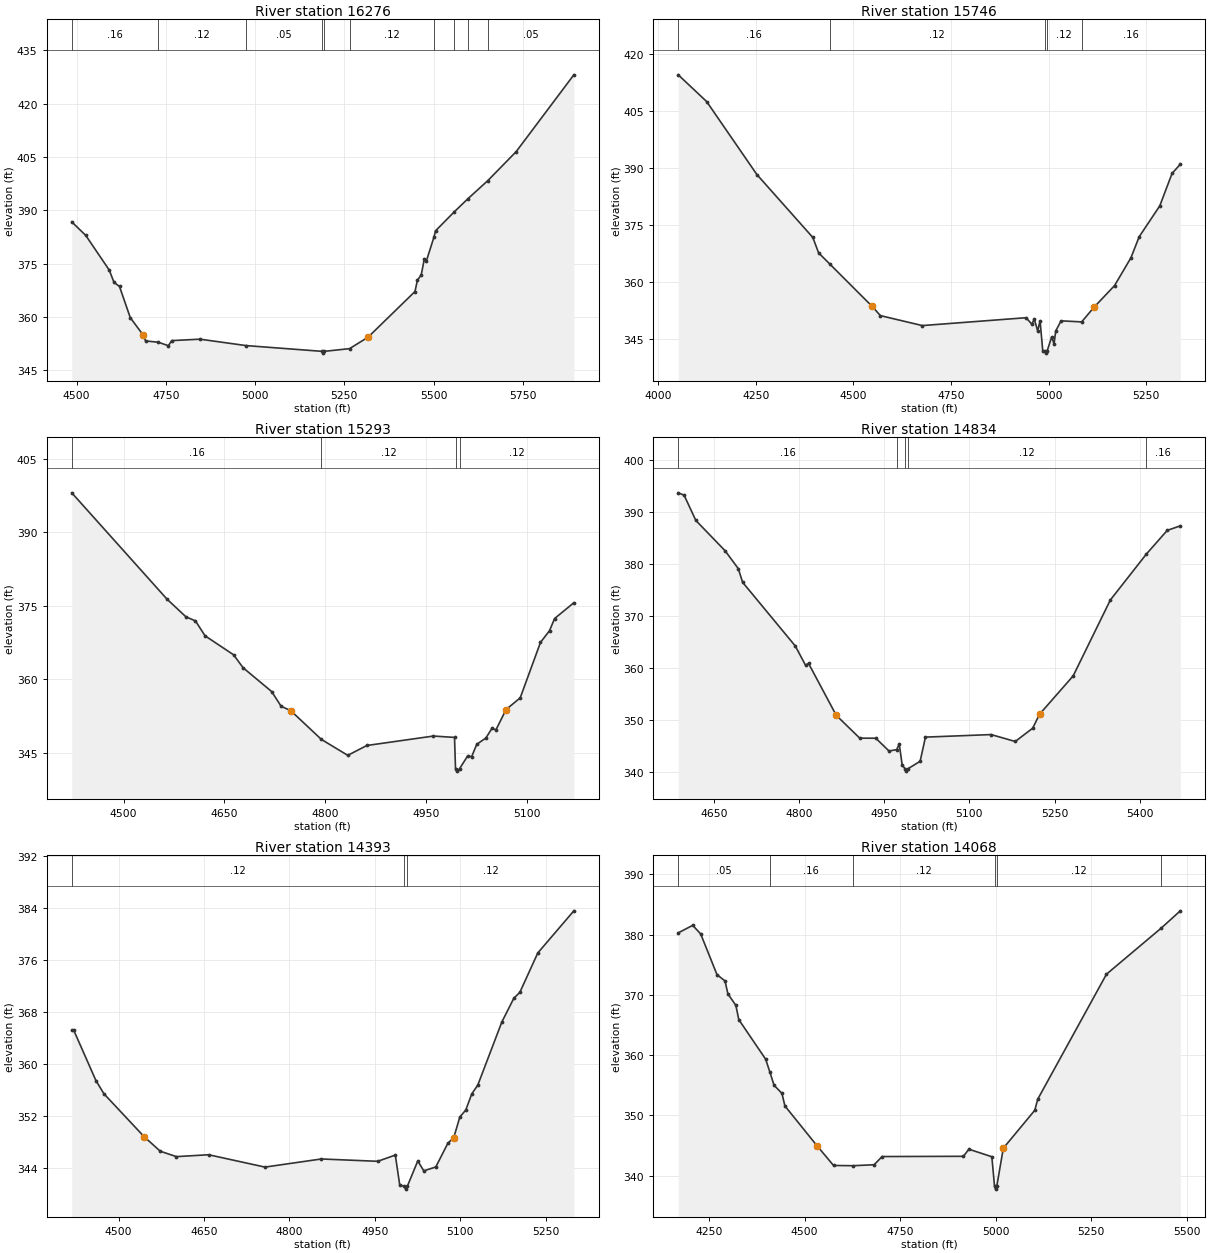
Type RM Length L Ch R = 1 ,16276   ,530,530,530
BEGIN DESCRIPTION:
BRINKLEY CREEK 31.0
END DESCRIPTION:
XS GIS Cut Line= 3
      3641590.48     10606635.44      3642092.22     10606322.93
      3642864.71     10606062.54
#Sta/Elev= 30
  4486.6  386.75  4525.9  382.94  4591.6   373.2  4604.9  369.75  4620.3   368.6
  4650.5  359.83  4685.9  355.05  4693.4  353.29  4728.9  352.94  4757.2  351.95
  4766.6  353.39  4845.7  353.79  4974.8  351.99  5187.8  350.37  5190.6  349.87
  5193.8  350.37  5264.7  351.13  5316.7  354.37  5447.9  367.18  5454.8  370.39
  5465.4  371.83  5474.2  376.41  5479.4  375.64    5501  382.44  5505.6  384.25
  5557.8  389.56  5596.5  393.29  5651.9  398.35  5731.3  406.49  5892.9  428.08
#Mann= 10 ,-1 , 0
  4486.6     .16       0  4728.9     .12       0  4974.8     .05       0
  5187.8     .03       0  5193.8     .05       0  5264.7     .12       0
    5501     .16       0  5557.8     .12       0  5596.5     .16       0
  5651.9     .05       0
Bank Sta=4685.9,5316.7
XS Rating Curve= 0 ,0
Exp/Cntr=0.3,0.1

Type RM Length L Ch R = 1 ,15746   ,453,453,453
BEGIN DESCRIPTION:
BRINKLEY CREEK 30.0
END DESCRIPTION:
XS GIS Cut Line= 3
      3641349.65     10607310.16      3642149.61     10606760.19
       3642449.6     10606660.19
#Sta/Elev= 30
  4050.8  414.58  4123.6  407.55  4252.4  388.34  4395.8  371.78  4410.7  367.71
  4439.8  364.74    4548  353.63    4569  351.21  4676.5  348.59  4942.4  350.66
  4957.3  348.95  4963.4  350.32  4972.2  347.18  4978.3  349.86  4985.2  341.96
  4990.2  341.84  4992.9  341.34  4996.2  341.84  5008.1   345.6  5014.1  343.75
  5018.5  347.19  5032.1  349.84  5084.9  349.56  5116.4  353.39  5169.2  359.11
  5211.3  366.45  5232.4  371.98  5285.1  380.08  5316.7  388.64  5337.8  391.05
#Mann= 5 ,-1 , 0
  4050.8     .16       0  4439.8     .12       0  4990.2     .07       0
  4996.2     .12       0  5084.9     .16       0
Bank Sta=4548,5116.4
XS Rating Curve= 0 ,0
Exp/Cntr=0.3,0.1

Type RM Length L Ch R = 1 ,15293   ,459,459,459
BEGIN DESCRIPTION:
BRINKLEY CREEK 29.0
END DESCRIPTION:
XS GIS Cut Line= 3
      3641749.61     10607610.18      3642149.61     10607210.19
      3642299.65     10607110.16
#Sta/Elev= 30
  4423.1  398.01  4564.5  376.33  4592.8   372.7  4606.9  371.88  4621.1  368.84
  4663.5  364.96  4677.7  362.31  4720.1  357.46  4734.2  354.45  4748.4  353.57
    4794  347.69  4833.2  344.44  4861.5  346.45  4960.5  348.38  4991.8   348.1
  4993.3  341.72    4996  341.22  4999.3  341.72  5011.3  344.31  5017.3  344.18
  5024.8  346.69  5038.4  347.98  5047.4  349.94  5053.4  349.65  5068.4  353.79
  5089.4  356.17  5119.5  367.48    5133  369.89  5140.5  372.36  5169.1  375.58
#Mann= 4 ,-1 , 0
  4423.1     .16       0    4794     .12       0  4993.3     .07       0
  4999.3     .12       0
Bank Sta=4748.4,5068.4
XS Rating Curve= 0 ,0
Exp/Cntr=0.3,0.1

Type RM Length L Ch R = 1 ,14834   ,441,441,441
BEGIN DESCRIPTION:
BRINKLEY CREEK 28.0
END DESCRIPTION:
XS GIS Cut Line= 3
      3641849.58      10607660.2      3642249.61     10607560.19
      3642499.59     10607160.22
#Sta/Elev= 30
  4587.5  393.63  4597.8  393.18  4618.5  388.32    4670  382.49  4693.2  379.06
  4700.9  376.42  4793.7  364.16  4811.7  360.46  4816.9  360.83  4865.8  350.83
  4907.1  346.45  4935.4  346.44  4958.6  343.98  4972.1  344.24  4976.6  345.34
  4981.8   341.3  4986.5  340.61  4989.3  340.11  4992.5  340.61  5013.4     342
  5022.8  346.65  5138.4  347.14  5180.9  345.81  5211.5  348.36  5223.9  351.08
  5282.9  358.43  5348.3  373.02  5411.8  381.86  5448.5  386.41  5471.5  387.28
#Mann= 5 ,-1 , 0
  4587.5     .16       0  4972.1     .12       0  4986.5     .07       0
  4992.5     .12       0  5411.8     .16       0
Bank Sta=4865.8,5223.9
XS Rating Curve= 0 ,0
Exp/Cntr=0.3,0.1

Type RM Length L Ch R = 1 ,14393   ,325,325,325
BEGIN DESCRIPTION:
BRINKLEY CREEK 27.0
END DESCRIPTION:
XS GIS Cut Line= 3
      3642249.64     10608060.15      3642649.61     10607660.19
      3642749.62     10607360.16
#Sta/Elev= 30
  4417.8  365.18  4421.3  365.18  4460.2  357.45  4474.3  355.41    4545   348.8
  4573.3  346.57  4601.6  345.74  4658.2  346.03  4757.2  344.13  4856.2  345.38
  4955.2  345.02  4986.1  345.98    4994  341.31  5001.5  341.24  5004.3  340.74
  5007.5  341.24  5025.6  345.08  5036.1  343.55  5057.2  344.15  5078.3  347.78
  5088.8  348.67  5099.4  351.83  5109.9  352.92  5120.5  355.41    5131  356.75
  5173.2  366.45  5194.3  370.11  5204.8  371.01  5236.4  377.08  5299.7  383.56
#Mann= 3 ,-1 , 0
  4417.8     .12       0  5001.5     .07       0  5007.5     .12       0
Bank Sta=4545,5088.8
XS Rating Curve= 0 ,0
Exp/Cntr=0.3,0.1

Type RM Length L Ch R = 1 ,14068   ,579,579,579
BEGIN DESCRIPTION:
BRINKLEY CREEK 26.0
END DESCRIPTION:
XS GIS Cut Line= 3
      3642418.36     10608412.13      3642928.81     10607818.35
      3642949.64     10607287.08
#Sta/Elev= 30
    4169   380.3  4206.9  381.55  4227.8  380.12  4270.5  373.36  4291.4  372.32
  4299.1  370.16  4319.9  368.26  4327.6  365.89  4397.8  359.33  4408.9   357.2
  4419.8     355  4440.6  353.64  4448.3  351.56  4532.8  344.91  4575.6  341.67
  4626.3  341.63    4682  341.79  4702.9  343.15  4915.8  343.19    4930  344.37
  4990.2  343.12  4997.2  338.24    5000  337.74  5003.2  338.24  5020.2  344.53
  5102.7  350.84  5110.3  352.67  5290.4  373.44  5433.5  381.08  5483.7  383.96
#Mann= 6 ,-1 , 0
    4169     .05       0  4408.9     .16       0  4626.3     .12       0
  4997.2     .07       0  5003.2     .12       0  5433.5     .16       0
Bank Sta=4532.8,5020.2
XS Rating Curve= 0 ,0
Exp/Cntr=0.3,0.1

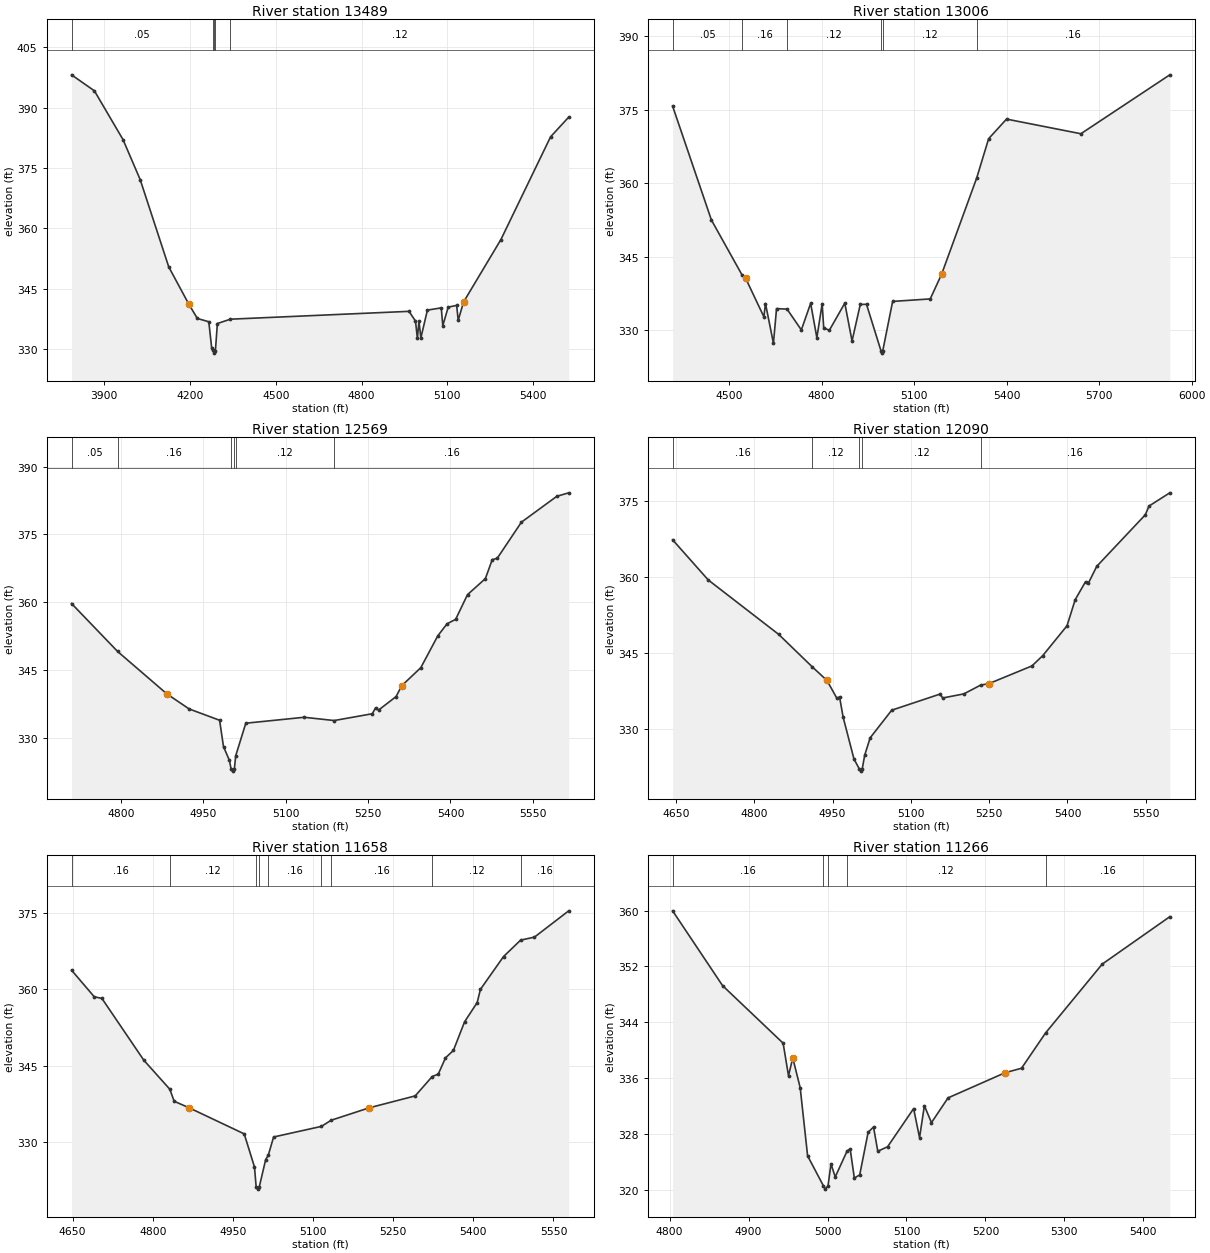
Type RM Length L Ch R = 1 ,13489   ,483,483,483
BEGIN DESCRIPTION:
BRINKLEY CREEK 25.0
END DESCRIPTION:
XS GIS Cut Line= 3
      3643349.61     10608810.16      3643349.61     10607610.19
       3643149.6     10607110.17
#Sta/Elev= 30
  3785.9  398.16  3865.9  394.18  3965.9  382.06  4025.9  372.12  4125.9  350.39
  4195.9  341.15  4225.9  337.58  4265.9  336.76  4275.9  330.29  4280.9   329.7
  4282.9  329.46  4285.6  328.96  4288.9  329.46  4295.9  336.32  4341.5   337.4
  4965.9  339.35  4988.6  336.94  4995.3  332.61  5000.7  337.01  5007.4  332.73
  5030.3  339.66  5078.8  340.21  5084.1  335.78    5103  340.39  5132.6  340.83
    5138  337.12  5156.8  341.68  5287.4  357.21  5461.1  382.76  5524.4  387.64
#Mann= 5 ,-1 , 0
  3785.9     .05       0  4280.9     .16       0  4282.9     .07       0
  4288.9     .16       0  4341.5     .12       0
Bank Sta=4195.9,5156.8
XS Rating Curve= 0 ,0
Exp/Cntr=0.3,0.1

Type RM Length L Ch R = 1 ,13006   ,437,437,437
BEGIN DESCRIPTION:
BRINKLEY CREEK 24.0
END DESCRIPTION:
XS GIS Cut Line= 3
      3643522.42     10608605.23      3643595.62     10607926.16
      3644081.95     10607134.51
#Sta/Elev= 30
    4317  375.77  4442.8  352.51  4542.6  341.24  4553.4  340.66    4613  332.74
  4618.1  335.46  4643.9  327.34    4654  334.42    4688  334.32  4734.4  330.07
  4764.6   335.5  4784.7  328.48  4801.9  335.41  4806.9  330.53    4825  329.97
  4875.3  335.53  4898.8  327.81  4925.5  335.27  4945.7   335.3  4992.5  325.83
  4995.2  325.33  4998.5  325.83  5030.4  335.89  5152.3   336.4    5189  341.41
    5303  361.09  5341.7  369.12  5399.7  373.12  5640.8  370.13  5929.1  382.16
#Mann= 6 ,-1 , 0
    4317     .05       0  4542.6     .16       0    4688     .12       0
  4992.5     .07       0  4998.5     .12       0    5303     .16       0
Bank Sta=4553.4,5189
XS Rating Curve= 0 ,0
Exp/Cntr=0.3,0.1

Type RM Length L Ch R = 1 ,12569   ,479,479,479
BEGIN DESCRIPTION:
BRINKLEY CREEK 23.0
END DESCRIPTION:
XS GIS Cut Line= 3
       3643999.6     10608360.15      3643949.61     10608110.19
      3644199.61      10607510.2
#Sta/Elev= 30
  4710.3  359.73  4794.2  349.13  4883.6  339.78  4924.4  336.43  4979.8  333.93
  4986.9  328.11  4997.7  325.05  5000.7  323.19  5003.4  322.69  5006.7  323.19
  5009.1  326.08  5027.5  333.28  5133.7  334.59  5188.3  333.87  5257.7  335.37
  5263.7  336.67  5269.1  336.18    5301  339.16  5311.3  341.57    5346  345.55
  5376.9  352.58  5393.7  355.24  5409.4  356.23    5431  361.69  5463.5  365.23
    5476  369.41  5485.2  369.74  5529.1   377.7  5593.5  383.42  5615.2  384.19
#Mann= 6 ,-1 , 0
  4710.3     .05       0  4794.2     .16       0  5000.7     .07       0
  5006.7     .16       0  5009.1     .12       0  5188.3     .16       0
Bank Sta=4883.6,5311.3
XS Rating Curve= 0 ,0
Exp/Cntr=0.3,0.1

Type RM Length L Ch R = 1 ,12090   ,432,432,432
BEGIN DESCRIPTION:
BRINKLEY CREEK 22.0
END DESCRIPTION:
XS GIS Cut Line= 2
      3644324.63     10608516.29      3644564.12      10607594.8
#Sta/Elev= 30
  4643.8  367.28  4712.1  359.34    4847  348.59  4911.2  342.18  4939.4  339.49
  4958.3  335.98  4963.5  336.23  4970.4  332.22  4991.1  323.98    5001  322.08
  5003.8  321.58    5007  322.08  5011.7  324.75  5022.1  328.16  5063.4  333.62
  5155.9   336.8    5161  336.03  5201.6  336.84  5233.7  338.58  5249.4  338.86
    5332  342.37  5352.7  344.41  5399.1   350.3  5414.7  355.44  5434.5     359
  5439.7  358.65    5456  362.04    5549  372.22  5556.1  373.95  5595.9  376.56
#Mann= 5 ,-1 , 0
  4643.8     .16       0  4911.2     .12       0    5001     .07       0
    5007     .12       0  5233.7     .16       0
Bank Sta=4939.4,5249.4
XS Rating Curve= 0 ,0
Exp/Cntr=0.3,0.1

Type RM Length L Ch R = 1 ,11658   ,392,392,392
BEGIN DESCRIPTION:
BRINKLEY CREEK 21.0
END DESCRIPTION:
XS GIS Cut Line= 3
      3644599.59     10608510.22      3644799.61     10608260.19
       3645149.6      10607760.2
#Sta/Elev= 30
    4648  363.75  4690.5  358.54  4704.9  358.21  4783.3  346.11    4832  340.42
  4840.1  338.07  4868.1  336.79  4971.2  331.68  4990.4   325.2  4993.5  321.36
  4996.3  320.86  4999.5  321.36  5011.4  326.66  5016.2  327.49  5026.2  331.07
  5115.7  333.15  5133.9  334.35  5204.9  336.78  5291.2  339.12    5323  342.91
  5334.4  343.39  5347.9  346.57  5362.7  348.03  5383.7  353.65  5407.2   357.4
  5413.3  359.99  5456.5  366.41  5488.5  369.63  5514.4  370.22  5578.5  375.37
#Mann= 9 ,-1 , 0
    4648     .16       0    4832     .12       0  4993.5     .07       0
  4999.5     .12       0  5016.2     .16       0  5115.7     .12       0
  5133.9     .16       0    5323     .12       0  5488.5     .16       0
Bank Sta=4868.1,5204.9
XS Rating Curve= 0 ,0
Exp/Cntr=0.3,0.1

Type RM Length L Ch R = 1 ,11266   ,488,488,488
BEGIN DESCRIPTION:
BRINKLEY CREEK 20.0
END DESCRIPTION:
XS GIS Cut Line= 3
       3645049.6     10608610.21      3645149.61     10608360.19
      3645349.59     10608060.22
#Sta/Elev= 30
  4803.8  359.96  4867.1  349.26  4943.8  341.03  4950.6  336.38    4956  338.92
  4965.4  334.67  4974.8  324.92  4994.7  320.66  4997.4  320.16  5000.7  320.66
  5004.4  323.77  5009.8   321.9  5024.8  325.61  5028.7  325.91    5034  321.75
  5040.8   322.2  5051.5   328.3  5058.3  329.04  5063.7  325.58  5076.1  326.22
  5109.1  331.68  5116.6  327.52  5122.7  332.09  5131.7  329.67  5152.7  333.21
  5224.8   336.8  5245.8  337.45  5276.2  342.49    5348  352.34  5433.6  359.12
#Mann= 5 ,-1 , 0
  4803.8     .16       0  4994.7     .07       0  5000.7     .16       0
  5024.8     .12       0  5276.2     .16       0
Bank Sta=4956,5224.8
XS Rating Curve= 0 ,0
Exp/Cntr=0.3,0.1

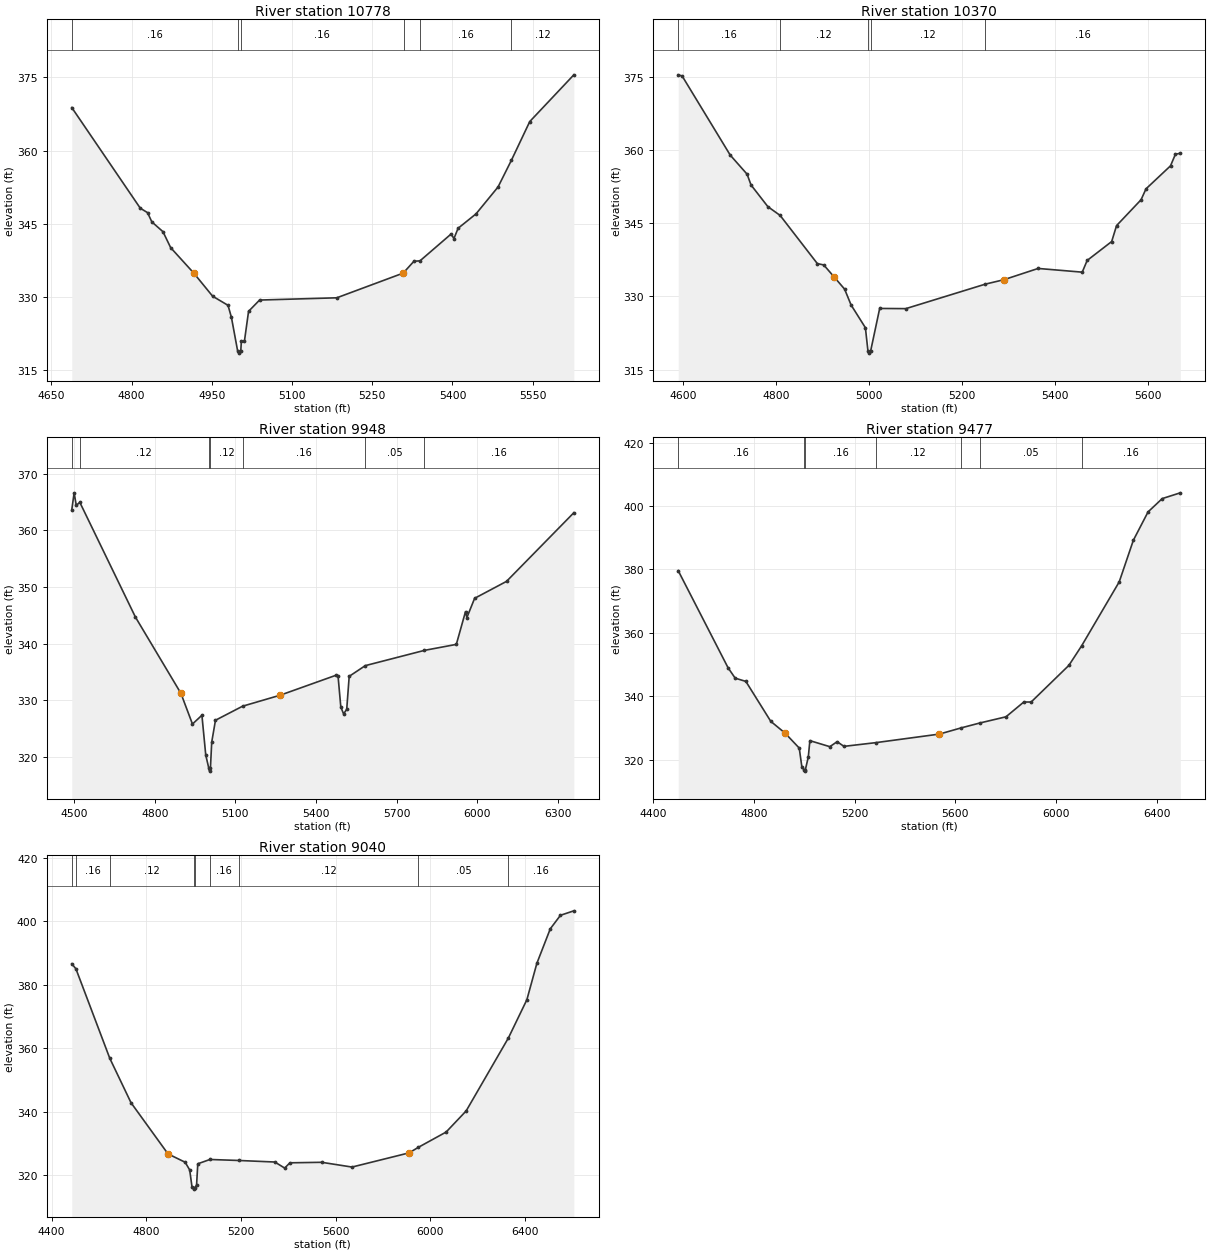
Type RM Length L Ch R = 1 ,10778   ,408,408,408
BEGIN DESCRIPTION:
BRINKLEY CREEK 19.0
END DESCRIPTION:
XS GIS Cut Line= 3
      3645249.61     10608810.19      3645499.61     10608610.19
       3645649.6     10608010.21
#Sta/Elev= 30
  4688.3  368.84  4816.4  348.22    4830  347.31    4838  345.42  4858.8  343.41
  4873.2  340.14  4916.4  334.93  4951.6   330.2  4980.4  328.33  4986.8  325.85
  4998.3  319.04    5001  318.54  5004.3  319.04  5005.3  320.93    5011  320.93
  5018.8   327.1  5039.4  329.41  5183.7  329.87  5307.4  334.91    5309  335.07
    5328  337.36  5339.3  337.44  5397.6  342.95  5402.7  341.99  5410.5  344.11
    5444  347.06  5485.2  352.57  5510.3  358.07  5544.5  365.97  5626.9  375.54
#Mann= 6 ,-1 , 0
  4688.3     .16       0  4998.3     .07       0  5004.3     .16       0
    5309     .12       0  5339.3     .16       0  5510.3     .12       0
Bank Sta=4916.4,5307.4
XS Rating Curve= 0 ,0
Exp/Cntr=0.3,0.1

Type RM Length L Ch R = 1 ,10370   ,422,422,422
BEGIN DESCRIPTION:
BRINKLEY CREEK 18.0
END DESCRIPTION:
XS GIS Cut Line= 3
      3645299.63     10609160.18      3645699.61     10608960.19
      3645899.62     10608360.14
#Sta/Elev= 30
  4590.1  375.39  4598.5  375.15  4701.9  358.95  4738.2  355.04  4746.6  352.84
  4782.9  348.39  4809.2   346.6  4889.2  336.74  4903.1  336.45  4925.5  333.98
  4947.9   331.5  4961.8  328.26  4992.6   323.6    4998   318.9  5000.7   318.4
    5004   318.9  5023.3  327.55  5079.5  327.51  5250.6  332.53  5290.3  333.43
  5364.1  335.74  5458.9  334.98  5469.5  337.38  5522.2  341.25  5532.7  344.51
  5585.4  349.81    5596  352.04  5648.7  356.75  5659.2  359.11  5669.8  359.34
#Mann= 5 ,-1 , 0
  4590.1     .16       0  4809.2     .12       0    4998     .07       0
    5004     .12       0  5250.6     .16       0
Bank Sta=4925.5,5290.3
XS Rating Curve= 0 ,0
Exp/Cntr=0.3,0.1

Type RM Length L Ch R = 1 ,9948    ,471,471,471
BEGIN DESCRIPTION:
BRINKLEY CREEK 17.0
END DESCRIPTION:
XS GIS Cut Line= 3
      3645640.44     10609603.75      3646178.67     10608948.33
      3646451.82     10607964.12
#Sta/Elev= 30
  4490.6  363.61  4499.4  366.62  4507.3  364.41  4520.6  364.94  4727.6  344.69
  4896.9  331.24    4940  325.81  4975.2  327.36  4989.5  320.34  5000.9     318
  5003.6   317.5  5006.9     318  5011.7  322.62  5025.7  326.48  5126.7  328.96
  5267.2  330.91    5475  334.43  5482.1  334.29  5492.4  328.81  5502.8   327.6
  5514.4  328.41  5523.6  334.23  5583.6  336.12  5803.5  338.81  5922.5  339.87
  5956.7  345.65  5961.9  344.61  5990.6     348  6109.4  350.99  6360.1  363.11
#Mann= 7 ,-1 , 0
  4490.6     .16       0  4520.6     .12       0  5000.9     .07       0
  5006.9     .12       0  5126.7     .16       0  5583.6     .05       0
  5803.5     .16       0
Bank Sta=4896.9,5267.2
XS Rating Curve= 0 ,0
Exp/Cntr=0.3,0.1

Type RM Length L Ch R = 1 ,9477    ,437,437,437
BEGIN DESCRIPTION:
BRINKLEY CREEK 16.0
END DESCRIPTION:
XS GIS Cut Line= 3
      3645999.61     10609760.18      3646349.61     10609410.19
      3647549.64     10608510.17
#Sta/Elev= 30
  4498.8  379.59  4696.8  348.99  4725.1  345.71  4767.5  344.69  4866.5   332.1
  4923.1   328.4  4979.6  323.67  4990.2  317.64  4998.1   316.9  5000.8   316.4
  5004.1   316.9  5015.6  320.85  5021.9  326.01  5101.1  324.11  5130.2  325.68
  5157.3  324.21  5282.9  325.37  5536.5  328.08  5622.4  330.02  5697.9  331.59
  5801.1  333.53  5871.9  338.19  5901.1  338.19  6051.1  349.75  6101.8  355.92
  6251.1  376.08  6307.3  389.21  6365.6  398.13  6421.9  402.33  6493.8  404.15
#Mann= 7 ,-1 , 0
  4498.8     .16       0  4998.1     .07       0  5004.1     .16       0
  5282.9     .12       0  5622.4     .16       0  5697.9     .05       0
  6101.8     .16       0
Bank Sta=4923.1,5536.5
XS Rating Curve= 0 ,0
Exp/Cntr=0.3,0.1

Type RM Length L Ch R = 1 ,9040    ,597,597,597
BEGIN DESCRIPTION:
BRINKLEY CREEK 15.0
END DESCRIPTION:
XS GIS Cut Line= 3
      3645999.57      10609860.2      3646549.61     10609760.19
      3647549.61     10608560.19
#Sta/Elev= 30
  4485.3  386.62  4502.8  385.04  4645.9  356.81  4735.6   342.8  4891.9  326.66
  4964.3  324.03  4983.4  321.61  4993.5  316.12  5000.7  316.05  5003.4  315.55
  5006.7  316.05  5012.6  316.91  5017.7  323.54  5069.1   324.9  5189.7  324.59
  5343.1   324.1  5384.8  322.19  5406.9  323.85    5541  324.01  5669.2  322.51
  5910.6  326.99  5949.9  328.75  6066.8  333.55  6151.5  340.22    6330  363.24
  6407.9  375.27  6450.2  386.77  6506.8  397.64  6549.8  401.91  6606.4  403.32
#Mann= 9 ,-1 , 0
  4485.3     .05       0  4502.8     .16       0  4645.9     .12       0
  5000.7     .07       0  5006.7     .12       0  5069.1     .16       0
  5189.7     .12       0  5949.9     .05       0    6330     .16       0
Bank Sta=4891.9,5910.6
XS Rating Curve= 0 ,0
Exp/Cntr=0.3,0.1