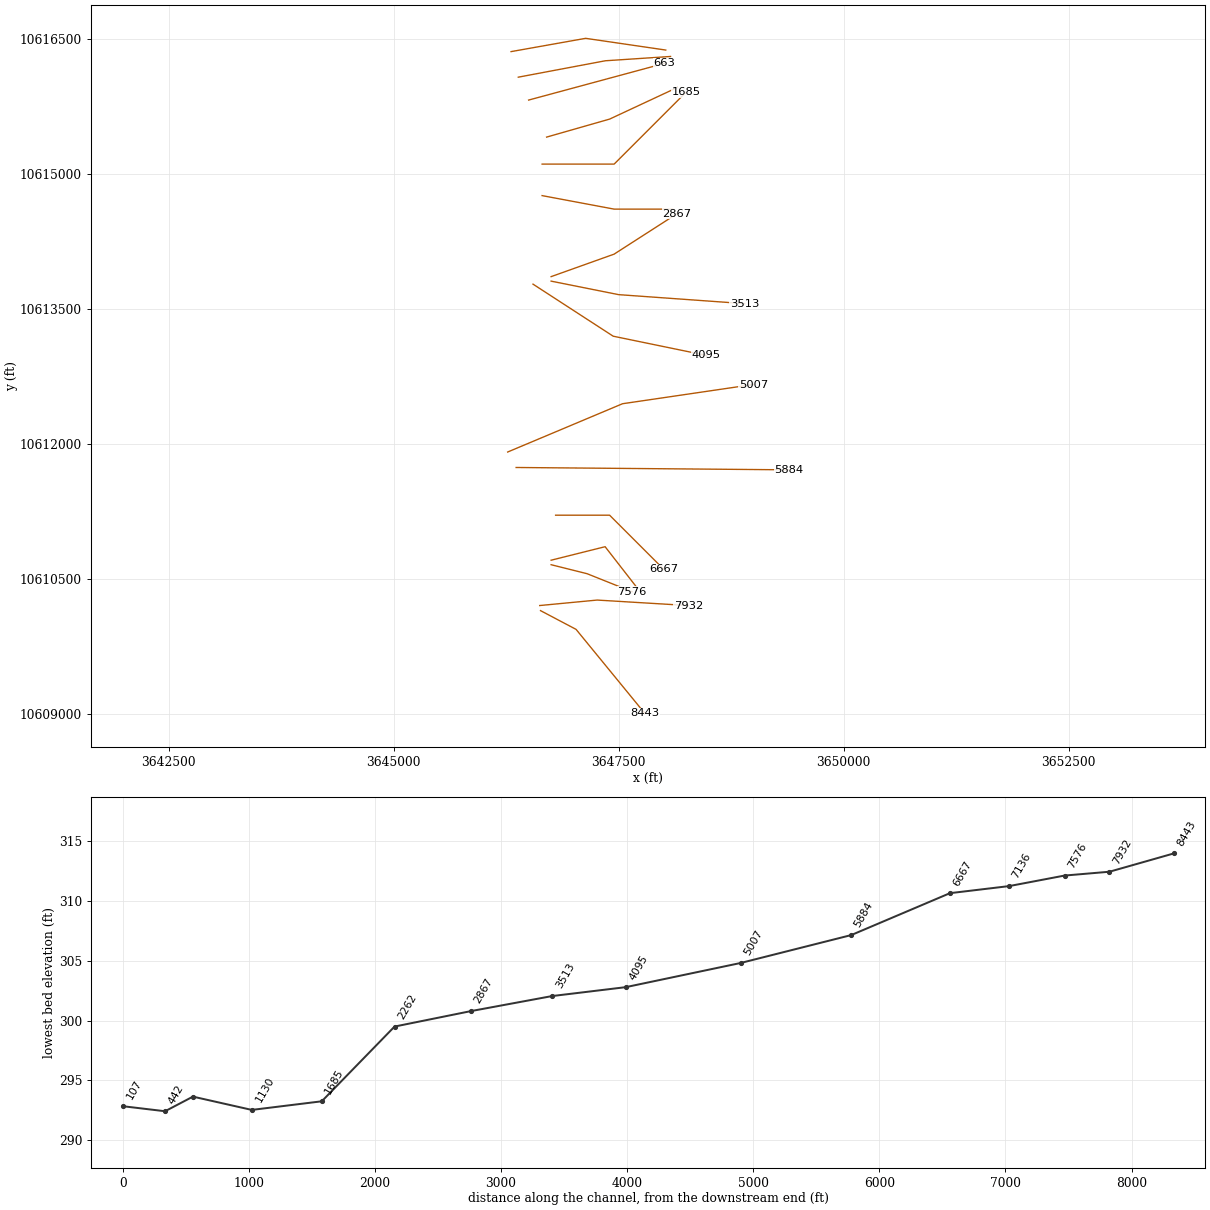
HEC-RAS study BRINKLEY CREEK.prj: BRINKLEY CREEK Base Level Engineering

--- BRINKLEY CREEK.g01 (geometry) --- (continued)

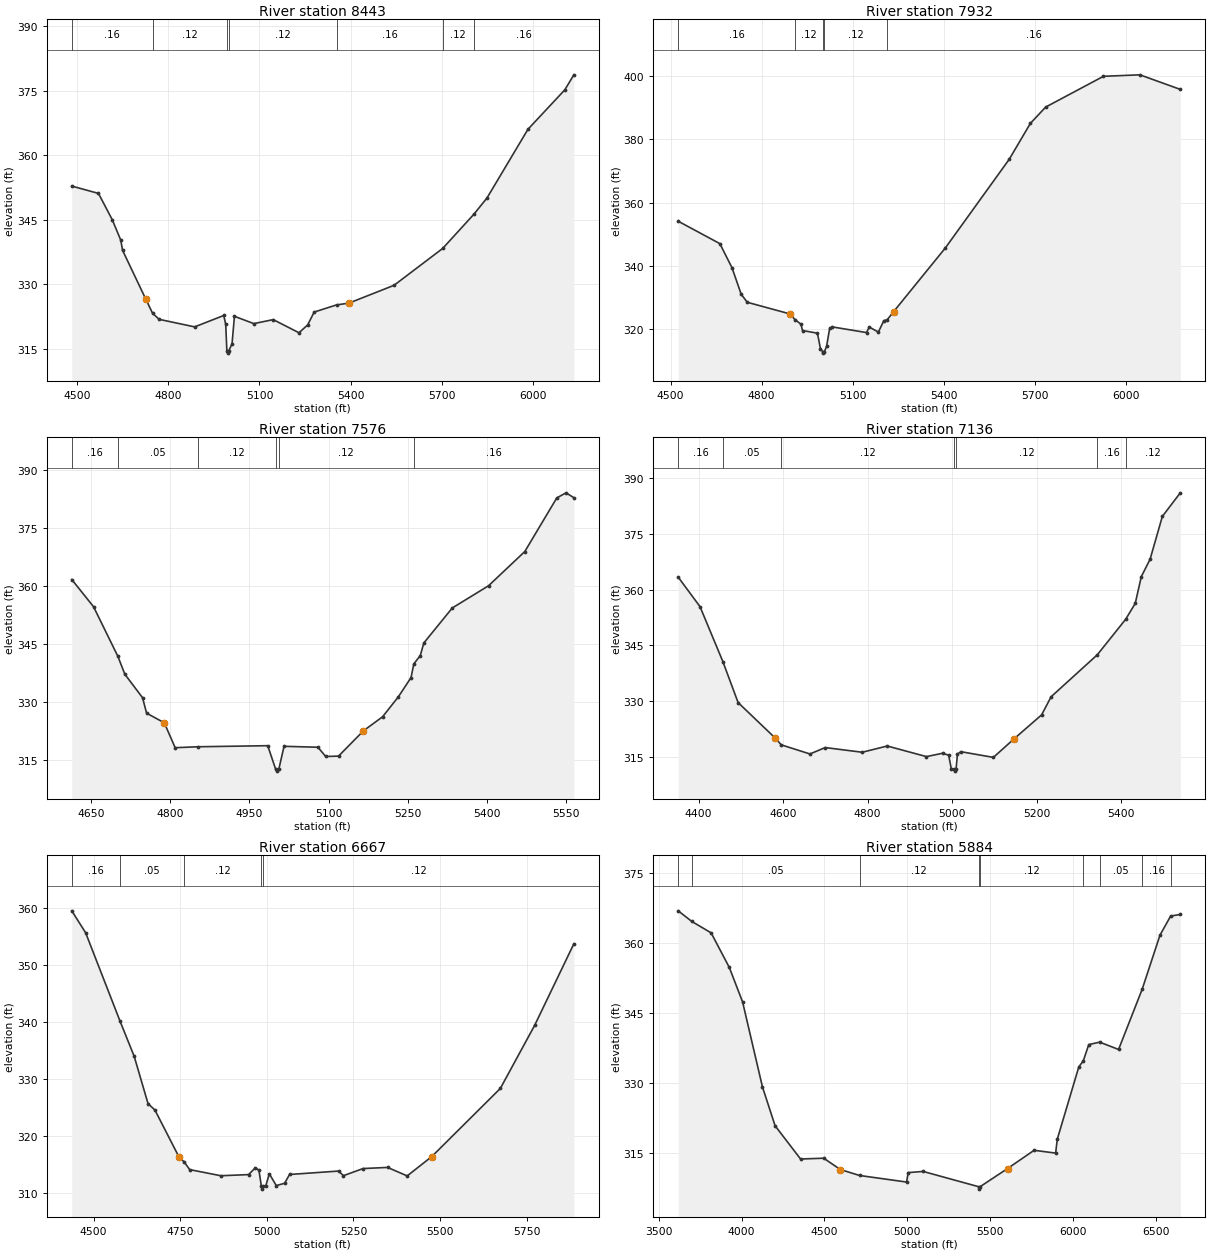
Type RM Length L Ch R = 1 ,8443    ,511,511,511
BEGIN DESCRIPTION:
BRINKLEY CREEK 14.0
END DESCRIPTION:
XS GIS Cut Line= 3
      3646631.82     10610150.34      3647026.79       10609942.
      3647790.68     10609008.84
#Sta/Elev= 30
  4482.2  352.84  4570.1  351.13  4615.4  345.01  4643.5  340.25  4649.3   337.9
  4725.9  326.51  4748.3  323.22  4769.9  321.82  4886.7  320.07  4982.4  322.72
  4988.9  320.66  4992.7  314.46  4995.5  313.96  4998.7  314.46  5009.7  316.12
  5017.6  322.53  5081.4  320.83  5145.3  321.76    5230   318.7  5258.7  320.53
    5280  323.52  5353.6  325.18  5394.4   325.6    5543  329.75  5703.1  338.33
    5805  346.23  5848.6  350.04  5983.7  366.06    6105  375.24  6134.7  378.73
#Mann= 7 ,-1 , 0
  4482.2     .16       0  4748.3     .12       0  4992.7     .07       0
  4998.7     .12       0  5353.6     .16       0  5703.1     .12       0
    5805     .16       0
Bank Sta=4725.9,5394.4
XS Rating Curve= 0 ,0
Exp/Cntr=0.3,0.1

Type RM Length L Ch R = 1 ,7932    ,356,356,356
BEGIN DESCRIPTION:
BRINKLEY CREEK 13.0
END DESCRIPTION:
XS GIS Cut Line= 3
       3646623.1     10610206.75      3647261.17     10610267.52
      3648272.49     10610206.76
#Sta/Elev= 30
  4525.2  354.12  4662.3  347.04  4702.5  339.38  4732.6  331.04  4752.7   328.5
  4893.4  324.82  4909.9  323.01  4929.6  321.58  4934.6  319.57  4983.8  318.74
  4993.8   313.8  5000.9  312.93  5003.6  312.43  5006.9  312.93  5013.9  314.53
    5024  320.23  5032.5  320.72  5145.5  318.93  5154.5  320.67  5184.6  319.09
  5202.4  322.67  5213.5  322.97  5234.7  325.53    5405  345.65  5615.4  373.67
  5685.5  385.07  5735.6   390.2    5926  399.93  6046.2   400.4  6179.3  395.79
#Mann= 5 ,-1 , 0
  4525.2     .16       0  4909.9     .12       0  5000.9     .07       0
  5006.9     .12       0  5213.5     .16       0
Bank Sta=4893.4,5234.7
XS Rating Curve= 0 ,0
Exp/Cntr=0.3,0.1

Type RM Length L Ch R = 1 ,7576    ,440,440,440
BEGIN DESCRIPTION:
BRINKLEY CREEK 12.0
END DESCRIPTION:
XS GIS Cut Line= 3
      3646749.64     10610660.18      3647149.61     10610560.19
      3647649.61     10610360.19
#Sta/Elev= 30
  4613.7  361.75  4654.9  354.71  4700.9  341.88  4714.2  337.22  4747.7  331.13
  4755.4  327.13  4788.9  324.63  4809.5  318.18  4851.9  318.42  4984.8   318.7
  4999.8  312.61  5002.5  312.11  5005.8  312.61  5015.7  318.54  5079.8   318.3
  5094.6   315.9  5118.9     316    5166  322.55  5202.3  326.19    5232  331.33
  5256.2  336.35  5261.4  339.88  5273.7  342.05  5280.4  345.31  5334.3  354.38
  5402.9  360.13  5471.6     369  5532.2  382.89  5549.7  384.21  5564.5  382.95
#Mann= 6 ,-1 , 0
  4613.7     .16       0  4700.9     .05       0  4851.9     .12       0
  4999.8     .07       0  5005.8     .12       0  5261.4     .16       0
Bank Sta=4788.9,5166
XS Rating Curve= 0 ,0
Exp/Cntr=0.3,0.1

Type RM Length L Ch R = 1 ,7136    ,469,469,469
BEGIN DESCRIPTION:
BRINKLEY CREEK 11.0
END DESCRIPTION:
XS GIS Cut Line= 3
      3646749.63     10610710.19      3647349.61     10610860.19
      3647699.59     10610410.22
#Sta/Elev= 30
  4351.9  363.32  4403.4  355.42  4457.5  340.67  4493.6  329.65  4581.2  320.14
  4595.9  318.28  4663.7  315.84  4699.8  317.56  4787.4   316.3  4846.7  317.98
  4939.4  315.13  4977.6  316.03  4992.1  315.51  4998.4  311.78  5003.5  311.73
  5006.3  311.23  5009.5  311.73  5012.9  315.83    5021  316.45  5097.9  314.92
  5147.7  319.99    5212  326.33  5234.6  331.21  5343.9  342.48  5411.1  352.02
  5433.7  356.28  5448.1  363.47  5468.9  368.16  5497.9  379.65  5540.4  385.98
#Mann= 7 ,-1 , 0
  4351.9     .16       0  4457.5     .05       0  4595.9     .12       0
  5003.5     .07       0  5009.5     .12       0  5343.9     .16       0
  5411.1     .12       0
Bank Sta=4581.2,5147.7
XS Rating Curve= 0 ,0
Exp/Cntr=0.3,0.1

Type RM Length L Ch R = 1 ,6667    ,783,783,783
BEGIN DESCRIPTION:
BRINKLEY CREEK 10.0
END DESCRIPTION:
XS GIS Cut Line= 3
      3646799.62     10611210.19      3647399.61     10611210.19
      3647999.59      10610610.2
#Sta/Elev= 30
  4437.3  359.48  4477.3  355.63  4576.8  340.08  4617.3  333.96  4657.3  325.65
  4677.3  324.51  4747.3   316.2  4761.5  315.43  4777.3  314.07  4867.3  312.99
  4947.3  313.19  4967.3   314.4  4977.3  313.94  4984.3  311.14    4987  310.64
  4990.3  311.14  4997.3  311.27  5007.3  313.33  5027.3  311.26  5051.4  311.67
  5065.6  313.21    5207  313.81  5221.1     313  5277.7  314.25  5348.4  314.45
    5405  312.96  5475.7  316.34  5673.7  328.31  5772.7  339.38  5885.8  353.69
#Mann= 5 ,-1 , 0
  4437.3     .16       0  4576.8     .05       0  4761.5     .12       0
  4984.3     .07       0  4990.3     .12       0
Bank Sta=4747.3,5475.7
XS Rating Curve= 0 ,0
Exp/Cntr=0.3,0.1

Type RM Length L Ch R = 1 ,5884    ,877,877,877
BEGIN DESCRIPTION:
BRINKLEY CREEK 9.0
END DESCRIPTION:
XS GIS Cut Line= 2
      3646361.11     10611740.22       3649392.3     10611714.18
#Sta/Elev= 30
  3617.9  366.92  3699.8  364.64  3816.4  362.19  3926.4  354.75  4006.4  347.35
  4126.4  329.09  4202.7  320.75  4356.4  313.61  4496.4  313.78  4596.4  311.35
  4712.9  310.07  4996.5  308.66  5006.5  310.69  5096.5  310.94  5433.5  307.64
  5436.2  307.14  5439.5  307.64  5606.5  311.57  5766.5  315.48  5896.5  314.88
  5906.5  317.88  6036.5  333.41  6063.3  334.68  6096.5  338.19  6162.3  338.71
  6276.5  337.14  6419.3  350.11  6526.5   361.7  6590.9   365.8  6649.2  366.14
#Mann= 9 ,-1 , 0
  3617.9     .16       0  3699.8     .05       0  4712.9     .12       0
  5433.5     .07       0  5439.5     .12       0  6063.3     .16       0
  6162.3     .05       0  6419.3     .16       0  6590.9     .12       0
Bank Sta=4596.4,5606.5
XS Rating Curve= 0 ,0
Exp/Cntr=0.3,0.1

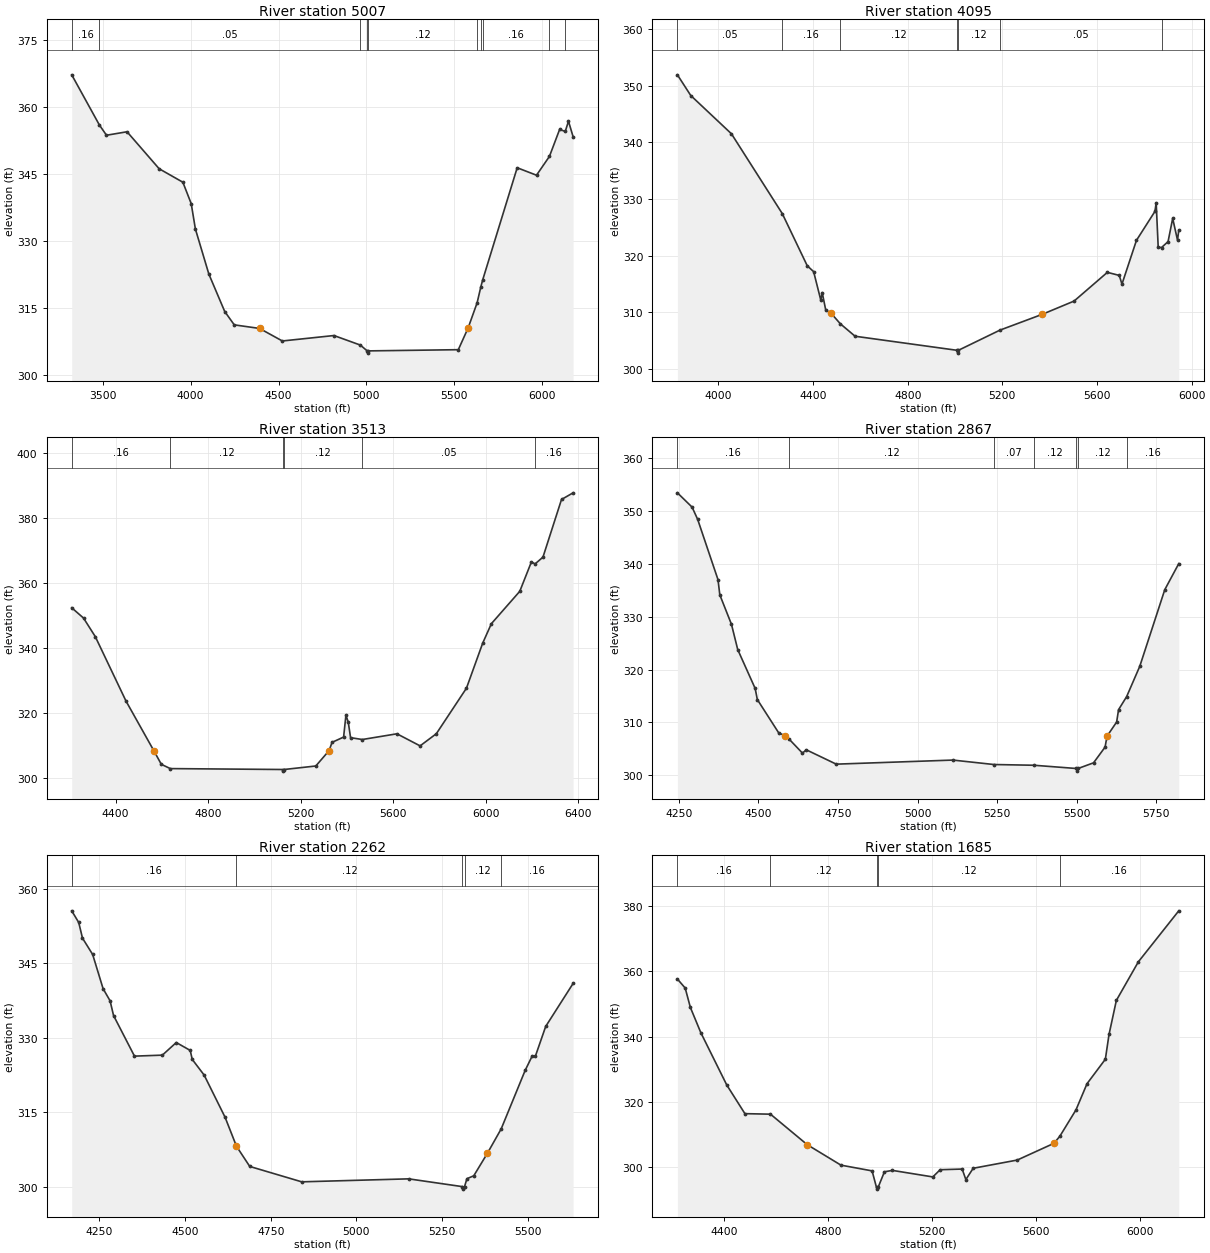
Type RM Length L Ch R = 1 ,5007    ,912,912,912
BEGIN DESCRIPTION:
BRINKLEY CREEK 8.0
END DESCRIPTION:
XS GIS Cut Line= 3
      3646267.32     10611912.09      3647543.39     10612448.56
      3648995.54     10612661.95
#Sta/Elev= 30
  3323.8  367.13  3480.9  355.91  3521.5   353.6  3638.4  354.38    3821   346.1
    3956  343.08  4003.5  338.28  4027.2  332.61  4103.9   322.5  4194.1  314.13
  4248.3  311.14  4392.3  310.34  4521.9  307.53  4815.4  308.75  4965.8  306.61
  5004.5  305.31  5007.2  304.81  5010.5  305.31  5522.9  305.58  5578.8  310.46
  5629.8  316.07  5650.6  319.58  5661.2  321.16  5857.8  346.32  5967.7  344.65
  6041.2  348.86  6099.1  354.89  6131.3  354.46  6149.6  356.74  6175.8  353.28
#Mann= 10 ,-1 , 0
  3323.8     .16       0  3480.9     .05       0  4965.8     .12       0
  5004.5     .07       0  5010.5     .12       0  5629.8     .16       0
  5650.6     .05       0  5661.2     .16       0  6041.2     .12       0
  6131.3     .16       0
Bank Sta=4392.3,5578.8
XS Rating Curve= 0 ,0
Exp/Cntr=0.3,0.1

Type RM Length L Ch R = 1 ,4095    ,582,582,582
BEGIN DESCRIPTION:
BRINKLEY CREEK 7.0
END DESCRIPTION:
XS GIS Cut Line= 3
      3646548.59     10613776.69      3647439.22     10613198.56
      3648474.75     10612985.21
#Sta/Elev= 30
  3826.5  351.92  3882.9  348.27  4054.9  341.51  4269.8  327.42  4375.2  318.22
  4402.3  317.17  4432.6  312.14  4438.5  313.48  4453.7  310.35  4474.8  309.89
  4515.1  307.97  4577.6  305.77  5008.2  303.29    5011  302.79  5014.2  303.29
  5189.8  306.85  5368.6  309.64  5503.1  311.98  5643.8  317.05  5694.1  316.51
  5705.5  314.97  5766.8   322.7    5845  327.82  5850.1  329.35  5858.7  321.49
  5872.8  321.43  5900.4  322.48  5919.9  326.57  5940.4  322.72  5945.6  324.53
#Mann= 7 ,-1 , 0
  3826.5     .05       0  4269.8     .16       0  4515.1     .12       0
  5008.2     .07       0  5014.2     .12       0  5189.8     .05       0
  5872.8     .16       0
Bank Sta=4474.8,5368.6
XS Rating Curve= 0 ,0
Exp/Cntr=0.3,0.1

Type RM Length L Ch R = 1 ,3513    ,646,646,646
BEGIN DESCRIPTION:
BRINKLEY CREEK 6.0
END DESCRIPTION:
XS GIS Cut Line= 3
      3646749.61     10613810.19      3647499.61     10613660.19
      3648899.59     10613560.19
#Sta/Elev= 30
  4210.2  352.37  4261.2   349.2  4312.2  343.47  4444.8  323.65  4567.1  308.11
  4597.7  304.15  4636.5  302.83  5122.4  302.55  5125.2  302.05  5128.4  302.55
  5265.8  303.63  5323.4  308.38    5336  310.91  5386.1  312.54  5396.1  319.27
  5406.2  317.14  5416.2  312.36  5466.9  311.79  5616.7  313.55  5716.9  309.83
  5787.1  313.57  5917.4   327.6  5987.6  341.47  6025.2  347.47    6148  357.44
  6198.2  366.48  6214.3  365.89  6248.3  367.97  6328.5  385.73  6378.6  387.78
#Mann= 6 ,-1 , 0
  4210.2     .16       0  4636.5     .12       0  5122.4     .07       0
  5128.4     .12       0  5466.9     .05       0  6214.3     .16       0
Bank Sta=4567.1,5323.4
XS Rating Curve= 0 ,0
Exp/Cntr=0.3,0.1

Type RM Length L Ch R = 1 ,2867    ,605,605,605
BEGIN DESCRIPTION:
BRINKLEY CREEK 5.0
END DESCRIPTION:
XS GIS Cut Line= 3
      3646749.58     10613860.18      3647449.61     10614110.19
       3648149.6     10614560.19
#Sta/Elev= 30
  4245.4  353.42  4291.6  350.71  4309.1  348.39  4372.9  337.01  4378.7  334.12
  4415.3  328.55    4435  323.77  4489.7  316.43  4496.6  314.32    4564     308
  4583.6  307.51  4596.8  306.82  4638.3   304.2  4650.5  304.82  4744.5  302.11
  5111.3  302.88    5240  302.04  5365.9   301.9  5498.6  301.29  5501.3  300.79
  5504.6  301.29  5553.1  302.36  5589.4  305.34  5595.4  307.39  5625.7  310.08
  5631.7  312.41  5657.1  314.88  5698.4  320.62    5777  335.11  5820.9  340.03
#Mann= 7 ,-1 , 0
  4245.4     .16       0  4596.8     .12       0    5240     .07       0
  5365.9     .12       0  5498.6     .07       0  5504.6     .12       0
  5657.1     .16       0
Bank Sta=4583.6,5595.4
XS Rating Curve= 0 ,0
Exp/Cntr=0.3,0.1

Type RM Length L Ch R = 1 ,2262    ,577,577,577
BEGIN DESCRIPTION:
BRINKLEY CREEK 4.0
END DESCRIPTION:
XS GIS Cut Line= 3
      3646649.57      10614760.2      3647449.61     10614610.19
      3648099.63     10614610.19
#Sta/Elev= 30
    4169  355.56  4189.4  353.21  4200.4  350.06  4230.1  346.77  4260.6  339.87
    4281  337.43  4291.1  334.47  4352.2  326.29  4433.6  326.49  4474.3  329.03
    4515  327.44  4520.9  325.63  4555.7  322.47  4616.7  313.99  4650.1  308.13
  4688.8  304.07  4840.5  300.97    5153  301.57    5310     300  5312.7   299.5
    5316     300    5323   301.6    5343  302.19    5383  306.75    5423  311.63
    5493  323.41    5513  326.24    5523   326.3    5553  332.27    5633  340.93
#Mann= 5 ,-1 , 0
    4169     .16       0  4650.1     .12       0    5310     .07       0
    5316     .12       0    5423     .16       0
Bank Sta=4650.1,5383
XS Rating Curve= 0 ,0
Exp/Cntr=0.3,0.1

Type RM Length L Ch R = 1 ,1685    ,555,555,555
BEGIN DESCRIPTION:
BRINKLEY CREEK 3.0
END DESCRIPTION:
XS GIS Cut Line= 3
      3646649.57     10615110.19      3647449.61     10615110.19
       3648249.6     10615910.18
#Sta/Elev= 30
  4219.5  357.64  4249.5  354.88  4269.5  348.93  4309.5  341.24  4409.5  325.19
  4479.5  316.39  4578.1  316.23  4719.5  306.89  4849.5  300.61  4969.5  298.85
  4986.5  293.76  4989.3  293.26  4992.5  293.76    5017  298.57  5047.8     299
  5203.4     297  5231.7  299.21  5316.5  299.41  5330.7  296.19  5358.9  299.65
  5528.7  302.17  5670.1   307.3  5692.8  309.47  5754.9  317.54  5797.4  325.56
  5868.1  333.07  5882.2  340.65  5910.5   351.1  5995.3  362.93  6150.9  378.55
#Mann= 5 ,-1 , 0
  4219.5     .16       0  4578.1     .12       0  4986.5     .07       0
  4992.5     .12       0  5692.8     .16       0
Bank Sta=4719.5,5670.1
XS Rating Curve= 0 ,0
Exp/Cntr=0.3,0.1

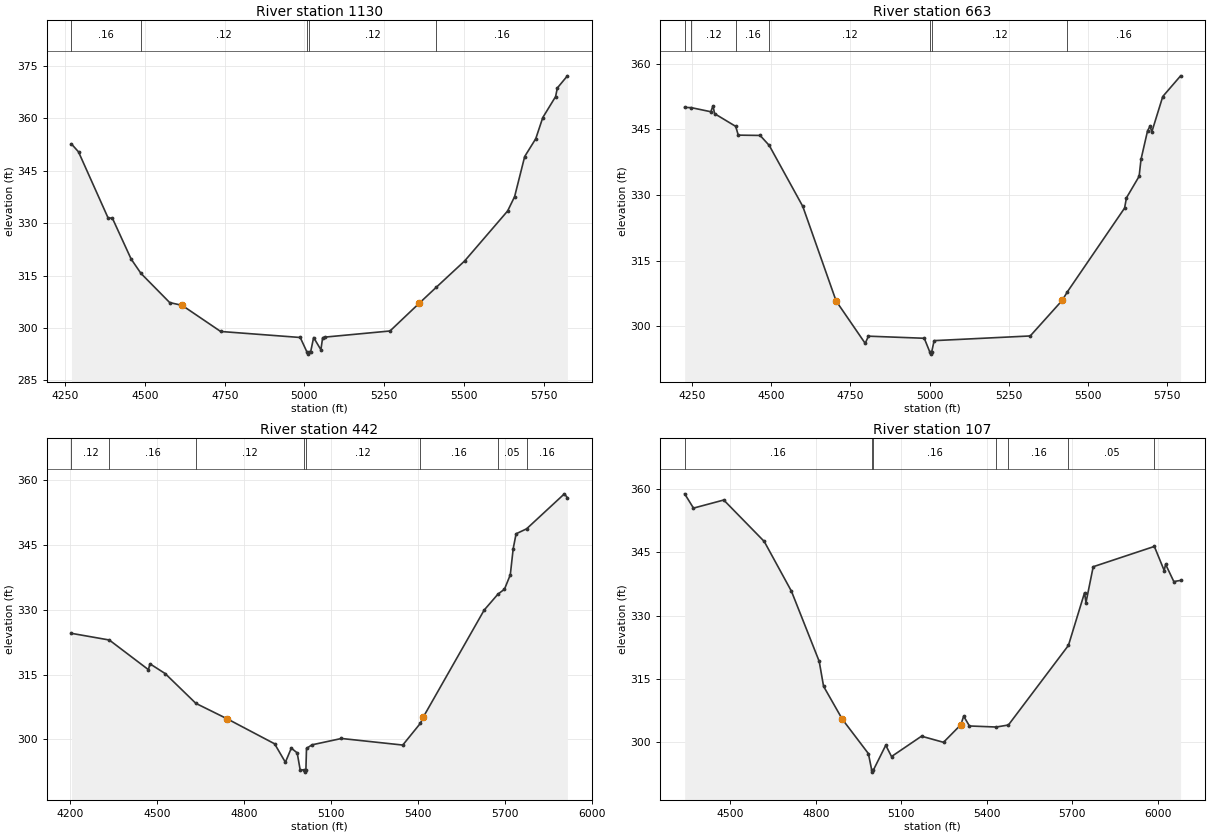
Type RM Length L Ch R = 1 ,1130    ,467,467,467
BEGIN DESCRIPTION:
BRINKLEY CREEK 2.0
END DESCRIPTION:
XS GIS Cut Line= 3
      3646699.59     10615410.18      3647399.61     10615610.19
      3648149.63      10615960.2
#Sta/Elev= 30
  4269.3  352.65  4291.4  350.39  4383.7  331.59    4398  331.36  4456.5  319.73
  4487.3  315.63  4577.4  307.29  4616.4  306.49  4737.3  299.02  4986.9   297.3
  5008.5  293.04  5011.3  292.54  5014.5  293.04  5019.4  293.12  5028.9  297.29
  5051.7  293.79  5057.2  297.24  5063.5   297.4  5268.5  299.16  5359.9  307.07
    5413  311.61  5502.6  319.19  5637.4  333.48  5659.4   337.6    5691  349.06
  5725.7  354.16  5747.7   360.2  5787.9   366.2  5793.4  368.67    5825  372.14
#Mann= 5 ,-1 , 0
  4269.3     .16       0  4487.3     .12       0  5008.5     .07       0
  5014.5     .12       0    5413     .16       0
Bank Sta=4616.4,5359.9
XS Rating Curve= 0 ,0
Exp/Cntr=0.3,0.1

Type RM Length L Ch R = 1 ,663     ,221,221,221
BEGIN DESCRIPTION:
Mapping XS baf59775
END DESCRIPTION:
XS GIS Cut Line= 2
      3646499.83      10615821.5       3648010.3      10616229.5
#Sta/Elev= 30
  4227.1  349.98  4248.4  349.92  4309.7  348.99  4316.4  350.34  4321.6  348.55
  4388.1  345.65  4396.2  343.65  4465.1  343.58  4493.9   341.3  4599.8  327.37
    4705  305.77  4796.6  296.11  4806.9  297.75    4983  297.27  5000.4  294.15
  5003.1  293.65  5006.4  294.15  5014.1  296.73  5317.3   297.8  5418.1  305.92
  5434.4  307.87  5614.9  326.99  5620.9  329.34  5660.8  334.25  5666.7   338.1
  5687.4  344.63  5695.5  345.75  5700.7  344.36  5735.4  352.47  5791.7  357.19
#Mann= 7 ,-1 , 0
  4227.1     .16       0  4248.4     .12       0  4388.1     .16       0
  4493.9     .12       0  5000.4     .07       0  5006.4     .12       0
  5434.4     .16       0
Bank Sta=4705,5418.1
XS Rating Curve= 0 ,0
Exp/Cntr=0.3,0.1

Type RM Length L Ch R = 1 ,442     ,335,335,335
BEGIN DESCRIPTION:
Mapping XS 9a85e5dc
END DESCRIPTION:
XS GIS Cut Line= 3
      3646384.88     10616075.86      3647352.78     10616258.15
       3648076.1     10616305.79
#Sta/Elev= 30
  4205.7  324.52  4336.1  322.98  4471.1  316.12  4476.2  317.48  4528.7  315.22
  4634.6  308.33  4743.6  304.72    4906  298.98  4943.2  294.71  4963.6  297.98
  4983.9  296.88  4994.1  292.98  5007.9  292.93  5010.7  292.43  5013.9  292.93
    5016  297.91  5034.8  298.74  5136.5  300.21  5347.8  298.69  5408.6  303.72
  5417.9  305.08  5628.4  329.89  5675.9  333.58  5698.5  334.73  5718.6  338.06
  5728.6  344.13  5738.6  347.54  5774.8  348.69  5905.1  356.78  5915.5  355.87
#Mann= 8 ,-1 , 0
  4205.7     .12       0  4336.1     .16       0  4634.6     .12       0
  5007.9     .07       0  5013.9     .12       0  5408.6     .16       0
  5675.9     .05       0  5774.8     .16       0
Bank Sta=4743.6,5417.9
XS Rating Curve= 0 ,0
Exp/Cntr=0.3,0.1

Type RM Length L Ch R = 1 ,107     ,0,0,0
BEGIN DESCRIPTION:
BRINKLEY CREEK 1.0
END DESCRIPTION:
XS GIS Cut Line= 3
      3646304.51      10616359.7      3647133.53     10616507.27
       3648023.3     10616377.06
#Sta/Elev= 30
  4339.5  358.93  4370.5  355.54  4476.7  357.46  4618.9  347.62  4714.3  335.82
  4811.9  319.15  4827.2  313.23  4893.2  305.39  4984.6  297.25  4996.2  293.35
  4998.9  292.85  5002.2  293.35  5045.5  299.23  5065.8  296.55  5171.1  301.38
  5248.3  299.93    5309  304.09  5319.1  306.14  5339.3  303.81  5433.5  303.56
  5476.2  304.04  5686.9  322.94  5743.5  335.44  5748.5  333.11  5773.9  341.62
  5988.6  346.44  6023.1  340.72  6028.1   342.2  6056.9   338.1  6080.8  338.37
#Mann= 7 ,-1 , 0
  4339.5     .16       0  4996.2     .07       0  5002.2     .16       0
  5433.5     .12       0  5476.2     .16       0  5686.9     .05       0
  5988.6     .16       0
Bank Sta=4893.2,5309
XS Rating Curve= 0 ,0
Exp/Cntr=0.3,0.1

Chan Stop Cuts=-1
Use User Specified Reach Order=0
Composite Channel Slope=5