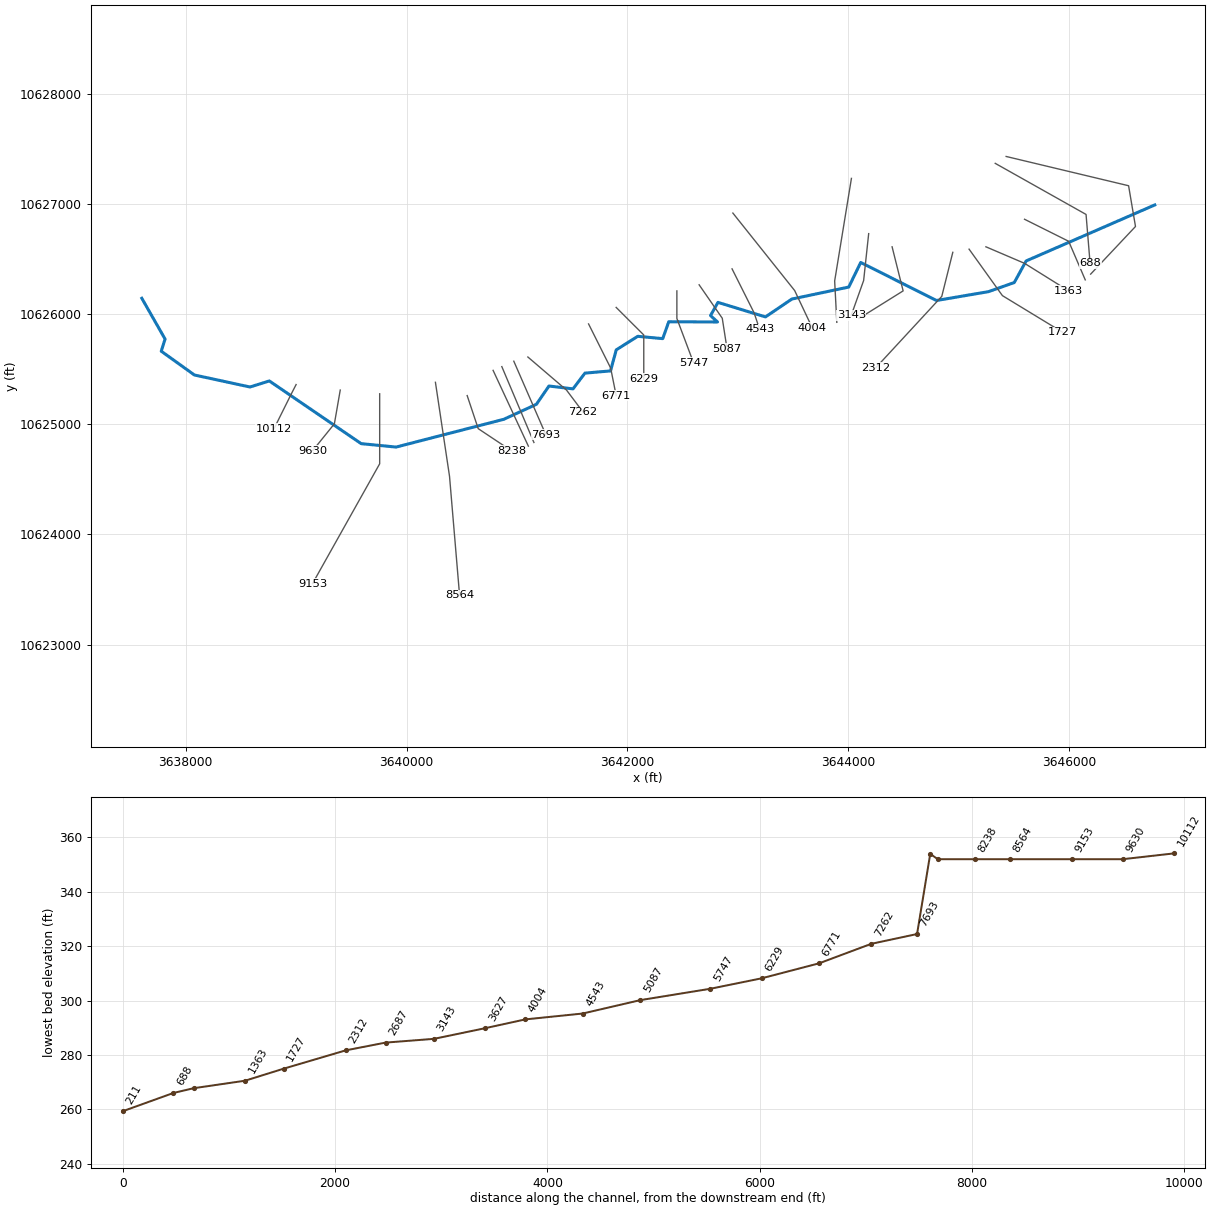
--- COLD SPRINGS BRANCH.prj (project) ---

Proj Title=COLD SPRINGS BRANCH Base Level Engineering
Current Plan=p01
Default Exp/Contr=0.3,0.1
English Units
Geom File=g01
Flow File=f01
Plan File=p01
BEGIN DESCRIPTION:
COLD SPRINGS BRANCH
END DESCRIPTION:

--- COLD SPRINGS BRANCH.p01 (plan) ---

Plan Title=Multiple Run
Short Identifier=Multiple
Geom File=g01
Flow File=f01
Subcritical Flow
K Sum by GR= 0
Std Step Tol= 0.01
Critical Tol= 0.01
Num of Std Step Trials= 20
Max Error Tol= 0.3
Flow Tol Ratio= 0.001
Split Flow NTrial= 30
Split Flow Tol= 0.02
Split Flow Ratio= 0.02
Log Output Level= 0
Friction Slope Method= 1
Unsteady Friction Slope Method= 2
Unsteady Bridges Friction Slope Method= 1
Parabolic Critical Depth
Global Vel Dist=  1 , 1 , 1
Global Log Level= 0
CheckData=True
Encroach Param= -1, 0, 0, 0
BEGIN DESCRIPTION:
Multiple Run
END DESCRIPTION:

--- COLD SPRINGS BRANCH.f01 (steady flow) ---

Flow Title=Multiple
Number of Profiles=7
Profile Names=10-year,25-year,50-year,1pct_min,100-year,1pct_plu,500-year
River Rch & RM= COLD SPRINGS BRA,Reach-1,10112
    1318    1846    2291    2076    2808    3798    4202
River Rch & RM= COLD SPRINGS BRA,Reach-1,7817
    1784    2545    3199    2933    3967    5365    6084
River Rch & RM= COLD SPRINGS BRA,Reach-1,879
    1942    2787    3518    3241    4383    5928    6792
Boundary for River Rch & Prof#=COLD SPRINGS BRA,Reach-1,1
Up Type=0
Dn Type=3
Dn Slope=0.005
Boundary for River Rch & Prof#=COLD SPRINGS BRA,Reach-1,2
Up Type=0
Dn Type=3
Dn Slope=0.005
Boundary for River Rch & Prof#=COLD SPRINGS BRA,Reach-1,3
Up Type=0
Dn Type=3
Dn Slope=0.005
Boundary for River Rch & Prof#=COLD SPRINGS BRA,Reach-1,4
Up Type=0
Dn Type=3
Dn Slope=0.005
Boundary for River Rch & Prof#=COLD SPRINGS BRA,Reach-1,5
Up Type=0
Dn Type=3
Dn Slope=0.005
Boundary for River Rch & Prof#=COLD SPRINGS BRA,Reach-1,6
Up Type=0
Dn Type=3
Dn Slope=0.005
Boundary for River Rch & Prof#=COLD SPRINGS BRA,Reach-1,7
Up Type=0
Dn Type=3
Dn Slope=0.005

--- COLD SPRINGS BRANCH.g01 (geometry) ---

Geom Title=Existing Conditions

River Reach=COLD SPRINGS BRA,Reach-1
Reach XY= 30
      3637601.75     10626143.00      3637812.50     10625773.00
      3637777.75     10625663.00      3638078.25     10625447.00
      3638582.00     10625338.00      3638757.00     10625393.00
      3639589.50     10624824.00      3639905.50     10624793.00
      3640881.50     10625045.00      3641176.75     10625181.00
      3641290.75     10625347.00      3641508.50     10625321.00
      3641616.75     10625464.00      3641848.50     10625484.00
      3641900.25     10625675.00      3642095.00     10625798.00
      3642321.50     10625777.00      3642376.00     10625930.00
      3642818.00     10625928.00      3642754.50     10625986.00
      3642821.50     10626106.00      3643252.50     10625974.00
      3643491.00     10626136.00      3644007.00     10626245.00
      3644115.25     10626468.00      3644801.50     10626123.00
      3645272.25     10626203.00      3645506.50     10626286.00
      3645614.25     10626482.00      3646779.50     10626990.00

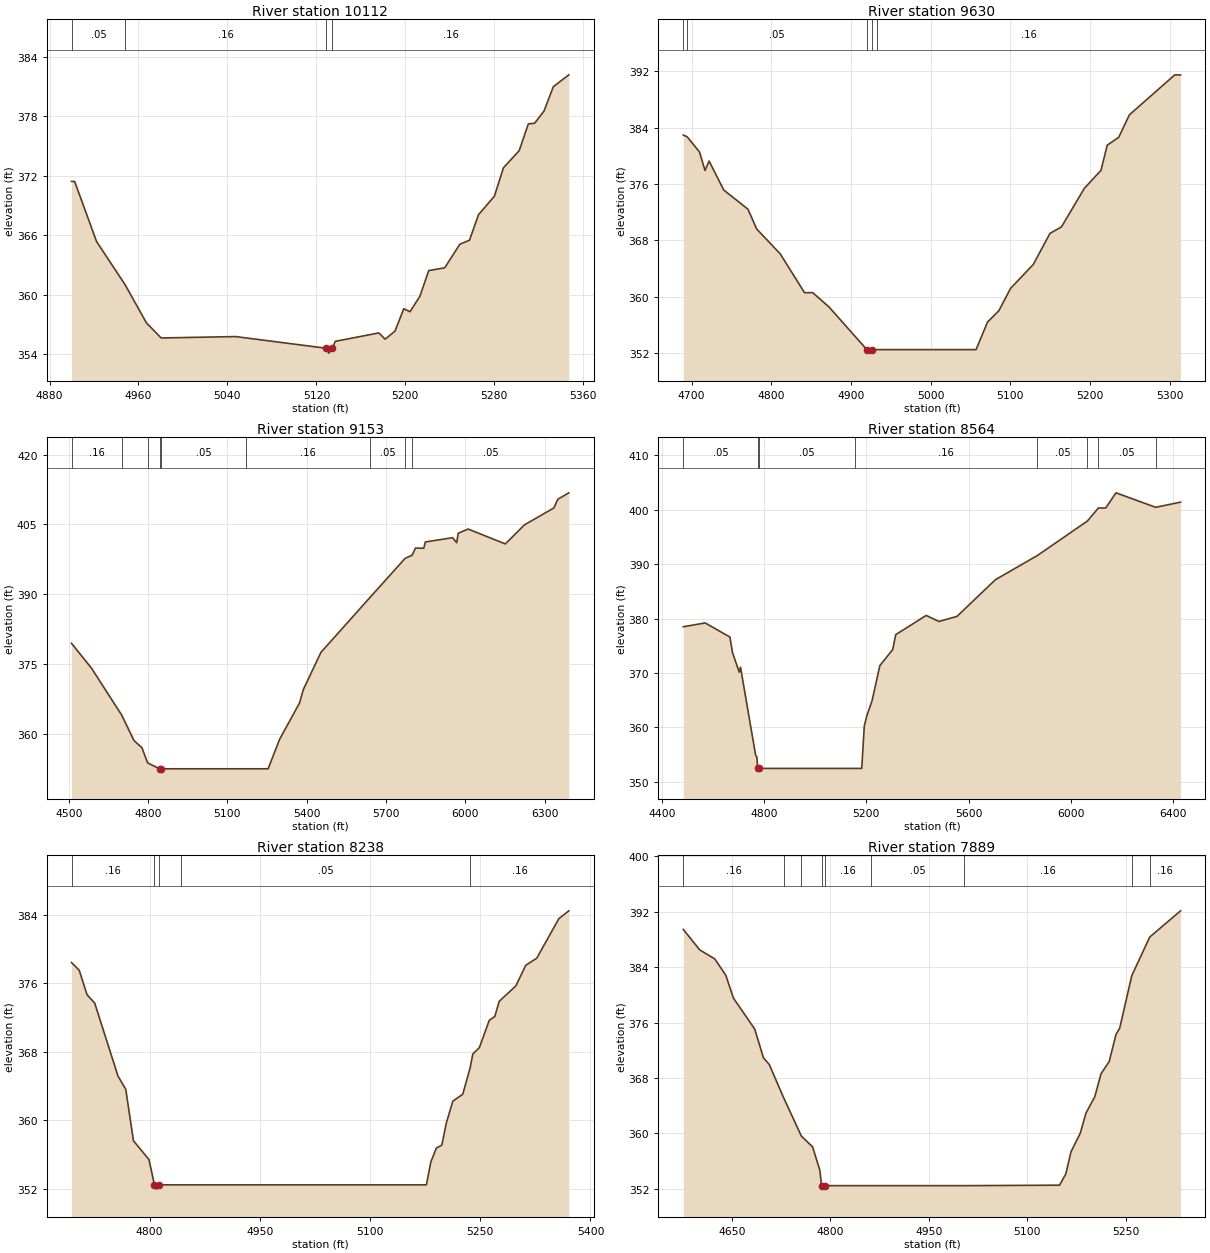
Type RM Length L Ch R = 1,10112,482,482,482
BEGIN DESCRIPTION:
COLD SPRINGS BRANCH 21.0
END DESCRIPTION:
XS GIS Cut Line= 3
      3638999.62     10625360.21      3638954.00     10625271.00
      3638799.63     10624960.23
#Sta/Elev= 30
  4899.8  371.42  4902.6  371.42  4922.3  365.36  4948.0  360.99  4967.2  357.14
  4980.4  355.62  5047.4  355.76  5128.4  354.59  5131.2  354.09  5134.4  354.59
  5137.0  355.28  5176.2  356.13  5181.8  355.50  5190.7  356.31  5198.6  358.57
  5204.2  358.27  5213.1  359.83  5221.0  362.42  5235.4  362.70  5249.0  365.08
  5257.7  365.49  5265.8  368.06  5280.1  369.93  5288.2  372.79  5302.4  374.53
  5310.6  377.23  5316.2  377.29  5324.7  378.52  5333.1  380.98  5347.0  382.18
#Mann=4,-1,0
  4899.8    0.05       0  4948.0    0.16       0  5128.4    0.07       0
  5134.4    0.16       0
Bank Sta=5128.4,5134.4
Exp/Cntr=0.3,0.1

Type RM Length L Ch R = 1,9630,477,477,477
BEGIN DESCRIPTION:
COLD SPRINGS BRANCH 20.0
END DESCRIPTION:
XS GIS Cut Line= 3
      3639399.61     10625310.20      3639346.55     10625004.26
      3639149.62     10624760.21
#Sta/Elev= 30
  4689.5  382.92  4694.3  382.69  4709.8  380.54  4716.8  377.90  4721.9  379.24
  4740.3  375.12  4770.7  372.40  4781.6  369.59  4811.3  366.04  4841.7  360.54
  4851.9  360.55  4872.2  358.54  4919.9  352.46  4922.7  351.96  4925.9  352.46
  4932.2  352.46  5057.0  352.46  5071.3  356.36  5085.7  358.00  5100.1  361.13
  5128.9  364.57  5149.7  368.96  5164.1  369.88  5192.9  375.37  5213.7  377.91
  5221.6  381.49  5236.0  382.61  5249.4  385.80  5306.4  391.48  5313.6  391.46
#Mann=5,-1,0
  4689.5    0.16       0  4694.3    0.05       0  4919.9    0.07       0
  4925.9    0.05       0  4932.2    0.16       0
Bank Sta=4919.9,4925.9
Exp/Cntr=0.3,0.1

Type RM Length L Ch R = 1,9153,589,589,589
BEGIN DESCRIPTION:
COLD SPRINGS BRANCH 19.0
END DESCRIPTION:
XS GIS Cut Line= 3
      3639756.82     10625276.50      3639756.82     10624641.13
      3639148.16     10623553.88
#Sta/Elev= 30
  4510.5  379.45  4586.8  374.04  4700.4  364.00  4746.8  358.54  4776.8  357.00
  4798.5  353.73  4843.8  352.46  4846.6  351.96  4849.8  352.46  5169.2  352.46
  5254.3  352.46  5297.7  358.79  5373.0  366.60  5387.6  369.51  5454.1  377.50
  5639.9  389.32  5772.9  397.73  5799.3  398.40  5811.7  399.93  5843.4  399.90
  5849.1  401.24  5951.9  402.16  5967.8  401.10  5973.5  403.12  6011.2  404.02
  6151.6  400.82  6224.2  404.92  6335.4  408.56  6350.3  410.42  6391.9  411.81
#Mann=9,-1,0
  4510.5    0.16       0  4700.4     0.1       0  4798.5    0.05       0
  4843.8   0.033       0  4849.8    0.05       0  5169.2    0.16       0
  5639.9    0.05       0  5772.9    0.16       0  5799.3    0.05       0
Bank Sta=4843.8,4849.8
Exp/Cntr=0.3,0.1

Type RM Length L Ch R = 1,8564,326,326,326
BEGIN DESCRIPTION:
COLD SPRINGS BRANCH 18.0
END DESCRIPTION:
XS GIS Cut Line= 3
      3640262.03     10625380.70      3640389.78     10624527.38
      3640480.78     10623448.44
#Sta/Elev= 30
  4483.7  378.49  4569.4  379.19  4666.2  376.60  4676.3  373.74  4702.7  370.15
  4707.7  371.05  4766.8  354.88  4771.8  354.53  4774.5  352.46  4777.2  351.96
  4780.5  352.46  5153.9  352.46  5181.9  352.46  5192.0  360.28  5202.1  362.17
  5222.4  364.90  5252.7  371.34  5303.2  374.31  5315.0  377.04  5434.0  380.57
  5484.2  379.46  5554.5  380.39  5705.0  387.14  5869.1  391.58  6064.9  397.92
  6108.1  400.32  6136.5  400.32  6176.7  403.10  6332.0  400.44  6429.3  401.39
#Mann=8,-1,0
  4483.7    0.05       0  4774.5   0.033       0  4780.5    0.05       0
  5153.9    0.16       0  5869.1    0.05       0  6064.9    0.08       0
  6108.1    0.05       0  6332.0    0.16       0
Bank Sta=4774.5,4780.5
Exp/Cntr=0.3,0.1

Type RM Length L Ch R = 1,8238,349,349,349
BEGIN DESCRIPTION:
COLD SPRINGS BRANCH 17.0
END DESCRIPTION:
XS GIS Cut Line= 3
      3640549.61     10625260.17      3640649.61     10624960.19
      3640949.64     10624760.17
#Sta/Elev= 30
  4693.7  378.42  4704.2  377.52  4714.8  374.66  4725.3  373.68  4756.9  365.17
  4767.5  363.62  4778.0  357.61  4799.1  355.41  4806.6  352.46  4809.4  351.96
  4812.6  352.46  4842.2  352.46  5176.7  352.46  5182.7  355.13  5190.2  356.75
  5197.7  357.10  5203.7  359.65  5212.7  362.24  5226.2  363.04  5236.4  366.19
  5239.8  367.73  5248.8  368.49  5262.3  371.68  5269.8  372.12  5275.8  373.89
  5298.4  375.69  5311.9  378.10  5326.9  378.93  5356.9  383.54  5370.5  384.46
#Mann=5,-1,0
  4693.7    0.16       0  4806.6   0.033       0  4812.6    0.16       0
  4842.2    0.05       0  5236.4    0.16       0
Bank Sta=4806.6,4812.6
Exp/Cntr=0.3,0.1

Type RM Length L Ch R = 1,7889,72,72,72
BEGIN DESCRIPTION:
COLD SPRINGS BRANCH 16.0
END DESCRIPTION:
XS GIS Cut Line= 2
      3640784.52     10625489.04      3641103.97     10624801.53
#Sta/Elev= 30
  4575.6  389.47  4600.7  386.51  4623.6  385.21  4640.5  382.84  4652.0  379.56
  4684.6  375.06  4697.8  370.93  4706.7  369.96  4728.5  365.18  4755.6  359.63
  4772.8  358.05  4783.8  354.68  4786.4  352.46  4789.1  351.96  4792.4  352.46
  4861.9  352.46  5003.0  352.46  5149.3  352.53  5158.8  354.16  5166.7  357.35
  5180.8  360.03  5189.6  362.97  5202.9  365.28  5212.5  368.63  5224.9  370.38
  5235.4  374.33  5240.9  375.19  5259.3  382.77  5286.7  388.36  5333.7  392.15
#Mann=9,-1,0
  4575.6    0.16       0  4728.5    0.05       0  4755.6    0.16       0
  4786.4   0.033       0  4792.4    0.16       0  4861.9    0.05       0
  5003.0    0.16       0  5259.3     0.1       0  5286.7    0.16       0
Bank Sta=4786.4,4792.4
Exp/Cntr=0.3,0.1

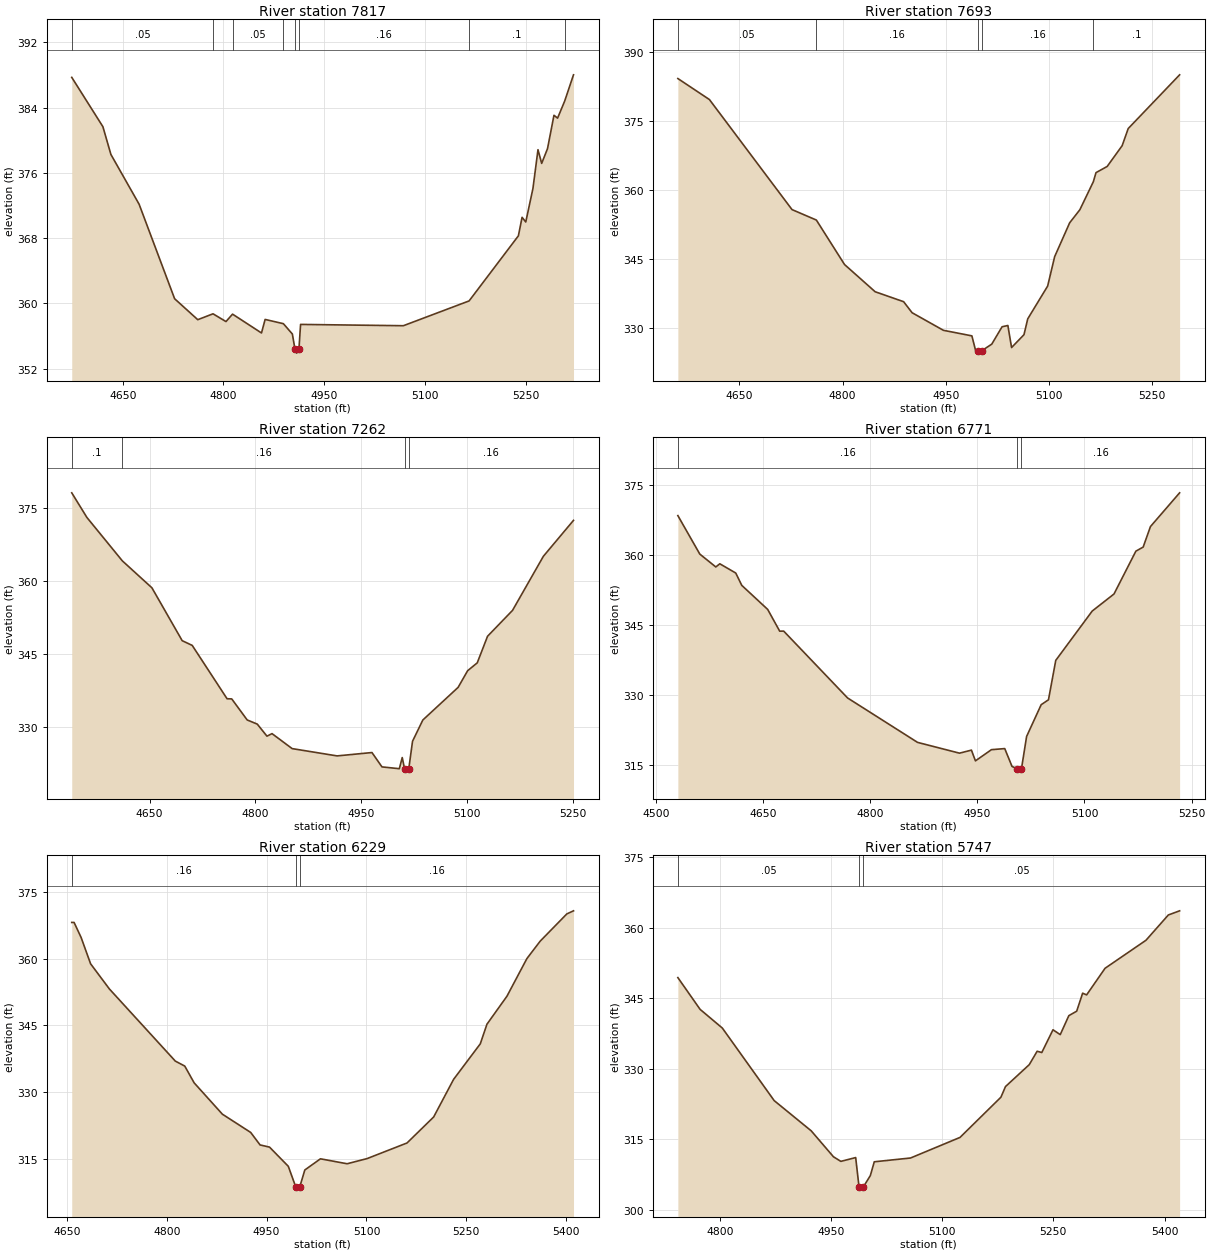
Type RM Length L Ch R = 1,7817,124,124,124
BEGIN DESCRIPTION:
Mapping XS 61bbda2a
END DESCRIPTION:
XS GIS Cut Line= 2
      3640863.61     10625522.94      3641154.33     10624834.51
#Sta/Elev= 30
  4574.1  387.70  4620.5  381.65  4632.4  378.25  4674.4  372.15  4727.3  360.56
  4761.8  357.99  4784.5  358.71  4803.8  357.76  4813.6  358.67  4856.7  356.36
  4862.1  358.02  4889.3  357.50  4902.7  356.23  4906.5  354.39  4909.2  353.89
  4912.5  354.39  4914.9  357.41  5068.0  357.25  5165.9  360.29  5239.3  368.27
  5244.8  370.54  5250.3  369.97  5261.0  374.08  5268.5  378.83  5274.0  377.15
  5282.7  378.96  5292.3  383.05  5297.7  382.70  5308.2  384.78  5321.4  388.01
#Mann=8,-1,0
  4574.1    0.05       0  4784.5    0.16       0  4813.6    0.05       0
  4889.3    0.16       0  4906.5    0.07       0  4912.5    0.16       0
  5165.9     0.1       0  5308.2    0.16       0
Bank Sta=4906.5,4912.5
Exp/Cntr=0.3,0.1

Type RM Length L Ch R = 1,7693,431,431,431
BEGIN DESCRIPTION:
Mapping XS 4edf1898
END DESCRIPTION:
XS GIS Cut Line= 2
      3640972.06     10625572.28      3641263.06     10624903.67
#Sta/Elev= 30
  4560.6  384.26  4606.5  379.68  4726.5  355.72  4761.9  353.44  4802.8  343.76
  4847.3  337.83  4888.7  335.66  4901.0  333.26  4946.5  329.43  4987.9  328.22
  4993.3  325.04  4996.1  324.96  4998.9  324.46  5002.1  324.96  5016.8  326.42
  5031.8  330.20  5040.2  330.48  5045.6  325.68  5063.6  328.47  5069.1  331.93
  5098.0  339.06  5108.2  345.47  5130.0  352.84  5144.8  355.68  5164.4  361.78
  5168.3  363.77  5184.5  365.11  5206.3  369.64  5215.1  373.37  5289.8  385.07
#Mann=5,-1,0
  4560.6    0.05       0  4761.9    0.16       0  4996.1    0.07       0
  5002.1    0.16       0  5164.4     0.1       0
Bank Sta=4996.1,5002.1
Exp/Cntr=0.3,0.1

Type RM Length L Ch R = 1,7262,491,491,491
BEGIN DESCRIPTION:
COLD SPRINGS BRANCH 15.0
END DESCRIPTION:
XS GIS Cut Line= 3
      3641099.57     10625610.22      3641449.61     10625310.19
      3641599.59     10625110.21
#Sta/Elev= 30
  4539.8  378.09  4561.3  373.02  4611.5  364.10  4653.4  358.56  4696.3  347.69
  4710.5  346.72  4759.9  335.75  4766.5  335.72  4788.4  331.39  4802.7  330.54
  4816.4  328.06  4823.6  328.58  4852.1  325.50  4915.8  324.00  4965.2  324.69
  4979.4  321.74  5004.0  321.37  5008.1  323.66  5011.4  321.37  5014.1  320.87
  5017.4  321.37  5022.7  327.01  5037.3  331.38  5087.3  338.09  5100.8  341.52
  5114.4  343.13  5129.0  348.60  5164.4  353.92  5208.1  365.04  5250.8  372.43
#Mann=4,-1,0
  4539.8     0.1       0  4611.5    0.16       0  5011.4    0.07       0
  5017.4    0.16       0
Bank Sta=5011.4,5017.4
Exp/Cntr=0.3,0.1

Type RM Length L Ch R = 1,6771,542,542,542
BEGIN DESCRIPTION:
COLD SPRINGS BRANCH 14.0
END DESCRIPTION:
XS GIS Cut Line= 3
      3641649.63     10625910.16      3641849.61     10625510.19
      3641899.60     10625260.22
#Sta/Elev= 30
  4531.0  368.48  4561.7  360.23  4584.1  357.47  4589.7  358.15  4612.0  356.17
  4620.4  353.53  4656.7  348.37  4673.5  343.71  4679.1  343.72  4768.5  329.39
  4866.4  319.87  4925.1  317.56  4941.8  318.21  4947.4  315.91  4969.8  318.31
  4988.4  318.54  4998.6  314.72  5005.8  314.21  5008.5  313.71  5011.8  314.21
  5019.0  321.14  5039.4  327.95  5049.6  329.00  5059.8  337.45  5110.8  348.02
  5141.3  351.68  5171.9  360.86  5182.1  361.73  5192.3  366.13  5233.1  373.36
#Mann=3,-1,0
  4531.0    0.16       0  5005.8    0.07       0  5011.8    0.16       0
Bank Sta=5005.8,5011.8
Exp/Cntr=0.3,0.1

Type RM Length L Ch R = 1,6229,482,482,482
BEGIN DESCRIPTION:
COLD SPRINGS BRANCH 13.0
END DESCRIPTION:
XS GIS Cut Line= 3
      3641899.63     10626060.17      3642149.61     10625810.19
      3642149.61     10625410.21
#Sta/Elev= 30
  4657.4  368.11  4660.9  368.11  4671.5  364.72  4685.7  358.82  4713.9  353.17
  4812.9  336.96  4827.1  335.84  4841.2  332.07  4883.6  325.03  4926.1  320.93
  4940.2  318.12  4954.4  317.63  4982.6  313.32  4993.8  308.69  4996.5  308.19
  4999.8  308.69  5007.4  312.49  5030.9  315.00  5070.9  313.89  5100.9  315.05
  5160.9  318.56  5200.9  324.40  5230.9  332.87  5270.9  340.83  5280.9  345.24
  5310.9  351.52  5340.9  359.99  5360.9  363.91  5400.9  370.03  5410.9  370.72
#Mann=3,-1,0
  4657.4    0.16       0  4993.8    0.07       0  4999.8    0.16       0
Bank Sta=4993.8,4999.8
Exp/Cntr=0.3,0.1

Type RM Length L Ch R = 1,5747,660,660,660
BEGIN DESCRIPTION:
COLD SPRINGS BRANCH 12.0
END DESCRIPTION:
XS GIS Cut Line= 3
      3642449.61     10626210.16      3642449.61     10625960.19
      3642599.62     10625560.16
#Sta/Elev= 30
  4743.2  349.40  4773.2  342.64  4803.2  338.66  4873.2  323.21  4923.2  316.77
  4953.2  311.25  4963.2  310.27  4983.2  311.08  4987.7  304.86  4990.4  304.36
  4993.7  304.86  5003.0  307.25  5008.3  310.18  5057.3  310.99  5124.0  315.37
  5179.2  323.93  5185.4  326.20  5217.5  330.87  5228.1  333.72  5234.4  333.45
  5249.5  338.29  5259.3  337.26  5270.9  341.30  5281.5  342.25  5289.5  346.08
  5294.9  345.72  5319.8  351.39  5375.0  357.35  5405.2  362.74  5420.4  363.62
#Mann=3,-1,0
  4743.2    0.05       0  4987.7    0.03       0  4993.7    0.05       0
Bank Sta=4987.7,4993.7
Exp/Cntr=0.3,0.1

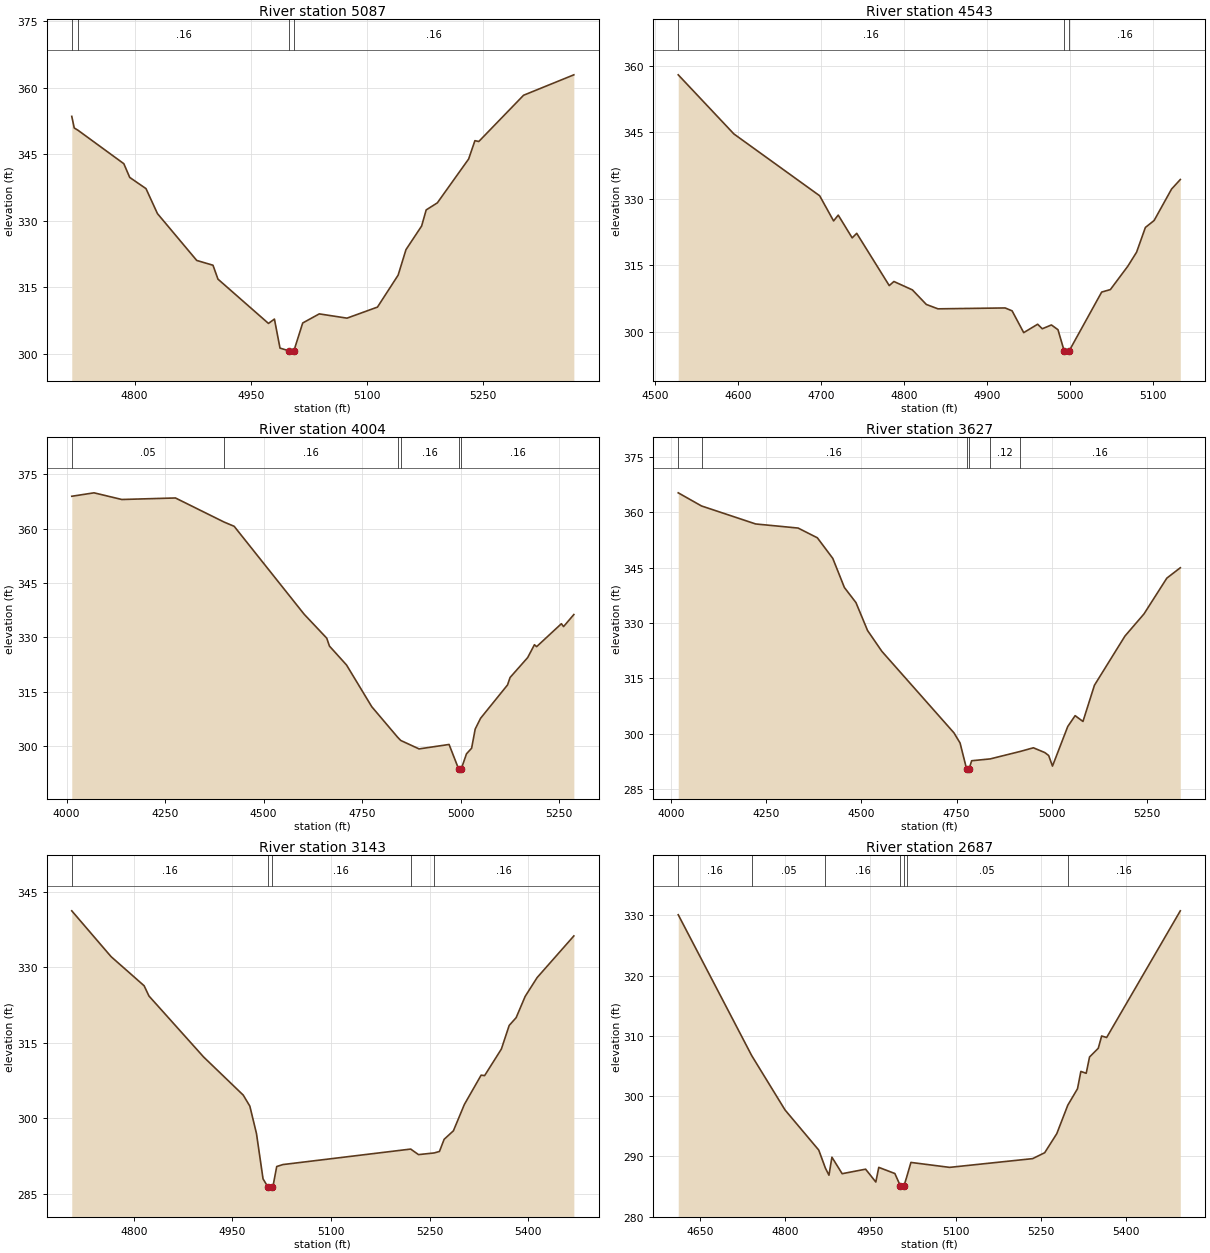
Type RM Length L Ch R = 1,5087,544,544,544
BEGIN DESCRIPTION:
COLD SPRINGS BRANCH 11.0
END DESCRIPTION:
XS GIS Cut Line= 3
      3642651.20     10626265.44      3642860.84     10625962.05
      3642903.80     10625686.05
#Sta/Elev= 30
  4718.9  353.51  4722.1  350.90  4727.2  350.35  4786.1  342.85  4793.7  339.76
  4814.7  337.24  4829.5  331.61  4880.2  321.06  4901.2  319.98  4907.6  316.85
  4972.8  306.87  4980.5  307.85  4987.7  301.31  4999.6  300.68  5002.3  300.18
  5005.6  300.68  5017.0  306.97  5038.4  309.02  5074.2  308.06  5113.5  310.55
  5140.2  317.75  5150.3  323.49  5170.5  328.81  5176.4  332.44  5190.8  334.03
  5231.2  343.91  5239.3  348.04  5244.3  347.85  5302.1  358.27  5367.0  362.87
#Mann=4,-1,0
  4718.9    0.05       0  4727.2    0.16       0  4999.6    0.07       0
  5005.6    0.16       0
Bank Sta=4999.6,5005.6
Exp/Cntr=0.3,0.1

Type RM Length L Ch R = 1,4543,539,539,539
BEGIN DESCRIPTION:
COLD SPRINGS BRANCH 10.0
END DESCRIPTION:
XS GIS Cut Line= 3
      3642949.60     10626410.21      3643149.61     10626010.19
      3643199.59     10625860.24
#Sta/Elev= 30
  4527.6  357.96  4594.7  344.64  4698.1  330.71  4714.9  325.04  4720.5  326.35
  4737.3  321.22  4742.8  322.24  4782.0  310.47  4787.6  311.39  4809.9  309.50
  4826.7  306.22  4840.7  305.23  4921.7  305.43  4930.1  304.78  4944.1  299.87
  4960.9  301.76  4966.5  300.74  4977.5  301.60  4985.4  300.53  4992.9  295.75
  4995.7  295.25  4998.9  295.75  5038.1  309.01  5048.6  309.57  5069.7  314.86
  5080.2  318.00  5090.8  323.57  5101.3  325.13  5122.4  332.23  5132.9  334.37
#Mann=3,-1,0
  4527.6    0.16       0  4992.9    0.07       0  4998.9    0.16       0
Bank Sta=4992.9,4998.9
Exp/Cntr=0.3,0.1

Type RM Length L Ch R = 1,4004,377,377,377
BEGIN DESCRIPTION:
COLD SPRINGS BRANCH 9.0
END DESCRIPTION:
XS GIS Cut Line= 3
      3642956.92     10626916.29      3643516.80     10626213.18
      3643676.77     10625873.79
#Sta/Elev= 30
  4013.1  368.95  4069.6  369.90  4140.1  368.06  4276.2  368.48  4399.3  361.85
  4425.2  360.66  4602.9  336.38  4660.1  329.79  4667.0  327.60  4710.3  322.39
  4774.3  310.88  4840.0  302.45  4847.9  301.56  4894.4  299.23  4970.5  300.46
  4995.1  293.60  4997.9  293.10  5001.1  293.60  5014.7  297.88  5027.7  299.42
  5036.8  304.71  5050.4  307.68  5118.8  316.88  5125.3  318.94  5169.9  324.43
  5187.1  327.98  5192.7  327.45  5255.5  333.78  5261.0  332.99  5287.1  336.31
#Mann=6,-1,0
  4013.1    0.05       0  4399.3    0.16       0  4840.0    0.12       0
  4847.9    0.16       0  4995.1    0.07       0  5001.1    0.16       0
Bank Sta=4995.1,5001.1
Exp/Cntr=0.3,0.1

Type RM Length L Ch R = 1,3627,484,484,484
BEGIN DESCRIPTION:
COLD SPRINGS BRANCH 8.0
END DESCRIPTION:
XS GIS Cut Line= 3
      3644031.12     10627230.95      3643879.22     10626299.99
      3643898.73     10625924.87
#Sta/Elev= 30
  4018.7  365.24  4079.9  361.68  4222.1  356.81  4333.6  355.70  4384.2  353.06
  4424.8  347.47  4455.2  339.60  4485.6  335.51  4516.0  327.96  4553.7  322.31
  4743.1  300.23  4759.1  297.49  4776.4  290.38  4779.1  289.88  4782.4  290.38
  4789.5  292.69  4838.3  293.19  4917.4  295.22  4951.6  296.20  4981.8  294.90
  4991.8  294.11  5001.8  291.24  5041.9  301.96  5061.3  304.90  5081.9  303.33
  5112.0  313.13  5192.1  326.44  5242.2  332.45  5302.2  342.14  5337.6  344.95
#Mann=6,-1,0
  4018.7    0.05       0  4079.9    0.16       0  4776.4    0.07       0
  4782.4    0.16       0  4838.3    0.12       0  4917.4    0.16       0
Bank Sta=4776.4,4782.4
Exp/Cntr=0.3,0.1

Type RM Length L Ch R = 1,3143,456,456,456
BEGIN DESCRIPTION:
COLD SPRINGS BRANCH 7.0
END DESCRIPTION:
XS GIS Cut Line= 3
      3644187.38     10626729.68      3644141.80     10626304.33
      3644028.96     10625987.51
#Sta/Elev= 30
  4705.5  341.26  4765.3  332.16  4815.6  326.37  4823.0  324.33  4906.1  312.22
  4966.5  304.63  4976.5  302.45  4986.6  297.00  4996.6  287.99  5003.7  286.45
  5006.5  285.95  5009.7  286.45  5012.4  286.97  5017.4  290.44  5026.8  290.83
  5221.3  293.91  5233.2  292.81  5257.1  293.14  5265.1  293.44  5272.2  295.85
  5286.3  297.54  5303.0  302.78  5328.5  308.60  5333.8  308.51  5359.3  313.79
  5371.2  318.48  5381.8  320.03  5395.5  324.25  5413.7  327.99  5469.6  336.27
#Mann=5,-1,0
  4705.5    0.16       0  5003.7    0.07       0  5009.7    0.16       0
  5221.3    0.05       0  5257.1    0.16       0
Bank Sta=5003.7,5009.7
Exp/Cntr=0.3,0.1

Type RM Length L Ch R = 1,2687,375,375,375
BEGIN DESCRIPTION:
COLD SPRINGS BRANCH 6.0
END DESCRIPTION:
XS GIS Cut Line= 3
      3644399.61     10626610.20      3644499.61     10626210.19
      3644099.63     10625960.20
#Sta/Elev= 30
  4611.8  330.10  4741.2  306.72  4799.9  297.70  4859.2  291.05  4871.0  288.04
  4877.2  286.88  4882.4  289.87  4900.4  287.13  4941.7  287.88  4959.7  285.75
  4964.9  288.18  4993.2  287.16  5003.1  285.07  5005.8  284.57  5009.1  285.07
  5014.0  286.56  5021.5  289.00  5089.6  288.18  5235.8  289.63  5257.0  290.61
  5278.3  293.77  5297.7  298.50  5314.8  301.23  5320.7  304.10  5330.1  303.79
  5336.0  306.50  5351.4  307.95  5357.3  309.98  5366.1  309.73  5495.8  330.75
#Mann=7,-1,0
  4611.8    0.16       0  4741.2    0.05       0  4871.0    0.16       0
  5003.1    0.07       0  5009.1    0.16       0  5014.0    0.05       0
  5297.7    0.16       0
Bank Sta=5003.1,5009.1
Exp/Cntr=0.3,0.1

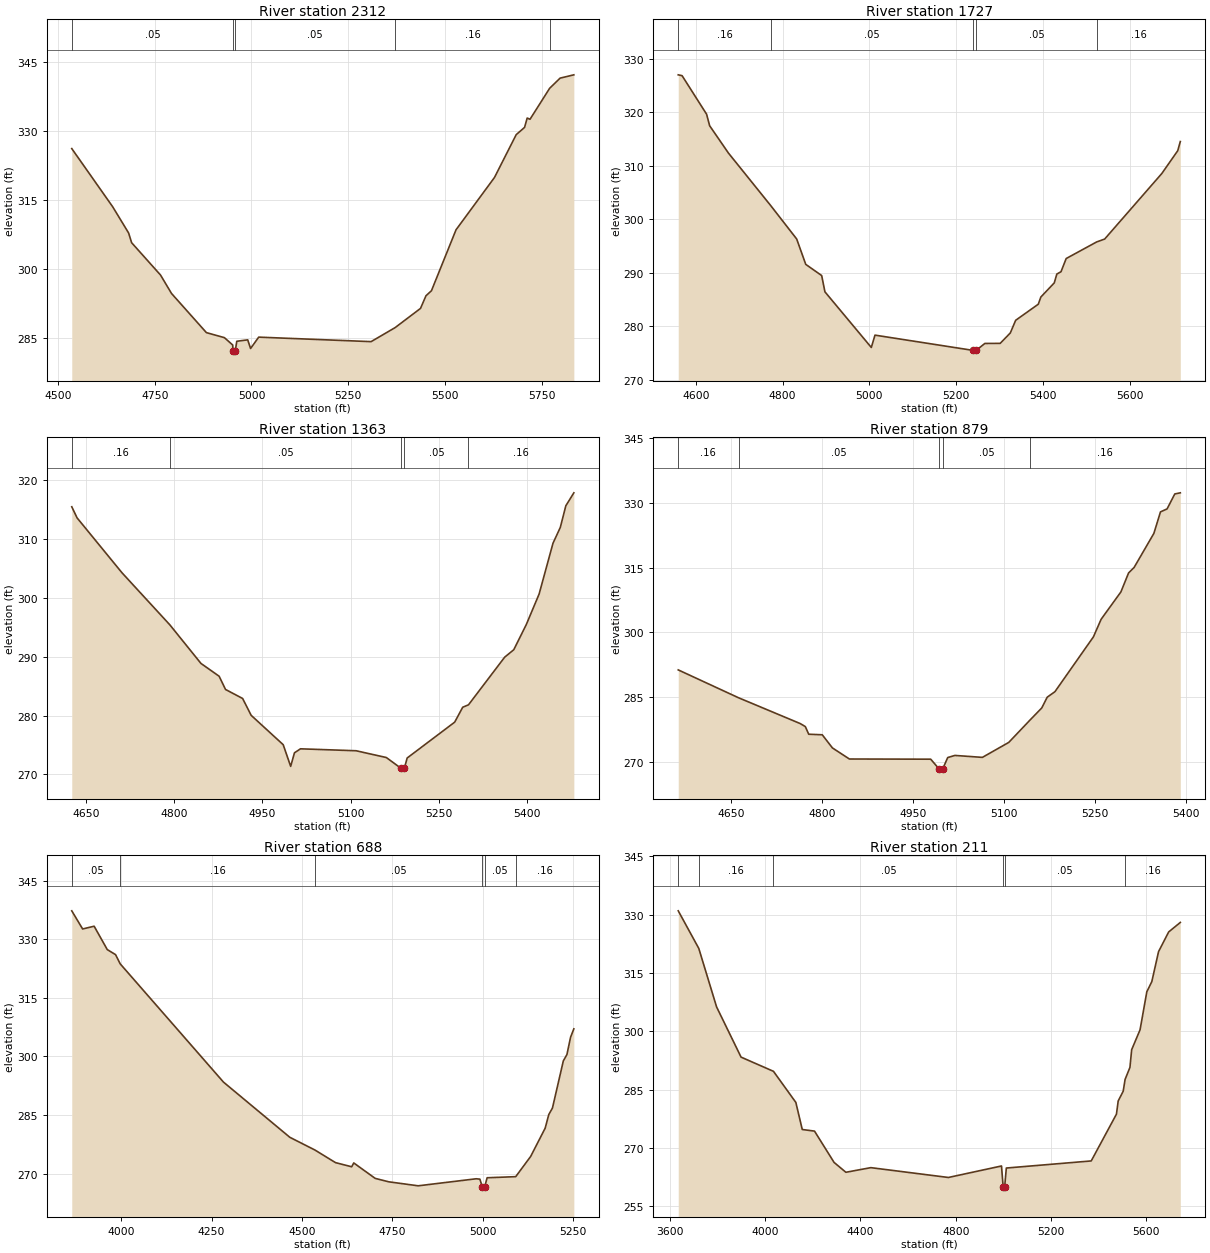
Type RM Length L Ch R = 1,2312,585,585,585
BEGIN DESCRIPTION:
COLD SPRINGS BRANCH 5.0
END DESCRIPTION:
XS GIS Cut Line= 3
      3644949.60     10626560.15      3644849.61     10626160.19
      3644249.58     10625510.16
#Sta/Elev= 30
  4535.8  326.23  4641.4  313.58  4682.6  307.87  4690.4  305.75  4765.1  298.71
  4793.5  294.70  4883.6  286.18  4930.0  285.09  4951.5  283.49  4952.2  282.22
  4954.9  281.72  4958.2  282.22  4962.0  284.30  4990.3  284.61  4997.7  282.73
  5018.7  285.20  5309.0  284.22  5371.2  287.28  5436.6  291.45  5450.8  294.21
  5464.9  295.30  5528.4  308.56  5627.7  319.94  5683.8  329.26  5705.4  330.84
  5712.2  332.87  5719.5  332.61  5770.2  339.35  5797.2  341.56  5832.7  342.28
#Mann=5,-1,0
  4535.8    0.05       0  4952.2    0.03       0  4958.2    0.05       0
  5371.2    0.16       0  5770.2    0.05       0
Bank Sta=4952.2,4958.2
Exp/Cntr=0.3,0.1

Type RM Length L Ch R = 1,1727,364,364,364
BEGIN DESCRIPTION:
COLD SPRINGS BRANCH 4.0
END DESCRIPTION:
XS GIS Cut Line= 3
      3645097.03     10626589.01      3645399.13     10626167.12
      3645944.16     10625834.91
#Sta/Elev= 30
  4559.6  326.97  4568.5  326.81  4625.0  319.61  4632.0  317.46  4675.3  312.36
  4773.1  302.51  4832.6  296.31  4853.5  291.57  4890.2  289.48  4897.7  286.44
  5004.6  276.05  5013.1  278.35  5240.0  275.49  5242.8  274.99  5246.0  275.49
  5266.4  276.80  5301.6  276.81  5325.0  278.76  5337.3  281.12  5389.5  284.13
  5395.4  285.47  5426.3  288.11  5432.2  289.76  5441.8  290.19  5453.8  292.66
  5524.1  295.76  5542.5  296.30  5674.2  308.54  5710.9  312.80  5716.8  314.51
#Mann=5,-1,0
  4559.6    0.16       0  4773.1    0.05       0  5240.0    0.03       0
  5246.0    0.05       0  5524.1    0.16       0
Bank Sta=5240,5246
Exp/Cntr=0.3,0.1

Type RM Length L Ch R = 1,1363,484,484,484
BEGIN DESCRIPTION:
COLD SPRINGS BRANCH 3.0
END DESCRIPTION:
XS GIS Cut Line= 3
      3645249.63     10626610.18      3645599.61     10626460.19
      3645999.63     10626210.17
#Sta/Elev= 30
  4626.3  315.46  4635.3  313.58  4711.5  304.26  4792.8  295.41  4845.7  288.85
  4876.5  286.68  4887.4  284.43  4916.4  282.90  4930.9  280.04  4985.3  275.05
  4998.0  271.37  5004.4  273.67  5014.7  274.35  5109.1  274.02  5160.4  272.87
  5185.1  271.06  5187.8  270.56  5191.1  271.06  5195.8  272.79  5276.5  278.88
  5290.1  281.41  5299.9  281.82  5361.4  289.92  5376.8  291.18  5398.0  295.44
  5419.8  300.63  5443.4  309.27  5455.8  311.95  5465.2  315.63  5478.8  317.83
#Mann=5,-1,0
  4626.3    0.16       0  4792.8    0.05       0  5185.1    0.03       0
  5191.1    0.05       0  5299.9    0.16       0
Bank Sta=5185.1,5191.1
Exp/Cntr=0.3,0.1

Type RM Length L Ch R = 1,879,191,191,191
BEGIN DESCRIPTION:
COLD SPRINGS BRANCH 2.0
END DESCRIPTION:
XS GIS Cut Line= 3
      3645599.65     10626860.17      3645999.61     10626660.19
      3646149.63     10626310.15
#Sta/Elev= 30
  4562.9  291.29  4662.3  284.83  4764.1  278.84  4772.5  278.14  4778.1  276.37
  4800.4  276.24  4817.2  273.19  4845.2  270.62  4979.3  270.58  4993.1  268.31
  4995.8  267.81  4999.1  268.31  5007.3  270.96  5019.1  271.45  5064.5  271.00
  5108.0  274.47  5143.2  279.68  5162.4  282.46  5171.4  284.96  5184.1  286.23
  5247.6  298.95  5260.3  303.03  5292.9  309.37  5305.6  313.78  5314.7  315.05
  5347.3  322.95  5358.2  327.94  5369.1  328.63  5381.8  332.10  5390.9  332.36
#Mann=5,-1,0
  4562.9    0.16       0  4662.3    0.05       0  4993.1    0.03       0
  4999.1    0.05       0  5143.2    0.16       0
Bank Sta=4993.1,4999.1
Exp/Cntr=0.3,0.1

Type RM Length L Ch R = 1,688,477,477,477
BEGIN DESCRIPTION:
Mapping XS 022b6a7c
END DESCRIPTION:
XS GIS Cut Line= 3
      3645334.02     10627367.42      3646156.94     10626903.88
      3646193.40     10626461.17
#Sta/Elev= 30
  3863.4  337.27  3893.4  332.63  3925.3  333.33  3961.6  327.35  3984.5  326.06
  3997.4  323.70  4283.0  293.44  4466.6  279.31  4535.9  276.06  4592.9  272.83
  4637.6  271.77  4643.4  272.75  4702.6  268.80  4740.2  267.92  4821.6  266.90
  4982.2  268.70  4992.2  268.60  4999.2  266.55  5002.0  266.05  5005.2  266.55
  5012.3  268.96  5091.3  269.24  5132.7  274.42  5172.8  281.65  5182.8  285.14
  5192.9  286.79  5223.0  298.86  5233.0  300.50  5243.0  304.91  5252.1  307.07
#Mann=6,-1,0
  3863.4    0.05       0  3997.4    0.16       0  4535.9    0.05       0
  4999.2    0.03       0  5005.2    0.05       0  5091.3    0.16       0
Bank Sta=4999.2,5005.2
Exp/Cntr=0.3,0.1

Type RM Length L Ch R = 1,211,0,0,0
BEGIN DESCRIPTION:
COLD SPRINGS BRANCH 1.0
END DESCRIPTION:
XS GIS Cut Line= 4
      3645432.97     10627429.92      3646542.35     10627164.30
      3646604.85     10626794.51      3646198.61     10626362.22
#Sta/Elev= 30
  3634.4  331.01  3720.7  321.34  3795.5  306.27  3898.3  293.34  4034.5  289.68
  4128.4  281.68  4155.4  274.70  4206.8  274.29  4289.0  266.23  4338.6  263.69
  4443.3  264.88  4769.2  262.35  4992.3  265.31  4999.4  259.85  5002.2  259.35
  5005.4  259.85  5012.6  264.78  5369.2  266.61  5475.2  278.66  5482.5  282.06
  5503.5  284.56  5511.5  287.61  5531.8  290.69  5539.1  295.26  5574.3  300.37
  5602.7  310.16  5623.7  312.78  5652.0  320.50  5694.5  325.57  5743.4  328.02
#Mann=6,-1,0
  3634.4    0.05       0  3720.7    0.16       0  4034.5    0.05       0
  4999.4    0.03       0  5005.4    0.05       0  5511.5    0.16       0
Bank Sta=4999.4,5005.4
Exp/Cntr=0.3,0.1

Chan Stop Cuts=-1