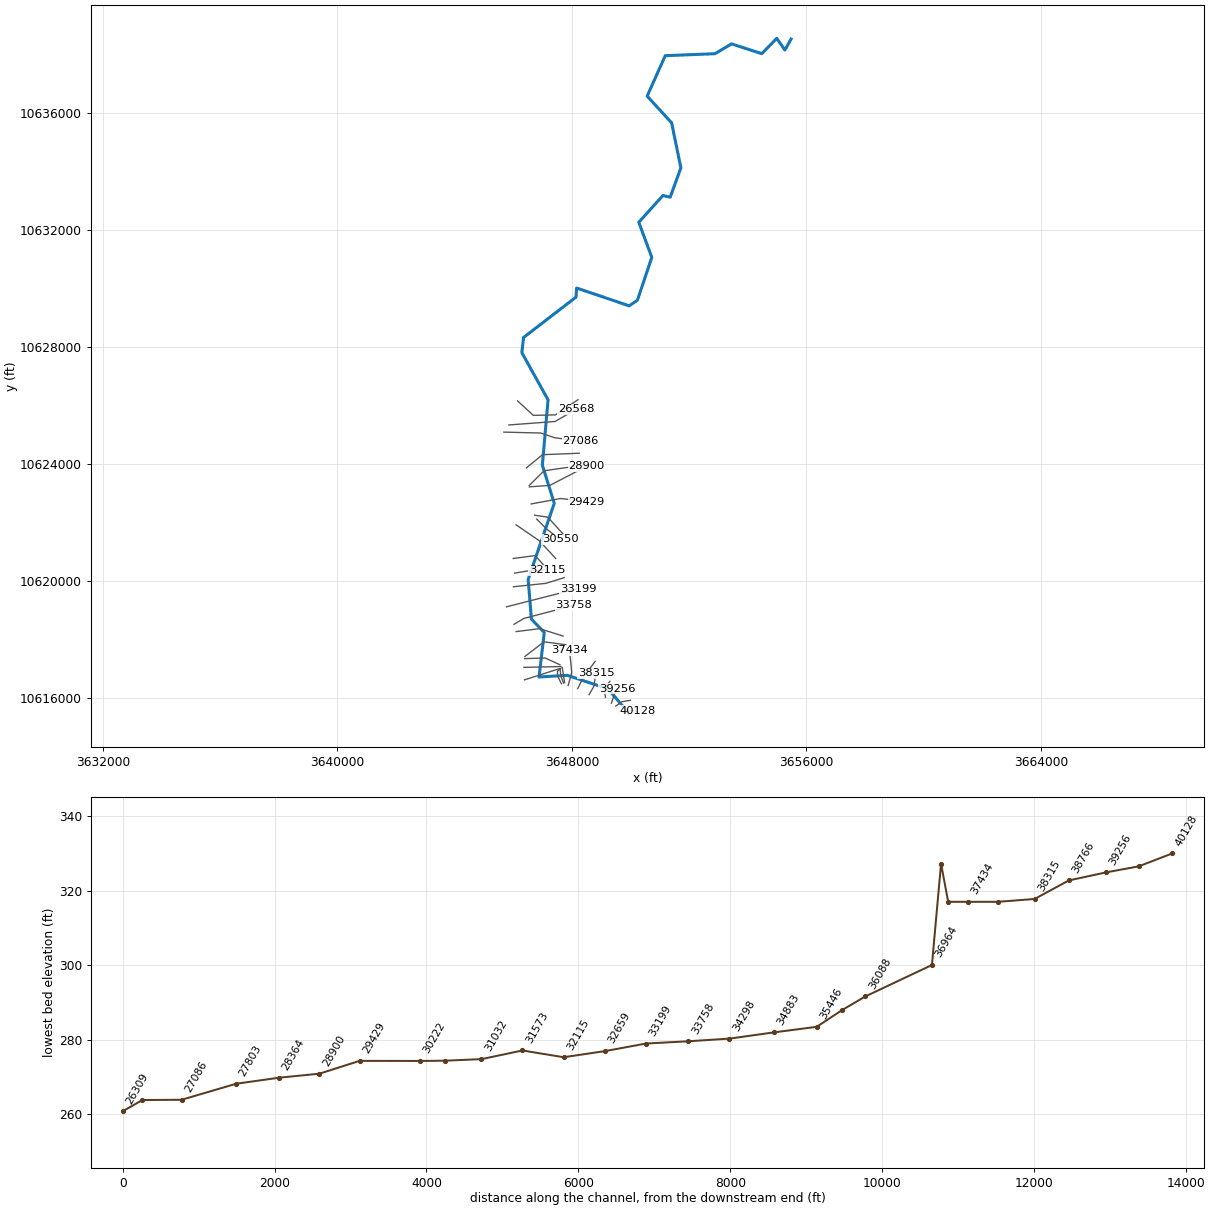
--- EDWARDS CREEK.prj (project) ---

Proj Title=EDWARDS CREEK Base Level Engineering
Current Plan=p01
Default Exp/Contr=0.3,0.1
English Units
Geom File=g01
Flow File=f01
Plan File=p01
Y Axis Title=Elevation
X Axis Title(PF)=Main Channel Distance
X Axis Title(XS)=Station
BEGIN DESCRIPTION:
EDWARDS CREEK
END DESCRIPTION:
DSS Export Rating Curves= 0
DSS Export Rating Curve Sorted= 0
DSS Export Volume Flow Curves= 0
DXF OffsetX= 0
DXF OffsetY= 0
DXF ScaleX= 1
DXF ScaleY= 10

--- EDWARDS CREEK.p01 (plan) ---

Plan Title=Multiple Run
Short Identifier=Multiple
Geom File=g01
Flow File=f01
Subcritical Flow
K Sum by GR= 0
Std Step Tol= 0.01
Critical Tol= 0.01
Num of Std Step Trials= 20
Max Error Tol= 0.3
Flow Tol Ratio= 0.001
Split Flow NTrial= 30
Split Flow Tol= 0.02
Split Flow Ratio= 0.02
Log Output Level= 0
Friction Slope Method= 1
Unsteady Friction Slope Method= 2
Unsteady Bridges Friction Slope Method= 1
Parabolic Critical Depth
Global Vel Dist=  1 , 1 , 1
Global Log Level= 0
CheckData=True
Encroach Param= -1, 0, 0, 0
BEGIN DESCRIPTION:
Multiple Run
END DESCRIPTION:

--- EDWARDS CREEK.f01 (steady flow) ---

Flow Title=Multiple
Program Version=4.10
Number of Profiles= 7
Profile Names=10-year,25-year,50-year,1pct_min,100-year,1pct_plu,500-year
River Rch & RM=EDWARDS CREEK,Reach-1         ,40128
     287     374     444     388     525     710     736
River Rch & RM=EDWARDS CREEK,Reach-1         ,36088
    4762    6992    8956    8342   11282   15258   17897
River Rch & RM=EDWARDS CREEK,Reach-1         ,29429
    4742    6956    8907    8293   11215   15167   17779
River Rch & RM=EDWARDS CREEK,Reach-1         ,27086
    5526    8149   10471    9780   13227   17888   21102
River Rch & RM=EDWARDS CREEK,Reach-1         ,26568
    5526    8149   10471    9780   13227   17888   21102
River Rch & RM=EDWARDS CREEK,Reach-1         ,24271
    6130    9069   11681   10933   14786   19996   23683
River Rch & RM=EDWARDS CREEK,Reach-1         ,22377
    6165    9104   11711   10949   14808   20026   23671
River Rch & RM=EDWARDS CREEK,Reach-1         ,16539
    6068    8937   11476   10712   14486   19591   23091
River Rch & RM=EDWARDS CREEK,Reach-1         ,7567
    6175    9100   11691   10920   14768   19972   23578
Boundary for River Rch & Prof#=EDWARDS CREEK,Reach-1         , 1
Up Type= 0
Dn Type= 3
Dn Slope=0.0015
Boundary for River Rch & Prof#=EDWARDS CREEK,Reach-1         , 2
Up Type= 0
Dn Type= 3
Dn Slope=0.0015
Boundary for River Rch & Prof#=EDWARDS CREEK,Reach-1         , 3
Up Type= 0
Dn Type= 3
Dn Slope=0.0015
Boundary for River Rch & Prof#=EDWARDS CREEK,Reach-1         , 4
Up Type= 0
Dn Type= 3
Dn Slope=0.0015
Boundary for River Rch & Prof#=EDWARDS CREEK,Reach-1         , 5
Up Type= 0
Dn Type= 3
Dn Slope=0.0015
Boundary for River Rch & Prof#=EDWARDS CREEK,Reach-1         , 6
Up Type= 0
Dn Type= 3
Dn Slope=0.0015
Boundary for River Rch & Prof#=EDWARDS CREEK,Reach-1         , 7
Up Type= 0
Dn Type= 3
Dn Slope=0.0015
DSS Import GetInterval= 0
DSS Import GetPeak= 0
DSS Import FillOption= 0

--- EDWARDS CREEK.g01 (geometry) ---

Geom Title=Existing Conditions
Program Version=4.10

River Reach=EDWARDS CREEK   ,Reach-1
Reach XY= 30
      3649942.78     10615463.13       3649242.5       10616295.
      3647844.25       10616766.       3646881.5       10616706.
        3647059.       10618231.      3646621.25       10618686.
      3646509.75       10620045.      3647399.75       10622647.
      3646994.25       10623952.        3647189.       10626188.
       3646293.5       10627801.      3646353.25       10628319.
      3648143.25       10629700.       3648163.5       10630010.
       3649955.5       10629402.      3650236.25       10629591.
      3650728.75       10631060.       3650283.5       10632259.
      3651107.75       10633175.      3651355.75       10633116.
       3651719.5       10634120.      3651405.75       10635659.
       3650569.5       10636574.      3651187.25       10637957.
      3652885.75       10638024.      3653448.25       10638360.
      3654481.25       10638026.       3654991.5       10638550.
      3655269.75       10638150.      3655479.11     10638525.24

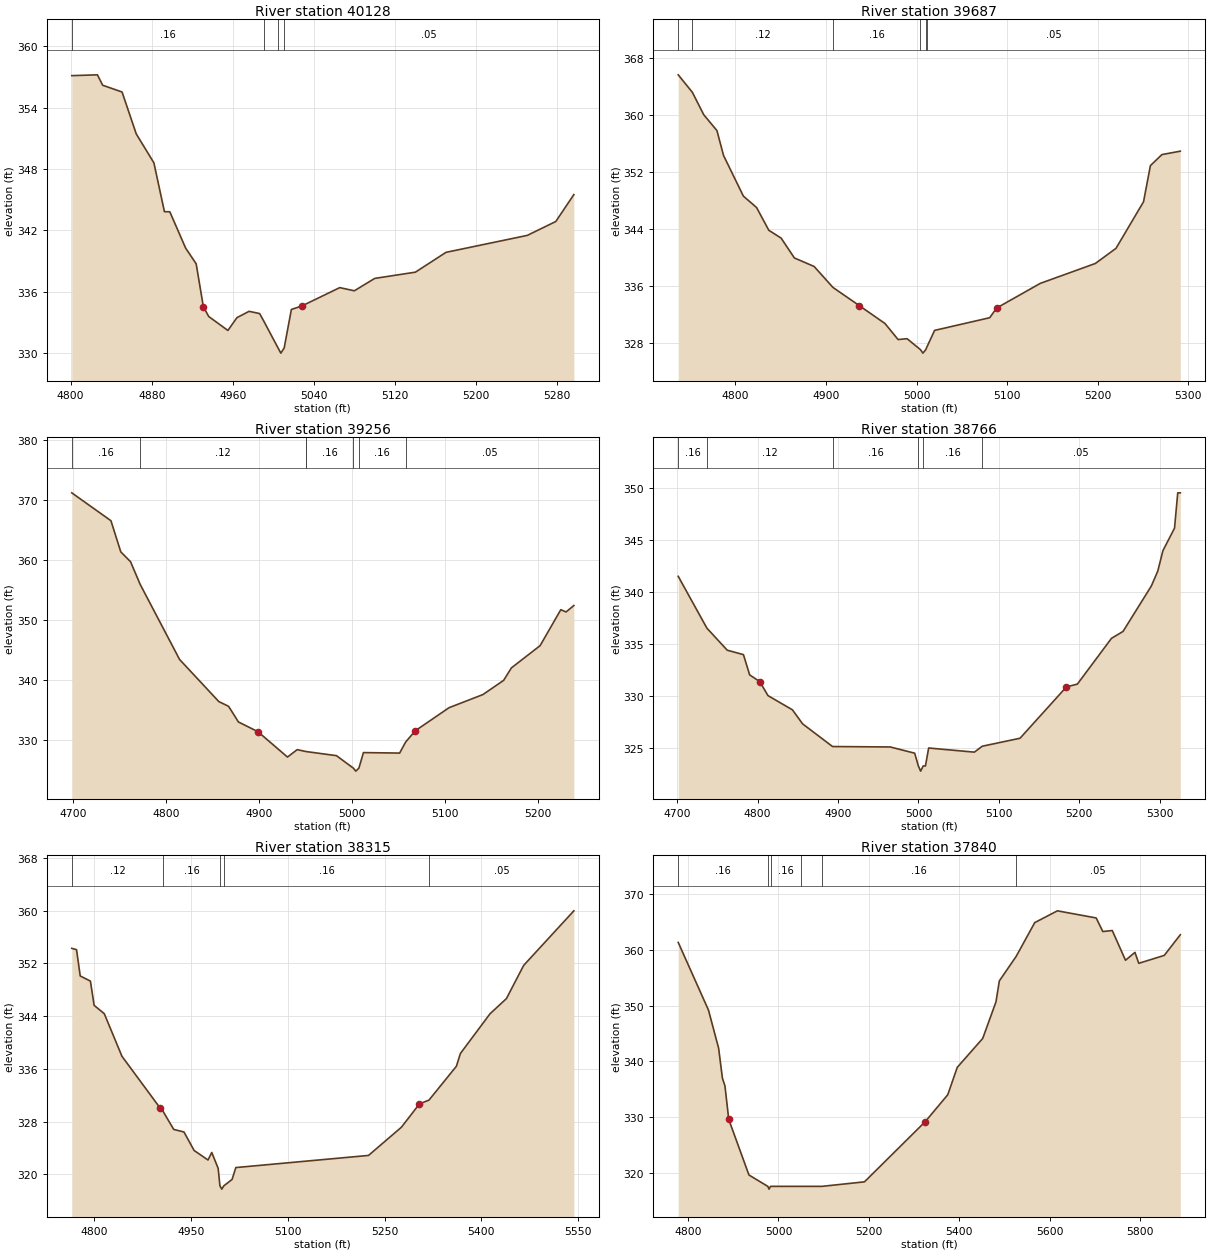
Type RM Length L Ch R = 1 ,40128   ,441,441,441
BEGIN DESCRIPTION:
EDWARDS CREEK 70.0
END DESCRIPTION:
XS GIS Cut Line= 3
      3649762.05     10615487.43        3650016.      10615563.4
       3650245.3     10615543.93
#Sta/Elev= 30
  4801.1  357.14  4826.4  357.22  4831.6   356.2  4850.7  355.54  4864.7  351.44
  4882.1  348.61  4892.5  343.83  4897.8  343.82  4913.4  340.27  4923.8  338.73
  4930.9  334.53  4936.2  333.57  4955.1  332.21    4964  333.46    4976  334.08
  4986.4  333.86  4990.5  333.12  5004.6  330.49  5007.3  329.99  5010.6  330.49
  5017.7  334.26  5028.2  334.61  5065.4   336.4  5079.8  336.09  5099.9   337.3
    5140  337.91  5170.2  339.85  5250.4  341.51  5278.5  342.87  5296.3   345.5
#Mann= 4 ,-1 , 0
  4801.1     .16       0  4990.5     .05       0  5004.6     .03       0
  5010.6     .05       0
Bank Sta=4930.9,5028.2
XS Rating Curve= 0 ,0
Exp/Cntr=0.3,0.1

Type RM Length L Ch R = 1 ,39687   ,431,431,431
BEGIN DESCRIPTION:
EDWARDS CREEK 69.0
END DESCRIPTION:
XS GIS Cut Line= 3
      3649499.58     10615710.17      3649699.61     10615860.19
      3649999.64     10615910.19
#Sta/Elev= 30
  4736.9  365.67  4752.5  363.21  4765.1  360.05  4779.6  357.83  4786.9  354.33
  4808.8  348.61  4823.4     347  4836.9   343.8  4850.5   342.7  4865.1  339.91
  4886.9  338.71  4907.7  335.76  4936.9  333.19  4965.1  330.69  4979.6  328.43
  4989.5  328.55  5004.2  327.02    5007  326.52  5010.2  327.02  5011.3  327.36
  5019.9  329.72  5080.7   331.5  5088.3  332.86  5136.5  336.33  5197.3  339.13
  5220.1  341.26  5250.5  347.81  5258.1   352.9  5270.8  354.45  5291.1  354.93
#Mann= 6 ,-1 , 0
  4736.9     .16       0  4752.5     .12       0  4907.7     .16       0
  5004.2     .07       0  5010.2     .16       0  5011.3     .05       0
Bank Sta=4936.9,5088.3
XS Rating Curve= 0 ,0
Exp/Cntr=0.3,0.1

Type RM Length L Ch R = 1 ,39256   ,490,490,490
BEGIN DESCRIPTION:
EDWARDS CREEK 68.0
END DESCRIPTION:
XS GIS Cut Line= 3
      3649349.62     10615810.22      3649449.61     10616110.19
      3649549.61     10616310.18
#Sta/Elev= 30
  4698.9  371.15    4741  366.52  4751.6  361.34  4762.1   359.7  4772.4  355.95
  4814.8  343.46    4857  336.46  4867.5  335.67  4878.1  333.07  4899.1  331.45
  4930.8  327.24  4941.3  328.47  4950.3  328.17  4950.5  328.16  4983.5  327.47
  5001.6   325.4  5004.3   324.9  5007.6   325.4  5012.5  327.98  5051.4   327.9
  5057.9  329.74  5068.2   331.6  5104.5  335.44  5140.9  337.62  5163.2  339.98
  5171.6  342.06  5202.4  345.75  5224.7  351.73  5230.3  351.35  5238.7  352.42
#Mann= 7 ,-1 , 0
  4698.9     .16       0  4772.4     .12       0  4950.3     .16       0
  4950.5     .16       0  5001.6     .07       0  5007.6     .16       0
  5057.9     .05       0
Bank Sta=4899.1,5068.2
XS Rating Curve= 0 ,0
Exp/Cntr=0.3,0.1

Type RM Length L Ch R = 1 ,38766   ,451,451,451
BEGIN DESCRIPTION:
EDWARDS CREEK 67.0
END DESCRIPTION:
XS GIS Cut Line= 3
      3649149.62     10616010.14      3649099.61     10616310.19
      3649299.58     10616560.16
#Sta/Elev= 30
  4701.3  341.52  4736.9  336.53  4762.2   334.4  4782.4  333.97  4790.1  332.02
  4802.7  331.37  4812.9  330.02  4843.3  328.65  4855.9   327.3  4893.2  325.11
  4964.9  325.07  4995.3  324.47  4999.9  323.24  5002.7  322.74  5005.9  323.24
  5008.7  323.24  5012.7  324.97  5069.5  324.57  5079.3  325.14  5126.3  325.91
    5184  330.86  5197.6  331.13    5240  335.54  5254.4  336.21  5289.6  340.59
  5297.6  342.03    5304     344  5318.4  346.16  5322.4  349.57  5325.6  349.57
#Mann= 6 ,-1 , 0
  4701.3     .16       0  4736.9     .12       0  4893.2     .16       0
  4999.9     .07       0  5005.9     .16       0  5079.3     .05       0
Bank Sta=4802.7,5184
XS Rating Curve= 0 ,0
Exp/Cntr=0.3,0.1

Type RM Length L Ch R = 1 ,38315   ,475,475,475
BEGIN DESCRIPTION:
EDWARDS CREEK 66.0
END DESCRIPTION:
XS GIS Cut Line= 3
      3648588.05     10616103.77      3648739.96     10616366.35
      3648828.93     10616832.89
#Sta/Elev= 30
    4765  354.29  4772.4  354.09  4778.1   350.1  4793.9  349.32  4799.7  345.64
  4815.4  344.38  4842.8  337.92  4901.6  330.12  4906.5  329.57  4923.1  326.82
  4938.9  326.44  4954.7  323.63  4976.2  322.19    4982  323.33  4991.9  320.93
  4994.7  318.27  4997.5  317.77  5000.7  318.27  5013.5  319.24  5019.3  321.04
    5225  322.88  5275.9  327.15    5304   330.7  5318.7  331.27  5361.2   336.4
  5367.5  338.35  5413.4  344.37  5438.8  346.67  5465.5   351.7  5543.3  359.98
#Mann= 5 ,-1 , 0
    4765     .12       0  4906.5     .16       0  4994.7     .07       0
  5000.7     .16       0  5318.7     .05       0
Bank Sta=4901.6,5304
XS Rating Curve= 0 ,0
Exp/Cntr=0.3,0.1

Type RM Length L Ch R = 1 ,37840   ,406,406,406
BEGIN DESCRIPTION:
EDWARDS CREEK 65.0
END DESCRIPTION:
XS GIS Cut Line= 3
      3648199.63     10616310.23      3648384.06     10616678.85
      3648795.45     10617243.98
#Sta/Elev= 30
  4778.1  361.35  4845.1  349.18  4867.5  342.34  4875.9  336.95  4881.5  335.57
  4889.9  329.55  4934.6  319.56  4976.3  317.52  4979.1  317.02  4982.3  317.52
  5050.2  317.52  5096.5  317.52  5190.3  318.33  5324.5  329.12  5374.7  333.99
  5395.6   338.9    5452   344.1  5481.3  350.66  5488.8  354.44  5526.1  358.85
  5567.1  364.91  5617.3  367.03  5703.1  365.75  5717.8  363.31  5738.7  363.49
    5768  358.15  5788.9  359.56  5797.4   357.6  5853.8  359.02  5889.3  362.73
#Mann= 6 ,-1 , 0
  4778.1     .16       0  4976.3     .07       0  4982.3     .16       0
  5050.2     .05       0  5096.5     .16       0  5526.1     .05       0
Bank Sta=4889.9,5324.5
XS Rating Curve= 0 ,0
Exp/Cntr=0.3,0.1

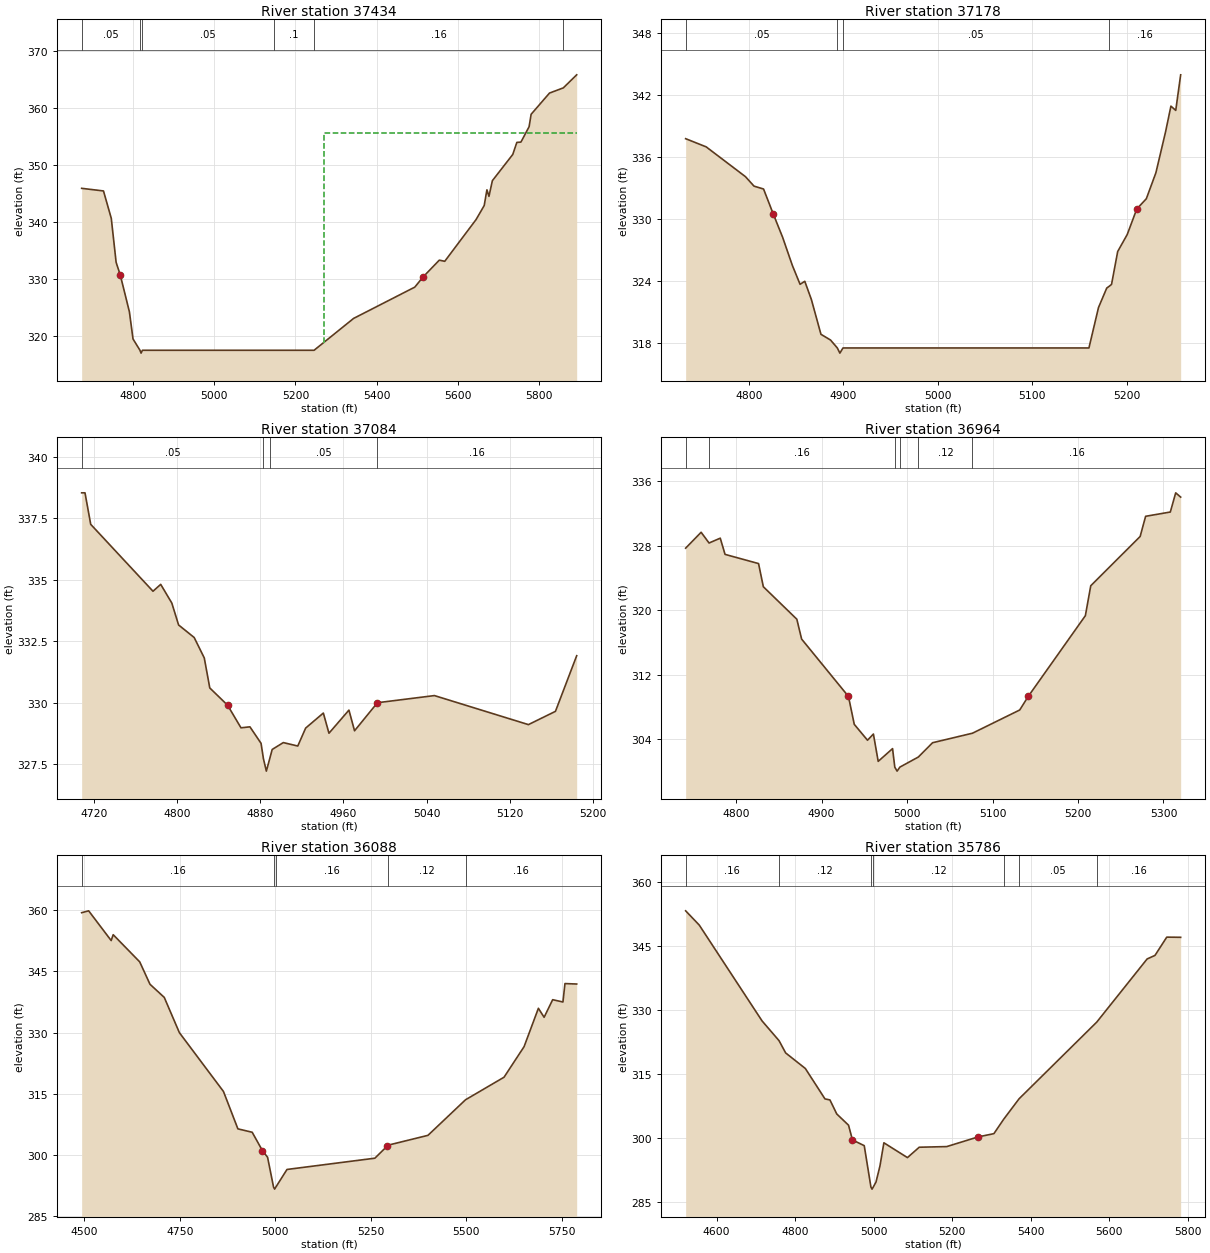
Type RM Length L Ch R = 1 ,37434   ,256,256,256
BEGIN DESCRIPTION:
EDWARDS CREEK 64.0
END DESCRIPTION:
XS GIS Cut Line= 3
      3647874.08     10616418.46       3647995.6     10616854.63
      3647924.15     10617616.81
#Sta/Elev= 30
  4673.8  345.93  4727.5  345.47  4746.7  340.66  4758.6  332.95    4769  330.67
  4791.3  324.27  4800.2   319.5  4817.3  317.52    4820  317.02  4823.3  317.52
  5147.6  317.52  5245.8  317.52  5343.1  323.11  5493.7   328.6  5513.8  330.36
    5554  333.33  5567.4  333.13  5644.4  340.44  5664.5  342.91  5671.2  345.67
  5676.2  344.52  5684.6  347.27  5734.8  351.87  5744.8  353.98  5754.9  354.04
    5775  356.74    5780  358.92  5825.2  362.64  5859.2  363.55  5892.1  365.84
#Mann= 6 ,-1 , 0
  4673.8     .05       0  4817.3    .035       0  4823.3     .05       0
  5147.6      .1       0  5245.8     .16       0  5859.2     .12       0
#XS Ineff= 2 , 0
                         5269.06          355.57
Permanent Ineff=
       F       F
Bank Sta=4769,5513.8
XS Rating Curve= 0 ,0
Exp/Cntr=0.3,0.1

Type RM Length L Ch R = 1 ,37178   ,94,94,94
BEGIN DESCRIPTION:
Mapping XS 6ca7ce5a
END DESCRIPTION:
XS GIS Cut Line= 2
      3647753.71     10616518.78      3647673.13     10617036.04
#Sta/Elev= 30
  4733.3  337.77    4755  336.98  4796.5   334.1  4805.6  333.18  4815.7   332.9
  4825.8  330.52  4835.9  328.22  4846.1  325.52  4854.3  323.68  4859.3  323.97
  4866.3   322.2  4876.4  318.84  4886.5  318.29  4893.7  317.52  4896.4  317.02
  4899.7  317.52  5159.8  317.52  5169.9  321.43  5178.6  323.31  5181.5  323.51
  5183.7  323.67  5190.2  326.85  5200.3   328.5  5210.4  330.97  5220.5  331.96
  5230.6  334.47  5240.8  338.42  5246.5  340.92  5251.6  340.51  5256.8  343.95
#Mann= 4 ,-1 , 0
  4733.3     .05       0  4893.7     .03       0  4899.7     .05       0
  5181.5     .16       0
Bank Sta=4825.8,5210.4
XS Rating Curve= 0 ,0
Exp/Cntr=0.3,0.1

Type RM Length L Ch R = 1 ,37084   ,120,120,120
BEGIN DESCRIPTION:
Mapping XS d073b884
END DESCRIPTION:
XS GIS Cut Line= 3
      3647718.55     10616499.24      3647622.21     10616749.21
      3647602.78     10616956.41
#Sta/Elev= 30
  4708.3  338.53  4711.5  338.53    4717  337.25  4776.9  334.53  4784.3  334.81
    4795  334.05  4801.5  333.16  4816.5  332.65  4826.2  331.82  4831.5   330.6
  4848.6   329.9  4861.5  328.98  4870.1  329.02  4880.8  328.35  4883.1  327.72
  4885.9  327.22  4889.1  327.72  4891.5   328.1  4902.2  328.38  4916.1  328.24
  4923.7  328.97  4940.7  329.58  4946.1  328.76  4965.3   329.7  4970.7  328.86
  4992.7     330  5047.5  330.29  5137.9  329.11  5163.9  329.65  5184.3  331.91
#Mann= 4 ,-1 , 0
  4708.3     .05       0  4883.1     .07       0  4889.1     .05       0
  4992.7     .16       0
Bank Sta=4848.6,4992.7
XS Rating Curve= 0 ,0
Exp/Cntr=0.3,0.1

Type RM Length L Ch R = 1 ,36964   ,876,876,876
BEGIN DESCRIPTION:
EDWARDS CREEK 63.0
END DESCRIPTION:
XS GIS Cut Line= 4
      3647643.05     10616479.66      3647514.14     10616738.79
      3647508.93     10616905.46      3647605.62     10616981.52
#Sta/Elev= 30
  4740.9  327.71    4759  329.68  4768.3  328.35  4781.4  328.95    4787  326.94
  4826.2   325.8  4831.8  322.93    4871   318.9  4876.6  316.44  4931.4  309.33
  4938.2  305.87  4953.7   303.9  4960.6  304.67  4966.2  301.28    4983  302.86
  4985.6  300.57  4988.3  300.07  4991.6  300.57  5013.2  301.82  5029.8  303.59
  5076.5  304.77  5131.8  307.65  5141.8  309.34  5208.6  319.34  5214.9  323.05
  5272.7  329.16  5279.1  331.66    5308  332.19  5314.3  334.57  5320.1  334.04
#Mann= 6 ,-1 , 0
  4740.9     .05       0  4768.3     .16       0  4985.6     .07       0
  4991.6     .16       0  5013.2     .12       0  5076.5     .16       0
Bank Sta=4931.4,5141.8
XS Rating Curve= 0 ,0
Exp/Cntr=0.3,0.1

Type RM Length L Ch R = 1 ,36088   ,302,302,302
BEGIN DESCRIPTION:
EDWARDS CREEK 62.0
END DESCRIPTION:
XS GIS Cut Line= 2
      3646385.82     10616610.05      3647620.85     10617005.54
#Sta/Elev= 30
  4492.9   359.4  4511.2  359.86  4570.2  352.58  4575.5  354.01    4645  347.35
  4671.9  341.86  4709.3  338.64  4748.9     330  4864.4  315.58  4902.2  306.42
  4939.6  305.59  4966.5  301.08  4979.9  299.47  4995.6  292.15  4998.4  291.65
  5001.6  292.15  5030.8  296.47    5261  299.23  5293.2  302.19  5296.3  302.44
  5400.1  304.83  5498.5  313.55  5599.4  319.08  5651.9  326.57  5689.4  335.97
  5704.4  333.77  5726.8  338.08  5753.7  337.51    5759  342.03  5789.7  341.92
#Mann= 5 ,-1 , 0
  4492.9     .16       0  4995.6     .07       0  5001.6     .16       0
  5296.3     .12       0  5498.5     .16       0
Bank Sta=4966.5,5293.2
XS Rating Curve= 0 ,0
Exp/Cntr=0.3,0.1

Type RM Length L Ch R = 1 ,35786   ,340,340,340
BEGIN DESCRIPTION:
EDWARDS CREEK 61.0
END DESCRIPTION:
XS GIS Cut Line= 2
      3646365.02     10617037.14      3647625.02     10617064.91
#Sta/Elev= 30
  4521.2   353.2  4555.8  349.87  4715.8  327.42    4759   322.8  4775.8  319.93
  4825.9  316.29  4875.9  309.17  4888.6  308.92  4905.9  305.64  4935.9  303.01
  4945.9  299.55  4975.9  298.22  4992.9  288.54  4995.7  288.04  4998.9  288.54
  5005.9  289.71  5015.9  293.46  5025.9  298.89  5085.9  295.42  5115.9  297.85
  5185.9     298    5266  300.27    5306  301.03  5330.9   304.4  5370.1  309.19
  5567.8  327.14  5696.1  341.93  5716.1  342.76  5746.1  347.04  5781.5     347
#Mann= 7 ,-1 , 0
  4521.2     .16       0    4759     .12       0  4992.9     .07       0
  4998.9     .12       0  5330.9     .16       0  5370.1     .05       0
  5567.8     .16       0
Bank Sta=4945.9,5266
XS Rating Curve= 0 ,0
Exp/Cntr=0.3,0.1

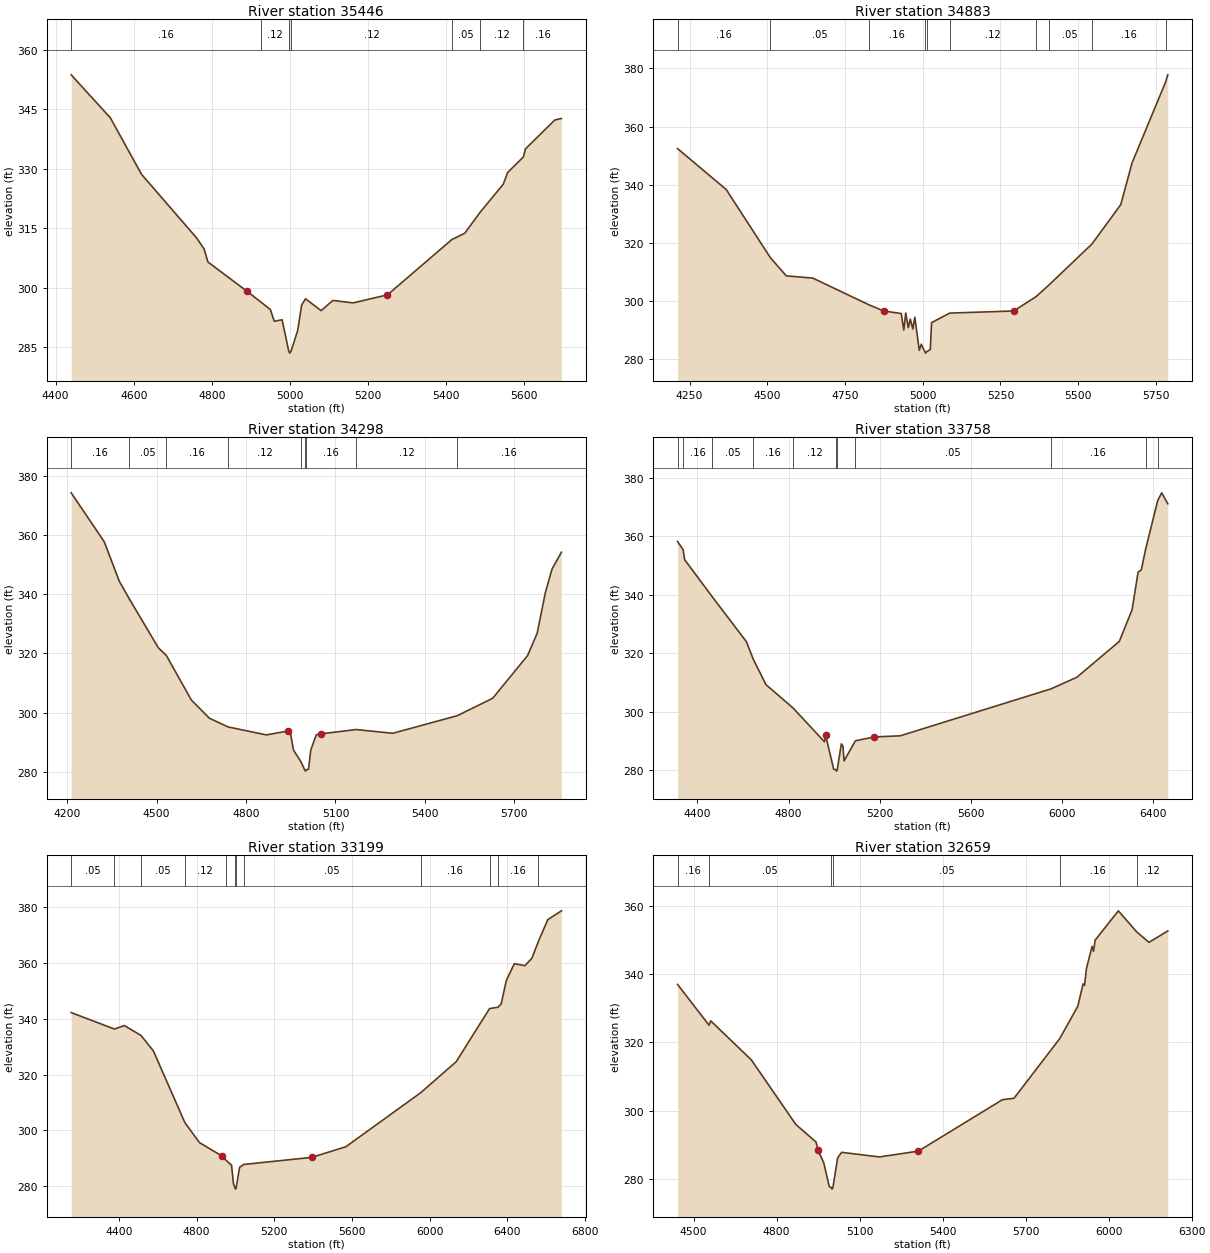
Type RM Length L Ch R = 1 ,35446   ,563,563,563
BEGIN DESCRIPTION:
EDWARDS CREEK 60.0
END DESCRIPTION:
XS GIS Cut Line= 3
       3646389.3     10617335.75       3647090.7     10617356.59
      3647594.75     10617125.28
#Sta/Elev= 30
  4439.8  353.74  4540.2  342.89  4620.2  328.61  4761.4  312.55  4780.3  309.79
  4790.3  306.49  4890.3  299.11  4926.6  296.34  4950.3  294.48  4960.3  291.53
  4980.4  291.91  4997.4  283.99  5000.1  283.49  5003.4  283.99  5020.4  289.27
  5030.4  295.63  5040.4  297.21  5080.4  294.21  5110.4  296.79  5162.3  296.17
  5250.3   298.2  5415.3  312.15  5448.4  313.76  5487.8  319.04  5547.2  326.14
  5558.4   329.1  5598.6     333  5604.2  335.07  5679.4  342.35  5696.1  342.72
#Mann= 7 ,-1 , 0
  4439.8     .16       0  4926.6     .12       0  4997.4     .07       0
  5003.4     .12       0  5415.3     .05       0  5487.8     .12       0
  5598.6     .16       0
Bank Sta=4890.3,5250.3
XS Rating Curve= 0 ,0
Exp/Cntr=0.3,0.1

Type RM Length L Ch R = 1 ,34883   ,585,585,585
BEGIN DESCRIPTION:
EDWARDS CREEK 59.0
END DESCRIPTION:
XS GIS Cut Line= 3
      3646399.62      10617410.2      3647049.61     10617910.19
      3647799.62     10617810.19
#Sta/Elev= 30
  4211.4  352.41  4368.1   338.3    4510  314.84  4561.2   308.6  4646.3  307.83
  4828.1  298.58  4874.7  296.51  4930.8  295.62    4939  289.97  4945.3  295.83
  4953.5  290.75  4959.9  293.73  4968.1   290.3  4974.4  294.37  4988.9  282.96
  4995.2  285.07  5006.7   282.5  5009.4     282  5012.7   282.5  5024.2   283.2
  5028.3   292.5  5086.9  295.78  5292.5  296.51  5364.7  301.46  5404.6  305.33
  5544.4  319.58  5636.8  333.11  5673.3   347.5    5781   375.3  5788.1   377.8
#Mann= 10 ,-1 , 0
  4211.4     .16       0    4510     .05       0  4828.1     .16       0
  5006.7     .07       0  5012.7     .16       0  5086.9     .12       0
  5364.7     .16       0  5404.6     .05       0  5544.4     .16       0
    5781     .12       0
Bank Sta=4874.7,5292.5
XS Rating Curve= 0 ,0
Exp/Cntr=0.3,0.1

Type RM Length L Ch R = 1 ,34298   ,540,540,540
BEGIN DESCRIPTION:
EDWARDS CREEK 58.0
END DESCRIPTION:
XS GIS Cut Line= 3
      3646099.66     10618260.19      3646899.61     10618360.19
      3647699.58      10618110.2
#Sta/Elev= 30
  4213.6  374.17  4324.4   357.7  4374.8   344.4  4407.2  338.65  4505.8  321.94
  4532.7  319.35  4616.7   304.3  4677.1  298.18  4739.9  295.23  4868.6  292.54
  4939.2  293.83  4949.2  293.05  4959.3  287.44  4983.8  283.56  4996.6  280.83
  4999.4  280.33  5002.6  280.83  5009.7  280.96  5017.3  287.47    5036  292.61
  5051.2  292.89  5169.1  294.35  5292.2  293.09  5508.8  299.03  5627.4   304.9
  5744.3  319.27  5776.7  326.84    5804  340.49  5826.5  348.49  5857.9  354.14
#Mann= 9 ,-1 , 0
  4213.6     .16       0  4407.2     .05       0  4532.7     .16       0
  4739.9     .12       0  4983.8     .16       0  4996.6     .07       0
  5002.6     .16       0  5169.1     .12       0  5508.8     .16       0
Bank Sta=4939.2,5051.2
XS Rating Curve= 0 ,0
Exp/Cntr=0.3,0.1

Type RM Length L Ch R = 1 ,33758   ,559,559,559
BEGIN DESCRIPTION:
EDWARDS CREEK 57.0
END DESCRIPTION:
XS GIS Cut Line= 3
       3646026.8     10618509.92      3646367.04     10618711.29
      3648065.48     10619154.96
#Sta/Elev= 30
  4312.7  358.17    4337  355.41  4343.8  351.97  4464.7   339.3  4614.9  323.89
  4644.1  318.03  4700.7   309.2  4818.8  301.27  4957.2  289.68  4962.4  291.85
  4997.7  280.27  5007.4  280.12  5010.2  279.62  5013.4  280.12  5031.1  288.95
  5038.2  288.23  5043.3  283.13    5093     290  5175.8  291.32  5289.5   291.7
  5951.3  307.77  6064.1  311.71  6250.7  323.99  6306.8  334.83  6333.4  347.76
  6347.3  348.43  6366.1  355.51  6419.2  372.18  6436.8  374.84  6463.5  371.11
#Mann= 11 ,-1 , 0
  4312.7     .12       0    4337     .16       0  4464.7     .05       0
  4644.1     .16       0  4818.8     .12       0  5007.4     .07       0
  5013.4     .12       0    5093     .05       0  5951.3     .16       0
  6366.1     .12       0  6419.2     .05       0
Bank Sta=4962.4,5175.8
XS Rating Curve= 0 ,0
Exp/Cntr=0.3,0.1

Type RM Length L Ch R = 1 ,33199   ,540,540,540
BEGIN DESCRIPTION:
EDWARDS CREEK 56.0
END DESCRIPTION:
XS GIS Cut Line= 2
      3645769.84     10619107.12       3648214.3     10619732.13
#Sta/Elev= 30
  4154.9   342.2  4377.6   336.3  4428.9  337.56  4514.3     334  4577.9   328.5
    4740  302.83  4815.3  295.65  4928.8  290.95  4949.7  289.49  4980.4  287.56
  4990.2   280.9    4998  279.51  5000.8  279.01    5004  279.51  5021.7  286.82
  5043.3  287.84  5393.3  290.38  5568.7  294.18  5953.8  313.51  6136.4  324.61
  6308.1  343.61  6351.9  344.12    6368   345.3  6394.5  353.69  6435.8  359.68
  6490.5  358.99  6526.2  361.66  6559.8   367.7  6607.8  375.44    6678  378.61
#Mann= 12 ,-1 , 0
  4154.9     .05       0  4377.6     .16       0  4514.3     .05       0
    4740     .12       0  4949.7     .16       0    4998     .07       0
    5004     .16       0  5043.3     .05       0  5953.8     .16       0
  6308.1     .12       0  6351.9     .16       0  6559.8     .05       0
Bank Sta=4928.8,5393.3
XS Rating Curve= 0 ,0
Exp/Cntr=0.3,0.1

Type RM Length L Ch R = 1 ,32659   ,544,544,544
BEGIN DESCRIPTION:
EDWARDS CREEK 55.0
END DESCRIPTION:
XS GIS Cut Line= 3
      3646004.16     10619792.64      3647115.28      10619910.7
      3647740.26     10620105.14
#Sta/Elev= 30
  4441.8  337.01  4555.6  325.05  4561.7  326.33  4708.7  314.86  4869.6  295.92
  4942.1  290.82  4950.1  288.31  4970.2  284.71  4990.3  277.67  4997.4  277.48
  5000.1  276.98  5003.4  277.48  5020.5  286.16  5034.7  287.77  5171.3  286.42
  5312.1  288.12  5616.1  303.21    5658  303.63  5823.1  321.11  5888.4  330.59
  5907.5  337.17  5912.7  336.72  5919.8  341.68    5940  348.17  5945.3  346.73
  5951.2  349.99    6035  358.59  6101.1  352.43  6145.7  349.35  6213.7  352.69
#Mann= 6 ,-1 , 0
  4441.8     .16       0  4555.6     .05       0  4997.4     .03       0
  5003.4     .05       0  5823.1     .16       0  6101.1     .12       0
Bank Sta=4950.1,5312.1
XS Rating Curve= 0 ,0
Exp/Cntr=0.3,0.1

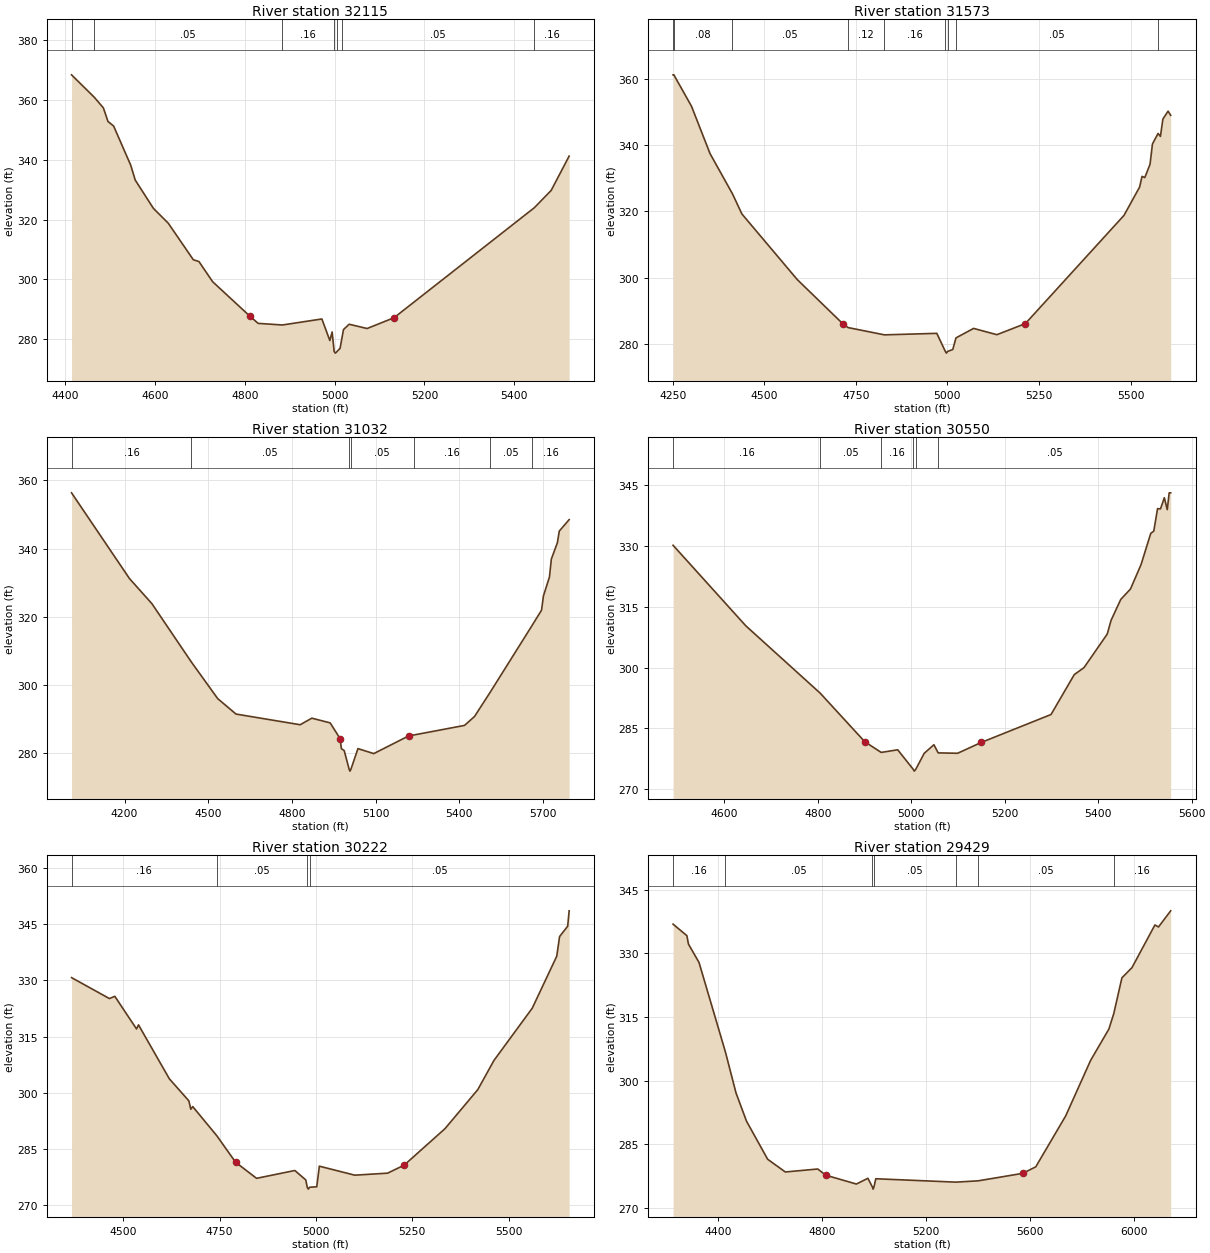
Type RM Length L Ch R = 1 ,32115   ,542,542,542
BEGIN DESCRIPTION:
EDWARDS CREEK 54.0
END DESCRIPTION:
XS GIS Cut Line= 3
      3646049.63     10620260.19      3646649.61     10620360.19
      3647149.65     10620360.19
#Sta/Elev= 30
  4414.1  368.39  4464.4  360.94    4485  357.35  4495.2  352.81  4507.9  351.25
  4545.9  338.19    4556  333.19  4596.6  323.71  4629.5  318.79  4685.3  306.57
  4697.9  305.95  4728.4  299.21    4812   287.6  4829.7  285.29  4883.7  284.75
  4971.7  286.76  4989.4  279.55  4994.5  282.42  4999.1  275.84  5001.8  275.34
  5005.1  275.84  5012.2  276.95  5015.6  279.76  5019.8  283.22  5032.4     285
  5072.4  283.57  5132.4  287.18  5444.9  323.96  5482.4  329.75  5522.4  341.22
#Mann= 7 ,-1 , 0
  4414.1     .16       0  4464.4     .05       0  4883.7     .16       0
  4999.1     .07       0  5005.1     .16       0  5015.6     .05       0
  5444.9     .16       0
Bank Sta=4812,5132.4
XS Rating Curve= 0 ,0
Exp/Cntr=0.3,0.1

Type RM Length L Ch R = 1 ,31573   ,541,541,541
BEGIN DESCRIPTION:
EDWARDS CREEK 53.0
END DESCRIPTION:
XS GIS Cut Line= 3
      3645999.62     10620760.19      3646749.61     10620860.19
      3647149.61     10620410.19
#Sta/Elev= 30
  4250.9  361.24    4253  361.24  4301.3  351.72  4351.8  337.44  4412.9  325.32
  4438.8   319.2  4590.1  299.36    4715  285.95  4728.8  284.87  4828.1  282.67
    4971  283.13  4994.4  277.65  4997.2  277.15  5000.4  277.65  5014.6  278.24
  5023.3  281.75  5071.5  284.62    5135  282.72  5212.8  286.07  5482.1  318.77
  5524.7  327.32  5531.4  330.56  5538.9   330.2  5553.2   334.2  5559.8  340.34
  5575.2  343.54  5581.6  342.63  5588.3  347.86  5602.5  350.27  5609.6     349
#Mann= 9 ,-1 , 0
  4250.9     .05       0    4253     .08       0  4412.9     .05       0
  4728.8     .12       0  4828.1     .16       0  4994.4     .07       0
  5000.4     .16       0  5023.3     .05       0  5575.2     .16       0
Bank Sta=4715,5212.8
XS Rating Curve= 0 ,0
Exp/Cntr=0.3,0.1

Type RM Length L Ch R = 1 ,31032   ,482,482,482
BEGIN DESCRIPTION:
EDWARDS CREEK 52.0
END DESCRIPTION:
XS GIS Cut Line= 3
      3646099.57     10621910.22      3646899.61     10621360.19
       3647449.6      10620760.2
#Sta/Elev= 30
  4009.7  356.34  4217.4  331.24    4298  323.87  4439.5  306.79    4534  296.06
  4599.7  291.54  4829.7  288.42  4871.6  290.34  4937.3  288.96  4973.1  284.33
  4977.5  281.42  4987.7  280.84  5005.6  275.33  5008.4  274.83  5011.6  275.33
    5037  281.43  5093.7  279.96  5221.4  285.25    5237  285.41  5419.3  288.22
  5455.1  290.83  5511.6  297.97  5660.4  317.34  5695.5  321.97  5702.3  326.15
  5723.9   331.7  5730.7  336.95  5752.3  341.72  5759.1  345.13  5794.5  348.49
#Mann= 7 ,-1 , 0
  4009.7     .16       0  4439.5     .05       0  5005.6     .03       0
  5011.6     .05       0    5237     .16       0  5511.6     .05       0
  5660.4     .16       0
Bank Sta=4973.1,5221.4
XS Rating Curve= 0 ,0
Exp/Cntr=0.3,0.1

Type RM Length L Ch R = 1 ,30550   ,328,328,328
BEGIN DESCRIPTION:
EDWARDS CREEK 51.0
END DESCRIPTION:
XS GIS Cut Line= 3
      3646799.61     10622110.19      3647149.61     10621760.19
      3647599.64     10621410.16
#Sta/Elev= 30
    4490  330.21  4645.6  310.32  4805.1  293.65  4900.1   281.7  4935.4  279.03
  4970.8  279.68  5003.7  274.91  5006.4  274.41  5009.7  274.91  5027.5  278.81
  5048.3  280.93  5057.4  278.92    5099  278.82  5149.7   281.5    5299   288.4
  5348.7  298.25  5369.6  299.99  5419.3  308.28  5427.5  311.67  5448.3  316.84
  5469.1  319.42  5491.7  325.45  5512.5  333.17  5518.9  333.69    5527  339.26
  5533.3   339.2  5541.5  341.96  5547.8  339.01  5551.9  343.17  5555.1  343.17
#Mann= 6 ,-1 , 0
    4490     .16       0  4805.1     .05       0  4935.4     .16       0
  5003.7     .07       0  5009.7     .16       0  5057.4     .05       0
Bank Sta=4900.1,5149.7
XS Rating Curve= 0 ,0
Exp/Cntr=0.3,0.1

Type RM Length L Ch R = 1 ,30222   ,793,793,793
BEGIN DESCRIPTION:
EDWARDS CREEK 50.0
END DESCRIPTION:
XS GIS Cut Line= 3
      3646728.41     10622239.36      3647179.83     10622174.25
      3647739.01     10621554.39
#Sta/Elev= 30
    4366  330.74  4464.2  325.16  4478.3  325.75  4534.6  317.05  4539.7  318.14
  4619.8  303.75  4670.3  297.89  4675.4  295.64  4680.4  296.35  4743.1  288.55
  4791.6  281.51    4846  277.22  4945.3  279.31  4973.7  276.79  4977.5  274.84
  4980.2  274.34  4983.5  274.84  5002.1  274.96  5008.9  280.46  5100.8  278.06
    5186   278.6  5228.6  280.71  5334.7  290.45  5419.9  300.87  5461.8  308.65
  5561.2  322.59  5624.7  336.43  5632.1  341.68  5653.1  344.46  5656.9  348.55
#Mann= 4 ,-1 , 0
    4366     .16       0  4743.1     .05       0  4977.5     .03       0
  4983.5     .05       0
Bank Sta=4791.6,5228.6
XS Rating Curve= 0 ,0
Exp/Cntr=0.3,0.1

Type RM Length L Ch R = 1 ,29429   ,529,529,529
BEGIN DESCRIPTION:
EDWARDS CREEK 49.0
END DESCRIPTION:
XS GIS Cut Line= 3
      3646611.27     10622625.64      3647613.86     10622812.27
      3648506.31      10622708.3
#Sta/Elev= 30
    4225  336.91  4278.2   334.2  4284.3  332.21    4325  327.87  4426.8  306.74
  4467.4  297.11  4508.1  290.41  4589.5  281.43  4657.6  278.42  4782.8  279.12
  4813.3  277.67  4931.6  275.57    4976  276.93  4993.4  274.87  4996.1  274.37
  4999.4  274.87  5006.5  276.82    5315  276.02  5401.3  276.33  5572.8  278.09
  5623.1  279.63  5738.5  291.65  5834.5  304.74    5905  312.15  5923.7  315.75
  5955.3  324.25    5994  326.64  6082.5  336.72  6096.3  336.25  6143.3  340.06
#Mann= 7 ,-1 , 0
    4225     .16       0  4426.8     .05       0  4993.4     .03       0
  4999.4     .05       0    5315     .08       0  5401.3     .05       0
  5923.7     .16       0
Bank Sta=4813.3,5572.8
XS Rating Curve= 0 ,0
Exp/Cntr=0.3,0.1

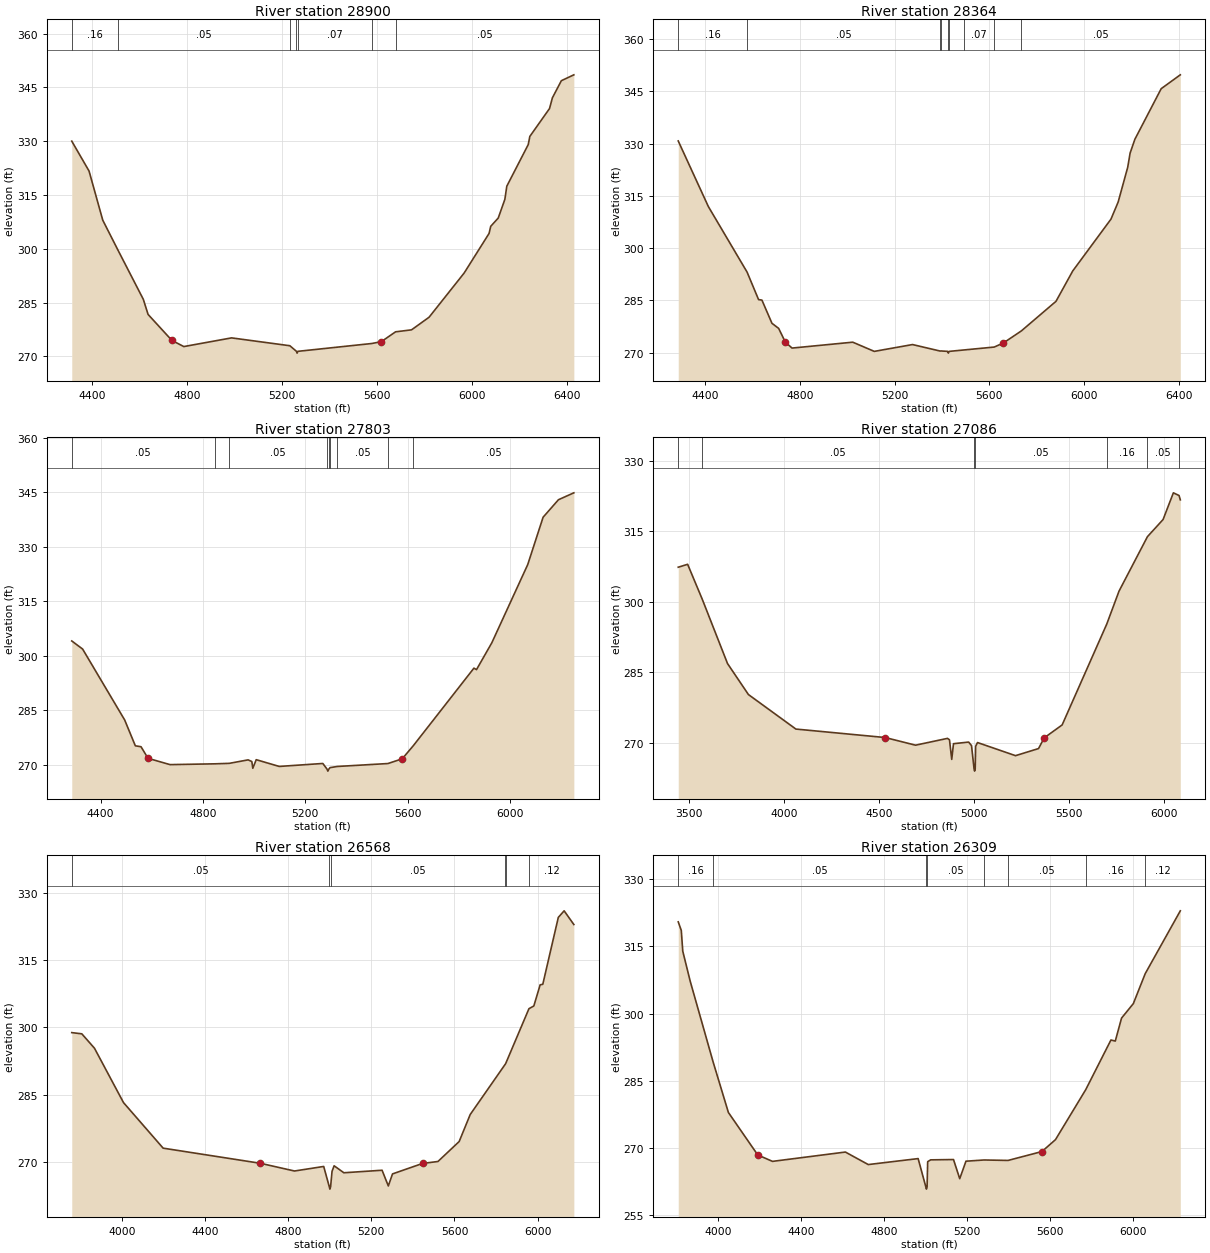
Type RM Length L Ch R = 1 ,28900   ,536,536,536
BEGIN DESCRIPTION:
EDWARDS CREEK 48.0
END DESCRIPTION:
XS GIS Cut Line= 3
      3646549.61     10623210.19      3647249.61     10623260.19
      3648499.63      10623910.2
#Sta/Elev= 30
  4316.1  330.04  4388.8   321.7  4446.4     308  4511.5   299.5  4616.9  285.93
  4636.9  281.72  4737.2  274.46  4787.3  272.76  4987.8  275.18  5232.9  272.99
  5260.7  271.43  5263.4  270.93  5266.7  271.43    5577  273.61  5617.4  274.13
  5677.4  276.87  5744.4  277.42  5818.1  280.93  5965.5  293.25  6070.4   304.3
  6077.4  306.29    6109   308.6  6136.8  313.81    6145  317.48  6235.2  329.09
  6241.7  331.35  6324.5  339.12  6336.6  342.11  6374.3  346.89  6426.8  348.53
#Mann= 7 ,-1 , 0
  4316.1     .16       0  4511.5     .05       0  5232.9     .07       0
  5260.7     .03       0  5266.7     .07       0    5577     .12       0
  5677.4     .05       0
Bank Sta=4737.2,5617.4
XS Rating Curve= 0 ,0
Exp/Cntr=0.3,0.1

Type RM Length L Ch R = 1 ,28364   ,561,561,561
BEGIN DESCRIPTION:
EDWARDS CREEK 47.0
END DESCRIPTION:
XS GIS Cut Line= 3
      3646549.61     10623260.19      3647049.61     10623760.19
      3648449.59     10623960.19
#Sta/Elev= 30
  4285.2  330.73  4412.5   311.9  4576.2  293.08  4624.6   285.2  4638.8  285.06
  4681.2   278.4  4709.5  276.94  4737.7  273.01    4766  271.29  5022.6  272.98
  5113.5  270.34  5275.1   272.3  5391.6  270.44  5396.3  270.46  5423.7  270.34
  5426.4  269.84  5429.7  270.34    5491  270.74  5620.2  271.58    5659  272.75
    5735  276.22  5881.2   284.7  5951.9  293.41  6113.6   308.3  6143.9   313.2
  6184.3  323.18  6194.4  327.25  6214.6  331.22  6325.7  345.73  6406.5  349.71
#Mann= 9 ,-1 , 0
  4285.2     .16       0  4576.2     .05       0  5391.6     .07       0
  5396.3     .05       0  5423.7     .03       0  5429.7     .05       0
    5491     .07       0  5620.2     .12       0    5735     .05       0
Bank Sta=4737.7,5659
XS Rating Curve= 0 ,0
Exp/Cntr=0.3,0.1

Type RM Length L Ch R = 1 ,27803   ,717,717,717
BEGIN DESCRIPTION:
EDWARDS CREEK 46.0
END DESCRIPTION:
XS GIS Cut Line= 3
      3646449.59     10623860.17      3646999.61     10624310.19
      3648249.65     10624360.19
#Sta/Elev= 30
  4287.7  304.08  4330.1  301.85  4494.5  282.31  4536.1   275.2  4558.3  274.95
  4585.6  271.76  4671.8  270.02  4846.4  270.24  4902.9  270.37  4976.8  271.33
  4991.2  270.87  4995.1  269.02  5008.4  271.38  5098.4  269.52  5268.6  270.34
  5285.6  268.73  5288.3  268.23  5291.6  268.73  5296.6  269.19  5325.3  269.51
    5523  270.32  5578.8  271.62  5621.8   275.2    5859  296.59  5869.1  296.19
  5929.1   303.6  6069.2  325.11  6129.3  338.16  6189.3  342.98  6249.4  344.88
#Mann= 9 ,-1 , 0
  4287.7     .05       0  4846.4     .07       0  4902.9     .05       0
  5285.6     .03       0  5291.6     .05       0  5296.6     .07       0
  5325.3     .05       0    5523     .12       0  5621.8     .05       0
Bank Sta=4585.6,5578.8
XS Rating Curve= 0 ,0
Exp/Cntr=0.3,0.1

Type RM Length L Ch R = 1 ,27086   ,518,518,518
BEGIN DESCRIPTION:
EDWARDS CREEK 45.0
END DESCRIPTION:
XS GIS Cut Line= 4
      3645680.08     10625082.53      3646940.47     10625051.28
      3647419.63     10624889.82      3648289.41     10624770.03
#Sta/Elev= 30
  3443.8  307.33  3493.3  307.95  3570.2  300.53  3703.4  286.83  3813.4  280.24
  4063.5  272.89  4533.7  271.09  4693.7  269.46    4862  270.91  4872.5   270.6
  4884.3  266.44  4893.6  269.78  4973.5  270.12  4988.6  269.36  5001.9  264.44
  5004.7  263.94  5007.9  264.44  5010.2  269.23  5020.2  270.02  5220.3  267.23
  5341.4  268.74  5371.7  271.03  5465.8  273.77  5700.7  295.22  5765.4  302.24
  5915.1  313.83  5997.5  317.48  6051.7  323.16  6081.5  322.59  6088.2  321.67
#Mann= 7 ,-1 , 0
  3443.8     .16       0  3570.2     .05       0  5001.9     .03       0
  5007.9     .05       0  5700.7     .16       0  5915.1     .05       0
  6081.5     .16       0
Bank Sta=4533.7,5371.7
XS Rating Curve= 0 ,0
Exp/Cntr=0.3,0.1

Type RM Length L Ch R = 1 ,26568   ,259,259,259
BEGIN DESCRIPTION:
Mapping XS 000ef761
END DESCRIPTION:
XS GIS Cut Line= 3
      3645851.42     10625327.37      3647427.78     10625445.42
      3648150.02      10625862.1
#Sta/Elev= 30
  3759.5  298.85  3807.8  298.58  3868.6  295.37  4008.4   283.2  4198.9  273.02
  4666.4  269.64  4830.7  267.91  4971.1  268.93  4998.2  264.36  5000.9  263.86
  5004.2  264.36  5011.2  267.83  5021.2  269.08  5067.9  267.52  5251.9  268.08
  5281.9  264.57    5302  267.26  5446.3   269.6  5520.6  270.04  5622.6   274.5
  5675.7  280.54  5844.6  291.81  5846.5  291.95  5958.2   304.2  5981.7  304.81
    6012  309.53  6024.8  309.66  6099.4  324.61  6127.4  326.08  6174.1  323.02
#Mann= 6 ,-1 , 0
  3759.5     .05       0  4998.2     .03       0  5004.2     .05       0
  5844.6     .08       0  5846.5     .07       0  5958.2     .12       0
Bank Sta=4666.4,5446.3
XS Rating Curve= 0 ,0
Exp/Cntr=0.3,0.1

Type RM Length L Ch R = 1 ,26309   ,429,429,429
BEGIN DESCRIPTION:
EDWARDS CREEK 44.0
END DESCRIPTION:
XS GIS Cut Line= 4
       3646148.8     10626150.23      3646685.26     10625655.44
      3647440.47     10625671.07      3648211.33     10626191.92
#Sta/Elev= 30
  3809.8  320.48  3824.5  318.57  3831.6  313.94  3866.8  307.34  3977.3  289.28
  4051.1  277.96  4192.3  268.49  4263.2  267.05    4614  269.13    4724  266.34
    4964  267.67    5001  261.36  5003.8  260.86    5007  261.36  5009.9  266.98
  5024.1  267.39  5134.1  267.46  5164.1  263.19  5194.1  267.09  5281.2  267.36
  5396.5  267.26  5559.4  269.24  5624.8   271.9  5770.1  283.03  5891.5  294.12
  5912.5  293.89  5942.5     299  5999.4  302.25  6056.4  308.92  6225.3  322.94
#Mann= 8 ,-1 , 0
  3809.8     .16       0  3977.3     .05       0    5001     .03       0
    5007     .05       0  5281.2     .12       0  5396.5     .05       0
  5770.1     .16       0  6056.4     .12       0
Bank Sta=4192.3,5559.4
XS Rating Curve= 0 ,0
Exp/Cntr=0.3,0.1