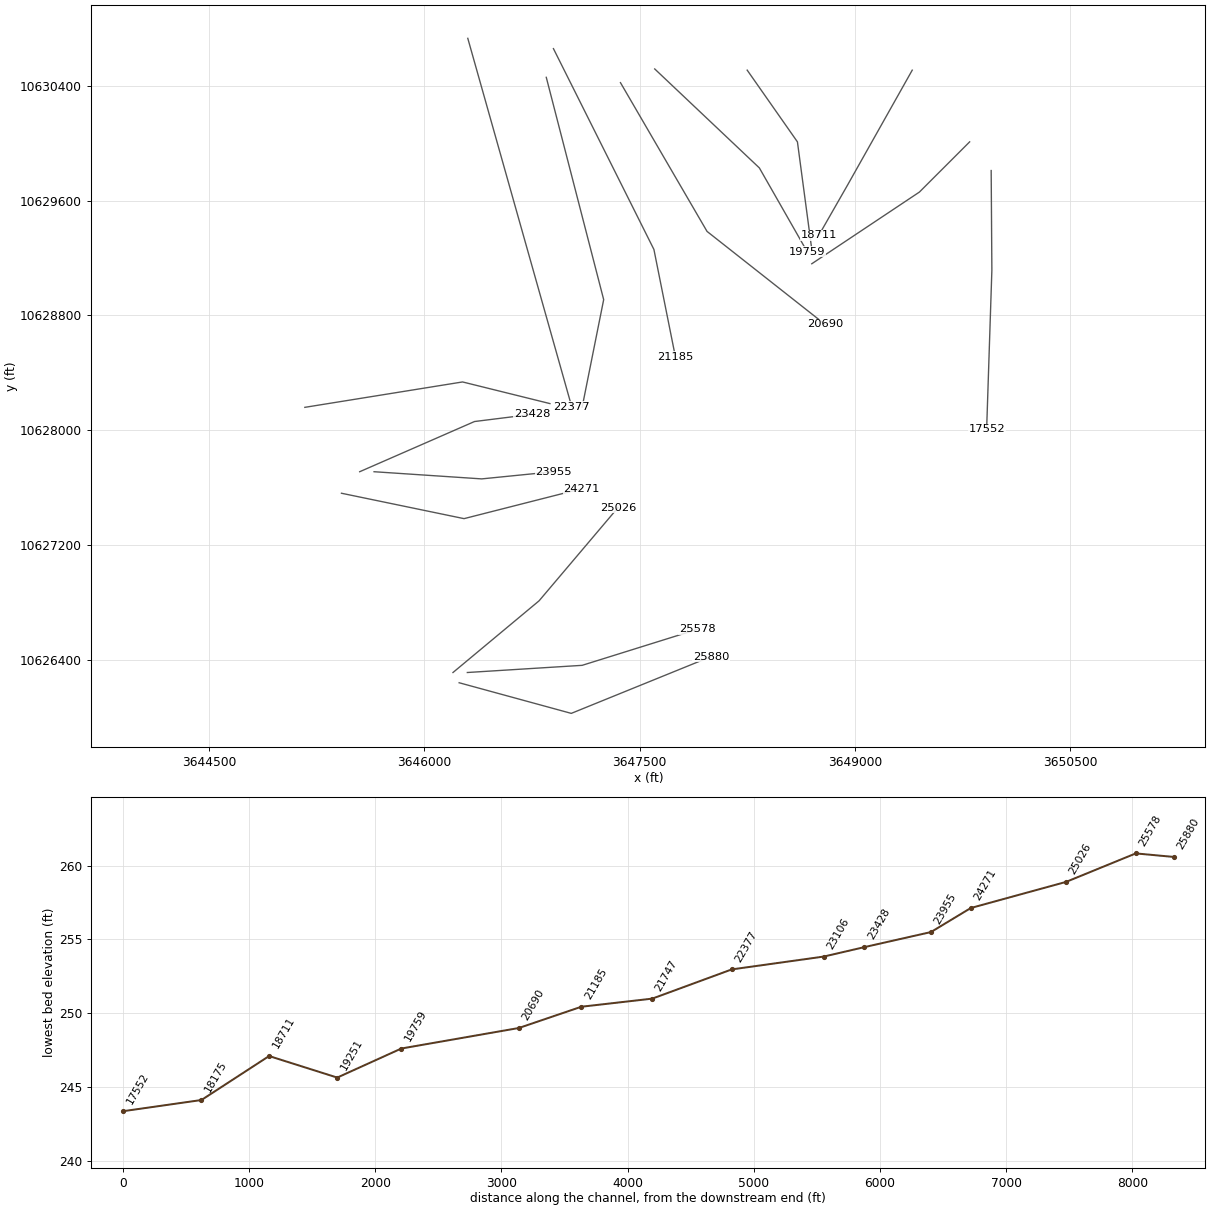
HEC-RAS study EDWARDS CREEK.prj: EDWARDS CREEK Base Level Engineering

--- EDWARDS CREEK.g01 (geometry) --- (continued)

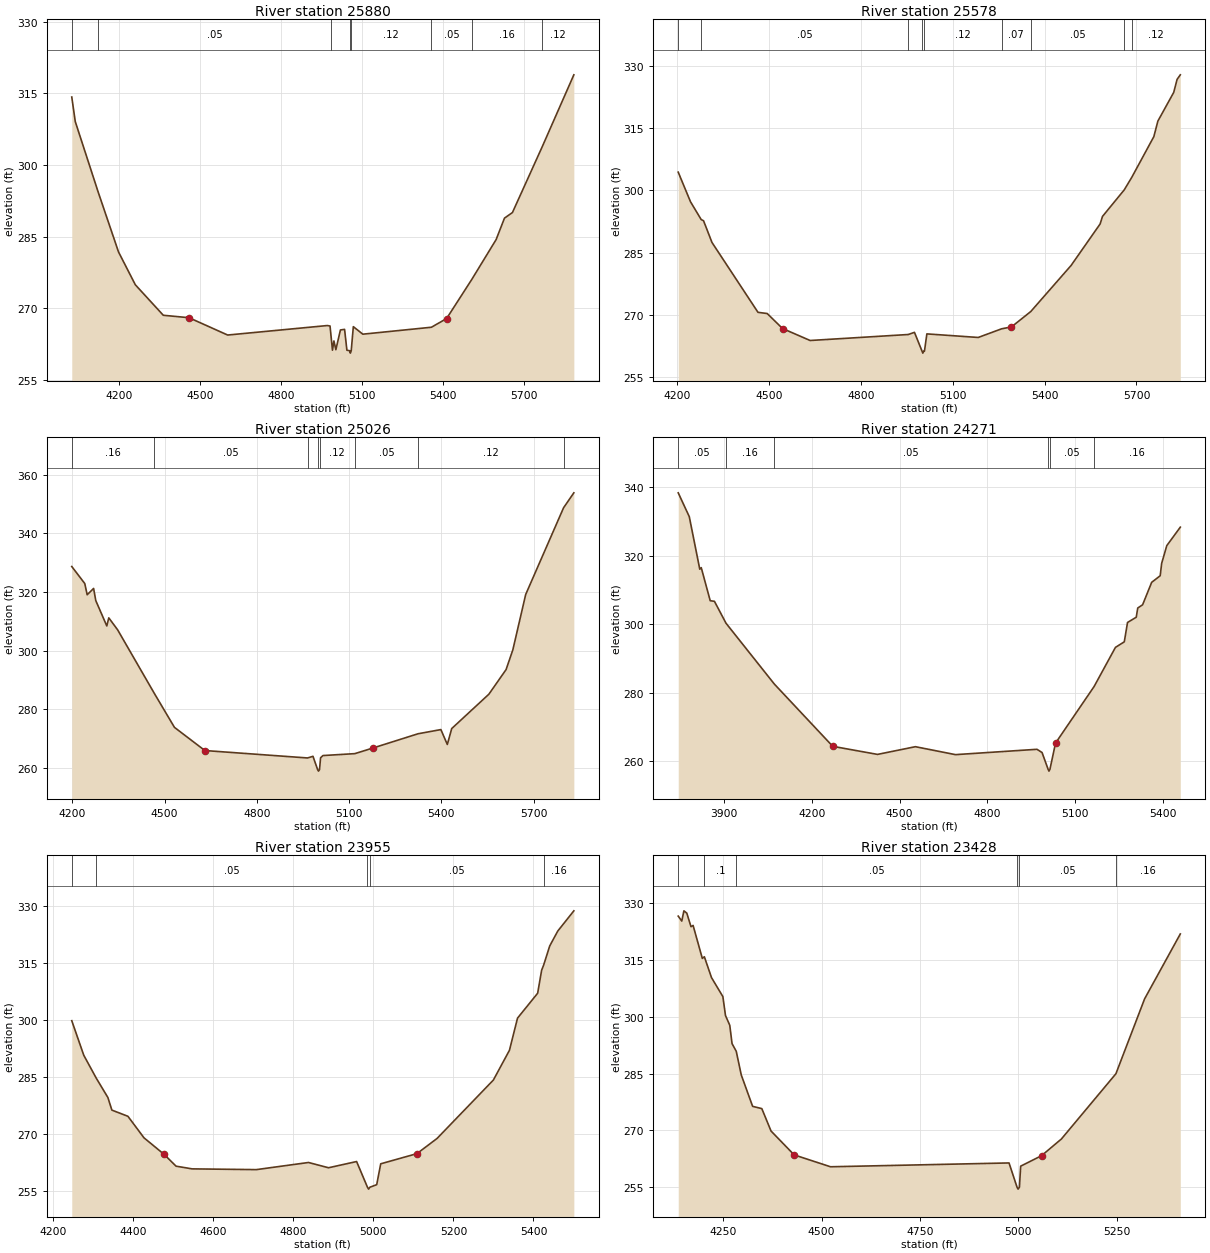
Type RM Length L Ch R = 1 ,25880   ,302,302,302
BEGIN DESCRIPTION:
EDWARDS CREEK 43.0
END DESCRIPTION:
XS GIS Cut Line= 3
      3646242.58     10626238.77       3647023.8     10626025.23
      3647996.18     10626420.43
#Sta/Elev= 30
  4026.2  314.24  4039.2  309.09  4123.9  294.35  4199.4  281.78  4261.6  274.91
  4365.2  268.52  4460.3  268.01  4603.6  264.38    4973  266.37  4982.7  266.27
  4987.5  263.57  4991.7  261.21  4997.1  263.15  5004.3  261.31  5021.2  265.44
  5036.6  265.57  5045.2   261.2  5055.2  261.09    5058  260.59  5061.2  261.09
    5069  266.13  5104.2  264.56  5358.1  266.01  5414.4  267.83  5507.3  275.99
  5597.9  284.38  5628.8  288.87  5658.3  290.04  5769.1  303.89  5885.7  318.89
#Mann= 8 ,-1 , 0
  4026.2     .16       0  4123.9     .05       0  4987.5     .12       0
  5055.2     .07       0  5061.2     .12       0  5358.1     .05       0
  5507.3     .16       0  5769.1     .12       0
Bank Sta=4460.3,5414.4
XS Rating Curve= 0 ,0
Exp/Cntr=0.3,0.1

Type RM Length L Ch R = 1 ,25578   ,552,552,552
BEGIN DESCRIPTION:
EDWARDS CREEK 42.0
END DESCRIPTION:
XS GIS Cut Line= 3
      3646299.61     10626310.19      3647099.61     10626360.19
       3647899.6     10626610.19
#Sta/Elev= 30
  4203.5  304.39  4243.6  297.26  4278.4  292.99  4286.2  292.69  4313.7  287.47
    4464  270.65  4494.1  270.36  4544.2  266.75  4634.3  263.87  4954.6  265.31
    4975  265.83  4999.6  261.33  5002.3  260.83  5005.6  261.33  5007.7  261.33
  5015.5  265.46  5183.2   264.6  5259.9  266.69  5291.6  267.13  5354.8  270.84
  5486.5  281.93  5581.3  291.92  5589.1  293.74    5660  300.12  5685.4  303.24
  5756.8  312.95  5769.9  316.68  5821.7  323.59  5832.7  326.73  5843.2  327.82
#Mann= 9 ,-1 , 0
  4203.5     .16       0  4278.4     .05       0  4954.6     .12       0
  4999.6     .07       0  5005.6     .12       0  5259.9     .07       0
  5354.8     .05       0    5660     .16       0  5685.4     .12       0
Bank Sta=4544.2,5291.6
XS Rating Curve= 0 ,0
Exp/Cntr=0.3,0.1

Type RM Length L Ch R = 1 ,25026   ,755,755,755
BEGIN DESCRIPTION:
EDWARDS CREEK 41.0
END DESCRIPTION:
XS GIS Cut Line= 3
       3646199.6     10626310.18      3646799.61     10626810.19
       3647349.6     10627460.18
#Sta/Elev= 30
  4198.4  328.66  4240.7  322.85  4248.5  319.03  4269.4  321.18  4276.5  317.04
  4312.3   308.4  4318.8  311.15  4347.5  307.08  4466.7  285.43  4532.3  273.82
  4631.2  265.92  4964.9  263.39  4982.7  263.95  4997.9   259.4  5000.6   258.9
  5003.9   259.4  5007.4  263.45  5015.2  264.21  5118.7  264.86  5177.7  266.78
  5324.4  271.64  5398.6  273.06  5419.5  267.99  5433.8  273.41  5554.6  285.12
  5610.6  293.52  5632.6  300.26  5674.3  319.11  5797.6  348.71  5830.9  353.78
#Mann= 8 ,-1 , 0
  4198.4     .16       0  4466.7     .05       0  4964.9     .12       0
  4997.9     .07       0  5003.9     .12       0  5118.7     .05       0
  5324.4     .12       0  5797.6     .16       0
Bank Sta=4631.2,5177.7
XS Rating Curve= 0 ,0
Exp/Cntr=0.3,0.1

Type RM Length L Ch R = 1 ,24271   ,316,316,316
BEGIN DESCRIPTION:
EDWARDS CREEK 40.0
END DESCRIPTION:
XS GIS Cut Line= 3
      3645422.55     10627560.13      3646276.73     10627383.05
      3647094.46     10627591.39
#Sta/Elev= 30
  3743.2  338.34    3781  331.38  3816.8  316.06  3821.9   316.5  3852.5  306.86
    3867  306.68  3906.4   300.3  4071.9  282.52  4271.3  264.37  4424.4  262.01
  4553.9  264.26  4690.8  261.94  4969.4   263.5  4986.8  262.56  5007.7  257.63
  5010.4  257.13  5013.7  257.63  5032.9  265.31  5164.8  281.83  5237.7  293.24
  5267.9  294.86    5279  300.51  5308.8  302.04  5313.9  304.72  5330.6  305.68
  5361.5  312.22  5390.6  314.14  5395.7  317.77  5413.1  322.92  5459.4  328.32
#Mann= 6 ,-1 , 0
  3743.2     .05       0  3906.4     .16       0  4071.9     .05       0
  5007.7     .03       0  5013.7     .05       0  5164.8     .16       0
Bank Sta=4271.3,5032.9
XS Rating Curve= 0 ,0
Exp/Cntr=0.3,0.1

Type RM Length L Ch R = 1 ,23955   ,527,527,527
BEGIN DESCRIPTION:
EDWARDS CREEK 39.0
END DESCRIPTION:
XS GIS Cut Line= 3
      3645649.64     10627710.19      3646399.61     10627660.19
      3646899.58     10627710.19
#Sta/Elev= 30
  4246.8  299.81  4276.8  290.72  4307.9  284.71    4337  279.61    4347  276.29
  4387.1  274.66  4427.2     269  4477.3  264.66  4507.3  261.54  4547.4  260.83
  4707.8  260.63  4838.1  262.51  4888.2  261.12  4958.3  262.76  4985.4     256
  4988.2   255.5  4991.4     256  5008.5  256.67  5018.5  262.16    5109  264.84
  5159.2  268.83  5299.9   284.2  5340.1  292.04  5360.2  300.49  5410.5  307.04
  5420.5  313.11  5425.7  314.51  5440.6  319.47  5460.7  323.39  5500.9  328.72
#Mann= 5 ,-1 , 0
  4246.8      .1       0  4307.9     .05       0  4985.4     .03       0
  4991.4     .05       0  5425.7     .16       0
Bank Sta=4477.3,5109
XS Rating Curve= 0 ,0
Exp/Cntr=0.3,0.1

Type RM Length L Ch R = 1 ,23428   ,322,322,322
BEGIN DESCRIPTION:
EDWARDS CREEK 38.0
END DESCRIPTION:
XS GIS Cut Line= 3
       3645549.6     10627710.18      3646349.61     10628060.19
      3646749.57     10628110.18
#Sta/Elev= 30
  4135.4  326.64  4144.4  325.33  4149.8  328.04  4157.2  327.43  4167.8  323.85
  4173.2  324.18  4196.6  315.47  4201.8   315.9    4220  310.39  4248.9  305.36
  4255.5  300.37  4266.4  297.79  4272.2  292.94  4282.9  290.91  4295.6  284.67
  4324.5  276.36  4347.9  275.76  4371.3  269.84  4430.1  263.53  4522.5  260.39
  4976.3   261.4  4996.7  254.98  4999.4  254.48  5002.7  254.98  5005.9  260.55
    5059  263.32  5109.4  267.73    5248  284.98    5321  304.79  5411.7  321.93
#Mann= 6 ,-1 , 0
  4135.4     .05       0  4201.8      .1       0  4282.9     .05       0
  4996.7     .03       0  5002.7     .05       0    5248     .16       0
Bank Sta=4430.1,5059
XS Rating Curve= 0 ,0
Exp/Cntr=0.3,0.1

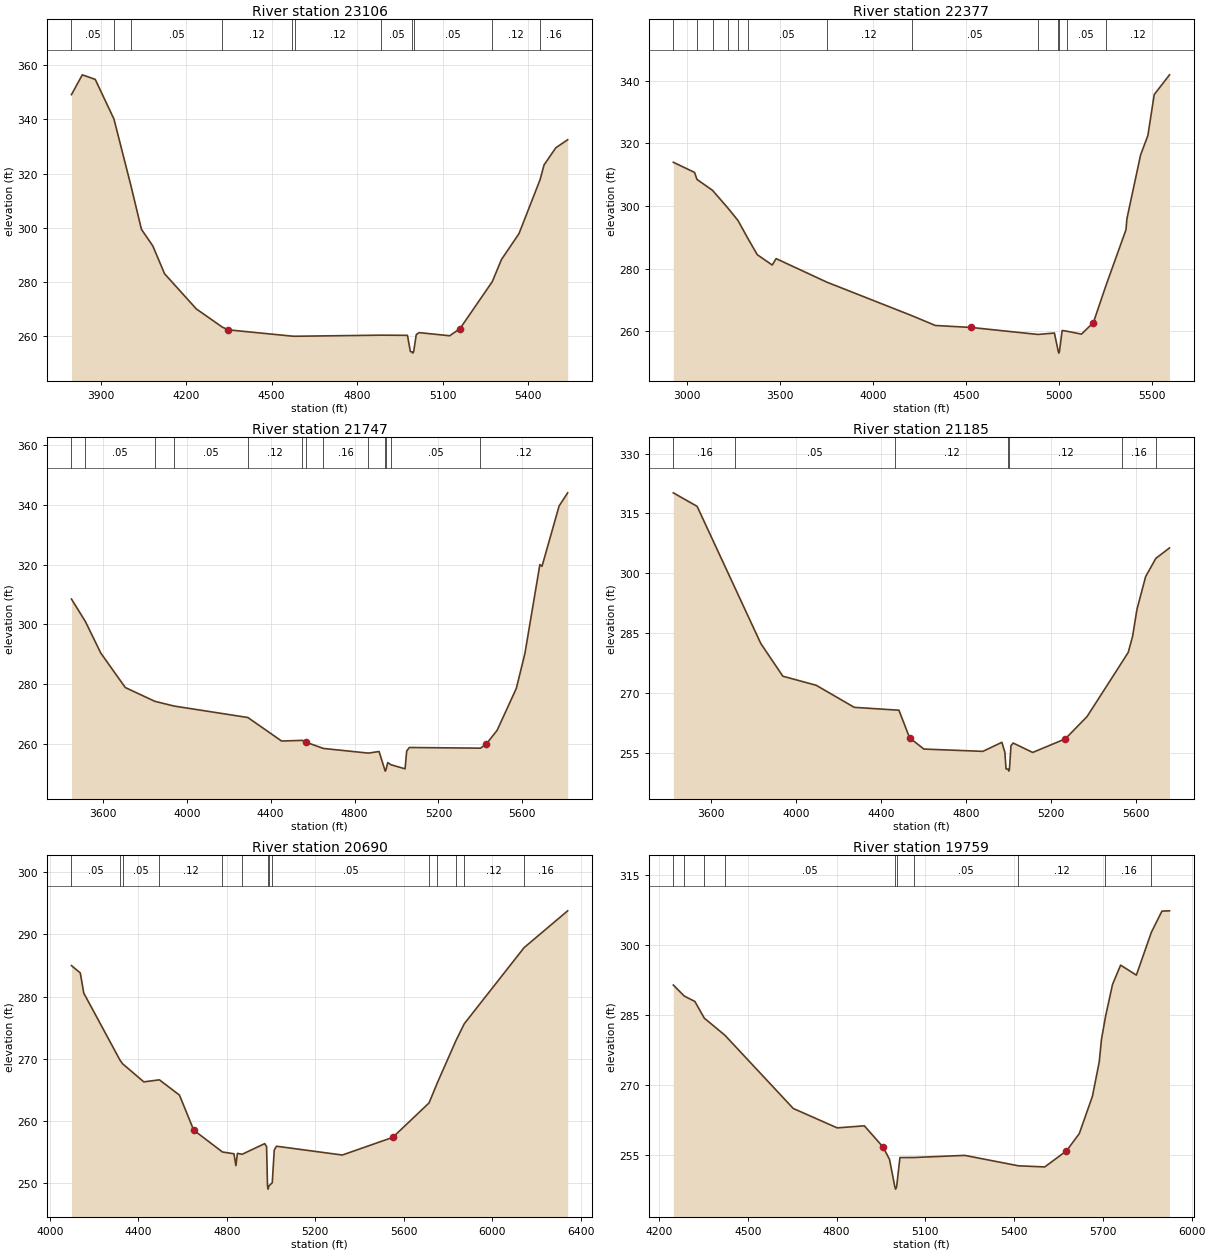
Type RM Length L Ch R = 1 ,23106   ,729,729,729
BEGIN DESCRIPTION:
EDWARDS CREEK 37.0
END DESCRIPTION:
XS GIS Cut Line= 3
      3645167.35     10628159.09      3646266.31     10628336.17
      3646875.05     10628185.29
#Sta/Elev= 30
  3798.1  349.12  3836.1  356.42  3881.4  354.75  3947.1  340.13  4006.4  315.66
  4043.5  299.48  4083.4  293.36  4124.5  283.12  4235.9  270.14  4327.1  263.44
  4347.4  262.43  4570.2  260.12  4581.4  260.06  4885.2  260.46  4976.5   260.4
  4986.8   254.4  4992.2  254.34  4994.9  253.84  4998.2  254.34  5007.4  260.69
  5017.7   261.4  5124.5  260.24  5160.7  262.87  5273.9  280.17  5306.1  288.32
  5367.7  297.89  5441.7  317.79  5455.6  323.21    5497  329.55  5538.4  332.48
#Mann= 11 ,-1 , 0
  3798.1     .05       0  3947.1     .16       0  4006.4     .05       0
  4327.1     .12       0  4570.2     .05       0  4581.4     .12       0
  4885.2     .05       0  4992.2     .03       0  4998.2     .05       0
  5273.9     .12       0  5441.7     .16       0
Bank Sta=4347.4,5160.7
XS Rating Curve= 0 ,0
Exp/Cntr=0.3,0.1

Type RM Length L Ch R = 1 ,22377   ,630,630,630
BEGIN DESCRIPTION:
EDWARDS CREEK 36.0
END DESCRIPTION:
XS GIS Cut Line= 2
      3646302.76     10630732.04      3647026.61     10628164.73
#Sta/Elev= 30
  2924.5  313.97  3038.7  310.73  3051.5   308.5  3135.4  304.99  3218.4   299.3
  3272.4  295.34  3324.2  289.75  3375.9  284.42  3456.3  281.13  3477.1  283.18
  3749.6  275.66  4205.8  264.97  4332.9  261.81  4526.5  261.17  4884.6  258.94
  4973.2  259.39  4994.1  253.47  4996.8  252.97  5000.1  253.47  5014.8  260.21
  5038.8  259.99  5118.7  259.04  5182.7  262.74  5248.2  274.24  5357.7  292.39
  5363.1     296  5436.4  316.31  5475.6  322.54  5509.6  335.61  5591.9  341.92
#Mann= 13 ,-1 , 0
  2924.5     .16       0  3051.5     .05       0  3135.4     .08       0
  3218.4     .05       0  3272.4     .16       0  3324.2     .05       0
  3749.6     .12       0  4205.8     .05       0  4884.6     .16       0
  4994.1     .07       0  5000.1     .16       0  5038.8     .05       0
  5248.2     .12       0
Bank Sta=4526.5,5182.7
XS Rating Curve= 0 ,0
Exp/Cntr=0.3,0.1

Type RM Length L Ch R = 1 ,21747   ,562,562,562
BEGIN DESCRIPTION:
EDWARDS CREEK 35.0
END DESCRIPTION:
XS GIS Cut Line= 3
      3646849.61     10630460.18      3647249.61     10628910.19
      3647099.61     10628160.22
#Sta/Elev= 30
  3450.3   308.5    3517  300.95    3590  290.46  3706.9  278.93  3847.8  274.32
  3939.4  272.74  4291.2  268.91  4452.1  261.05  4550.9  261.27  4570.3  260.62
  4651.2  258.57    4866  257.01  4916.8  257.55  4943.8  251.49  4946.6  250.99
  4949.8  251.49  4958.1  253.86  4973.3  253.13  5040.7  251.76  5048.5  257.74
  5061.3  258.89  5400.3  258.66  5428.4   260.1  5479.4  264.61  5571.2  278.65
    5612  290.29  5683.4  320.01  5693.6  319.45  5775.1  339.61  5815.9     344
#Mann= 13 ,-1 , 0
  3450.3     .16       0    3517     .05       0  3847.8     .12       0
  3939.4     .05       0  4291.2     .12       0  4550.9     .16       0
  4570.3     .12       0  4651.2     .16       0    4866     .12       0
  4943.8     .03       0  4949.8     .12       0  4973.3     .05       0
  5400.3     .12       0
Bank Sta=4570.3,5428.4
XS Rating Curve= 0 ,0
Exp/Cntr=0.3,0.1

Type RM Length L Ch R = 1 ,21185   ,495,495,495
BEGIN DESCRIPTION:
EDWARDS CREEK 34.0
END DESCRIPTION:
XS GIS Cut Line= 3
      3646899.62     10630660.18      3647599.61     10629260.19
      3647749.61     10628510.17
#Sta/Elev= 30
  3425.4  320.16  3537.2  316.77  3717.2  296.08  3836.3   282.4  3939.7  274.22
  4096.2  271.95  4275.1  266.42    4467  265.76  4484.7  265.71    4535  258.78
  4602.1  255.97  4878.8  255.39  4968.3  257.66  4982.2   255.2  4987.8  250.99
  4997.8  250.94  5000.6  250.44  5003.8  250.94    5011  256.83  5021.2  257.48
    5113  255.12    5266  258.52    5368  264.09  5530.7   277.6  5561.7   280.2
  5582.1  284.22  5602.5  290.95  5643.3  299.17  5691.2  303.74  5755.5  306.36
#Mann= 7 ,-1 , 0
  3425.4     .16       0  3717.2     .05       0    4467     .12       0
  4997.8     .03       0  5003.8     .12       0  5530.7     .16       0
  5691.2     .12       0
Bank Sta=4535,5266
XS Rating Curve= 0 ,0
Exp/Cntr=0.3,0.1

Type RM Length L Ch R = 1 ,20690   ,931,931,931
BEGIN DESCRIPTION:
EDWARDS CREEK 33.0
END DESCRIPTION:
XS GIS Cut Line= 3
      3647366.51     10630423.11      3647969.83     10629385.75
      3648790.12     10628739.06
#Sta/Elev= 30
  4097.1  284.99    4137  283.81  4152.8  280.56  4316.9  269.75  4328.5  269.18
  4424.4  266.27  4494.8   266.6  4585.6  264.14  4650.1   258.5  4780.1  254.98
  4832.2  254.69  4840.9  252.78  4847.9  254.76  4869.1  254.61  4971.2  256.33
  4979.7  255.85  4983.9   249.5  4986.7     249  4989.9   249.5  5005.4  250.03
  5014.4  255.29  5024.2  255.91  5322.3  254.49  5550.8  257.34  5714.7  262.88
  5752.2  266.12  5836.8  272.95    5874  275.63  6144.5  287.88  6341.7  293.81
#Mann= 14 ,-1 , 0
  4097.1     .05       0  4316.9     .12       0  4328.5     .05       0
  4494.8     .12       0  4780.1     .16       0  4869.1     .12       0
  4983.9     .07       0  4989.9     .12       0  5005.4     .05       0
  5714.7     .07       0  5752.2     .16       0  5836.8     .07       0
    5874     .12       0  6144.5     .16       0
Bank Sta=4650.1,5550.8
XS Rating Curve= 0 ,0
Exp/Cntr=0.3,0.1

Type RM Length L Ch R = 1 ,19759   ,508,508,508
BEGIN DESCRIPTION:
EDWARDS CREEK 32.0
END DESCRIPTION:
XS GIS Cut Line= 3
      3647605.26     10630518.55      3648334.41     10629828.46
      3648667.83     10629243.89
#Sta/Elev= 30
  4248.3  291.45  4285.5  289.08  4321.1  287.93    4353  284.34  4422.5  280.68
  4653.6  264.94  4802.1  260.77  4893.9  261.21  4957.4  256.63  4978.9     254
  4996.9  248.11  4999.6  247.61  5002.9  248.11  5014.1  254.39  5060.2   254.4
  5233.3  254.86  5414.7  252.62  5503.5  252.38    5577  255.83  5620.2  259.54
  5664.7  267.57  5687.7  274.96  5695.1  279.72  5708.6   284.6  5732.5  291.57
  5759.9  295.73  5813.2  293.59  5863.7  302.77  5899.6  307.34  5925.2   307.4
#Mann= 10 ,-1 , 0
  4248.3     .16       0  4285.5     .05       0    4353     .08       0
  4422.5     .05       0  4996.9     .07       0  5002.9     .05       0
  5060.2     .05       0  5414.7     .12       0  5708.6     .16       0
  5863.7     .12       0
Bank Sta=4957.4,5577
XS Rating Curve= 0 ,0
Exp/Cntr=0.3,0.1

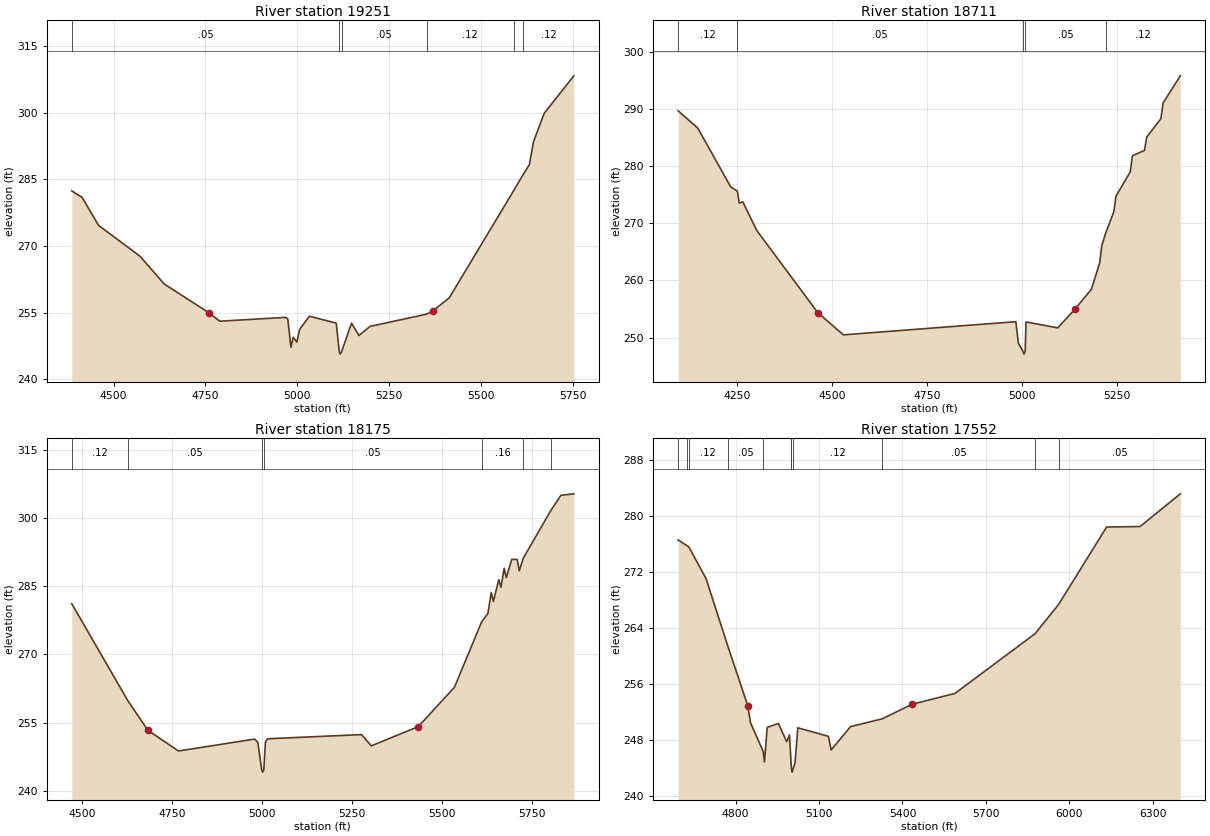
Type RM Length L Ch R = 1 ,19251   ,540,540,540
BEGIN DESCRIPTION:
EDWARDS CREEK 31.0
END DESCRIPTION:
XS GIS Cut Line= 3
      3648249.59     10630510.21      3648599.61     10630010.19
      3648699.61     10629260.19
#Sta/Elev= 30
  4386.1  282.44  4414.5  280.94  4458.9  274.67  4572.3  267.68  4637.7  261.45
  4759.7  254.95  4788.9  253.06  4968.1  253.92  4974.2  253.59  4982.9  247.18
    4989  249.43    4999  248.35  5006.5  251.23    5033  254.18  5106.2  252.63
  5114.5  246.14  5117.3  245.64  5120.5  246.14  5147.8  252.61    5168  249.84
  5198.2  251.89  5352.8  254.66  5369.7  255.42  5413.9  258.33  5589.9  282.57
  5615.7   286.2    5632  288.34  5643.4  293.55  5672.4  299.92  5753.1  308.36
#Mann= 6 ,-1 , 0
  4386.1     .05       0  5114.5     .03       0  5120.5     .05       0
  5352.8     .12       0  5589.9     .16       0  5615.7     .12       0
Bank Sta=4759.7,5369.7
XS Rating Curve= 0 ,0
Exp/Cntr=0.3,0.1

Type RM Length L Ch R = 1 ,18711   ,536,536,536
BEGIN DESCRIPTION:
EDWARDS CREEK 30.0
END DESCRIPTION:
XS GIS Cut Line= 3
      3649399.62      10630510.2      3648949.61     10629710.19
      3648749.61      10629360.2
#Sta/Elev= 30
  4095.5  289.63  4146.8  286.62  4233.5  276.35  4251.1  275.58  4256.1   273.5
  4265.4  273.72    4302  268.73  4462.7  254.35  4529.9  250.47  4983.8  252.77
  4990.4  249.03  5002.4   247.6  5005.2   247.1  5008.4   247.6  5010.5  252.73
    5094  251.69  5139.4  254.97  5182.6  258.44  5204.2     263  5209.9  266.04
  5219.9  268.23  5241.6  271.99  5247.3  274.72  5284.8  278.97  5290.5  281.78
  5322.2  282.71    5328  285.03  5365.4  288.25  5371.2  291.01  5416.5  295.75
#Mann= 5 ,-1 , 0
  4095.5     .12       0  4251.1     .05       0  5002.4     .03       0
  5008.4     .05       0  5219.9     .12       0
Bank Sta=4462.7,5139.4
XS Rating Curve= 0 ,0
Exp/Cntr=0.3,0.1

Type RM Length L Ch R = 1 ,18175   ,623,623,623
BEGIN DESCRIPTION:
EDWARDS CREEK 29.0
END DESCRIPTION:
XS GIS Cut Line= 3
      3649799.64     10630010.22      3649449.61     10629660.19
      3648699.62      10629160.2
#Sta/Elev= 30
  4470.4  281.14  4625.7   259.9  4682.6  253.27  4767.4  248.77  4978.9  251.38
    4988  250.65  4998.5  244.62  5001.2  244.12  5004.5  244.62    5009  250.72
    5015  251.45  5276.4  252.37  5303.4  249.89  5434.1  254.12  5534.8  262.78
  5610.3  277.13  5627.9  279.01    5637   283.6    5643  281.63    5658  286.42
    5664  284.73    5673  288.93    5679  286.87    5694  290.87  5709.1  290.88
  5715.1  288.36  5726.2  291.15    5802   301.5  5830.8  304.96  5866.8  305.28
#Mann= 7 ,-1 , 0
  4470.4     .12       0  4625.7     .05       0  4998.5     .03       0
  5004.5     .05       0  5610.3     .16       0  5726.2     .12       0
    5802     .16       0
Bank Sta=4682.6,5434.1
XS Rating Curve= 0 ,0
Exp/Cntr=0.3,0.1

Type RM Length L Ch R = 1 ,17552   ,490,490,490
BEGIN DESCRIPTION:
EDWARDS CREEK 28.0
END DESCRIPTION:
XS GIS Cut Line= 3
      3649949.61      10629810.2      3649954.45      10629114.8
      3649917.99     10628005.42
#Sta/Elev= 30
  4593.8  276.51  4624.8  275.71  4631.6  275.54  4693.8     271  4771.6  261.42
  4843.8  252.84  4853.8   250.4  4899.4   246.3  4903.8  244.82  4913.8  249.75
  4953.8  250.31  4983.8  247.71  4993.8  248.68  4997.5  246.13  5000.8  243.86
  5003.6  243.36  5006.8  243.86  5013.8  244.67  5023.8  249.69  5133.8  248.47
  5143.8  246.53  5213.8  249.87  5327.2  250.97  5433.9  253.04  5588.9   254.6
  5877.1  263.13  5961.6  267.31  6134.3  278.36  6254.4  278.43  6399.2   283.1
#Mann= 11 ,-1 , 0
  4593.8     .12       0  4624.8     .16       0  4631.6     .12       0
  4771.6     .05       0  4899.4     .16       0  4997.5     .12       0
  5000.8     .07       0  5006.8     .12       0  5327.2     .05       0
  5877.1     .16       0  5961.6     .05       0
Bank Sta=4843.8,5433.9
XS Rating Curve= 0 ,0
Exp/Cntr=0.3,0.1