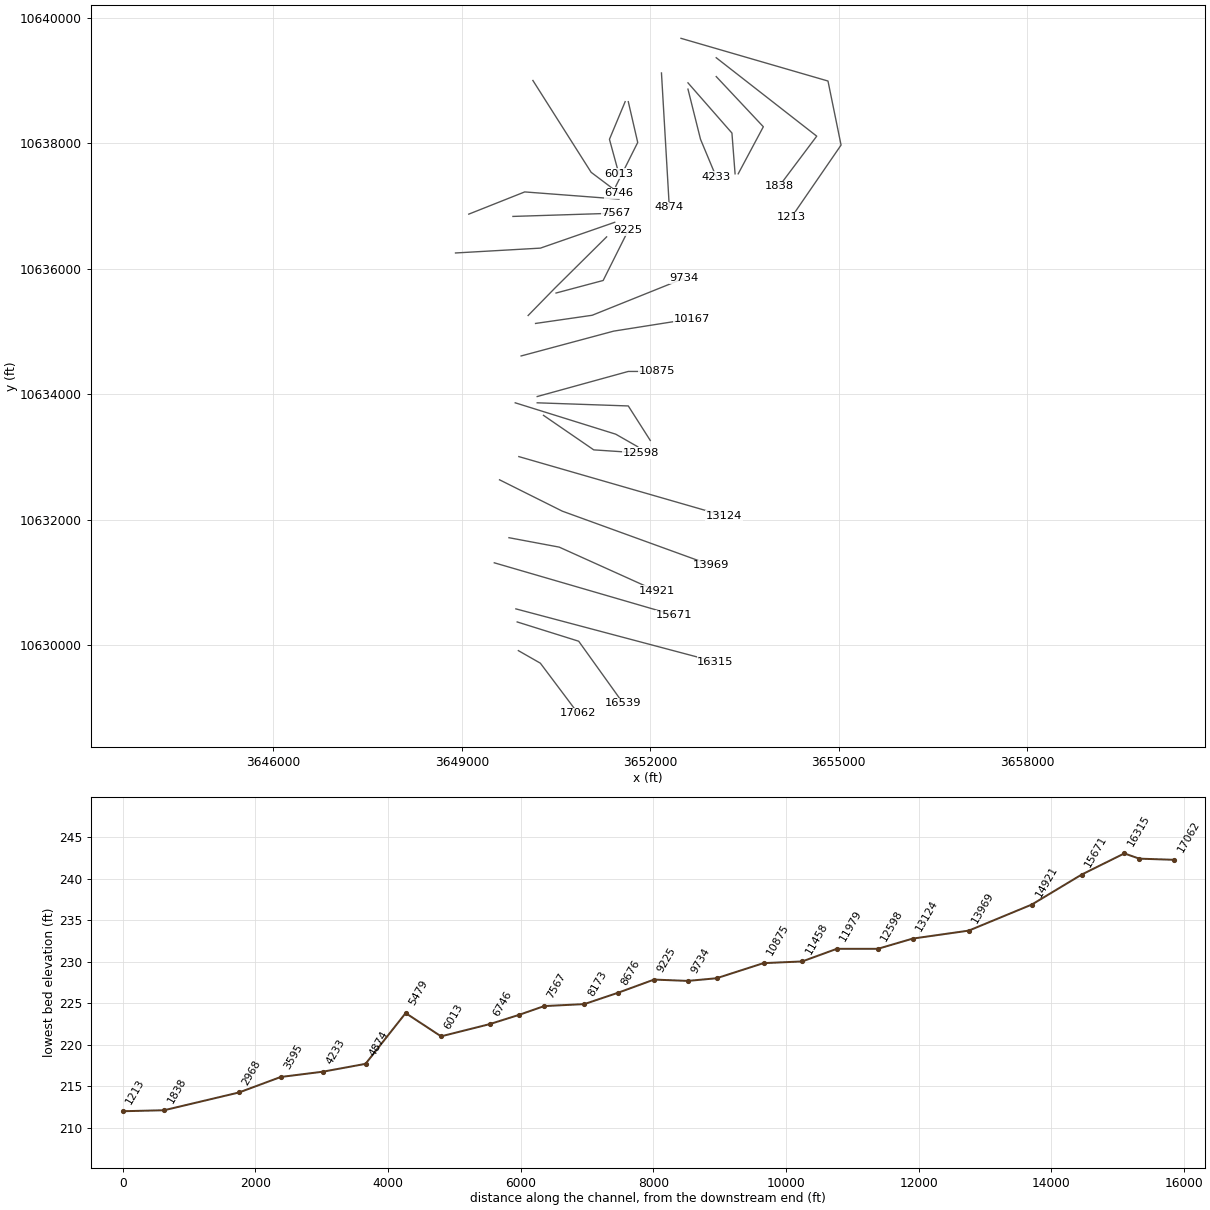
HEC-RAS study EDWARDS CREEK.prj: EDWARDS CREEK Base Level Engineering

--- EDWARDS CREEK.g01 (geometry) --- (continued)

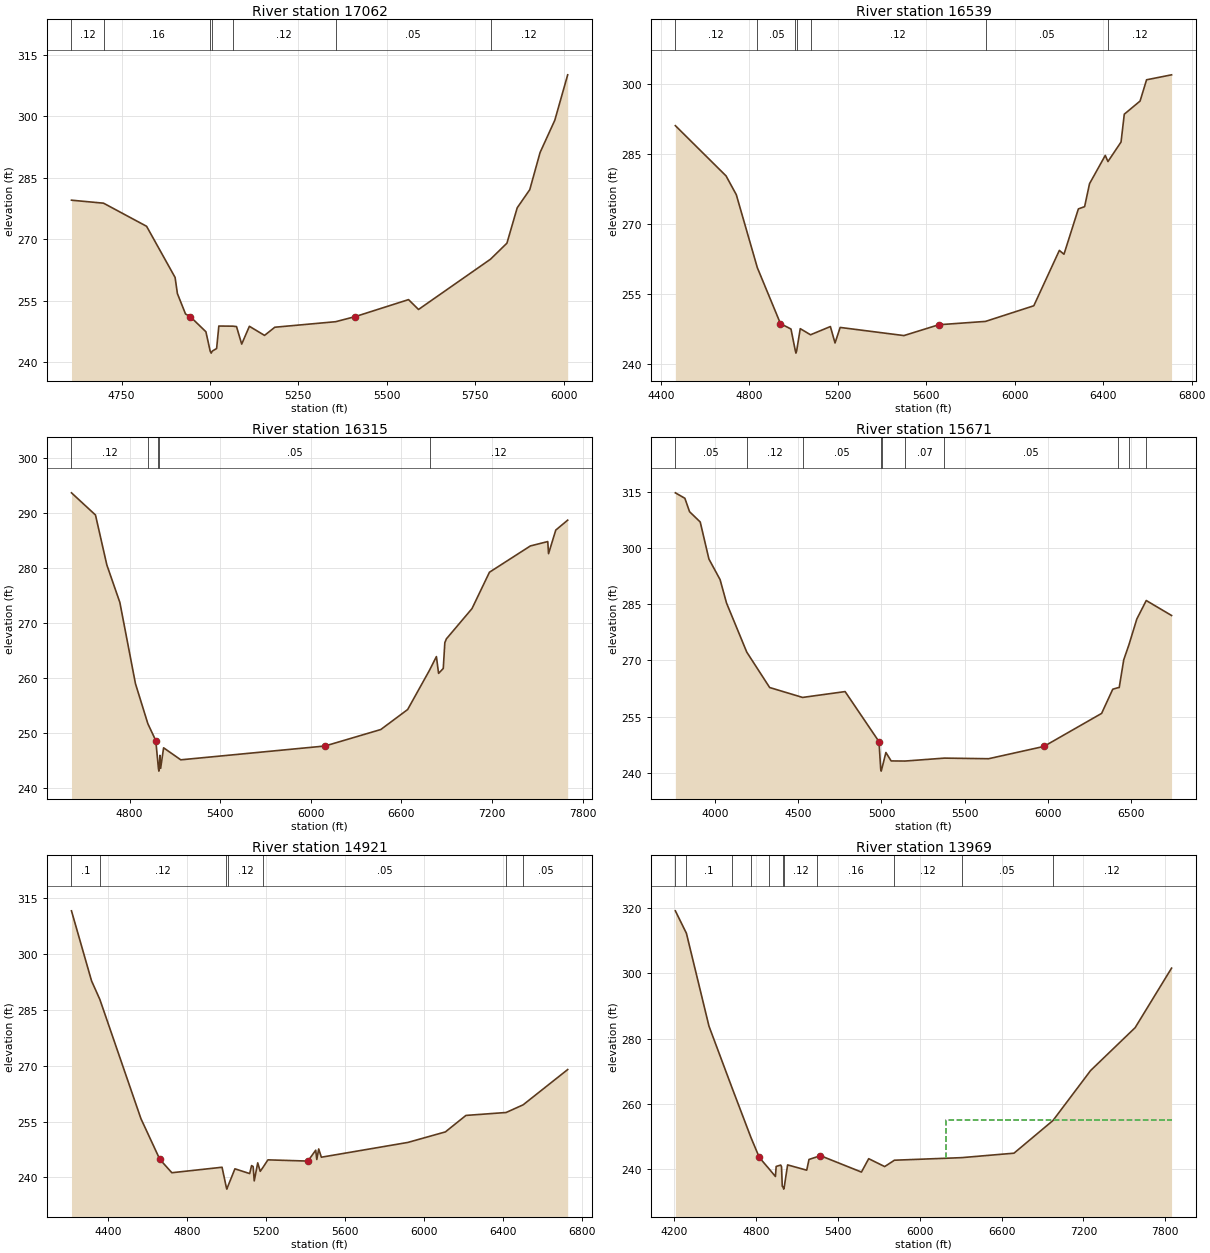
Type RM Length L Ch R = 1 ,17062   ,523,523,523
BEGIN DESCRIPTION:
EDWARDS CREEK 27.0
END DESCRIPTION:
XS GIS Cut Line= 3
      3649899.58      10629910.2      3650249.61     10629710.19
      3650849.58     10628910.22
#Sta/Elev= 30
  4608.5  279.52  4699.2  278.79  4820.9  273.16  4901.5  260.69    4908  256.77
    4931  251.79  4944.7  251.12  4988.6  247.46  5000.7  242.75  5003.5  242.25
  5006.7  242.75  5018.9  243.37  5025.2  248.85  5064.5  248.82  5075.2  248.72
  5089.8  244.45  5111.6  248.79  5154.4  246.57  5183.5  248.56  5355.7  249.91
  5411.6  251.17  5561.6  255.29  5589.8  252.89  5793.4  265.14  5839.8  269.04
  5868.9  277.67  5904.4  282.09  5933.5  291.13  5975.2  299.01  6011.6  310.07
#Mann= 7 ,-1 , 0
  4608.5     .12       0  4699.2     .16       0  5000.7     .07       0
  5006.7     .16       0  5064.5     .12       0  5355.7     .05       0
  5793.4     .12       0
Bank Sta=4944.7,5411.6
XS Rating Curve= 0 ,0
Exp/Cntr=0.3,0.1

Type RM Length L Ch R = 1 ,16539   ,224,224,224
BEGIN DESCRIPTION:
EDWARDS CREEK 26.0
END DESCRIPTION:
XS GIS Cut Line= 3
      3649880.88     10630367.43      3650860.06     10630060.13
      3651568.37     10629070.58
#Sta/Elev= 30
    4466     291  4695.2  280.26  4741.5  276.25  4836.6  260.65  4941.3  248.69
  4988.7  247.54  5008.4  242.89  5011.1  242.39  5014.4  242.89  5030.6  247.62
    5077  246.31  5166.9  248.07  5187.8  244.56  5211.1  247.88  5499.2  246.14
  5656.5  248.45  5868.1  249.17  6086.4  252.51  6201.9  264.34  6222.8  263.52
  6287.9  273.21  6316.1  273.69  6338.3  278.59  6409.5  284.64  6421.6  283.33
  6480.8   287.5  6495.5  293.45  6566.8  296.25  6596.2   300.8  6709.2  301.86
#Mann= 7 ,-1 , 0
    4466     .12       0  4836.6     .05       0  5008.4     .03       0
  5014.4     .05       0    5077     .12       0  5868.1     .05       0
  6421.6     .12       0
Bank Sta=4941.3,5656.5
XS Rating Curve= 0 ,0
Exp/Cntr=0.3,0.1

Type RM Length L Ch R = 1 ,16315   ,644,644,644
BEGIN DESCRIPTION:
EDWARDS CREEK 25.0
END DESCRIPTION:
XS GIS Cut Line= 2
      3649860.06     10630575.76      3653035.88     10629732.34
#Sta/Elev= 30
  4415.4  293.73  4574.4  289.69  4649.5   280.6  4735.7  273.77  4839.1  258.96
    4921  251.68  4973.6  248.59  4991.3  243.52  4994.1  243.02  4997.3  243.52
  5000.8   245.9  5005.9  243.53  5025.4  247.27  5139.2  245.08  6094.6   247.6
  6463.6   250.6  6641.5  254.24  6786.6  261.42    6832  263.89  6846.4  260.83
  6877.4  261.73  6887.8  266.43  6898.1  267.12  7067.8  272.64  7183.2  279.26
  7454.1  284.05  7569.4  284.85  7574.6  282.64  7622.4  286.94  7701.3  288.75
#Mann= 5 ,-1 , 0
  4415.4     .12       0    4921     .05       0  4991.3     .03       0
  4997.3     .05       0  6786.6     .12       0
Bank Sta=4973.6,6094.6
XS Rating Curve= 0 ,0
Exp/Cntr=0.3,0.1

Type RM Length L Ch R = 1 ,15671   ,750,750,750
BEGIN DESCRIPTION:
EDWARDS CREEK 24.0
END DESCRIPTION:
XS GIS Cut Line= 2
      3649516.34     10631310.12       3652375.1     10630476.97
#Sta/Elev= 30
  3763.2  314.71  3820.2  313.26  3848.5  309.67  3912.4  306.93  3964.6  297.05
  4031.6  291.56  4070.3  285.31  4191.7  272.22  4329.1  262.77  4526.8  260.13
  4781.9  261.69  4985.3  248.33  4995.5  240.97  4998.2  240.47  5001.5  240.97
  5026.7  245.44  5058.2  243.19  5142.7  243.16  5377.3  243.94    5643  243.78
  5974.8  247.06  6321.1  255.87    6388  262.32  6417.3   262.7  6426.8  262.77
  6453.9  270.17  6484.8  274.14  6532.4  281.05    6589  285.98  6740.9  281.99
#Mann= 10 ,-1 , 0
  3763.2     .05       0  4191.7     .12       0  4526.8     .05       0
  4995.5     .03       0  5001.5     .05       0  5142.7     .07       0
  5377.3     .05       0  6417.3      .1       0  6484.8     .16       0
    6589     .12       0
Bank Sta=4985.3,5974.8
XS Rating Curve= 0 ,0
Exp/Cntr=0.3,0.1

Type RM Length L Ch R = 1 ,14921   ,952,952,952
BEGIN DESCRIPTION:
EDWARDS CREEK 23.0
END DESCRIPTION:
XS GIS Cut Line= 3
      3649749.59     10631710.19      3650549.61     10631560.19
      3652099.61     10630860.19
#Sta/Elev= 30
  4214.8  311.68  4316.6  292.84  4358.5  287.88  4566.7  255.83  4662.5  244.88
  4723.5  241.28  4977.9  242.75  4999.5  237.37  5002.2  236.87  5005.5  237.37
  5043.1  242.33  5117.9  241.05  5127.5   243.2  5135.5  242.93    5141  239.08
  5158.7  243.94  5171.4  241.65  5187.6   242.9  5210.4  244.74  5412.8  244.41
  5452.6  247.33  5458.1  244.84  5467.7  247.67  5481.2  245.45  5919.3  249.42
  6109.7  252.25  6213.8  256.68  6417.5  257.47  6503.7  259.53  6729.5  269.01
#Mann= 7 ,-1 , 0
  4214.8      .1       0  4358.5     .12       0  4999.5     .07       0
  5005.5     .12       0  5187.6     .05       0  6417.5     .08       0
  6503.7     .05       0
Bank Sta=4662.5,5412.8
XS Rating Curve= 0 ,0
Exp/Cntr=0.3,0.1

Type RM Length L Ch R = 1 ,13969   ,845,845,845
BEGIN DESCRIPTION:
EDWARDS CREEK 22.0
END DESCRIPTION:
XS GIS Cut Line= 3
      3649599.65     10632633.04      3650599.65     10632133.05
       3652964.2     10631273.68
#Sta/Elev= 30
  4211.4  319.22  4292.4  312.32  4457.7  283.78  4626.7  264.83  4764.5  249.64
  4826.3  243.45    4898  239.94  4944.1  237.62  4949.7   240.7  4982.8  241.12
  4988.8  240.64  4994.4  234.62  5002.2  234.23  5004.9  233.73  5008.2  234.23
  5033.5  241.17  5173.3  239.55  5190.1  242.84  5252.1   243.7  5273.5  244.01
  5574.1  238.97  5627.3  243.08  5744.3  240.66  5815.7  242.61  6307.9   243.4
  6691.3  244.77  6976.9  254.81  7252.6  270.17  7578.6  283.33  7845.3  301.62
#Mann= 11 ,-1 , 0
  4211.4     .05       0  4292.4      .1       0  4626.7     .05       0
  4764.5     .16       0    4898     .12       0  5002.2     .07       0
  5008.2     .12       0  5252.1     .16       0  5815.7     .12       0
  6307.9     .05       0  6976.9     .12       0
#XS Ineff= 2 , 0
                         6193.18          254.92
Permanent Ineff=
       F       F
Bank Sta=4826.3,5273.5
XS Rating Curve= 0 ,0
Exp/Cntr=0.3,0.1

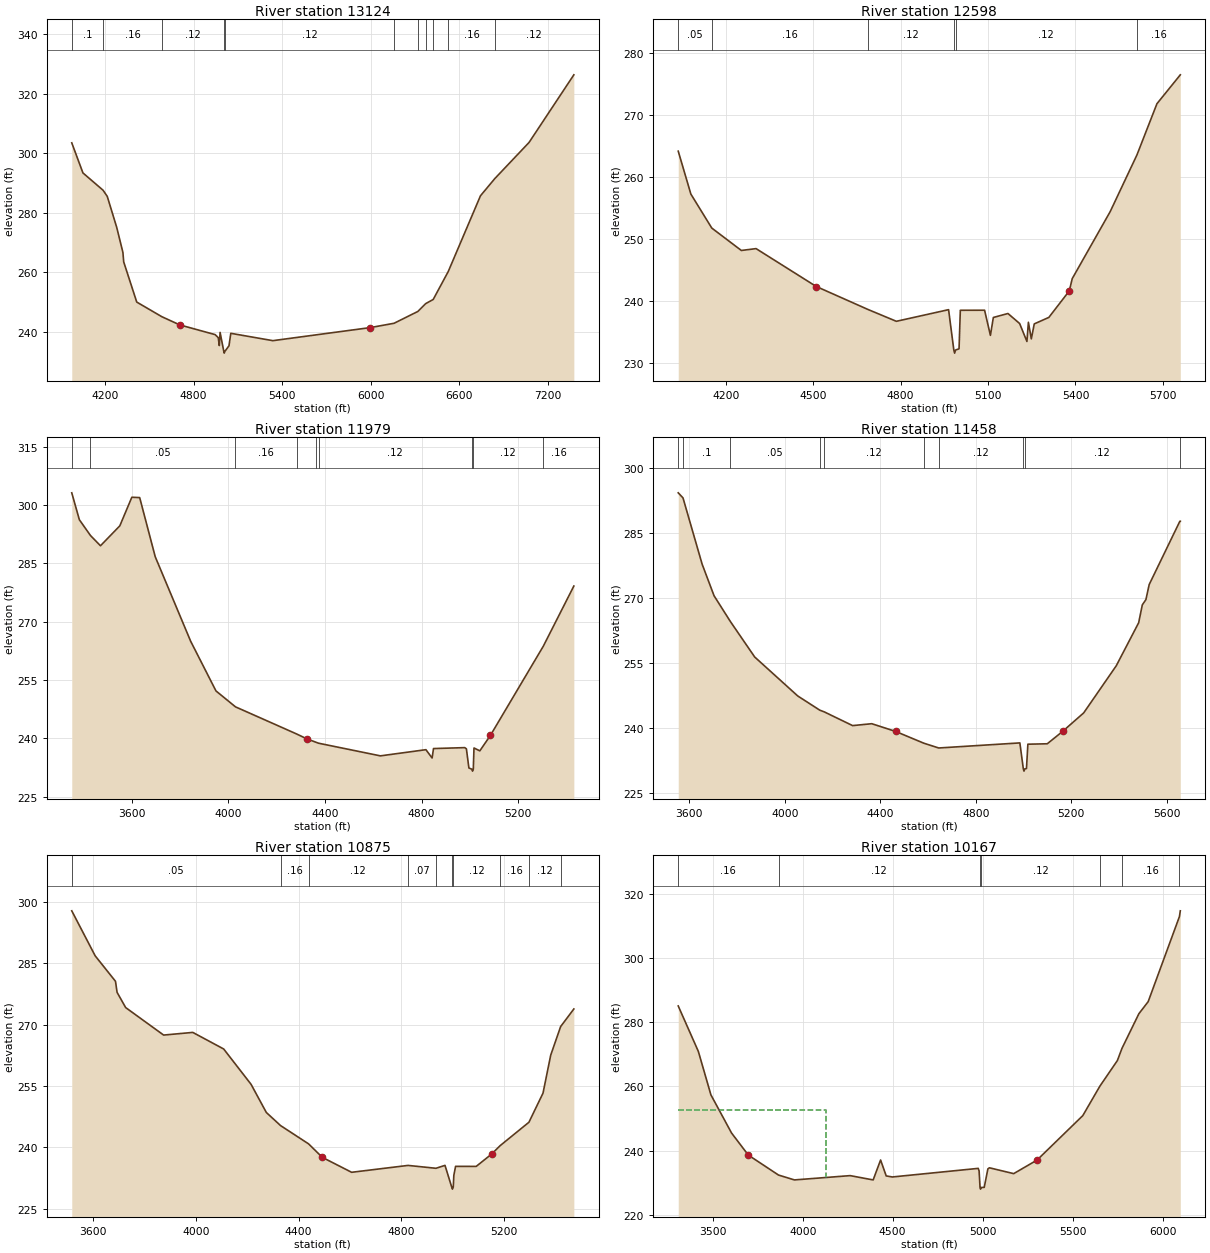
Type RM Length L Ch R = 1 ,13124   ,526,526,526
BEGIN DESCRIPTION:
EDWARDS CREEK 21.0
END DESCRIPTION:
XS GIS Cut Line= 2
      3649906.98     10633002.83      3653172.54     10632060.14
#Sta/Elev= 30
  3975.9  303.45  4051.5  293.34  4187.8  287.52  4216.3  285.44  4280.5  274.98
  4322.1  266.62  4327.6  263.41  4415.8  249.93  4585.4  245.02  4707.2  242.25
  4946.6  238.99  4967.4  237.98  4974.8  235.31    4980  239.73  5005.4  233.27
  5008.2  232.77  5011.4  233.27  5040.3  235.25  5052.5  239.43  5337.2  236.96
  5997.8  241.36  6157.6   242.8  6318.7  246.77  6371.9  249.41  6422.8  250.81
  6524.8  260.22  6742.8  285.66  6839.4  291.41  7071.6  303.58  7374.8  326.31
#Mann= 11 ,-1 , 0
  3975.9      .1       0  4187.8     .16       0  4585.4     .12       0
  5005.4     .07       0  5011.4     .12       0  6157.6     .16       0
  6318.7     .12       0  6371.9     .16       0  6422.8     .12       0
  6524.8     .16       0  6839.4     .12       0
Bank Sta=4707.2,5997.8
XS Rating Curve= 0 ,0
Exp/Cntr=0.3,0.1

Type RM Length L Ch R = 1 ,12598   ,619,619,619
BEGIN DESCRIPTION:
EDWARDS CREEK 20.0
END DESCRIPTION:
XS GIS Cut Line= 3
      3650299.61     10633660.19      3651099.61     10633110.19
      3651849.62     10633060.19
#Sta/Elev= 30
  4037.2  264.16  4080.5  257.23  4152.3  251.74  4253.7  248.12  4304.2  248.42
  4510.8   242.3  4687.2  238.61  4785.5  236.68  4964.7  238.56  4982.7  232.04
  4985.4  231.54  4988.7  232.04  5000.6  232.24    5005  238.46  5088.2  238.47
  5108.2  234.41  5118.3   237.3  5168.4  237.94  5208.5  236.32  5233.5  233.42
  5238.5  236.52  5248.6  233.84  5258.6  236.26  5308.7  237.31  5378.8  241.59
  5388.9  243.57  5519.2   254.4  5610.8  263.54  5679.5  271.82  5759.7  276.49
#Mann= 6 ,-1 , 0
  4037.2     .05       0  4152.3     .16       0  4687.2     .12       0
  4982.7     .07       0  4988.7     .12       0  5610.8     .16       0
Bank Sta=4510.8,5378.8
XS Rating Curve= 0 ,0
Exp/Cntr=0.3,0.1

Type RM Length L Ch R = 1 ,11979   ,521,521,521
BEGIN DESCRIPTION:
EDWARDS CREEK 19.0
END DESCRIPTION:
XS GIS Cut Line= 3
      3649849.64     10633860.18      3651449.61     10633360.19
      3651799.62     10633160.18
#Sta/Elev= 30
  3351.5  303.19  3382.9  296.27    3429   292.2  3470.4  289.56  3550.5  294.69
  3600.3  302.05  3632.8  301.96  3697.2  286.73  3843.9  264.98  3948.7  252.19
  4029.5  248.09  4282.6  241.11  4325.8  239.83  4361.8     239  4373.4  238.73
  4629.7  235.47  4818.2  237.06  4843.9  234.92  4849.7  237.35  4979.1  237.59
  4985.9  237.28  4996.3  232.35  5008.5  232.04  5011.3  231.54  5014.5  232.04
  5017.3   237.5  5041.5  236.76  5085.4  240.74  5304.4   263.7  5430.9  279.19
#Mann= 9 ,-1 , 0
  3351.5      .1       0    3429     .05       0  4029.5     .16       0
  4282.6     .12       0  4361.8     .16       0  4373.4     .12       0
  5008.5     .07       0  5014.5     .12       0  5304.4     .16       0
Bank Sta=4325.8,5085.4
XS Rating Curve= 0 ,0
Exp/Cntr=0.3,0.1

Type RM Length L Ch R = 1 ,11458   ,583,583,583
BEGIN DESCRIPTION:
EDWARDS CREEK 18.0
END DESCRIPTION:
XS GIS Cut Line= 3
      3650199.62     10633860.19      3651649.61     10633810.19
      3651999.62     10633260.17
#Sta/Elev= 30
  3553.6  294.22  3573.5  293.06  3653.7  277.76  3703.7  270.47  3771.8  264.55
  3873.8  256.35  4053.9  247.37  4146.2  244.09  4165.5  243.68    4284  240.52
  4364.1  240.96  4464.1  239.18  4582.3  236.46  4644.6  235.36  4984.4  236.53
    4999  230.52  5001.7  230.02    5005  230.52  5012.1  230.63    5018  236.23
  5099.3  236.33  5163.6  239.19  5251.7  243.45    5388  254.31    5482  264.25
  5497.2  268.36  5512.4   269.6    5526  273.05  5654.5  287.66  5656.4  287.66
#Mann= 10 ,-1 , 0
  3553.6     .05       0  3573.5      .1       0  3771.8     .05       0
  4146.2     .16       0  4165.5     .12       0  4582.3     .16       0
  4644.6     .12       0    4999     .07       0    5005     .12       0
  5654.5     .16       0
Bank Sta=4464.1,5163.6
XS Rating Curve= 0 ,0
Exp/Cntr=0.3,0.1

Type RM Length L Ch R = 1 ,10875   ,708,708,708
BEGIN DESCRIPTION:
EDWARDS CREEK 17.0
END DESCRIPTION:
XS GIS Cut Line= 3
      3650199.63      10633960.2      3651649.61     10634360.19
      3652099.57     10634360.19
#Sta/Elev= 30
  3517.1  297.78  3608.2  286.79  3687.3  280.57  3693.4  277.88  3726.8  274.16
  3874.6  267.44  3988.1  268.09  4108.4  264.04    4215  255.41  4274.3  248.54
  4329.7  245.34  4438.8  240.87  4492.2  237.58  4606.3  233.93  4825.9  235.61
  4934.5  234.91  4969.7  235.62  4995.9  230.32  4998.6  229.82  5001.9  230.32
  5004.1  233.17  5010.9  235.38  5091.2  235.37  5151.2  238.38  5184.4  240.44
  5296.4  246.15  5351.2  253.26  5381.2  262.54  5419.9  269.53  5471.2  273.81
#Mann= 10 ,-1 , 0
  3517.1     .05       0  4329.7     .16       0  4438.8     .12       0
  4825.9     .07       0  4934.5     .12       0  4995.9     .07       0
  5001.9     .12       0  5184.4     .16       0  5296.4     .12       0
  5419.9     .16       0
Bank Sta=4492.2,5151.2
XS Rating Curve= 0 ,0
Exp/Cntr=0.3,0.1

Type RM Length L Ch R = 1 ,10167   ,433,433,433
BEGIN DESCRIPTION:
EDWARDS CREEK 16.0
END DESCRIPTION:
XS GIS Cut Line= 3
      3649943.36       10634607.      3651417.35     10635002.84
      3652665.98     10635200.54
#Sta/Elev= 30
  3308.3  285.11  3420.2  270.92  3489.9  257.39  3604.6   245.5  3697.9  238.61
  3865.6  232.39  3954.2  230.87  4263.7  232.21  4391.6  230.87    4433  237.08
  4464.1  232.12  4498.5  231.79  4975.5  234.47  4980.5  233.66  4985.7   228.5
  4988.4     228  4991.7   228.5  5008.9  228.55  5029.2   234.3  5037.8  234.65
  5172.6  232.83  5302.5  237.06  5556.8  250.92  5651.3  260.07  5748.9  268.08
  5774.5  271.89  5868.6   282.7  5920.1  286.45  6093.8  312.97  6098.7  314.77
#Mann= 7 ,-1 , 0
  3308.3     .16       0  3865.6     .12       0  4985.7     .07       0
  4991.7     .12       0  5651.3      .1       0  5774.5     .16       0
  6093.8     .12       0
#XS Ineff= 2 , 0
         4127.56  252.79
Permanent Ineff=
       F       F
Bank Sta=3697.9,5302.5
XS Rating Curve= 0 ,0
Exp/Cntr=0.3,0.1

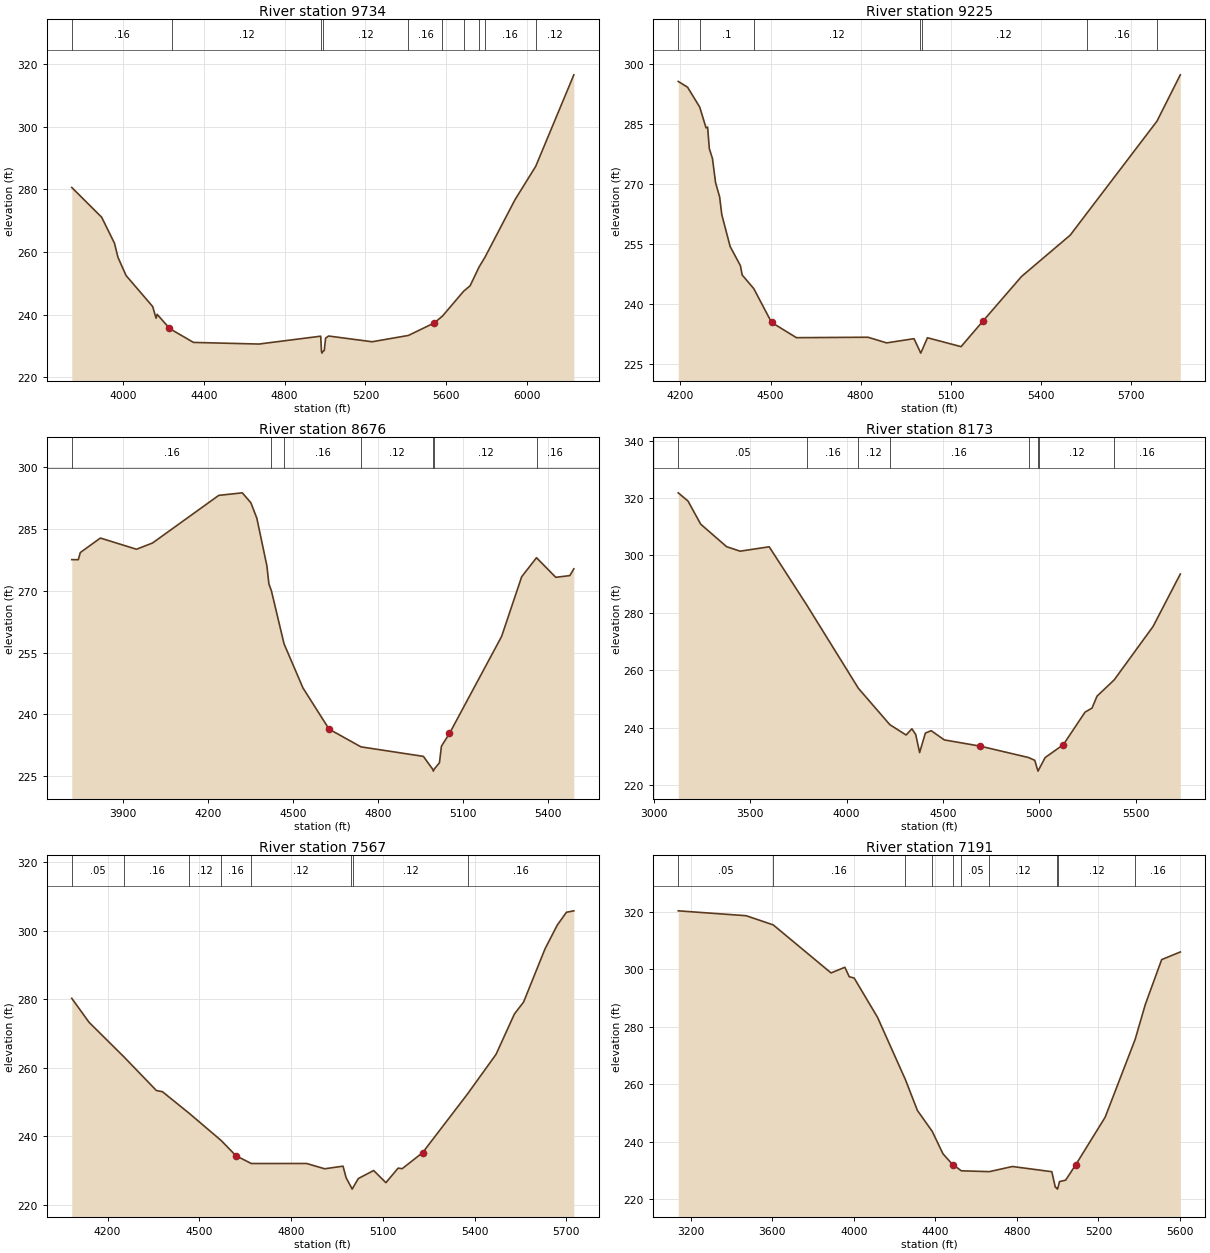
Type RM Length L Ch R = 1 ,9734    ,509,509,509
BEGIN DESCRIPTION:
EDWARDS CREEK 15.0
END DESCRIPTION:
XS GIS Cut Line= 3
      3650173.25     10635125.23      3651074.24     10635255.43
       3652536.2     10635843.34
#Sta/Elev= 30
    3746  280.55  3893.9  271.06  3957.5  262.76  3974.7  258.26  4015.1  252.43
  4146.5  242.56  4163.4  238.83  4168.5  240.06  4227.3  235.82    4240  235.17
  4348.6   231.1  4672.9  230.58  4978.7  233.09  4982.5  228.18  4985.2  227.68
  4988.5  228.18  4996.3  228.51  5002.9  232.47  5017.8  233.14  5233.4  231.31
  5413.1  233.33  5540.4   237.3  5581.4  239.49  5686.4  247.44  5718.4  249.17
  5762.9  255.18  5791.4  258.21  5940.8  276.65  6043.2  287.28  6232.1   316.5
#Mann= 10 ,-1 , 0
    3746     .16       0    4240     .12       0  4982.5     .07       0
  4988.5     .12       0  5413.1     .16       0  5581.4     .12       0
  5686.4      .1       0  5762.9     .05       0  5791.4     .16       0
  6043.2     .12       0
Bank Sta=4227.3,5540.4
XS Rating Curve= 0 ,0
Exp/Cntr=0.3,0.1

Type RM Length L Ch R = 1 ,9225    ,549,549,549
BEGIN DESCRIPTION:
EDWARDS CREEK 14.0
END DESCRIPTION:
XS GIS Cut Line= 3
      3650499.59     10635610.18      3651249.61     10635810.19
      3651649.63     10636610.23
#Sta/Elev= 30
  4192.9  295.71    4224  294.27  4264.5  289.29  4285.4  284.11  4290.6  284.32
  4296.4   278.9  4306.8  276.46  4317.1  270.44  4330.7  266.84  4337.8  262.45
  4365.6  254.48  4399.9  249.68  4405.7  247.36  4444.2  243.97  4503.4  235.52
  4586.2   231.7  4824.2  231.81  4886.3   230.4  4977.5  231.45  4996.9  228.34
  4999.6  227.84  5002.9  228.34  5022.2  231.68    5134  229.46  5206.7  235.83
  5335.3  246.99  5497.4  257.32  5552.2  262.74  5785.8  285.77  5863.6  297.36
#Mann= 7 ,-1 , 0
  4192.9     .16       0  4264.5      .1       0  4444.2     .12       0
  4996.9     .07       0  5002.9     .12       0  5552.2     .16       0
  5785.8     .05       0
Bank Sta=4503.4,5206.7
XS Rating Curve= 0 ,0
Exp/Cntr=0.3,0.1

Type RM Length L Ch R = 1 ,8676    ,503,503,503
BEGIN DESCRIPTION:
EDWARDS CREEK 13.0
END DESCRIPTION:
XS GIS Cut Line= 3
      3650055.17     10635251.98      3650475.28     10635682.51
      3651304.76     10636505.04
#Sta/Elev= 30
  3720.6  277.55  3743.7  277.54  3750.7  279.27  3821.5  282.79  3948.8  280.07
  4005.3  281.59  4238.7  293.14  4321.7  293.76  4351.9  291.35    4373  287.59
  4408.4  276.03  4415.5  271.65  4424.3  269.99  4468.8  257.13  4535.7   246.4
  4627.6  236.43  4739.9  232.13    4960  229.82  4992.3  226.74  4995.1  226.24
  4998.3  226.74  5016.6  228.26  5023.6   232.3  5051.9  235.37  5235.7  258.92
  5306.4   273.4  5358.7  278.02  5426.7  273.26  5476.2  273.68  5490.3  275.32
#Mann= 7 ,-1 , 0
  3720.6     .16       0  4424.3      .1       0  4468.8     .16       0
  4739.9     .12       0  4992.3     .07       0  4998.3     .12       0
  5358.7     .16       0
Bank Sta=4627.6,5051.9
XS Rating Curve= 0 ,0
Exp/Cntr=0.3,0.1

Type RM Length L Ch R = 1 ,8173    ,606,606,606
BEGIN DESCRIPTION:
EDWARDS CREEK 12.0
END DESCRIPTION:
XS GIS Cut Line= 3
      3648898.88     10636248.48      3650250.69     10636325.76
      3651433.02     10636737.23
#Sta/Elev= 30
  3125.9  321.83  3176.7  318.96  3242.6  310.91    3377  303.07  3447.2   301.5
  3598.1  303.04  3792.5   282.8  4061.2  253.72  4224.3  241.07  4308.6  237.47
  4338.6  239.64  4358.6  237.63  4378.7  231.36  4408.7  238.15  4438.8  238.98
  4506.9  235.77  4693.5  233.59    4944  229.63  4976.4  228.66  4990.9  225.39
  4993.6  224.89  4996.9  225.39  5030.2  229.61  5124.7  234.11  5237.3  245.43
  5273.7  246.86  5299.5  251.01  5388.6  256.67  5590.5  275.29  5731.8  293.55
#Mann= 8 ,-1 , 0
  3125.9     .05       0  3792.5     .16       0  4061.2     .12       0
  4224.3     .16       0    4944     .12       0  4990.9     .07       0
  4996.9     .12       0  5388.6     .16       0
Bank Sta=4693.5,5124.7
XS Rating Curve= 0 ,0
Exp/Cntr=0.3,0.1

Type RM Length L Ch R = 1 ,7567    ,376,376,376
BEGIN DESCRIPTION:
EDWARDS CREEK 11.0
END DESCRIPTION:
XS GIS Cut Line= 2
      3649813.14     10636830.96      3651453.81     10636883.05
#Sta/Elev= 30
  4082.8  280.29  4139.3   273.3  4252.7  263.28  4359.4  253.41  4379.4  253.05
  4466.9  246.75    4571  238.85  4619.5   234.4  4669.9  232.11  4850.5  232.13
  4909.7  230.58  4969.7  231.35  4979.7  227.98  4996.7  225.15  4999.5  224.65
  5002.7  225.15  5019.7  227.74  5069.8  230.08  5109.8  226.53  5149.8  230.78
  5163.1  230.61  5229.8  235.28  5377.2  252.46    5470  263.96    5530  275.72
    5560   279.2    5630  294.69  5670.1  301.64  5700.1  305.38  5724.3   305.8
#Mann= 8 ,-1 , 0
  4082.8     .05       0  4252.7     .16       0  4466.9     .12       0
    4571     .16       0  4669.9     .12       0  4996.7     .07       0
  5002.7     .12       0  5377.2     .16       0
Bank Sta=4619.5,5229.8
XS Rating Curve= 0 ,0
Exp/Cntr=0.3,0.1

Type RM Length L Ch R = 1 ,7191    ,445,445,445
BEGIN DESCRIPTION:
EDWARDS CREEK 10.0
END DESCRIPTION:
XS GIS Cut Line= 3
      3649110.02     10636867.41      3650000.69     10637221.59
      3651500.71       10637107.
#Sta/Elev= 30
  3138.7  320.39  3471.9  318.69  3604.8   315.5  3888.3  298.79  3956.1  300.76
  3977.7  297.46  4001.6  297.03  4116.2  283.37    4253   261.7  4312.1  250.94
  4384.7  243.69  4437.1  235.92  4484.2  232.16  4487.3  232.04  4527.4  229.97
  4664.9  229.68  4778.1  231.47  4971.3  229.66  4988.7   224.2  4995.7   224.1
  4998.5   223.6  5001.7   224.1  5008.8  226.22  5038.9  226.71    5089  232.11
    5233  248.62  5379.9  275.64    5430  287.85  5510.2  303.43  5601.6  306.08
#Mann= 10 ,-1 , 0
  3138.7     .05       0  3604.8     .16       0    4253     .12       0
  4384.7     .16       0  4484.2     .12       0  4527.4     .05       0
  4664.9     .12       0  4995.7     .07       0  5001.7     .12       0
  5379.9     .16       0
Bank Sta=4487.3,5089
XS Rating Curve= 0 ,0
Exp/Cntr=0.3,0.1

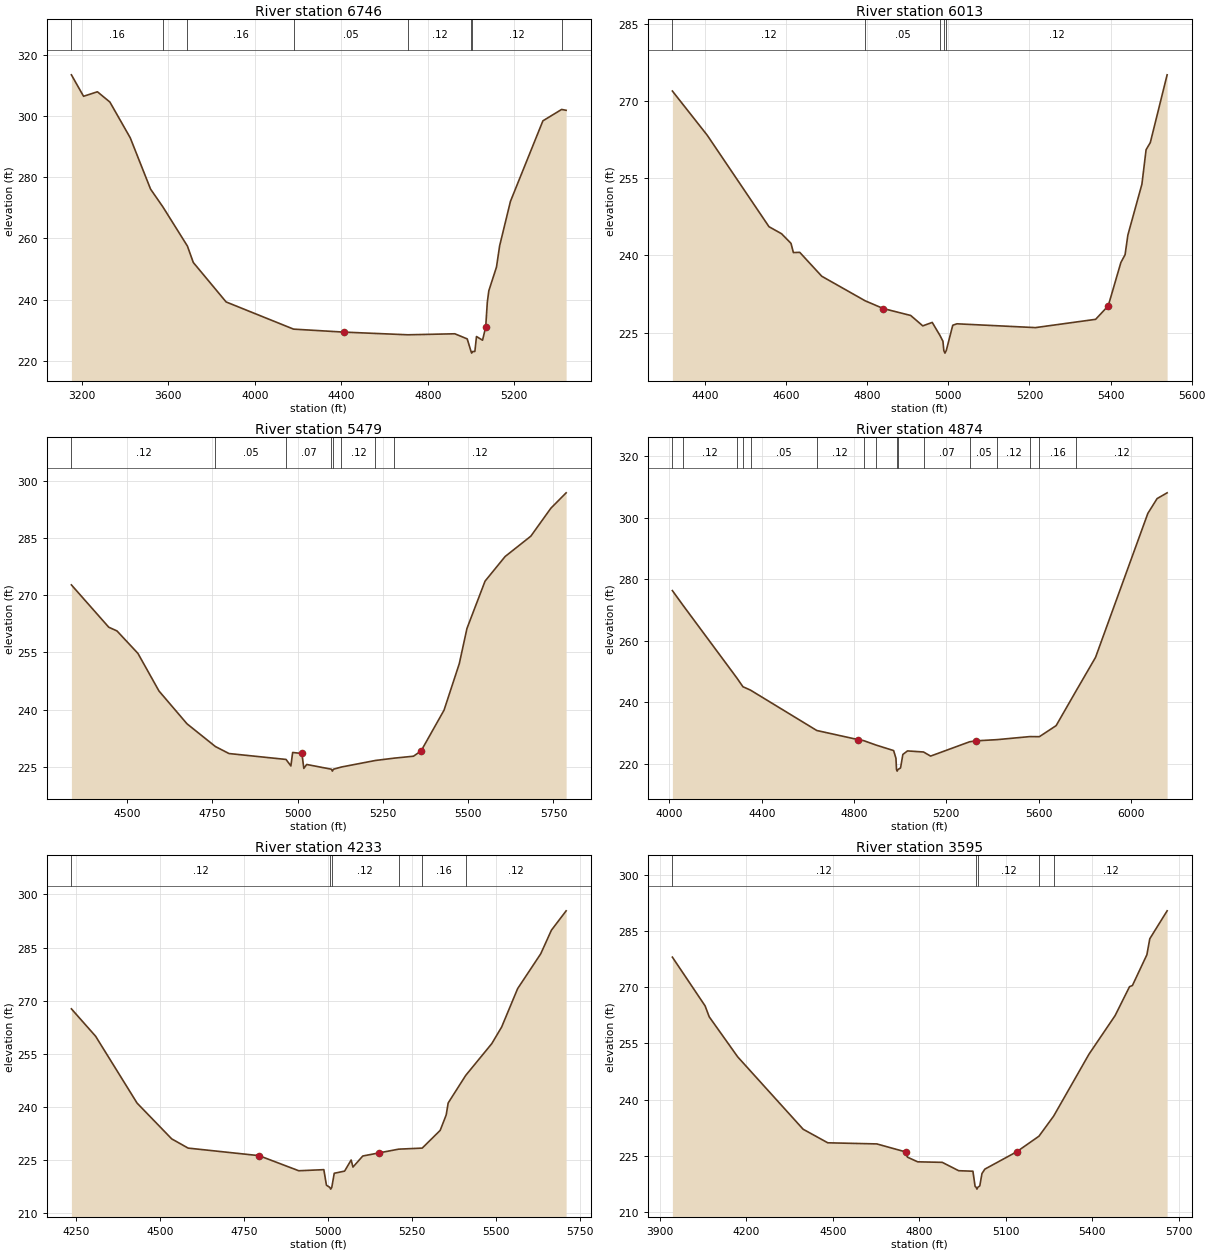
Type RM Length L Ch R = 1 ,6746    ,733,733,733
BEGIN DESCRIPTION:
EDWARDS CREEK 9.0
END DESCRIPTION:
XS GIS Cut Line= 3
      3650130.89     10638997.63      3651057.98     10637534.09
      3651500.66     10637200.78
#Sta/Elev= 30
  3152.7  313.41  3208.9   306.4  3272.9  307.87  3330.5  304.52  3424.6  292.84
  3518.6  276.07  3575.7  270.24  3688.9  257.46  3716.1   252.1  3867.8   239.2
  4179.5  230.32    4411  229.35  4707.9  228.47  4924.8   228.8  4982.1  227.13
  4999.9  222.98  5002.7  222.48  5005.9  222.98  5017.5  223.03  5024.9  227.91
  5052.9   226.7  5067.5  230.99    5075  239.13    5082  242.87  5117.4  250.61
    5132  257.58    5182  272.09  5331.9  298.38  5418.5   302.1  5439.3  301.82
#Mann= 8 ,-1 , 0
  3152.7     .16       0  3575.7     .05       0  3688.9     .16       0
  4179.5     .05       0  4707.9     .12       0  4999.9     .07       0
  5005.9     .12       0  5418.5     .16       0
Bank Sta=4411,5067.5
XS Rating Curve= 0 ,0
Exp/Cntr=0.3,0.1

Type RM Length L Ch R = 1 ,6013    ,534,534,534
BEGIN DESCRIPTION:
EDWARDS CREEK 8.0
END DESCRIPTION:
XS GIS Cut Line= 3
      3651599.59     10638660.15      3651349.61     10638060.19
      3651499.62     10637510.14
#Sta/Elev= 30
  4319.4  271.96  4405.5  263.35  4557.7  245.58  4588.6  244.22  4611.9  242.35
  4617.8  240.56  4633.5   240.6  4687.7  235.96  4794.6  231.19  4839.4  229.68
  4907.1  228.33  4936.9  226.31  4960.2  226.98  4979.3  224.44  4986.6  223.32
  4988.8  221.51  4991.6  221.01  4994.8  221.51  5010.8  226.43  5021.2  226.71
  5214.7  225.97  5363.2  227.58  5394.3  230.21  5425.4  238.62  5435.8  240.15
  5442.7  243.97  5477.3  253.85  5487.6  260.55    5498  261.94  5539.5  275.11
#Mann= 5 ,-1 , 0
  4319.4     .12       0  4794.6     .05       0  4979.3     .12       0
  4988.8     .07       0  4994.8     .12       0
Bank Sta=4839.4,5394.3
XS Rating Curve= 0 ,0
Exp/Cntr=0.3,0.1

Type RM Length L Ch R = 1 ,5479    ,605,605,605
BEGIN DESCRIPTION:
EDWARDS CREEK 7.0
END DESCRIPTION:
XS GIS Cut Line= 3
       3651649.6     10638660.23      3651799.61     10638010.19
      3651449.59     10637310.14
#Sta/Elev= 30
  4337.3  272.74  4446.8  261.62  4470.8  260.65  4532.3  254.74  4593.9  244.87
    4676  236.25  4759.3  230.27  4799.2  228.43  4966.3  226.88  4980.5  225.17
  4985.6  228.71  5012.8  228.45  5018.4  224.53  5026.8  225.56  5099.3  224.31
    5102  223.81  5105.3  224.31  5128.5  224.89  5228.2  226.61  5283.2  227.22
  5339.8  227.73  5362.2  229.14  5429.3  239.83    5474  252.05  5496.4  261.28
  5549.5  273.73  5608.2  280.19  5683.6  285.54  5742.3  292.88  5787.1  296.93
#Mann= 8 ,-1 , 0
  4337.3     .12       0  4759.3     .05       0  4966.3     .07       0
  5099.3     .07       0  5105.3     .07       0  5128.5     .12       0
  5228.2     .05       0  5283.2     .12       0
Bank Sta=5012.8,5362.2
XS Rating Curve= 0 ,0
Exp/Cntr=0.3,0.1

Type RM Length L Ch R = 1 ,4874    ,641,641,641
BEGIN DESCRIPTION:
EDWARDS CREEK 6.0
END DESCRIPTION:
XS GIS Cut Line= 2
      3652177.77     10639117.42      3652302.77     10636976.77
#Sta/Elev= 30
  4012.9  276.29  4059.6  271.46    4292  247.97  4318.7  245.09  4351.5  243.99
  4638.7  230.89  4816.4  227.95  4842.3  227.59  4895.6  226.16  4971.8  224.37
  4981.8  221.88  4984.3   218.2  4987.1   217.7  4990.3   218.2  5001.8  218.74
  5011.8  223.11  5031.9  224.26  5101.5  223.91    5132  222.58  5300.9  227.22
  5329.2  227.53  5420.3  227.92  5562.1  228.91  5603.5  228.88    5676  232.46
  5762.2  243.69  5846.9  254.62  6073.6  301.36  6113.7  306.16  6157.2  308.03
#Mann= 16 ,-1 , 0
  4012.9     .05       0  4059.6     .12       0    4292     .16       0
  4318.7     .12       0  4351.5     .05       0  4638.7     .12       0
  4842.3     .05       0  4895.6     .12       0  4984.3     .07       0
  4990.3     .12       0  5101.5     .07       0  5300.9     .05       0
  5420.3     .12       0  5562.1     .05       0  5603.5     .16       0
  5762.2     .12       0
Bank Sta=4816.4,5329.2
XS Rating Curve= 0 ,0
Exp/Cntr=0.3,0.1

Type RM Length L Ch R = 1 ,4233    ,638,638,638
BEGIN DESCRIPTION:
EDWARDS CREEK 5.0
END DESCRIPTION:
XS GIS Cut Line= 3
      3652599.62     10638860.16      3652799.61     10638060.19
      3653049.61     10637460.18
#Sta/Elev= 30
    4235  267.69  4307.1  259.96  4430.8  241.06  4533.9  230.96  4582.9  228.35
  4794.2  226.22  4912.7  221.95  4987.4  222.26  4995.2  217.86  5005.1  217.26
  5007.8  216.76  5011.1  217.26  5018.4  221.24  5049.3  221.85  5068.8  224.99
  5074.2  222.99  5103.5  226.12  5151.1  226.98  5210.2  228.05  5280.6  228.35
  5334.2  233.36  5352.1  237.72    5358   241.1  5410.1  248.86    5488  257.87
  5517.3  262.54    5565   273.4  5633.8  283.23  5665.7  289.91  5709.6  295.38
#Mann= 6 ,-1 , 0
    4235     .12       0  5005.1     .07       0  5011.1     .12       0
  5210.2     .07       0  5280.6     .16       0  5410.1     .12       0
Bank Sta=4794.2,5151.1
XS Rating Curve= 0 ,0
Exp/Cntr=0.3,0.1

Type RM Length L Ch R = 1 ,3595    ,627,627,627
BEGIN DESCRIPTION:
EDWARDS CREEK 4.0
END DESCRIPTION:
XS GIS Cut Line= 3
       3652599.6      10638960.2      3653299.61     10638160.19
      3653349.61     10637510.24
#Sta/Elev= 30
  3944.3  278.05  4057.7  265.04    4072  262.12  4170.7  251.43  4397.5  232.11
  4482.9  228.49  4652.8  228.19  4752.5  226.06  4759.1  224.65  4794.7  223.41
  4879.7  223.27  4936.6  221.04    4986   220.9  4993.6  216.83  4997.2  216.62
    5000  216.12  5003.2  216.62  5009.8  216.98  5017.4  220.29  5027.4  221.46
  5137.7  226.09  5214.9  230.25  5265.8  235.61  5388.5  252.17  5478.7  262.43
  5528.9  270.17  5538.9  270.49    5589  278.69  5599.1  282.97  5659.2  290.42
#Mann= 5 ,-1 , 0
  3944.3     .12       0  4997.2     .07       0  5003.2     .12       0
  5214.9     .16       0  5265.8     .12       0
Bank Sta=4752.5,5137.7
XS Rating Curve= 0 ,0
Exp/Cntr=0.3,0.1

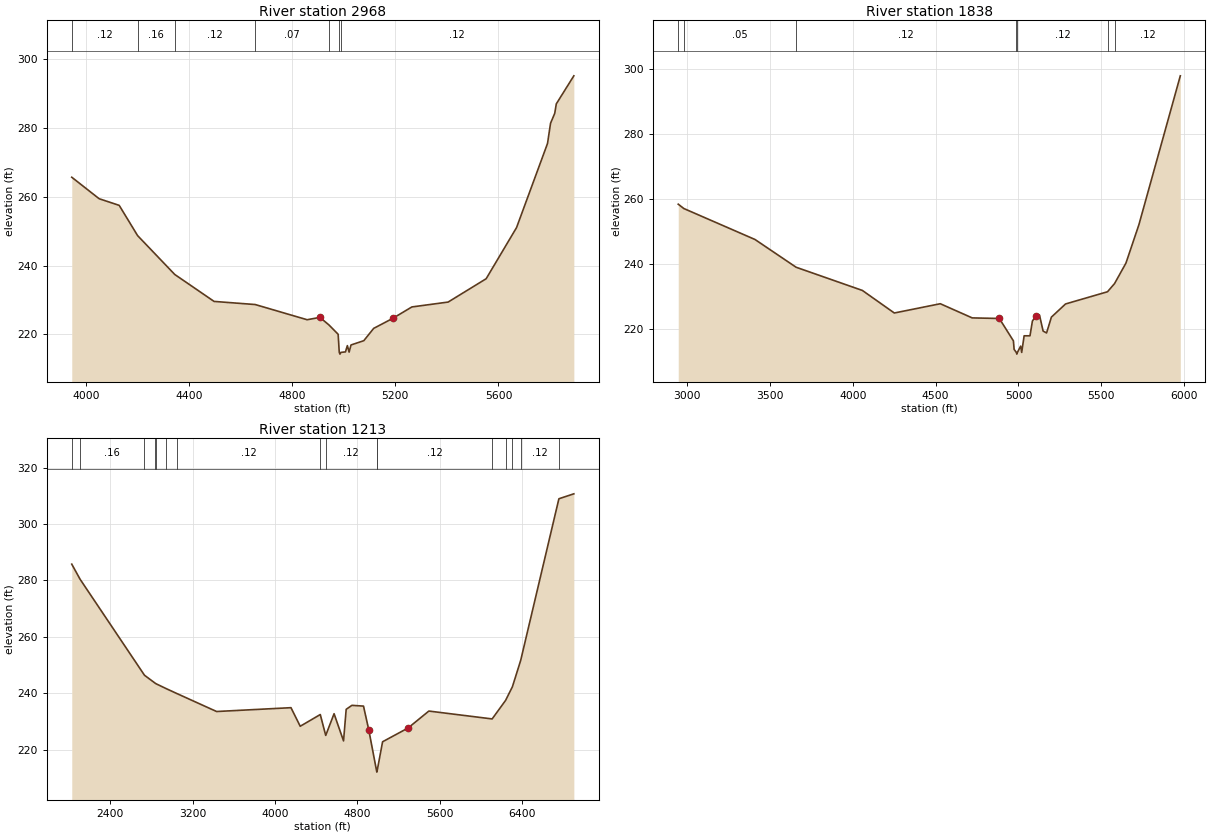
Type RM Length L Ch R = 1 ,2968    ,1130,1130,1130
BEGIN DESCRIPTION:
EDWARDS CREEK 3.0
END DESCRIPTION:
XS GIS Cut Line= 3
      3653049.63     10639060.17      3653799.61     10638260.19
      3653399.59     10637510.15
#Sta/Elev= 30
  3945.6   265.7  4051.8  259.45  4129.5  257.52  4200.9  248.72  4344.8  237.43
  4497.3  229.59  4656.8  228.68  4858.2  224.26  4907.6  224.95  4942.8  222.74
  4978.4  220.03  4982.7  214.76  4985.5  214.26  4988.7  214.76  5006.7  214.91
  5014.1  216.73  5020.9  214.85  5028.2  216.92  5077.9  218.17  5116.2  221.75
  5189.5  224.63  5264.2  227.98  5404.8   229.4  5552.2  236.18  5670.1  251.06
  5790.2  275.53  5801.8  281.38  5818.1  284.28  5824.2  287.03  5892.2  295.19
#Mann= 7 ,-1 , 0
  3945.6     .12       0  4200.9     .16       0  4344.8     .12       0
  4656.8     .07       0  4942.8     .12       0  4982.7     .07       0
  4988.7     .12       0
Bank Sta=4907.6,5189.5
XS Rating Curve= 0 ,0
Exp/Cntr=0.3,0.1

Type RM Length L Ch R = 1 ,1838    ,625,625,625
BEGIN DESCRIPTION:
EDWARDS CREEK 2.0
END DESCRIPTION:
XS GIS Cut Line= 3
      3653049.61     10639360.19      3654649.61     10638110.19
      3654049.61     10637310.19
#Sta/Elev= 30
  2946.6  258.27  2980.6  256.93  3409.7  247.41  3658.2  238.86  4058.1  231.72
  4250.8  224.78  4528.4  227.63    4721  223.27  4884.7  223.09  4969.8  216.19
  4973.8  213.59  4987.5  212.62  4990.3  212.12  4993.5  212.62  5013.5  214.59
  5019.7  212.65  5034.3  217.76  5069.7  217.76  5084.3  222.29  5105.1  223.88
    5127  224.15  5148.9  219.22  5169.7  218.64  5198.9  223.51  5284.3  227.56
  5537.7  231.32  5580.3  233.85  5648.9  240.14    5727  251.94    5977  297.78
#Mann= 7 ,-1 , 0
  2946.6     .16       0  2980.6     .05       0  3658.2     .12       0
  4987.5     .07       0  4993.5     .12       0  5537.7     .16       0
  5580.3     .12       0
Bank Sta=4884.7,5105.1
XS Rating Curve= 0 ,0
Exp/Cntr=0.3,0.1

Type RM Length L Ch R = 1 ,1213    ,0,0,0
BEGIN DESCRIPTION:
EDWARDS CREEK 1.0
END DESCRIPTION:
XS GIS Cut Line= 4
      3652488.56      10639669.5      3654828.81     10638988.95
      3655037.15     10637968.12      3654245.48     10636815.35
#Sta/Elev= 30
  2027.1  285.77  2108.3   280.4  2733.5  246.37  2837.7  243.54  2847.5  243.32
    2942  241.66  3046.2  239.91  3434.1   233.5  4156.7  234.86  4246.4  228.27
  4441.3  232.43  4494.2  225.02  4575.3  232.72  4667.2  223.08    4693  234.28
  4748.8  235.69  4861.1  235.42  4912.1  227.05    4988   212.5  4990.8     212
    4994   212.5  5046.6  222.77  5294.1  227.65  5496.2  233.66  6110.9  230.87
  6241.8  237.46  6307.6  242.26  6388.4  251.66  6759.4  308.97  6904.6  310.72
#Mann= 16 ,-1 , 0
  2027.1     .12       0  2108.3     .16       0  2733.5     .05       0
  2837.7     .16       0  2847.5     .05       0    2942     .16       0
  3046.2     .12       0  4441.3     .05       0  4494.2     .12       0
    4988     .07       0    4994     .12       0  6110.9     .16       0
  6241.8     .12       0  6307.6     .16       0  6388.4     .12       0
  6759.4     .05       0
Bank Sta=4912.1,5294.1
XS Rating Curve= 0 ,0
Exp/Cntr=0.3,0.1

Chan Stop Cuts=-1
Use User Specified Reach Order=0
Composite Channel Slope=5