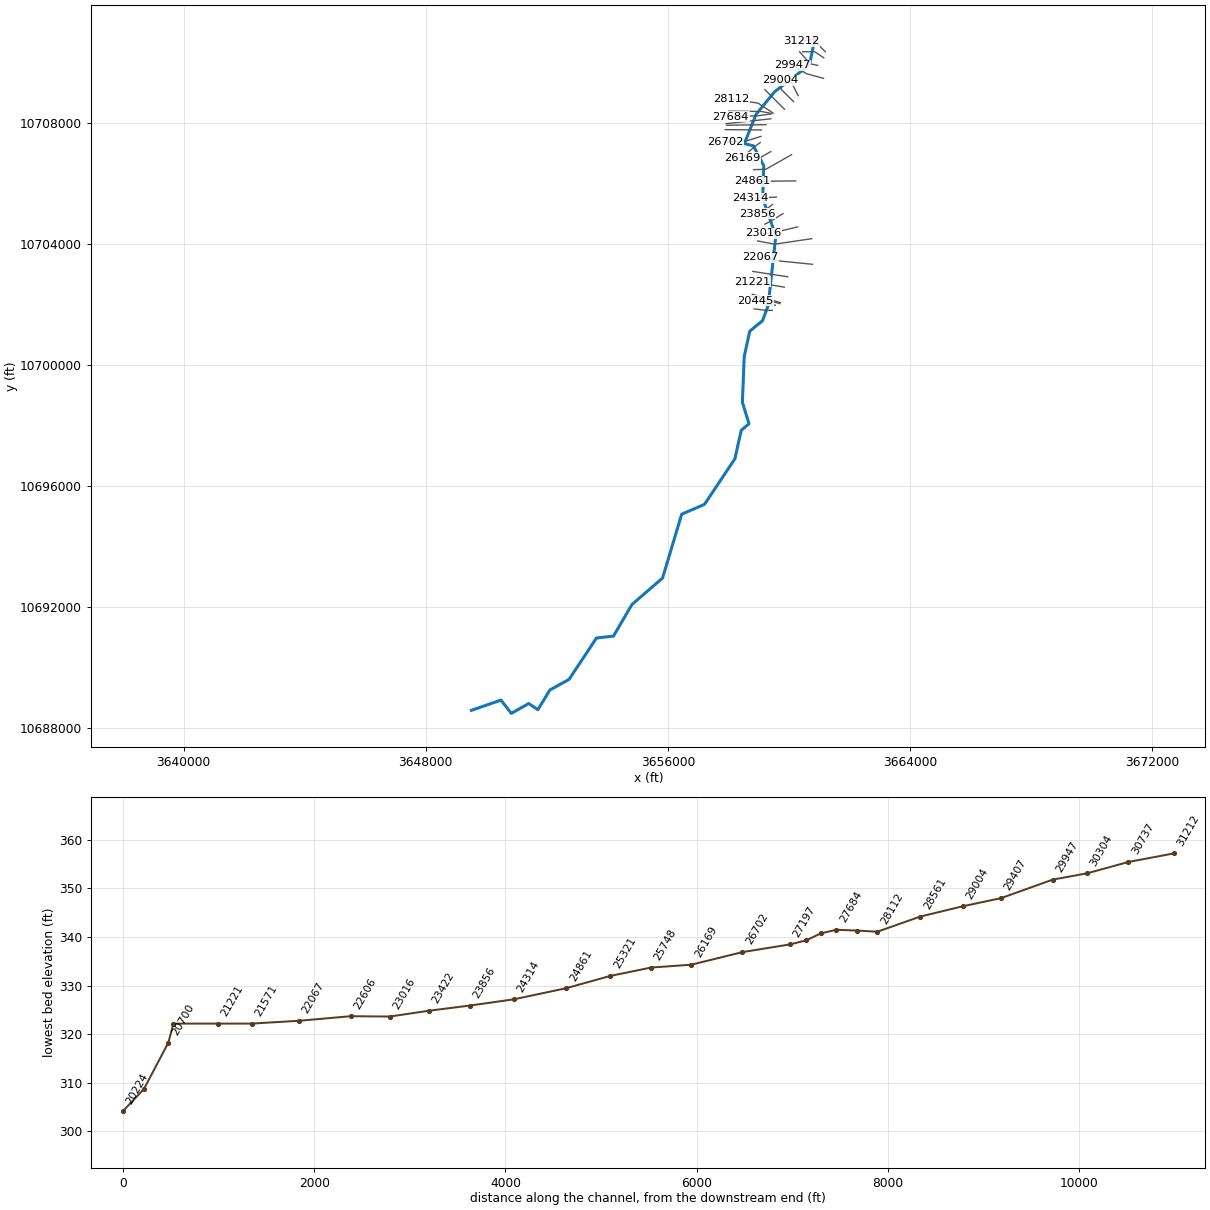
--- HALL BRANCH.prj (project) ---

Proj Title=HALL BRANCH Base Level Engineering
Current Plan=p01
Default Exp/Contr=0.3,0.1
English Units
Geom File=g01
Flow File=f01
Plan File=p01
Y Axis Title=Elevation
X Axis Title(PF)=Main Channel Distance
X Axis Title(XS)=Station
BEGIN DESCRIPTION:
HALL BRANCH
END DESCRIPTION:
DSS File=dss
DSS Export Rating Curves= 0
DSS Export Rating Curve Sorted= 0
DSS Export Volume Flow Curves= 0
DXF OffsetX= 0
DXF OffsetY= 0
DXF ScaleX= 1
DXF ScaleY= 10

--- HALL BRANCH.p01 (plan) ---

Plan Title=Multiple Run
Program Version=4.10
Short Identifier=Multiple Run
Geom File=g01
Flow File=f01
Subcritical Flow
K Sum by GR= 0
Std Step Tol= 0.01
Critical Tol= 0.01
Num of Std Step Trials= 20
Max Error Tol= 0.3
Flow Tol Ratio= 0.001
Split Flow NTrial= 30
Split Flow Tol= 0.02
Split Flow Ratio= 0.02
Log Output Level= 0
Friction Slope Method= 1
Unsteady Friction Slope Method= 2
Unsteady Bridges Friction Slope Method= 1
Parabolic Critical Depth
Global Vel Dist= 1 , 1 , 1
Global Log Level= 0
CheckData=True
Encroach Param=-1 ,0,0, 0
BEGIN DESCRIPTION:
Multiple Run
END DESCRIPTION:
Computation Interval=1HOUR
Output Interval=1HOUR
Run HTab= 0
Run UNet= 0
Run PostProcess= 0
Run WQNet= 0
UNET Theta= 1
UNET Theta Warmup= 1
UNET ZTol= 0.02
UNET ZSATol= 0.05
UNET MxIter= 20
UNET MaxInSteps= 0
UNET DtIC= 0
UNET DtMin= 0
UNET MaxCRTS= 20
UNET WFStab= 2
UNET SFStab= 1
UNET WFX= 1
UNET SFX= 1
UNET DSS MLevel= 4
UNET DZMax Abort= 100
UNET Convert EG Bridges= 0
UNET Use Existing IB Tables=-1
UNET Froude Reduction=False
UNET Froude Limit= 1
UNET Froude Power= 10
UNET Time Slicing=0,0, 5
UNET Junction Losses=0
Instantaneous Interval=1HOUR
DSS File=dss
Write IC File= 0
Write IC File at Sim End=0
Echo Input=False
Echo Parameters=False
Echo Output=False
Write Detailed= 0
WQ AD Non Conservative
WQ ULTIMATE=-1
WQ Max Comp Step=1HOUR
WQ Output Interval=15MIN
WQ Output Selected Increments= 0
WQ Output face flow=0
WQ Output face velocity=0
WQ Output face area=0
WQ Output face dispersion=0
WQ Output cell volume=0
WQ Output cell surface area=0
WQ Output cell continuity=0
WQ Output cumulative cell continuity=0
WQ Output face conc=0
WQ Output face dconc_dx=0
WQ Output face courant=0
WQ Output face peclet=0
WQ Output face adv mass=0
WQ Output face disp mass=0
WQ Output cell mass=0
WQ Output cell source sink temp=0
WQ Output cell source sink nsm=0
WQ Output MaxMinRange=-1
WQ Daily Max Min Mean=-1
WQ Daily Range=0
WQ Daily Time=0
WQ Create Restart=0
WQ Fixed Restart=0
WQ System Summary=0
WQ Use Fixed Temperature=0
Sorting and Armoring Iterations= 10
XS Update Threshold= 0.02
Hydraulics Update Threshold= 0.02
Energy Slope Method= 1
Volume Change Method= 0
XS Weighting Method= 0
Number of US Weighted Cross Sections= 1
Number of DS Weighted Cross Sections= 1
Upstream XS Weight=0.25
Main XS Weight=0.5
Downstream XS Weight=0.25
Number of DS XS's Weighted with US Boundary= 1
Upstream Boundary Weight= 1
Weight of XSs Associated with US Boundary= 0
Number of US XS's Weighted with DS Boundary= 1
Downstream Boundary Weight= 0.5
Weight of XSs Associated with DS Boundary= 0.5
Sediment Output Level= 4
Mass or Volume Output= 0
Output Increment Type= 1
Profile and TS Output Increment= 10
XS Output Flag= 0
XS Output Increment= 10
Disregard all LS=0
Disregard all Conn=0
Disregard all Breaches=0
Disregard all Pumps=0

--- HALL BRANCH.f01 (steady flow) ---

Flow Title=Multiple
Program Version=4.10
Number of Profiles= 7
Profile Names=10-year,25-year,50-year,1pct_min,100-year,1pct_plu,500-year
River Rch & RM=HALL BRANCH,Reach-1         ,31212
    1091    1552    1951    1800    2435    3292    3810
River Rch & RM=HALL BRANCH,Reach-1         ,28112
    1275    1818    2288    2111    2855    3861    4470
River Rch & RM=HALL BRANCH,Reach-1         ,22067
    1448    2073    2616    2419    3272    4425    5146
River Rch & RM=HALL BRANCH,Reach-1         ,19294
    1700    2446    3096    2871    3882    5250    6138
River Rch & RM=HALL BRANCH,Reach-1         ,15037
    1911    2760    3504    3256    4403    5955    6994
River Rch & RM=HALL BRANCH,Reach-1         ,13760
    2043    2956    3756    3493    4724    6389    7515
River Rch & RM=HALL BRANCH,Reach-1         ,7636
    2046    2949    3737    3465    4687    6338    7412
River Rch & RM=HALL BRANCH,Reach-1         ,345
    2613    3805    4854    4529    6124    8283    9804
Boundary for River Rch & Prof#=HALL BRANCH,Reach-1         , 1
Up Type= 0
Dn Type= 3
Dn Slope=0.001
Boundary for River Rch & Prof#=HALL BRANCH,Reach-1         , 2
Up Type= 0
Dn Type= 3
Dn Slope=0.001
Boundary for River Rch & Prof#=HALL BRANCH,Reach-1         , 3
Up Type= 0
Dn Type= 3
Dn Slope=0.001
Boundary for River Rch & Prof#=HALL BRANCH,Reach-1         , 4
Up Type= 0
Dn Type= 3
Dn Slope=0.001
Boundary for River Rch & Prof#=HALL BRANCH,Reach-1         , 5
Up Type= 0
Dn Type= 3
Dn Slope=0.001
Boundary for River Rch & Prof#=HALL BRANCH,Reach-1         , 6
Up Type= 0
Dn Type= 3
Dn Slope=0.001
Boundary for River Rch & Prof#=HALL BRANCH,Reach-1         , 7
Up Type= 0
Dn Type= 3
Dn Slope=0.001
DSS Import GetInterval= 0
DSS Import GetPeak= 0
DSS Import FillOption= 0

--- HALL BRANCH.g01 (geometry) ---

Geom Title=Existing Conditions
Program Version=4.10

River Reach=HALL BRANCH     ,Reach-1
Reach XY= 30
      3660854.35      10710803.2      3660676.75       10709922.
      3659528.75       10709041.        3658914.       10708294.
      3658524.75       10707324.        3658827.       10707249.
      3659165.75       10706590.      3659131.25       10705526.
       3659563.5       10704270.        3659311.       10701970.
        3659124.       10701468.      3658703.25       10701123.
        3658521.       10700286.      3658459.75       10698775.
        3658679.       10698063.       3658422.5       10697849.
      3658211.75       10696906.      3657206.25       10695398.
       3656454.5       10695073.      3655822.75       10692963.
        3654812.       10692089.       3654202.5       10691045.
      3653639.25       10690981.      3652735.25       10689614.
      3652099.25       10689261.      3651705.75       10688612.
       3651401.5       10688816.      3650827.25       10688490.
       3650485.5       10688929.      3649507.56     10688589.91

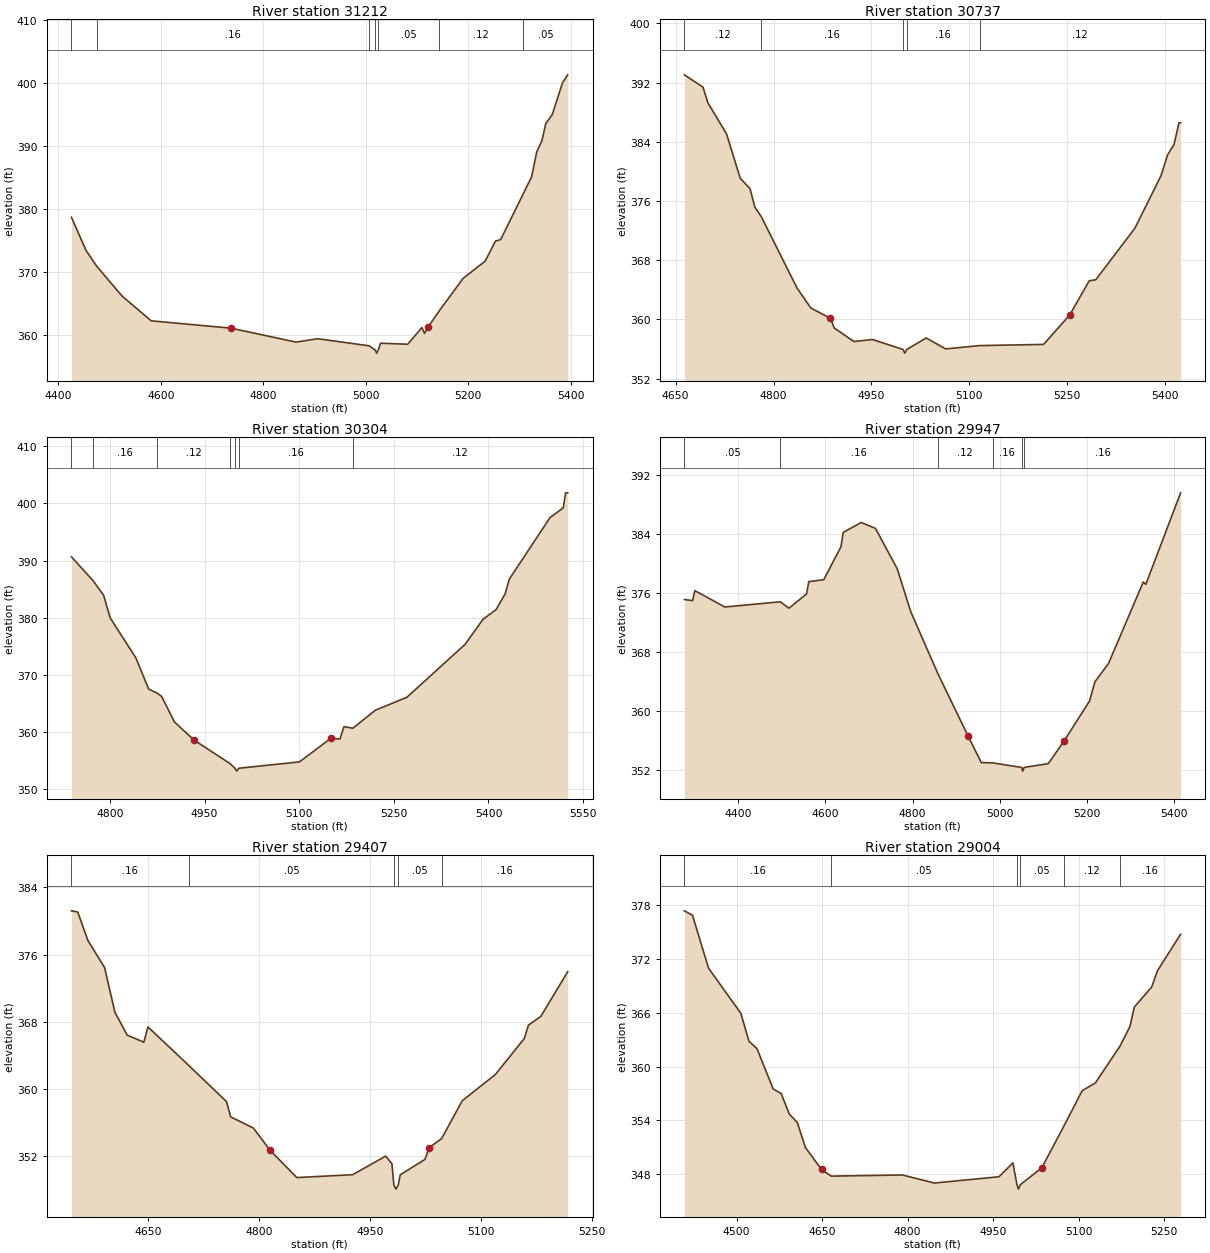
Type RM Length L Ch R = 1 ,31212   ,475,475,475
BEGIN DESCRIPTION:
HALL BRANCH 67.0
END DESCRIPTION:
XS GIS Cut Line= 3
      3661199.63     10710360.17      3660799.61     10710760.19
      3660399.64     10710710.19
#Sta/Elev= 30
  4425.6  378.74  4453.9  373.49  4474.9  370.97  4524.6  366.23  4581.2  362.32
  4736.8  361.16    4864  358.95  4906.5  359.48  5006.6  358.36  5018.5   357.7
  5021.3   357.2  5024.5   357.7  5029.1  358.77    5082  358.61  5109.7  361.25
  5114.8  360.33  5122.3  361.39  5143.9  363.94  5190.4  369.07  5233.2  371.78
  5253.3  374.96  5263.4  375.19  5307.6  382.46  5323.9  385.15    5334  389.12
    5344  390.87  5351.6  393.59  5364.2  395.02  5384.3  400.07  5394.4  401.32
#Mann= 7 ,-1 , 0
  4425.6     .12       0  4474.9     .16       0  5006.6     .05       0
  5018.5     .07       0  5024.5     .05       0  5143.9     .12       0
  5307.6     .05       0
Bank Sta=4736.8,5122.3
XS Rating Curve= 0 ,0
Exp/Cntr=0.3,0.1

Type RM Length L Ch R = 1 ,30737   ,433,433,433
BEGIN DESCRIPTION:
HALL BRANCH 66.0
END DESCRIPTION:
XS GIS Cut Line= 3
      3661149.58     10710160.21      3660849.61     10710360.19
      3660449.63     10710360.19
#Sta/Elev= 30
  4663.4  393.06  4691.9   391.4  4699.4  389.29    4728  385.08    4749  379.09
    4764  377.67  4771.5  375.16  4781.1  373.92  4836.1  364.23  4857.2  361.54
  4887.2  360.15  4893.2  358.83  4923.3  357.01  4951.8  357.28  4998.4  355.94
  5001.1  355.44  5004.4  355.94  5033.9  357.49  5063.9  356.01  5116.2  356.46
  5213.9  356.62  5253.9  360.59  5283.9  365.22  5293.9  365.36  5353.9  372.33
  5393.9  379.43  5403.9  382.23  5413.9  383.66  5421.4  386.59  5423.9  386.59
#Mann= 5 ,-1 , 0
  4663.4     .12       0  4781.1     .16       0  4998.4     .07       0
  5004.4     .16       0  5116.2     .12       0
Bank Sta=4887.2,5253.9
XS Rating Curve= 0 ,0
Exp/Cntr=0.3,0.1

Type RM Length L Ch R = 1 ,30304   ,357,357,357
BEGIN DESCRIPTION:
HALL BRANCH 65.0
END DESCRIPTION:
XS GIS Cut Line= 3
      3660949.65     10709910.18      3660699.61     10709960.19
      3660349.61     10710360.19
#Sta/Elev= 30
  4739.1  390.64  4773.3  386.48  4790.1  383.92  4800.3  379.98  4841.1  372.96
  4861.5  367.47  4873.9  366.82  4881.9  366.21  4902.3  361.72  4932.9  358.58
  4991.1  354.37  4998.2   353.6    5001   353.1  5004.2   353.6  5100.4  354.72
  5150.2  358.85  5164.5  358.73  5171.1   360.9    5185  360.61  5220.5  363.76
  5270.8  366.05  5362.8   375.3  5391.3  379.69  5412.2  381.42  5426.4  384.16
  5433.1  386.76  5497.6  397.53  5518.5  399.24  5522.3  401.87  5525.6  401.87
#Mann= 7 ,-1 , 0
  4739.1     .12       0  4773.3     .16       0  4873.9     .12       0
  4991.1     .16       0  4998.2     .07       0  5004.2     .16       0
    5185     .12       0
Bank Sta=4932.9,5150.2
XS Rating Curve= 0 ,0
Exp/Cntr=0.3,0.1

Type RM Length L Ch R = 1 ,29947   ,540,540,540
BEGIN DESCRIPTION:
HALL BRANCH 64.0
END DESCRIPTION:
XS GIS Cut Line= 3
      3661141.32     10709479.74      3660578.51     10709634.41
      3660099.63     10709918.12
#Sta/Elev= 30
  4275.7  375.09  4294.7  374.94  4299.8  376.29  4368.7  374.07  4496.2  374.78
    4516  373.91  4556.4  375.84  4561.6  377.51    4596  377.77  4635.6  382.25
  4640.8  384.18  4681.9  385.53  4714.8  384.73  4764.9  379.25    4796  373.42
  4857.8  365.09  4927.8  356.55    4958  352.98  4984.4  352.94  5050.5  352.32
  5053.2  351.82  5056.5  352.32    5112  352.84  5148.7  355.95  5206.8  361.33
  5219.1  363.93  5250.4  366.42  5330.3  377.47  5336.1  377.14    5416  389.55
#Mann= 6 ,-1 , 0
  4275.7     .05       0  4496.2     .16       0  4857.8     .12       0
  4984.4     .16       0  5050.5     .07       0  5056.5     .16       0
Bank Sta=4927.8,5148.7
XS Rating Curve= 0 ,0
Exp/Cntr=0.3,0.1

Type RM Length L Ch R = 1 ,29407   ,403,403,403
BEGIN DESCRIPTION:
HALL BRANCH 63.0
END DESCRIPTION:
XS GIS Cut Line= 3
       3660299.6     10708910.21      3660099.61     10709310.19
      3659999.61      10709510.2
#Sta/Elev= 30
  4546.8  381.21  4555.2  381.08  4569.1  377.65  4591.5  374.46  4605.5  369.12
  4622.2  366.38  4644.6  365.54  4650.2  367.36  4705.5  362.75  4756.4  358.45
    4762  356.63  4792.7   355.3  4815.1  352.66  4851.4  349.39  4926.9  349.73
  4971.6  351.95    4980  351.03  4982.6  348.51  4985.3  348.01  4988.6  348.51
  4991.2  349.72  5024.7  351.56  5030.3  352.96  5047.1  354.03    5075  358.55
  5119.8  361.68  5158.9  365.98  5164.5  367.57  5181.3  368.62  5217.6  373.95
#Mann= 5 ,-1 , 0
  4546.8     .16       0  4705.5     .05       0  4982.6     .03       0
  4988.6     .05       0  5047.1     .16       0
Bank Sta=4815.1,5030.3
XS Rating Curve= 0 ,0
Exp/Cntr=0.3,0.1

Type RM Length L Ch R = 1 ,29004   ,443,443,443
BEGIN DESCRIPTION:
HALL BRANCH 62.0
END DESCRIPTION:
XS GIS Cut Line= 3
      3660149.63     10708710.16      3659749.61     10709110.19
       3659699.6     10709410.23
#Sta/Elev= 30
  4408.6  377.37  4422.8  376.88  4451.1  370.96  4507.6  365.94  4521.8  362.82
  4535.9     362  4564.2   357.5  4578.3  356.99  4592.5   354.7  4606.6  353.75
  4620.8  350.97  4649.1  348.51    4666  347.77  4790.5   347.9    4847     347
  4960.2   347.7  4984.5  349.25  4991.6  346.82  4994.3  346.32  4997.6  346.82
  5035.1  348.69  5073.7  353.33  5106.1  357.32  5128.9  358.15  5172.4  362.29
  5189.8  364.48  5197.4  366.64  5227.8  368.87  5237.9  370.68  5278.5  374.76
#Mann= 6 ,-1 , 0
  4408.6     .16       0    4666     .05       0  4991.6     .03       0
  4997.6     .05       0  5073.7     .12       0  5172.4     .16       0
Bank Sta=4649.1,5035.1
XS Rating Curve= 0 ,0
Exp/Cntr=0.3,0.1

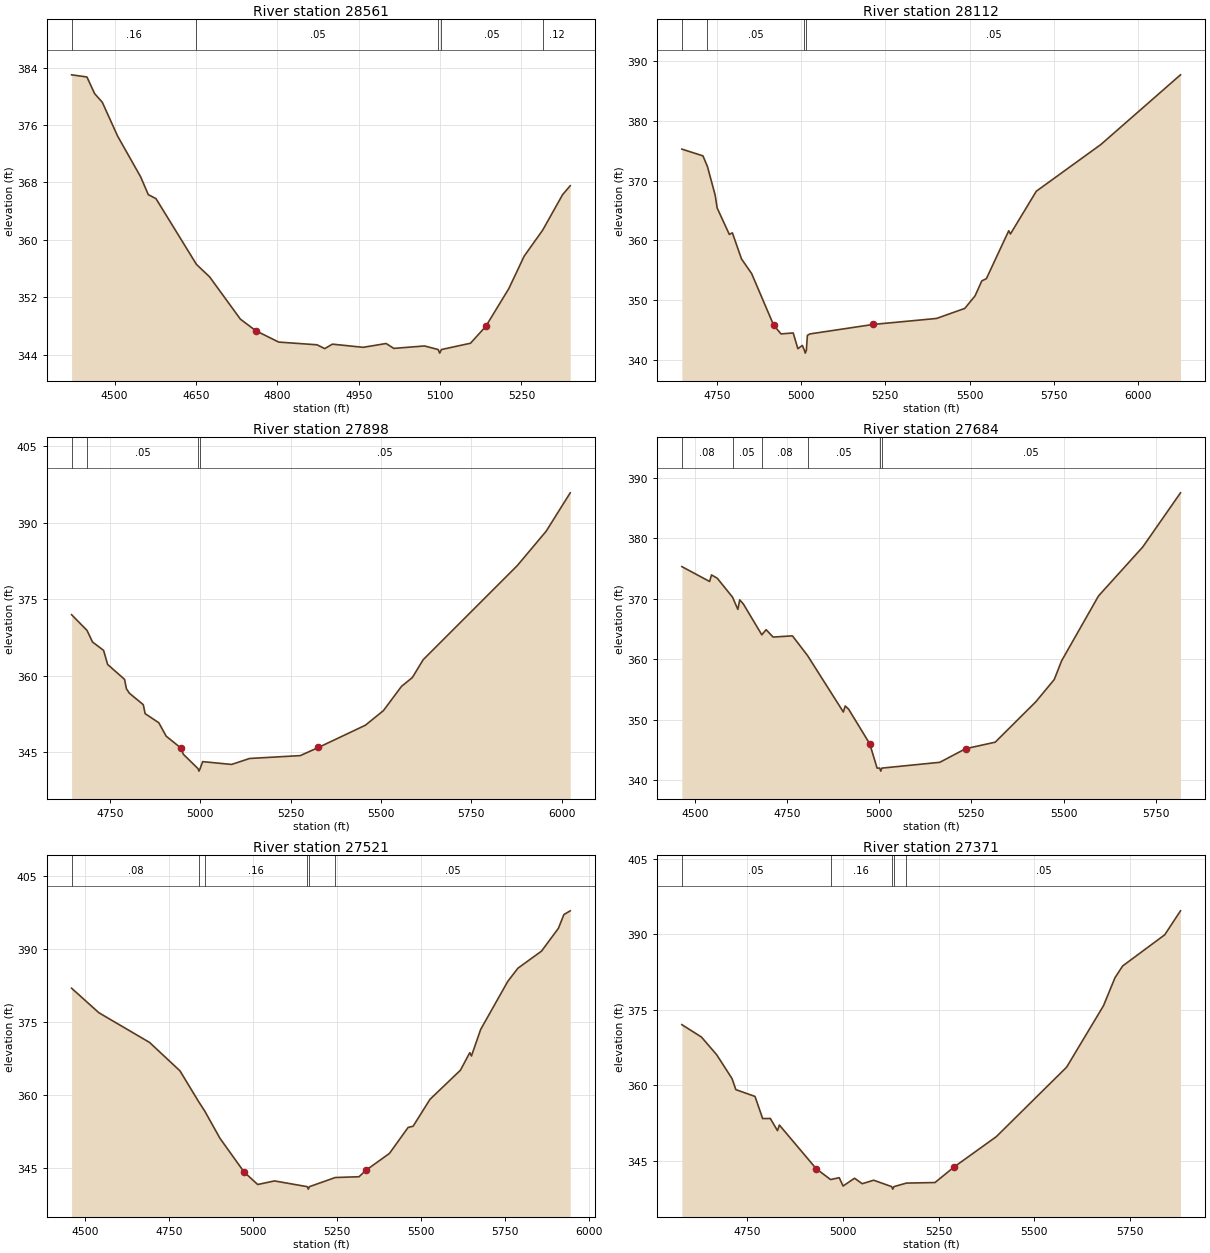
Type RM Length L Ch R = 1 ,28561   ,449,449,449
BEGIN DESCRIPTION:
HALL BRANCH 61.0
END DESCRIPTION:
XS GIS Cut Line= 3
      3659849.61     10708460.19      3659449.61     10708860.19
      3659199.63     10709110.16
#Sta/Elev= 30
  4420.7  382.98    4449  382.68  4463.1  380.37  4477.3  379.16  4505.5  374.45
    4548  368.77  4562.1  366.29  4576.3  365.73  4650.9  356.57  4675.3  354.82
  4731.8  348.95  4760.1  347.34  4802.5  345.75  4873.2  345.37  4887.4  344.84
  4901.5  345.46  4958.1  345.02  5000.5  345.55  5014.7  344.87  5071.2  345.21
  5096.5  344.71  5099.3  344.21  5102.5  344.71  5156.1  345.59  5184.4  347.95
  5226.8  353.21  5255.1  357.73  5289.1  361.34  5325.8  366.28  5339.9  367.53
#Mann= 5 ,-1 , 0
  4420.7     .16       0  4650.9     .05       0  5096.5     .03       0
  5102.5     .05       0  5289.1     .12       0
Bank Sta=4760.1,5184.4
XS Rating Curve= 0 ,0
Exp/Cntr=0.3,0.1

Type RM Length L Ch R = 1 ,28112   ,214,214,214
BEGIN DESCRIPTION:
HALL BRANCH 60.0
END DESCRIPTION:
XS GIS Cut Line= 3
      3659476.71     10708330.52      3658973.25     10708663.84
      3658105.82     10708785.28
#Sta/Elev= 30
  4646.2  375.28  4708.8  374.15  4722.1  372.36    4745  367.58  4750.9  365.42
  4787.1  360.98  4796.1  361.25  4823.2  356.88  4853.3  354.42  4918.6  345.78
  4940.5  344.31  4976.6  344.47  4990.5  341.83  5003.7  342.38  5009.7  341.59
  5012.5  341.09  5015.7  341.59  5018.7  344.07  5026.5  344.31  5214.3   345.9
    5402   346.9  5485.9  348.59  5516.2  350.68  5536.4   353.2  5549.9  353.57
  5616.2   361.6  5621.3  361.06    5698  368.22  5889.8  376.06  6125.9  387.73
#Mann= 4 ,-1 , 0
  4646.2     .08       0  4722.1     .05       0  5009.7     .03       0
  5015.7     .05       0
Bank Sta=4918.6,5214.3
XS Rating Curve= 0 ,0
Exp/Cntr=0.3,0.1

Type RM Length L Ch R = 1 ,27898   ,214,214,214
BEGIN DESCRIPTION:
Mapping XS b69cb347
END DESCRIPTION:
XS GIS Cut Line= 3
      3659386.47     10708327.03      3659080.89     10708386.07
      3658013.07     10708396.47
#Sta/Elev= 30
  4644.4  371.98  4687.1   368.9  4702.3  366.63  4732.9  364.99  4744.1  362.23
  4790.9  359.31    4796  357.48  4804.2   356.6  4842.7  354.35  4847.8  352.59
  4885.6  350.81    4906  348.18  4946.3  345.88  4953.7  344.62  4993.9  341.83
  4996.7  341.33  4999.9  341.83  5006.9  343.19  5086.9  342.64  5136.9  343.81
  5276.9  344.37  5326.9  345.96  5456.9  350.32  5506.9  353.19  5556.9  357.94
  5586.9  359.67  5616.9  363.17    5877  381.59    5957  388.34  6023.5  395.86
#Mann= 4 ,-1 , 0
  4644.4     .08       0  4687.1     .05       0  4993.9     .03       0
  4999.9     .05       0
Bank Sta=4946.3,5326.9
XS Rating Curve= 0 ,0
Exp/Cntr=0.3,0.1

Type RM Length L Ch R = 1 ,27684   ,163,163,163
BEGIN DESCRIPTION:
HALL BRANCH 59.0
END DESCRIPTION:
XS GIS Cut Line= 3
      3659424.67     10708306.21      3658976.72     10708243.71
      3658077.44     10708215.93
#Sta/Elev= 30
  4465.2  375.28  4540.5  372.82  4545.5  373.91  4561.2  373.36  4602.6  370.23
    4617  368.21  4622.1  369.78  4631.9  369.11    4682  364.01  4693.6  364.86
  4712.6  363.64  4765.1  363.84  4805.9  360.59  4903.1  351.26  4908.1  352.26
  4917.5  351.71  4974.6  346.01  4994.6  341.99  5001.6  341.99  5004.4  341.49
  5007.6  341.99  5164.7  342.95  5234.8   345.2  5314.8  346.27  5424.8  352.94
  5474.9  356.62  5494.9  359.72  5594.9  370.43    5715  378.53  5817.2  387.47
#Mann= 6 ,-1 , 0
  4465.2     .08       0  4602.6     .05       0    4682     .08       0
  4805.9     .05       0  5001.6     .03       0  5007.6     .05       0
Bank Sta=4974.6,5234.8
XS Rating Curve= 0 ,0
Exp/Cntr=0.3,0.1

Type RM Length L Ch R = 1 ,27521   ,150,150,150
BEGIN DESCRIPTION:
Mapping XS c2c794cc
END DESCRIPTION:
XS GIS Cut Line= 2
      3659400.36     10708143.01      3657924.67     10707983.29
#Sta/Elev= 30
  4459.8  381.94    4541  376.91  4691.9  370.82  4782.4     365  4839.2  358.55
  4855.9  356.79  4901.2   351.2  4973.5  344.24  5013.8   341.7  5064.1  342.43
  5161.6  341.25  5164.4  340.75  5167.6  341.25  5244.7  343.13  5315.5  343.29
  5335.6  344.59    5406  348.07  5461.6   353.4  5476.4  353.64  5526.7  359.16
  5617.3  365.13  5645.1  368.72  5650.1  368.05  5677.6  373.49  5758.1  383.32
  5788.3  386.03  5858.7  389.54    5909  394.22  5925.3  397.03  5944.1   397.8
#Mann= 6 ,-1 , 0
  4459.8     .08       0  4839.2     .05       0  4855.9     .16       0
  5161.6     .07       0  5167.6     .16       0  5244.7     .05       0
Bank Sta=4973.5,5335.6
XS Rating Curve= 0 ,0
Exp/Cntr=0.3,0.1

Type RM Length L Ch R = 1 ,27371   ,174,174,174
BEGIN DESCRIPTION:
Mapping XS 6a98aafb
END DESCRIPTION:
XS GIS Cut Line= 2
       3659240.6     10707948.57      3657938.52     10707931.21
#Sta/Elev= 30
  4579.5  372.01  4630.5  369.56  4670.5  366.03  4710.5   361.3  4720.5   359.1
  4770.5  357.75  4790.5  353.35  4810.5  353.37  4829.2  350.95  4834.2  352.06
  4930.5  343.38  4967.9  341.23  4990.5   341.6  5000.5  339.95  5030.5  341.49
  5050.5  340.41  5080.5   341.1  5127.5  339.83  5130.3  339.33  5133.5  339.83
    5166  340.53  5240.6  340.64  5290.6  343.74  5400.6  349.75  5584.3  363.56
  5680.6  375.77  5710.6  381.33  5730.6  383.67  5840.6  389.87  5881.7  394.63
#Mann= 5 ,-1 , 0
  4579.5     .05       0  4967.9     .16       0  5127.5     .07       0
  5133.5     .16       0    5166     .05       0
Bank Sta=4930.5,5290.6
XS Rating Curve= 0 ,0
Exp/Cntr=0.3,0.1

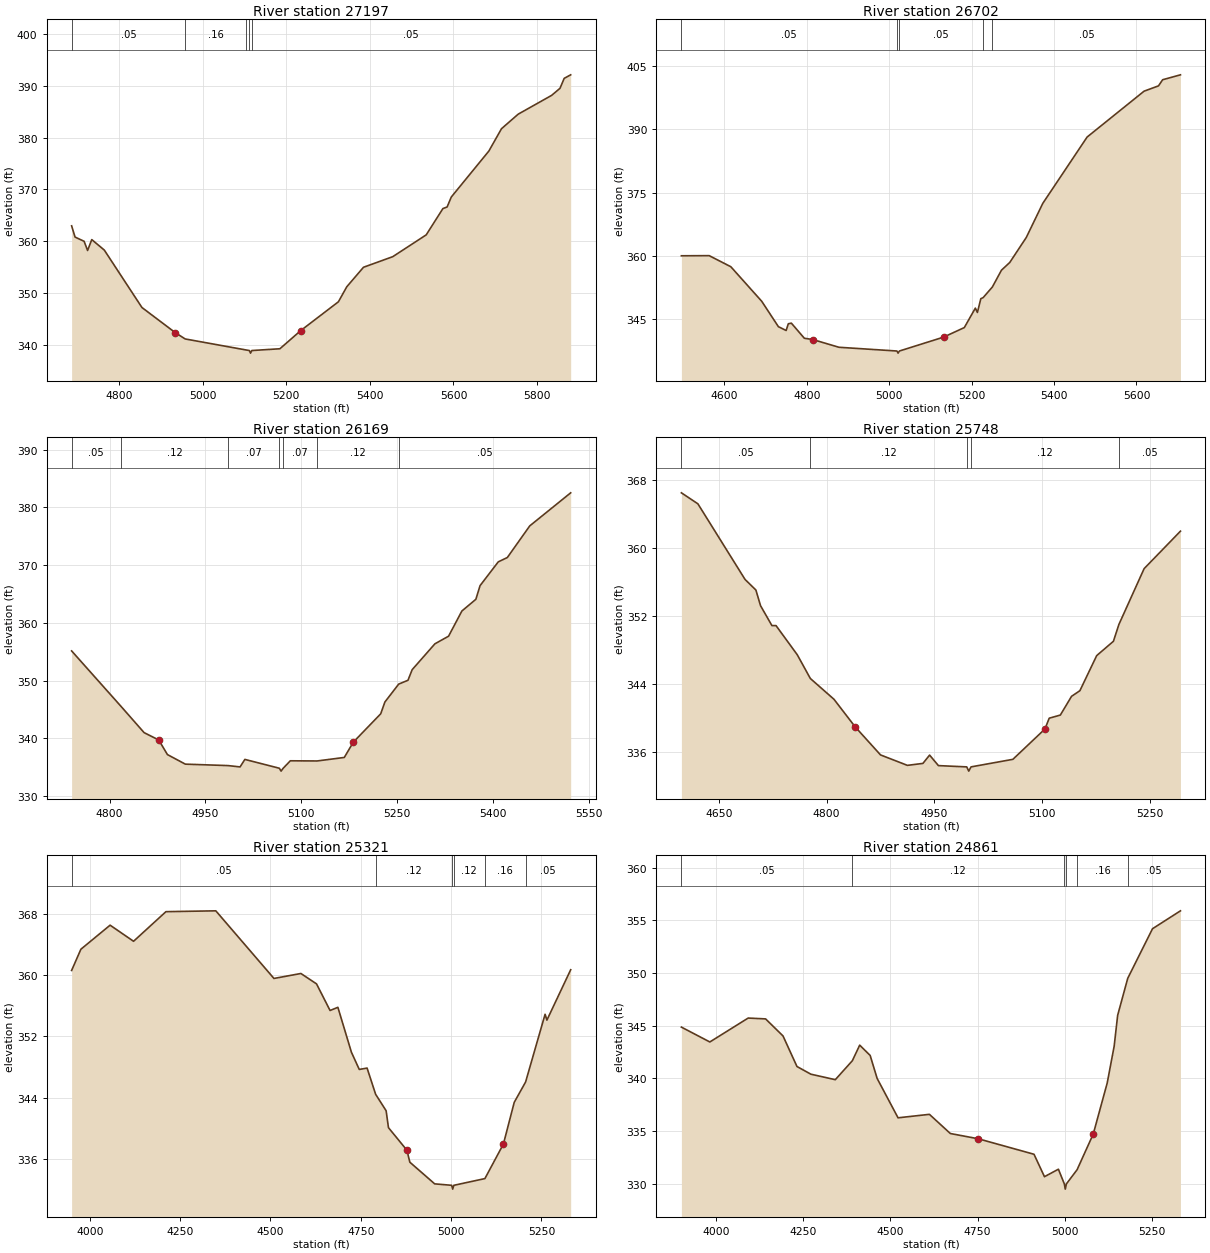
Type RM Length L Ch R = 1 ,27197   ,495,495,495
BEGIN DESCRIPTION:
HALL BRANCH 58.0
END DESCRIPTION:
XS GIS Cut Line= 2
       3659087.8     10707774.96      3657894.05     10707785.37
#Sta/Elev= 30
  4686.6  362.99  4694.8  360.83  4716.5  360.01  4724.8  358.24  4734.8  360.34
  4764.8  358.32  4854.8  347.26  4934.8   342.4  4958.3   341.2  5104.5  339.07
  5111.8  338.97  5114.6  338.47  5117.8  338.97  5184.8  339.31  5234.8  342.82
  5324.8  348.36  5344.8  351.25  5384.8  355.01  5454.8  357.05  5534.8  361.25
  5574.8  366.32  5584.8  366.62  5594.8  368.54  5684.8  377.41  5714.8  381.69
  5754.8   384.5  5834.8  388.12  5854.8  389.48  5864.9   391.4  5880.4  392.08
#Mann= 5 ,-1 , 0
  4686.6     .05       0  4958.3     .16       0  5104.5     .05       0
  5111.8     .07       0  5117.8     .05       0
Bank Sta=4934.8,5234.8
XS Rating Curve= 0 ,0
Exp/Cntr=0.3,0.1

Type RM Length L Ch R = 1 ,26702   ,533,533,533
BEGIN DESCRIPTION:
HALL BRANCH 57.0
END DESCRIPTION:
XS GIS Cut Line= 3
      3659073.98     10707563.16      3658636.53     10707424.03
      3657886.41      10707368.7
#Sta/Elev= 30
  4495.6     360  4563.1  360.03  4615.6   357.4  4690.6   349.2    4731  343.18
  4749.8  342.27  4755.1  343.87  4762.5  344.01    4794  340.43  4814.3  340.13
    4878  338.29  5018.7   337.4  5021.5   336.9  5024.7   337.4    5132   340.7
  5182.2  342.96    5209  347.58    5214  346.55  5222.3  349.82    5228  350.08
  5250.3  352.59  5272.4  356.58  5292.5  358.41  5332.6  364.34  5372.7  372.44
  5480.3  388.18  5618.5  399.06  5653.5  400.32  5663.5  401.77  5706.8  402.94
#Mann= 5 ,-1 , 0
  4495.6     .05       0  5018.7     .03       0  5024.7     .05       0
    5228     .12       0  5250.3     .05       0
Bank Sta=4814.3,5132
XS Rating Curve= 0 ,0
Exp/Cntr=0.3,0.1

Type RM Length L Ch R = 1 ,26169   ,421,421,421
BEGIN DESCRIPTION:
HALL BRANCH 56.0
END DESCRIPTION:
XS GIS Cut Line= 3
       3659049.6     10707360.19      3658849.61     10707210.19
      3658449.61     10706860.19
#Sta/Elev= 30
  4740.6  355.14  4817.8  345.55  4854.1  340.98  4877.1   339.7  4890.6  337.18
  4918.7  335.52  4985.5  335.27  5004.4  335.04  5011.9  336.34  5065.9  334.81
  5068.6  334.31  5071.9  334.81  5083.1   336.1    5125  336.07  5167.6  336.68
  5181.8  339.34  5224.6  344.24  5231.2  346.29  5252.8  349.39  5267.3  350.05
  5273.9  351.89  5309.5  356.37  5330.9  357.69  5351.7  362.05  5373.6  364.08
  5380.2  366.45  5408.7  370.57  5422.9  371.32    5458   376.8  5522.1  382.53
#Mann= 7 ,-1 , 0
  4740.6     .05       0  4817.8     .12       0  4985.5     .07       0
  5065.9     .07       0  5071.9     .07       0    5125     .12       0
  5252.8     .05       0
Bank Sta=4877.1,5181.8
XS Rating Curve= 0 ,0
Exp/Cntr=0.3,0.1

Type RM Length L Ch R = 1 ,25748   ,427,427,427
BEGIN DESCRIPTION:
HALL BRANCH 55.0
END DESCRIPTION:
XS GIS Cut Line= 3
      3659399.62      10707060.2      3659049.61     10706860.19
      3658799.59     10706710.18
#Sta/Elev= 30
  4597.9  366.53  4620.9  365.23  4686.5  356.32  4701.6  355.07  4708.1  353.22
  4723.9  350.88  4729.6  350.88  4759.2  347.44  4777.4  344.64  4810.3  342.19
  4839.8  338.94  4875.1  335.63  4912.5   334.4  4934.1  334.63  4943.4  335.61
  4955.7  334.37  4995.1  334.22  4997.9  333.72  5001.1  334.22  5059.3  335.11
    5104  338.69  5109.9  339.96  5125.4  340.33    5141  342.54  5152.6   343.2
    5176  347.34  5199.3  349.03  5206.8  350.99    5242  357.59  5292.6  362.01
#Mann= 5 ,-1 , 0
  4597.9     .05       0  4777.4     .12       0  4995.1     .07       0
  5001.1     .12       0  5206.8     .05       0
Bank Sta=4839.8,5104
XS Rating Curve= 0 ,0
Exp/Cntr=0.3,0.1

Type RM Length L Ch R = 1 ,25321   ,460,460,460
BEGIN DESCRIPTION:
HALL BRANCH 54.0
END DESCRIPTION:
XS GIS Cut Line= 3
      3660086.65     10706958.04       3659233.4     10706474.15
      3658833.45     10706463.28
#Sta/Elev= 30
  3949.8  360.65  3975.5  363.43  4056.3  366.58  4121.2  364.47  4210.8  368.35
  4348.8  368.46  4509.7   359.6  4584.2  360.25  4627.5  358.89    4665   355.4
  4686.6  355.82  4724.1  349.93  4745.8  347.68  4767.4  347.86  4791.1  344.42
  4820.1  342.27  4826.6  340.05  4877.6   337.1  4885.7  335.53  4954.5  332.69
  5001.5   332.5  5004.3     332  5007.5   332.5  5093.4  333.38  5144.6   337.9
  5174.6  343.37    5206  346.03    5260  354.91    5265  354.14  5330.8  360.74
#Mann= 6 ,-1 , 0
  3949.8     .05       0  4791.1     .12       0  5001.5     .07       0
  5007.5     .12       0  5093.4     .16       0    5206     .05       0
Bank Sta=4877.6,5144.6
XS Rating Curve= 0 ,0
Exp/Cntr=0.3,0.1

Type RM Length L Ch R = 1 ,24861   ,547,547,547
BEGIN DESCRIPTION:
HALL BRANCH 53.0
END DESCRIPTION:
XS GIS Cut Line= 2
      3660221.22     10706089.98       3658789.4     10706074.95
#Sta/Elev= 30
  3900.4  344.86    3982  343.45    4092  345.72    4142  345.64    4192  344.02
    4232  341.12    4272  340.39    4342  339.87  4390.9  341.67    4412  343.15
    4442  342.17    4462  339.99    4522  336.25    4612  336.58  4672.1  334.76
  4752.1  334.26  4912.1  332.79  4942.1  330.66  4982.1  331.37  4999.1  329.98
  5001.8  329.48  5005.1  329.98  5035.7  331.32  5082.1  334.71  5122.1  339.55
  5142.1  343.05  5152.1  345.98    5181  349.49  5252.1   354.2  5332.3   355.9
#Mann= 6 ,-1 , 0
  3900.4     .05       0  4390.9     .12       0  4999.1     .07       0
  5005.1     .12       0  5035.7     .16       0    5181     .05       0
Bank Sta=4752.1,5082.1
XS Rating Curve= 0 ,0
Exp/Cntr=0.3,0.1

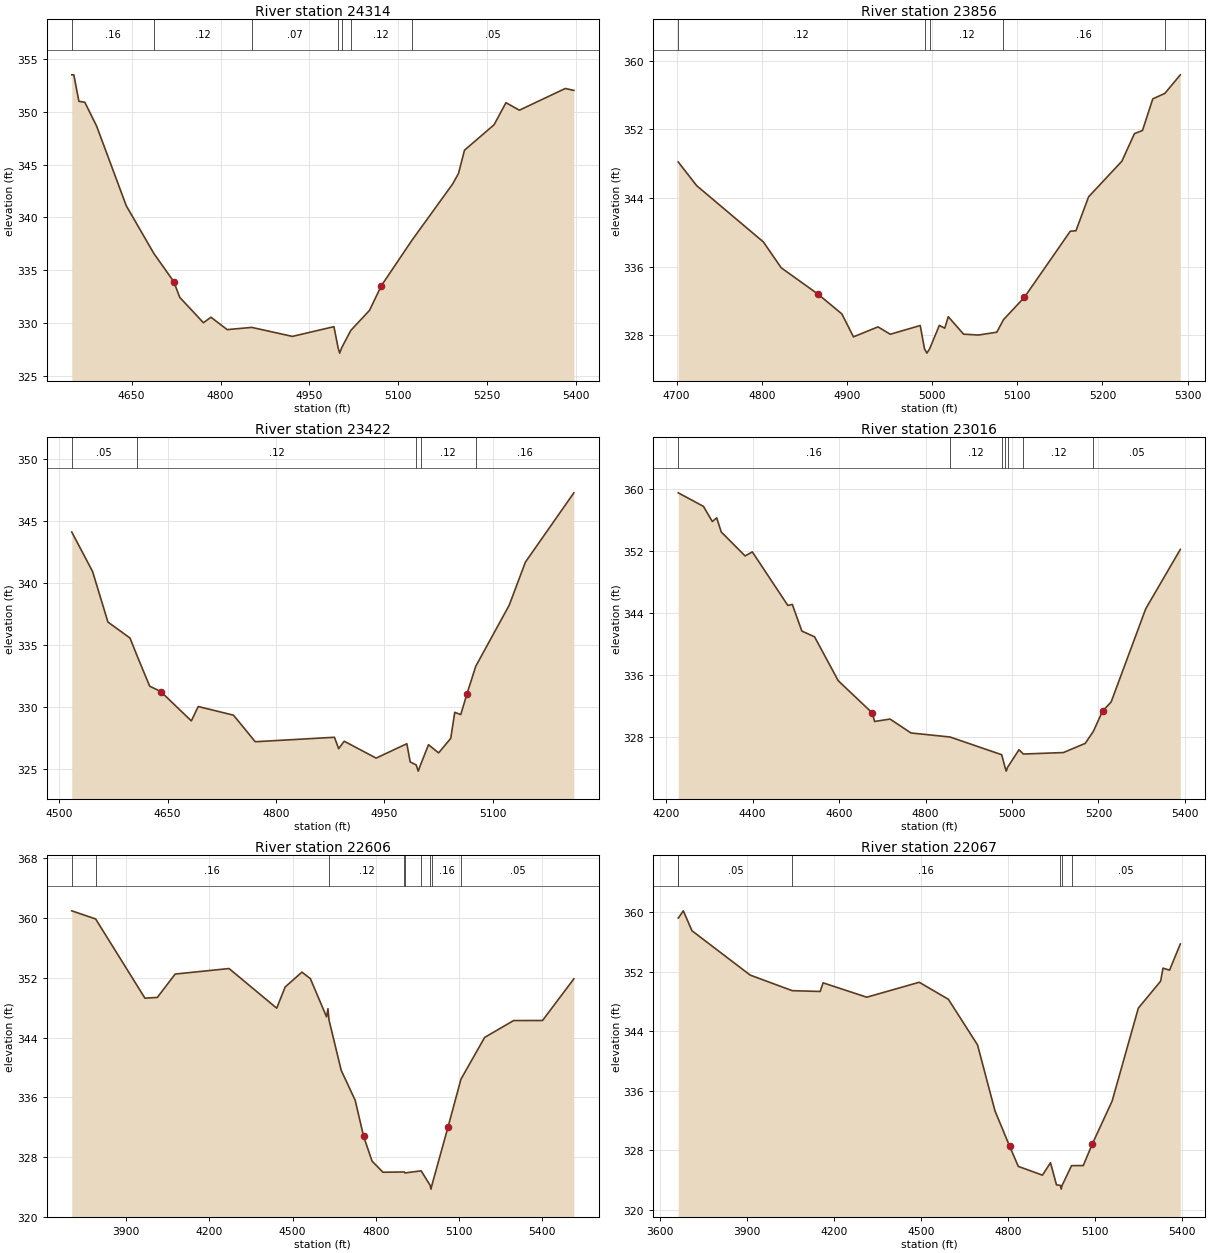
Type RM Length L Ch R = 1 ,24314   ,458,458,458
BEGIN DESCRIPTION:
HALL BRANCH 52.0
END DESCRIPTION:
XS GIS Cut Line= 2
      3659581.57     10705554.12       3658735.2     10705521.57
#Sta/Elev= 30
    4549  353.47  4552.5  353.47    4561  350.97    4571  350.88    4591  348.62
    4641   341.1  4687.4  336.61  4721.1  333.94  4731.1  332.46  4771.1  330.06
  4783.8  330.58  4811.2  329.41  4852.6  329.62  4921.2  328.77  4991.3  329.69
  4998.3  327.69    5001  327.19  5004.3  327.69  5019.7  329.33  5051.3  331.23
  5071.3  333.56  5122.8  337.84  5191.4  343.15  5201.4  344.16  5211.5  346.35
  5261.5  348.76  5281.5  350.84  5304.1  350.13  5381.6  352.18    5396     352
#Mann= 7 ,-1 , 0
    4549     .16       0  4687.4     .12       0  4852.6     .07       0
  4998.3     .07       0  5004.3     .07       0  5019.7     .12       0
  5122.8     .05       0
Bank Sta=4721.1,5071.3
XS Rating Curve= 0 ,0
Exp/Cntr=0.3,0.1

Type RM Length L Ch R = 1 ,23856   ,434,434,434
BEGIN DESCRIPTION:
HALL BRANCH 51.0
END DESCRIPTION:
XS GIS Cut Line= 3
      3659449.61     10705310.19      3659199.61     10705110.19
      3658949.62     10705010.19
#Sta/Elev= 30
    4702   348.2  4723.6  345.44    4802  338.87  4822.9  335.86  4866.1  332.79
  4894.1  330.48  4907.7  327.81  4936.5  328.97  4950.9  328.11  4986.1  329.13
  4991.1  326.41  4993.9  325.91  4997.1  326.41  5008.5  329.14  5014.9  328.82
    5019  330.16    5037  328.12  5054.5  328.02    5076  328.35  5083.8  329.81
  5108.3  332.41  5162.2  340.12  5168.9  340.18  5183.7  344.13  5222.8  348.29
  5237.6  351.51    5247  351.87  5259.1  355.56  5273.2  356.19  5291.4  358.36
#Mann= 5 ,-1 , 0
    4702     .12       0  4991.1     .07       0  4997.1     .12       0
  5083.8     .16       0  5273.2     .05       0
Bank Sta=4866.1,5108.3
XS Rating Curve= 0 ,0
Exp/Cntr=0.3,0.1

Type RM Length L Ch R = 1 ,23422   ,406,406,406
BEGIN DESCRIPTION:
HALL BRANCH 50.0
END DESCRIPTION:
XS GIS Cut Line= 3
      3659799.57     10705010.16      3659399.61     10704760.19
      3659199.57     10704660.17
#Sta/Elev= 30
  4517.2  344.11    4546  340.93  4567.3  336.85  4597.9  335.56  4607.3  334.18
  4625.1  331.68  4640.4  331.25  4682.8  328.88  4692.3  330.04  4741.2  329.34
  4771.3   327.2    4881  327.56  4886.8  326.64  4894.5  327.24  4938.7  325.88
  4981.2  327.04  4985.9  325.57  4994.2  325.33    4997  324.83  5000.2  325.33
  5011.2  326.96  5025.2   326.3    5042  327.47  5047.6  329.57  5055.9  329.39
  5064.3  331.03  5076.7  333.29    5123  338.21  5145.4  341.68  5212.5  347.27
#Mann= 5 ,-1 , 0
  4517.2     .05       0  4607.3     .12       0  4994.2     .07       0
  5000.2     .12       0  5076.7     .16       0
Bank Sta=4640.4,5064.3
XS Rating Curve= 0 ,0
Exp/Cntr=0.3,0.1

Type RM Length L Ch R = 1 ,23016   ,410,410,410
BEGIN DESCRIPTION:
HALL BRANCH 49.0
END DESCRIPTION:
XS GIS Cut Line= 3
      3660286.27     10704570.88      3659405.21     10704360.19
      3659149.61     10704360.19
#Sta/Elev= 30
  4227.8  359.45  4286.1  357.71  4306.6  355.76  4316.9  356.23  4327.2  354.42
  4382.5  351.33  4399.2  351.85  4481.4  344.96  4491.7  345.09  4513.8  341.66
  4543.1  340.93    4598  335.27  4676.8  331.12  4682.1  330.03  4717.9  330.34
  4766.2  328.55  4856.7  328.03  4976.1  325.75  4983.8  324.14  4986.5  323.64
  4989.8  324.14  5016.1  326.39  5026.3  325.84  5118.9  326.03  5169.3  327.21
  5188.2  328.76  5209.3  331.35  5229.3  332.54  5309.3  344.53  5389.3  352.17
#Mann= 7 ,-1 , 0
  4227.8     .16       0  4856.7     .12       0  4976.1     .16       0
  4983.8     .07       0  4989.8     .16       0  5026.3     .12       0
  5188.2     .05       0
Bank Sta=4676.8,5209.3
XS Rating Curve= 0 ,0
Exp/Cntr=0.3,0.1

Type RM Length L Ch R = 1 ,22606   ,539,539,539
BEGIN DESCRIPTION:
HALL BRANCH 48.0
END DESCRIPTION:
XS GIS Cut Line= 3
      3660750.69     10704180.26      3659527.18     10703999.02
      3658963.55     10704106.27
#Sta/Elev= 30
  3703.5  360.99  3789.6   359.9  3967.4  349.29    4012  349.39  4076.4  352.52
  4270.7  353.26  4442.6  347.95  4472.9  350.78  4533.5  352.78  4563.9  351.91
  4622.4  346.78  4627.4  347.88  4631.1  346.38  4675.1  339.63  4725.6  335.61
  4755.9  330.79  4786.3  327.47  4825.8  325.97  4902.7  326.01  4904.7  325.88
  4963.5  326.16    4996  324.21  4998.7  323.71    5002  324.21    5060  331.98
    5107  338.44  5192.4  344.03  5296.8  346.29  5401.2   346.3  5514.1  351.88
#Mann= 9 ,-1 , 0
  3703.5     .05       0  3789.6     .16       0  4631.1     .12       0
  4902.7     .16       0  4904.7     .12       0  4963.5     .16       0
    4996     .07       0    5002     .16       0    5107     .05       0
Bank Sta=4755.9,5060
XS Rating Curve= 0 ,0
Exp/Cntr=0.3,0.1

Type RM Length L Ch R = 1 ,22067   ,496,496,496
BEGIN DESCRIPTION:
HALL BRANCH 47.0
END DESCRIPTION:
XS GIS Cut Line= 3
      3660776.74      10703333.9      3659526.74     10703460.19
      3659063.49     10703568.01
#Sta/Elev= 30
  3663.1  359.24  3663.7  359.25  3680.6  360.21  3710.5  357.53  3911.5  351.56
  4056.4  349.47  4152.7  349.36  4162.8  350.52  4313.5  348.59  4494.4   350.6
    4595  348.31  4695.5  342.18  4755.8   333.3    4806  328.57  4836.2  325.83
  4919.5  324.65  4947.3  326.32  4967.9  323.35  4981.4  323.27  4984.2  322.77
  4987.4  323.27  5019.8  325.93  5060.3  325.94  5091.1  328.81  5159.9  334.62
  5250.3  347.12  5327.2  350.75  5335.4   352.5    5358  352.23  5395.1  355.75
#Mann= 6 ,-1 , 0
  3663.1     .16       0  3663.7     .05       0  4056.4     .16       0
  4981.4     .07       0  4987.4     .16       0  5019.8     .05       0
Bank Sta=4806,5091.1
XS Rating Curve= 0 ,0
Exp/Cntr=0.3,0.1

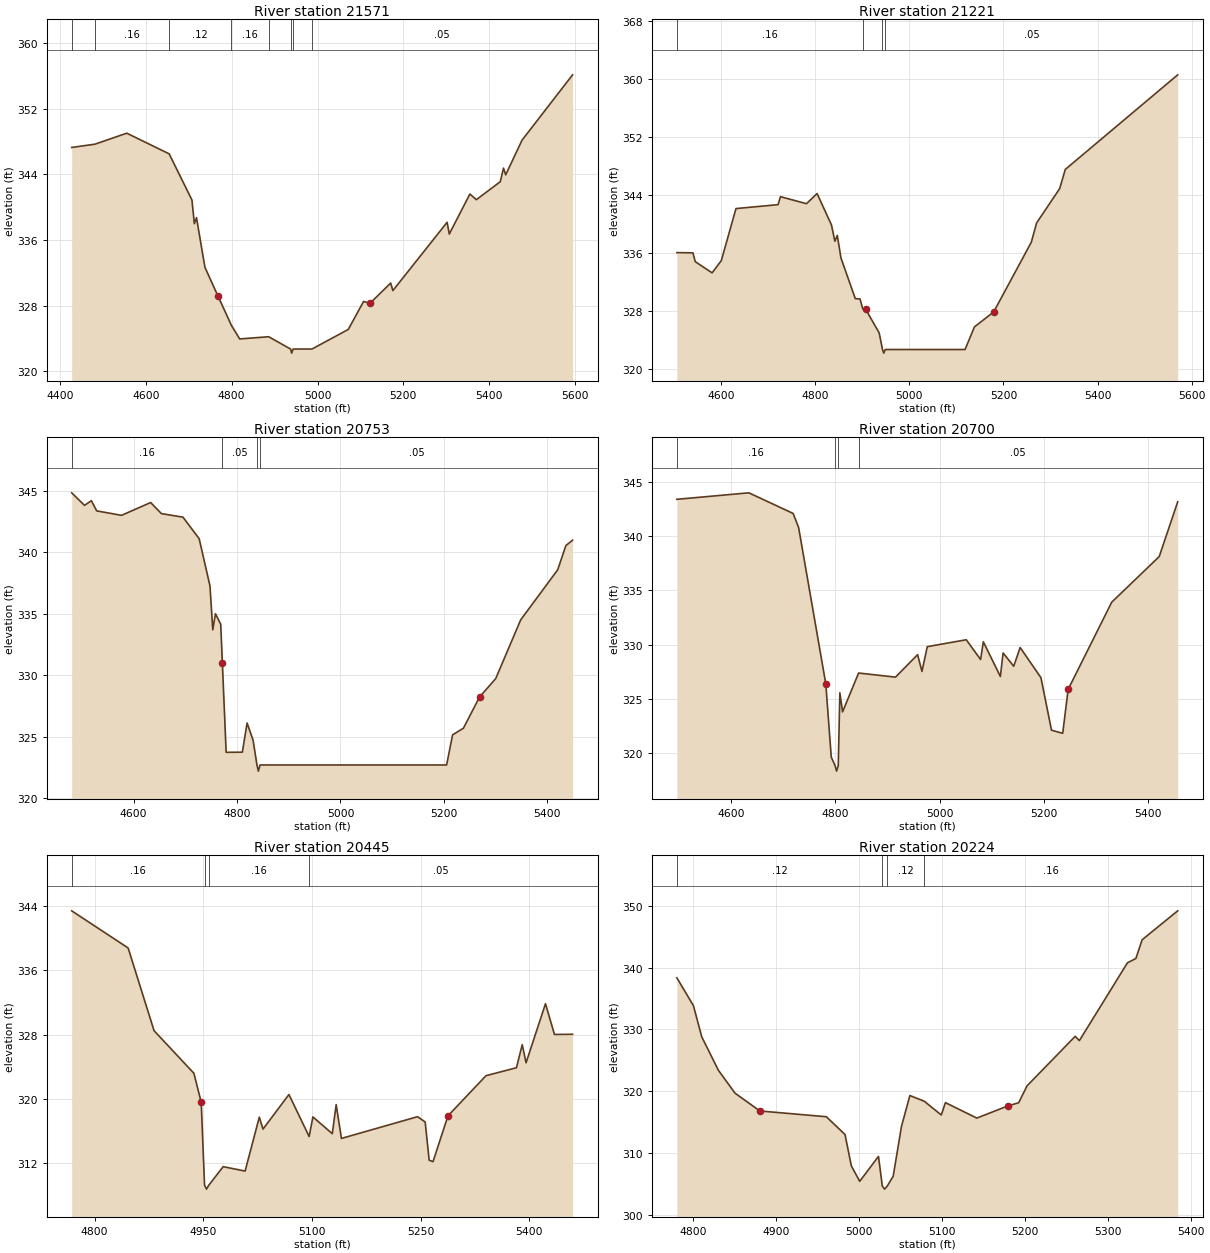
Type RM Length L Ch R = 1 ,21571   ,350,350,350
BEGIN DESCRIPTION:
HALL BRANCH 46.0
END DESCRIPTION:
XS GIS Cut Line= 2
       3659956.4     10702921.58      3658803.22     10703099.33
#Sta/Elev= 30
  4427.4  347.28  4481.6  347.68  4555.7  349.02  4654.4   346.5  4707.5  340.87
  4713.1  337.98  4718.1  338.71  4737.8  332.65  4768.2  329.15  4799.5  325.57
  4818.8  323.92  4886.3  324.19  4937.2  322.69  4939.9  322.19  4943.2  322.69
  4987.1  322.69  5071.7  325.08  5107.3  328.49  5122.3  328.27  5170.5  330.74
  5175.6  329.82  5301.9  338.15    5307  336.72    5355   341.6  5370.1  340.91
  5425.8   343.1  5433.3  344.76  5438.4  343.94  5476.4  348.16  5594.2  356.14
#Mann= 8 ,-1 , 0
  4427.4     .05       0  4481.6     .16       0  4654.4     .12       0
  4799.5     .16       0  4886.3      .1       0  4937.2     .03       0
  4943.2      .1       0  4987.1     .05       0
Bank Sta=4768.2,5122.3
XS Rating Curve= 0 ,0
Exp/Cntr=0.3,0.1

Type RM Length L Ch R = 1 ,21221   ,468,468,468
BEGIN DESCRIPTION:
HALL BRANCH 45.0
END DESCRIPTION:
XS GIS Cut Line= 2
      3659843.56      10702578.7      3658793.92     10702756.53
#Sta/Elev= 30
  4505.8  336.04  4539.9  336.01    4545  334.79  4580.8  333.25  4600.3  334.94
  4631.5  342.11    4721  342.65  4726.1  343.75  4781.3  342.78  4803.9  344.18
  4834.4  339.86  4841.7  337.61  4846.8  338.41  4854.7  335.29  4885.1   329.7
  4895.2  329.65  4900.9   328.3  4907.1  328.23  4935.8  324.99  4942.9  322.69
  4945.7  322.19  4948.9  322.69  5118.4  322.69  5138.4  325.81  5179.2  327.86
  5259.2  337.47  5270.5  340.13  5319.5  344.86  5331.4   347.5  5570.4  360.54
#Mann= 4 ,-1 , 0
  4505.8     .16       0  4900.9     .05       0  4942.9    .033       0
  4948.9     .05       0
Bank Sta=4907.1,5179.2
XS Rating Curve= 0 ,0
Exp/Cntr=0.3,0.1

Type RM Length L Ch R = 1 ,20753   ,53,53,53
BEGIN DESCRIPTION:
HALL BRANCH 44.0
END DESCRIPTION:
XS GIS Cut Line= 2
        3659716.      10702067.4      3658787.16     10702343.45
#Sta/Elev= 30
  4480.1  344.82  4504.9   343.8  4518.1  344.18  4528.5  343.35  4576.5  342.99
  4632.8  344.03  4653.7  343.13  4695.4  342.84  4726.7  341.09  4747.6  337.25
    4753  333.68  4758.2  334.99  4768.4  334.13  4771.6  330.96  4778.9  323.72
  4810.2  323.73  4819.4   326.1    4831  324.71  4838.5  322.69  4841.2  322.19
  4844.5  322.69  5205.4  322.69    5217  325.14  5237.9  325.68  5269.2  328.22
  5300.5  329.72  5348.7  334.49  5420.3  338.56  5436.1  340.53  5449.1  340.97
#Mann= 4 ,-1 , 0
  4480.1     .16       0  4771.6     .05       0  4838.5     .03       0
  4844.5     .05       0
Bank Sta=4771.6,5269.2
XS Rating Curve= 0 ,0
Exp/Cntr=0.3,0.1

Type RM Length L Ch R = 1 ,20700   ,255,255,255
BEGIN DESCRIPTION:
Mapping XS 9a882986
END DESCRIPTION:
XS GIS Cut Line= 4
      3659693.38     10702033.91      3659363.22     10702134.25
      3659181.62     10702168.16      3658768.43     10702294.89
#Sta/Elev= 30
  4495.5  343.44  4633.8  344.04  4718.9  342.13  4729.4  340.83  4781.6  326.35
  4792.1  319.57  4799.5  318.78  4802.3  318.28  4805.5  318.78  4808.6  325.53
  4813.8  323.76  4844.6  327.36  4915.5  326.98  4957.9  329.06  4966.3  327.51
  4976.5   329.8  5051.4  330.44  5078.9  328.61  5084.2  330.25  5116.9  327.04
  5122.1  329.22  5142.5  327.99  5154.9  329.72  5194.8  326.93  5215.1  322.07
  5236.6  321.78  5247.1  325.85  5330.8  333.92    5422  338.14  5457.5  343.21
#Mann= 4 ,-1 , 0
  4495.5     .16       0  4799.5     .03       0  4805.5     .16       0
  4844.6     .05       0
Bank Sta=4781.6,5247.1
XS Rating Curve= 0 ,0
Exp/Cntr=0.3,0.1

Type RM Length L Ch R = 1 ,20445   ,221,221,221
BEGIN DESCRIPTION:
Mapping XS d67ff5aa
END DESCRIPTION:
XS GIS Cut Line= 3
      3659546.82      10701979.9      3659225.63      10702023.3
      3658875.82     10702135.59
#Sta/Elev= 30
  4768.4  343.43  4846.3   338.8  4882.1  328.49  4937.1  323.18  4947.2  319.57
  4951.8  309.24  4954.5  308.74  4957.8  309.24  4977.5  311.54  5007.8  310.99
  5027.4  317.71  5032.5  316.22  5068.3  320.53  5096.2   315.3  5101.4  317.74
  5128.2  315.65  5133.5  319.28  5140.8  315.06  5245.9  317.77  5256.4  317.11
  5261.9  312.35  5267.2  312.16  5287.9  317.88  5340.4  322.88  5382.4  323.87
  5390.4  326.75  5395.7  324.49  5422.5  331.85  5434.9  328.02  5459.9  328.04
#Mann= 4 ,-1 , 0
  4768.4     .16       0  4951.8     .07       0  4957.8     .16       0
  5096.2     .05       0
Bank Sta=4947.2,5287.9
XS Rating Curve= 0 ,0
Exp/Cntr=0.3,0.1

Type RM Length L Ch R = 1 ,20224   ,366,366,366
BEGIN DESCRIPTION:
HALL BRANCH 43.0
END DESCRIPTION:
XS GIS Cut Line= 3
       3659449.6     10701810.19      3659249.61     10701810.19
      3658849.62     10701860.19
#Sta/Elev= 30
  4780.6  338.37  4800.6  333.85  4810.6  328.81  4830.6  323.41  4850.6   319.7
  4880.6  316.81  4960.6  315.88  4983.1     313  4990.7  307.93  5000.8  305.42
  5023.4  309.46    5028  304.66  5030.7  304.16    5034  304.66  5041.1  306.25
  5051.1  314.32  5061.2  319.31  5078.5  318.39    5099  316.16    5104  318.16
  5141.8  315.66  5179.6  317.65  5192.2  318.14  5202.3  320.88  5260.3   328.9
  5265.3   328.2  5323.2   340.8  5333.3  341.49  5340.9  344.53  5383.7  349.21
#Mann= 4 ,-1 , 0
  4780.6     .12       0    5028     .07       0    5034     .12       0
  5078.5     .16       0
Bank Sta=4880.6,5179.6
XS Rating Curve= 0 ,0
Exp/Cntr=0.3,0.1