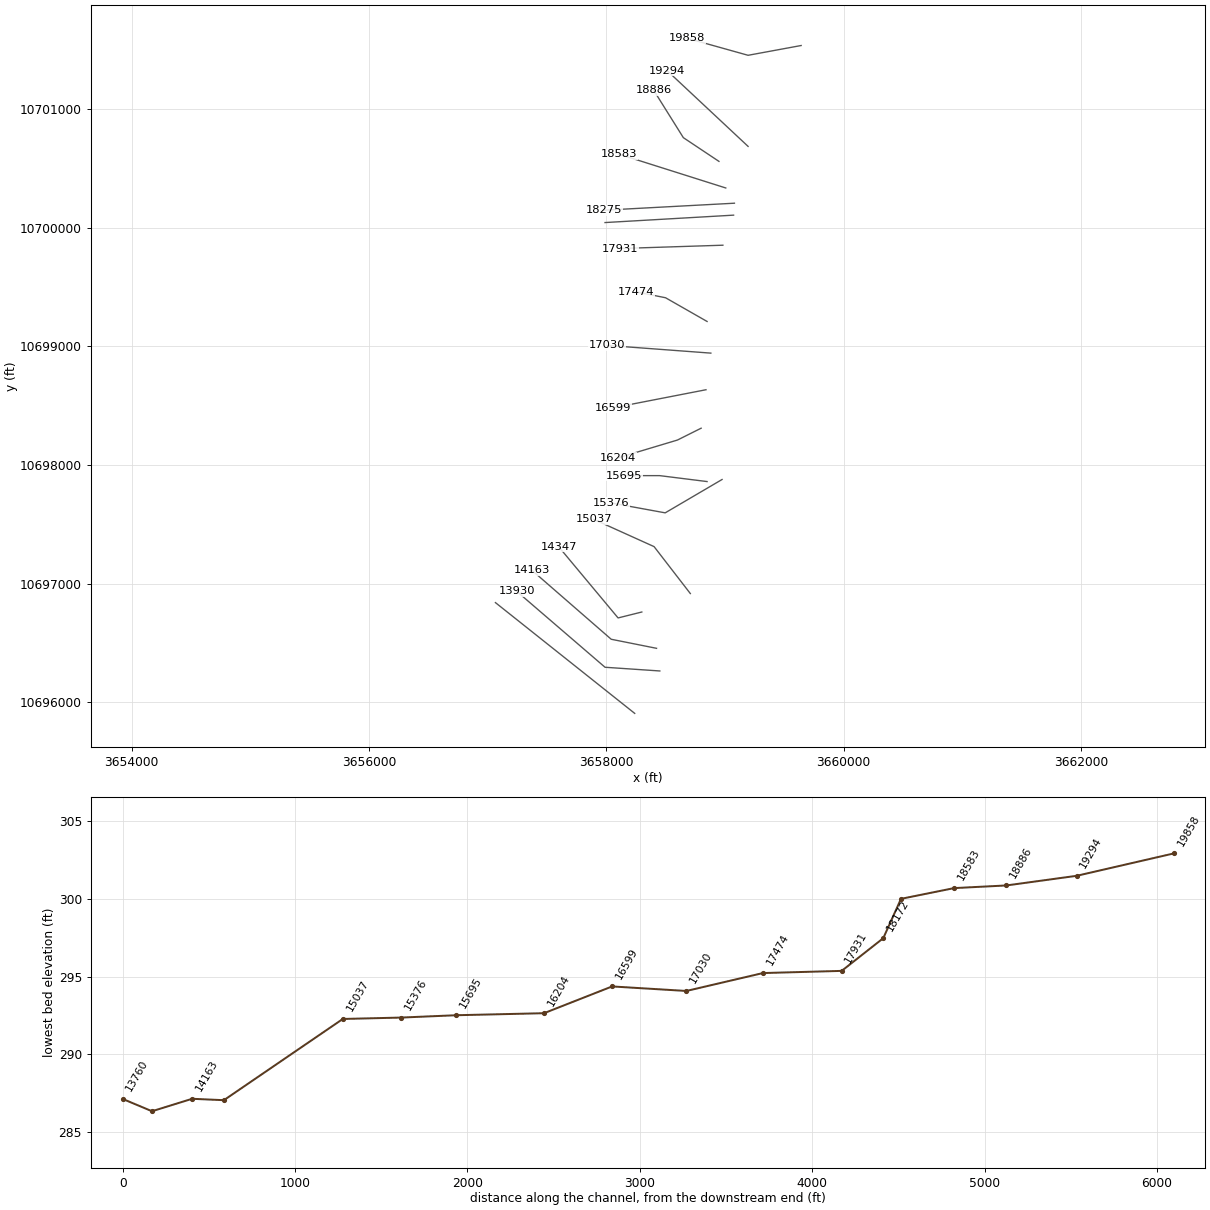
HEC-RAS study HALL BRANCH.prj: HALL BRANCH Base Level Engineering

--- HALL BRANCH.g01 (geometry) --- (continued)

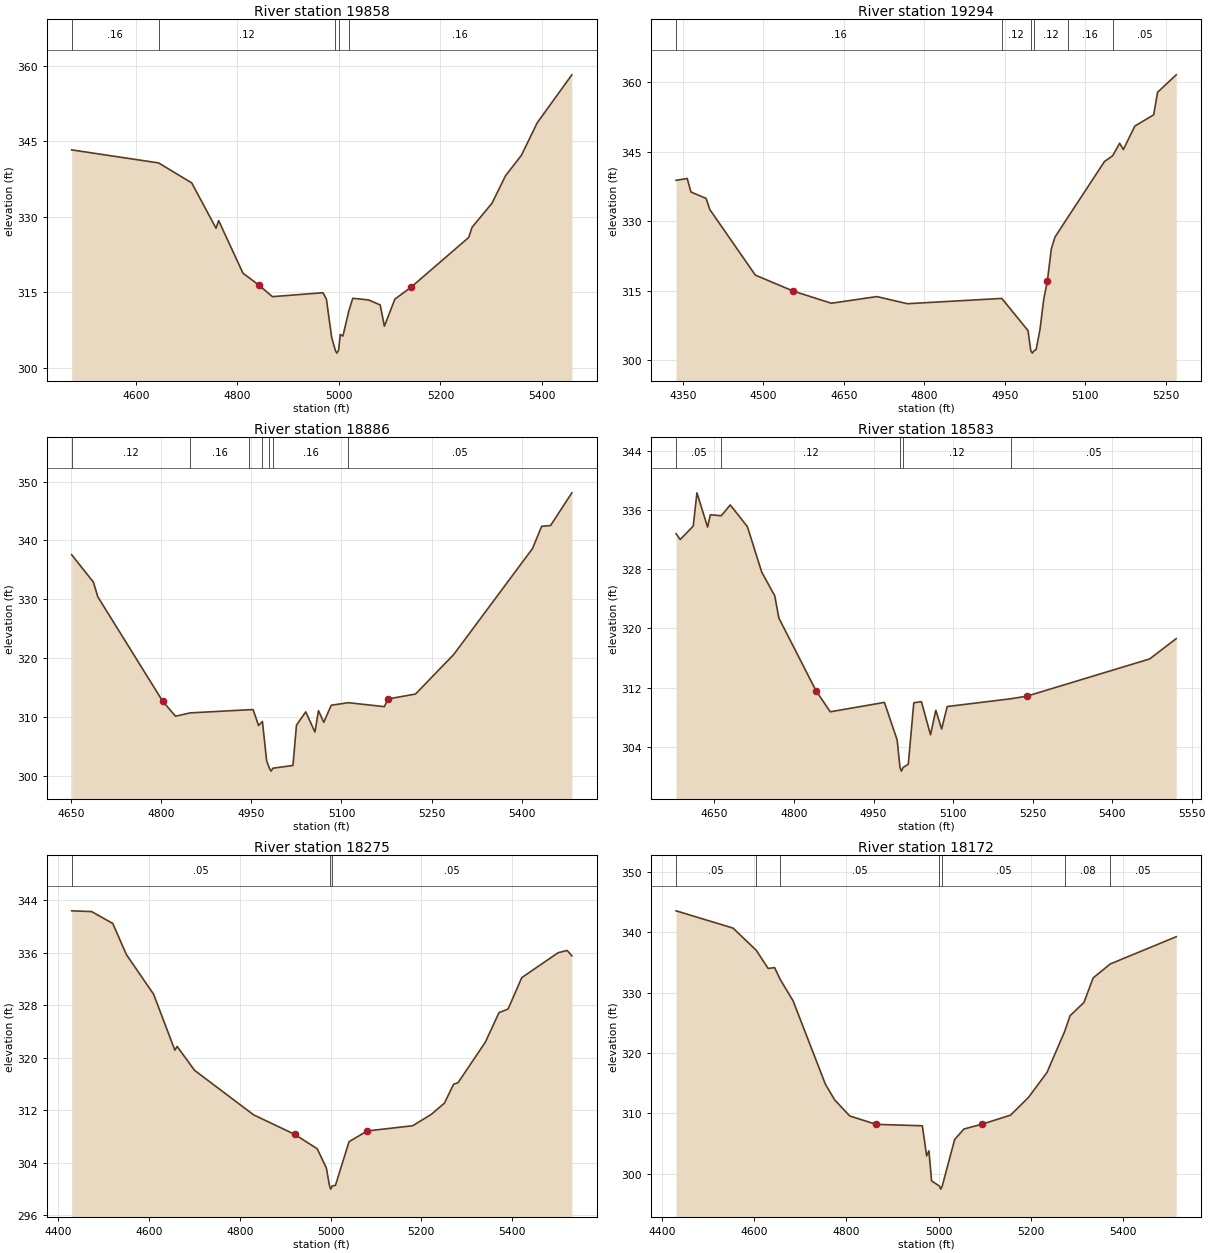
Type RM Length L Ch R = 1 ,19858   ,564,564,564
BEGIN DESCRIPTION:
HALL BRANCH 42.0
END DESCRIPTION:
XS GIS Cut Line= 3
      3659642.31     10701537.19      3659195.25     10701454.73
      3658683.87     10701597.74
#Sta/Elev= 30
  4473.4  343.27  4644.7  340.68    4710  336.71  4757.9  327.71    4763  329.24
  4810.9   318.8  4842.2  316.43    4869  314.13  4968.5  314.91  4975.4  313.63
  4985.8  305.99  4993.2  303.42  4995.9  302.92  4999.2  303.42  5002.7  306.62
  5007.9  306.31  5019.5  311.28  5027.3  313.81  5058.5  313.48  5081.3  312.49
  5089.6  308.26  5110.3  313.64  5141.5  315.95  5255.8  325.89  5262.4   327.9
  5301.7  332.69  5328.4  338.15  5359.6  342.19  5390.7  348.63    5459  358.17
#Mann= 5 ,-1 , 0
  4473.4     .16       0  4644.7     .12       0  4993.2     .07       0
  4999.2     .12       0  5019.5     .16       0
Bank Sta=4842.2,5141.5
XS Rating Curve= 0 ,0
Exp/Cntr=0.3,0.1

Type RM Length L Ch R = 1 ,19294   ,408,408,408
BEGIN DESCRIPTION:
HALL BRANCH 41.0
END DESCRIPTION:
XS GIS Cut Line= 2
      3659195.22     10700686.52      3658514.23     10701324.13
#Sta/Elev= 30
    4337  338.82  4357.9  339.21  4364.8   336.3  4393.1  334.91    4400  332.51
  4484.9  318.34  4555.8  314.88  4626.6  312.26  4711.6   313.7  4768.3  312.16
  4944.6   313.3  4993.5  306.35  4998.7  301.98  5001.5  301.48  5004.7  301.98
  5008.6  302.26  5015.9  306.65  5022.8  313.11  5029.7  317.14  5036.9  323.99
  5043.8  326.56  5067.4  330.76  5136.1  342.89  5151.4  344.14  5164.4  346.84
  5171.3  345.47  5192.7  350.55  5227.9  352.98  5235.1  357.85  5269.9  361.62
#Mann= 6 ,-1 , 0
    4337     .16       0  4944.6     .12       0  4998.7     .07       0
  5004.7     .12       0  5067.4     .16       0  5151.4     .05       0
Bank Sta=4555.8,5029.7
XS Rating Curve= 0 ,0
Exp/Cntr=0.3,0.1

Type RM Length L Ch R = 1 ,18886   ,303,303,303
BEGIN DESCRIPTION:
HALL BRANCH 40.0
END DESCRIPTION:
XS GIS Cut Line= 3
      3658949.62     10700560.18      3658649.61     10700760.19
      3658399.59     10701160.22
#Sta/Elev= 30
  4651.1  337.57  4687.2  332.94  4694.7  330.42  4802.8  312.68  4823.9  310.18
  4848.2  310.74  4946.3  311.28  4953.1  311.29  4962.1   308.6  4968.5  309.29
  4975.6  302.58  4980.1  301.36  4982.9  300.86  4986.1  301.36  5019.3  301.82
  5025.2  308.67  5040.6  310.91  5055.9   307.5  5061.8  311.13  5070.6  309.14
    5083  312.04  5111.6  312.47  5171.5   311.8  5177.3   313.1  5223.3  313.94
    5287  320.67  5417.9  338.62  5433.2   342.4    5448  342.53  5483.4  348.08
#Mann= 7 ,-1 , 0
  4651.1     .12       0  4848.2     .16       0  4946.3     .12       0
  4968.5     .16       0  4980.1     .07       0  4986.1     .16       0
  5111.6     .05       0
Bank Sta=4802.8,5177.3
XS Rating Curve= 0 ,0
Exp/Cntr=0.3,0.1

Type RM Length L Ch R = 1 ,18583   ,308,308,308
BEGIN DESCRIPTION:
Mapping XS 7d51eea0
END DESCRIPTION:
XS GIS Cut Line= 2
      3659007.14     10700335.91      3658107.84     10700620.63
#Sta/Elev= 30
  4577.6  332.82  4585.5  332.03    4610  333.85    4617  338.35  4637.1  333.72
  4642.3  335.38  4662.9  335.25  4679.9  336.71  4712.2  333.77  4739.2  327.62
  4763.8  324.41  4771.5  321.41  4841.4  311.59  4868.4  308.72  4970.6  309.99
  4994.6  304.91  4999.9  301.19  5002.6  300.69  5005.9  301.19  5015.6  301.62
    5026  309.94  5040.4  310.09  5057.5  305.61  5067.5  308.92  5078.5  306.39
    5089  309.43  5208.8  310.48  5239.5  310.84  5470.8  315.87  5520.9  318.62
#Mann= 5 ,-1 , 0
  4577.6     .05       0  4662.9     .12       0  4999.9     .07       0
  5005.9     .12       0  5208.8     .05       0
Bank Sta=4841.4,5239.5
XS Rating Curve= 0 ,0
Exp/Cntr=0.3,0.1

Type RM Length L Ch R = 1 ,18275   ,103,103,103
BEGIN DESCRIPTION:
HALL BRANCH 39.0
END DESCRIPTION:
XS GIS Cut Line= 2
      3659080.07     10700207.45      3657979.35     10700148.42
#Sta/Elev= 30
  4429.4  342.42  4473.3  342.31    4520  340.49    4550  335.75  4610.1  329.69
  4656.8  321.18  4661.8  321.75  4700.2  318.11  4830.4  311.32  4920.6  308.36
  4970.6  306.15  4990.7  303.22  4997.7   300.5  5000.4     300  5003.7   300.5
  5010.7  300.57  5040.7  307.23  5080.8  308.87  5180.9  309.66  5222.3  311.41
    5251  313.12  5271.1  315.98  5281.1  316.24  5341.2  322.42  5371.2  326.91
  5391.2  327.45  5421.3  332.24  5501.4  336.03  5521.4  336.38  5531.7  335.57
#Mann= 3 ,-1 , 0
  4429.4     .05       0  4997.7     .04       0  5003.7     .05       0
Bank Sta=4920.6,5080.8
XS Rating Curve= 0 ,0
Exp/Cntr=0.3,0.1

Type RM Length L Ch R = 1 ,18172   ,241,241,241
BEGIN DESCRIPTION:
HALL BRANCH 38.0
END DESCRIPTION:
XS GIS Cut Line= 2
      3659073.11     10700106.75      3657989.71     10700044.25
#Sta/Elev= 30
  4430.4  343.56  4554.1   340.7  4604.7     337  4630.2  334.02  4644.3  334.16
  4656.3  332.21  4684.3  328.66  4754.4  314.85  4774.5  312.26  4807.2  309.59
  4864.6   308.2  4964.8  307.96  4974.1  302.97  4979.1  303.81  4984.8  298.84
  5001.9  297.97  5004.6  297.47  5007.9  297.97  5034.9  305.69  5054.9  307.42
    5095  308.24  5156.1  309.72  5195.2  312.67  5235.2  316.79  5273.6  323.59
  5285.3  326.19  5315.4  328.39  5335.4  332.45  5372.5  334.76  5515.6  339.27
#Mann= 7 ,-1 , 0
  4430.4     .05       0  4604.7     .08       0  4656.3     .05       0
  5001.9     .03       0  5007.9     .05       0  5273.6     .08       0
  5372.5     .05       0
Bank Sta=4864.6,5095
XS Rating Curve= 0 ,0
Exp/Cntr=0.3,0.1

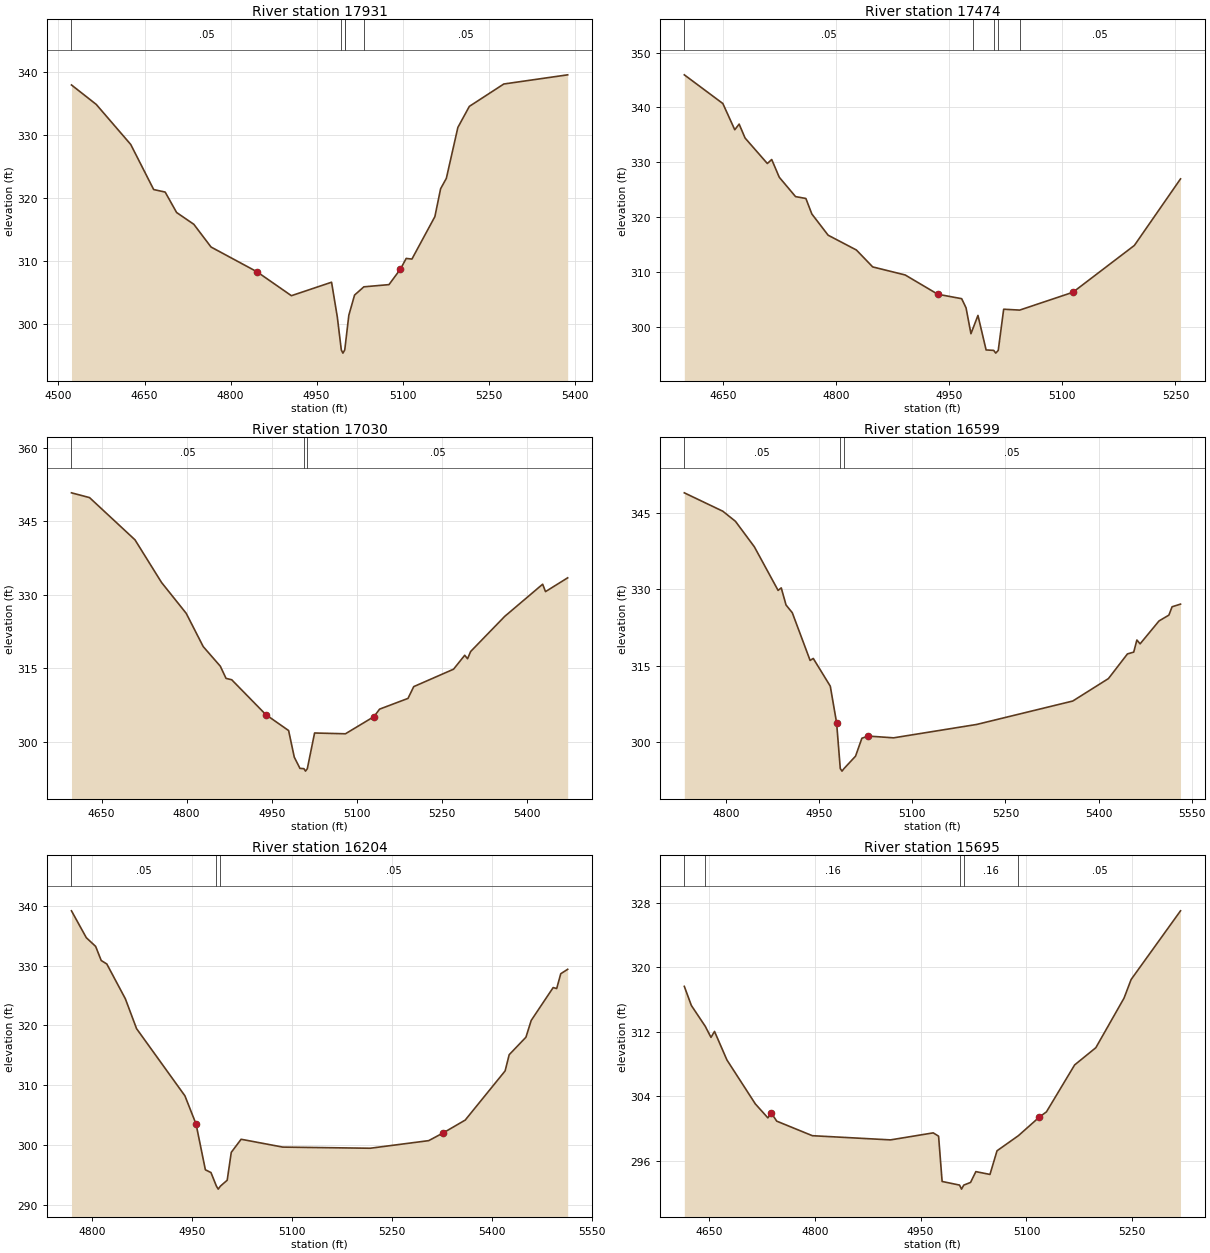
Type RM Length L Ch R = 1 ,17931   ,457,457,457
BEGIN DESCRIPTION:
Mapping XS a802b44f
END DESCRIPTION:
XS GIS Cut Line= 2
      3658982.81     10699853.28      3658118.26      10699825.5
#Sta/Elev= 30
  4522.7  337.96  4565.9  334.87    4626  328.51    4666  321.35    4686  320.95
    4706   317.7    4736  315.83    4766  312.22  4846.1  308.29  4906.1  304.49
  4976.1  306.63  4986.1  301.12  4993.1  295.87  4995.9  295.37  4999.1  295.87
  4999.2  295.95  5006.2  301.39  5016.2  304.59  5032.4   305.9  5076.2  306.25
  5096.2  308.72  5106.2  310.41  5116.2  310.31  5156.2  317.05  5166.2  321.48
  5176.2  323.13  5196.3  331.22  5216.3  334.56  5276.3  338.11  5387.7  339.57
#Mann= 5 ,-1 , 0
  4522.7     .05       0  4993.1     .07       0  4999.1     .05       0
  4999.2     .16       0  5032.4     .05       0
Bank Sta=4846.1,5096.2
XS Rating Curve= 0 ,0
Exp/Cntr=0.3,0.1

Type RM Length L Ch R = 1 ,17474   ,444,444,444
BEGIN DESCRIPTION:
HALL BRANCH 37.0
END DESCRIPTION:
XS GIS Cut Line= 3
      3658849.59      10699210.2      3658499.61     10699410.19
      3658249.64     10699460.18
#Sta/Elev= 30
  4598.7  345.94  4649.8  340.71  4665.6  335.93  4671.4  336.96  4679.3  334.42
  4708.8  329.78  4714.6  330.51  4724.6  327.28  4746.2  323.75  4759.9  323.41
  4767.8  320.59  4789.4  316.72  4826.9  314.02  4848.5  310.94  4891.6  309.47
  4934.8  305.96  4966.5  305.15  4972.3  303.48  4978.8  298.77  4981.2  299.63
  4988.1   302.1  4998.9  295.81    5009  295.73  5011.7  295.23    5015  295.73
  5022.2  303.23  5043.4  303.07    5114  306.32  5195.5  314.85  5256.7  326.98
#Mann= 5 ,-1 , 0
  4598.7     .05       0  4981.2     .16       0    5009     .07       0
    5015     .16       0  5043.4     .05       0
Bank Sta=4934.8,5114
XS Rating Curve= 0 ,0
Exp/Cntr=0.3,0.1

Type RM Length L Ch R = 1 ,17030   ,431,431,431
BEGIN DESCRIPTION:
HALL BRANCH 36.0
END DESCRIPTION:
XS GIS Cut Line= 2
      3658881.31     10698943.24      3658008.94     10699008.34
#Sta/Elev= 30
    4597  350.79  4628.8  349.82    4709  341.21  4755.8  332.52  4799.3  326.23
  4829.3  319.45  4859.4  315.46  4869.5  312.98  4879.5   312.7  4939.7  305.59
  4979.8  302.35  4989.8  296.93  4999.8  294.64  5006.8  294.58  5009.6  294.08
  5012.8  294.58  5025.6  301.85    5080  301.69  5130.2  305.18  5140.2  306.71
  5190.3   308.9  5200.4   311.3  5270.6  314.85  5290.3  317.69  5295.3  316.98
  5300.7  318.45  5360.8  325.61  5427.7  332.17  5432.7  330.66  5471.8  333.47
#Mann= 3 ,-1 , 0
    4597     .05       0  5006.8     .03       0  5012.8     .05       0
Bank Sta=4939.7,5130.2
XS Rating Curve= 0 ,0
Exp/Cntr=0.3,0.1

Type RM Length L Ch R = 1 ,16599   ,395,395,395
BEGIN DESCRIPTION:
HALL BRANCH 35.0
END DESCRIPTION:
XS GIS Cut Line= 2
      3658840.45     10698634.53      3658055.68     10698481.74
#Sta/Elev= 30
  4732.6  348.88  4794.6  345.28    4815   343.3  4845.5   338.3  4883.7  329.77
  4888.8  330.26  4896.5  326.91  4906.6  325.39  4935.3  316.05  4940.4  316.44
  4967.8  311.01    4978  303.83  4983.9  294.87  4986.7  294.37  4989.9  294.87
  5008.5   297.3  5018.7  300.81  5028.9  301.24  5069.7  300.89  5203.6  303.51
  5358.5   308.1    5416   312.5  5446.6  317.33  5456.7  317.68  5461.8  320.05
    5467   319.3  5497.5  323.79  5513.4  324.93  5518.5  326.56  5532.1  327.08
#Mann= 3 ,-1 , 0
  4732.6     .05       0  4983.9     .03       0  4989.9     .05       0
Bank Sta=4978,5028.9
XS Rating Curve= 0 ,0
Exp/Cntr=0.3,0.1

Type RM Length L Ch R = 1 ,16204   ,509,509,509
BEGIN DESCRIPTION:
HALL BRANCH 34.0
END DESCRIPTION:
XS GIS Cut Line= 3
      3658799.58     10698310.17      3658599.61     10698210.19
       3658099.6     10698060.19
#Sta/Elev= 30
  4768.5  339.14  4790.8  334.65  4804.8   333.2  4813.2  330.84  4821.6  330.26
  4849.5  324.44  4866.3  319.46    4939  308.23  4955.7  303.52  4969.7  295.88
  4978.1  295.42  4986.3  293.15    4989  292.65  4992.3  293.15  5002.5  294.14
  5008.6  298.79  5023.4  300.98    5086  299.67  5217.4  299.48  5305.3  300.75
    5327  302.04  5360.1  304.18  5420.1   312.4  5426.2   315.1  5451.4  318.03
  5459.3  320.83  5492.3  326.32  5497.6  326.16  5503.7  328.63  5514.1  329.37
#Mann= 3 ,-1 , 0
  4768.5     .05       0  4986.3     .03       0  4992.3     .05       0
Bank Sta=4955.7,5327
XS Rating Curve= 0 ,0
Exp/Cntr=0.3,0.1

Type RM Length L Ch R = 1 ,15695   ,319,319,319
BEGIN DESCRIPTION:
HALL BRANCH 33.0
END DESCRIPTION:
XS GIS Cut Line= 3
      3658849.58     10697860.19      3658449.61     10697910.19
      3658149.59     10697910.19
#Sta/Elev= 30
  4615.2  317.64  4625.2  315.27  4644.9  312.69    4653  311.32    4658  312.06
  4675.6  308.52  4715.9  303.07  4733.6  301.35  4738.6  301.92  4746.2  300.94
  4796.6  299.14  4907.4  298.62  4967.9  299.49  4975.5  299.08  4980.5  293.47
  5005.2  293.02    5008  292.52  5011.2  293.02  5020.8  293.35  5028.3  294.69
  5048.3  294.34  5058.3  297.27  5088.7  299.15  5118.3  301.45  5128.3  302.09
  5168.3  307.91  5198.3  310.04  5238.3  316.19  5248.3  318.49  5318.3     327
#Mann= 5 ,-1 , 0
  4615.2     .12       0  4644.9     .16       0  5005.2     .07       0
  5011.2     .16       0  5088.7     .05       0
Bank Sta=4738.6,5118.3
XS Rating Curve= 0 ,0
Exp/Cntr=0.3,0.1

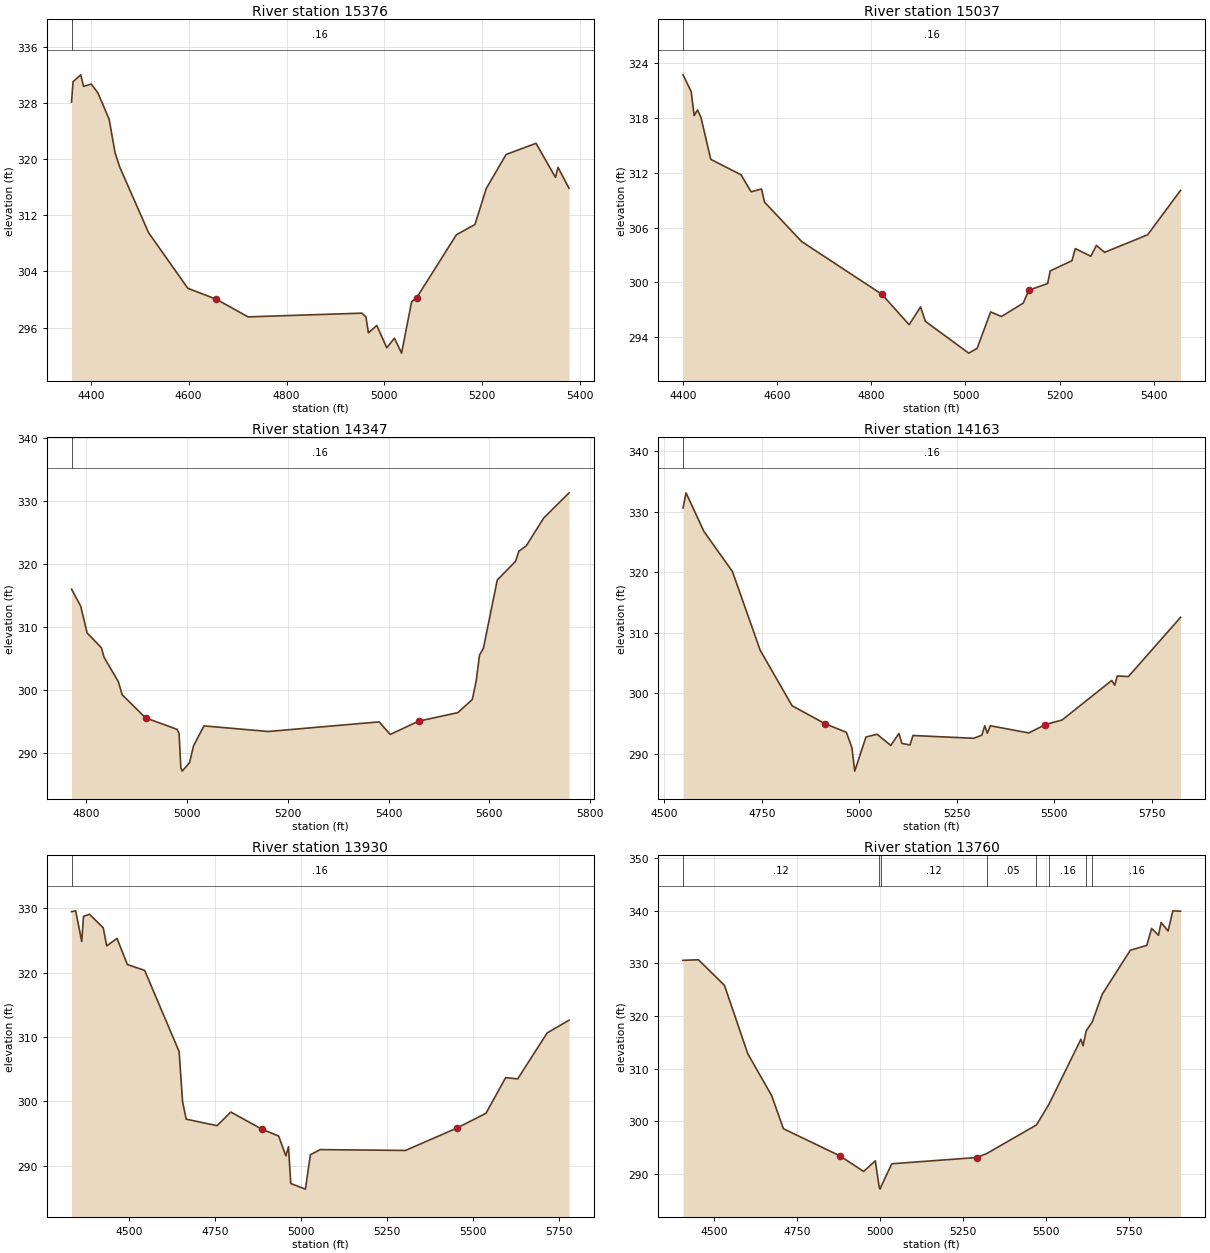
Type RM Length L Ch R = 1 ,15376   ,339,339,339
BEGIN DESCRIPTION:
HALL BRANCH 32.0
END DESCRIPTION:
XS GIS Cut Line= 3
      3658975.88      10697877.6       3658496.7     10697596.33
      3658043.17     10697679.42
#Sta/Elev= 30
  4360.7  328.11  4363.8     331  4379.5  331.98  4385.3  330.33    4401  330.67
  4414.4  329.43  4437.5  325.67  4449.7  320.87  4459.6  318.78  4518.2  309.51
  4598.3   301.6  4656.9  300.03  4721.3  297.53    4954  298.06  4962.3  297.53
  4967.4  295.25  4984.5  296.31  5004.9  293.13  5020.5   294.5  5035.1  292.37
  5055.7  299.69  5065.9  300.24  5147.2  309.22  5185.1  310.67  5208.2   315.8
  5248.9  320.65  5309.9  322.23  5349.7  317.38  5354.8  318.81  5377.4  315.83
#Mann= 1 ,-1 , 0
  4360.7     .16       0
Bank Sta=4656.9,5065.9
XS Rating Curve= 0 ,0
Exp/Cntr=0.3,0.1

Type RM Length L Ch R = 1 ,15037   ,690,690,690
BEGIN DESCRIPTION:
HALL BRANCH 31.0
END DESCRIPTION:
XS GIS Cut Line= 3
      3658708.48     10696915.81      3658402.95     10697311.61
      3657896.04     10697540.76
#Sta/Elev= 30
  4400.3  322.68  4417.6  320.86  4423.9  318.23  4431.1  318.84  4438.4  318.02
  4459.2  313.45  4523.5  311.76  4544.8   309.9    4567  310.21  4573.3  308.78
  4652.1  304.47  4822.7   298.7  4880.4  295.38  4904.6  297.33  4914.9  295.75
  5006.9  292.28  5024.7   292.8  5053.4  296.78  5076.5  296.28  5122.7  297.75
  5134.4  299.15  5174.4  299.88  5179.9  301.26  5226.1  302.38  5233.2   303.7
  5266.1  302.86  5277.9  304.04  5295.5  303.29  5386.8  305.21  5456.6  310.06
#Mann= 1 ,-1 , 0
  4400.3     .16       0
Bank Sta=4822.7,5134.4
XS Rating Curve= 0 ,0
Exp/Cntr=0.3,0.1

Type RM Length L Ch R = 1 ,14347   ,184,184,184
BEGIN DESCRIPTION:
HALL BRANCH 30.0
END DESCRIPTION:
XS GIS Cut Line= 3
      3658299.65      10696760.2      3658099.61     10696710.19
      3657599.62     10697310.17
#Sta/Elev= 30
  4770.8  315.98  4788.9   313.3  4801.8  309.02  4830.1  306.67  4835.3  305.16
  4863.6  301.29  4871.3   299.2  4917.7  295.53  4980.2   293.7  4984.2  293.05
  4987.7  287.56  4990.4  287.06    5005  288.42  5012.8  291.07  5033.6  294.25
  5161.2  293.36  5381.2  294.89  5403.3  292.89  5459.3     295  5537.4  296.36
    5566  298.44  5573.8  301.41  5580.3  305.49  5588.1   306.6  5615.5  317.43
  5651.9  320.42  5658.4  322.02  5672.8  322.85  5707.9  327.31    5758   331.3
#Mann= 1 ,-1 , 0
  4770.8     .16       0
Bank Sta=4917.7,5459.3
XS Rating Curve= 0 ,0
Exp/Cntr=0.3,0.1

Type RM Length L Ch R = 1 ,14163   ,233,233,233
BEGIN DESCRIPTION:
Mapping XS 74943c0e
END DESCRIPTION:
XS GIS Cut Line= 3
      3658423.74     10696453.98      3658041.83     10696530.36
      3657373.15     10697112.43
#Sta/Elev= 30
  4547.8  330.65  4555.5  333.15  4601.4  326.77  4674.4  320.16  4745.8  307.12
  4827.4  297.96  4912.5  294.97  4966.7  293.57  4980.9  291.04  4988.2  287.15
    5017  292.79  5045.4  293.25  5080.6   291.4  5101.4  293.37  5109.1  291.74
  5129.9  291.47  5137.5  293.04  5293.2  292.58  5314.1  293.09  5321.7  294.65
  5328.4  293.43    5336  294.65  5434.7  293.46  5477.4  294.85  5520.2  295.61
  5647.4  302.14    5655  301.36  5661.6  302.88  5690.1  302.78  5823.8  312.56
#Mann= 1 ,-1 , 0
  4547.8     .16       0
Bank Sta=4912.5,5477.4
XS Rating Curve= 0 ,0
Exp/Cntr=0.3,0.1

Type RM Length L Ch R = 1 ,13930   ,170,170,170
BEGIN DESCRIPTION:
HALL BRANCH 29.0
END DESCRIPTION:
XS GIS Cut Line= 3
      3658451.54       10696263.      3657989.75     10696294.25
      3657244.74     10696935.31
#Sta/Elev= 30
  4332.6  329.46  4344.6  329.59  4362.3  324.82  4367.3  328.72  4384.6  329.06
  4424.7  326.95  4434.8  324.14  4464.8   325.3  4494.9  321.24    4545  320.34
  4645.2  307.73  4655.3  299.92  4665.8  297.22  4755.5  296.21  4795.4  298.33
  4885.1  295.68  4934.5  294.59  4955.4  291.52    4963  292.94  4969.6  287.22
  5012.2  286.35  5026.7   291.7  5055.2  292.49  5303.2  292.36  5452.4  295.84
  5536.9  298.13    5594  303.67  5629.1  303.48  5714.6  310.61  5778.3   312.6
#Mann= 1 ,-1 , 0
  4332.6     .16       0
Bank Sta=4885.1,5452.4
XS Rating Curve= 0 ,0
Exp/Cntr=0.3,0.1

Type RM Length L Ch R = 1 ,13760   ,294,294,294
BEGIN DESCRIPTION:
Mapping XS c1f16ae5
END DESCRIPTION:
XS GIS Cut Line= 2
      3658239.72     10695905.39      3657066.13      10696839.4
#Sta/Elev= 30
  4406.4  330.55  4452.8  330.66  4531.3  325.81  4601.7  312.82  4673.8  304.86
    4709   298.6  4879.4  293.45  4950.9  290.49  4986.1  292.51  4997.5  287.64
  5000.3  287.14  5003.5  287.64  5035.8  291.95    5292  293.14  5321.7  293.88
  5471.8  299.31  5509.7  303.26    5606  315.58  5612.4  314.34  5621.9  317.17
  5640.2  318.86  5670.1   324.1  5754.9  332.47  5804.6  333.38    5819  336.61
  5839.8   335.3  5847.8  337.72  5868.7  336.11  5883.1  339.94  5906.3  339.87
#Mann= 8 ,-1 , 0
  4406.4     .12       0  4997.5     .07       0  5003.5     .12       0
  5321.7     .05       0  5471.8     .08       0  5509.7     .16       0
  5621.9     .05       0  5640.2     .16       0
Bank Sta=4879.4,5292
XS Rating Curve= 0 ,0
Exp/Cntr=0.3,0.1