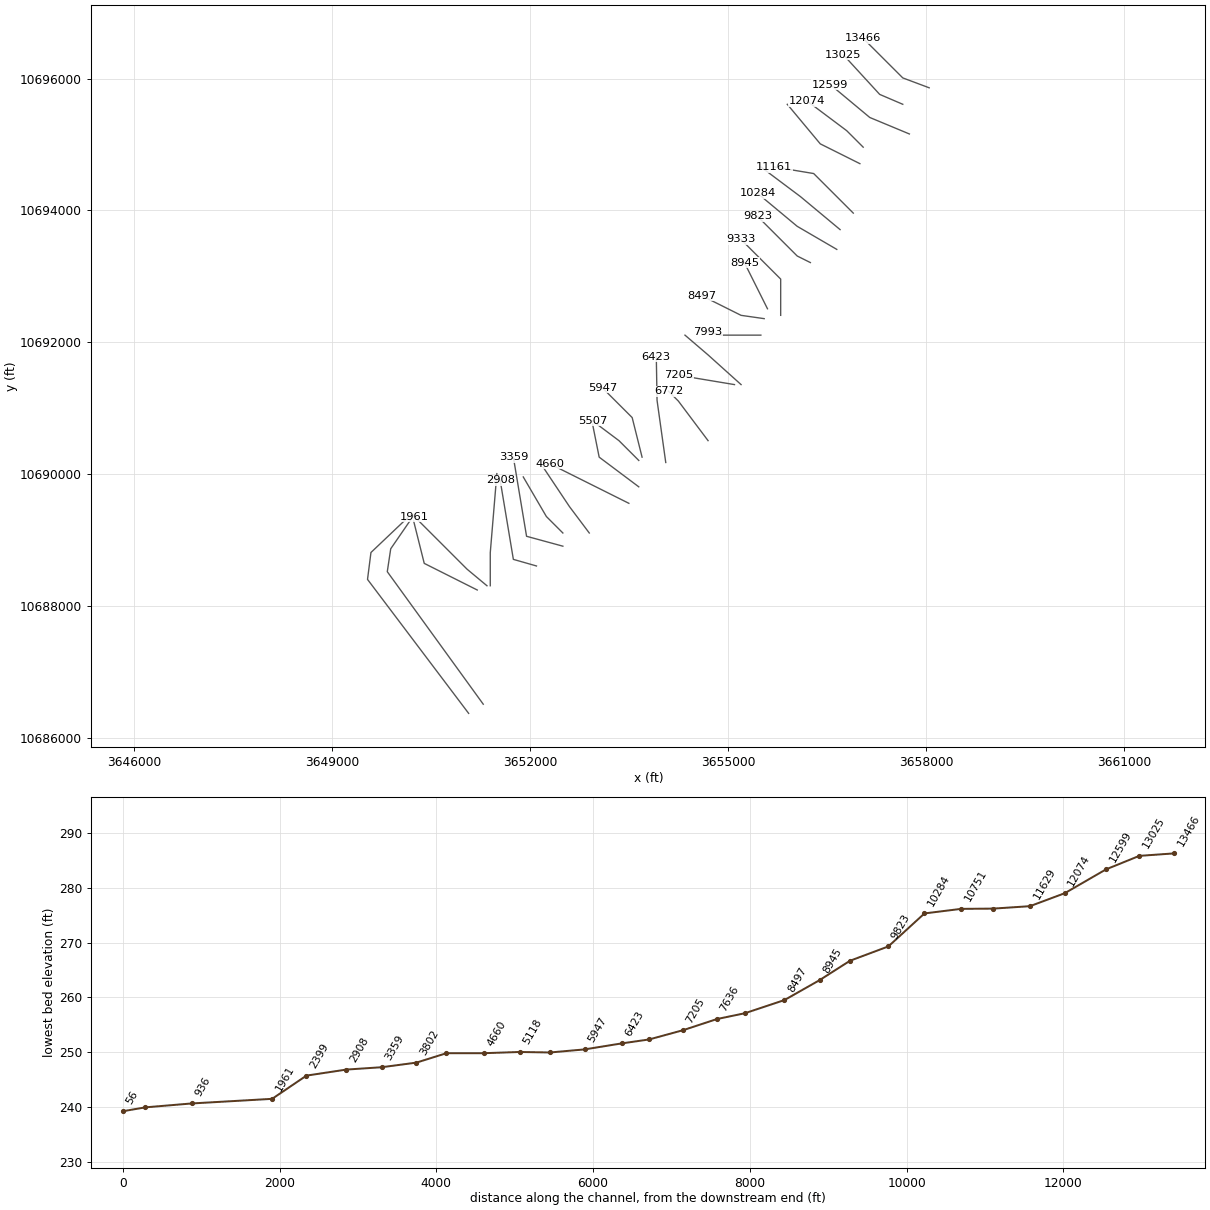
HEC-RAS study HALL BRANCH.prj: HALL BRANCH Base Level Engineering

--- HALL BRANCH.g01 (geometry) --- (continued)

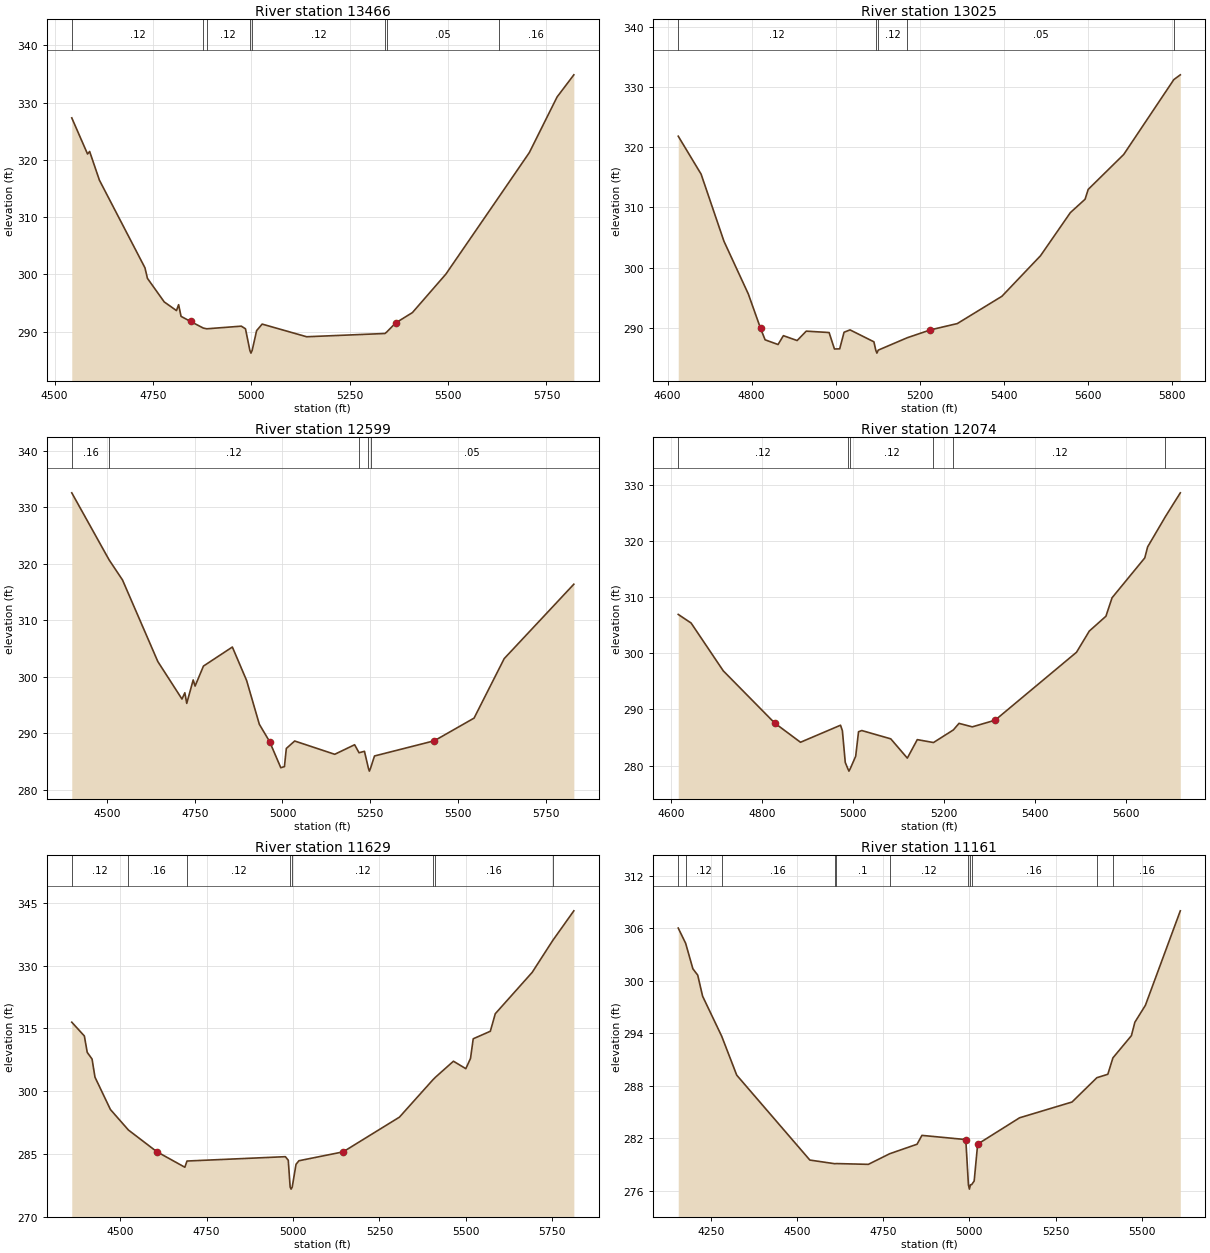
Type RM Length L Ch R = 1 ,13466   ,441,441,441
BEGIN DESCRIPTION:
HALL BRANCH 28.0
END DESCRIPTION:
XS GIS Cut Line= 3
      3658049.64     10695860.18      3657649.61     10696010.19
      3657049.58     10696610.21
#Sta/Elev= 30
  4543.8  327.35  4583.9  321.04  4589.2  321.48  4614.1  316.46  4729.8  301.16
  4736.1  299.32  4778.8   295.2  4809.9  293.69  4815.3  294.72  4821.5  292.68
  4845.5   291.8  4877.9  290.64  4886.8  290.51  4974.6  290.97  4985.2  290.51
  4996.3  286.76  4999.1  286.26  5002.3  286.76  5013.5  290.19  5027.6  291.33
  5140.7  289.12  5339.6  289.69    5344  289.94    5367  291.54  5409.4  293.34
  5494.3  300.05  5628.9  313.51  5706.4  321.28  5777.1  331.01  5819.6  334.87
#Mann= 8 ,-1 , 0
  4543.8     .12       0  4877.9     .16       0  4886.8     .12       0
  4996.3     .07       0  5002.3     .12       0  5339.6     .16       0
    5344     .05       0  5628.9     .16       0
Bank Sta=4845.5,5367
XS Rating Curve= 0 ,0
Exp/Cntr=0.3,0.1

Type RM Length L Ch R = 1 ,13025   ,426,426,426
BEGIN DESCRIPTION:
HALL BRANCH 27.0
END DESCRIPTION:
XS GIS Cut Line= 3
      3657649.59      10695610.2      3657299.61     10695760.19
      3656749.62     10696360.18
#Sta/Elev= 30
  4625.3  321.84  4679.7  315.54  4734.1  304.39  4792.1  295.63  4821.1  289.94
    4832  288.02  4862.8  287.24  4875.5  288.71  4908.2   287.9  4929.9  289.46
  4984.3  289.23    4997   286.5  5009.5  286.52  5019.9  289.28  5034.1  289.67
  5090.9  287.69  5095.3  286.31    5098  285.81  5101.3  286.31  5170.4  288.37
  5225.3  289.67  5289.4  290.72  5395.5  295.25  5487.3  301.98  5558.3  309.14
  5593.4  311.37  5600.8     313  5685.3   318.8  5804.6  331.24    5820  332.03
#Mann= 5 ,-1 , 0
  4625.3     .12       0  5095.3     .07       0  5101.3     .12       0
  5170.4     .05       0  5804.6     .16       0
Bank Sta=4821.1,5225.3
XS Rating Curve= 0 ,0
Exp/Cntr=0.3,0.1

Type RM Length L Ch R = 1 ,12599   ,525,525,525
BEGIN DESCRIPTION:
HALL BRANCH 26.0
END DESCRIPTION:
XS GIS Cut Line= 3
      3657749.57      10695160.2      3657149.61     10695410.19
       3656549.6      10695910.2
#Sta/Elev= 30
  4399.5  332.59  4505.9  320.73  4544.1  317.17  4644.8  302.73  4713.6   296.1
  4721.8  297.21  4727.2  295.33  4745.6  299.48    4751  298.39  4774.8  301.93
  4857.2   305.3  4897.8  299.39  4934.1  291.63  4963.3  288.58  4995.3  283.94
  5005.6  284.14    5011  287.35  5034.8  288.67    5149  286.32  5205.7  288.01
  5218.3  286.59  5233.7  286.85    5245  283.84  5247.7  283.34    5251  283.84
  5262.3  286.02  5432.8  288.71  5546.1  292.72    5632  303.25  5830.5  316.42
#Mann= 5 ,-1 , 0
  4399.5     .16       0  4505.9     .12       0  5218.3     .05       0
    5245     .07       0    5251     .05       0
Bank Sta=4963.3,5432.8
XS Rating Curve= 0 ,0
Exp/Cntr=0.3,0.1

Type RM Length L Ch R = 1 ,12074   ,445,445,445
BEGIN DESCRIPTION:
HALL BRANCH 25.0
END DESCRIPTION:
XS GIS Cut Line= 3
       3657049.6     10694960.19      3656799.61     10695210.19
      3656199.65     10695660.16
#Sta/Elev= 30
  4615.4  306.96  4643.7  305.42  4714.4  296.89  4827.5  287.57  4884.1  284.15
  4972.1  287.19  4976.2  286.21  4982.5  280.56  4987.8   279.5  4990.6     279
  4993.8   279.5  5005.4  281.65  5011.7  286.03  5018.9  286.24  5082.5  284.76
  5118.9  281.32  5140.8  284.62  5176.4   284.1  5220.1  286.35  5232.5  287.52
  5261.7   286.9  5311.7  288.08  5490.8  300.21  5518.9  303.99  5555.4  306.63
  5568.9  309.93  5640.8  317.04  5647.1  319.01  5686.1   324.4  5718.9  328.65
#Mann= 6 ,-1 , 0
  4615.4     .12       0  4987.8     .07       0  4993.8     .12       0
  5176.4     .16       0  5220.1     .12       0  5686.1     .12       0
Bank Sta=4827.5,5311.7
XS Rating Curve= 0 ,0
Exp/Cntr=0.3,0.1

Type RM Length L Ch R = 1 ,11629   ,468,468,468
BEGIN DESCRIPTION:
HALL BRANCH 24.0
END DESCRIPTION:
XS GIS Cut Line= 3
      3656999.63     10694710.18      3656399.61     10695010.19
      3655899.59     10695610.21
#Sta/Elev= 30
  4360.3   316.5  4396.7  313.21    4405   309.3    4419  307.69  4427.4  303.38
  4472.1  295.64  4524.2  290.74  4606.3  285.57  4687.3  281.86  4693.5  283.34
    4978  284.38  4986.4  283.53  4991.8  277.13  4994.6  276.63  4997.8  277.13
  5008.8  282.55  5017.2  283.41    5145  285.53  5307.8  293.82  5403.9  302.68
  5411.8  303.34    5464  307.18  5499.8   305.4  5513.4  307.85  5521.2  312.54
  5570.7  314.34    5585  318.52  5691.8  328.41  5751.1  336.01  5812.2   343.1
#Mann= 8 ,-1 , 0
  4360.3     .12       0  4524.2     .16       0  4693.5     .12       0
  4991.8     .07       0  4997.8     .12       0  5403.9     .12       0
  5411.8     .16       0  5751.1     .12       0
Bank Sta=4606.3,5145
XS Rating Curve= 0 ,0
Exp/Cntr=0.3,0.1

Type RM Length L Ch R = 1 ,11161   ,410,410,410
BEGIN DESCRIPTION:
HALL BRANCH 23.0
END DESCRIPTION:
XS GIS Cut Line= 3
      3656899.63     10693960.17      3656299.61     10694560.19
      3655699.64     10694660.18
#Sta/Elev= 30
  4155.3  306.01  4176.8  304.27  4197.8  301.36  4211.9  300.63    4226  298.23
  4281.5  293.65    4325  289.21  4537.2  279.51  4609.9  279.09  4613.6  279.11
  4706.9  279.02  4768.7  280.23  4848.3  281.32  4862.4  282.33  4989.7  281.85
  4997.3  276.69  5000.1  276.19  5003.3  276.69  5006.6   276.7    5014  277.12
  5024.1  281.33  5145.8  284.34  5297.9  286.14  5370.1  288.92  5401.8  289.31
  5416.5  291.18  5470.2  293.72  5480.3  295.26  5510.7  297.18  5612.1  307.98
#Mann= 11 ,-1 , 0
  4155.3     .05       0  4176.8     .12       0  4281.5     .16       0
  4609.9     .12       0  4613.6      .1       0  4768.7     .12       0
  4997.3     .07       0  5003.3     .12       0  5006.6     .16       0
  5370.1     .12       0  5416.5     .16       0
Bank Sta=4989.7,5024.1
XS Rating Curve= 0 ,0
Exp/Cntr=0.3,0.1

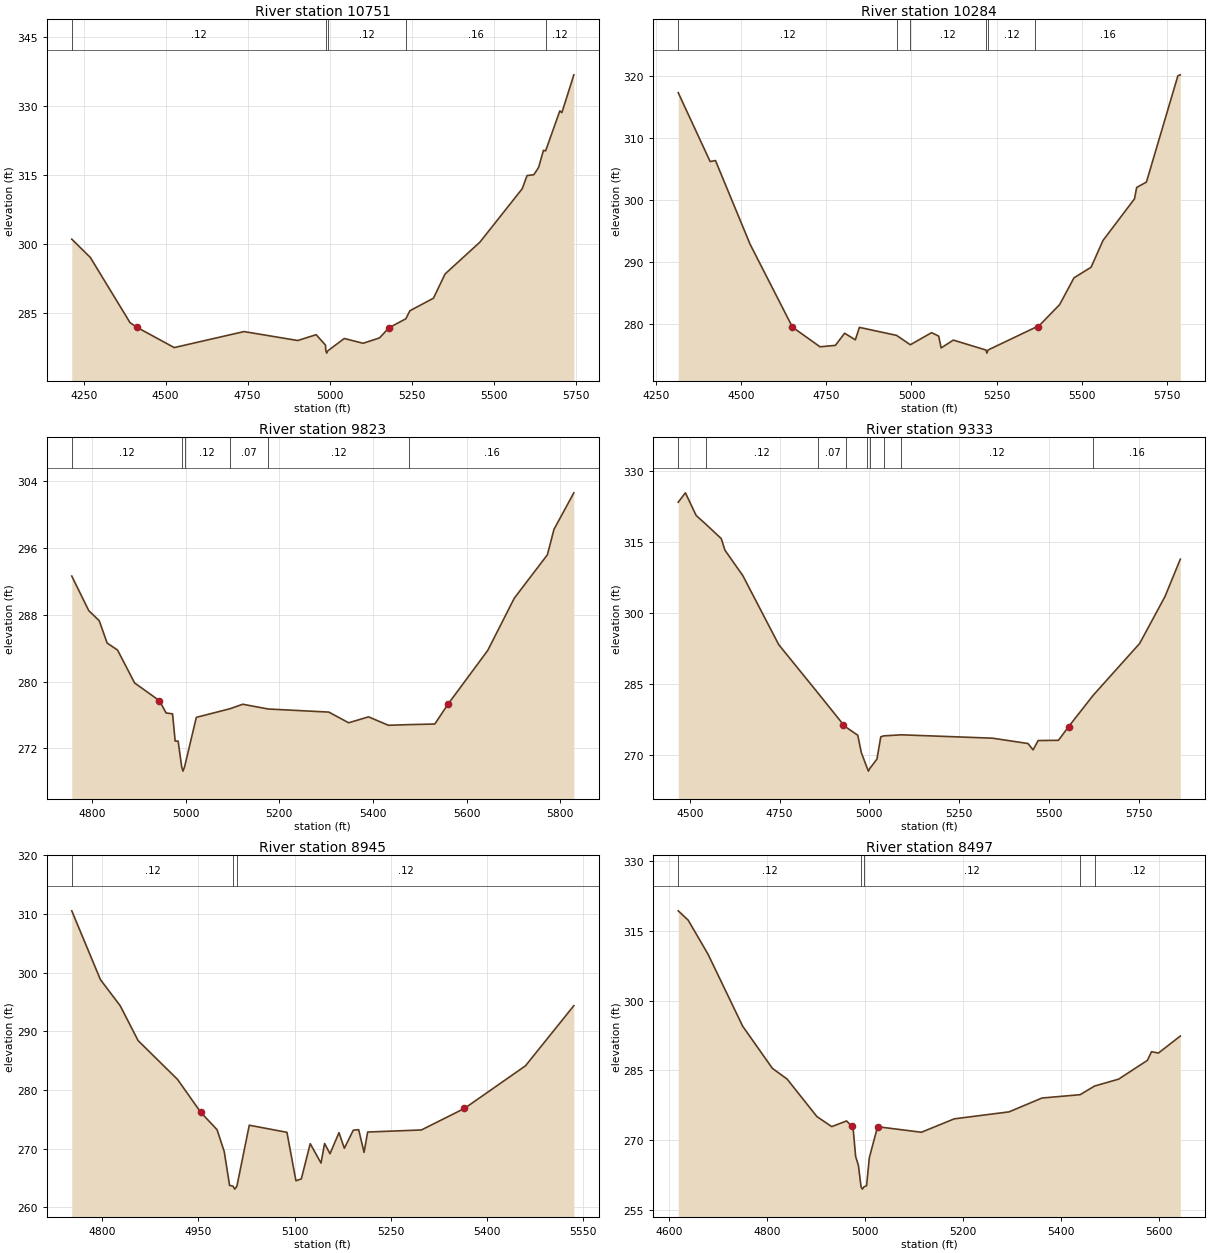
Type RM Length L Ch R = 1 ,10751   ,467,467,467
BEGIN DESCRIPTION:
HALL BRANCH 22.0
END DESCRIPTION:
XS GIS Cut Line= 3
      3656699.57     10693710.22      3656099.61     10694210.19
      3655499.59      10694660.2
#Sta/Elev= 30
  4213.8     301  4270.4  297.01  4391.4   282.8  4412.3  281.78  4526.2  277.35
    4739  280.84    4903  278.89    4959  280.16  4987.6  277.88  4988.5  276.64
  4991.3  276.14  4994.5  276.64  5044.8  279.33  5102.1  278.29  5152.1  279.45
  5181.2  281.67  5232.5  283.63  5244.8  285.38  5316.7  288.12  5352.1   293.4
  5458.3  300.34  5587.5  312.01  5602.1  314.86  5622.9  315.06  5637.5  316.66
  5652.1  320.37  5658.7  320.25  5702.1  328.98  5708.3  328.59  5744.8  336.84
#Mann= 5 ,-1 , 0
  4213.8     .12       0  4988.5     .07       0  4994.5     .12       0
  5232.5     .16       0  5658.7     .12       0
Bank Sta=4412.3,5181.2
XS Rating Curve= 0 ,0
Exp/Cntr=0.3,0.1

Type RM Length L Ch R = 1 ,10284   ,461,461,461
BEGIN DESCRIPTION:
HALL BRANCH 21.0
END DESCRIPTION:
XS GIS Cut Line= 3
      3656649.58     10693410.21      3656049.61     10693760.19
      3655449.62     10694260.18
#Sta/Elev= 30
  4314.5  317.29  4408.3  306.19    4424  306.35  4525.7  292.86  4650.2   279.5
  4731.2  276.33  4776.3  276.56  4803.6  278.52    4835  277.45    4847  279.46
  4956.3  278.17  4996.6  276.66  5059.2  278.61    5080  278.05  5087.2  276.15
    5123  277.41  5218.9  275.81  5221.7  275.31  5224.9  275.81  5364.4  279.46
  5371.6  279.52  5435.4  283.13  5477.7  287.45  5527.8  289.15    5563  293.48
  5655.4  300.18  5661.9  302.02  5690.5  302.88    5783  320.02  5790.1  320.17
#Mann= 6 ,-1 , 0
  4314.5     .12       0  4956.3     .07       0  4996.6     .12       0
  5218.9     .07       0  5224.9     .12       0  5364.4     .16       0
Bank Sta=4650.2,5371.6
XS Rating Curve= 0 ,0
Exp/Cntr=0.3,0.1

Type RM Length L Ch R = 1 ,9823    ,490,490,490
BEGIN DESCRIPTION:
HALL BRANCH 20.0
END DESCRIPTION:
XS GIS Cut Line= 3
      3656249.62     10693210.19      3656049.61     10693310.19
      3655449.64     10693910.16
#Sta/Elev= 30
    4757  292.65  4793.3  288.51  4815.7   287.3  4832.5  284.63  4854.8  283.79
  4891.2  279.85  4944.3  277.72  4958.3  276.26  4972.2  276.15  4977.8  272.89
  4984.1  272.89  4991.8  269.79  4994.5  269.29  4997.8  269.79    5023  275.73
  5094.8  276.76    5122   277.3  5176.7  276.73  5305.9  276.36  5348.3  275.08
  5390.7  275.79  5433.2  274.78  5477.2  274.86  5532.2  274.93  5560.4  277.31
  5645.3  283.75  5701.9     290  5772.6   295.2  5786.7  298.25  5829.1  302.62
#Mann= 6 ,-1 , 0
    4757     .12       0  4991.8     .07       0  4997.8     .12       0
  5094.8     .07       0  5176.7     .12       0  5477.2     .16       0
Bank Sta=4944.3,5560.4
XS Rating Curve= 0 ,0
Exp/Cntr=0.3,0.1

Type RM Length L Ch R = 1 ,9333    ,388,388,388
BEGIN DESCRIPTION:
HALL BRANCH 19.0
END DESCRIPTION:
XS GIS Cut Line= 3
      3655799.61     10692410.14      3655799.61     10692960.19
      3655199.59      10693560.2
#Sta/Elev= 30
  4467.6  323.47  4487.6  325.45  4517.6  320.66  4544.1  318.86  4587.6  315.77
  4597.6  313.35  4647.6  307.95  4747.6  293.38  4857.5  283.11  4927.7  276.48
  4936.2  275.89  4967.7  274.25  4977.7  270.56  4994.7  267.17  4997.4  266.67
  5000.7  267.17  5021.2  269.22  5031.8  273.92  5040.3  274.12  5089.5  274.34
  5342.9  273.63  5441.9   272.5  5456.1  271.16  5470.2  273.13  5526.8  273.18
  5555.1  276.07  5623.4  282.68    5753  293.64  5823.8  303.59  5866.2  311.44
#Mann= 9 ,-1 , 0
  4467.6     .05       0  4544.1     .12       0  4857.5     .07       0
  4936.2     .12       0  4994.7     .07       0  5000.7     .12       0
  5040.3     .07       0  5089.5     .12       0  5623.4     .16       0
Bank Sta=4927.7,5555.1
XS Rating Curve= 0 ,0
Exp/Cntr=0.3,0.1

Type RM Length L Ch R = 1 ,8945    ,448,448,448
BEGIN DESCRIPTION:
HALL BRANCH 18.0
END DESCRIPTION:
XS GIS Cut Line= 3
      3655599.61     10692510.19      3655499.61     10692710.19
      3655249.62     10693210.17
#Sta/Elev= 30
  4752.8  310.55  4797.5  298.82  4828.3  294.38  4856.2  288.44  4917.7  281.82
    4954   276.2  4979.2  273.27  4990.4  269.56  4998.8  263.77  5004.2  263.63
  5006.9  263.13  5010.2  263.63  5029.5  274.02  5088.2  272.81  5102.2  264.56
  5110.6  264.87  5124.5  270.88  5141.3  267.57  5146.9  270.91  5155.3  269.16
  5169.3  272.75  5177.7  270.09  5191.6  273.17    5200  273.26  5208.4  269.39
    5214  272.86  5297.8  273.21  5364.9  276.88    5460  284.14  5535.4  294.39
#Mann= 3 ,-1 , 0
  4752.8     .12       0  5004.2     .07       0  5010.2     .12       0
Bank Sta=4954,5364.9
XS Rating Curve= 0 ,0
Exp/Cntr=0.3,0.1

Type RM Length L Ch R = 1 ,8497    ,504,504,504
BEGIN DESCRIPTION:
HALL BRANCH 17.0
END DESCRIPTION:
XS GIS Cut Line= 3
      3655549.65     10692360.18      3655199.61     10692410.19
      3654599.63     10692710.18
#Sta/Elev= 30
  4618.4  319.29  4638.6   317.3  4679.1  309.99  4749.8  294.52  4810.4  285.46
  4840.7  283.13  4901.3  275.09  4931.6  272.93  4961.9  274.15    4972  273.04
  4974.8  273.04  4980.4   266.5    4986  264.61  4991.4     260  4994.1   259.5
  4997.4     260  5002.7  260.22  5008.3  266.25  5025.1  272.91  5114.5  271.72
  5181.6   274.6  5293.4   276.1  5360.5  279.07  5438.4  279.79    5468  281.65
    5517  283.13  5575.7  287.17  5584.1  289.03  5598.1  288.73  5642.8  292.39
#Mann= 5 ,-1 , 0
  4618.4     .12       0  4991.4     .07       0  4997.4     .12       0
  5438.4     .16       0    5468     .12       0
Bank Sta=4972,5025.1
XS Rating Curve= 0 ,0
Exp/Cntr=0.3,0.1

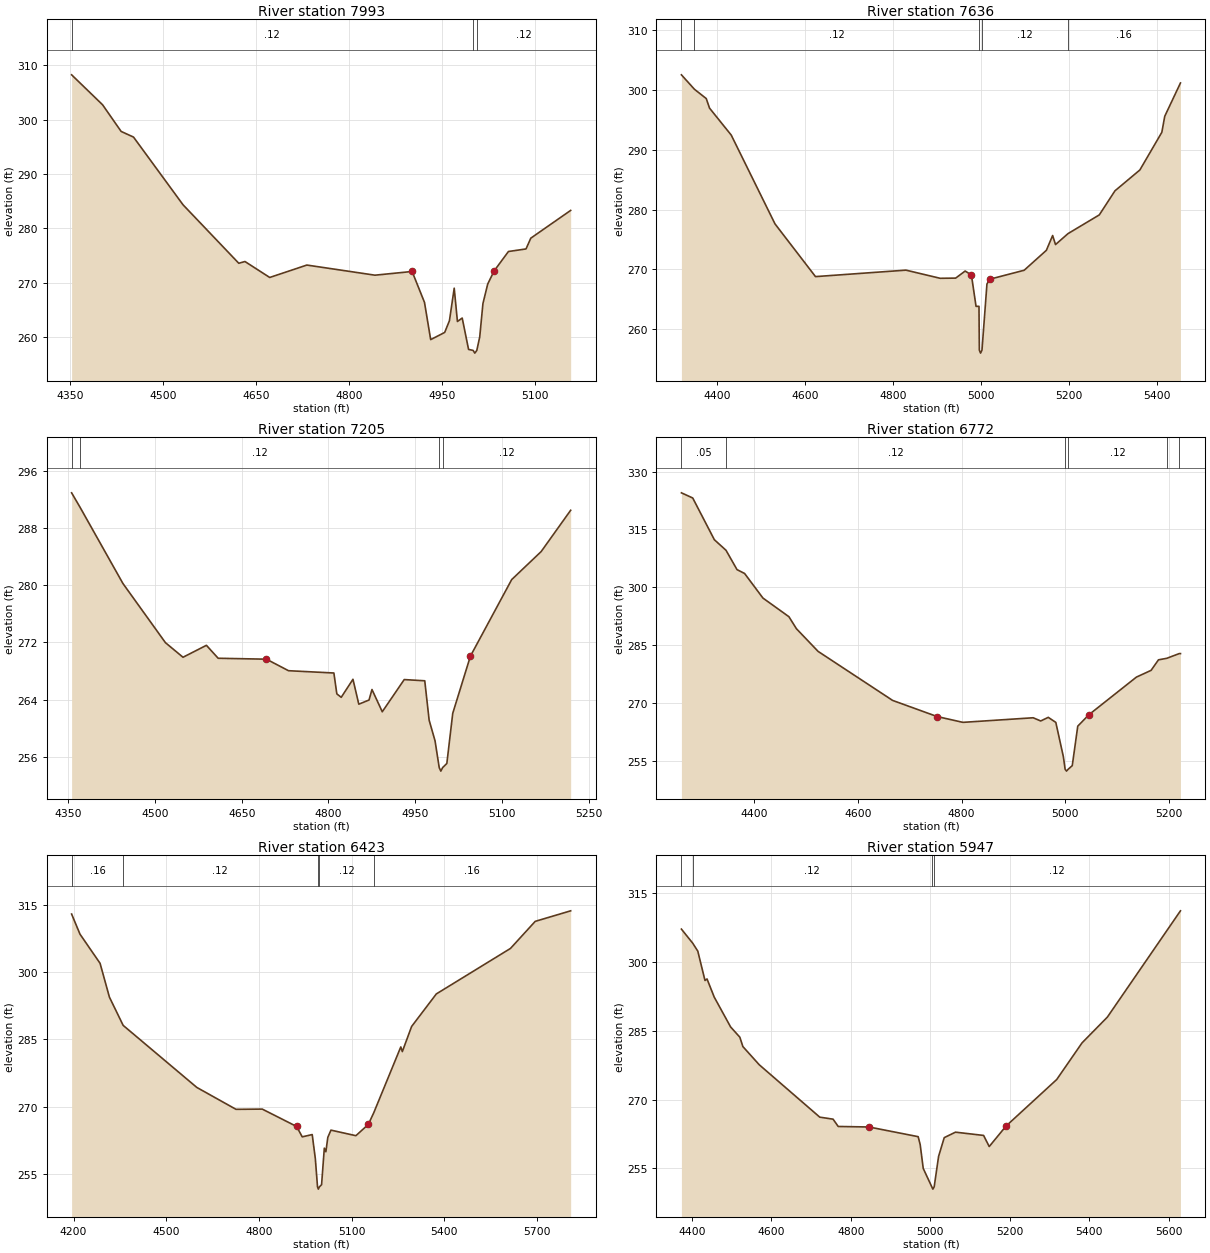
Type RM Length L Ch R = 1 ,7993    ,357,357,357
BEGIN DESCRIPTION:
HALL BRANCH 16.0
END DESCRIPTION:
XS GIS Cut Line= 3
      3655499.58     10692110.19      3654899.61     10692110.19
      3654699.64     10692160.18
#Sta/Elev= 30
  4352.2  308.23  4402.2  302.73  4432.2  297.83  4452.2  296.79  4532.2  284.35
  4622.2  273.61  4632.2  273.93  4672.2     271  4732.2  273.28  4842.2  271.42
  4902.2   272.1  4922.2  266.42  4932.2  259.58  4954.8   260.9  4962.5  263.06
  4970.2  269.03  4975.4  262.91  4983.1  263.55  4993.4  257.78  5000.7   257.6
  5003.5   257.1  5006.7   257.6  5011.4  260.07  5016.6  266.21  5024.3  269.79
  5034.6  272.19  5057.8  275.77  5086.2  276.24  5093.9  278.22  5158.3  283.32
#Mann= 3 ,-1 , 0
  4352.2     .12       0  5000.7     .07       0  5006.7     .12       0
Bank Sta=4902.2,5034.6
XS Rating Curve= 0 ,0
Exp/Cntr=0.3,0.1

Type RM Length L Ch R = 1 ,7636    ,431,431,431
BEGIN DESCRIPTION:
HALL BRANCH 15.0
END DESCRIPTION:
XS GIS Cut Line= 3
       3655199.6     10691360.19      3654699.61     10691810.19
      3654349.57     10692110.22
#Sta/Elev= 30
  4319.5  302.49  4349.1  300.08  4375.9  298.53  4383.4  296.93  4432.7  292.43
  4532.1  277.61  4624.1  268.81  4829.6  269.89  4907.3  268.53  4942.5  268.56
  4964.1  269.74  4978.3  269.09  4988.8  263.85  4995.5  263.85  4996.3  256.54
  4999.1  256.04  5002.3  256.54  5013.6  267.58  5020.2  268.38  5098.1  269.87
  5148.6   273.2  5162.8  275.67  5169.4  274.16  5197.8  275.99  5268.8  279.11
  5304.4  283.13    5361  286.61  5410.9   292.9  5417.5  295.57  5453.2  301.13
#Mann= 5 ,-1 , 0
  4319.5     .16       0  4349.1     .12       0  4996.3     .07       0
  5002.3     .12       0  5197.8     .16       0
Bank Sta=4978.3,5020.2
XS Rating Curve= 0 ,0
Exp/Cntr=0.3,0.1

Type RM Length L Ch R = 1 ,7205    ,433,433,433
BEGIN DESCRIPTION:
HALL BRANCH 14.0
END DESCRIPTION:
XS GIS Cut Line= 3
      3655099.66     10691360.18      3654499.61     10691460.19
      3654249.59     10691510.19
#Sta/Elev= 30
  4355.7  292.92  4370.5  290.87  4444.5  280.24    4518  271.97  4548.4  269.93
  4588.9   271.6  4609.2  269.79  4692.8  269.66  4730.9  268.05  4809.4  267.73
  4814.5  264.81  4822.1  264.33  4842.4  266.85  4852.5  263.37  4870.2  263.95
  4875.3  265.42  4893.1  262.31  4931.1  266.81  4966.6  266.64  4974.2  261.13
  4984.4  258.25  4991.6  254.51  4994.4  254.01  4997.6  254.51  5004.8  255.08
    5015  262.09  5045.6  270.09    5117  280.79    5168  284.71    5219  290.48
#Mann= 4 ,-1 , 0
  4355.7     .16       0  4370.5     .12       0  4991.6     .07       0
  4997.6     .12       0
Bank Sta=4692.8,5045.6
XS Rating Curve= 0 ,0
Exp/Cntr=0.3,0.1

Type RM Length L Ch R = 1 ,6772    ,349,349,349
BEGIN DESCRIPTION:
HALL BRANCH 13.0
END DESCRIPTION:
XS GIS Cut Line= 3
      3654699.58     10690510.23      3654249.61     10691110.19
       3654099.6      10691260.2
#Sta/Elev= 30
  4259.7  324.51  4281.5  323.17  4323.2  312.35  4345.7   309.6  4366.9  304.59
  4381.5  303.59  4416.9  297.21  4466.9  292.38  4481.5  289.25  4523.2  283.38
  4666.9  270.66  4752.4  266.49  4802.4  264.97  4937.8  266.16  4952.4  265.33
  4966.9  266.27  4981.5  264.96  4996.1  256.03  4999.4  252.82  5002.1  252.32
  5005.4  252.82  5013.2  253.74  5023.8  263.98    5045  266.92  5136.9  276.71
  5165.2  278.46  5179.4  281.19  5195.3  281.58  5219.5  282.81  5221.8  282.81
#Mann= 6 ,-1 , 0
  4259.7     .05       0  4345.7     .12       0  4999.4     .07       0
  5005.4     .12       0  5195.3     .16       0  5219.5     .12       0
Bank Sta=4752.4,5045
XS Rating Curve= 0 ,0
Exp/Cntr=0.3,0.1

Type RM Length L Ch R = 1 ,6423    ,476,476,476
BEGIN DESCRIPTION:
HALL BRANCH 12.0
END DESCRIPTION:
XS GIS Cut Line= 3
      3654058.41     10690178.99      3653926.55     10691121.85
      3653915.18     10691784.92
#Sta/Elev= 30
  4193.7  312.96  4220.7  308.49  4285.8  301.97  4316.1  294.42  4360.5  288.13
  4598.8  274.29  4725.8   269.4  4810.8  269.45  4921.9  265.58  4940.1  263.26
  4972.4  263.77  4982.5  258.41  4989.6   252.1  4992.3   251.6  4995.6   252.1
  5002.7  252.59  5011.6  260.74  5016.6  259.93  5022.9  263.14    5033  264.76
  5113.8  263.52  5154.1  266.04  5171.9  268.68  5259.1  283.32  5264.1  282.28
  5294.1  287.88  5374.1  295.14  5614.1  305.29  5694.2  311.33  5808.9  313.68
#Mann= 5 ,-1 , 0
  4193.7     .16       0  4360.5     .12       0  4989.6     .07       0
  4995.6     .12       0  5171.9     .16       0
Bank Sta=4921.9,5154.1
XS Rating Curve= 0 ,0
Exp/Cntr=0.3,0.1

Type RM Length L Ch R = 1 ,5947    ,440,440,440
BEGIN DESCRIPTION:
HALL BRANCH 11.0
END DESCRIPTION:
XS GIS Cut Line= 3
      3653699.61      10690260.2      3653549.61     10690860.19
      3653099.57     10691310.22
#Sta/Elev= 30
    4374  307.11  4402.7  304.01  4415.2  302.31  4433.3  295.92  4438.4  296.26
  4456.5  292.31  4497.7  285.81  4520.9  283.58  4528.6  281.53  4569.8  277.57
  4721.9  266.17  4755.4  265.73  4768.3  264.14  4845.6  264.03  4969.3  261.92
  4974.4   260.2  4982.1     255  5003.6     251  5006.3   250.5  5009.6     251
  5020.7  257.63  5034.9  261.71  5063.2   262.9  5133.9  262.19    5148  259.77
  5190.4  264.24  5317.7  274.36  5381.4  282.34    5445  287.94  5628.9  311.09
#Mann= 4 ,-1 , 0
    4374     .16       0  4402.7     .12       0  5003.6     .07       0
  5009.6     .12       0
Bank Sta=4845.6,5190.4
XS Rating Curve= 0 ,0
Exp/Cntr=0.3,0.1

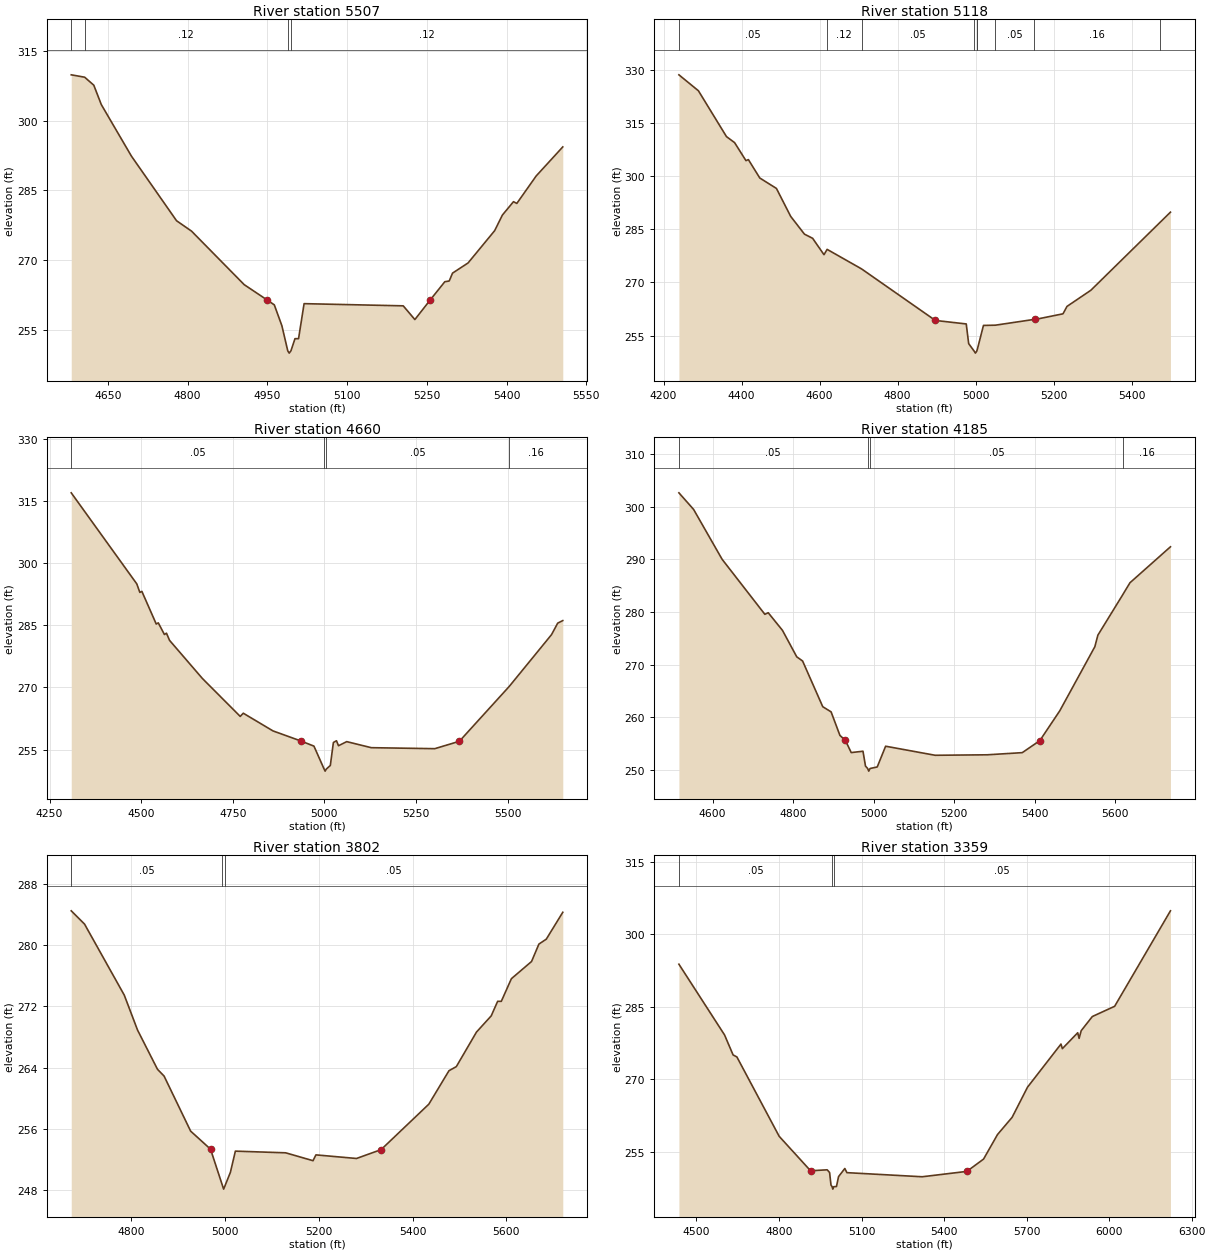
Type RM Length L Ch R = 1 ,5507    ,389,389,389
BEGIN DESCRIPTION:
HALL BRANCH 10.0
END DESCRIPTION:
XS GIS Cut Line= 3
      3653649.59     10690210.21      3653349.61     10690510.19
      3652949.64     10690810.17
#Sta/Elev= 30
  4581.4  309.85  4606.6  309.34  4623.8  307.62  4637.9  303.45  4694.5  292.36
  4779.4  278.44  4807.6   276.2  4906.6  264.68  4949.1  261.43  4963.2  260.33
  4977.4  255.86  4988.5  250.44  4991.2  249.94  4994.5  250.44  5002.1  253.05
  5008.8  253.05  5019.2  260.59  5205.6  260.12  5227.5  257.17  5255.6  261.28
  5283.8  265.31  5292.1  265.47  5298.3  267.16  5327.5  269.35  5377.5   276.3
  5392.1  279.67  5412.9  282.54  5419.2  282.17  5455.6  288.08  5505.6  294.33
#Mann= 4 ,-1 , 0
  4581.4     .16       0  4606.6     .12       0  4988.5     .07       0
  4994.5     .12       0
Bank Sta=4949.1,5255.6
XS Rating Curve= 0 ,0
Exp/Cntr=0.3,0.1

Type RM Length L Ch R = 1 ,5118    ,458,458,458
BEGIN DESCRIPTION:
HALL BRANCH 9.0
END DESCRIPTION:
XS GIS Cut Line= 3
       3653649.6     10689810.19      3653049.61     10690260.19
      3652949.61     10690760.19
#Sta/Elev= 30
  4239.5  328.61  4289.5  324.11  4361.4  311.17  4382.2  309.47  4411.4  304.38
  4417.6  304.67  4446.8  299.48  4489.5  296.53    4526  288.64  4561.4  283.61
  4582.2  282.46  4611.4  277.82  4619.4  279.33  4707.7  273.81  4896.8  259.26
    4976  258.27  4982.2  252.72  4996.7  250.53  4999.4  250.03  5002.7  250.53
  5004.3  251.04  5020.1  257.85  5050.7  257.92    5150  259.55  5152.7  259.54
    5224  261.13  5234.2  263.22  5295.4  267.78  5471.8  286.85  5499.4  289.83
#Mann= 9 ,-1 , 0
  4239.5     .05       0  4619.4     .12       0  4707.7     .05       0
  4996.7     .03       0  5002.7     .05       0  5004.3     .16       0
  5050.7     .05       0    5150     .16       0  5471.8     .12       0
Bank Sta=4896.8,5152.7
XS Rating Curve= 0 ,0
Exp/Cntr=0.3,0.1

Type RM Length L Ch R = 1 ,4660    ,475,475,475
BEGIN DESCRIPTION:
HALL BRANCH 8.0
END DESCRIPTION:
XS GIS Cut Line= 3
       3653499.6     10689560.19      3652899.61     10689860.19
      3652299.63     10690160.18
#Sta/Elev= 30
  4309.1  316.99    4488  295.01  4496.4  292.95  4501.9   293.2  4541.1  285.32
  4546.7   285.6  4563.4  282.79    4569  283.11  4577.4  281.38  4666.9  272.19
  4770.3  263.02  4778.7  263.79  4859.7  259.52  4935.2  257.11  4971.5  255.85
  4999.3  250.31    5002  249.81  5005.3  250.31  5016.2  251.17  5024.6  256.72
    5033  257.14  5038.6  255.94    5061  256.93    5128  255.47  5301.3  255.23
  5368.4  257.01  5504.7  270.27    5620  282.76  5636.8  285.53  5650.7  286.15
#Mann= 4 ,-1 , 0
  4309.1     .05       0  4999.3     .03       0  5005.3     .05       0
  5504.7     .16       0
Bank Sta=4935.2,5368.4
XS Rating Curve= 0 ,0
Exp/Cntr=0.3,0.1

Type RM Length L Ch R = 1 ,4185    ,383,383,383
BEGIN DESCRIPTION:
HALL BRANCH 7.0
END DESCRIPTION:
XS GIS Cut Line= 3
      3652899.61     10689110.19      3652599.61     10689510.19
      3652199.62     10690110.18
#Sta/Elev= 30
  4516.1  302.66  4552.6  299.51  4623.4  290.04  4729.6  279.59    4738  279.89
  4773.4  276.54  4808.8  271.52  4823.4  270.72  4873.4  262.05  4894.2  261.06
  4916.1  256.59  4929.6  255.65  4944.2  253.33  4973.4  253.59  4979.6  250.77
    4985  250.31  4987.7  249.81    4991  250.31  5008.8   250.6  5029.6  254.54
  5152.8  252.82    5282  252.91  5369.1  253.32  5412.7   255.6  5462.3  261.27
  5549.4  273.44  5556.9  275.63  5618.3  283.26  5636.6  285.58  5737.2  292.41
#Mann= 4 ,-1 , 0
  4516.1     .05       0    4985     .03       0    4991     .05       0
  5618.3     .16       0
Bank Sta=4929.6,5412.7
XS Rating Curve= 0 ,0
Exp/Cntr=0.3,0.1

Type RM Length L Ch R = 1 ,3802    ,443,443,443
BEGIN DESCRIPTION:
HALL BRANCH 6.0
END DESCRIPTION:
XS GIS Cut Line= 3
      3652499.61     10689110.18      3652249.61     10689360.19
       3651899.6      10689960.2
#Sta/Elev= 30
    4672   284.5  4700.3  282.77  4785.1  273.47  4813.4   268.9  4855.9  263.77
    4870  262.88  4926.6  255.68    4969  253.32  4994.3  248.59    4997  248.09
  5000.3  248.59  5011.4  250.29    5022  253.06  5129.3  252.84  5187.6  251.81
  5193.8  252.57  5280.3   252.1  5332.8  253.26  5434.5   259.2  5477.5  263.58
  5493.2  264.12  5536.2  268.64  5567.6  270.76  5581.3  272.66  5589.1  272.66
  5610.6  275.62  5653.6  277.87  5669.3  280.15    5685  280.79  5720.2  284.31
#Mann= 3 ,-1 , 0
    4672     .05       0  4994.3     .03       0  5000.3     .05       0
Bank Sta=4969,5332.8
XS Rating Curve= 0 ,0
Exp/Cntr=0.3,0.1

Type RM Length L Ch R = 1 ,3359    ,451,451,451
BEGIN DESCRIPTION:
HALL BRANCH 5.0
END DESCRIPTION:
XS GIS Cut Line= 3
      3652499.64     10688910.18      3651949.61     10689060.19
       3651749.6     10690260.22
#Sta/Elev= 30
  4436.2  293.81  4602.1  279.17  4633.2  275.03    4647  274.61  4800.7  258.18
  4914.8  251.05  4975.2  251.25  4983.9  250.69    4989   248.1    4993  247.75
  4995.7  247.25    4999  247.75  5008.9  247.79  5016.5  249.84  5039.3  251.52
  5046.9  250.66  5320.6  249.81  5482.8  250.92  5543.6  253.47  5594.3  258.55
  5647.5  262.12  5703.3  268.35    5825  277.28    5830  276.33  5885.8  279.62
  5890.9  278.46  5898.5  280.05    5939  282.98  6020.1   285.1  6222.9  304.86
#Mann= 3 ,-1 , 0
  4436.2     .05       0    4993     .03       0    4999     .05       0
Bank Sta=4914.8,5482.8
XS Rating Curve= 0 ,0
Exp/Cntr=0.3,0.1

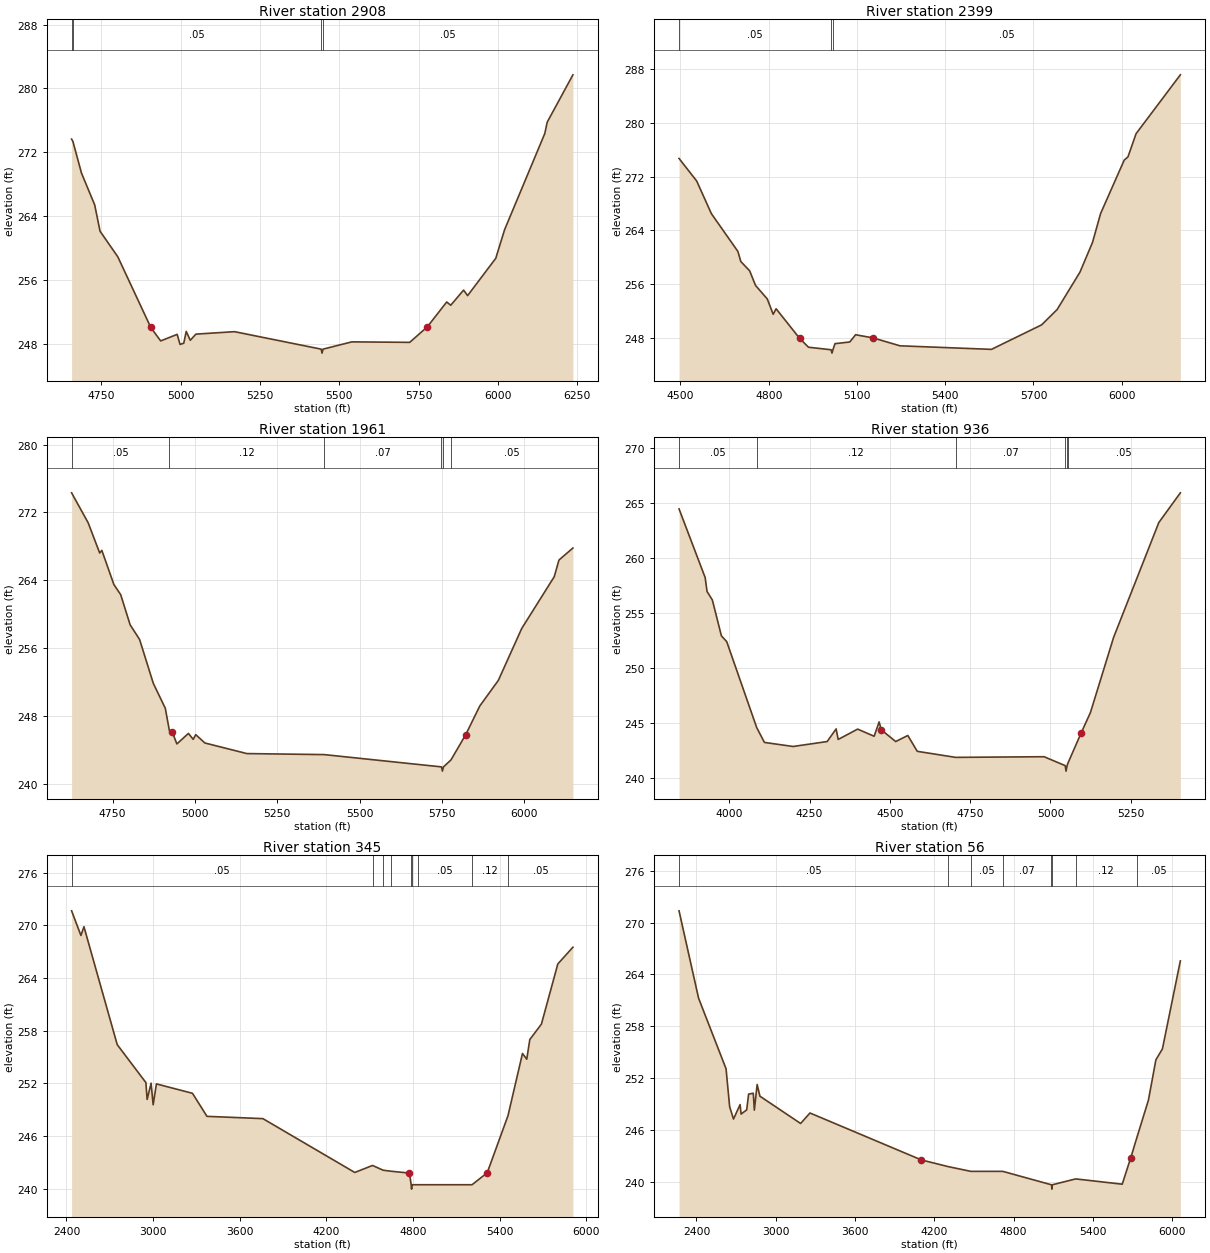
Type RM Length L Ch R = 1 ,2908    ,509,509,509
BEGIN DESCRIPTION:
HALL BRANCH 4.0
END DESCRIPTION:
XS GIS Cut Line= 3
      3652099.65     10688610.18      3651749.61     10688710.19
      3651549.61     10689910.19
#Sta/Elev= 30
  4655.9  273.64    4660  273.35  4687.1  269.38  4728.7   265.4  4745.6   262.1
  4801.5   258.9  4905.5  250.04  4936.7  248.35  4988.7  249.17  4997.8  247.91
  5009.5  248.06  5017.3  249.54  5030.1  248.43  5047.8   249.2  5169.5  249.51
  5442.7  247.32  5445.5  246.82  5448.7  247.32  5539.5  248.23    5722  248.17
  5777.8  250.13  5838.6  253.23  5851.3  252.82  5891.8  254.72  5904.5  254.03
  5993.2   258.7  6021.1  262.29  6147.8  274.34  6155.4  275.76  6236.5   281.7
#Mann= 4 ,-1 , 0
  4655.9     .16       0    4660     .05       0  5442.7     .03       0
  5448.7     .05       0
Bank Sta=4905.5,5777.8
XS Rating Curve= 0 ,0
Exp/Cntr=0.3,0.1

Type RM Length L Ch R = 1 ,2399    ,438,438,438
BEGIN DESCRIPTION:
HALL BRANCH 3.0
END DESCRIPTION:
XS GIS Cut Line= 3
      3651399.61      10688310.2      3651399.61     10688810.19
       3651499.6     10690010.14
#Sta/Elev= 30
  4495.2  274.73  4555.2  271.37  4605.2   266.5  4695.2  260.88  4705.2  259.37
  4735.2  257.99  4755.2  255.81  4795.2  253.79  4815.2  251.51  4825.2  252.33
  4905.2  247.92  4935.2   246.6  5012.3  246.22    5015  245.72  5018.3  246.22
  5025.3  247.13  5075.5  247.38  5095.5  248.46  5155.7  247.98  5246.1  246.81
  5557.1  246.28  5727.7  249.93  5780.4  252.21  5858.2   257.8  5900.8  262.23
  5928.4  266.54  6008.7   274.5  6021.2  274.96  6048.8  278.42  6199.3  287.19
#Mann= 3 ,-1 , 0
  4495.2     .05       0  5012.3     .03       0  5018.3     .05       0
Bank Sta=4905.2,5155.7
XS Rating Curve= 0 ,0
Exp/Cntr=0.3,0.1

Type RM Length L Ch R = 1 ,1961    ,1025,1025,1025
BEGIN DESCRIPTION:
HALL BRANCH 2.0
END DESCRIPTION:
XS GIS Cut Line= 3
      3651349.63     10688310.17      3651049.61     10688560.19
      3650249.62     10689360.18
#Sta/Elev= 30
  4625.7  274.31  4675.8  270.79    4711  267.21  4717.5  267.52    4754   263.5
  4774.8  262.29  4803.4  258.74  4832.1  257.01  4873.7  251.84  4910.2  248.89
  4922.7  246.23    4931  246.12  4945.3  244.69  4980.4  245.93  4994.8  245.23
  5002.6  245.78  5030.4   244.8  5157.7  243.55  5392.1  243.43  5748.6  241.98
  5751.4  241.48  5754.6  241.98  5777.4   242.8  5822.3  245.79  5864.8  249.16
  5921.3  252.19  5992.1   258.3    6091  264.42  6105.2  266.38  6147.6   267.8
#Mann= 6 ,-1 , 0
  4625.7     .05       0  4922.7     .12       0  5392.1     .07       0
  5748.6     .07       0  5754.6     .07       0  5777.4     .05       0
Bank Sta=4931,5822.3
XS Rating Curve= 0 ,0
Exp/Cntr=0.3,0.1

Type RM Length L Ch R = 1 ,936     ,591,591,591
BEGIN DESCRIPTION:
Mapping XS 57299f12
END DESCRIPTION:
XS GIS Cut Line= 3
       3651202.3     10688245.87      3650399.34     10688649.53
      3650238.76     10689291.85
#Sta/Elev= 30
  3843.5  264.48  3924.9  258.23  3930.7  256.97  3947.2   256.2  3975.4  252.94
    3992  252.41  4085.3   244.6  4109.3  243.25  4198.6  242.88  4304.7  243.33
  4332.6  244.48    4339  243.52  4399.6  244.46  4450.9  243.81  4466.5  245.11
  4473.3  244.39  4518.1  243.33  4555.8  243.88  4585.2  242.44  4704.6  241.89
    4980  241.95  5045.7  241.14  5048.4  240.64  5051.7  241.14    5054  241.34
    5095  244.08  5124.3  245.96  5196.4  252.79  5337.3  263.24  5404.3  265.94
#Mann= 6 ,-1 , 0
  3843.5     .05       0  4085.3     .12       0  4704.6     .07       0
  5045.7     .07       0  5051.7     .07       0    5054     .05       0
Bank Sta=4473.3,5095
XS Rating Curve= 0 ,0
Exp/Cntr=0.3,0.1

Type RM Length L Ch R = 1 ,345     ,289,289,289
BEGIN DESCRIPTION:
Mapping XS 2a4ef013
END DESCRIPTION:
XS GIS Cut Line= 4
      3651293.42     10686514.13      3649839.44     10688523.66
      3649891.53     10688870.88      3650255.34     10689399.27
#Sta/Elev= 30
  2435.4  271.67    2500  268.86  2520.9  269.86  2751.4  256.41  2950.1  252.08
  2958.7  250.16    2986  252.01  3000.4  249.55    3023  251.93  3272.7  250.86
  3373.2  248.23  3760.7  247.97  4397.2  241.83  4520.2  242.63  4593.3  242.09
  4648.5  241.97  4776.2  241.76  4787.9  240.43  4790.6  239.93  4793.9  240.43
  4833.6  240.43  5209.4  240.43  5314.6  241.79  5458.7  248.31    5559   255.4
  5588.7  254.75  5609.7  256.99  5690.2  258.75  5803.8  265.61  5908.4  267.52
#Mann= 9 ,-1 , 0
  2435.4     .05       0  4520.2     .07       0  4593.3     .05       0
  4648.5     .07       0  4787.9    .033       0  4793.9     .07       0
  4833.6     .05       0  5209.4     .12       0  5458.7     .05       0
Bank Sta=4776.2,5314.6
XS Rating Curve= 0 ,0
Exp/Cntr=0.3,0.1

Type RM Length L Ch R = 1 ,56      ,0,0,0
BEGIN DESCRIPTION:
HALL BRANCH 1.0
END DESCRIPTION:
XS GIS Cut Line= 4
      3651072.08     10686375.23      3649539.96     10688406.47
      3649592.05     10688814.46      3650199.69     10689391.72
#Sta/Elev= 30
    2268  271.35  2415.8  261.27  2623.9  253.11    2651  248.74  2680.1  247.31
  2730.1  248.98  2737.7  247.89    2780  248.37  2794.6  250.19    2830  250.29
  2837.9  248.34  2859.1   251.3    2880  249.95    3188   246.8  3258.8  248.01
  4101.9  242.59  4304.6  241.82  4476.9  241.27  4718.4  241.27  5086.6  239.72
  5089.3  239.22  5092.6  239.72  5269.9   240.4  5621.9  239.79  5685.8  242.81
  5731.7  245.12  5820.1  249.49  5876.7  254.15    5926  255.41  6061.7  265.57
#Mann= 8 ,-1 , 0
    2268     .05       0  4304.6     .07       0  4476.9     .05       0
  4718.4     .07       0  5086.6     .07       0  5092.6     .07       0
  5269.9     .12       0  5731.7     .05       0
Bank Sta=4101.9,5685.8
XS Rating Curve= 0 ,0
Exp/Cntr=0.3,0.1

Chan Stop Cuts=-1
Use User Specified Reach Order=0
Composite Channel Slope=5