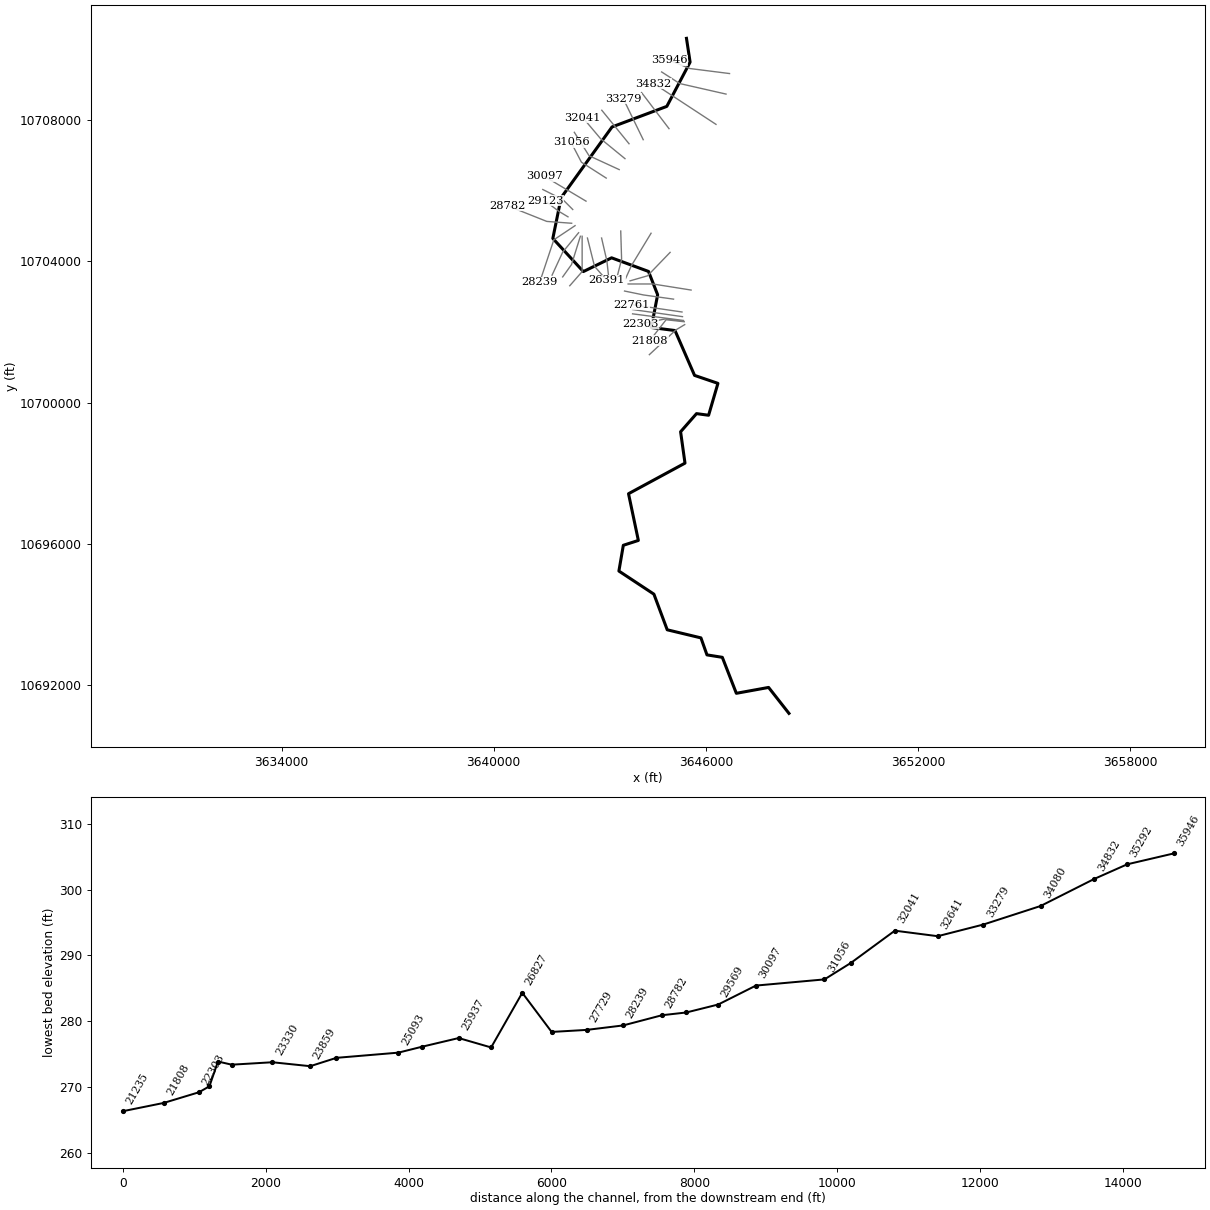
--- INDIAN CREEK 1.prj (project) ---

Proj Title=INDIAN CREEK 1 Base Level Engineering
Current Plan=p01
Default Exp/Contr=0.3,0.1
English Units
Geom File=g01
Flow File=f01
Plan File=p01
Y Axis Title=Elevation
X Axis Title(PF)=Main Channel Distance
X Axis Title(XS)=Station
BEGIN DESCRIPTION:
INDIAN CREEK 1
END DESCRIPTION:
DSS Export Rating Curves= 0
DSS Export Rating Curve Sorted= 0
DSS Export Volume Flow Curves= 0
DXF OffsetX= 0
DXF OffsetY= 0
DXF ScaleX= 1
DXF ScaleY= 10

--- INDIAN CREEK 1.p01 (plan) ---

Plan Title=Multiple Run
Short Identifier=Multiple
Geom File=g01
Flow File=f01
Subcritical Flow
K Sum by GR= 0
Std Step Tol= 0.01
Critical Tol= 0.01
Num of Std Step Trials= 20
Max Error Tol= 0.3
Flow Tol Ratio= 0.001
Split Flow NTrial= 30
Split Flow Tol= 0.02
Split Flow Ratio= 0.02
Log Output Level= 0
Friction Slope Method= 1
Unsteady Friction Slope Method= 2
Unsteady Bridges Friction Slope Method= 1
Parabolic Critical Depth
Global Vel Dist=  1 , 1 , 1
Global Log Level= 0
CheckData=True
Encroach Param= -1, 0, 0, 0
BEGIN DESCRIPTION:
Multiple Run
END DESCRIPTION:

--- INDIAN CREEK 1.f01 (steady flow) ---

Flow Title=Multiple
Number of Profiles=7
Profile Names=10-year,25-year,50-year,1pct_min,100-year,1pct_plu,500-year
River Rch & RM= INDIAN CREEK 1,Reach-1,35946
     403     533     637     560     757    1024    1073
River Rch & RM= INDIAN CREEK 1,Reach-1,35292
     611     824     999     888    1201    1624    1746
River Rch & RM= INDIAN CREEK 1,Reach-1,30097
    1179    1635    2016    1818    2459    3325    3668
River Rch & RM= INDIAN CREEK 1,Reach-1,28239
    1393    1944    2408    2180    2948    3987    4434
River Rch & RM= INDIAN CREEK 1,Reach-1,22449
    1459    2029    2507    2262    3059    4137    4575
Boundary for River Rch & Prof#=INDIAN CREEK 1,Reach-1,1
Up Type=0
Dn Type=3
Dn Slope=0.005
Boundary for River Rch & Prof#=INDIAN CREEK 1,Reach-1,2
Up Type=0
Dn Type=3
Dn Slope=0.005
Boundary for River Rch & Prof#=INDIAN CREEK 1,Reach-1,3
Up Type=0
Dn Type=3
Dn Slope=0.005
Boundary for River Rch & Prof#=INDIAN CREEK 1,Reach-1,4
Up Type=0
Dn Type=3
Dn Slope=0.005
Boundary for River Rch & Prof#=INDIAN CREEK 1,Reach-1,5
Up Type=0
Dn Type=3
Dn Slope=0.005
Boundary for River Rch & Prof#=INDIAN CREEK 1,Reach-1,6
Up Type=0
Dn Type=3
Dn Slope=0.005
Boundary for River Rch & Prof#=INDIAN CREEK 1,Reach-1,7
Up Type=0
Dn Type=3
Dn Slope=0.005

--- INDIAN CREEK 1.g01 (geometry) ---

Geom Title=Existing Conditions
Program Version=4.10

River Reach=INDIAN CREEK 1  ,Reach-1
Reach XY= 30
      3645449.61     10710310.19        3645552.       10709637.
      3644893.75       10708385.       3643344.5       10707803.
       3641905.5       10705802.      3641671.25       10704649.
      3642533.75       10703711.      3643332.25       10704100.
      3644375.75       10703715.       3644634.5       10703055.
      3644455.75       10702129.       3645125.5       10702043.
        3645678.       10700774.        3646339.       10700548.
        3646075.       10699646.      3645733.75       10699692.
       3645283.5       10699179.       3645407.5       10698291.
        3643811.       10697426.        3644089.       10696104.
        3643664.       10695967.        3643539.       10695238.
        3644529.       10694584.      3644905.25       10693576.
       3645858.5       10693347.        3646029.       10692866.
        3646463.       10692797.       3646859.5       10691779.
       3647771.5       10691945.      3648347.18     10691211.14

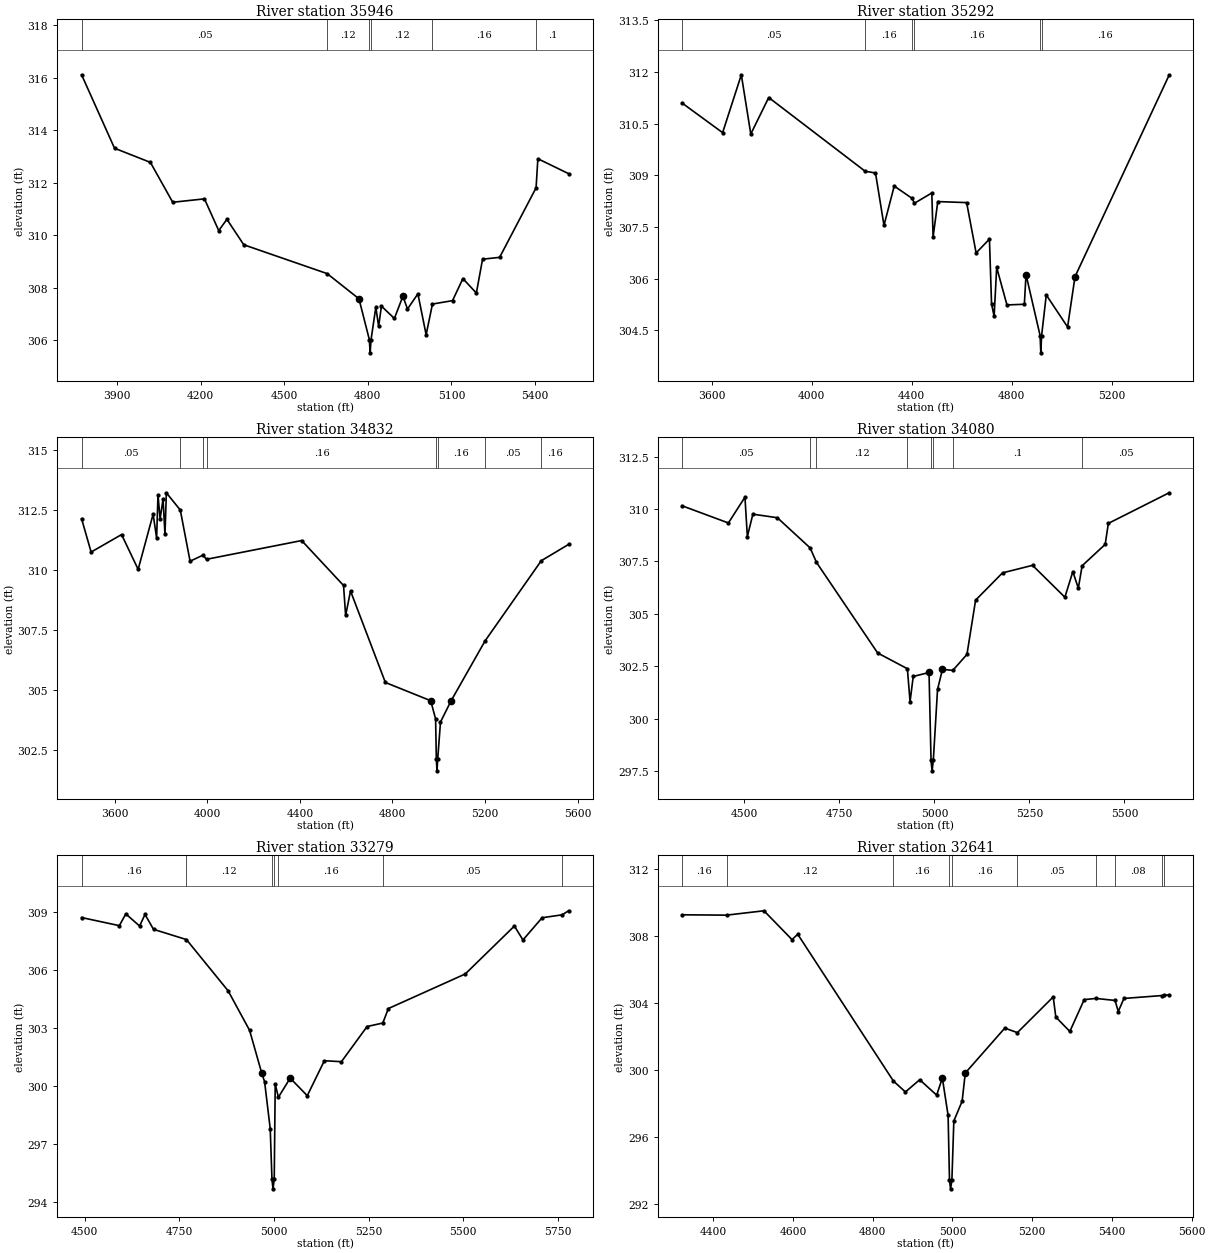
Type RM Length L Ch R = 1 ,35946   ,654,654,654
BEGIN DESCRIPTION:
INDIAN CREEK 1 43.0
END DESCRIPTION:
XS GIS Cut Line= 3
      3646666.86     10709313.77      3645549.13     10709455.59
      3644973.02     10709686.61
#Sta/Elev= 30
  3773.2  316.11  3891.4  313.31  4020.1  312.77  4100.2  311.25    4214  311.38
  4265.3  310.17  4294.6   310.6  4355.1  309.63  4654.3  308.53  4768.4  307.57
  4805.7  306.01  4808.4  305.51  4811.7  306.01  4828.9  307.25  4838.9  306.52
    4849  307.29  4895.5  306.82    4926  307.67  4942.5  307.18  4979.8  307.76
  5009.4   306.2    5032  307.37  5104.1   307.5  5141.2  308.34  5189.6  307.79
  5211.8  309.08    5273  309.15  5403.8   311.8  5410.2  312.91  5520.6  312.34
#Mann= 6 ,-1 , 0
  3773.2     .05       0  4654.3     .12       0  4805.7     .07       0
  4811.7     .12       0    5032     .16       0  5403.8      .1       0
Bank Sta=4768.4,4926
XS Rating Curve= 0 ,0
Exp/Cntr=0.3,0.1

Type RM Length L Ch R = 1 ,35292   ,460,460,460
BEGIN DESCRIPTION:
INDIAN CREEK 1 42.0
END DESCRIPTION:
XS GIS Cut Line= 3
      3646567.88     10708733.04      3645257.97     10709030.96
      3644747.59     10709359.06
#Sta/Elev= 30
  3480.5   311.1  3642.8  310.24  3717.7  311.92  3755.6   310.2  3827.4  311.26
  4213.5  309.12  4254.9  309.07  4288.9  307.55  4329.9  308.69  4402.1  308.33
  4410.5  308.19  4480.4  308.49  4485.5  307.21  4504.3  308.24  4619.8  308.21
  4657.8  306.75  4711.1  307.15  4719.6  305.27  4729.9  304.91  4740.1  306.33
  4781.2  305.24  4850.9  305.26  4857.6  306.12    4914  304.35  4916.8  303.85
    4920  304.35  4938.7  305.53    5024   304.6  5053.7  306.06  5430.6  311.91
#Mann= 6 ,-1 , 0
  3480.5     .05       0  4213.5     .16       0  4402.1     .12       0
  4410.5     .16       0    4914     .07       0    4920     .16       0
Bank Sta=4857.6,5053.7
XS Rating Curve= 0 ,0
Exp/Cntr=0.3,0.1

Type RM Length L Ch R = 1 ,34832   ,752,752,752
BEGIN DESCRIPTION:
Mapping XS 02e30cf1
END DESCRIPTION:
XS GIS Cut Line= 2
      3646284.07     10707876.25      3644524.08     10709030.64
#Sta/Elev= 30
  3456.7  312.13  3497.9  310.74  3629.5  311.47  3701.2  310.02  3765.9  312.32
    3781  311.32  3786.9  313.12    3796  312.13  3808.8  312.94  3817.1  311.48
  3823.1  313.21  3883.3  312.49  3925.6  310.36  3980.8  310.61  3996.8  310.44
  4407.8  311.22  4588.7  309.35  4597.8   308.1  4618.9  309.12  4769.5  305.31
  4965.5  304.55  4986.6  303.79  4989.8  302.13  4992.6  301.63  4995.8  302.13
  5007.7  303.66  5052.6  304.53  5200.3  307.04  5443.2  310.38  5561.5  311.06
#Mann= 8 ,-1 , 0
  3456.7     .05       0  3883.3     .16       0  3980.8     .05       0
  3996.8     .16       0  4989.8     .07       0  4995.8     .16       0
  5200.3     .05       0  5443.2     .16       0
Bank Sta=4965.5,5052.6
XS Rating Curve= 0 ,0
Exp/Cntr=0.3,0.1

Type RM Length L Ch R = 1 ,34080   ,801,801,801
BEGIN DESCRIPTION:
INDIAN CREEK 1 41.0
END DESCRIPTION:
XS GIS Cut Line= 2
      3644955.88     10707754.93      3644180.03     10708775.51
#Sta/Elev= 30
  4335.8  310.15  4457.7  309.33  4501.3  310.56  4507.6  308.68  4522.1  309.75
  4586.6  309.58  4672.9  308.14  4689.6  307.45  4850.6  303.13  4928.8  302.38
  4935.9  300.81  4944.2  302.01  4985.8   302.2  4991.1  298.01  4993.8  297.51
  4997.1  298.01  5008.2  301.39  5021.2  302.35  5048.4   302.3  5085.6  303.06
  5108.4  305.65  5179.2  306.95  5258.2  307.31  5343.4  305.79  5364.3  307.01
  5378.8  306.22  5388.8  307.29  5449.5  308.31  5457.8  309.31  5617.8  310.77
#Mann= 8 ,-1 , 0
  4335.8     .05       0  4672.9     .16       0  4689.6     .12       0
  4928.8     .16       0  4991.1     .07       0  4997.1     .16       0
  5048.4      .1       0  5388.8     .05       0
Bank Sta=4985.8,5021.2
XS Rating Curve= 0 ,0
Exp/Cntr=0.3,0.1

Type RM Length L Ch R = 1 ,33279   ,638,638,638
BEGIN DESCRIPTION:
INDIAN CREEK 1 40.0
END DESCRIPTION:
XS GIS Cut Line= 2
      3644226.73     10707442.39      3643664.24     10708598.63
#Sta/Elev= 30
  4492.1  308.73  4591.8  308.31  4608.8  308.92  4645.3  308.29  4659.5  308.89
    4682  308.12  4768.9  307.59  4878.9  304.94  4935.7  302.89  4967.8  300.67
  4975.2  300.24  4990.1   297.8  4994.7  295.19  4997.5  294.69  5000.7  295.19
  5003.3  300.11  5011.7  299.43  5042.8  300.42  5087.9  299.51    5133  301.32
  5178.1  301.27  5245.8  303.09  5287.3  303.27    5302  304.02    5505  305.81
  5634.7  308.29  5657.3  307.57  5707.9  308.72  5760.6  308.87  5777.9  309.08
#Mann= 7 ,-1 , 0
  4492.1     .16       0  4768.9     .12       0  4994.7     .07       0
  5000.7     .12       0  5011.7     .16       0  5287.3     .05       0
  5760.6     .12       0
Bank Sta=4967.8,5042.8
XS Rating Curve= 0 ,0
Exp/Cntr=0.3,0.1

Type RM Length L Ch R = 1 ,32641   ,600,600,600
BEGIN DESCRIPTION:
INDIAN CREEK 1 39.0
END DESCRIPTION:
XS GIS Cut Line= 2
      3643825.69     10707327.83      3643055.09     10708275.45
#Sta/Elev= 30
  4322.1  309.27  4433.7  309.25  4527.4  309.51  4597.8  307.79  4612.1  308.11
  4852.1  299.35  4882.2   298.7    4918  299.43  4960.5  298.51  4974.8  299.53
  4989.2   297.3  4992.7  293.42  4995.4  292.92  4998.7  293.42  5003.6  296.97
  5024.4  298.15  5032.3  299.83  5131.4  302.51  5162.9  302.24  5252.8  304.37
  5259.3  303.17  5294.5  302.31  5330.5  304.21  5359.9  304.28  5407.9  304.16
  5415.9   303.5  5430.2  304.28  5524.7  304.45  5530.4  304.46  5543.5   304.5
#Mann= 10 ,-1 , 0
  4322.1     .16       0  4433.7     .12       0  4852.1     .16       0
  4992.7     .07       0  4998.7     .16       0  5162.9     .05       0
  5359.9      .1       0  5407.9     .08       0  5524.7     .05       0
  5530.4     .16       0
Bank Sta=4974.8,5032.3
XS Rating Curve= 0 ,0
Exp/Cntr=0.3,0.1

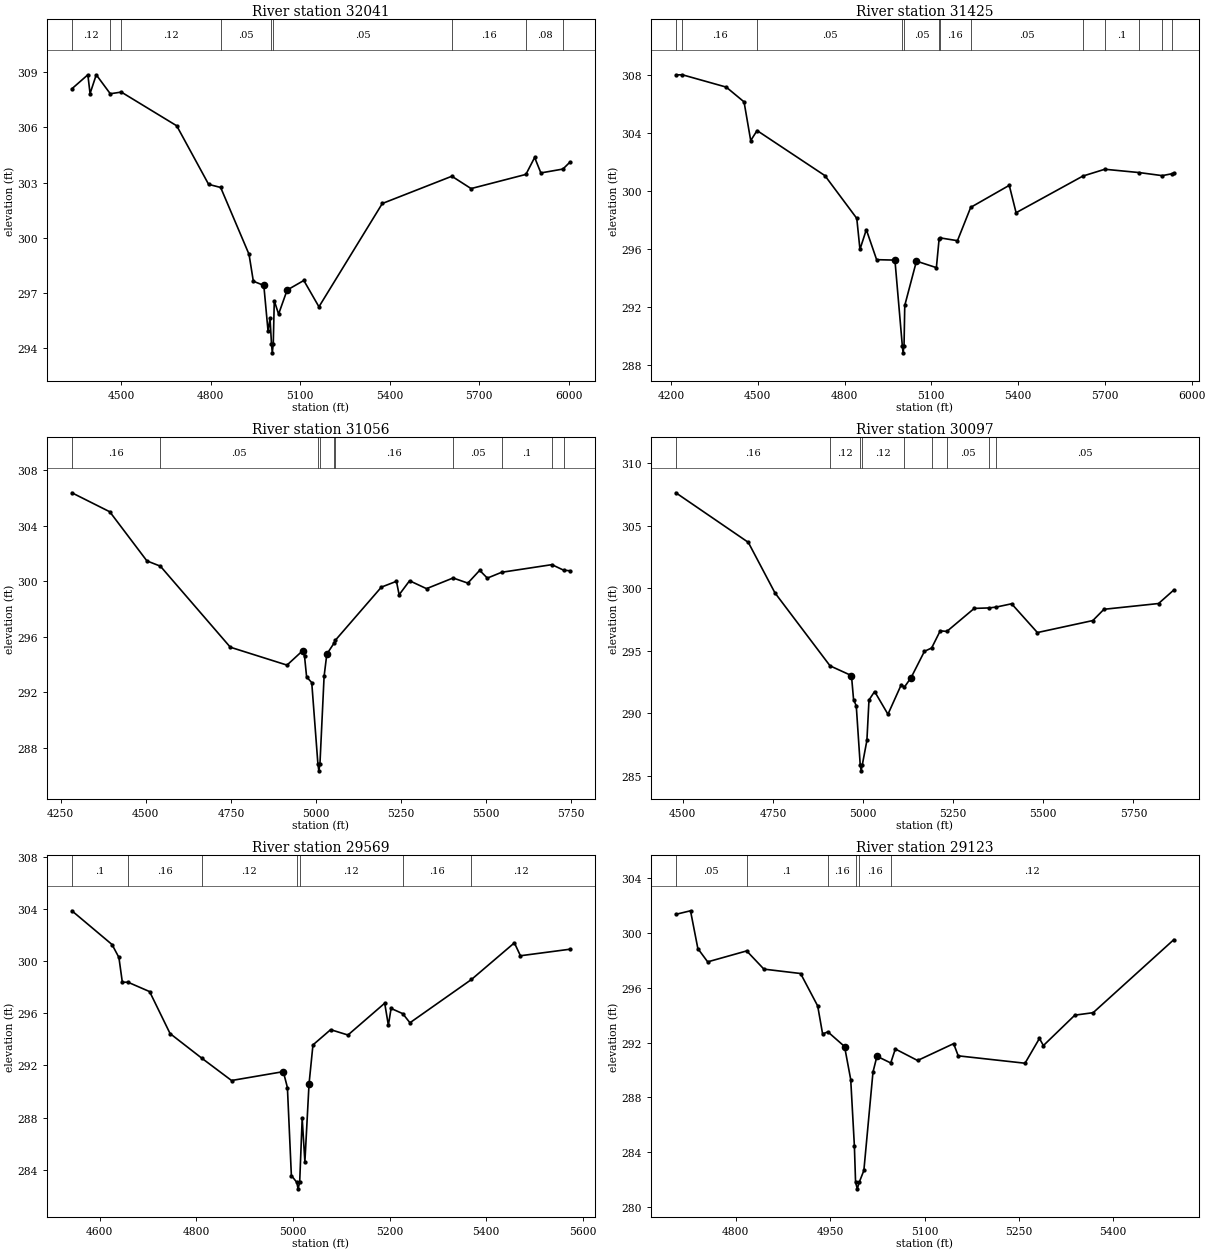
Type RM Length L Ch R = 1 ,32041   ,616,616,616
BEGIN DESCRIPTION:
INDIAN CREEK 1 38.0
END DESCRIPTION:
XS GIS Cut Line= 3
       3643711.1     10706905.96      3643023.59     10707468.46
      3642519.33      10708066.3
#Sta/Elev= 30
  4333.8   308.1  4387.4  308.86  4394.8  307.84  4415.6  308.86  4462.6  307.83
  4499.7  307.92  4685.5  306.09  4792.5  302.91  4832.9  302.74  4928.1  299.11
  4942.5  297.65  4977.7  297.42    4992  294.92  4998.5  295.64  5003.4  294.26
  5006.1  293.76  5009.4  294.26  5012.8  296.59  5027.2  295.86  5055.9  297.17
  5111.9  297.69  5162.6  296.26  5375.2  301.87  5608.5  303.35    5673  302.68
  5856.9  303.45  5886.2  304.37  5907.1  303.53    5981  303.74  6004.2  304.11
#Mann= 9 ,-1 , 0
  4333.8     .12       0  4462.6     .16       0  4499.7     .12       0
  4832.9     .05       0  5003.4     .03       0  5009.4     .05       0
  5608.5     .16       0  5856.9     .08       0    5981     .05       0
Bank Sta=4977.7,5055.9
XS Rating Curve= 0 ,0
Exp/Cntr=0.3,0.1

Type RM Length L Ch R = 1 ,31425   ,369,369,369
BEGIN DESCRIPTION:
INDIAN CREEK 1 37.0
END DESCRIPTION:
XS GIS Cut Line= 3
      3643547.72     10706596.05      3642695.47     10706988.66
      3642278.89     10707651.84
#Sta/Elev= 30
  4216.8  308.03  4239.3  308.04  4390.9  307.19  4452.6  306.17  4475.6   303.5
  4497.6  304.19  4732.2  301.08  4842.3  298.13  4853.3  295.99  4875.3  297.35
  4910.9  295.28  4974.2  295.25  4999.7  289.35  5002.4  288.85  5005.7  289.35
  5008.2  292.12  5048.6  295.18  5117.5  294.73  5126.9   296.7  5128.3  296.79
  5190.4  296.59  5236.2  298.89  5369.5  300.41  5393.1  298.52    5624  301.05
  5699.8  301.52  5819.1  301.29  5898.2  301.08  5932.1  301.21  5938.3  301.24
#Mann= 13 ,-1 , 0
  4216.8     .05       0  4239.3     .16       0  4497.6     .05       0
  4999.7     .03       0  5005.7     .05       0  5126.9     .12       0
  5128.3     .16       0  5236.2     .05       0    5624     .08       0
  5699.8      .1       0  5819.1     .05       0  5898.2     .08       0
  5932.1     .16       0
Bank Sta=4974.2,5048.6
XS Rating Curve= 0 ,0
Exp/Cntr=0.3,0.1

Type RM Length L Ch R = 1 ,31056   ,959,959,959
BEGIN DESCRIPTION:
INDIAN CREEK 1 36.0
END DESCRIPTION:
XS GIS Cut Line= 3
      3643180.35     10706356.33      3642479.38     10706805.56
      3642188.66     10707365.29
#Sta/Elev= 30
  4282.7  306.39  4394.1  305.02  4503.2  301.48  4542.8   301.1  4748.3  295.26
  4914.9  293.97  4960.5     295  4966.4  294.61  4972.5  293.12  4987.6  292.71
  5005.7  286.85  5008.5  286.35  5011.7  286.85  5023.9  293.16  5031.9  294.76
  5053.8  295.58  5056.6  295.75  5192.2  299.59  5236.5  300.01  5244.4  299.04
  5275.1  300.05  5324.9  299.48    5403  300.25  5446.3  299.88  5481.1   300.8
  5503.6  300.24  5545.7  300.66  5693.4  301.21  5727.9  300.81    5746  300.77
#Mann= 10 ,-1 , 0
  4282.7     .16       0  4542.8     .05       0  5005.7     .03       0
  5011.7     .05       0  5053.8     .12       0  5056.6     .16       0
    5403     .05       0  5545.7      .1       0  5693.4     .08       0
  5727.9      .1       0
Bank Sta=4960.5,5031.9
XS Rating Curve= 0 ,0
Exp/Cntr=0.3,0.1

Type RM Length L Ch R = 1 ,30097   ,528,528,528
BEGIN DESCRIPTION:
INDIAN CREEK 1 35.0
END DESCRIPTION:
XS GIS Cut Line= 2
       3642609.4     10705703.58      3641423.29     10706411.09
#Sta/Elev= 30
  4480.8  307.63  4681.7  303.67  4755.7  299.63  4908.5   293.8  4967.9  293.02
  4973.7  291.11  4981.2   290.6  4992.1  285.91  4994.8  285.41  4998.1  285.91
  5010.7  287.84  5016.5  291.07  5032.1  291.75  5069.1  289.93  5106.1   292.3
  5114.4  292.09  5133.3  292.86  5170.3  294.96  5190.3  295.23  5214.1   296.6
  5232.4  296.55  5308.4  298.39  5350.3  298.43  5369.9   298.5  5412.1  298.76
  5483.6  296.46  5637.4  297.42  5668.2  298.32  5819.6  298.78  5861.9  299.86
#Mann= 9 ,-1 , 0
  4480.8     .16       0  4908.5     .12       0  4992.1     .07       0
  4998.1     .12       0  5114.4     .05       0  5190.3     .16       0
  5232.4     .05       0  5350.3     .16       0  5369.9     .05       0
Bank Sta=4967.9,5133.3
XS Rating Curve= 0 ,0
Exp/Cntr=0.3,0.1

Type RM Length L Ch R = 1 ,29569   ,446,446,446
BEGIN DESCRIPTION:
INDIAN CREEK 1 34.0
END DESCRIPTION:
XS GIS Cut Line= 3
       3642234.3     10705467.17      3641953.05     10705748.42
      3641387.08     10706033.14
#Sta/Elev= 30
  4542.1  303.86  4625.3  301.27  4639.5  300.28  4646.6  298.38  4658.3  298.38
  4703.1  297.66  4745.5  294.44  4810.9  292.56  4872.8  290.84    4980  291.52
  4988.5   290.3  4996.7  283.55  5007.9  283.03  5010.6  282.53  5013.9  283.03
  5019.1  287.93  5024.7   284.6  5033.3  290.58  5041.4  293.57    5078  294.74
  5113.9  294.33    5190  296.77  5197.6  295.08  5203.2  296.37  5227.3  295.97
  5242.3  295.27  5369.7  298.59  5458.6   301.4  5471.1  300.41  5573.4  300.91
#Mann= 7 ,-1 , 0
  4542.1      .1       0  4658.3     .16       0  4810.9     .12       0
  5007.9     .07       0  5013.9     .12       0  5227.3     .16       0
  5369.7     .12       0
Bank Sta=4980,5033.3
XS Rating Curve= 0 ,0
Exp/Cntr=0.3,0.1

Type RM Length L Ch R = 1 ,29123   ,341,341,341
BEGIN DESCRIPTION:
INDIAN CREEK 1 33.0
END DESCRIPTION:
XS GIS Cut Line= 3
      3642099.63     10705260.18      3641849.61     10705410.19
      3641449.59     10705710.21
#Sta/Elev= 30
  4704.6  301.36  4727.9  301.62  4739.6  298.86  4755.2  297.89  4817.2  298.69
  4844.6  297.36  4902.9  297.04  4930.1  294.67  4937.9  292.63  4946.3  292.78
  4972.8  291.71  4982.6   289.3  4988.4  284.47  4990.3  281.82    4993  281.32
  4996.3  281.82  5003.5  282.66    5018  289.85  5024.3     291  5046.2  290.51
  5053.5  291.53  5088.9  290.69  5146.2  291.92  5153.5  291.03  5259.7  290.49
  5282.6   292.3  5288.9  291.78  5338.9     294    5368  294.18  5496.2  299.51
#Mann= 6 ,-1 , 0
  4704.6     .05       0  4817.2      .1       0  4946.3     .16       0
  4990.3     .07       0  4996.3     .16       0  5046.2     .12       0
Bank Sta=4972.8,5024.3
XS Rating Curve= 0 ,0
Exp/Cntr=0.3,0.1

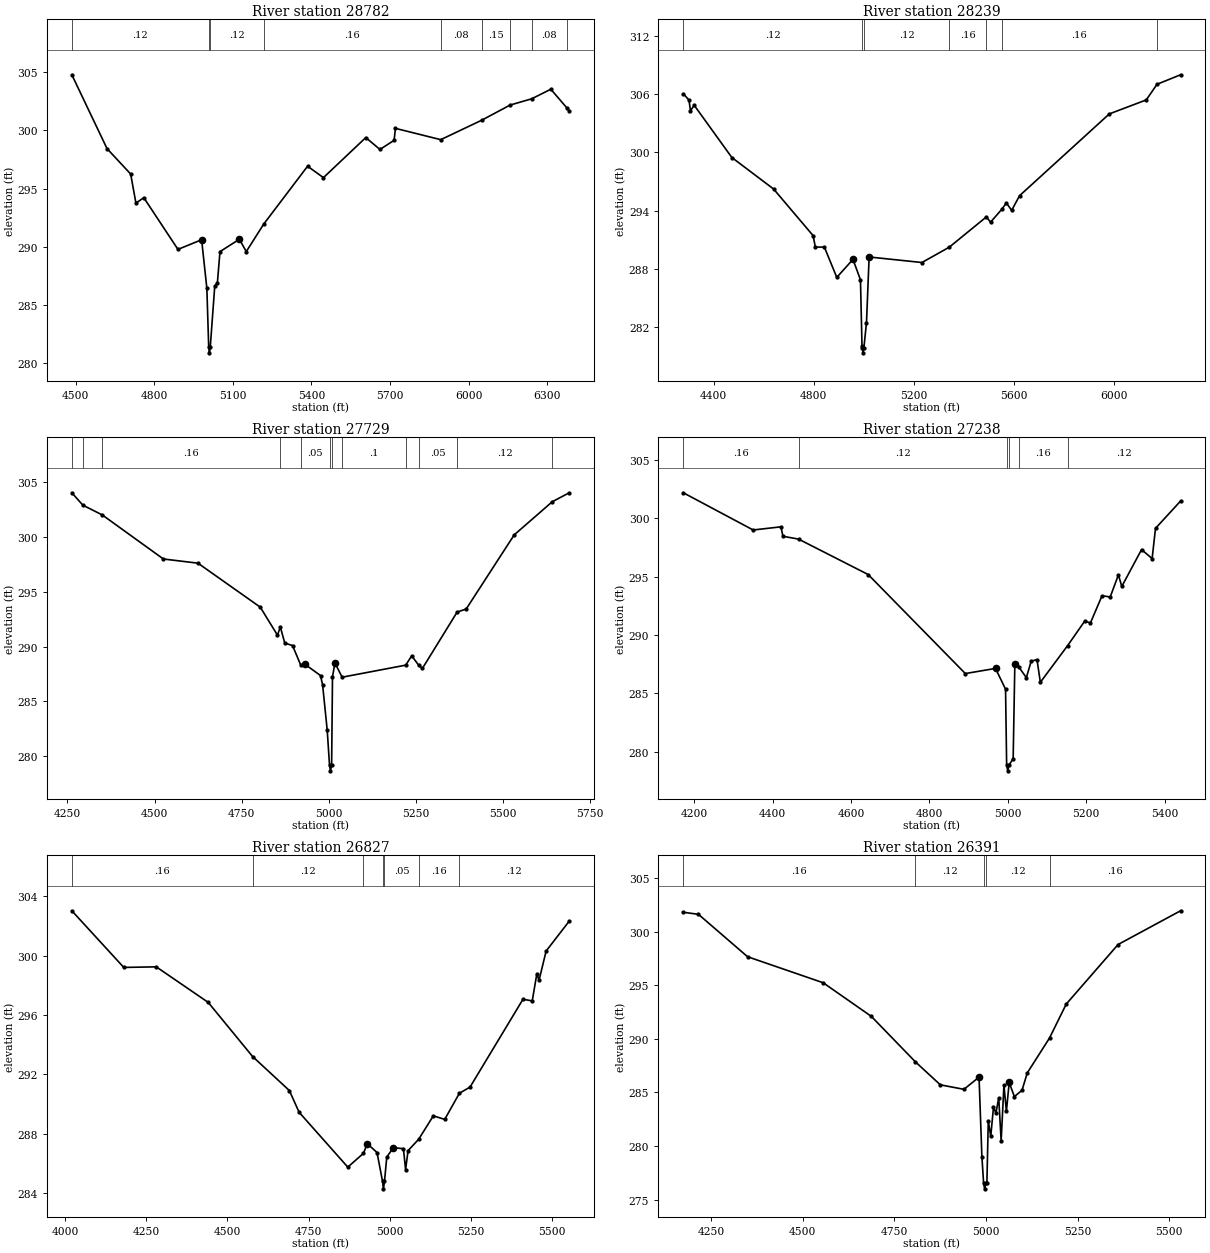
Type RM Length L Ch R = 1 ,28782   ,543,543,543
BEGIN DESCRIPTION:
INDIAN CREEK 1 32.0
END DESCRIPTION:
XS GIS Cut Line= 3
      3642203.51     10705078.05      3641500.36     10705130.14
      3640392.77     10705572.13
#Sta/Elev= 30
  4485.7  304.77    4620  298.43  4710.2  296.25  4730.3  293.75  4760.3  294.22
  4890.7  289.78    4981  290.61    5001  286.43    5008   281.4  5010.8   280.9
    5014   281.4  5031.1  286.63  5041.1  286.89  5051.1  289.59  5125.1  290.65
  5151.4  289.59  5217.9  291.95  5385.4  296.92  5445.9  295.94  5607.6  299.38
  5661.5  298.36  5715.4  299.14  5720.8  300.17  5893.6   299.2    6050  300.87
  6158.3  302.17  6240.9  302.71  6313.7  303.53  6374.8  301.93  6383.3  301.68
#Mann= 9 ,-1 , 0
  4485.7     .12       0    5008     .07       0    5014     .12       0
  5217.9     .16       0  5893.6     .08       0    6050     .15       0
  6158.3      .1       0  6240.9     .08       0  6374.8     .05       0
Bank Sta=4981,5125.1
XS Rating Curve= 0 ,0
Exp/Cntr=0.3,0.1

Type RM Length L Ch R = 1 ,28239   ,510,510,510
BEGIN DESCRIPTION:
INDIAN CREEK 1 31.0
END DESCRIPTION:
XS GIS Cut Line= 3
      3642299.57     10705010.16      3641699.61     10704610.19
       3641299.6     10703410.17
#Sta/Elev= 30
  4278.7  306.02  4301.2  305.38  4307.2  304.28  4322.2  304.84  4472.5  299.46
  4639.2  296.22    4797  291.42    4806  290.24    4842  290.24  4891.6  287.12
  4956.2  288.97  4986.2  286.87  4992.3   280.1  4993.8  279.85  4996.5  279.35
  4999.8  279.85  5010.3  282.47  5020.8  289.22  5231.7  288.65    5341  290.23
  5489.3  293.35  5505.7   292.8  5550.4  294.12    5569  294.78  5590.1  294.02
  5621.7  295.53  5980.1  303.95  6127.6  305.39  6170.7     307  6264.7  307.98
#Mann= 7 ,-1 , 0
  4278.7     .12       0  4993.8     .07       0  4999.8     .12       0
    5341     .16       0  5489.3     .12       0  5550.4     .16       0
  6170.7     .05       0
Bank Sta=4956.2,5020.8
XS Rating Curve= 0 ,0
Exp/Cntr=0.3,0.1

Type RM Length L Ch R = 1 ,27729   ,491,491,491
BEGIN DESCRIPTION:
INDIAN CREEK 1 30.0
END DESCRIPTION:
XS GIS Cut Line= 3
      3642399.61     10704810.19      3641949.61     10704260.19
      3641649.62     10703610.21
#Sta/Elev= 30
  4262.8  304.03  4294.4   302.9  4350.1  302.01  4525.5  297.99  4624.6  297.61
  4803.3   293.6  4852.8  291.04  4860.9   291.8  4873.7  290.32  4895.9   290.1
  4919.8  288.29  4931.1   288.4  4976.2  287.36  4982.2  286.52  4995.5  282.36
  5002.1  279.17  5004.8  278.67  5008.1  279.17  5010.6  287.23  5017.5  288.51
  5038.3  287.21  5220.7  288.31  5237.8  289.16  5258.2  288.29  5268.5  288.01
  5368.2  293.15  5394.2  293.43  5531.9  300.19    5641  303.21  5689.3  304.02
#Mann= 12 ,-1 , 0
  4262.8     .16       0  4294.4     .12       0  4350.1     .16       0
  4860.9     .12       0  4919.8     .05       0  5002.1     .04       0
  5008.1     .05       0  5038.3      .1       0  5220.7     .08       0
  5258.2     .05       0  5368.2     .12       0    5641     .16       0
Bank Sta=4931.1,5017.5
XS Rating Curve= 0 ,0
Exp/Cntr=0.3,0.1

Type RM Length L Ch R = 1 ,27238   ,411,411,411
BEGIN DESCRIPTION:
INDIAN CREEK 1 29.0
END DESCRIPTION:
XS GIS Cut Line= 3
      3642449.62     10704710.21      3642199.61     10703910.19
      3641949.61     10703560.19
#Sta/Elev= 30
  4172.1   302.2  4350.2  299.01    4421  299.28  4426.2  298.47  4465.9  298.23
  4643.6  295.19  4891.4   286.7  4968.4  287.14    4994  285.36  4996.8  278.86
  4999.6  278.36  5002.8  278.86  5013.4  279.39  5017.7  287.52  5027.6  287.27
  5047.1  286.35  5059.4  287.76  5074.2   287.9  5082.8  285.95  5152.2  289.09
  5195.8  291.19  5210.6  291.05  5240.1  293.37    5261  293.27  5281.9  295.16
  5290.5  294.17  5340.9  297.33  5367.9  296.56  5376.5  299.15  5440.4  301.49
#Mann= 6 ,-1 , 0
  4172.1     .16       0  4465.9     .12       0  4996.8     .07       0
  5002.8     .12       0  5027.6     .16       0  5152.2     .12       0
Bank Sta=4968.4,5017.7
XS Rating Curve= 0 ,0
Exp/Cntr=0.3,0.1

Type RM Length L Ch R = 1 ,26827   ,436,436,436
BEGIN DESCRIPTION:
INDIAN CREEK 1 28.0
END DESCRIPTION:
XS GIS Cut Line= 3
      3642499.61     10704710.18      3642499.61     10703710.19
      3642149.61     10703310.19
#Sta/Elev= 30
  4020.9  303.01  4180.9   299.2  4280.9  299.24  4440.9  296.85  4577.6  293.21
  4690.9  290.92  4720.9  289.46  4870.9  285.77  4919.2   286.7  4930.9  287.35
  4960.9  286.75  4977.9  284.81  4980.6  284.31  4983.9  284.81  4990.9  286.44
  5010.9  287.08  5042.2  287.01  5048.9  285.61  5056.5  286.88  5089.4  287.65
  5134.3  289.22  5169.4  288.98  5214.7  290.74  5247.3  291.15  5410.5  297.06
    5439  296.95  5453.2  298.78  5459.9  298.33  5481.7   300.3  5552.4   302.3
#Mann= 7 ,-1 , 0
  4020.9     .16       0  4577.6     .12       0  4919.2     .05       0
  4977.9     .07       0  4983.9     .05       0  5089.4     .16       0
  5214.7     .12       0
Bank Sta=4930.9,5010.9
XS Rating Curve= 0 ,0
Exp/Cntr=0.3,0.1

Type RM Length L Ch R = 1 ,26391   ,454,454,454
BEGIN DESCRIPTION:
INDIAN CREEK 1 27.0
END DESCRIPTION:
XS GIS Cut Line= 3
      3642649.62     10704660.16      3642849.61     10703860.19
      3643199.61     10703460.19
#Sta/Elev= 30
  4174.6  301.82  4215.8  301.63  4349.8  297.67    4556  295.24  4687.4   292.1
  4807.4  287.86  4875.5  285.71  4939.9  285.29  4981.1  286.43  4988.9     279
  4993.6   276.5  4996.4     276  4999.6   276.5  5002.5   276.5  5006.3  282.37
    5013  280.89  5020.5  283.62  5027.2  283.08  5034.8  284.49  5041.4  280.48
    5049  285.68  5055.7  283.23  5063.3  285.93  5077.5  284.61  5098.4  285.21
  5112.6  286.82  5173.3  290.08  5218.9  293.25  5360.3  298.81  5530.7  301.96
#Mann= 5 ,-1 , 0
  4174.6     .16       0  4807.4     .12       0  4993.6     .07       0
  4999.6     .12       0  5173.3     .16       0
Bank Sta=4981.1,5063.3
XS Rating Curve= 0 ,0
Exp/Cntr=0.3,0.1

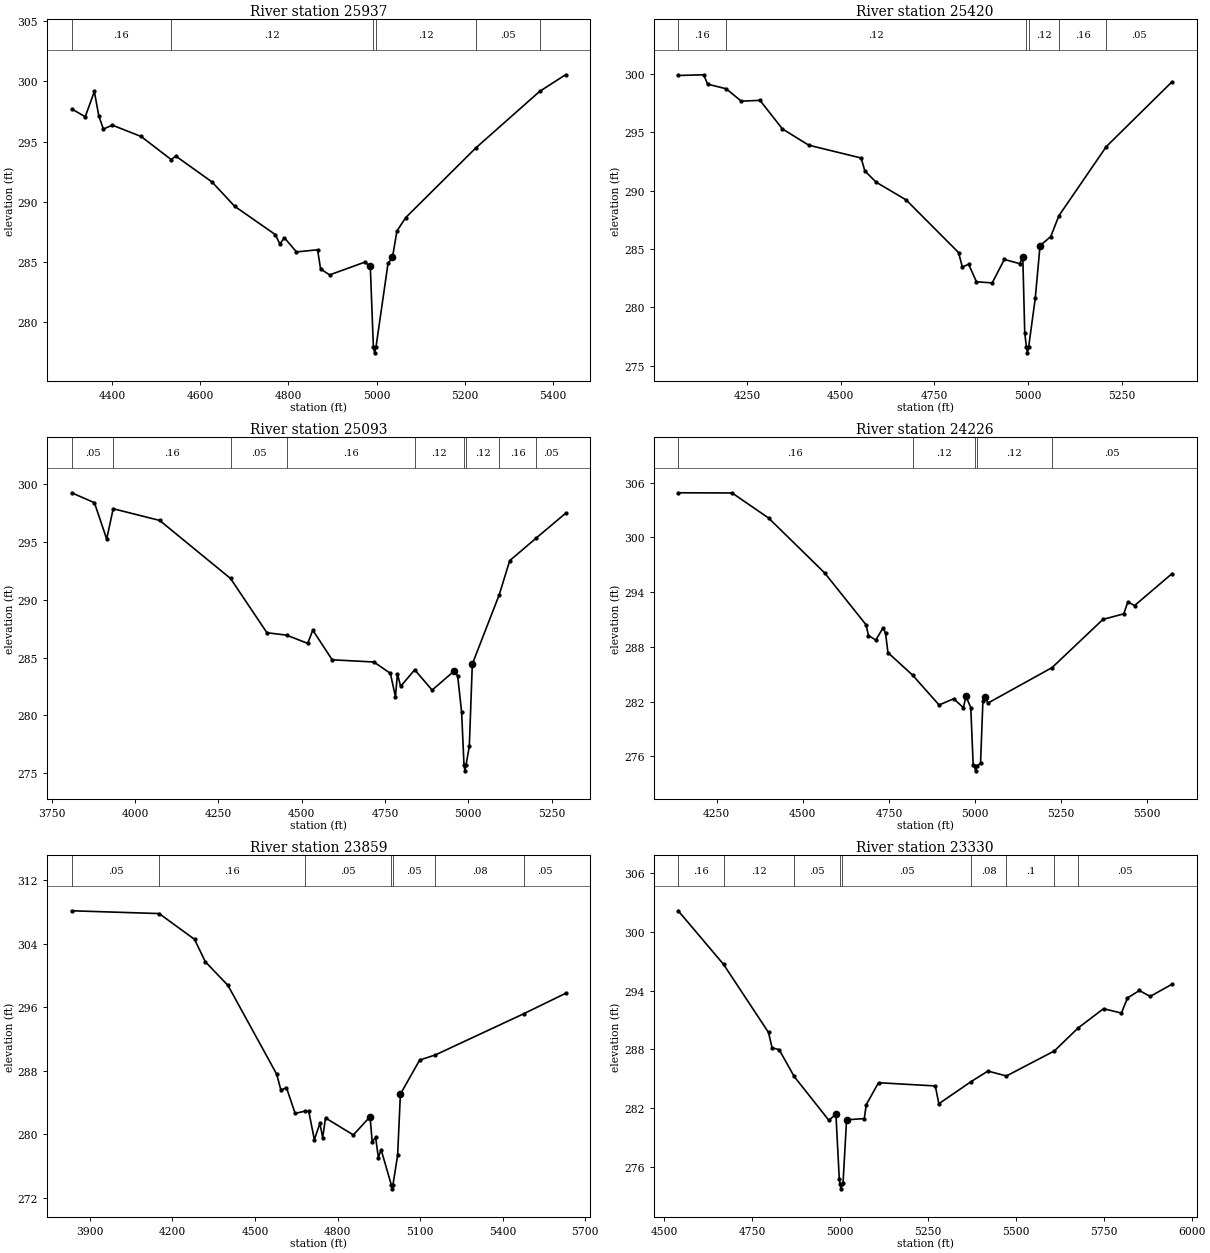
Type RM Length L Ch R = 1 ,25937   ,517,517,517
BEGIN DESCRIPTION:
INDIAN CREEK 1 26.0
END DESCRIPTION:
XS GIS Cut Line= 3
       3643049.6     10704660.23      3643199.61     10704010.19
      3643249.61     10703560.18
#Sta/Elev= 30
  4308.4  297.71  4339.2  297.06  4359.8  299.16    4370  297.12  4380.3  296.04
  4400.8  296.36  4465.8  295.42  4534.1   293.5  4544.5  293.79  4626.6  291.64
  4677.9  289.62  4770.3  287.26  4780.5  286.48  4790.8     287  4818.2  285.82
  4866.1     286  4872.9   284.4  4893.4  283.91    4973  284.97  4985.6  284.63
  4992.6  277.93  4995.4  277.43  4998.6  277.93  5025.8  284.86  5035.9  285.36
    5046  287.56  5066.1  288.68  5225.3  294.48  5369.7  299.17  5428.3  300.55
#Mann= 6 ,-1 , 0
  4308.4     .16       0  4534.1     .12       0  4992.6     .07       0
  4998.6     .12       0  5225.3     .05       0  5369.7     .16       0
Bank Sta=4985.6,5035.9
XS Rating Curve= 0 ,0
Exp/Cntr=0.3,0.1

Type RM Length L Ch R = 1 ,25420   ,327,327,327
BEGIN DESCRIPTION:
INDIAN CREEK 1 25.0
END DESCRIPTION:
XS GIS Cut Line= 3
      3643590.96      10704858.4      3643615.27     10704059.79
      3643486.79     10703556.31
#Sta/Elev= 30
  4066.2  299.86  4134.4  299.92  4144.5  299.12  4194.4  298.72  4234.5  297.66
  4284.5  297.73  4344.5  295.28  4414.6  293.89  4554.6  292.79  4564.6  291.68
  4594.7  290.72  4674.7   289.2  4814.8  284.69  4824.8  283.45  4841.6  283.69
  4862.5  282.19  4904.6  282.09    4937   284.1  4978.3  283.74  4986.3  284.32
  4991.5  277.81  4995.9   276.6  4998.7   276.1  5001.9   276.6  5019.6  280.78
  5032.3  285.28  5060.9  286.06  5082.8  287.85  5209.3  293.77  5384.8  299.32
#Mann= 6 ,-1 , 0
  4066.2     .16       0  4194.4     .12       0  4995.9     .07       0
  5001.9     .12       0  5082.8     .16       0  5209.3     .05       0
Bank Sta=4986.3,5032.3
XS Rating Curve= 0 ,0
Exp/Cntr=0.3,0.1

Type RM Length L Ch R = 1 ,25093   ,867,867,867
BEGIN DESCRIPTION:
INDIAN CREEK 1 24.0
END DESCRIPTION:
XS GIS Cut Line= 3
       3644448.6     10704795.89      3643893.48     10703880.07
      3643724.61     10703505.17
#Sta/Elev= 30
  3809.6  299.25  3877.9  298.39  3914.7  295.25  3934.2  297.87  4073.7  296.86
  4286.4  291.84  4395.6  287.15  4454.8  286.94  4517.9  286.23  4533.3  287.37
  4591.4  284.81  4716.7  284.62    4766  283.64  4781.4  281.61  4787.3   283.6
  4796.9  282.51  4839.1  283.95  4891.4  282.19  4957.2  283.83  4968.1   283.4
  4979.9  280.29  4987.1  275.71  4989.8  275.21  4993.1  275.71    5003  277.32
    5012  284.44  5092.9  290.44  5124.2  293.38  5202.3   295.3  5291.7  297.47
#Mann= 9 ,-1 , 0
  3809.6     .05       0  3934.2     .16       0  4286.4     .05       0
  4454.8     .16       0  4839.1     .12       0  4987.1     .07       0
  4993.1     .12       0  5092.9     .16       0  5202.3     .05       0
Bank Sta=4957.2,5012
XS Rating Curve= 0 ,0
Exp/Cntr=0.3,0.1

Type RM Length L Ch R = 1 ,24226   ,367,367,367
BEGIN DESCRIPTION:
INDIAN CREEK 1 23.0
END DESCRIPTION:
XS GIS Cut Line= 3
      3644986.77     10704254.21      3644347.91     10703591.04
      3643854.88     10703448.69
#Sta/Elev= 30
  4138.2   304.9  4294.7  304.88  4400.7  302.13  4563.3  296.12  4683.7  290.43
  4690.6  289.25    4712  288.76  4733.1   290.1  4740.3  289.51  4747.2  287.38
  4818.6  284.92  4895.7  281.64  4938.1  282.32  4966.4  281.34  4973.6  282.58
  4987.8  281.36  4994.7  275.08  4998.9  274.92  5001.7  274.42  5004.9  274.92
  5016.1  275.24    5023  282.08  5030.2  282.56  5037.2  281.84  5223.9  285.74
  5371.6  291.02    5432  291.63  5444.1  292.96  5463.2  292.53  5572.2  296.04
#Mann= 5 ,-1 , 0
  4138.2     .16       0  4818.6     .12       0  4998.9     .07       0
  5004.9     .12       0  5223.9     .05       0
Bank Sta=4973.6,5030.2
XS Rating Curve= 0 ,0
Exp/Cntr=0.3,0.1

Type RM Length L Ch R = 1 ,23859   ,529,529,529
BEGIN DESCRIPTION:
INDIAN CREEK 1 22.0
END DESCRIPTION:
XS GIS Cut Line= 3
      3645580.51     10703188.27      3644499.61     10703360.19
       3643799.6     10703360.19
#Sta/Elev= 30
  3833.7  308.13  4151.5  307.78  4280.1  304.54  4319.5  301.71  4401.7  298.74
  4578.4  287.59    4594  285.58  4614.3  285.88  4645.7  282.64  4680.8  282.92
  4695.3  282.89  4715.5  279.34  4735.8  281.39  4745.9  279.59  4756.1  282.07
  4857.3  279.93  4918.1  282.23  4925.7  279.04  4938.2  279.64  4948.2  277.08
  4958.2  278.07  4995.2  273.65  4997.9  273.15  5001.2  273.65  5018.2  277.38
  5028.2  285.06  5098.2  289.35    5155  289.99  5477.2  295.19  5628.2  297.74
#Mann= 7 ,-1 , 0
  3833.7     .05       0  4151.5     .16       0  4680.8     .05       0
  4995.2     .04       0  5001.2     .05       0    5155     .08       0
  5477.2     .05       0
Bank Sta=4918.1,5028.2
XS Rating Curve= 0 ,0
Exp/Cntr=0.3,0.1

Type RM Length L Ch R = 1 ,23330   ,569,569,569
BEGIN DESCRIPTION:
INDIAN CREEK 1 21.0
END DESCRIPTION:
XS GIS Cut Line= 3
      3645084.06     10702931.31       3644236.8     10703049.37
       3643698.6     10703160.49
#Sta/Elev= 30
  4539.2  302.18  4668.2   296.7  4796.1  289.74  4806.2  288.17  4826.4  287.98
  4869.1  285.24  4967.8  280.76  4987.9  281.38  4997.5  274.72  4999.6  274.25
  5002.3  273.75  5005.6  274.25  5008.1  274.33  5018.2  280.81  5068.7  280.93
  5074.1  282.35  5109.1   284.6  5270.7  284.27  5280.7  282.45  5371.5  284.69
  5420.4  285.79    5473  285.29  5609.4  287.85  5676.7  290.19  5749.2  292.17
  5800.2  291.72  5817.3  293.26  5851.3  294.03  5881.9  293.42  5944.2  294.67
#Mann= 9 ,-1 , 0
  4539.2     .16       0  4668.2     .12       0  4869.1     .05       0
  4999.6     .04       0  5005.6     .05       0  5371.5     .08       0
    5473      .1       0  5609.4     .08       0  5676.7     .05       0
Bank Sta=4987.9,5018.2
XS Rating Curve= 0 ,0
Exp/Cntr=0.3,0.1

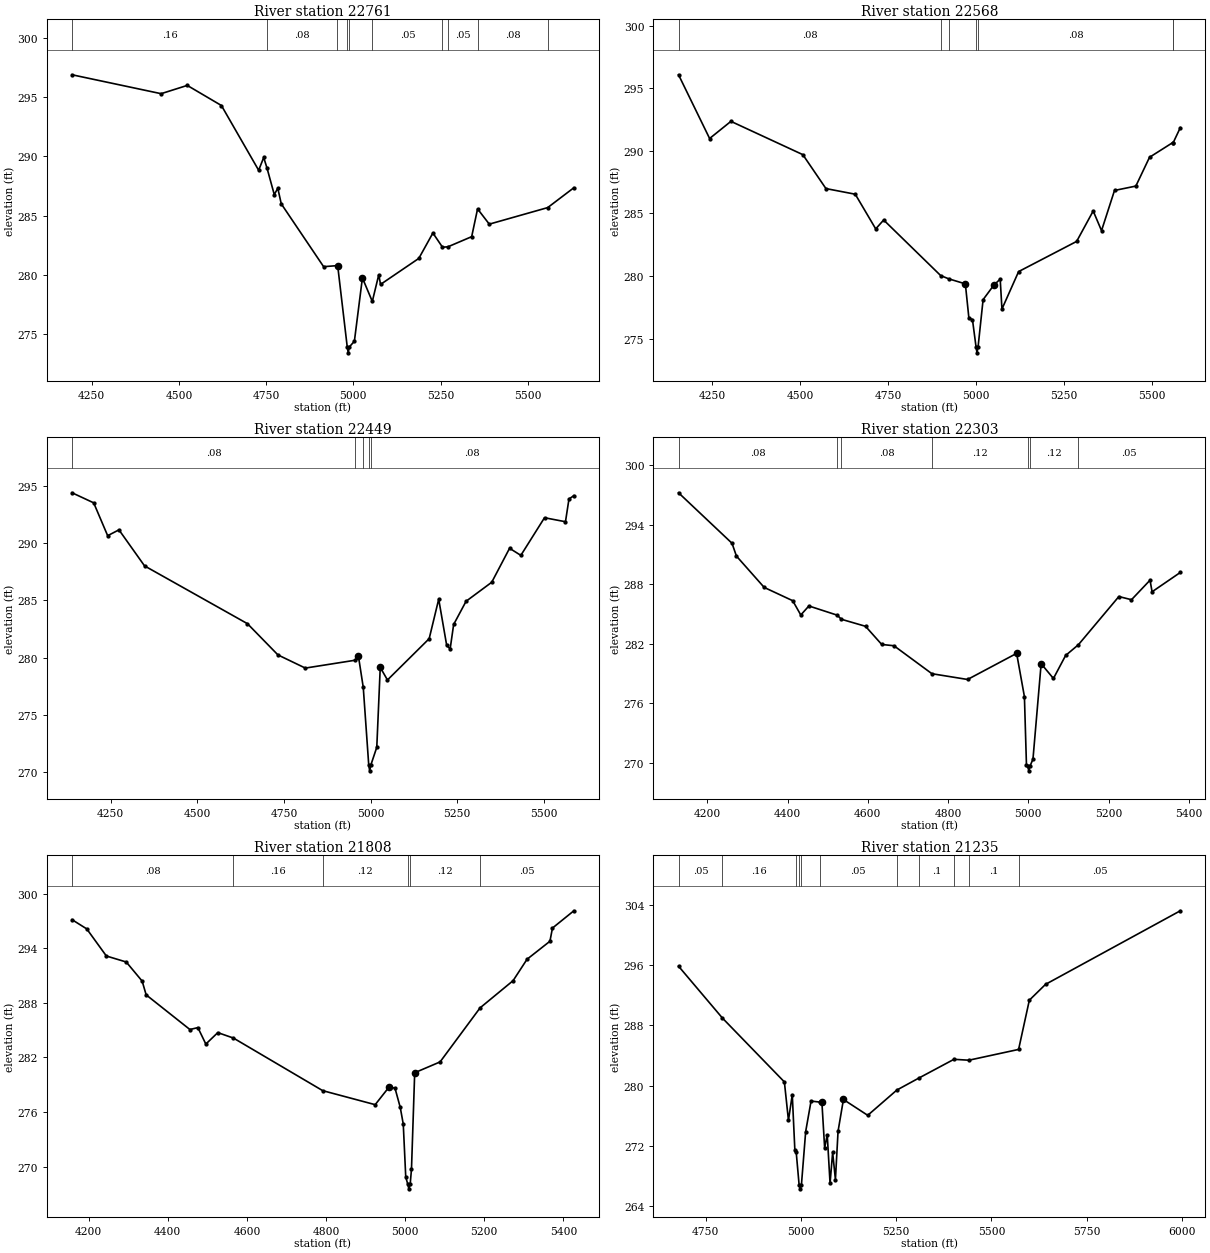
Type RM Length L Ch R = 1 ,22761   ,193,193,193
BEGIN DESCRIPTION:
Mapping XS 769f975d
END DESCRIPTION:
XS GIS Cut Line= 2
      3645323.29     10702567.63      3643899.66     10702775.97
#Sta/Elev= 30
  4193.5  296.91  4448.8  295.31  4523.8  296.01  4621.7  294.31  4728.5  288.83
    4743  289.91  4752.6     289  4773.3  286.77  4783.4  287.31  4793.3  285.99
  4914.8  280.67  4953.8  280.76  4955.2  280.73  4982.5  273.88  4985.3  273.38
  4988.5  273.88    5003  274.36    5026  279.72  5054.4  277.73  5072.9  279.99
    5078  279.17  5187.7  281.37  5228.1  283.52  5255.6  282.32    5271  282.35
  5339.3  283.21  5356.2  285.56  5389.8  284.27  5557.3  285.67  5632.3  287.35
#Mann= 10 ,-1 , 0
  4193.5     .16       0  4752.6     .08       0  4953.8     .16       0
  4982.5     .07       0  4988.5     .16       0  5054.4     .05       0
  5255.6     .08       0    5271     .05       0  5356.2     .08       0
  5557.3     .05       0
Bank Sta=4955.2,5026
XS Rating Curve= 0 ,0
Exp/Cntr=0.3,0.1

Type RM Length L Ch R = 1 ,22568   ,119,119,119
BEGIN DESCRIPTION:
Mapping XS 8d009595
END DESCRIPTION:
XS GIS Cut Line= 2
      3645337.15     10702435.69      3643924.33     10702637.03
#Sta/Elev= 30
  4153.8  296.07  4242.2  290.98  4302.8  292.35  4507.3  289.69    4573  286.98
  4656.4  286.53  4714.6  283.76  4737.2  284.47  4899.4  280.03  4922.4  279.77
  4969.5  279.37  4979.6  276.63  4989.7  276.52  4999.8  274.36  5002.6  273.86
  5005.8  274.36    5020  278.11  5050.3  279.26  5068.6  279.75  5073.6  277.36
    5121  280.35    5286  282.76  5333.1  285.19  5356.8  283.62  5393.7  286.83
  5454.4  287.18  5493.3  289.48  5559.7  290.66  5560.7  290.65  5580.9  291.85
#Mann= 7 ,-1 , 0
  4153.8     .08       0  4899.4     .16       0  4922.4     .08       0
  4999.8     .07       0  5005.8     .08       0  5559.7      .1       0
  5560.7     .08       0
Bank Sta=4969.5,5050.3
XS Rating Curve= 0 ,0
Exp/Cntr=0.3,0.1

Type RM Length L Ch R = 1 ,22449   ,146,146,146
BEGIN DESCRIPTION:
INDIAN CREEK 1 20.0
END DESCRIPTION:
XS GIS Cut Line= 2
      3645361.48     10702328.05      3643925.65     10702515.34
#Sta/Elev= 30
  4138.5   294.4  4200.9  293.52  4241.2  290.65  4273.8  291.16  4347.7  288.01
  4644.6  282.96  4732.6  280.23  4811.6  279.08  4956.1  279.77  4964.6  280.17
  4978.8  277.39  4994.6   270.6  4997.3   270.1  5000.6   270.6  5017.8  272.16
  5027.8  279.14  5048.6  278.04    5169  281.65  5196.5   285.1  5219.5  281.07
  5229.5  280.75  5239.6  282.89  5275.5  284.92  5349.5  286.58    5401  289.55
  5433.5  288.93  5501.8  292.22  5562.3  291.87  5572.4  293.86  5586.5  294.15
#Mann= 5 ,-1 , 0
  4138.5     .08       0  4956.1      .1       0  4978.8     .08       0
  4994.6     .07       0  5000.6     .08       0
Bank Sta=4964.6,5027.8
XS Rating Curve= 0 ,0
Exp/Cntr=0.3,0.1

Type RM Length L Ch R = 1 ,22303   ,495,495,495
BEGIN DESCRIPTION:
INDIAN CREEK 1 19.0
END DESCRIPTION:
XS GIS Cut Line= 3
      3645371.84     10702307.23      3644861.47     10702373.19
      3644139.28     10702230.84
#Sta/Elev= 30
  4128.3  297.22  4261.6  292.13  4272.6  290.84  4341.8  287.68  4412.9  286.34
    4433   284.9  4453.2  285.81    4524  284.88  4534.1  284.47  4594.4  283.76
  4634.7  281.93  4665.2   281.8  4759.9  278.98  4848.7   278.4    4971  281.03
  4990.4  276.67  4995.5  269.77  4998.5  269.69  5001.3  269.19  5004.5  269.69
  5011.7  270.36  5032.1  279.99  5062.7   278.5  5093.1  280.82  5124.9   281.9
  5225.8  286.76  5257.3  286.44  5303.5  288.41  5308.6  287.24    5379  289.19
#Mann= 7 ,-1 , 0
  4128.3     .08       0    4524     .16       0  4534.1     .08       0
  4759.9     .12       0  4998.5     .07       0  5004.5     .12       0
  5124.9     .05       0
Bank Sta=4971,5032.1
XS Rating Curve= 0 ,0
Exp/Cntr=0.3,0.1

Type RM Length L Ch R = 1 ,21808   ,573,573,573
BEGIN DESCRIPTION:
INDIAN CREEK 1 18.0
END DESCRIPTION:
XS GIS Cut Line= 3
      3645385.76      10702291.6      3644873.62     10702348.02
       3644409.9     10701754.29
#Sta/Elev= 30
    4158  297.14  4195.1  296.13  4244.7  293.15    4295  292.49  4335.2  290.39
  4345.3  288.88  4455.9  285.07  4476.1  285.28  4496.2  283.47  4526.4  284.73
    4566  284.13  4791.7  278.35  4924.3  276.81    4960  278.78  4974.5  278.61
  4987.7  276.51  4995.3  274.68  5001.6  268.85  5006.8  268.06  5009.5  267.56
  5012.8  268.06  5016.1  269.73  5024.2  280.32  5088.4  281.51  5189.5  287.45
    5273  290.44  5308.2  292.79  5366.1  294.77  5372.5  296.22  5426.6  298.12
#Mann= 6 ,-1 , 0
    4158     .08       0    4566     .16       0  4791.7     .12       0
  5006.8     .07       0  5012.8     .12       0  5189.5     .05       0
Bank Sta=4960,5024.2
XS Rating Curve= 0 ,0
Exp/Cntr=0.3,0.1

Type RM Length L Ch R = 1 ,21235   ,471,471,471
BEGIN DESCRIPTION:
INDIAN CREEK 1 17.0
END DESCRIPTION:
XS GIS Cut Line= 3
      3645399.58     10702210.17      3645149.61     10702060.19
      3644399.63     10701360.21
#Sta/Elev= 30
  4678.6  295.83    4794  288.94  4956.5  280.48  4967.2  275.38  4977.2  278.79
    4984  271.44  4987.5  271.19  4995.2   266.8    4998   266.3  5001.2   266.8
  5012.4   273.9  5026.5  277.94  5048.9  277.81  5054.9  277.85  5062.2  271.73
    5069  273.47  5076.4  267.04  5083.2  271.13  5090.5  267.53  5097.4  273.93
  5111.5  278.15  5175.3  276.05  5251.7   279.4  5310.2  281.01  5401.7  283.48
  5440.8  283.36  5571.4  284.79  5599.6  291.32  5642.1  293.42    5996  303.18
#Mann= 11 ,-1 , 0
  4678.6     .05       0    4794     .16       0  4987.5     .12       0
  4995.2     .07       0  5001.2     .12       0  5048.9     .05       0
  5251.7     .08       0  5310.2      .1       0  5401.7     .15       0
  5440.8      .1       0  5571.4     .05       0
Bank Sta=5054.9,5111.5
XS Rating Curve= 0 ,0
Exp/Cntr=0.3,0.1