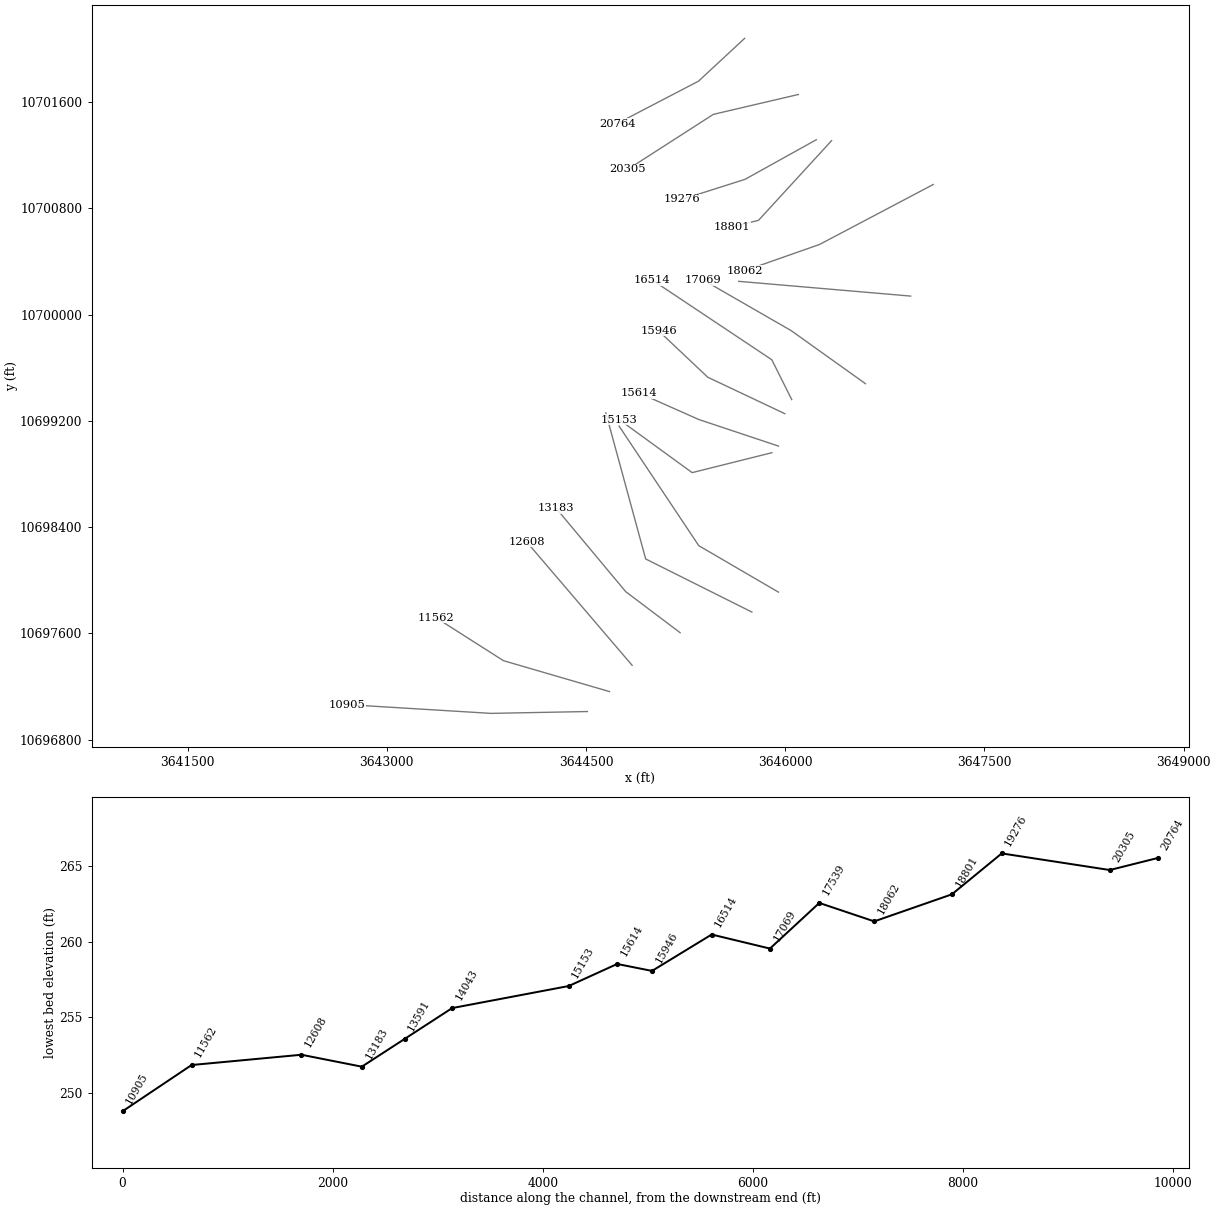
HEC-RAS study INDIAN CREEK 1.prj: INDIAN CREEK 1 Base Level Engineering

--- INDIAN CREEK 1.g01 (geometry) --- (continued)

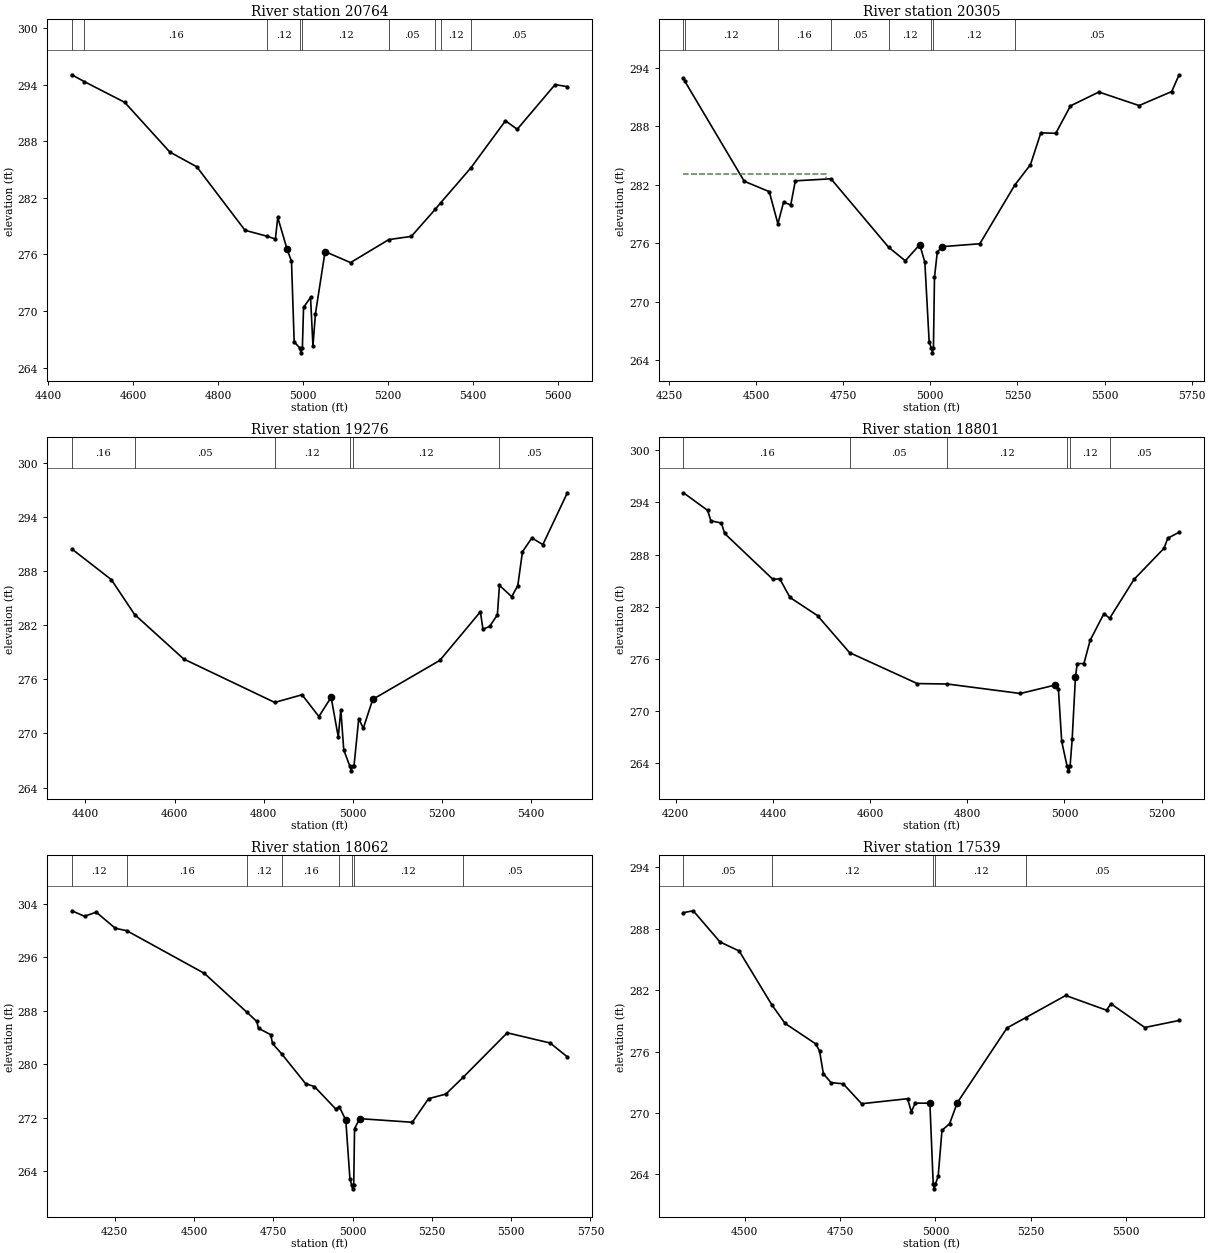
Type RM Length L Ch R = 1 ,20764   ,459,459,459
BEGIN DESCRIPTION:
INDIAN CREEK 1 16.0
END DESCRIPTION:
XS GIS Cut Line= 3
      3645695.13     10702080.62      3645347.52      10701758.1
      3644734.01     10701438.62
#Sta/Elev= 30
  4455.4  295.05  4485.2  294.32  4579.9  292.13    4686  286.86  4749.5  285.29
  4862.9  278.56  4915.3  277.92  4934.4  277.63    4940  279.92  4962.1  276.53
  4972.3  275.27  4978.6  266.74  4991.9  266.06  4994.6  265.56  4997.9  266.06
  5000.7  270.38  5017.1  271.44  5022.8   266.3  5028.7  269.73  5051.3   276.3
  5111.2  275.13  5201.2  277.57  5254.2  277.91  5310.6  280.79  5323.8   281.5
  5394.1  285.17  5475.6  290.17  5503.3  289.27  5592.4  294.01  5621.3  293.79
#Mann= 9 ,-1 , 0
  4455.4     .05       0  4485.2     .16       0  4915.3     .12       0
  4991.9     .07       0  4997.9     .12       0  5201.2     .05       0
  5310.6     .08       0  5323.8     .12       0  5394.1     .05       0
Bank Sta=4962.1,5051.3
XS Rating Curve= 0 ,0
Exp/Cntr=0.3,0.1

Type RM Length L Ch R = 1 ,20305   ,1029,1029,1029
BEGIN DESCRIPTION:
INDIAN CREEK 1 15.0
END DESCRIPTION:
XS GIS Cut Line= 3
      3646099.36      10701657.8      3645459.21     10701508.07
      3644815.97      10701094.4
#Sta/Elev= 30
  4291.8  292.94    4296  292.63  4466.1  282.38    4538  281.31  4562.8  278.01
  4579.1  280.24  4599.6  279.94  4612.8  282.42    4715  282.63  4880.5   275.6
  4928.3  274.21  4969.8  275.87  4984.4  274.07  4996.9  265.86  5003.1  265.26
  5005.9  264.76  5009.1  265.26  5012.1  272.52  5020.1  275.08  5033.2  275.66
  5142.2  275.96  5242.6  281.99  5287.5  284.08  5317.3  287.35  5360.1   287.3
  5402.4  290.12  5483.8  291.54  5599.2  290.15  5692.9  291.59    5714  293.31
#Mann= 8 ,-1 , 0
  4291.8     .16       0    4296     .12       0  4562.8     .16       0
    4715     .05       0  4880.5     .12       0  5003.1     .07       0
  5009.1     .12       0  5242.6     .05       0
#XS Ineff= 2 , 0
         4699.92  283.13
Permanent Ineff=
       F       F
Bank Sta=4969.8,5033.2
XS Rating Curve= 0 ,0
Exp/Cntr=0.3,0.1

Type RM Length L Ch R = 1 ,19276   ,475,475,475
BEGIN DESCRIPTION:
INDIAN CREEK 1 14.0
END DESCRIPTION:
XS GIS Cut Line= 3
      3646234.47     10701316.98      3645698.03     10701018.81
      3645223.65     10700868.05
#Sta/Elev= 30
  4369.4  290.45  4458.1  287.05  4510.4  283.18  4620.5  278.25  4824.6  273.44
  4885.9  274.29  4923.6  271.88  4951.1  274.01  4967.1  269.61  4972.8  272.64
  4979.4  268.17  4993.2  266.36  4995.9  265.86  4999.2  266.36  5002.5  266.45
    5013  271.65  5023.2  270.57  5044.4  273.78  5194.9   278.1  5285.8  283.48
  5291.6  281.55  5306.8  281.87  5323.9  283.15  5328.6  286.41  5356.1  285.16
  5369.7  286.39  5380.2  290.14  5401.2  291.66  5425.9  290.93  5480.9  296.67
#Mann= 6 ,-1 , 0
  4369.4     .16       0  4510.4     .05       0  4824.6     .12       0
  4993.2     .07       0  4999.2     .12       0  5328.6     .05       0
Bank Sta=4951.1,5044.4
XS Rating Curve= 0 ,0
Exp/Cntr=0.3,0.1

Type RM Length L Ch R = 1 ,18801   ,739,739,739
BEGIN DESCRIPTION:
INDIAN CREEK 1 13.0
END DESCRIPTION:
XS GIS Cut Line= 3
       3646349.6     10701310.18      3645799.61     10700710.19
      3645599.59     10700660.18
#Sta/Elev= 30
  4215.9  295.11  4265.5  293.09  4272.3  291.89  4293.9  291.63  4300.7  290.43
    4400  285.16  4414.1  285.22  4435.1  283.08  4491.8  280.99  4557.7  276.74
  4697.2  273.18    4759  273.13  4909.3  272.04  4980.2     273  4987.6  272.56
  4994.4  266.53  5005.6  263.65  5008.3  263.15  5011.6  263.65    5016  266.84
  5022.7  273.96  5026.4  275.48  5040.1  275.48    5053  278.16  5081.4  281.23
  5093.1  280.68  5143.2  285.15  5205.1  288.74  5212.8  289.89    5236  290.57
#Mann= 6 ,-1 , 0
  4215.9     .16       0  4557.7     .05       0    4759     .12       0
  5005.6     .07       0  5011.6     .12       0  5093.1     .05       0
Bank Sta=4980.2,5022.7
XS Rating Curve= 0 ,0
Exp/Cntr=0.3,0.1

Type RM Length L Ch R = 1 ,18062   ,523,523,523
BEGIN DESCRIPTION:
INDIAN CREEK 1 12.0
END DESCRIPTION:
XS GIS Cut Line= 3
      3647115.23     10700979.91      3646258.92     10700528.33
      3645698.25     10700331.52
#Sta/Elev= 30
    4115  302.96  4155.3  302.14  4192.1  302.75  4252.6  300.33  4288.1  299.99
  4533.2  293.59  4667.5  287.76  4697.9  286.42  4703.8  285.37  4742.2  284.42
  4747.8  283.11  4777.1  281.53  4852.3  277.09    4880  276.66  4946.6  273.33
  4958.8   273.6  4978.8  271.65  4991.9  262.84  4997.8  261.86  5000.5  261.36
  5003.8  261.86  5006.4  270.37  5022.8  271.86  5188.4  271.32  5239.8  274.85
  5294.3  275.54  5348.4  278.03  5487.7   284.7  5622.9  283.18  5677.3   281.1
#Mann= 8 ,-1 , 0
    4115     .12       0  4288.1     .16       0  4667.5     .12       0
  4777.1     .16       0  4958.8     .12       0  4997.8     .07       0
  5003.8     .12       0  5348.4     .05       0
Bank Sta=4978.8,5022.8
XS Rating Curve= 0 ,0
Exp/Cntr=0.3,0.1

Type RM Length L Ch R = 1 ,17539   ,470,470,470
BEGIN DESCRIPTION:
Mapping XS 512bda2d
END DESCRIPTION:
XS GIS Cut Line= 2
      3646945.17     10700139.65      3645650.03     10700250.76
#Sta/Elev= 30
  4339.1  289.58  4364.8  289.76    4435  286.71  4485.2  285.83  4570.4  280.59
  4605.6  278.75  4685.9  276.75    4696  276.06    4706  273.84  4726.1  272.96
    4758  272.85  4806.4   270.9  4926.8  271.39  4936.8  270.11  4946.9  270.96
  4985.4  270.95  4994.1  263.08  4996.8  262.58  5000.1  263.08  5007.1  263.79
  5017.1  268.29  5037.2  268.96  5057.3     271  5187.8  278.31  5236.5  279.31
  5341.6  281.48  5448.7  280.04  5460.3  280.67  5549.1  278.35    5639  279.04
#Mann= 5 ,-1 , 0
  4339.1     .05       0  4570.4     .12       0  4994.1     .07       0
  5000.1     .12       0  5236.5     .05       0
Bank Sta=4985.4,5057.3
XS Rating Curve= 0 ,0
Exp/Cntr=0.3,0.1

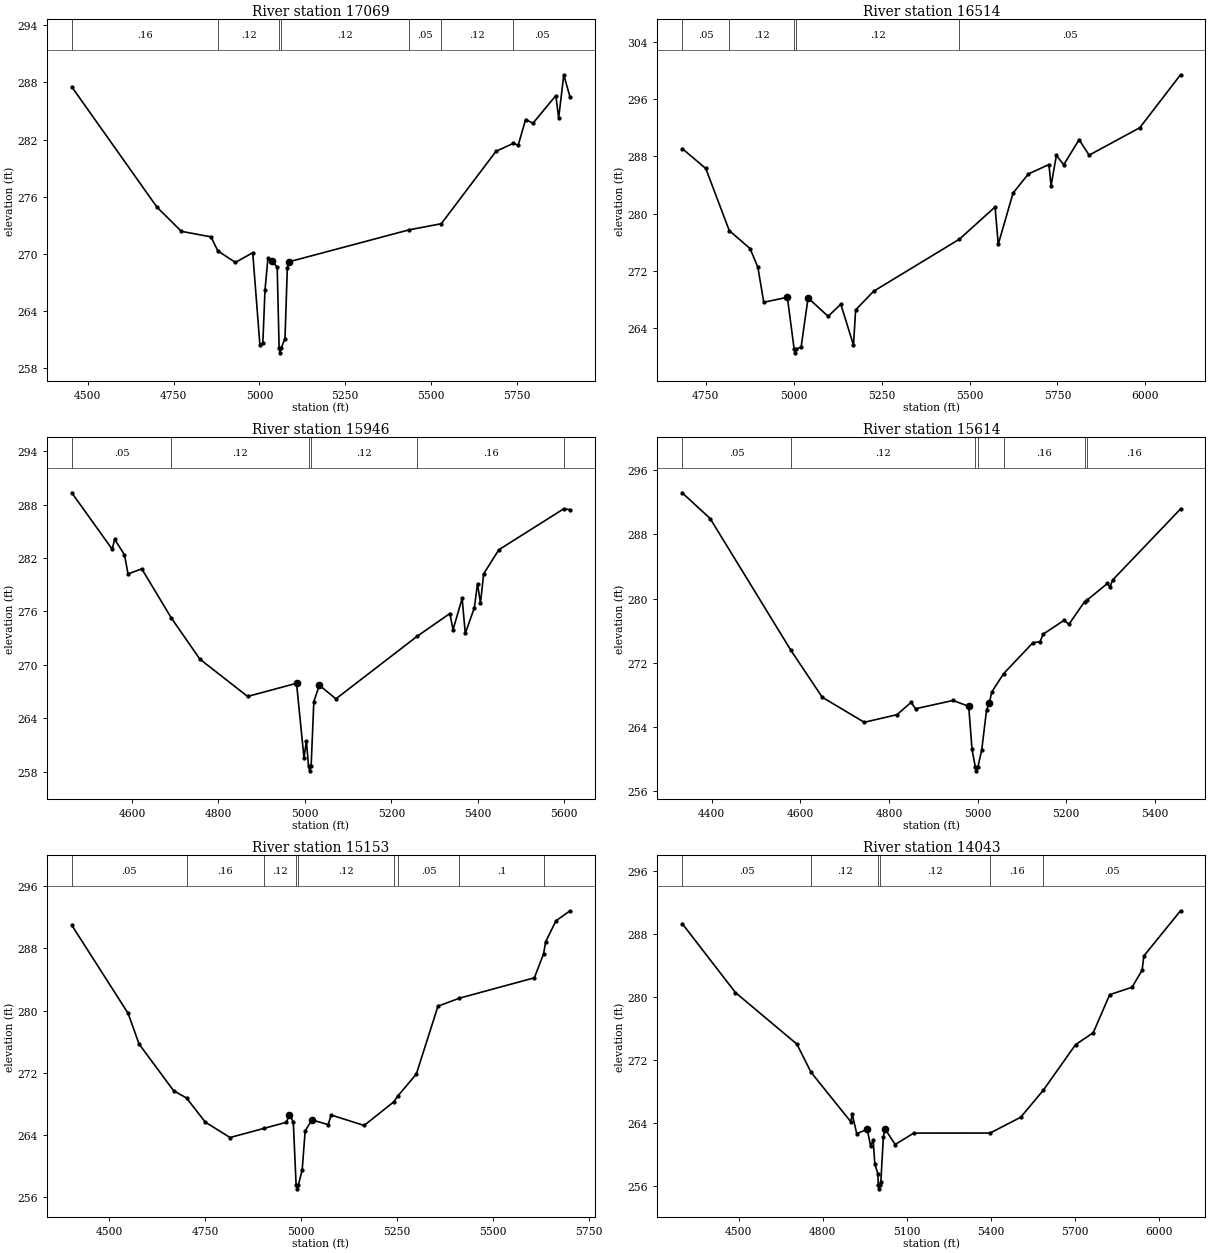
Type RM Length L Ch R = 1 ,17069   ,555,555,555
BEGIN DESCRIPTION:
INDIAN CREEK 1 11.0
END DESCRIPTION:
XS GIS Cut Line= 3
      3646604.82     10699479.95      3646045.82     10699879.24
      3645383.65     10700260.59
#Sta/Elev= 30
  4453.5  287.54  4701.5  274.89  4772.7  272.34  4858.8  271.76  4878.9  270.28
    4930  269.07  4980.4  270.09  5001.3  260.41  5009.9  260.58  5016.1  266.12
  5024.7  269.52  5037.5  269.23  5051.7  268.55  5057.3  260.06  5060.1  259.56
  5063.3  260.06  5074.4  261.06  5081.2  268.51  5087.3  269.15    5436   272.5
  5529.5  273.14  5688.8  280.76  5739.6   281.6  5753.5   281.4    5775   284.1
  5796.6  283.72  5863.1  286.62  5871.3  284.27  5886.2  288.81  5904.6  286.45
#Mann= 7 ,-1 , 0
  4453.5     .16       0  4878.9     .12       0  5057.3     .07       0
  5063.3     .12       0    5436     .05       0  5529.5     .12       0
  5739.6     .05       0
Bank Sta=5037.5,5087.3
XS Rating Curve= 0 ,0
Exp/Cntr=0.3,0.1

Type RM Length L Ch R = 1 ,16514   ,568,568,568
BEGIN DESCRIPTION:
INDIAN CREEK 1 10.0
END DESCRIPTION:
XS GIS Cut Line= 3
      3646049.62     10699360.17      3645899.61     10699660.19
      3644999.61     10700260.19
#Sta/Elev= 30
  4682.9   289.1    4750  286.31  4816.8  277.61  4875.8   275.1  4898.1   272.5
  4914.9  267.57    4982  268.27  5001.4  260.99  5004.1  260.49  5007.4  260.99
  5021.3  261.34  5040.9  268.18    5098   265.6    5134   267.3  5170.1  261.56
  5176.1   266.5  5227.2  269.11  5471.3  276.41  5572.7  280.92  5581.7  275.68
  5623.8  282.86  5667.3  285.54  5725.9  286.86  5731.9  283.89    5747  288.14
    5768  286.83  5811.6  290.34  5840.1  288.17  5984.3  292.02    6100  299.43
#Mann= 5 ,-1 , 0
  4682.9     .05       0  4816.8     .12       0  5001.4     .07       0
  5007.4     .12       0  5471.3     .05       0
Bank Sta=4982,5040.9
XS Rating Curve= 0 ,0
Exp/Cntr=0.3,0.1

Type RM Length L Ch R = 1 ,15946   ,332,332,332
BEGIN DESCRIPTION:
INDIAN CREEK 1 9.0
END DESCRIPTION:
XS GIS Cut Line= 3
      3645997.25     10699254.22      3645417.35     10699528.54
      3645045.83     10699879.23
#Sta/Elev= 30
    4461  289.33  4554.6  282.98  4560.1  284.11  4582.9  282.36  4591.1  280.21
  4622.9  280.78  4690.8  275.29  4757.1  270.64  4867.7  266.44  4980.8  267.92
    4998  259.54  5003.6  261.44  5008.5  258.58  5011.3  258.08  5014.5  258.58
  5020.8  265.87  5033.6   267.7  5071.8  266.17  5260.2  273.22  5335.4  275.76
  5342.7  273.94  5363.7  277.46    5371  273.53    5392  276.41  5399.3  279.12
  5406.2  276.92  5413.5  280.22  5448.7  282.93  5598.4  287.52  5613.4  287.44
#Mann= 6 ,-1 , 0
    4461     .05       0  4690.8     .12       0  5008.5     .07       0
  5014.5     .12       0  5260.2     .16       0  5598.4     .05       0
Bank Sta=4980.8,5033.6
XS Rating Curve= 0 ,0
Exp/Cntr=0.3,0.1

Type RM Length L Ch R = 1 ,15614   ,461,461,461
BEGIN DESCRIPTION:
INDIAN CREEK 1 8.0
END DESCRIPTION:
XS GIS Cut Line= 3
       3645949.6     10699010.19      3645349.61     10699210.19
       3644899.6     10699410.19
#Sta/Elev= 30
  4333.1  293.19  4396.3  289.98  4578.4  273.57  4649.3  267.71  4744.2  264.59
    4818  265.54  4849.6  267.06  4860.1  266.28  4944.5  267.31  4979.9  266.58
  4987.4  261.22  4994.7  259.04  4997.4  258.54  5000.7  259.04  5009.3  261.13
  5020.3  266.16  5026.4  266.98  5031.9  268.36  5058.7  270.65  5124.9  274.51
  5140.6  274.62  5148.2  275.58  5194.7  277.28  5206.3  276.81  5241.3  279.61
  5247.7  279.84  5293.2   281.9  5298.6  281.41  5304.8  282.32    5458  291.17
#Mann= 7 ,-1 , 0
  4333.1     .05       0  4578.4     .12       0  4994.7     .07       0
  5000.7     .12       0  5058.7     .16       0  5241.3     .05       0
  5247.7     .16       0
Bank Sta=4979.9,5026.4
XS Rating Curve= 0 ,0
Exp/Cntr=0.3,0.1

Type RM Length L Ch R = 1 ,15153   ,1110,1110,1110
BEGIN DESCRIPTION:
INDIAN CREEK 1 7.0
END DESCRIPTION:
XS GIS Cut Line= 3
      3645899.65      10698960.2      3645299.61     10698810.19
      3644749.59      10699210.2
#Sta/Elev= 30
  4401.8  290.99  4548.7  279.64  4577.1  275.71  4667.3  269.69    4701  268.76
  4749.7  265.66  4814.2  263.68  4903.1  264.86    4961  265.64  4968.8  266.62
  4979.1   265.7  4986.4  257.58  4989.1  257.08  4992.4  257.58  5002.3  259.53
    5010  264.53  5027.6  265.95  5069.8  265.34  5077.9  266.57  5163.7  265.23
  5241.3  268.28    5252  269.05  5299.7  271.84  5356.1  280.57    5412   281.6
  5607.3  284.22  5631.4  287.32  5636.6  288.84  5663.7  291.56  5700.4  292.84
#Mann= 9 ,-1 , 0
  4401.8     .05       0    4701     .16       0  4903.1     .12       0
  4986.4     .07       0  4992.4     .12       0  5241.3     .16       0
    5252     .05       0    5412      .1       0  5631.4     .05       0
Bank Sta=4968.8,5027.6
XS Rating Curve= 0 ,0
Exp/Cntr=0.3,0.1

Type RM Length L Ch R = 1 ,14043   ,452,452,452
BEGIN DESCRIPTION:
INDIAN CREEK 1 6.0
END DESCRIPTION:
XS GIS Cut Line= 3
      3645949.59      10697910.2      3645349.61     10698260.19
      3644749.59     10699160.22
#Sta/Elev= 30
  4298.7  289.37  4488.5  280.59  4707.6  274.03    4758  270.45  4899.4  264.17
  4905.2  265.08  4920.9  262.63  4958.2   263.2  4970.1  261.12  4979.7  261.77
  4985.4  258.76  4996.3  257.55  4997.8  256.12  5000.6  255.62  5003.8  256.12
  5006.8  256.47  5015.8  262.22  5021.8  263.24  5057.9  261.26    5124  262.71
  5396.6  262.72  5505.6  264.73  5586.1  268.17  5700.9  273.96    5764  275.48
  5822.6  280.32  5902.2  281.26  5938.3  283.44  5944.3  285.24    6075  290.99
#Mann= 6 ,-1 , 0
  4298.7     .05       0    4758     .12       0  4997.8     .07       0
  5003.8     .12       0  5396.6     .16       0  5586.1     .05       0
Bank Sta=4958.2,5021.8
XS Rating Curve= 0 ,0
Exp/Cntr=0.3,0.1

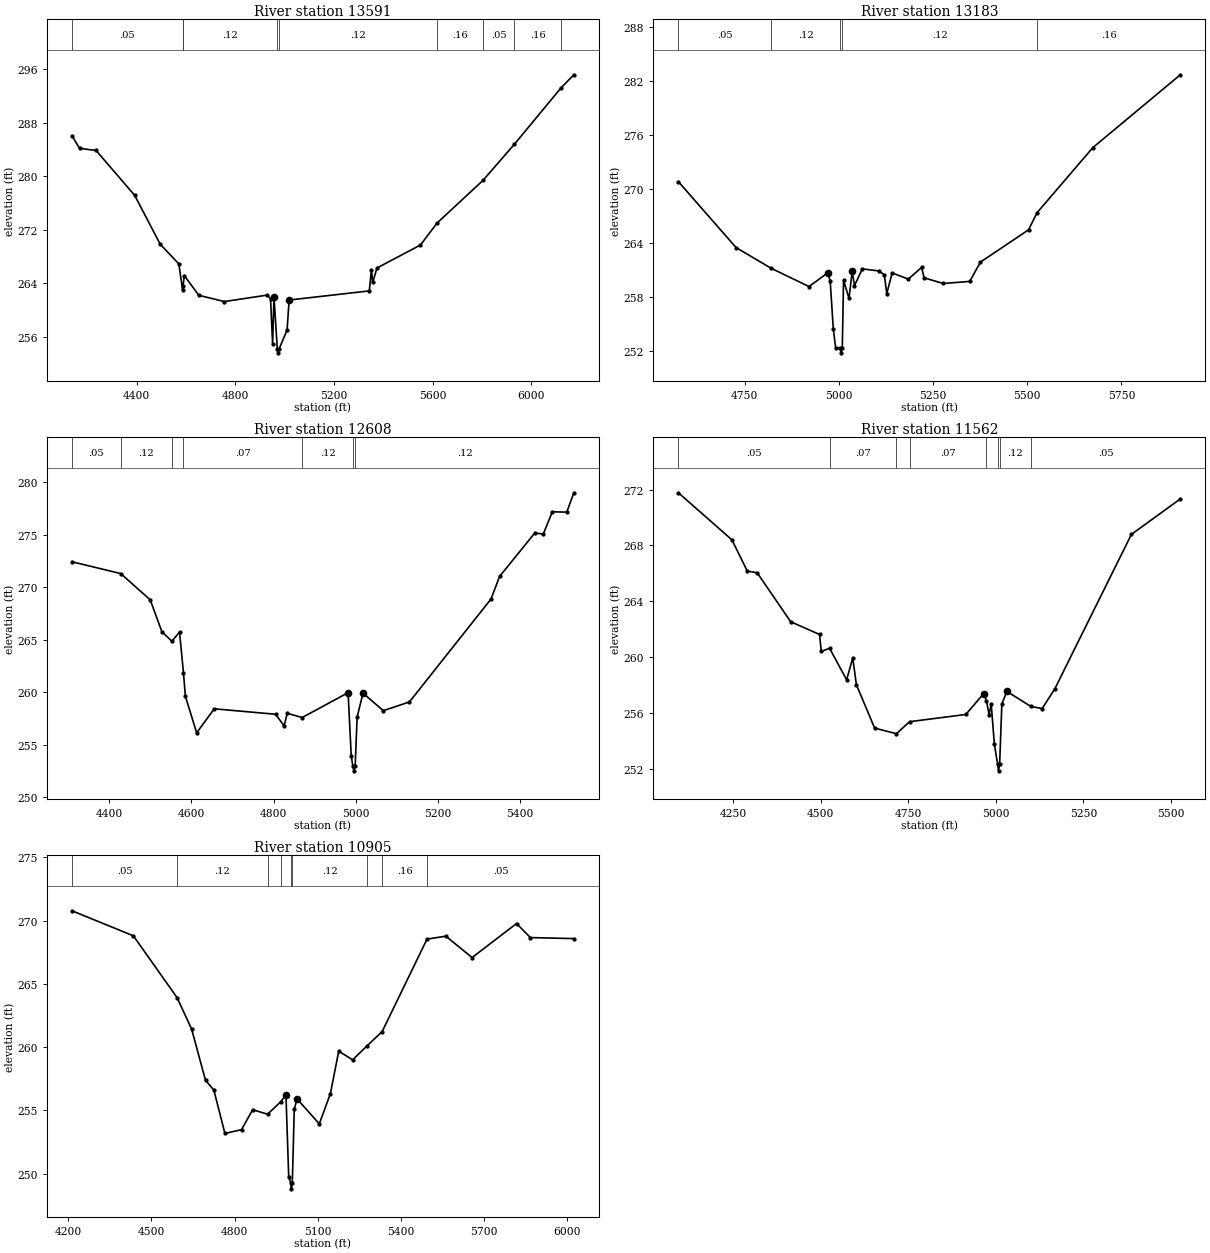
Type RM Length L Ch R = 1 ,13591   ,408,408,408
BEGIN DESCRIPTION:
INDIAN CREEK 1 5.0
END DESCRIPTION:
XS GIS Cut Line= 3
       3645749.6     10697760.19      3644949.61     10698160.19
      3644649.61     10699260.19
#Sta/Elev= 30
  4137.6  286.06  4168.3  284.16  4235.4  283.84  4391.9  277.13  4495.4  269.82
  4570.8  266.88    4586  263.04  4587.8  263.56  4593.2  265.13  4651.9  262.18
  4755.3  261.25  4928.6  262.21  4942.6  261.69    4951  254.97  4956.6  261.93
  4970.3  254.08  4973.1  253.58  4976.3  254.08  5009.7  256.99    5018  261.48
    5343  262.84  5351.6  266.01  5356.8   264.1  5374.1  266.27  5550.3   269.7
  5617.5  272.98  5803.9  279.37  5930.4  284.74  6120.2   293.2  6172.2  295.16
#Mann= 9 ,-1 , 0
  4137.6     .05       0    4586     .07       0  4587.8     .12       0
  4970.3     .07       0  4976.3     .12       0  5617.5     .16       0
  5803.9     .05       0  5930.4     .16       0  6120.2     .05       0
Bank Sta=4956.6,5018
XS Rating Curve= 0 ,0
Exp/Cntr=0.3,0.1

Type RM Length L Ch R = 1 ,13183   ,575,575,575
BEGIN DESCRIPTION:
Mapping XS 54c639ef
END DESCRIPTION:
XS GIS Cut Line= 3
      3645209.05      10697604.9       3644799.3     10697913.96
      3644274.99     10698542.43
#Sta/Elev= 30
  4574.4  270.79  4727.3  263.46  4820.5  261.15  4920.9  259.12  4970.8  260.65
  4977.1  259.71  4985.4  254.38  4991.7  252.28  5003.2  252.24    5006  251.74
  5009.2  252.24  5012.5  259.81  5027.1  257.81  5035.4   260.8  5041.6  259.23
  5062.5  261.09  5106.4  260.85  5120.7  260.43  5127.2  258.34  5141.6  260.63
  5184.5  259.95  5219.7  261.25  5226.2  260.09  5276.9  259.46  5347.2  259.69
  5375.8  261.84  5503.4  265.43  5525.8  267.33  5673.9  274.58  5906.1  282.69
#Mann= 5 ,-1 , 0
  4574.4     .05       0  4820.5     .12       0  5003.2     .07       0
  5009.2     .12       0  5525.8     .16       0
Bank Sta=4970.8,5035.4
XS Rating Curve= 0 ,0
Exp/Cntr=0.3,0.1

Type RM Length L Ch R = 1 ,12608   ,1046,1046,1046
BEGIN DESCRIPTION:
Mapping XS f7ccdcd4
END DESCRIPTION:
XS GIS Cut Line= 2
      3644847.58      10697359.3      3644053.55     10698288.56
#Sta/Elev= 30
    4309  272.41  4427.7  271.29  4499.6  268.79  4528.1  265.75  4552.5  264.85
    4571  265.73  4580.5  261.88  4585.2  259.63  4612.7  256.14  4655.5  258.43
  4804.8  257.91  4825.6  256.81  4833.3     258  4869.7   257.6  4981.5  259.96
  4989.2  253.94  4992.8  253.03  4995.6  252.53  4998.8  253.03  5003.5  257.64
  5017.8  259.92  5067.2  258.25  5130.8  259.08  5329.6  268.87  5350.4  271.01
    5436  275.14  5456.9  275.05  5478.9  277.16    5514  277.13  5531.3  278.97
#Mann= 7 ,-1 , 0
    4309     .05       0  4427.7     .12       0  4552.5     .16       0
  4580.5     .07       0  4869.7     .12       0  4992.8     .07       0
  4998.8     .12       0
Bank Sta=4981.5,5017.8
XS Rating Curve= 0 ,0
Exp/Cntr=0.3,0.1

Type RM Length L Ch R = 1 ,11562   ,657,657,657
BEGIN DESCRIPTION:
INDIAN CREEK 1 4.0
END DESCRIPTION:
XS GIS Cut Line= 3
      3644677.45     10697161.39      3643878.83     10697394.03
      3643371.86     10697716.96
#Sta/Elev= 30
    4094  271.77  4246.7   268.4  4290.6  266.16  4318.9  266.04  4414.6  262.53
  4496.8  261.62    4502   260.4  4525.6  260.63  4574.2  258.37  4591.7  259.94
  4602.1  258.02  4654.2  254.91  4716.5  254.51    4754  255.37  4914.6  255.89
  4965.8  257.39  4973.5  256.86    4981  255.88    4987  256.63    4996  253.77
  5005.1  252.35  5007.9  251.85  5011.1  252.35  5017.4  256.63  5031.6  257.54
  5100.5  256.46  5132.5  256.31  5168.9  257.74  5387.3  268.79  5526.9  271.33
#Mann= 8 ,-1 , 0
    4094     .05       0  4525.6     .07       0  4716.5     .05       0
    4754     .07       0  4973.5     .12       0  5005.1     .07       0
  5011.1     .12       0  5100.5     .05       0
Bank Sta=4965.8,5031.6
XS Rating Curve= 0 ,0
Exp/Cntr=0.3,0.1

Type RM Length L Ch R = 1 ,10905   ,1106,1106,1106
BEGIN DESCRIPTION:
INDIAN CREEK 1 3.0
END DESCRIPTION:
XS GIS Cut Line= 3
      3644511.07     10697011.18      3643785.41     10696997.29
      3642703.31     10697063.19
#Sta/Elev= 30
  4213.2  270.78  4434.7   268.8  4592.3  263.91  4644.7  261.43  4694.8  257.37
  4724.8  256.61  4764.8  253.17  4824.8  253.47  4864.8  255.05  4918.7  254.69
  4966.2  255.68  4984.9  256.22  4994.9  249.73  5001.9  249.29  5004.7  248.79
  5007.9  249.29  5014.9  255.09    5025   255.9  5105.1  253.93  5145.2  256.32
  5175.2  259.68  5225.3  258.99  5278.4  260.12  5331.9  261.23  5493.6  268.54
  5561.7  268.77  5656.1  267.08  5816.4  269.77  5866.5  268.66  6023.1  268.58
#Mann= 9 ,-1 , 0
  4213.2     .05       0  4592.3     .12       0  4918.7     .07       0
  4966.2     .12       0  5001.9     .07       0  5007.9     .12       0
  5278.4     .05       0  5331.9     .16       0  5493.6     .05       0
Bank Sta=4984.9,5025
XS Rating Curve= 0 ,0
Exp/Cntr=0.3,0.1