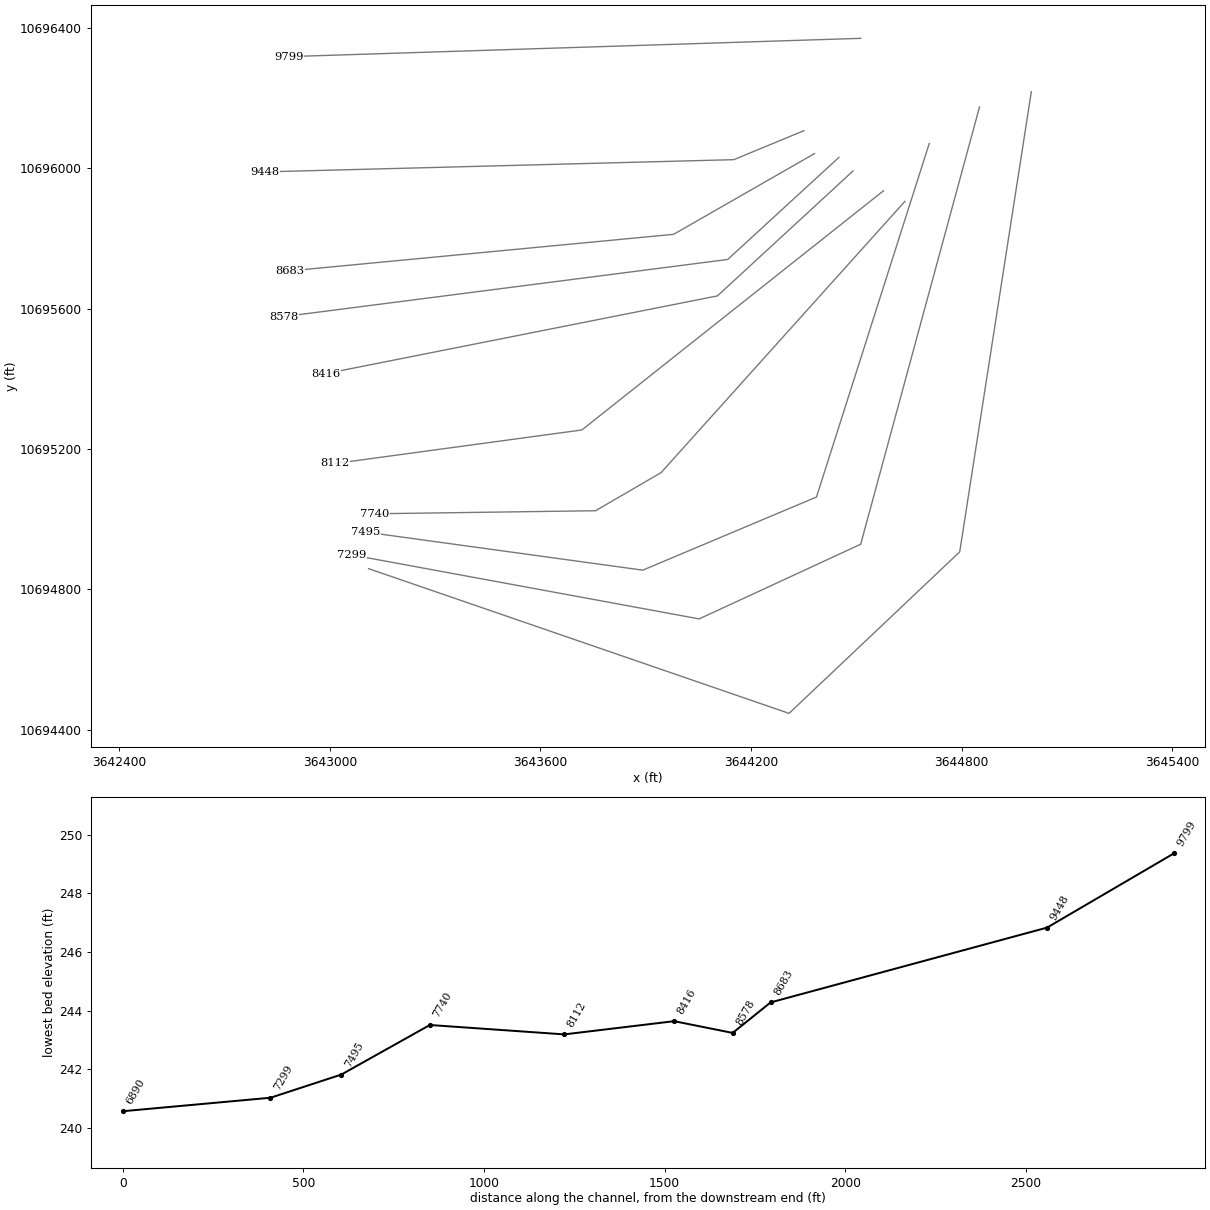
HEC-RAS study INDIAN CREEK 1.prj: INDIAN CREEK 1 Base Level Engineering

--- INDIAN CREEK 1.g01 (geometry) --- (continued)

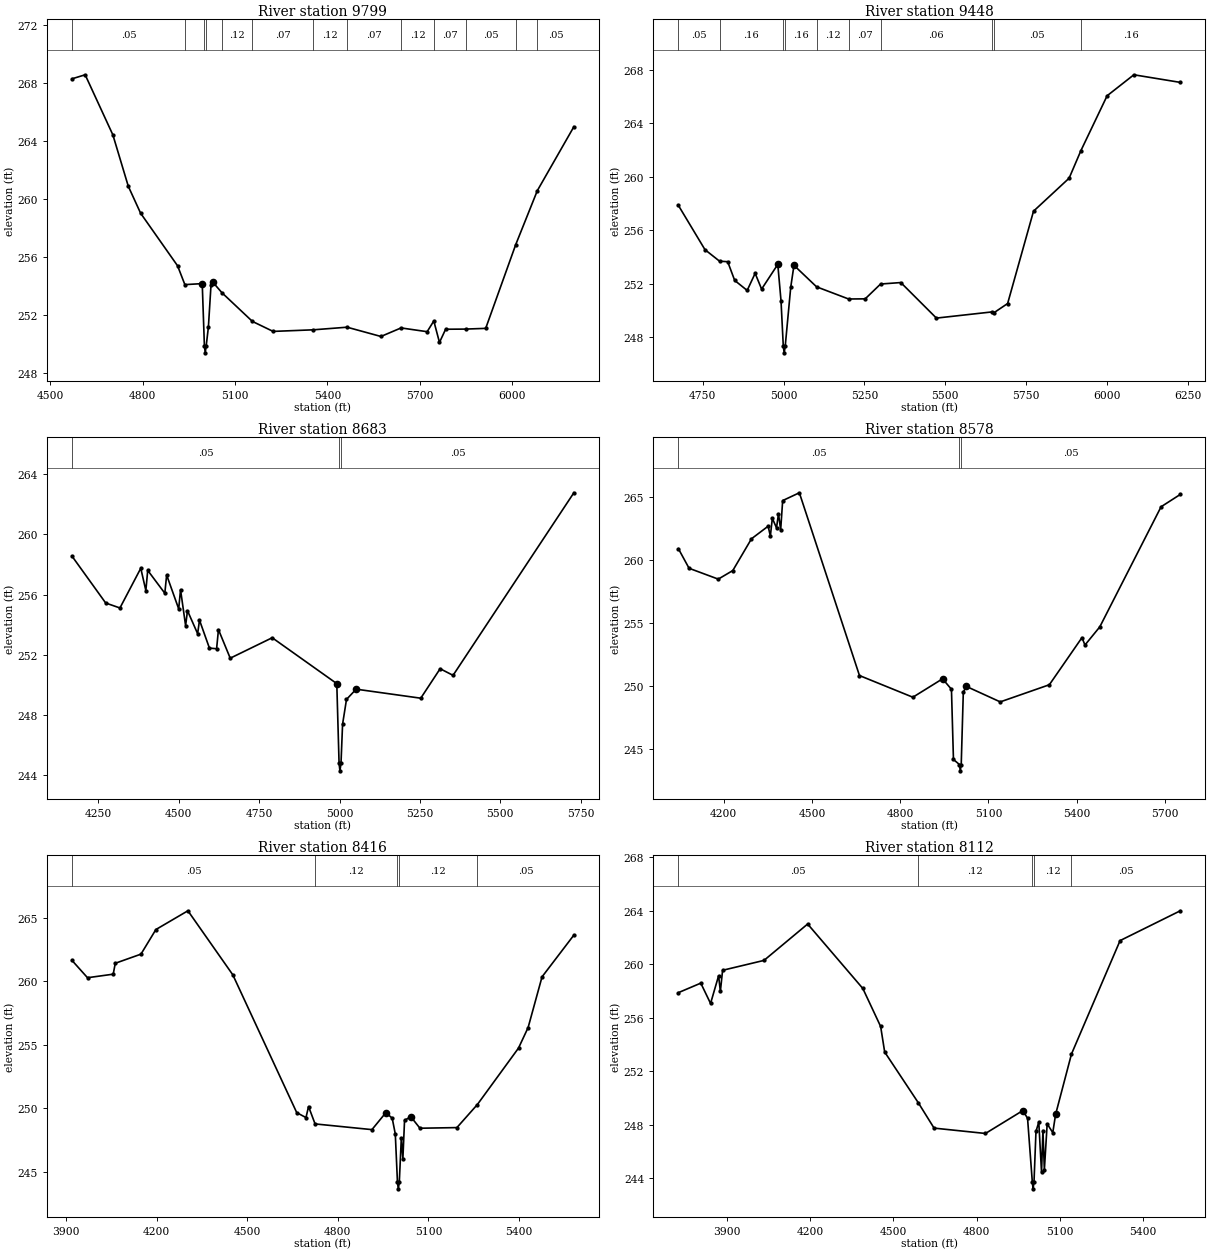
Type RM Length L Ch R = 1 ,9799    ,351,351,351
BEGIN DESCRIPTION:
INDIAN CREEK 1 2.0
END DESCRIPTION:
XS GIS Cut Line= 2
      3644512.48     10696369.72      3642883.41     10696317.67
#Sta/Elev= 30
  4570.4  268.28  4613.3  268.56  4703.3  264.41  4753.4  260.86  4793.4     259
  4913.4  255.37  4937.1  254.07  4993.5  254.14  5000.5  249.86  5003.2  249.36
  5006.5  249.86  5013.5  251.14    5022  254.05    5027  254.26  5057.5  253.51
  5156.4  251.53  5223.6  250.84  5354.2  250.95  5463.9  251.13  5573.8  250.49
  5639.2  251.08  5723.9  250.82  5745.5  251.56  5763.9  250.08  5783.9  250.99
  5848.6     251    5914  251.05  6011.5  256.83  6081.7  260.56  6200.3  264.97
#Mann= 13 ,-1 , 0
  4570.4     .05       0  4937.1     .16       0  5000.5     .07       0
  5006.5     .16       0  5057.5     .12       0  5156.4     .07       0
  5354.2     .12       0  5463.9     .07       0  5639.2     .12       0
  5745.5     .07       0  5848.6     .05       0  6011.5     .16       0
  6081.7     .05       0
Bank Sta=4993.5,5027
XS Rating Curve= 0 ,0
Exp/Cntr=0.3,0.1

Type RM Length L Ch R = 1 ,9448    ,765,765,765
BEGIN DESCRIPTION:
Mapping XS 2c3f6ab2
END DESCRIPTION:
XS GIS Cut Line= 3
      3644350.34     10696106.56      3644150.68     10696024.09
      3642816.05     10695989.37
#Sta/Elev= 30
  4675.2  257.86  4757.3  254.55  4802.3  253.69  4827.5  253.65  4849.1  252.25
  4887.7   251.5  4912.3  252.78  4932.3   251.6  4982.3  253.45  4992.3  250.72
  4999.3  247.33  5002.1  246.83  5005.3  247.33  5022.3  251.74  5032.3  253.38
  5102.2  251.77  5201.1  250.86  5252.4  250.87    5300  251.98  5362.5  252.09
  5472.5  249.43  5643.4  249.89    5649  249.81  5692.6  250.52  5772.6  257.43
  5882.6   259.9  5919.2  261.97  6000.1  266.07  6082.7  267.64  6226.3  267.07
#Mann= 10 ,-1 , 0
  4675.2     .05       0  4802.3     .16       0  4999.3     .07       0
  5005.3     .16       0  5102.2     .12       0  5201.1     .07       0
    5300     .06       0  5643.4     .07       0    5649     .05       0
  5919.2     .16       0
Bank Sta=4982.3,5032.3
XS Rating Curve= 0 ,0
Exp/Cntr=0.3,0.1

Type RM Length L Ch R = 1 ,8683    ,105,105,105
BEGIN DESCRIPTION:
Mapping XS 573f9b3a
END DESCRIPTION:
XS GIS Cut Line= 3
      3644380.68     10696041.43      3643979.24     10695811.42
      3642885.46     10695707.25
#Sta/Elev= 30
  4167.5  258.56  4272.5  255.44  4316.8  255.11  4381.6  257.75  4397.4  256.27
  4403.2  257.61  4456.4  256.09  4462.1   257.3  4499.6  255.05  4505.3  256.33
  4521.1  253.93  4526.9  254.93  4558.5   253.4  4564.3   254.3  4595.2  252.44
  4617.5   252.4  4623.3  253.67  4659.9  251.77  4790.5  253.13  4991.4  250.08
  4998.5  244.78  5001.2  244.28  5004.5  244.78  5009.4  247.38  5021.6  249.03
  5051.7  249.71  5252.6  249.11  5312.9  251.07  5353.1  250.63  5728.9  262.77
#Mann= 3 ,-1 , 0
  4167.5     .05       0  4998.5     .03       0  5004.5     .05       0
Bank Sta=4991.4,5051.7
XS Rating Curve= 0 ,0
Exp/Cntr=0.3,0.1

Type RM Length L Ch R = 1 ,8578    ,162,162,162
BEGIN DESCRIPTION:
Mapping XS 42e84838
END DESCRIPTION:
XS GIS Cut Line= 3
      3644450.18     10696030.62      3644133.32      10695739.8
      3642868.13     10695577.04
#Sta/Elev= 30
  4046.2  260.86  4082.4  259.31  4181.6  258.45    4231  259.13  4294.5  261.65
  4351.2  262.65  4358.6  261.86  4365.4  263.27  4379.6  262.52  4386.3  263.64
  4393.7  262.36  4400.5  264.68  4457.2   265.3  4661.5   250.8    4843  249.08
  4943.8  250.54  4974.1  249.71  4980.9  244.14  5001.3  243.74  5004.1  243.24
  5007.3  243.74  5014.4  249.48  5024.5  249.94  5139.9  248.71  5306.8  250.07
  5417.7  253.81  5427.8  253.22  5478.2  254.66  5686.5  264.19  5751.9  265.17
#Mann= 3 ,-1 , 0
  4046.2     .05       0  5001.3     .03       0  5007.3     .05       0
Bank Sta=4943.8,5024.5
XS Rating Curve= 0 ,0
Exp/Cntr=0.3,0.1

Type RM Length L Ch R = 1 ,8416    ,304,304,304
BEGIN DESCRIPTION:
Mapping XS 92b3af63
END DESCRIPTION:
XS GIS Cut Line= 3
      3644490.46     10695991.96      3644104.17     10695636.06
      3642989.95     10695414.95
#Sta/Elev= 30
    3920  261.66  3971.5  260.29  4056.6  260.57  4063.4  261.43  4148.4  262.15
  4197.8  264.09  4303.8  265.57  4452.4  260.52    4664  249.65  4694.6  249.26
  4703.1  250.13  4724.7  248.76  4912.9  248.31    4959  249.65    4980  249.21
  4990.2  247.97  4997.4  244.14  5000.2  243.64  5003.4  244.14  5010.2  247.66
  5015.3  246.01  5020.8  249.03  5041.2  249.34  5071.8  248.42  5194.1  248.47
  5261.9  250.29    5398  254.74  5429.8  256.36  5475.9  260.36  5581.2  263.65
#Mann= 5 ,-1 , 0
    3920     .05       0  4724.7     .12       0  4997.4     .07       0
  5003.4     .12       0  5261.9     .05       0
Bank Sta=4959,5041.2
XS Rating Curve= 0 ,0
Exp/Cntr=0.3,0.1

Type RM Length L Ch R = 1 ,8112    ,372,372,372
BEGIN DESCRIPTION:
Mapping XS 6232da0f
END DESCRIPTION:
XS GIS Cut Line= 3
      3644577.26     10695935.54      3643717.89     10695254.12
      3643014.79     10695158.63
#Sta/Elev= 30
  3726.9  257.86  3807.4  258.57  3842.6  257.05  3871.5  259.12  3877.9  257.95
  3885.9  259.53  4034.9  260.27    4192  262.99  4390.6  258.17  4454.7  255.33
  4469.2  253.42  4590.1  249.63    4647  247.73    4832  247.33  4966.3  249.04
  4983.4  248.47  5000.6  243.69  5003.3  243.19  5006.6  243.69  5013.7  247.48
  5023.8  248.18  5033.7  244.44  5038.8  247.55  5043.9  244.61    5054  248.05
  5074.2  247.39  5084.3  248.75  5141.5  253.27  5316.4  261.75  5533.2  263.98
#Mann= 5 ,-1 , 0
  3726.9     .05       0  4590.1     .12       0  5000.6     .07       0
  5006.6     .12       0  5141.5     .05       0
Bank Sta=4966.3,5084.3
XS Rating Curve= 0 ,0
Exp/Cntr=0.3,0.1

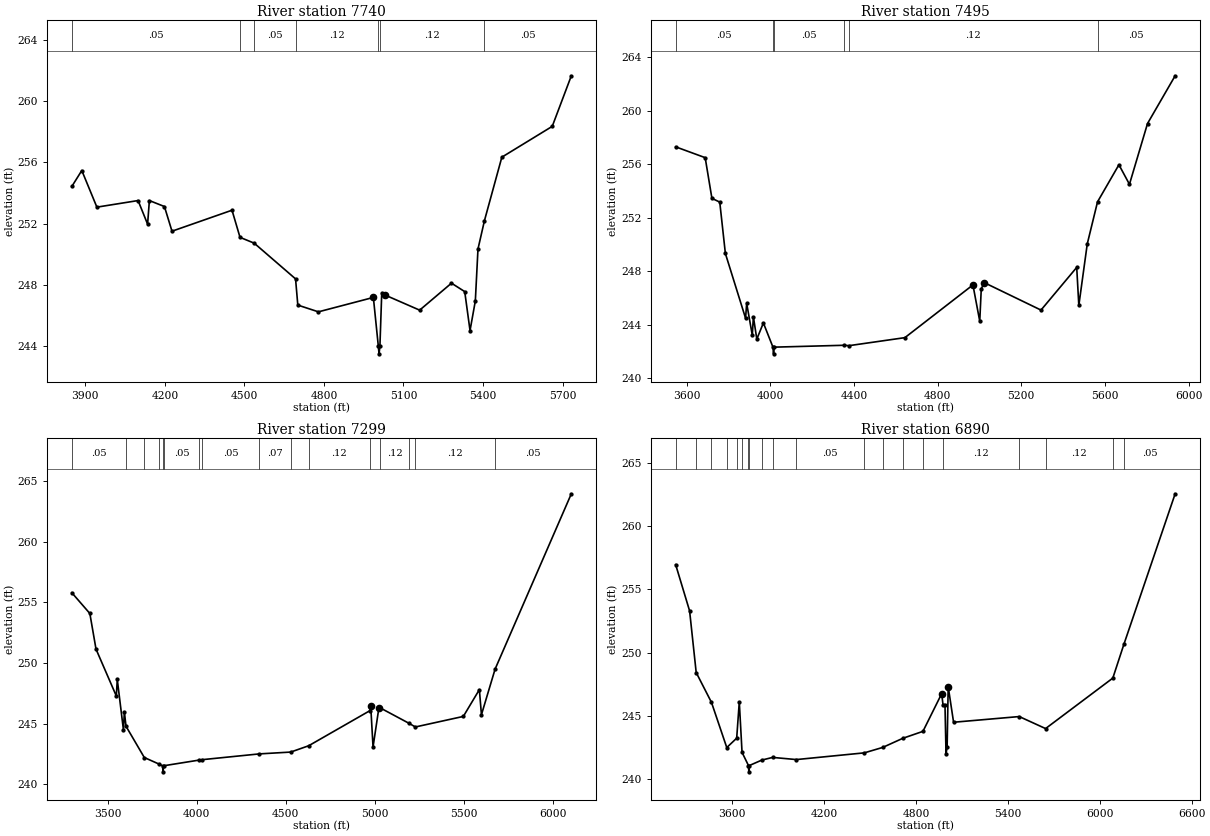
Type RM Length L Ch R = 1 ,7740    ,245,245,245
BEGIN DESCRIPTION:
Mapping XS cff9b79b
END DESCRIPTION:
XS GIS Cut Line= 4
      3644638.02     10695905.15      3643943.58     10695132.59
      3643756.95     10695024.08      3643127.58      10695015.4
#Sta/Elev= 30
  3849.2  254.43  3886.8  255.47  3943.7  253.08  4099.1  253.51    4135  251.97
  4141.7  253.51  4198.5  253.12    4227  251.51  4453.4  252.88  4483.6  251.11
  4537.1  250.73  4693.1   248.4  4701.6  246.69  4779.3  246.25  4986.6  247.19
  5005.3  244.01    5008  243.51  5011.3  244.01  5018.1  247.45  5031.4  247.34
  5161.2  246.36  5281.2  248.12  5331.2  247.57  5351.2  245.03  5371.2  246.96
  5381.2  250.35  5405.6   252.2  5471.2  256.34  5661.3  258.35  5733.3  261.65
#Mann= 7 ,-1 , 0
  3849.2     .05       0  4483.6     .12       0  4537.1     .05       0
  4693.1     .12       0  5005.3     .07       0  5011.3     .12       0
  5405.6     .05       0
Bank Sta=4986.6,5031.4
XS Rating Curve= 0 ,0
Exp/Cntr=0.3,0.1

Type RM Length L Ch R = 1 ,7495    ,196,196,196
BEGIN DESCRIPTION:
Mapping XS 3d296ac4
END DESCRIPTION:
XS GIS Cut Line= 4
      3644707.47     10696070.08      3644386.29     10695063.14
       3643891.5     10694854.81      3643103.08     10694963.11
#Sta/Elev= 30
  3546.4  257.29  3687.7  256.48  3719.9  253.44  3757.4  253.16  3784.3  249.32
  3880.9  244.48  3886.2  245.59  3913.1  243.21  3918.3  244.59  3934.7  242.92
  3966.1  244.13  4011.9  242.32  4014.7  241.82  4017.9  242.32  4352.6  242.46
  4375.3  242.43  4643.1  243.03  4968.6  246.97  5001.2  244.26  5008.5  246.68
  5022.9  247.14  5294.2  245.09  5465.1  248.28  5475.2  245.44  5515.6  250.04
  5564.7  253.18    5667  255.95  5717.4  254.49  5803.8  259.03    5936   262.6
#Mann= 6 ,-1 , 0
  3546.4     .05       0  4011.9     .07       0  4017.9     .05       0
  4352.6     .07       0  4375.3     .12       0  5564.7     .05       0
Bank Sta=4968.6,5022.9
XS Rating Curve= 0 ,0
Exp/Cntr=0.3,0.1

Type RM Length L Ch R = 1 ,7299    ,409,409,409
BEGIN DESCRIPTION:
Mapping XS 2b974698
END DESCRIPTION:
XS GIS Cut Line= 4
      3644850.69     10696174.24      3644512.16      10694928.6
      3644052.09     10694715.92      3643063.59     10694898.01
#Sta/Elev= 30
  3299.4   255.8  3400.5  254.09  3435.1  251.15  3549.2  247.28  3554.4  248.65
    3589  244.49  3594.2  245.98  3603.4  244.79  3706.1  242.21  3790.3  241.66
  3808.4  241.53  3811.1  241.03  3814.4  241.53  4014.1     242  4028.9  242.03
  4351.7  242.51  4527.5  242.66  4628.3  243.18  4972.7  246.08  4976.4  246.49
  4989.6  243.08  5022.2  246.29  5031.4  246.29  5191.7  245.03  5227.1  244.73
  5496.2   245.6  5586.2  247.81  5597.8  245.74  5674.4   249.5  6102.2  263.96
#Mann= 16 ,-1 , 0
  3299.4     .05       0  3603.4     .12       0  3706.1     .07       0
  3790.3     .05       0  3808.4     .07       0  3814.4     .05       0
  4014.1     .07       0  4028.9     .05       0  4351.7     .07       0
  4527.5     .05       0  4628.3     .12       0  4972.7     .07       0
  5031.4     .12       0  5191.7     .07       0  5227.1     .12       0
  5674.4     .05       0
Bank Sta=4976.4,5022.2
XS Rating Curve= 0 ,0
Exp/Cntr=0.3,0.1

Type RM Length L Ch R = 1 ,6890    ,0,0,0
BEGIN DESCRIPTION:
INDIAN CREEK 1 1.0
END DESCRIPTION:
XS GIS Cut Line= 4
      3644998.27     10696217.65      3644794.28     10694906.89
      3644308.16     10694446.82      3643110.28     10694859.14
#Sta/Elev= 30
  3229.5  256.95  3320.7  253.29  3363.7  248.42  3463.5  246.06  3563.4  242.49
  3628.2  243.23  3645.2   246.1  3663.2  242.11  3705.1  241.07  3707.8  240.57
  3711.1  241.07  3792.5   241.5  3862.9  241.71  4018.2  241.54  4461.8  242.07
    4582   242.5  4713.1  243.22  4844.8  243.77  4967.2  246.75  4976.2  245.84
  4988.7  245.89  4995.6  242.01  5002.8   242.5  5009.7  247.31  5044.9  244.49
  5473.8  244.94  5645.9  243.99  6085.1  247.98  6157.1  250.64  6492.2  262.55
#Mann= 20 ,-1 , 0
  3229.5     .05       0  3363.7     .16       0  3463.5     .12       0
  3563.4     .07       0  3628.2     .12       0  3663.2     .07       0
  3705.1     .07       0  3711.1     .07       0  3792.5     .05       0
  3862.9     .07       0  4018.2     .05       0  4461.8     .07       0
    4582     .07       0  4713.1     .12       0  4844.8     .07       0
  4976.2     .12       0  5473.8     .07       0  5645.9     .12       0
  6085.1     .07       0  6157.1     .05       0
Bank Sta=4967.2,5009.7
XS Rating Curve= 0 ,0
Exp/Cntr=0.3,0.1

Chan Stop Cuts=-1
Use User Specified Reach Order=0
Composite Channel Slope=5