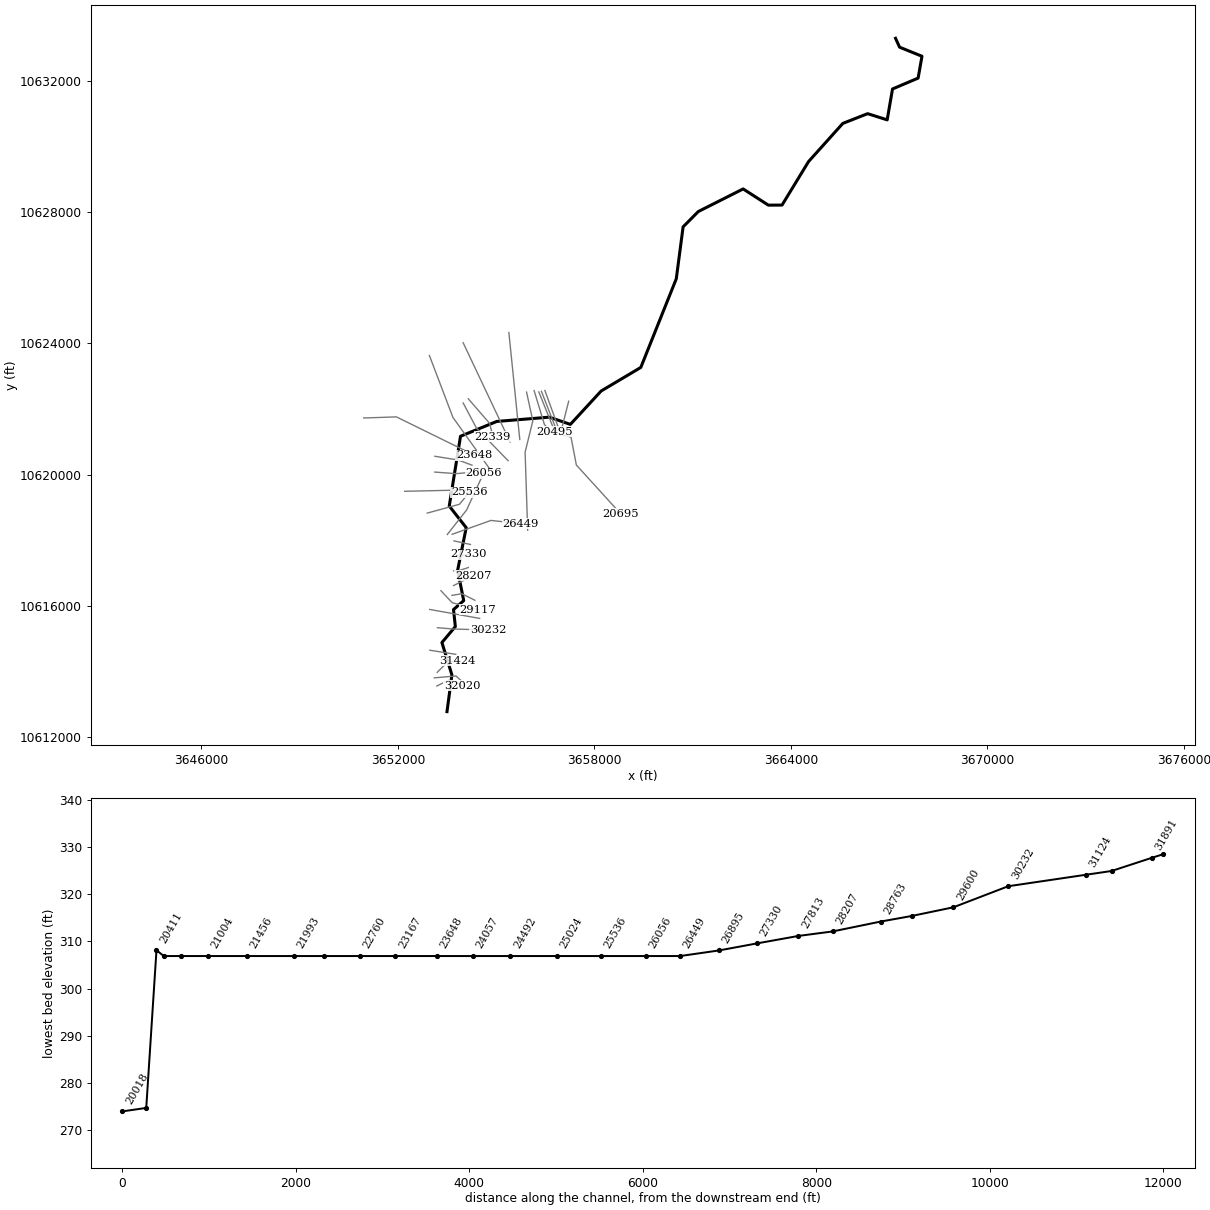
--- INDIAN CREEK 2.prj (project) ---

Proj Title=INDIAN CREEK 2 Base Level Engineering
Current Plan=p01
Default Exp/Contr=0.3,0.1
English Units
Geom File=g01
Flow File=f01
Plan File=p01
Y Axis Title=Elevation
X Axis Title(PF)=Main Channel Distance
X Axis Title(XS)=Station
BEGIN DESCRIPTION:
INDIAN CREEK 2
END DESCRIPTION:
DSS Export Rating Curves= 0
DSS Export Rating Curve Sorted= 0
DSS Export Volume Flow Curves= 0
DXF OffsetX= 0
DXF OffsetY= 0
DXF ScaleX= 1
DXF ScaleY= 10

--- INDIAN CREEK 2.p01 (plan) ---

Plan Title=Multiple Run
Short Identifier=Multiple
Geom File=g01
Flow File=f01
Subcritical Flow
K Sum by GR= 0
Std Step Tol= 0.01
Critical Tol= 0.01
Num of Std Step Trials= 20
Max Error Tol= 0.3
Flow Tol Ratio= 0.001
Split Flow NTrial= 30
Split Flow Tol= 0.02
Split Flow Ratio= 0.02
Log Output Level= 0
Friction Slope Method= 1
Unsteady Friction Slope Method= 2
Unsteady Bridges Friction Slope Method= 1
Parabolic Critical Depth
Global Vel Dist=  1 , 1 , 1
Global Log Level= 0
CheckData=True
Encroach Param= -1, 0, 0, 0
BEGIN DESCRIPTION:
Multiple Run
END DESCRIPTION:

--- INDIAN CREEK 2.f01 (steady flow) ---

Flow Title=Multiple
Program Version=4.10
Number of Profiles= 7
Profile Names=10-year,25-year,50-year,1pct_min,100-year,1pct_plu,500-year
River Rch & RM=INDIAN CREEK 2,Reach-1         ,32020
     601     816     994     890    1203    1627    1771
River Rch & RM=INDIAN CREEK 2,Reach-1         ,29600
     796    1092    1338    1203    1626    2200    2415
River Rch & RM=INDIAN CREEK 2,Reach-1         ,23167
     967    1336    1645    1484    2007    2715    3006
River Rch & RM=INDIAN CREEK 2,Reach-1         ,20695
    1322    1858    2315    2113    2858    3865    4376
River Rch & RM=INDIAN CREEK 2,Reach-1         ,16429
    1591    2245    2805    2564    3468    4690    5328
River Rch & RM=INDIAN CREEK 2,Reach-1         ,12898
    1882    2675    3357    3082    4169    5637    6460
River Rch & RM=INDIAN CREEK 2,Reach-1         ,11716
    1882    2675    3357    3082    4169    5637    6460
River Rch & RM=INDIAN CREEK 2,Reach-1         ,1298
    2197    3139    3953    3640    4923    6657    7674
Boundary for River Rch & Prof#=INDIAN CREEK 2,Reach-1         , 1
Up Type= 0
Dn Type= 3
Dn Slope=0.001
Boundary for River Rch & Prof#=INDIAN CREEK 2,Reach-1         , 2
Up Type= 0
Dn Type= 3
Dn Slope=0.001
Boundary for River Rch & Prof#=INDIAN CREEK 2,Reach-1         , 3
Up Type= 0
Dn Type= 3
Dn Slope=0.001
Boundary for River Rch & Prof#=INDIAN CREEK 2,Reach-1         , 4
Up Type= 0
Dn Type= 3
Dn Slope=0.001
Boundary for River Rch & Prof#=INDIAN CREEK 2,Reach-1         , 5
Up Type= 0
Dn Type= 3
Dn Slope=0.001
Boundary for River Rch & Prof#=INDIAN CREEK 2,Reach-1         , 6
Up Type= 0
Dn Type= 3
Dn Slope=0.001
Boundary for River Rch & Prof#=INDIAN CREEK 2,Reach-1         , 7
Up Type= 0
Dn Type= 3
Dn Slope=0.001
DSS Import GetInterval= 0
DSS Import GetPeak= 0
DSS Import FillOption= 0

--- INDIAN CREEK 2.g01 (geometry) ---

Geom Title=Existing Conditions
Program Version=4.10

River Reach=INDIAN CREEK 2  ,Reach-1
Reach XY= 30
      3653498.02     10612760.43      3653648.25       10613880.
        3653343.       10614870.        3653753.       10615357.
      3653697.25       10615877.       3654008.5       10616150.
      3653822.75       10617075.      3654084.75       10618377.
      3653566.75       10619037.      3653910.75       10621168.
       3655017.5       10621620.      3656623.75       10621751.
       3657264.5       10621530.        3658204.       10622549.
      3659415.25       10623269.       3660498.5       10625975.
      3660706.75       10627561.      3661171.25       10628029.
        3662540.       10628719.      3663309.25       10628224.
       3663727.5       10628226.        3664538.       10629556.
        3665584.       10630720.      3666340.25       10631017.
       3666937.5       10630828.       3667100.5       10631771.
      3667882.25       10632103.       3667999.5       10632770.
      3667315.75       10633047.      3667192.37      10633319.5

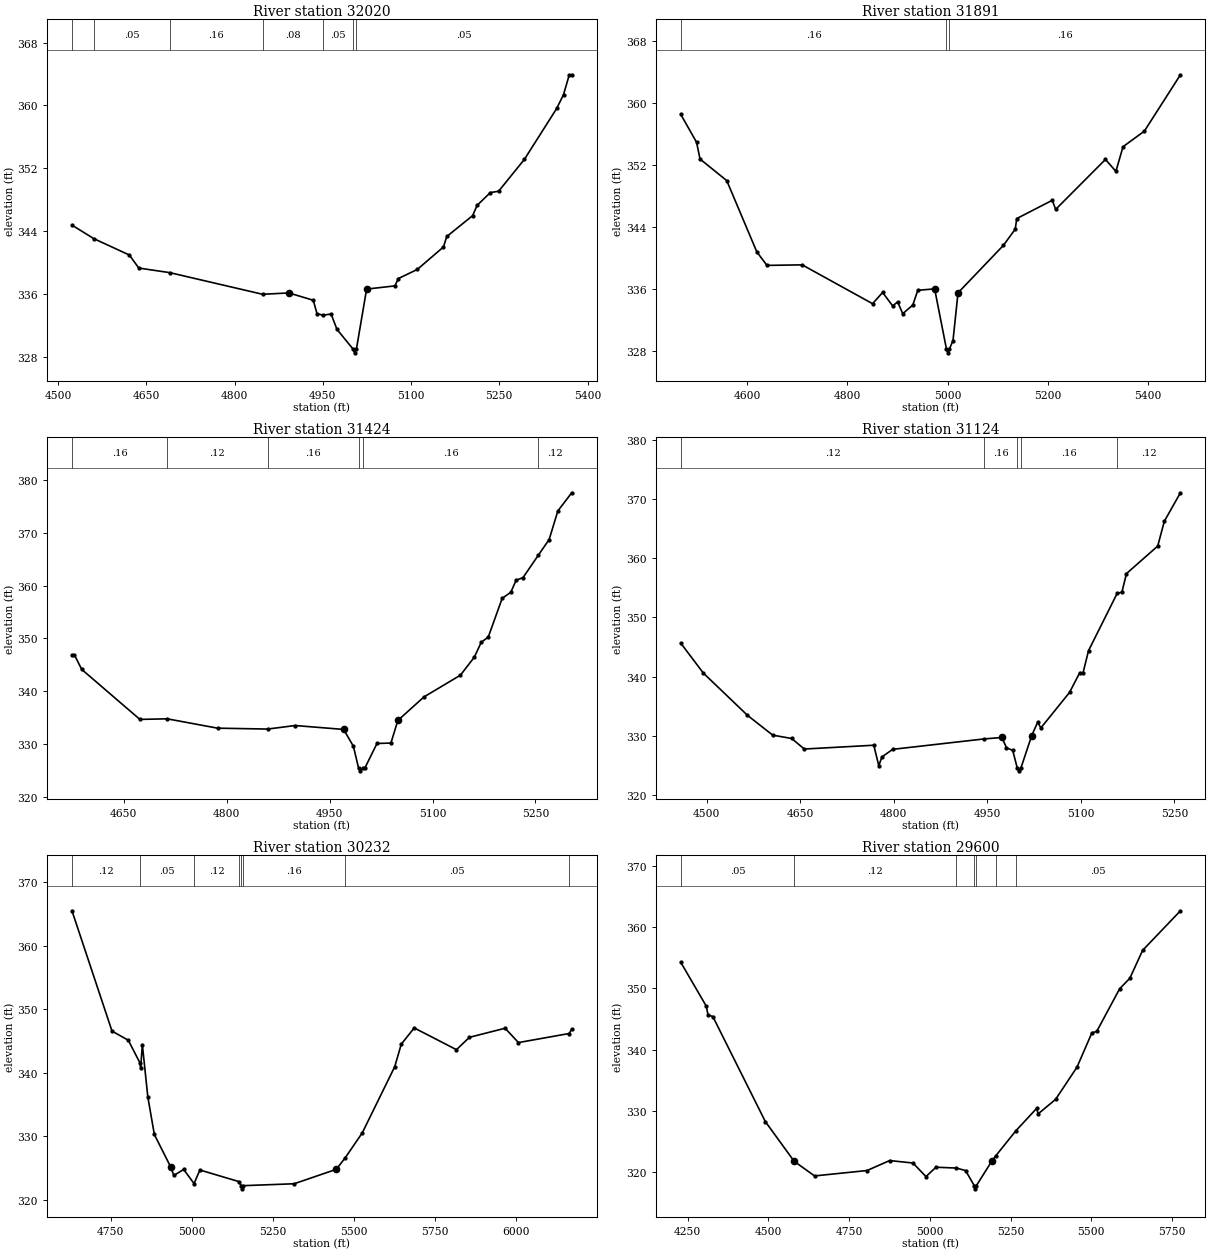
Type RM Length L Ch R = 1 ,32020   ,129,129,129
BEGIN DESCRIPTION:
Mapping XS 6702e750
END DESCRIPTION:
XS GIS Cut Line= 6
      3653187.15     10613542.75      3653495.31     10613694.66
      3653566.93     10613714.19      3653616.84     10613712.02
      3653686.29     10613701.17      3653961.89     10613555.78
#Sta/Elev= 30
  4523.4  344.76  4560.7  343.03    4621  340.95    4637  339.29  4689.4  338.71
  4847.5  335.95  4892.2  336.12  4933.7  335.19    4940  333.49  4950.2  333.28
    4964  333.44    4974  331.48  5001.1  328.99  5003.9  328.49  5007.1  328.99
  5024.4  336.61  5072.6  337.02  5078.3  337.95  5110.5  339.11    5155  341.97
  5160.7  343.31  5204.7  345.97  5212.2  347.27  5234.9  348.91  5248.8  349.07
  5292.8  353.15  5347.6  359.62  5359.2  361.39    5369  363.91  5373.1  363.91
#Mann= 7 ,-1 , 0
  4523.4     .16       0  4560.7     .05       0  4689.4     .16       0
  4847.5     .08       0  4950.2     .05       0  5001.1     .04       0
  5007.1     .05       0
Bank Sta=4892.2,5024.4
XS Rating Curve= 0 ,0
Exp/Cntr=0.3,0.1

Type RM Length L Ch R = 1 ,31891   ,467,467,467
BEGIN DESCRIPTION:
INDIAN CREEK 2 57.0
END DESCRIPTION:
XS GIS Cut Line= 3
      3653108.05      10613791.7      3653771.24     10613848.99
      3654017.79     10613626.75
#Sta/Elev= 30
  4467.3  358.51    4499   354.9  4505.9  352.74  4559.2  349.96  4619.2  340.77
  4639.5  339.02  4709.8  339.09  4850.3  334.08  4870.4  335.53  4890.4   333.8
  4900.5  334.31  4910.5  332.79  4930.6   333.9  4940.6  335.81  4974.2  335.99
  4997.8  328.24  5000.6  327.74  5003.8  328.24  5010.9  329.33  5020.9  335.48
  5111.3  341.59  5135.2   343.7  5138.1  345.06  5209.1  347.42  5215.8  346.24
  5315.2  352.69  5336.1  351.15  5350.3  354.33  5392.9  356.34  5464.9  363.61
#Mann= 3 ,-1 , 0
  4467.3     .16       0  4997.8     .07       0  5003.8     .16       0
Bank Sta=4974.2,5020.9
XS Rating Curve= 0 ,0
Exp/Cntr=0.3,0.1

Type RM Length L Ch R = 1 ,31424   ,300,300,300
BEGIN DESCRIPTION:
INDIAN CREEK 2 56.0
END DESCRIPTION:
XS GIS Cut Line= 3
      3653199.58     10613960.16      3653499.61     10614260.19
      3653799.57     10614310.18
#Sta/Elev= 30
  4574.4  346.88    4578  346.88  4588.6  344.14  4673.4  334.67  4713.2  334.78
  4786.6  333.01  4859.6  332.84  4899.7  333.51  4970.4  332.77  4984.6  329.58
  4992.2  325.43  4994.9  324.93  4998.2  325.43  5001.2  325.43    5019  330.11
  5039.3  330.19  5049.4  334.47  5087.4  338.92  5140.6  343.04  5160.9  346.46
    5171  349.28  5181.2  350.26  5201.5   357.6  5214.1  358.74  5221.7  361.01
  5231.9  361.53  5254.3  365.79  5269.9  368.72  5282.6  374.13  5302.8  377.58
#Mann= 6 ,-1 , 0
  4574.4     .16       0  4713.2     .12       0  4859.6     .16       0
  4992.2     .07       0  4998.2     .16       0  5254.3     .12       0
Bank Sta=4970.4,5049.4
XS Rating Curve= 0 ,0
Exp/Cntr=0.3,0.1

Type RM Length L Ch R = 1 ,31124   ,892,892,892
BEGIN DESCRIPTION:
Mapping XS b78533c7
END DESCRIPTION:
XS GIS Cut Line= 2
      3652973.89     10614635.15      3653765.09     10614510.22
#Sta/Elev= 30
  4458.6  345.68  4494.8  340.63  4565.6  333.49  4606.1  330.14  4636.5  329.58
  4656.7   327.8  4768.1  328.44  4776.1  324.99  4781.1  326.47  4798.5  327.75
  4945.4  329.51  4973.5  329.75  4980.7  328.03  4990.8  327.56    4998  324.62
  5000.7  324.12    5004  324.62  5021.2  330.06  5030.8  332.33  5035.9  331.36
  5081.9  337.36  5098.3   340.7  5103.4  340.62  5112.3   344.4  5158.2  354.07
  5165.8  354.27  5173.1   357.4  5223.2  362.05  5233.8  366.24  5259.6  371.04
#Mann= 5 ,-1 , 0
  4458.6     .12       0  4945.4     .16       0    4998     .07       0
    5004     .16       0  5158.2     .12       0
Bank Sta=4973.5,5021.2
XS Rating Curve= 0 ,0
Exp/Cntr=0.3,0.1

Type RM Length L Ch R = 1 ,30232   ,632,632,632
BEGIN DESCRIPTION:
INDIAN CREEK 2 53.0
END DESCRIPTION:
XS GIS Cut Line= 3
      3653206.58     10615322.65       3653675.3     10615284.45
      3654744.67     10615249.73
#Sta/Elev= 30
  4630.3  365.54  4753.7  346.57  4803.9  345.13  4839.4   341.6  4842.1  340.81
  4847.2  344.44  4864.1   336.2  4884.2  330.27  4934.3  325.18  4944.4  323.81
  4974.5  324.76  5006.6  322.53  5024.6  324.67    5145  322.84  5151.9   322.2
  5154.7   321.7  5157.9   322.2    5315   322.5  5445.1  324.78  5472.8  326.62
  5525.1  330.53  5625.2  340.97  5645.2  344.51  5685.2  347.07  5815.3  343.64
  5855.3  345.59  5965.3  347.02  6006.4  344.76  6162.7  346.19  6170.5  346.85
#Mann= 8 ,-1 , 0
  4630.3     .12       0  4839.4     .05       0  5006.6     .12       0
    5145     .16       0  5151.9     .03       0  5157.9     .16       0
  5472.8     .05       0  6162.7     .12       0
Bank Sta=4934.3,5445.1
XS Rating Curve= 0 ,0
Exp/Cntr=0.3,0.1

Type RM Length L Ch R = 1 ,29600   ,483,483,483
BEGIN DESCRIPTION:
INDIAN CREEK 2 52.0
END DESCRIPTION:
XS GIS Cut Line= 2
      3652971.66     10615880.18      3654494.82     10615606.79
#Sta/Elev= 30
  4228.7  354.27  4307.9  347.09  4313.3  345.66  4328.2  345.39  4490.8  328.23
    4580  321.74  4643.2  319.35  4805.7  320.23  4875.7  321.86    4948  321.46
  4988.2  319.24  5019.1  320.77  5081.6  320.64  5110.8  320.23    5138  317.74
  5140.7  317.24    5144  317.74  5191.8  321.74  5204.1  322.62  5266.7  326.73
  5330.7  330.37  5335.8   329.5  5389.5  331.85    5456  337.13    5502  342.73
  5516.9  342.95    5588  349.93  5619.5  351.64  5659.1   356.2  5776.2  362.67
#Mann= 7 ,-1 , 0
  4228.7     .05       0    4580     .12       0  5081.6     .16       0
    5138     .07       0    5144     .16       0  5204.1     .12       0
  5266.7     .05       0
Bank Sta=4580,5191.8
XS Rating Curve= 0 ,0
Exp/Cntr=0.3,0.1

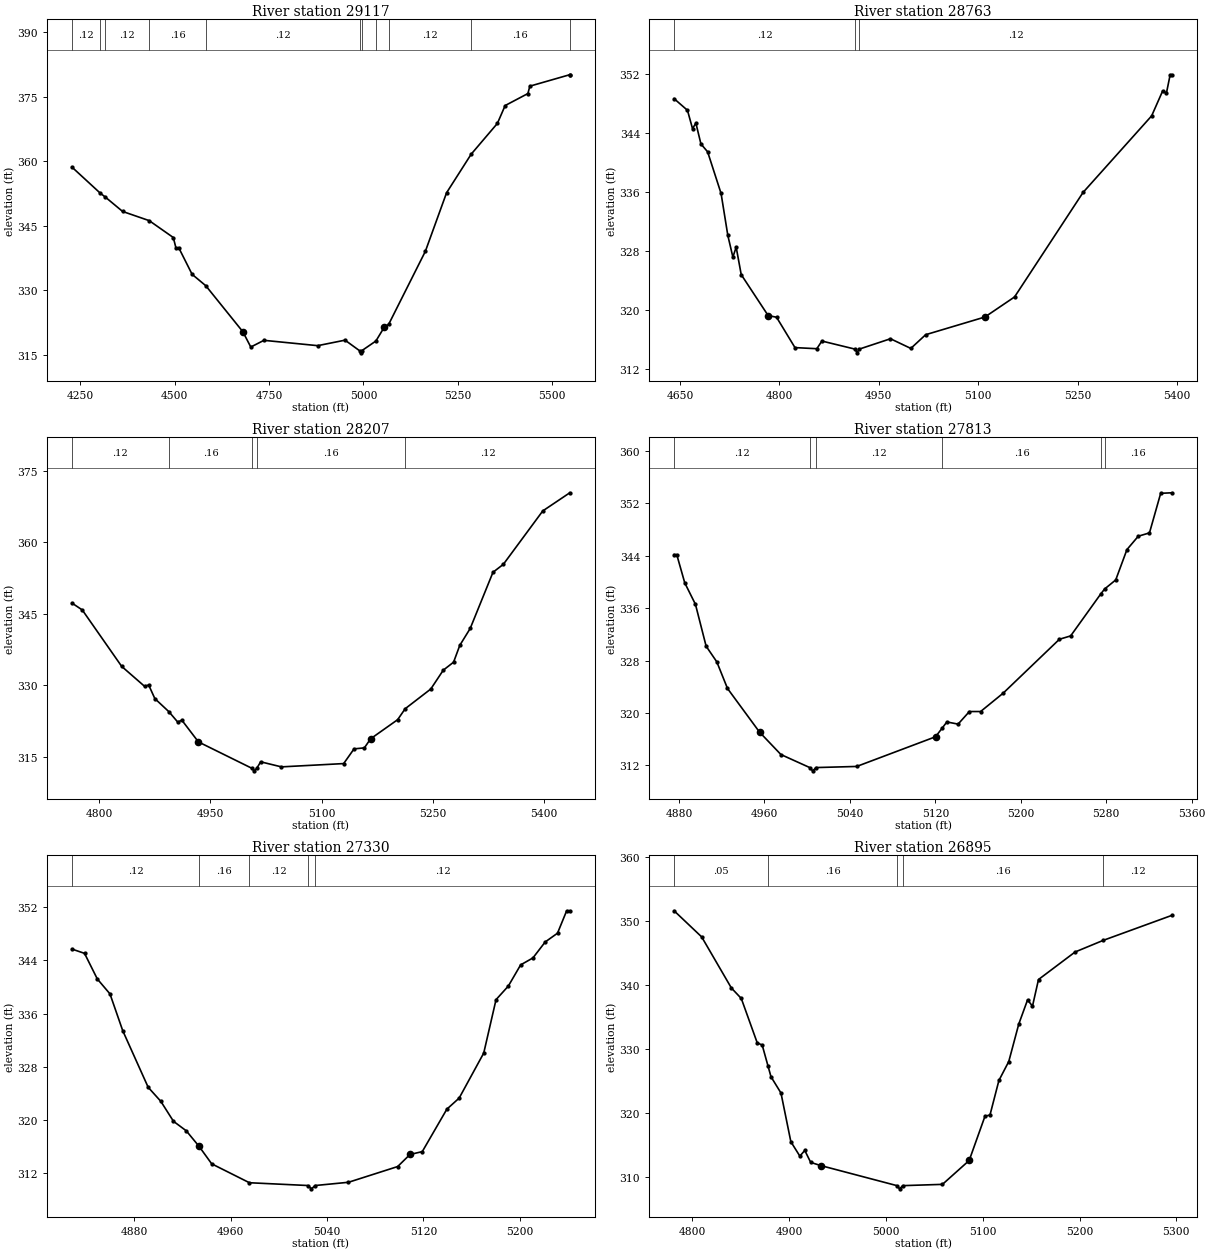
Type RM Length L Ch R = 1 ,29117   ,354,354,354
BEGIN DESCRIPTION:
INDIAN CREEK 2 51.0
END DESCRIPTION:
XS GIS Cut Line= 3
      3653312.76     10616453.12      3653656.53     10616085.91
       3654445.1     10615877.71
#Sta/Elev= 30
  4227.9  358.62  4303.1  352.54  4315.8  351.68  4362.2  348.29  4432.7  346.15
  4496.5  342.22  4503.8   339.7  4510.7  339.88  4546.3  333.66  4582.6     331
  4680.6  320.31  4701.7  316.74  4736.5   318.3  4878.9  317.06  4951.3  318.34
  4989.7  315.89  4992.4  315.39  4995.7  315.89    5033  318.14  5054.7  321.29
    5067  322.05    5164  339.01  5220.2  352.64  5285.3  361.61  5354.7  368.77
  5375.3  372.93  5435.5  375.72  5440.7  377.44  5545.8  380.09  5546.5  380.09
#Mann= 11 ,-1 , 0
  4227.9     .12       0  4303.1     .16       0  4315.8     .12       0
  4432.7     .16       0  4582.6     .12       0  4989.7     .07       0
  4995.7     .12       0    5033     .16       0    5067     .12       0
  5285.3     .16       0  5545.8     .05       0
Bank Sta=4680.6,5054.7
XS Rating Curve= 0 ,0
Exp/Cntr=0.3,0.1

Type RM Length L Ch R = 1 ,28763   ,556,556,556
BEGIN DESCRIPTION:
INDIAN CREEK 2 50.0
END DESCRIPTION:
XS GIS Cut Line= 3
      3653649.65      10616310.2      3653949.61     10616360.19
       3654349.6     10616160.19
#Sta/Elev= 30
  4641.1   348.7  4661.3  347.12  4668.9  344.64    4674  345.38  4681.6  342.56
  4691.7  341.49    4712  335.84  4722.2  330.14  4729.8  327.21  4734.8  328.55
  4742.4  324.83    4783  319.28  4795.7  319.05  4823.5  314.93  4856.5  314.78
  4864.1  315.82  4914.3  314.72  4917.1  314.22  4920.3  314.72  4967.6  316.13
  4998.3  314.82  5020.7  316.68  5110.1  319.08  5154.8   321.8  5258.2  335.98
  5361.7  346.37  5378.4  349.77    5384  349.46  5389.6  351.94  5392.4  351.94
#Mann= 3 ,-1 , 0
  4641.1     .12       0  4914.3     .07       0  4920.3     .12       0
Bank Sta=4783,5110.1
XS Rating Curve= 0 ,0
Exp/Cntr=0.3,0.1

Type RM Length L Ch R = 1 ,28207   ,394,394,394
BEGIN DESCRIPTION:
INDIAN CREEK 2 49.0
END DESCRIPTION:
XS GIS Cut Line= 3
      3653699.58     10616610.17      3653899.61     10616710.19
      3654299.65     10616910.21
#Sta/Elev= 30
  4763.6  347.27  4777.6  345.82  4830.7     334  4861.5  329.83  4867.1  330.09
  4875.4  327.25  4894.3  324.51  4906.2  322.34  4911.8  322.73  4934.1  318.18
  5006.6  312.62  5009.3  312.12  5012.6  312.62    5018  314.01  5045.9  312.95
  5129.8  313.64  5143.8  316.72  5157.7  316.93  5166.1  318.83  5202.5  322.83
  5212.7  325.13  5247.2  329.26    5264   333.2  5277.9  334.88  5286.3  338.41
  5300.3  341.94    5331  353.71    5345  355.38  5398.1  366.56  5434.5  370.36
#Mann= 5 ,-1 , 0
  4763.6     .12       0  4894.3     .16       0  5006.6     .07       0
  5012.6     .16       0  5212.7     .12       0
Bank Sta=4934.1,5166.1
XS Rating Curve= 0 ,0
Exp/Cntr=0.3,0.1

Type RM Length L Ch R = 1 ,27813   ,483,483,483
BEGIN DESCRIPTION:
INDIAN CREEK 2 48.0
END DESCRIPTION:
XS GIS Cut Line= 3
      3653699.65     10617060.19      3653849.61     10617060.19
      3654149.62     10617160.19
#Sta/Elev= 30
  4875.4  344.16  4877.9  344.16  4885.4  339.85  4895.4  336.58  4905.4  330.19
  4915.4   327.8  4925.4  323.74  4955.4  317.08  4975.4  313.66  5002.4  311.67
  5005.1  311.17  5008.4  311.67  5046.4  311.84  5120.2  316.37  5126.6  317.73
  5130.8  318.63  5141.3   318.3  5151.9  320.22  5162.4  320.22  5183.5  323.02
  5236.2  331.25  5246.7  331.76  5274.7  338.12  5278.5  338.92  5288.9   340.3
  5299.4  344.93    5310  346.97  5320.5  347.48    5331  353.52  5341.6   353.6
#Mann= 6 ,-1 , 0
  4875.4     .12       0  5002.4     .07       0  5008.4     .12       0
  5126.6     .16       0  5274.7     .12       0  5278.5     .16       0
Bank Sta=4955.4,5120.2
XS Rating Curve= 0 ,0
Exp/Cntr=0.3,0.1

Type RM Length L Ch R = 1 ,27330   ,435,435,435
BEGIN DESCRIPTION:
INDIAN CREEK 2 47.0
END DESCRIPTION:
XS GIS Cut Line= 3
       3653749.6     10617560.19      3653899.61     10617510.19
      3654149.64     10617560.19
#Sta/Elev= 30
  4828.3  345.72  4838.8  345.07  4849.4  341.21  4859.9  338.96  4870.5  333.41
  4891.6  324.88  4902.1  322.76  4912.6  319.75  4923.2  318.32  4933.8  315.98
  4944.3  313.34  4975.6  310.49  5024.2  310.07    5027  309.57  5030.2  310.07
  5057.8  310.56  5098.6  312.93  5108.8  314.75    5119  315.18  5139.4  321.58
  5149.6  323.25    5170  330.04  5180.2  338.09  5190.4  340.14  5200.6  343.33
  5210.8  344.38    5221  346.79  5231.2  348.11  5238.8  351.49  5241.4  351.49
#Mann= 5 ,-1 , 0
  4828.3     .12       0  4933.8     .16       0  4975.6     .12       0
  5024.2     .07       0  5030.2     .12       0
Bank Sta=4933.8,5108.8
XS Rating Curve= 0 ,0
Exp/Cntr=0.3,0.1

Type RM Length L Ch R = 1 ,26895   ,446,446,446
BEGIN DESCRIPTION:
Mapping XS 080c65cc
END DESCRIPTION:
XS GIS Cut Line= 2
      3653711.78     10617973.68      3654214.32     10617864.32
#Sta/Elev= 30
  4781.2  351.61  4809.7  347.52  4840.4  339.52  4850.6  337.89  4867.1  330.93
  4872.2   330.6  4878.2  327.32  4881.3  325.63  4891.6  323.09  4901.8  315.47
  4911.1  313.21  4916.2   314.1  4922.3  312.23  4932.5  311.74  5011.4  308.59
  5014.1  308.09  5017.4  308.59  5058.4  308.79    5086  312.53  5102.3  319.45
  5107.5  319.65  5116.7  325.05  5126.9  328.02  5137.2  333.87  5146.3  337.66
  5151.4  336.69  5157.6  340.85  5195.4  345.16  5224.3  346.97  5295.5   350.9
#Mann= 5 ,-1 , 0
  4781.2     .05       0  4878.2     .16       0  5011.4     .07       0
  5017.4     .16       0  5224.3     .12       0
Bank Sta=4932.5,5086
XS Rating Curve= 0 ,0
Exp/Cntr=0.3,0.1

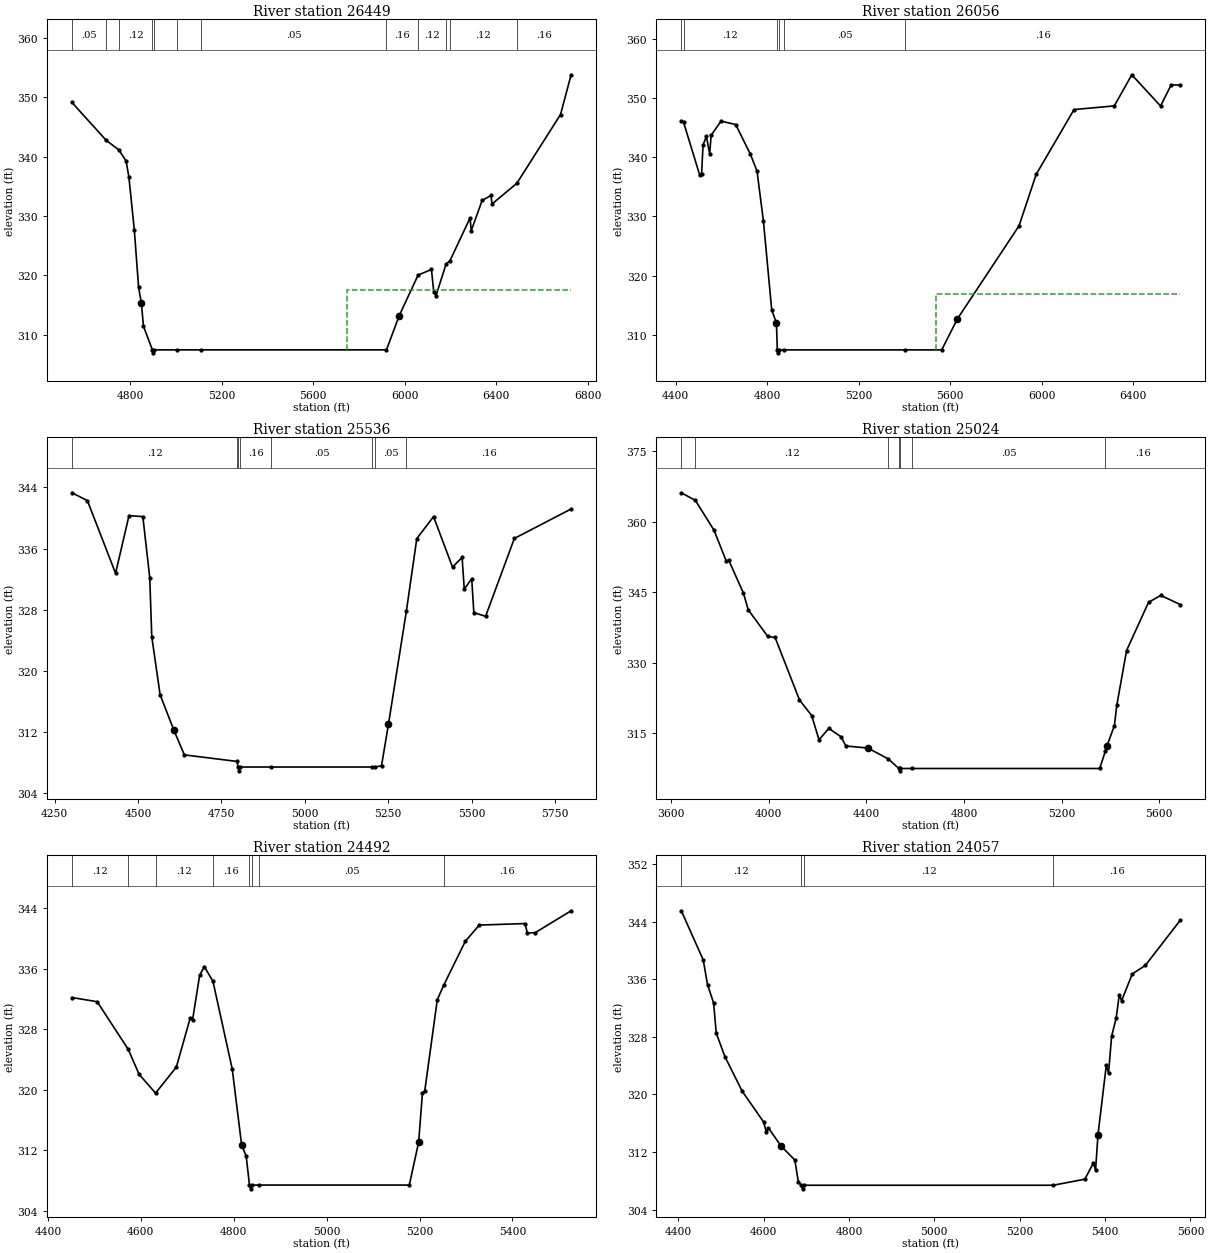
Type RM Length L Ch R = 1 ,26449   ,393,393,393
BEGIN DESCRIPTION:
INDIAN CREEK 2 45.0
END DESCRIPTION:
XS GIS Cut Line= 3
      3653655.65      10618174.3      3654839.72     10618597.93
      3655755.55     10618497.33
#Sta/Elev= 30
  4547.1  349.16  4696.2  342.79  4752.6  341.12  4783.4  339.28  4795.6  336.61
  4819.5  327.62  4838.1  317.96  4850.3  315.28  4859.3  311.41  4898.2  307.41
    4901  306.91  4904.2  307.41    5007  307.41  5110.6  307.41    5920  307.41
  5975.6  313.17  6058.1  320.03  6116.4  320.98  6126.5  317.17  6136.5  316.58
  6180.2   321.9  6196.9  322.43    6285  329.67  6290.1  327.53  6337.7  332.63
  6376.1  333.46  6381.1  332.03  6489.2  335.52  6679.8  347.12    6726  353.83
#Mann= 12 ,-1 , 0
  4547.1     .05       0  4696.2     .16       0  4752.6     .12       0
  4898.2     .07       0  4904.2     .12       0    5007     .07       0
  5110.6     .05       0    5920     .16       0  6058.1     .12       0
  6180.2     .16       0  6196.9     .12       0  6489.2     .16       0
#XS Ineff= 2 , 0
                         5748.94           317.5
Permanent Ineff=
       F       F
Bank Sta=4850.3,5975.6
XS Rating Curve= 0 ,0
Exp/Cntr=0.3,0.1

Type RM Length L Ch R = 1 ,26056   ,520,520,520
BEGIN DESCRIPTION:
INDIAN CREEK 2 44.0
END DESCRIPTION:
XS GIS Cut Line= 3
      3653507.38     10618168.23      3654096.42     10618915.36
      3654611.56     10620032.84
#Sta/Elev= 30
  4424.9  346.11  4434.8  345.95  4505.7  336.97  4513.7  337.27  4520.1  342.14
  4534.6  343.54    4549  340.62  4555.4  343.75  4598.7  346.15  4662.8  345.56
    4727  340.53  4755.9  337.68  4783.9  329.22    4820  314.23  4840.8  311.94
  4844.6  307.41  4847.4  306.91  4850.6  307.41  4875.1  307.41    5401  307.41
  5563.2  307.41  5632.1  312.68  5901.1  328.41  5976.2  337.13  6141.6   348.1
  6317.6  348.72  6394.1  353.99  6519.9   348.7  6565.8  352.25  6606.8  352.27
#Mann= 6 ,-1 , 0
  4424.9     .05       0  4434.8     .12       0  4844.6    .033       0
  4850.6     .12       0  4875.1     .05       0    5401     .16       0
#XS Ineff= 2 , 0
                         5539.37          316.85
Permanent Ineff=
       F       F
Bank Sta=4840.8,5632.1
XS Rating Curve= 0 ,0
Exp/Cntr=0.3,0.1

Type RM Length L Ch R = 1 ,25536   ,512,512,512
BEGIN DESCRIPTION:
INDIAN CREEK 2 43.0
END DESCRIPTION:
XS GIS Cut Line= 3
      3652894.61     10618821.62      3653880.68     10619092.44
      3654179.27     10619460.46
#Sta/Elev= 30
    4302   343.3  4348.4  342.27  4432.8  332.76  4473.1  340.31  4514.6  340.18
  4535.3  332.19  4541.3  324.48  4566.4  316.85  4607.9   312.2    4639     309
    4797  308.14  4800.1  307.41  4802.8  306.91  4806.1  307.41  4898.5  307.41
    5203  307.41  5209.3  307.41  5230.1  307.57  5250.9     313  5304.5  327.77
  5335.9   337.3  5386.1  340.18    5443  333.57  5471.7  334.84  5478.2  330.69
  5500.5  332.05  5506.9  327.62  5542.1  327.13  5628.3  337.32  5798.5  341.18
#Mann= 8 ,-1 , 0
    4302     .12       0    4797     .16       0  4800.1    .033       0
  4806.1     .16       0  4898.5     .05       0    5203     .16       0
  5209.3     .05       0  5304.5     .16       0
Bank Sta=4607.9,5250.9
XS Rating Curve= 0 ,0
Exp/Cntr=0.3,0.1

Type RM Length L Ch R = 1 ,25024   ,532,532,532
BEGIN DESCRIPTION:
Mapping XS 6b0cf57c
END DESCRIPTION:
XS GIS Cut Line= 2
       3652205.3     10619487.67       3654250.4     10619532.81
#Sta/Elev= 30
  3641.6  366.18  3699.3  364.56  3775.9  358.18    3826  351.59    3836   351.8
    3896  344.82    3916  341.24    3996  335.55    4026  335.34    4126  322.02
    4176  318.69    4206  313.53  4246.1  315.94  4296.1  314.18  4316.1  312.21
  4406.1  311.77  4490.2  309.44  4533.1  307.41  4535.9  306.91  4539.1  307.41
    4589  307.41  5356.3  307.41  5379.9   311.2  5386.3  312.28  5416.3  316.51
  5426.3  320.88  5466.4  332.56  5556.4  342.83  5606.4   344.3  5687.2  342.34
#Mann= 7 ,-1 , 0
  3641.6     .16       0  3699.3     .12       0  4490.2     .16       0
  4533.1    .033       0  4539.1     .16       0    4589     .05       0
  5379.9     .16       0
Bank Sta=4406.1,5386.3
XS Rating Curve= 0 ,0
Exp/Cntr=0.3,0.1

Type RM Length L Ch R = 1 ,24492   ,435,435,435
BEGIN DESCRIPTION:
INDIAN CREEK 2 41.0
END DESCRIPTION:
XS GIS Cut Line= 3
      3653125.43     10620074.48      3653778.21     10620025.87
       3654196.5     10620063.89
#Sta/Elev= 30
  4451.6   332.2  4505.9  331.65  4572.5  325.38  4596.2  322.05  4631.6  319.56
  4676.4  323.01  4706.4  329.53  4711.4  329.29  4726.5  335.13  4736.6  336.29
  4755.1  334.36  4796.7  322.75  4816.8  312.75  4826.8  311.19  4833.8  307.41
  4836.6  306.91  4839.8  307.41  4854.6  307.41  5177.9  307.41    5198  313.09
  5206.1  319.56  5211.1  319.83  5238.1   331.9  5251.8  333.81  5298.4  339.63
  5328.5  341.78    5427  341.98    5432  340.73    5449  340.78  5526.2  343.67
#Mann= 8 ,-1 , 0
  4451.6     .12       0  4572.5     .16       0  4631.6     .12       0
  4755.1     .16       0  4833.8    .033       0  4839.8     .16       0
  4854.6     .05       0  5251.8     .16       0
Bank Sta=4816.8,5198
XS Rating Curve= 0 ,0
Exp/Cntr=0.3,0.1

Type RM Length L Ch R = 1 ,24057   ,409,409,409
BEGIN DESCRIPTION:
INDIAN CREEK 2 40.0
END DESCRIPTION:
XS GIS Cut Line= 3
      3653128.87     10620557.12      3653837.24     10620442.53
      3654260.86     10620286.28
#Sta/Elev= 30
  4407.4  345.49  4458.8  338.67  4468.9  335.23  4483.1   332.7  4489.2  328.53
  4509.5  325.26    4550  320.46  4600.6  316.15  4606.5  314.76  4611.6  315.35
  4641.1  312.84  4673.3  310.91  4681.7  307.82  4688.8  307.41  4691.5  306.91
  4694.8  307.41  5278.6  307.41  5352.6  308.25  5372.4  310.47  5377.7  309.52
  5383.3  314.39  5402.8  324.04  5408.1  322.97  5415.3  328.08  5425.9  330.59
  5433.2  333.84  5438.6  333.01  5463.7  336.73  5494.1   337.9  5576.5  344.21
#Mann= 4 ,-1 , 0
  4407.4     .12       0  4688.8    .033       0  4694.8     .12       0
  5278.6     .16       0
Bank Sta=4641.1,5383.3
XS Rating Curve= 0 ,0
Exp/Cntr=0.3,0.1

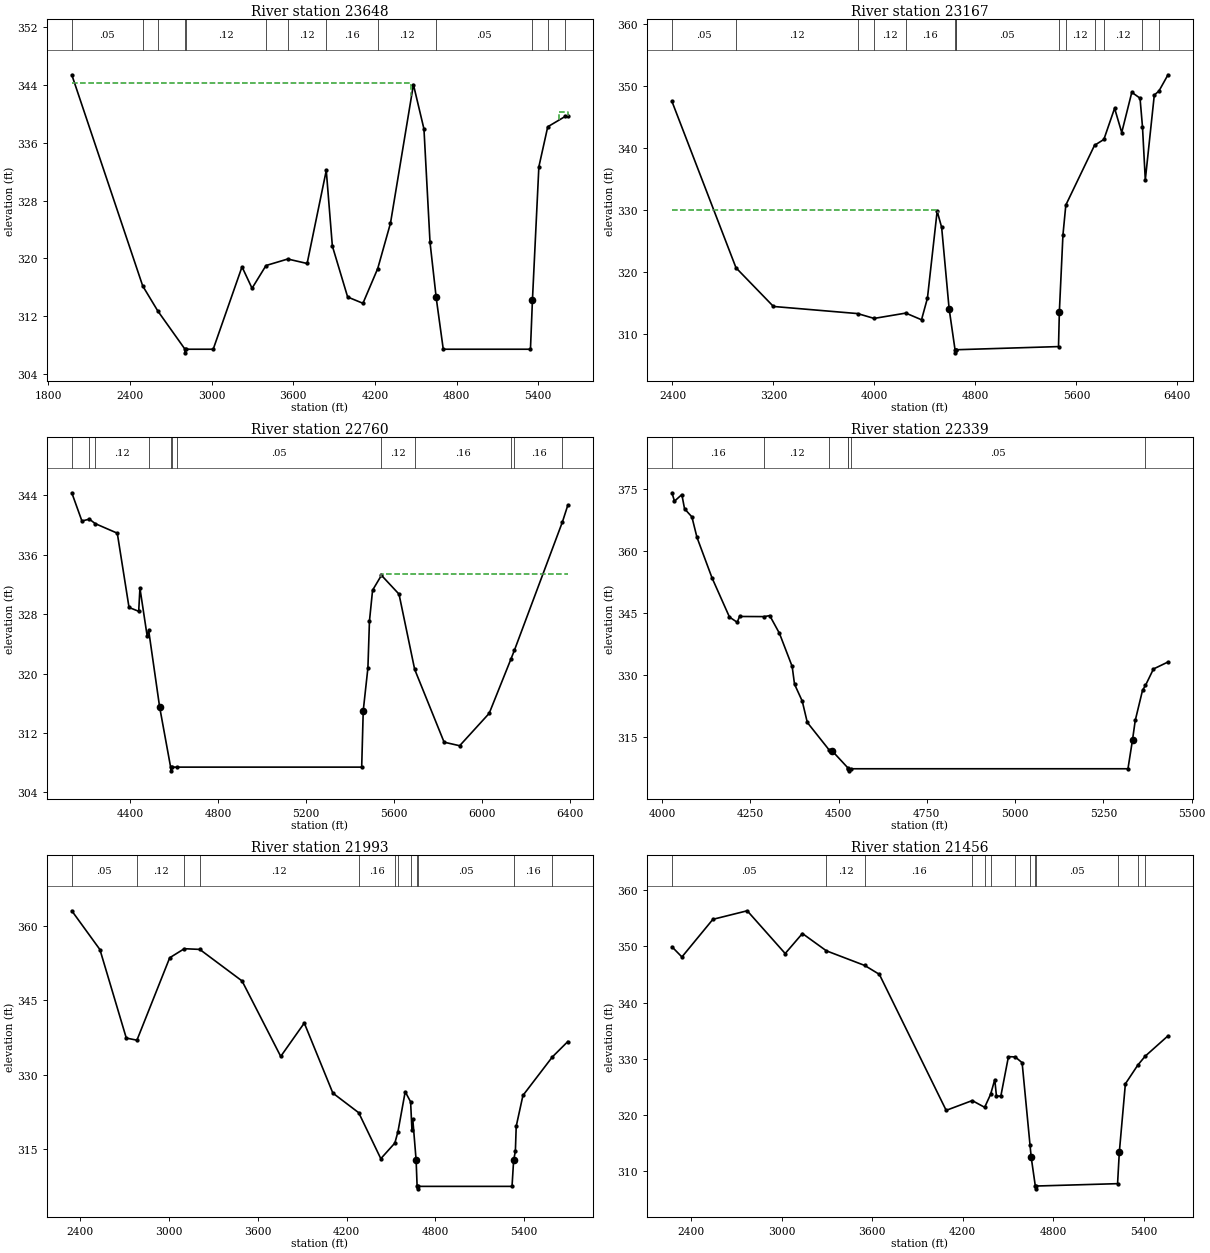
Type RM Length L Ch R = 1 ,23648   ,481,481,481
BEGIN DESCRIPTION:
INDIAN CREEK 2 39.0
END DESCRIPTION:
XS GIS Cut Line= 3
      3650955.22     10621725.53      3651953.44     10621759.39
      3654328.47      10620592.7
#Sta/Elev= 30
  1972.2  345.41  2493.4  316.17  2604.8  312.69  2804.1  307.41  2806.8  306.91
  2810.1  307.41  3011.3  307.41    3223  318.82  3296.7  315.85  3399.3     319
  3559.2   319.9  3701.4  319.28  3842.1  332.16  3886.8   321.7  3999.2  314.64
  4111.6  313.77  4220.2  318.58    4314  324.87  4482.5  344.05  4559.9   337.9
  4604.5  322.19  4649.1  314.68  4649.4  314.59  4701.7  307.41  5342.4  307.41
  5357.1  314.28  5404.2  332.67  5469.4  338.21  5599.2  339.66  5617.1  339.67
#Mann= 13 ,-1 , 0
  1972.2     .05       0  2493.4     .16       0  2604.8     .12       0
  2804.1    .033       0  2810.1     .12       0  3399.3     .16       0
  3559.2     .12       0  3842.1     .16       0  4220.2     .12       0
  4649.4     .05       0  5357.1     .16       0  5469.4     .12       0
  5599.2     .16       0
#XS Ineff= 2 , 0
         4468.25   344.3 5550.38           340.3
Permanent Ineff=
       F       F
Bank Sta=4649.1,5357.1
XS Rating Curve= 0 ,0
Exp/Cntr=0.3,0.1

Type RM Length L Ch R = 1 ,23167   ,407,407,407
BEGIN DESCRIPTION:
INDIAN CREEK 2 38.0
END DESCRIPTION:
XS GIS Cut Line= 3
      3652961.25     10623631.79      3653678.99     10621744.33
      3654790.01       10620190.
#Sta/Elev= 30
    2396  347.52  2903.6  320.64  3200.1   314.4  3867.1  313.25  3997.7  312.47
  4248.7  313.33  4373.2  312.25  4420.1  315.75    4497   329.8  4532.7  327.17
  4591.6  314.07  4638.7  307.41  4641.4  306.91  4644.7  307.41  4647.3  307.41
  5458.5  307.92  5465.2  313.56  5493.6  325.95  5516.4  330.78  5743.6  340.42
  5817.9  341.38  5902.7  346.41  5959.3  342.49  6039.1  348.99  6104.3  348.04
  6123.8  343.39    6146  334.84  6217.3  348.55  6253.8  349.19  6325.9  351.82
#Mann= 14 ,-1 , 0
    2396     .05       0  2903.6     .12       0  3867.1     .16       0
  3997.7     .12       0  4248.7     .16       0  4638.7    .033       0
  4644.7     .16       0  4647.3     .05       0  5458.5     .16       0
  5516.4     .12       0  5743.6     .16       0  5817.9     .12       0
  6123.8     .16       0  6253.8     .12       0
#XS Ineff= 2 , 0
         4502.12  330.04
Permanent Ineff=
       F       F
Bank Sta=4591.6,5465.2
XS Rating Curve= 0 ,0
Exp/Cntr=0.3,0.1

Type RM Length L Ch R = 1 ,22760   ,421,421,421
BEGIN DESCRIPTION:
INDIAN CREEK 2 37.0
END DESCRIPTION:
XS GIS Cut Line= 3
      3653991.42     10622183.01      3654397.09     10621418.24
      3655365.48     10620420.11
#Sta/Elev= 30
  4134.3  344.35  4180.4  340.55  4214.5   340.8  4240.7   340.2  4341.3  338.91
  4394.7  328.91  4438.7  328.39  4444.3  331.51    4477   325.1  4484.1  325.81
  4533.7  315.54  4583.9  307.41  4586.7  306.91  4589.9  307.41  4614.3  307.41
    5453  307.41    5460     315  5481.3  320.78  5488.3  327.08  5502.5  331.23
  5542.8  333.24  5622.8   330.7  5693.9  320.58  5827.8  310.77  5898.6  310.29
  6032.9  314.65  6131.3  321.92    6148  323.17    6366  340.42  6390.7  342.69
#Mann= 12 ,-1 , 0
  4134.3     .12       0  4214.5     .16       0  4240.7     .12       0
  4484.1     .16       0  4583.9    .033       0  4589.9     .16       0
  4614.3     .05       0  5542.8     .12       0  5693.9     .16       0
  6131.3     .12       0    6148     .16       0    6366     .12       0
#XS Ineff= 2 , 0
                         5538.95          333.38
Permanent Ineff=
       F       F
Bank Sta=4533.7,5460
XS Rating Curve= 0 ,0
Exp/Cntr=0.3,0.1

Type RM Length L Ch R = 1 ,22339   ,346,346,346
BEGIN DESCRIPTION:
INDIAN CREEK 2 36.0
END DESCRIPTION:
XS GIS Cut Line= 3
      3654149.59     10622310.21      3654799.61     10621560.19
      3654899.61      10621160.2
#Sta/Elev= 30
  4028.2  374.12  4035.4  372.09  4056.2  373.69  4063.9  370.25  4084.7  368.29
    4099  363.36  4141.7  353.55  4191.1  344.08    4213  342.82  4219.6  344.22
  4289.7  344.19  4305.1  344.44  4332.6  340.15  4368.7  332.13  4375.3  327.86
  4397.2  323.76  4411.5  318.61  4473.9   311.9  4481.7  311.75  4526.8  307.59
  4528.1  307.41  4530.8  306.91  4534.1  307.41  5319.6  307.41  5332.5   314.4
  5340.2  319.08  5360.9  326.39  5369.2  327.56  5391.8  331.53    5433  333.22
#Mann= 7 ,-1 , 0
  4028.2     .16       0  4289.7     .12       0  4473.9     .16       0
  4526.8     .05       0  4528.1    .033       0  4534.1     .05       0
  5369.2     .12       0
Bank Sta=4481.7,5332.5
XS Rating Curve= 0 ,0
Exp/Cntr=0.3,0.1

Type RM Length L Ch R = 1 ,21993   ,537,537,537
BEGIN DESCRIPTION:
INDIAN CREEK 2 35.0
END DESCRIPTION:
XS GIS Cut Line= 2
      3653991.42     10624023.29      3655424.81     10620991.79
#Sta/Elev= 30
  2341.6  363.14  2531.9  355.29  2710.1   337.4    2782  336.97  3003.6  353.64
  3102.3  355.47  3206.7  355.33  3492.6  348.95    3754  333.69  3913.3  340.44
  4106.5  326.27  4281.3   322.3  4430.6  313.01  4525.5  316.17  4546.5  318.47
  4595.5  326.56    4632   324.5    4641  318.86  4646.5  321.07  4669.3   312.7
    4676  307.41  4678.8  306.91    4682  307.41  5317.6  307.41  5328.4  312.67
  5340.3  314.54  5345.9  319.56  5391.4   325.8  5590.7   333.6  5694.9   336.7
#Mann= 12 ,-1 , 0
  2341.6     .05       0    2782     .12       0  3102.3     .16       0
  3206.7     .12       0  4281.3     .16       0  4525.5     .05       0
  4546.5     .16       0    4632     .05       0    4676    .033       0
    4682     .05       0  5328.4     .16       0  5590.7     .12       0
Bank Sta=4669.3,5328.4
XS Rating Curve= 0 ,0
Exp/Cntr=0.3,0.1

Type RM Length L Ch R = 1 ,21456   ,452,452,452
BEGIN DESCRIPTION:
INDIAN CREEK 2 34.0
END DESCRIPTION:
XS GIS Cut Line= 2
      3655387.24     10624335.81      3655720.14     10621069.53
#Sta/Elev= 30
  2274.9  349.94  2340.9  348.13  2545.9  354.82  2773.1  356.34  3024.4  348.74
  3138.3   352.3  3297.2  349.22  3550.7  346.62  3647.6  345.04  4089.9  320.86
  4262.3   322.6  4344.6   321.4  4384.3  323.74  4411.5  326.33  4422.6   323.4
  4451.7   323.4    4502  330.41  4546.5  330.36  4592.5  329.34  4644.7  314.74
  4652.8  312.49  4679.9  307.41  4682.7  306.91  4685.9  307.41  5224.3  307.83
  5235.8   313.4    5276  325.58  5358.3  328.91  5406.6  330.48  5558.1  334.11
#Mann= 13 ,-1 , 0
  2274.9     .05       0  3297.2     .12       0  3550.7     .16       0
  4262.3     .12       0  4344.6     .16       0  4384.3     .12       0
  4546.5     .16       0  4644.7     .05       0  4679.9    .033       0
  4685.9     .05       0  5224.3     .16       0  5358.3     .12       0
  5406.6     .16       0
Bank Sta=4652.8,5235.8
XS Rating Curve= 0 ,0
Exp/Cntr=0.3,0.1

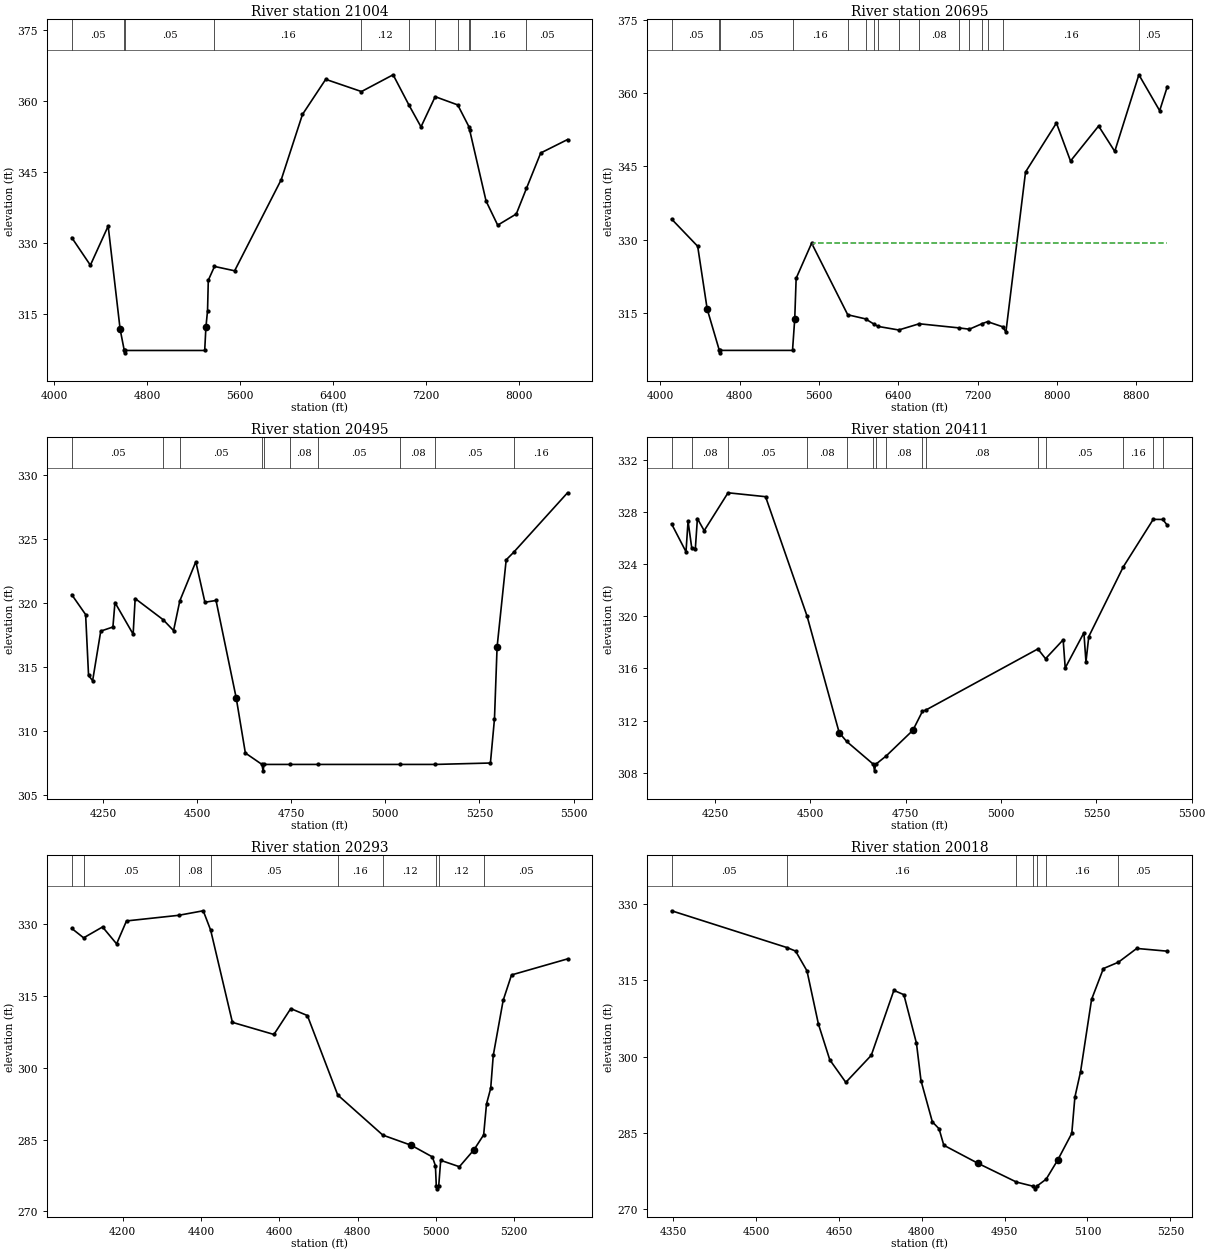
Type RM Length L Ch R = 1 ,21004   ,309,309,309
BEGIN DESCRIPTION:
INDIAN CREEK 2 33.0
END DESCRIPTION:
XS GIS Cut Line= 4
      3655926.36     10622516.63      3656119.06     10621639.05
      3655883.16     10620682.26      3655961.29     10618299.47
#Sta/Elev= 30
  4149.4  331.22  4309.6   325.4  4462.8  333.66  4565.8  311.87  4601.4  307.41
  4604.2  306.91  4607.4  307.41  5293.9  307.41  5304.2  312.31  5318.4  315.83
  5324.8  322.23  5378.2  325.14  5551.4  324.22  5953.1  343.47  6135.5  357.21
  6335.6  364.62  6643.5  362.04  6915.9  365.58  7053.3  359.14    7156  354.59
  7278.1  360.96  7472.3  359.22  7570.3  354.54  7574.5  353.96  7716.3  338.93
  7816.4  333.85  7976.4  336.21  8063.5  341.59  8186.6  349.08  8417.4  351.91
#Mann= 11 ,-1 , 0
  4149.4     .05       0  4601.4    .033       0  4607.4     .05       0
  5378.2     .16       0  6643.5     .12       0  7053.3     .16       0
  7278.1     .05       0  7472.3     .16       0  7570.3     .12       0
  7574.5     .16       0  8063.5     .05       0
Bank Sta=4565.8,5304.2
XS Rating Curve= 0 ,0
Exp/Cntr=0.3,0.1

Type RM Length L Ch R = 1 ,20695   ,200,200,200
BEGIN DESCRIPTION:
Mapping XS c03a2302
END DESCRIPTION:
XS GIS Cut Line= 6
      3656157.01     10622563.66      3656472.97     10621525.49
      3656691.72     10621285.91      3657284.16     10621144.24
      3657447.35     10620290.07       3658795.8     10618806.86
#Sta/Elev= 30
  4114.6  334.25  4377.7  328.69  4473.6  315.85  4596.1  307.41  4598.8  306.91
  4602.1  307.41  5334.2  307.41  5356.6  313.87  5370.8  322.15  5526.8  329.32
  5891.1  314.69  6070.5  313.85  6153.7   312.8    6197  312.31  6405.2  311.58
  6611.7  312.85  7011.9  312.01  7117.3  311.74  7248.2  312.89  7301.1  313.28
  7452.7  312.24  7486.2  311.16  7684.2  343.87  7995.8  353.88  8137.8  346.11
    8421  353.27  8583.9  348.08  8827.3  363.74  9036.8   356.4  9114.3  361.34
#Mann= 16 ,-1 , 0
  4114.6     .05       0  4596.1    .033       0  4602.1     .05       0
  5334.2     .16       0  5891.1     .05       0  6070.5     .08       0
  6153.7     .05       0    6197     .08       0  6405.2     .05       0
  6611.7     .08       0  7011.9     .05       0  7117.3     .08       0
  7248.2     .05       0  7301.1     .08       0  7452.7     .16       0
  8827.3     .05       0
#XS Ineff= 2 , 0
                         5539.37          329.44
Permanent Ineff=
       F       F
Bank Sta=4473.6,5356.6
XS Rating Curve= 0 ,0
Exp/Cntr=0.3,0.1

Type RM Length L Ch R = 1 ,20495   ,84,84,84
BEGIN DESCRIPTION:
Mapping XS 11a9c6bf
END DESCRIPTION:
XS GIS Cut Line= 2
      3656301.75     10622521.58      3656793.94     10621300.22
#Sta/Elev= 30
  4167.3  320.65  4204.1   319.1  4211.9  314.35  4222.7  313.94  4244.3  317.81
  4276.6  318.13    4282  320.04  4330.3  317.57  4335.7  320.35    4410   318.7
  4437.7  317.85  4454.3  320.17  4496.8  323.22    4521  320.06  4550.5   320.2
  4604.2  312.58  4628.4   308.3  4672.5  307.41  4675.3  306.91  4678.5  307.41
  4747.3  307.41  4820.3  307.41  5040.2  307.41  5132.6  307.41  5279.3  307.52
  5290.1  310.97    5297  316.56  5321.2  323.37  5340.8  323.95  5484.1   328.6
#Mann= 10 ,-1 , 0
  4167.3     .05       0    4410     .16       0  4454.3     .05       0
  4672.5    .033       0  4678.5     .05       0  4747.3     .08       0
  4820.3     .05       0  5040.2     .08       0  5132.6     .05       0
  5340.8     .16       0
Bank Sta=4604.2,5297
XS Rating Curve= 0 ,0
Exp/Cntr=0.3,0.1

Type RM Length L Ch R = 1 ,20411   ,118,118,118
BEGIN DESCRIPTION:
INDIAN CREEK 2 32.0
END DESCRIPTION:
XS GIS Cut Line= 2
      3656380.68     10622539.89      3656852.88     10621328.15
#Sta/Elev= 30
  4135.7   327.1  4173.5  324.96  4178.9  327.31  4188.6  325.25    4198   325.2
  4203.4  327.51  4221.2  326.58  4283.8  329.49  4382.2  329.19  4491.2  320.01
  4575.4  311.07  4594.8   310.4  4665.2  308.64    4668  308.14  4671.2  308.64
  4698.5  309.28  4768.6  311.25  4793.9  312.72  4802.2   312.8  5096.6   317.5
  5116.7  316.75  5162.9   318.2  5168.3  316.04  5217.3  318.74  5222.7   316.5
  5230.1  318.45  5320.6   323.8  5399.2  327.45  5424.3  327.44  5436.2  326.99
#Mann= 15 ,-1 , 0
  4135.7     .05       0  4188.6     .08       0  4283.8     .05       0
  4491.2     .08       0  4594.8      .1       0  4665.2     .07       0
  4671.2      .1       0  4698.5     .08       0  4793.9     .05       0
  4802.2     .08       0  5096.6     .12       0  5116.7     .05       0
  5320.6     .16       0  5399.2     .05       0  5424.3     .16       0
Bank Sta=4575.4,4768.6
XS Rating Curve= 0 ,0
Exp/Cntr=0.3,0.1

Type RM Length L Ch R = 1 ,20293   ,275,275,275
BEGIN DESCRIPTION:
Mapping XS 88e59a86
END DESCRIPTION:
XS GIS Cut Line= 2
      3656486.64     10622565.86      3656918.94     10621375.74
#Sta/Elev= 30
  4070.2  329.11  4100.5  327.15  4148.8  329.42  4184.7  325.89    4210  330.68
  4342.9  331.85    4406   332.8    4425  328.74  4480.5   309.5  4586.5  306.97
  4629.5  312.37    4672  310.92  4749.5  294.33  4864.7  285.95  4937.8  283.81
  4991.2   281.4    4999  279.55  5001.3  275.23  5004.1  274.73  5007.3  275.23
  5012.5  280.68  5060.2  279.35  5097.6   282.9  5122.2     286  5129.5  292.46
  5140.2  295.72  5146.7  302.58    5172  314.08  5193.4   319.4  5336.4  322.75
#Mann= 9 ,-1 , 0
  4070.2     .08       0  4100.5     .05       0  4342.9     .08       0
    4425     .05       0  4749.5     .16       0  4864.7     .12       0
  5001.3     .07       0  5007.3     .12       0  5122.2     .05       0
Bank Sta=4937.8,5097.6
XS Rating Curve= 0 ,0
Exp/Cntr=0.3,0.1

Type RM Length L Ch R = 1 ,20018   ,621,621,621
BEGIN DESCRIPTION:
INDIAN CREEK 2 31.0
END DESCRIPTION:
XS GIS Cut Line= 2
       3657213.2     10622237.73      3656991.85     10621367.96
#Sta/Elev= 30
  4347.1  328.71  4556.3  321.46  4571.6  320.78  4592.2  316.89  4612.9  306.42
  4633.5  299.38  4662.5  294.95  4708.6  300.27  4749.5  313.05  4767.6   312.2
  4790.4  302.65  4798.6   295.3  4819.2  287.17  4831.3  285.82  4839.9  282.58
  4901.8  279.02  4971.5  275.33    5002   274.5  5004.7     274    5008   274.5
  5025.2   275.9  5046.2  279.68  5071.6  284.91  5077.2  292.03  5087.5  297.05
  5107.4  311.26  5128.8  317.34    5156  318.59  5189.2   321.3  5244.6  320.76
#Mann= 7 ,-1 , 0
  4347.1     .05       0  4556.3     .16       0  4971.5     .12       0
    5002     .07       0    5008     .12       0  5025.2     .16       0
    5156     .05       0
Bank Sta=4901.8,5046.2
XS Rating Curve= 0 ,0
Exp/Cntr=0.3,0.1