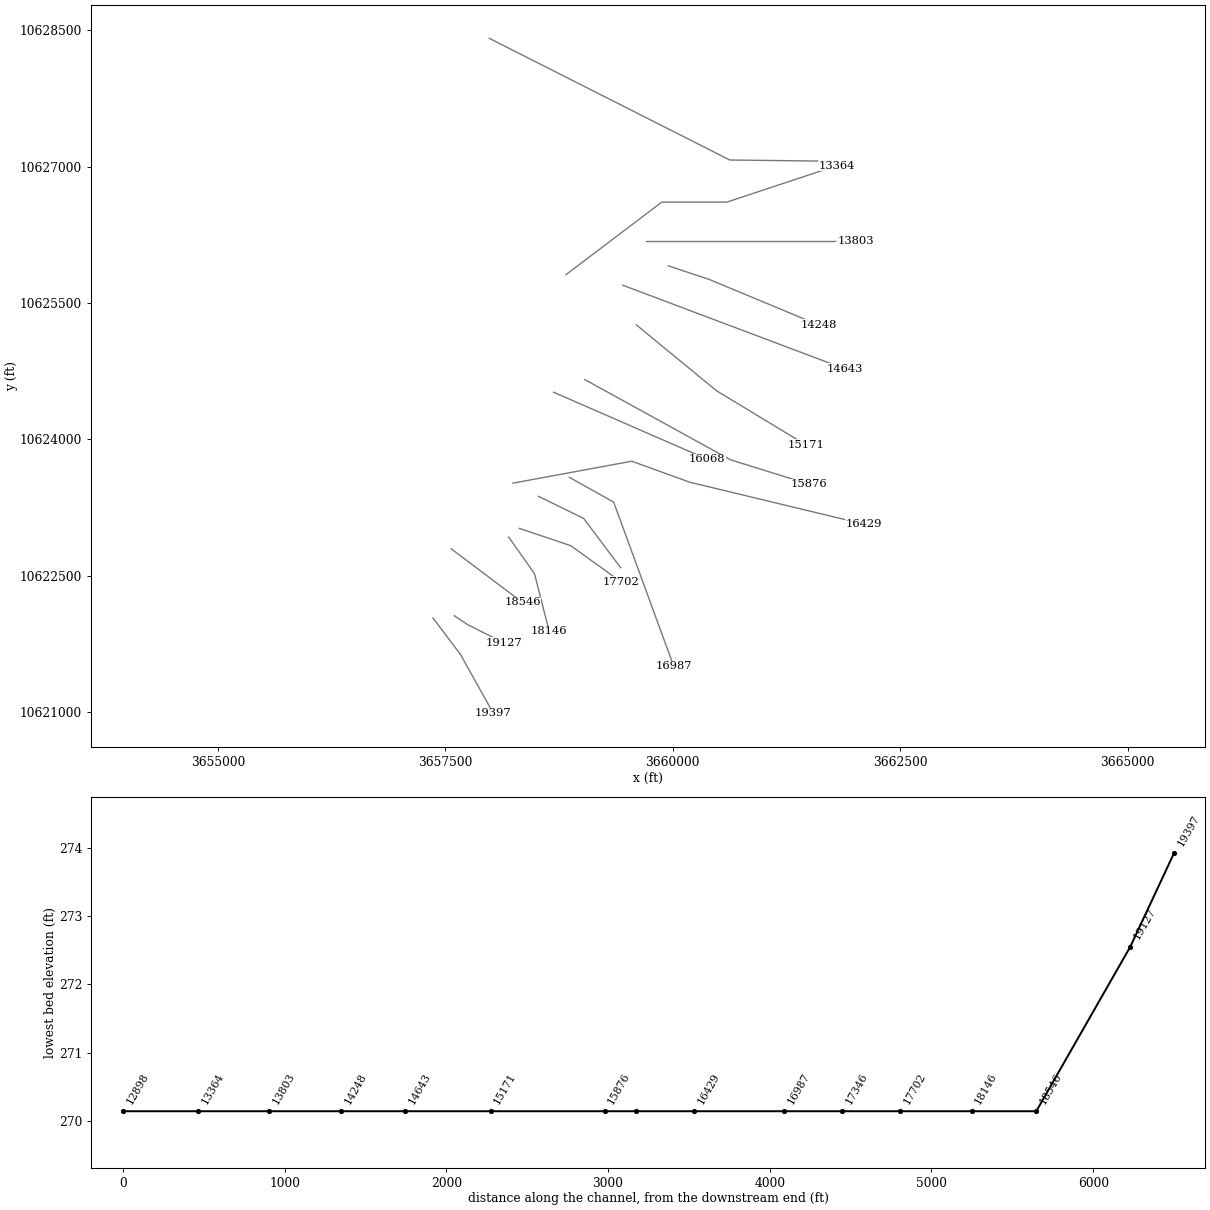
HEC-RAS study INDIAN CREEK 2.prj: INDIAN CREEK 2 Base Level Engineering

--- INDIAN CREEK 2.g01 (geometry) --- (continued)

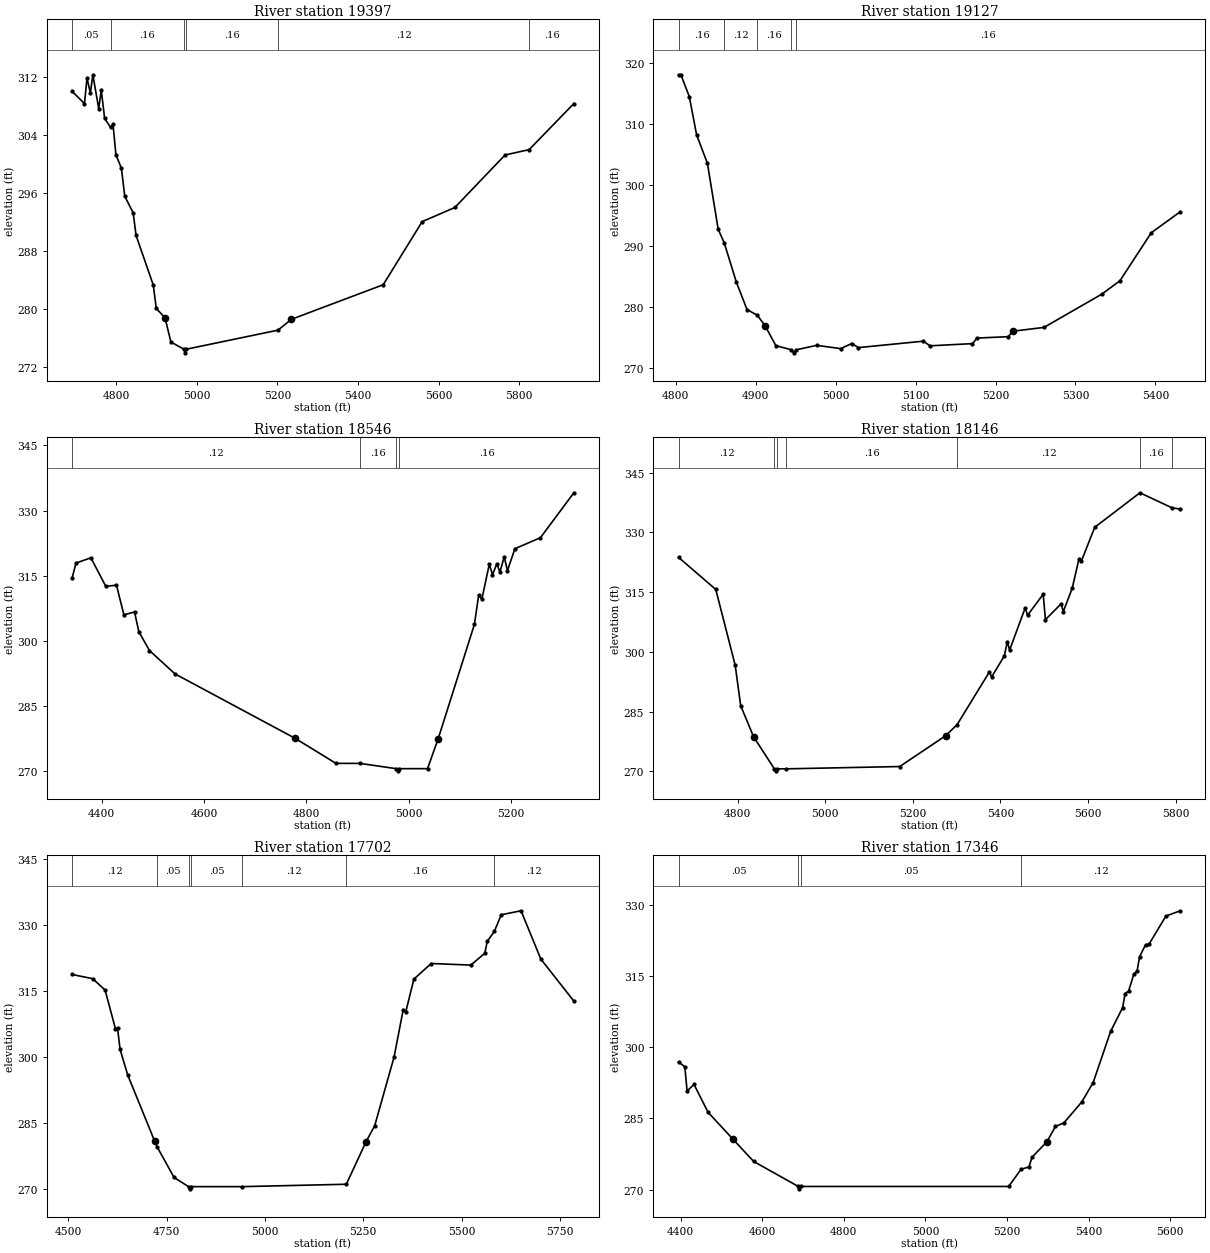
Type RM Length L Ch R = 1 ,19397   ,270,270,270
BEGIN DESCRIPTION:
INDIAN CREEK 2 30.0
END DESCRIPTION:
XS GIS Cut Line= 3
      3657364.07     10622037.14      3657667.88     10621633.51
      3658028.14     10620986.77
#Sta/Elev= 30
  4690.2  309.98    4721  308.29  4727.3  311.81  4735.6  309.76  4741.8  312.26
  4756.4  307.59  4762.7  310.14    4771  306.25  4785.7     305  4791.8  305.44
    4799  301.26  4812.6  299.37    4821  295.52  4841.8  293.23  4849.1   290.1
  4891.8  283.26  4899.2  280.04  4920.9  278.75  4935.5  275.41  4967.9  274.42
  4970.6  273.92  4973.9  274.42  5201.4  277.05  5234.5  278.54  5462.5  283.31
  5559.2  292.01  5640.3  293.96  5764.9   301.2  5824.7  301.94  5935.7  308.29
#Mann= 6 ,-1 , 0
  4690.2     .05       0  4785.7     .16       0  4967.9     .07       0
  4973.9     .16       0  5201.4     .12       0  5824.7     .16       0
Bank Sta=4920.9,5234.5
XS Rating Curve= 0 ,0
Exp/Cntr=0.3,0.1

Type RM Length L Ch R = 1 ,19127   ,581,581,581
BEGIN DESCRIPTION:
INDIAN CREEK 2 29.0
END DESCRIPTION:
XS GIS Cut Line= 3
       3657599.6      10622060.2      3657749.61     10621960.19
       3658149.6     10621760.19
#Sta/Elev= 30
  4803.6  318.13  4806.6  318.13  4817.1  314.53  4826.2  308.28  4839.7  303.62
  4853.2   292.8  4860.9  290.53  4875.7  284.22  4889.2  279.65  4902.1  278.71
  4911.8     277  4925.3  273.73  4944.8  273.05  4947.6  272.55  4950.8  273.05
  4976.4  273.78  5006.3  273.24  5020.2  274.08  5028.6  273.41  5109.7  274.46
  5118.1   273.7  5171.2  274.06  5176.8  274.97  5215.9   275.2  5221.5  276.09
  5260.6  276.72  5333.3   282.2  5355.6  284.37  5394.8  292.24  5431.1  295.68
#Mann= 5 ,-1 , 0
  4803.6     .16       0  4860.9     .12       0  4902.1     .16       0
  4944.8     .07       0  4950.8     .16       0
Bank Sta=4911.8,5221.5
XS Rating Curve= 0 ,0
Exp/Cntr=0.3,0.1

Type RM Length L Ch R = 1 ,18546   ,400,400,400
BEGIN DESCRIPTION:
INDIAN CREEK 2 28.0
END DESCRIPTION:
XS GIS Cut Line= 2
      3657564.98     10622797.14        3658348.     10622206.84
#Sta/Elev= 30
    4342  314.47  4349.7  317.94  4378.8  319.15  4407.9  312.59  4428.8  312.85
  4443.3  306.03  4464.1  306.69  4472.5  302.14  4493.3  297.81  4543.2  292.44
  4778.5  277.58  4857.6  271.86  4904.7  271.85  4975.4  270.64  4978.1  270.14
  4981.4  270.64  5036.6  270.64  5057.5  277.53  5128.3  303.85  5136.6  310.56
  5142.8  309.64  5157.4  317.69  5163.6  315.27    5172  317.75  5178.2  315.89
  5186.5  319.39  5192.8   316.2  5207.4  321.24  5257.3  323.78  5322.6  334.11
#Mann= 4 ,-1 , 0
    4342     .12       0  4904.7     .16       0  4975.4     .07       0
  4981.4     .16       0
Bank Sta=4778.5,5057.5
XS Rating Curve= 0 ,0
Exp/Cntr=0.3,0.1

Type RM Length L Ch R = 1 ,18146   ,444,444,444
BEGIN DESCRIPTION:
INDIAN CREEK 2 27.0
END DESCRIPTION:
XS GIS Cut Line= 3
       3658196.7     10622926.15      3658480.96     10622522.54
      3658641.56     10621891.01
#Sta/Elev= 30
  4665.2  323.72  4750.2  315.67  4794.6   296.6    4807  286.51  4836.4  278.71
  4883.9  270.64  4886.7  270.14  4889.9  270.64  4910.7  270.64  5170.1  271.22
  5274.8  278.95    5301  281.73  5374.7  294.96  5379.8  293.69  5408.9  299.01
  5415.6  302.58  5420.8  300.43  5456.5  311.08  5461.7  309.17  5497.5  314.46
  5502.6  308.09  5538.4  312.05  5543.5  310.13  5563.7  315.95  5579.3  323.39
  5584.5  322.74  5615.1  331.26  5718.3  339.93  5791.4  336.16  5810.5  335.84
#Mann= 7 ,-1 , 0
  4665.2     .12       0  4883.9     .07       0  4889.9     .12       0
  4910.7     .16       0    5301     .12       0  5718.3     .16       0
  5791.4     .12       0
Bank Sta=4836.4,5274.8
XS Rating Curve= 0 ,0
Exp/Cntr=0.3,0.1

Type RM Length L Ch R = 1 ,17702   ,356,356,356
BEGIN DESCRIPTION:
INDIAN CREEK 2 26.0
END DESCRIPTION:
XS GIS Cut Line= 3
       3658313.9     10623021.66      3658880.27      10622830.7
      3659430.37     10622434.37
#Sta/Elev= 30
  4509.9  318.72  4562.4  317.77  4593.9  315.18  4620.1  306.45  4625.4   306.6
    4632  301.73  4651.6  295.89  4719.8  280.96  4726.2  279.64  4769.2  272.72
    4806  270.64  4808.7  270.14    4812  270.64    4943  270.64  5207.1  271.18
  5257.4  280.84  5279.3  284.46  5328.6  300.03  5351.8  310.78    5358  310.16
  5378.9  317.67    5423  321.21  5523.6  320.85  5559.2  323.53  5565.4  326.23
  5583.4  328.48    5601  332.26  5651.3  333.16  5701.6  322.22  5785.6  312.69
#Mann= 7 ,-1 , 0
  4509.9     .12       0  4726.2     .05       0    4806     .07       0
    4812     .05       0    4943     .12       0  5207.1     .16       0
  5583.4     .12       0
Bank Sta=4719.8,5257.4
XS Rating Curve= 0 ,0
Exp/Cntr=0.3,0.1

Type RM Length L Ch R = 1 ,17346   ,359,359,359
BEGIN DESCRIPTION:
INDIAN CREEK 2 25.0
END DESCRIPTION:
XS GIS Cut Line= 3
      3658524.62     10623373.86      3659021.18     10623130.79
       3659427.4     10622589.16
#Sta/Elev= 30
  4394.8  296.86  4410.2  295.85  4415.8  290.74  4432.7  292.14  4467.2  286.26
  4528.3  280.59  4578.9  275.91  4688.4  270.64  4691.2  270.14  4694.4  270.64
    5204  270.64  5234.2  274.25    5254  274.77  5260.9  276.78  5297.8  280.06
  5318.6  283.28  5339.4  284.04  5383.2  288.45  5410.9   292.5    5454  303.33
  5483.2   308.3  5489.4  311.27  5497.8  311.78  5510.9   315.4  5518.6  315.98
  5524.9  319.05  5539.4  321.55  5547.8  321.65  5589.4   327.6  5624.7  328.71
#Mann= 4 ,-1 , 0
  4394.8     .05       0  4688.4    .033       0  4694.4     .05       0
  5234.2     .12       0
Bank Sta=4528.3,5297.8
XS Rating Curve= 0 ,0
Exp/Cntr=0.3,0.1

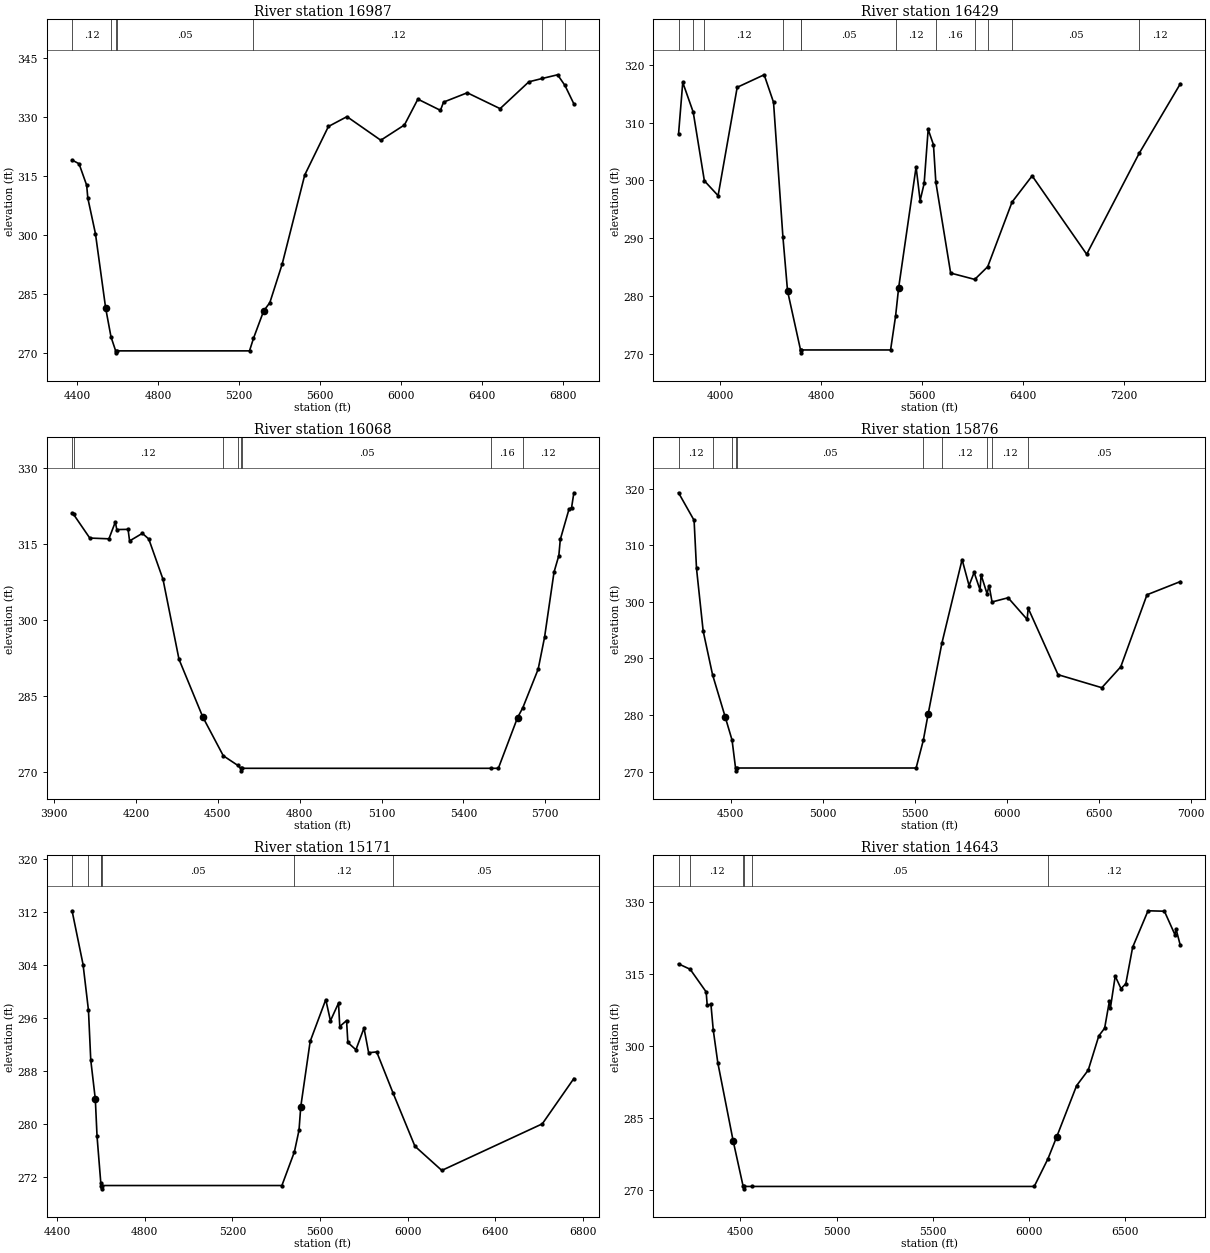
Type RM Length L Ch R = 1 ,16987   ,558,558,558
BEGIN DESCRIPTION:
INDIAN CREEK 2 24.0
END DESCRIPTION:
XS GIS Cut Line= 3
      3658864.92     10623582.18       3659350.3     10623310.92
      3660010.76      10621505.8
#Sta/Elev= 30
  4374.1  319.09  4408.5  318.15  4446.2   312.7  4451.9  309.42  4489.6  300.39
  4539.9  281.52  4566.4  274.19  4589.4  270.64  4592.2  270.14  4595.4  270.64
  5250.4  270.64  5270.1  273.83  5320.3  280.78  5350.8  282.88  5411.9   292.7
  5523.3  315.31  5640.1  327.61  5731.7  330.11  5898.8  324.12  6015.6     328
    6082  334.55  6193.4  331.71  6208.7   333.8  6325.9  336.17    6488  332.14
    6630  338.95  6696.6  339.81    6772  340.74  6808.3  338.03  6852.3  333.36
#Mann= 7 ,-1 , 0
  4374.1     .12       0  4566.4     .05       0  4589.4    .033       0
  4595.4     .05       0  5270.1     .12       0  6696.6     .16       0
  6808.3     .05       0
Bank Sta=4539.9,5320.3
XS Rating Curve= 0 ,0
Exp/Cntr=0.3,0.1

Type RM Length L Ch R = 1 ,16429   ,361,361,361
BEGIN DESCRIPTION:
INDIAN CREEK 2 23.0
END DESCRIPTION:
XS GIS Cut Line= 4
      3658242.48       10623519.      3659549.23     10623760.09
       3660187.3     10623529.33      3662101.03     10623068.29
#Sta/Elev= 30
  3671.2  308.03  3704.6  316.99  3787.5  311.84  3875.9  299.94  3984.7  297.37
    4136  316.14  4349.6  318.31  4423.8  313.55    4498  290.29  4534.9  280.86
  4637.8  270.64  4640.6  270.14  4643.8  270.64  5351.3  270.64  5391.1  276.54
  5415.1   281.4  5553.4  302.34  5585.3  296.51  5617.2  299.48  5649.1  308.85
  5691.1  306.18  5709.9  299.69  5827.2  283.96  6018.1  282.86  6120.8  285.06
  6313.7  296.26  6472.9   300.8  6904.9  287.22  7320.6  304.69    7647  316.75
#Mann= 12 ,-1 , 0
  3671.2     .12       0  3787.5     .05       0  3875.9     .12       0
    4498     .05       0  4637.8    .033       0  4643.8     .05       0
  5391.1     .12       0  5709.9     .16       0  6018.1     .12       0
  6120.8     .16       0  6313.7     .05       0  7320.6     .12       0
Bank Sta=4534.9,5415.1
XS Rating Curve= 0 ,0
Exp/Cntr=0.3,0.1

Type RM Length L Ch R = 1 ,16068   ,192,192,192
BEGIN DESCRIPTION:
INDIAN CREEK 2 22.0
END DESCRIPTION:
XS GIS Cut Line= 2
      3658690.34     10624519.01      3660376.22     10623783.61
#Sta/Elev= 30
  3965.6  321.06    3971  320.84  4030.5  316.15  4100.7     316  4124.1  319.32
  4129.6  317.83  4170.9  317.87  4176.4  315.58  4223.2  317.08  4246.7  315.97
  4298.9     308  4357.6  292.18  4444.8  280.78  4519.9  273.12  4572.1  271.25
  4583.7  270.64  4586.4  270.14  4589.7  270.64  5501.2  270.64  5528.1  270.64
  5598.4  280.65  5617.8  282.61  5674.1  290.24  5697.5  296.54  5732.2  309.42
  5749.8  312.69  5755.2  315.87  5786.8  321.81  5796.6  322.18  5804.9   325.1
#Mann= 8 ,-1 , 0
  3965.6     .16       0    3971     .12       0  4519.9     .16       0
  4572.1     .05       0  4583.7    .033       0  4589.7     .05       0
  5501.2     .16       0  5617.8     .12       0
Bank Sta=4444.8,5598.4
XS Rating Curve= 0 ,0
Exp/Cntr=0.3,0.1

Type RM Length L Ch R = 1 ,15876   ,705,705,705
BEGIN DESCRIPTION:
INDIAN CREEK 2 21.0
END DESCRIPTION:
XS GIS Cut Line= 3
       3659034.1      10624657.9      3660634.82     10623775.94
       3661492.5     10623508.57
#Sta/Elev= 30
  4215.8  319.27  4300.3   314.4  4313.4  305.91  4349.6  294.84  4400.5  287.14
  4468.8  279.72  4506.6  275.57  4525.5  270.64  4528.2  270.14  4531.5  270.64
  5506.4  270.64  5545.4  275.51  5571.7  280.16  5646.5   292.7  5756.3  307.47
  5794.1  302.88  5821.6   305.2  5853.8   302.1  5859.5  304.77  5891.7  301.45
    5903  302.87    5919  299.98  6006.2  300.72  6109.6   296.9  6115.3  298.87
  6277.4  287.13  6515.4  284.83  6618.2  288.52  6760.7  301.25  6941.8  303.58
#Mann= 10 ,-1 , 0
  4215.8     .12       0  4400.5     .16       0  4506.6     .05       0
  4525.5    .033       0  4531.5     .05       0  5545.4     .16       0
  5646.5     .12       0  5891.7     .16       0    5919     .12       0
  6115.3     .05       0
Bank Sta=4468.8,5571.7
XS Rating Curve= 0 ,0
Exp/Cntr=0.3,0.1

Type RM Length L Ch R = 1 ,15171   ,528,528,528
BEGIN DESCRIPTION:
INDIAN CREEK 2 20.0
END DESCRIPTION:
XS GIS Cut Line= 3
      3659599.61     10625260.19       3660480.3     10624535.72
      3661465.52     10623939.04
#Sta/Elev= 30
  4467.7  312.11  4517.9     304  4542.6  297.09  4553.1  289.57  4573.9  283.68
  4581.8  278.06  4598.9  271.04  4599.6  270.64  4602.3  270.14  4605.6  270.64
  5426.2  270.64  5483.3  275.72  5504.4  278.99  5512.3  282.52  5555.3  292.39
  5626.6   298.7    5648  295.51  5684.8  298.17  5690.6  294.64  5721.6  295.54
  5727.5  292.23  5764.3  291.13  5801.2   294.4  5822.5  290.68  5859.3  290.81
  5934.6  284.55  6033.9  276.57  6156.7  272.92  6615.7  279.95  6759.9  286.79
#Mann= 7 ,-1 , 0
  4467.7     .16       0  4542.6     .12       0  4598.9     .05       0
  4599.6    .033       0  4605.6     .05       0  5483.3     .12       0
  5934.6     .05       0
Bank Sta=4573.9,5512.3
XS Rating Curve= 0 ,0
Exp/Cntr=0.3,0.1

Type RM Length L Ch R = 1 ,14643   ,395,395,395
BEGIN DESCRIPTION:
INDIAN CREEK 2 19.0
END DESCRIPTION:
XS GIS Cut Line= 2
       3659450.8     10625696.08      3661891.73     10624775.95
#Sta/Elev= 30
  4178.1  317.14  4238.6  316.01  4321.7  311.28  4327.1  308.53  4346.6  308.66
  4358.5  303.34  4382.2   296.5  4462.1  280.15  4514.1  270.64  4516.9  270.14
  4520.1  270.64  4562.3  270.64  6027.2  270.64  6098.6  276.42  6143.2  280.92
  6247.5   291.7  6307.9  294.94    6363   302.1  6393.2   303.7    6418  309.37
  6423.4  307.97  6448.2  314.58  6478.4  311.96  6503.3  312.99  6538.8  320.61
  6618.8  328.23    6704  328.14  6759.1   323.2  6764.5  324.41  6786.7  320.99
#Mann= 6 ,-1 , 0
  4178.1     .05       0  4238.6     .12       0  4514.1    .033       0
  4520.1     .12       0  4562.3     .05       0  6098.6     .12       0
Bank Sta=4462.1,6143.2
XS Rating Curve= 0 ,0
Exp/Cntr=0.3,0.1

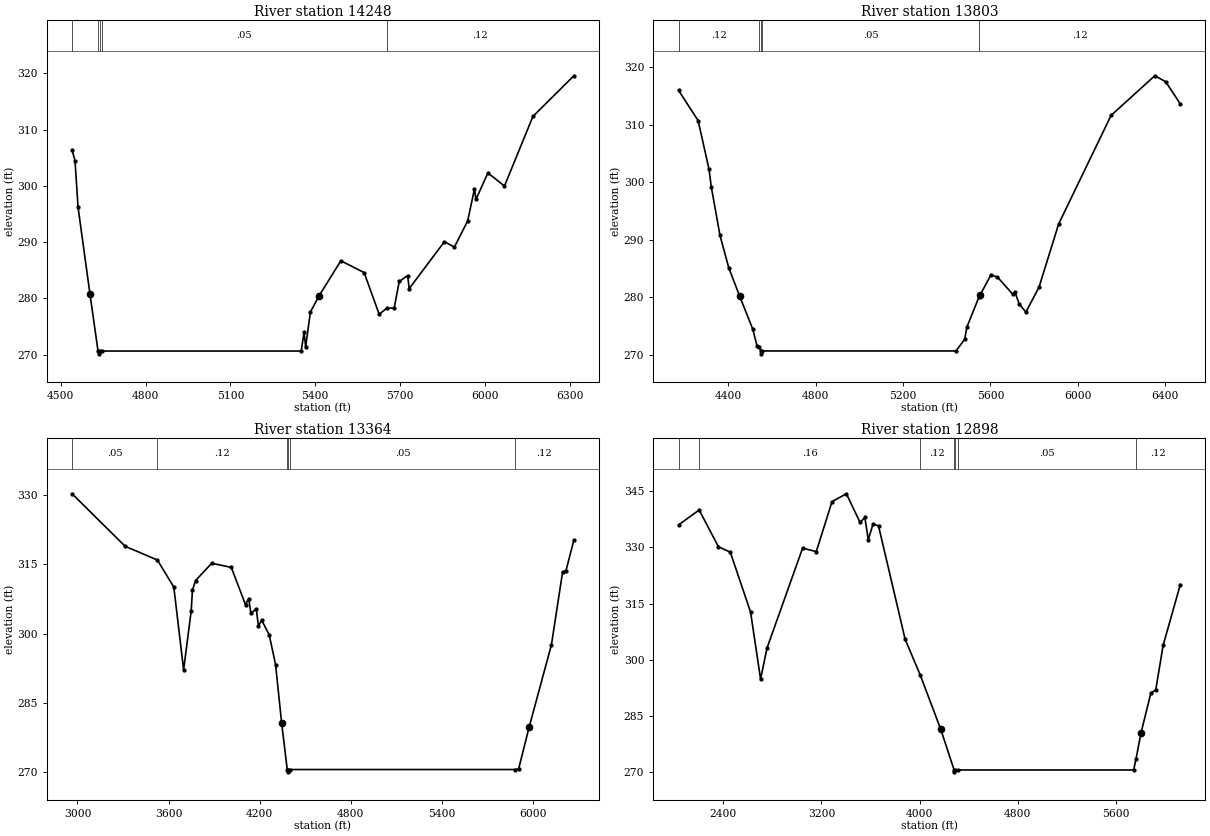
Type RM Length L Ch R = 1 ,14248   ,445,445,445
BEGIN DESCRIPTION:
INDIAN CREEK 2 18.0
END DESCRIPTION:
XS GIS Cut Line= 3
      3659949.63     10625910.18      3660399.61     10625760.19
      3661599.59      10625260.2
#Sta/Elev= 30
  4540.1  306.39  4550.6  304.42  4561.2  296.24  4603.3   280.8  4631.9  270.64
  4634.7  270.14  4637.9  270.64  4644.5  270.64  5350.3  270.64  5360.5  273.97
    5366  271.37  5382.8  277.58  5413.6  280.46  5490.5  286.69  5572.9  284.58
    5626  277.17  5653.4  278.27    5679  278.27  5696.9     283  5726.7  284.04
  5732.1  281.73  5856.7  290.08  5891.9  289.11    5939  293.78  5962.9  299.44
  5968.3   297.6  6010.5   302.3    6069  299.97  6169.8  312.35  6314.4  319.57
#Mann= 5 ,-1 , 0
  4540.1     .12       0  4631.9    .033       0  4637.9     .12       0
  4644.5     .05       0  5653.4     .12       0
Bank Sta=4603.3,5413.6
XS Rating Curve= 0 ,0
Exp/Cntr=0.3,0.1

Type RM Length L Ch R = 1 ,13803   ,439,439,439
BEGIN DESCRIPTION:
INDIAN CREEK 2 17.0
END DESCRIPTION:
XS GIS Cut Line= 2
      3659709.95     10626177.47      3662006.55     10626177.47
#Sta/Elev= 30
  4172.2  315.94  4261.9  310.68  4311.9  302.19  4321.9  299.19  4361.9  290.73
  4401.9  285.12  4451.9  280.16  4511.9  274.44  4531.9  271.44  4541.2   271.4
  4548.9  270.64  4551.6  270.14  4554.9  270.64  5441.9  270.64  5481.9  272.67
  5491.9  274.78  5546.7  279.97  5551.9  280.32  5601.9  283.87  5631.9  283.48
  5701.9   280.5  5711.9  280.88  5731.9  278.77  5761.9   277.4  5821.9  281.71
  5911.9  292.71  6151.9  311.58  6351.9  318.47  6401.9  317.44  6468.8  313.57
#Mann= 5 ,-1 , 0
  4172.2     .12       0  4541.2     .05       0  4548.9    .033       0
  4554.9     .05       0  5546.7     .12       0
Bank Sta=4451.9,5551.9
XS Rating Curve= 0 ,0
Exp/Cntr=0.3,0.1

Type RM Length L Ch R = 1 ,13364   ,466,466,466
BEGIN DESCRIPTION:
INDIAN CREEK 2 16.0
END DESCRIPTION:
XS GIS Cut Line= 4
      3658827.44     10625812.65      3659879.52     10626610.19
      3660594.91     10626610.19      3661799.64      10627010.2
#Sta/Elev= 30
  2964.4  330.28  3314.2  318.92  3526.3  315.95  3634.6   310.1  3699.1  292.19
    3749  304.96  3757.3  309.44  3778.1  311.52  3884.2  315.25  4013.2  314.36
  4106.8  306.28  4127.6  307.61  4142.2  304.44  4177.5  305.36  4192.1  301.64
  4212.9  302.95  4262.8   299.8  4304.7  293.33  4344.7   280.7  4381.7  270.64
  4384.4  270.14  4387.7  270.64  4402.2  270.64  5879.2  270.64  5905.1  270.72
  5974.3  279.74  6121.6  297.61  6195.6  313.45  6216.6  313.54  6269.4  320.26
#Mann= 6 ,-1 , 0
  2964.4     .05       0  3526.3     .12       0  4381.7    .033       0
  4387.7     .12       0  4402.2     .05       0  5879.2     .12       0
Bank Sta=4344.7,5974.3
XS Rating Curve= 0 ,0
Exp/Cntr=0.3,0.1

Type RM Length L Ch R = 1 ,12898   ,443,443,443
BEGIN DESCRIPTION:
INDIAN CREEK 2 15.0
END DESCRIPTION:
XS GIS Cut Line= 3
      3657983.68      10628411.6      3660626.86     10627073.46
      3661749.58     10627060.19
#Sta/Elev= 30
  2037.4  335.98  2205.3  339.97  2362.5  330.15  2458.8  328.73  2624.3  312.69
  2705.3  294.88  2757.9  303.16  3047.5  329.79  3158.9  328.88    3287  342.21
    3404  344.29  3515.4  336.64  3554.3  337.98  3582.2  332.05  3621.2  336.25
  3665.7  335.71  3882.2   305.5    4005  295.98  4172.5  281.46  4280.9  270.64
  4283.7  270.14  4286.9  270.64  4315.2  270.64  5742.8  270.64  5761.5  273.51
  5802.8  280.54  5882.8  291.13  5922.8     292  5982.8  303.87  6122.8  320.08
#Mann= 7 ,-1 , 0
  2037.4     .05       0  2205.3     .16       0    4005     .12       0
  4280.9    .033       0  4286.9     .12       0  4315.2     .05       0
  5761.5     .12       0
Bank Sta=4172.5,5802.8
XS Rating Curve= 0 ,0
Exp/Cntr=0.3,0.1