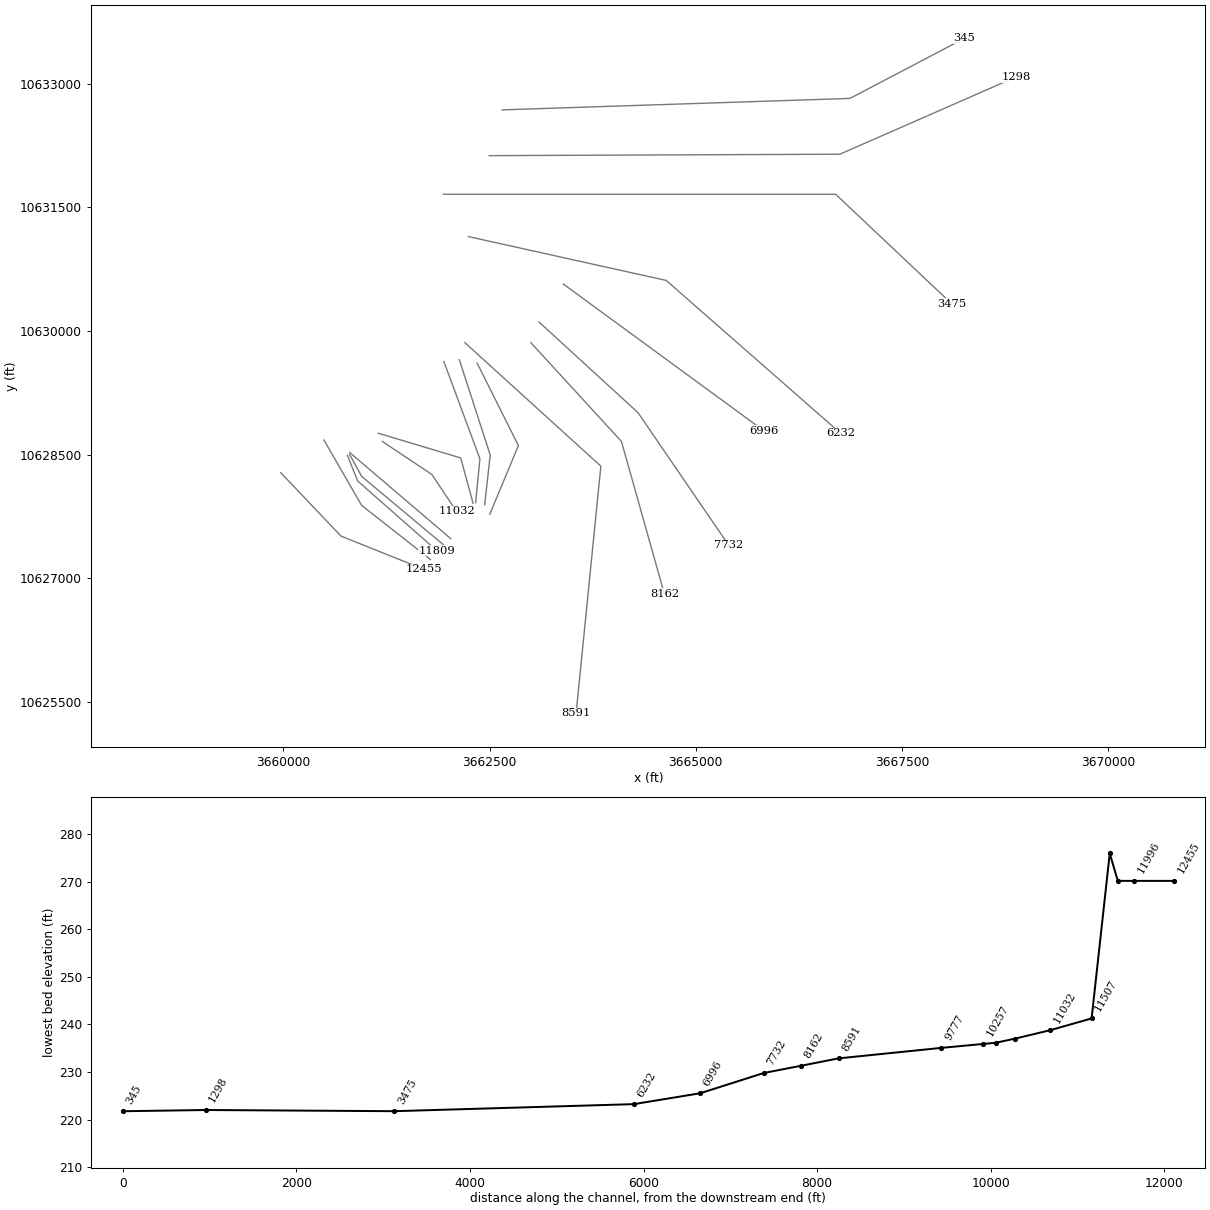
HEC-RAS study INDIAN CREEK 2.prj: INDIAN CREEK 2 Base Level Engineering

--- INDIAN CREEK 2.g01 (geometry) --- (continued)

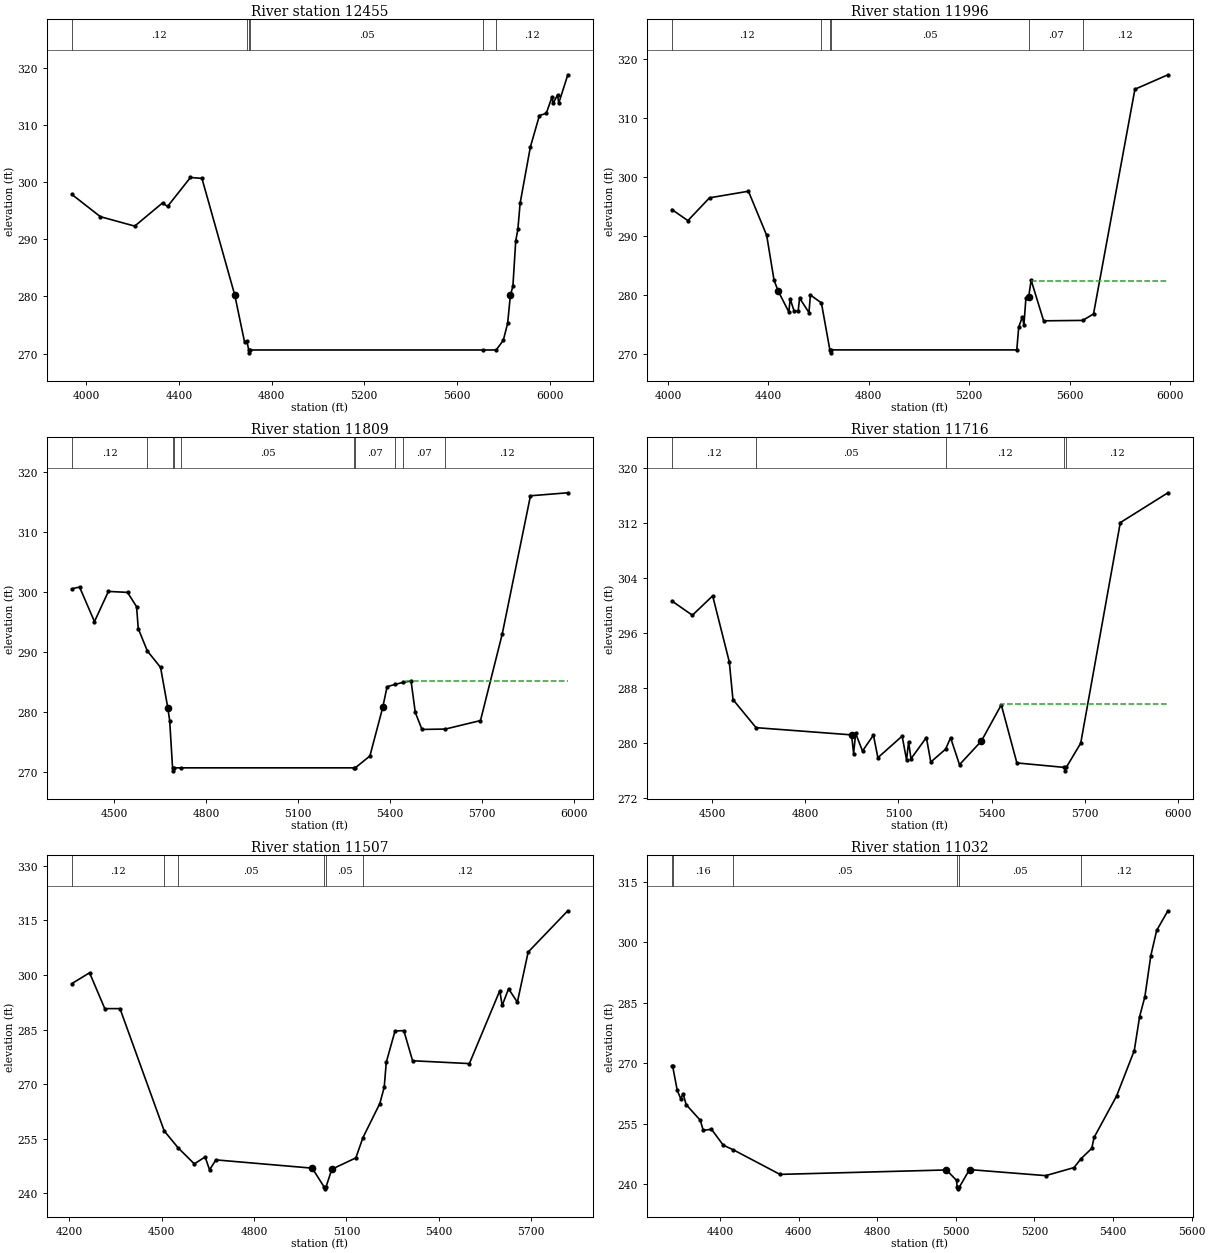
Type RM Length L Ch R = 1 ,12455   ,459,459,459
BEGIN DESCRIPTION:
INDIAN CREEK 2 14.0
END DESCRIPTION:
XS GIS Cut Line= 3
      3659966.89     10628281.61      3660698.59     10627511.21
      3661699.65     10627110.17
#Sta/Elev= 30
  3937.5  297.84  4060.8  293.94  4209.2  292.29  4329.4  296.35  4350.8  295.72
  4449.7  300.79  4499.3  300.63  4640.8  280.26  4683.3  272.01  4693.1  272.22
  4701.3  270.64  4704.1  270.14  4707.3  270.64  5711.5  270.64  5769.2  270.64
  5799.8  272.31  5818.7  275.29  5830.6  280.24  5841.4  281.77  5853.7  289.73
  5862.9  291.72  5872.5  296.27  5916.8  306.12  5955.9  311.62  5985.5     312
  6009.7   314.8  6015.1  313.76    6034  315.21  6039.3  313.77  6078.4  318.74
#Mann= 6 ,-1 , 0
  3937.5     .12       0  4693.1     .05       0  4701.3    .033       0
  4707.3     .05       0  5711.5     .07       0  5769.2     .12       0
Bank Sta=4640.8,5830.6
XS Rating Curve= 0 ,0
Exp/Cntr=0.3,0.1

Type RM Length L Ch R = 1 ,11996   ,187,187,187
BEGIN DESCRIPTION:
INDIAN CREEK 2 13.0
END DESCRIPTION:
XS GIS Cut Line= 3
      3660491.17     10628677.48      3660947.54     10627885.66
      3661783.02     10627228.13
#Sta/Elev= 30
    4015  294.49  4078.7  292.61  4164.9  296.48    4320   297.6  4392.8   290.1
    4422  282.52  4437.8  280.71  4480.9   277.1  4486.7  279.27  4502.5  277.19
  4518.2  277.23    4524  279.44  4561.3  276.98  4567.1  279.97  4610.9  278.62
  4644.6  270.64  4647.3  270.14  4650.6  270.64  5389.7  270.64  5397.3  274.48
  5411.8  276.27  5418.1  274.88  5426.2   279.5  5436.5  279.55    5447  282.47
  5496.7  275.58  5652.7  275.65  5695.5  276.75  5860.5  314.93  5992.1  317.39
#Mann= 6 ,-1 , 0
    4015     .12       0  4610.9     .05       0  4644.6    .033       0
  4650.6     .05       0  5436.5     .07       0  5652.7     .12       0
#XS Ineff= 2 , 0
                         5447.93          282.35
Permanent Ineff=
       F       F
Bank Sta=4437.8,5436.5
XS Rating Curve= 0 ,0
Exp/Cntr=0.3,0.1

Type RM Length L Ch R = 1 ,11809   ,93,93,93
BEGIN DESCRIPTION:
Mapping XS c88c8515
END DESCRIPTION:
XS GIS Cut Line= 3
      3660776.12      10628491.1       3660899.8      10628180.8
      3661863.31      10627332.3
#Sta/Elev= 30
    4362  300.51  4387.4  300.81    4436  295.04  4481.4  300.08  4543.8  299.92
  4573.4  297.52  4578.8  293.88  4608.3  290.16  4651.6   287.4  4675.2  280.65
  4681.3  278.54  4690.7  270.64  4693.4  270.14  4696.7  270.64  4718.3  270.64
  5282.2  270.64  5286.7  270.64  5334.4  272.62  5376.2  280.71  5390.4  284.18
  5416.1  284.56  5442.9   284.9  5468.6  285.15  5482.4  279.89  5504.2  277.05
  5580.4  277.11  5695.1  278.53  5766.1  292.99  5858.1  316.04  5979.9  316.54
#Mann= 10 ,-1 , 0
    4362     .12       0  4608.3     .07       0  4690.7     .03       0
  4696.7     .07       0  4718.3     .05       0  5282.2     .12       0
  5286.7     .07       0  5416.1     .12       0  5442.9     .07       0
  5580.4     .12       0
#XS Ineff= 2 , 0
                         5451.31          285.13
Permanent Ineff=
       F       F
Bank Sta=4675.2,5376.2
XS Rating Curve= 0 ,0
Exp/Cntr=0.3,0.1

Type RM Length L Ch R = 1 ,11716   ,209,209,209
BEGIN DESCRIPTION:
Mapping XS 4029fcf3
END DESCRIPTION:
XS GIS Cut Line= 3
      3660802.12     10628502.03      3660949.71     10628235.06
      3661941.43     10627406.09
#Sta/Elev= 30
  4370.5  300.61  4436.5  298.54  4501.8  301.36  4555.4  291.75  4567.1  286.28
  4641.5  282.19  4949.1  281.14  4955.8  278.43  4962.3  281.36  4984.4  278.79
  5019.6  281.11  5033.9  277.82    5112  280.96  5126.3  277.51  5132.8   280.1
  5140.6  277.67  5190.1  280.75  5204.4  277.19  5251.9  279.06  5268.1  280.72
  5296.8  276.81  5367.1  280.23  5431.4  285.51  5481.6  277.06  5634.7  276.41
  5637.5  275.91  5640.7  276.41  5687.2  279.93  5814.7  312.01  5968.1  316.35
#Mann= 5 ,-1 , 0
  4370.5     .12       0  4641.5     .05       0  5251.9     .12       0
  5634.7     .03       0  5640.7     .12       0
#XS Ineff= 2 , 0
                         5429.97          285.67
Permanent Ineff=
       F       F
Bank Sta=4949.1,5367.1
XS Rating Curve= 0 ,0
Exp/Cntr=0.3,0.1

Type RM Length L Ch R = 1 ,11507   ,475,475,475
BEGIN DESCRIPTION:
INDIAN CREEK 2 12.0
END DESCRIPTION:
XS GIS Cut Line= 2
      3660804.33     10628525.84      3662030.48     10627479.82
#Sta/Elev= 30
  4207.6  297.61  4265.4  300.59  4314.8  290.75  4364.2  290.75  4507.9  257.16
  4553.2  252.51  4605.8   248.1  4640.9  250.02  4655.2  246.48    4676   249.2
  4988.9  246.93  5027.6  241.75  5030.4  241.25  5033.6  241.75  5052.6  246.64
  5130.6  249.75  5153.6  255.31  5208.5  264.68  5222.8  269.16  5229.4  275.99
  5257.9  284.61  5286.5   284.7    5315  276.43  5499.5  275.65  5598.3  295.66
    5606  291.61  5626.8  296.19  5655.4  292.51  5690.5  306.28  5819.3  317.62
#Mann= 6 ,-1 , 0
  4207.6     .12       0  4507.9     .16       0  4553.2     .05       0
  5027.6     .03       0  5033.6     .05       0  5153.6     .12       0
Bank Sta=4988.9,5052.6
XS Rating Curve= 0 ,0
Exp/Cntr=0.3,0.1

Type RM Length L Ch R = 1 ,11032   ,402,402,402
BEGIN DESCRIPTION:
INDIAN CREEK 2 11.0
END DESCRIPTION:
XS GIS Cut Line= 3
      3661199.57     10628660.21      3661799.61     10628260.19
      3662099.61     10627810.18
#Sta/Elev= 30
  4277.6  269.37  4279.3  269.37  4291.2  263.25  4300.2  261.17  4306.2  262.44
  4313.7  259.73  4349.8  255.82  4357.3  253.32  4378.3  253.59  4408.3  249.63
  4434.3  248.46  4552.6  242.38  4976.2  243.48  5001.8  240.88  5003.3  239.29
    5006  238.79  5009.3  239.29  5034.8  243.57  5228.6  242.07  5300.7  244.07
  5318.2  246.25  5345.8  248.84  5351.8  251.57  5408.9  261.83    5454  273.14
  5467.5  281.54    5481  286.53    5496  296.68    5511  302.99  5539.6  307.86
#Mann= 6 ,-1 , 0
  4277.6     .12       0  4279.3     .16       0  4434.3     .05       0
  5003.3     .03       0  5009.3     .05       0  5318.2     .12       0
Bank Sta=4976.2,5034.8
XS Rating Curve= 0 ,0
Exp/Cntr=0.3,0.1

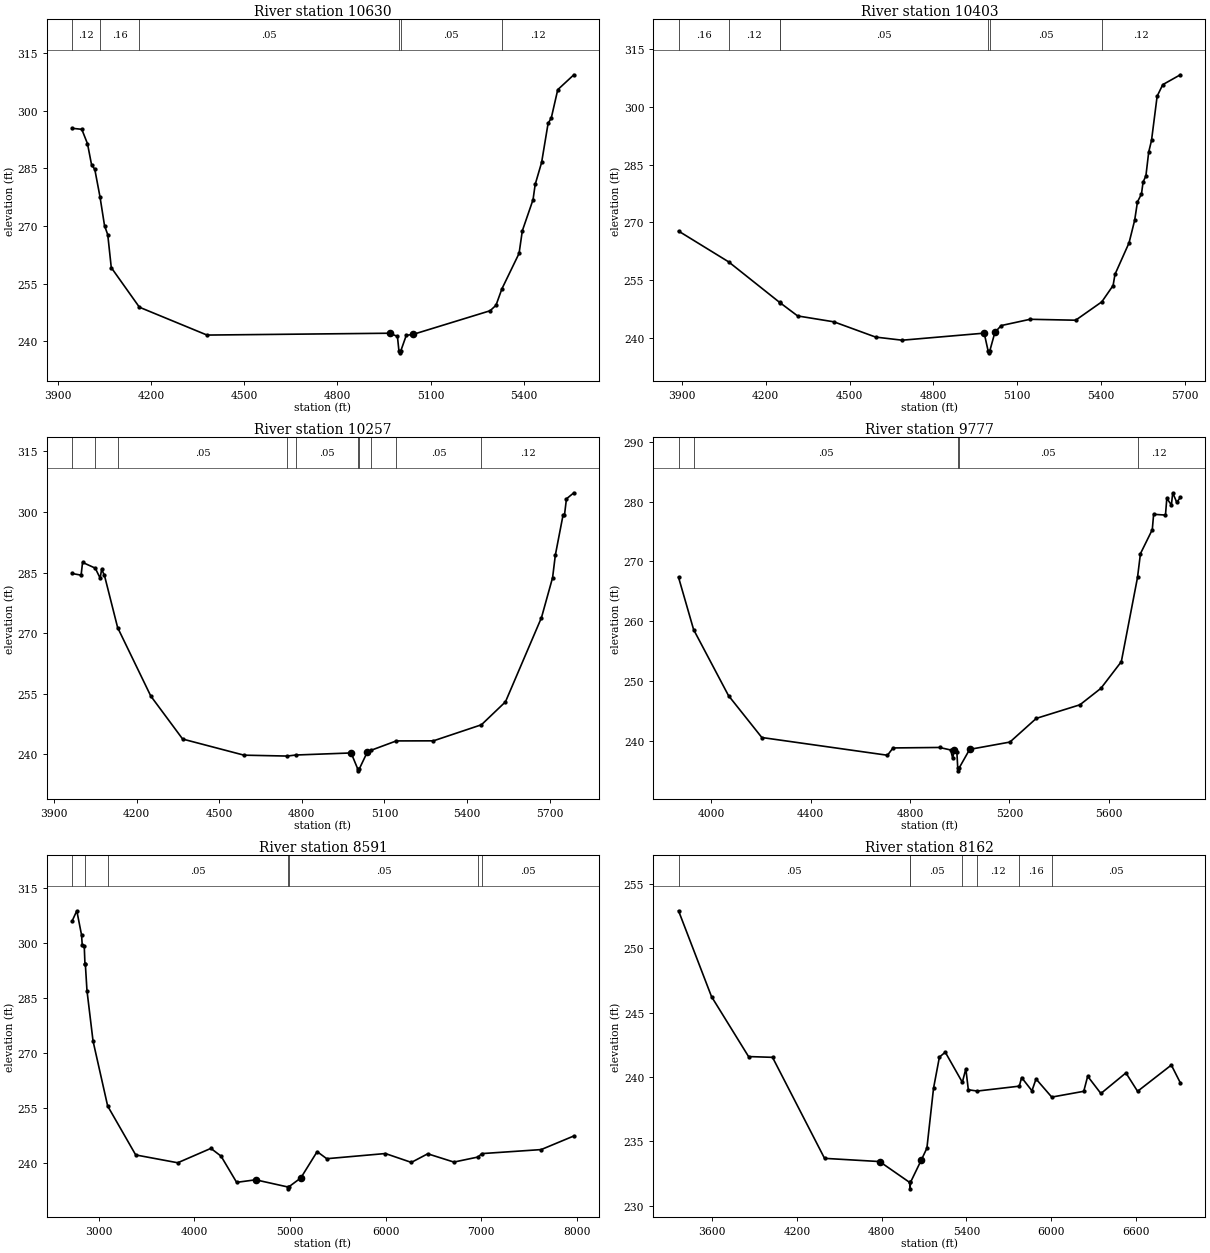
Type RM Length L Ch R = 1 ,10630   ,227,227,227
BEGIN DESCRIPTION:
INDIAN CREEK 2 10.0
END DESCRIPTION:
XS GIS Cut Line= 3
      3661149.63     10628760.18      3662149.61     10628460.19
      3662299.61     10627910.19
#Sta/Elev= 30
  3946.4  295.41  3977.7  295.14    3996   291.4    4009  285.96  4019.5  284.73
  4036.3  277.56  4050.8   270.1  4061.2  267.73  4072.5  259.19    4163  248.89
  4380.5  241.65  4968.7  242.13    4993  241.29  4997.8  237.53  5000.5  237.03
  5003.8  237.53  5021.5  241.59  5042.2   241.8    5291  247.97    5310  249.39
    5329  253.66  5384.3  262.89  5394.7  268.75  5429.2  276.85  5436.1  280.81
  5456.8  286.54  5477.6  296.67  5487.9   298.1  5508.7  305.45  5560.5  309.32
#Mann= 6 ,-1 , 0
  3946.4     .12       0  4036.3     .16       0    4163     .05       0
  4997.8     .03       0  5003.8     .05       0    5329     .12       0
Bank Sta=4968.7,5042.2
XS Rating Curve= 0 ,0
Exp/Cntr=0.3,0.1

Type RM Length L Ch R = 1 ,10403   ,146,146,146
BEGIN DESCRIPTION:
Mapping XS b14b1272
END DESCRIPTION:
XS GIS Cut Line= 3
      3661945.56     10629631.25      3662383.07     10628448.92
      3662330.99     10627917.65
#Sta/Elev= 30
  3888.4  267.75  4067.5  259.76  4249.8  249.24  4252.5  249.09  4314.3  245.72
    4444  244.19  4593.3  240.23  4688.2  239.42  4981.5  241.25  4995.5  236.64
  4998.2  236.14  5001.5  236.64  5019.8  241.46  5042.3  243.22  5145.7  244.85
  5308.6  244.61  5402.1  249.38  5442.5  253.62  5449.2  256.51  5499.5  264.69
  5519.6  270.56  5529.6  275.31    5544   277.4  5549.7  280.48  5559.8  282.07
  5569.8  288.26  5579.9  291.29    5600  302.77  5620.1  305.76  5682.9  308.32
#Mann= 7 ,-1 , 0
  3888.4     .16       0  4067.5     .12       0  4249.8     .08       0
  4252.5     .05       0  4995.5     .04       0  5001.5     .05       0
  5402.1     .12       0
Bank Sta=4981.5,5019.8
XS Rating Curve= 0 ,0
Exp/Cntr=0.3,0.1

Type RM Length L Ch R = 1 ,10257   ,480,480,480
BEGIN DESCRIPTION:
INDIAN CREEK 2 9.0
END DESCRIPTION:
XS GIS Cut Line= 3
      3662133.07     10629652.06      3662508.07     10628495.79
      3662440.57     10627893.42
#Sta/Elev= 30
  3965.8  284.76  3998.6  284.35  4003.9  287.51  4049.9  286.09  4067.8   283.6
  4073.1   285.8  4083.4  284.28  4131.2  271.37  4251.6  254.41  4367.3  243.76
    4590  239.77  4746.7  239.55  4778.6  239.81  4978.9  240.32  5002.7  236.39
  5005.4  235.89  5008.7  236.39  5037.6  240.53  5052.1     241  5142.9   243.3
  5277.6  243.32    5452   247.3  5539.2  252.98    5670  273.85  5710.3  283.74
  5720.3  289.33  5748.3  299.24  5753.4   299.2  5760.6  303.25  5787.5  304.75
#Mann= 10 ,-1 , 0
  3965.8     .05       0  4049.9     .16       0  4131.2     .05       0
  4746.7     .08       0  4778.6     .05       0  5002.7     .03       0
  5008.7     .05       0  5052.1     .08       0  5142.9     .05       0
    5452     .12       0
Bank Sta=4978.9,5037.6
XS Rating Curve= 0 ,0
Exp/Cntr=0.3,0.1

Type RM Length L Ch R = 1 ,9777    ,1186,1186,1186
BEGIN DESCRIPTION:
INDIAN CREEK 2 8.0
END DESCRIPTION:
XS GIS Cut Line= 3
      3662349.61     10629610.19      3662849.61     10628610.19
      3662502.85       10627777.
#Sta/Elev= 30
  3867.4  267.36  3928.1  258.63  4068.6  247.62  4202.8  240.63  4708.7  237.67
  4731.1  238.89  4918.4  238.97  4963.1  238.55  4971.5  237.15    4977  238.55
  4988.1  238.25  4991.6  235.57  4994.4  235.07  4997.6  235.57  5039.6  238.65
  5201.7  239.87  5307.9  243.82  5483.7  246.09    5568  248.83  5650.3  253.28
  5715.5  267.33  5727.3   271.3    5775  275.31  5780.4  277.87  5828.1  277.74
  5833.5  280.54  5851.9  279.42  5857.3  281.46  5873.6  279.86  5887.9  280.69
#Mann= 5 ,-1 , 0
  3867.4     .16       0  3928.1     .05       0  4991.6     .03       0
  4997.6     .05       0  5715.5     .12       0
Bank Sta=4977,5039.6
XS Rating Curve= 0 ,0
Exp/Cntr=0.3,0.1

Type RM Length L Ch R = 1 ,8591    ,429,429,429
BEGIN DESCRIPTION:
INDIAN CREEK 2 7.0
END DESCRIPTION:
XS GIS Cut Line= 3
      3662199.64     10629860.16      3663849.61     10628360.19
      3663549.61     10625360.21
#Sta/Elev= 30
  2723.5  305.97  2773.1   308.8  2822.4  302.21  2829.9  299.45  2850.8  299.16
  2858.3  294.22  2862.4  294.18  2879.2  287.02  2942.7  273.22  3095.5  255.48
  3388.7  242.12  3827.9  239.98  4174.6  243.91  4280.7  241.79  4443.5  234.63
  4642.2  235.33  4980.5  233.36  4983.3  232.86  4986.5  233.36  5114.2  235.83
    5285  243.02  5385.5  241.09  5998.5   242.5  6269.9  240.08  6440.7  242.43
  6714.6  240.17  6968.5  241.56  7004.7  242.48  7626.6  243.58  7968.3   247.3
#Mann= 7 ,-1 , 0
  2723.5     .05       0  2862.4     .16       0  3095.5     .05       0
  4980.5     .03       0  4986.5     .05       0  6968.5     .12       0
  7004.7     .05       0
Bank Sta=4642.2,5114.2
XS Rating Curve= 0 ,0
Exp/Cntr=0.3,0.1

Type RM Length L Ch R = 1 ,8162    ,430,430,430
BEGIN DESCRIPTION:
INDIAN CREEK 2 6.0
END DESCRIPTION:
XS GIS Cut Line= 3
      3662999.58     10629860.22      3664099.61     10628660.19
      3664620.06     10626808.98
#Sta/Elev= 30
  3362.9  252.93  3596.3  246.26  3858.4   241.6    4028  241.54  4396.1  233.69
  4785.8  233.44  4998.2  231.82    5001  231.32  5004.2  231.82  5081.2  233.57
  5120.4  234.48  5167.4  239.14    5209  241.56  5250.5  241.94  5371.3   239.6
  5395.9  240.65  5413.6  239.02  5476.9  238.92  5774.4   239.3  5790.7  239.97
  5863.8  238.94  5892.7  239.86  6003.9  238.45  6230.4   238.9  6258.1  240.07
  6351.6  238.73  6528.8  240.33  6611.3   238.9  6850.2  240.94  6913.8  239.56
#Mann= 7 ,-1 , 0
  3362.9     .05       0  4998.2     .03       0  5004.2     .05       0
  5371.3     .16       0  5476.9     .12       0  5774.4     .16       0
  6003.9     .05       0
Bank Sta=4785.8,5081.2
XS Rating Curve= 0 ,0
Exp/Cntr=0.3,0.1

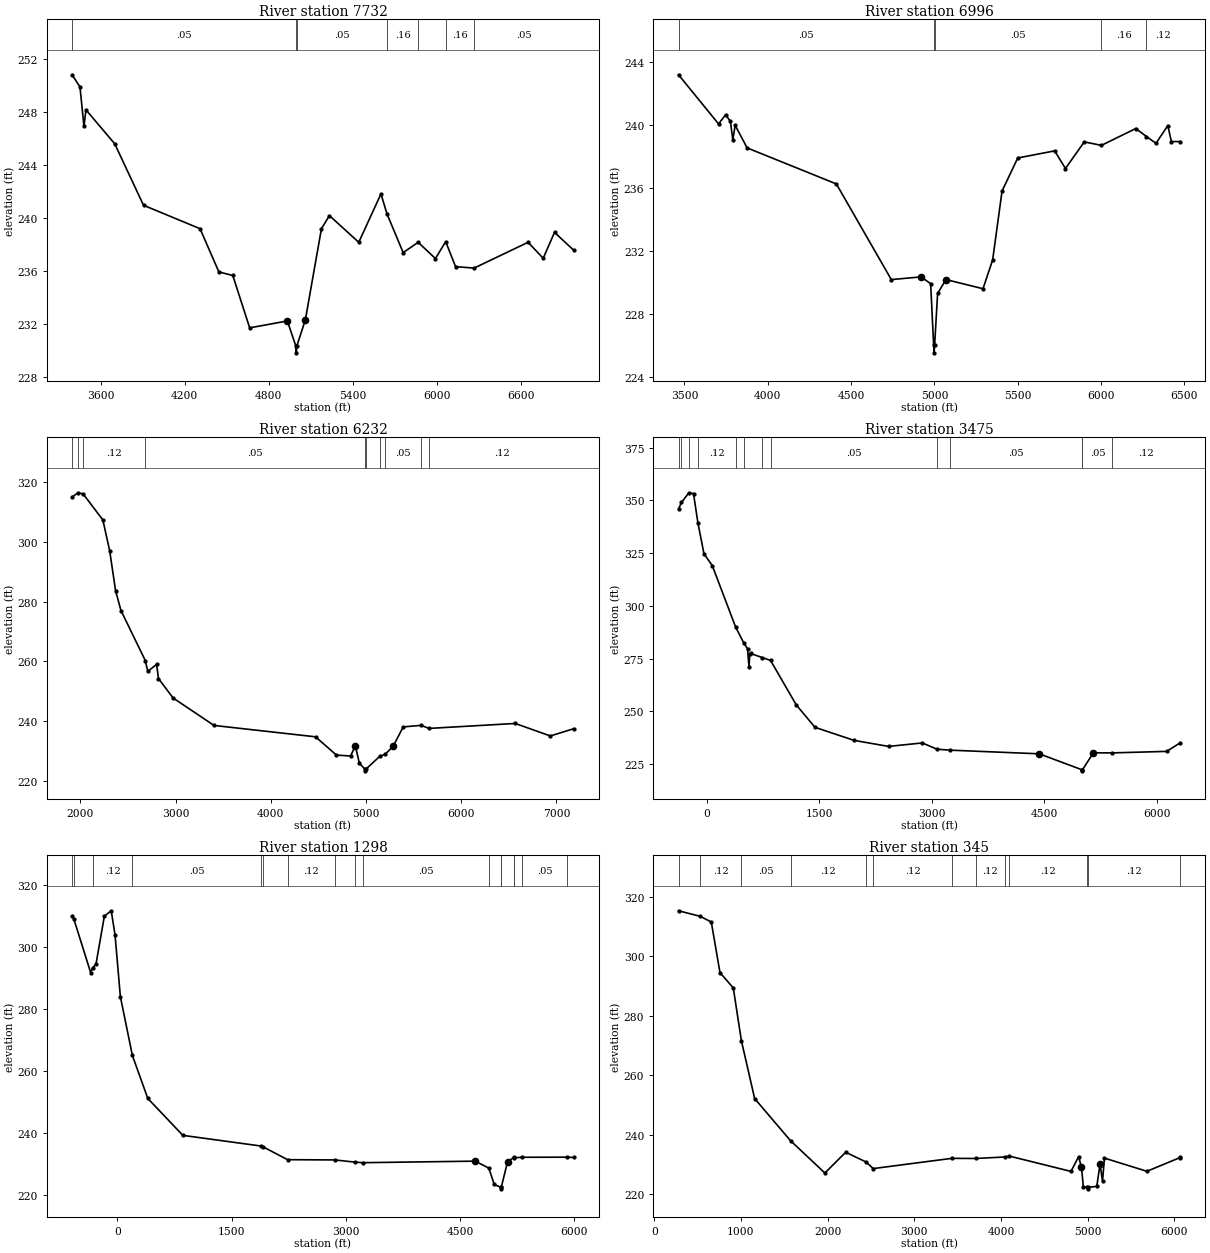
Type RM Length L Ch R = 1 ,7732    ,736,736,736
BEGIN DESCRIPTION:
INDIAN CREEK 2 5.0
END DESCRIPTION:
XS GIS Cut Line= 3
       3663099.6      10630110.2      3664299.61     10629010.19
      3665401.31     10627399.28
#Sta/Elev= 30
  3396.8  250.83  3453.2  249.91  3481.6  246.93  3495.8  248.18  3701.1  245.61
  3906.5  240.96  4309.7  239.19  4444.1  235.92  4543.4  235.65  4663.7  231.69
  4932.5  232.21  4993.6   230.3  4996.4   229.8  4999.6   230.3    5061   232.3
  5175.7  239.19  5232.6  240.18  5441.8  238.16  5600.3  241.82  5642.5  240.33
  5758.7  237.38  5865.6  238.16    5989  236.93    6062  238.21  6132.5  236.32
  6264.6  236.21  6649.9  238.16  6757.5  236.95  6838.2  238.91  6976.3  237.55
#Mann= 7 ,-1 , 0
  3396.8     .05       0  4993.6     .03       0  4999.6     .05       0
  5642.5     .16       0  5865.6     .12       0    6062     .16       0
  6264.6     .05       0
Bank Sta=4932.5,5061
XS Rating Curve= 0 ,0
Exp/Cntr=0.3,0.1

Type RM Length L Ch R = 1 ,6996    ,764,764,764
BEGIN DESCRIPTION:
Mapping XS 626bee3f
END DESCRIPTION:
XS GIS Cut Line= 2
      3663395.16     10630570.22      3665825.18     10628791.09
#Sta/Elev= 30
  3464.4  243.18  3704.6  240.06  3746.3  240.64  3775.6  240.23  3790.3  239.05
  3804.5  239.97  3875.9  238.54  4411.8  236.25  4741.4  230.18    4920  230.35
  4977.6  229.92  4995.5  226.03  4998.2  225.53  5001.5  226.03  5019.3   229.3
  5069.5  230.18  5291.8   229.6  5349.7  231.43  5406.1   235.8  5500.3   237.9
  5721.9  238.35  5786.7  237.23  5899.4  238.92  6002.6   238.7  6208.9  239.77
  6272.7  239.26  6330.2  238.83  6401.2  239.96  6422.1  238.94  6476.1  238.94
#Mann= 5 ,-1 , 0
  3464.4     .05       0  4995.5     .03       0  5001.5     .05       0
  6002.6     .16       0  6272.7     .12       0
Bank Sta=4920,5069.5
XS Rating Curve= 0 ,0
Exp/Cntr=0.3,0.1

Type RM Length L Ch R = 1 ,6232    ,2757,2757,2757
BEGIN DESCRIPTION:
Mapping XS fab5dc2d
END DESCRIPTION:
XS GIS Cut Line= 3
      3662243.77      10631146.4      3664641.75     10630614.72
      3666757.62     10628759.26
#Sta/Elev= 30
  1912.2  315.02    1975  316.44  2029.1  316.04  2235.7  307.33  2307.4  296.98
  2368.9  283.68  2425.6  276.98  2681.3  260.22  2707.6  256.59  2799.9  258.92
  2819.6  254.19  2973.2  247.67  3403.4  238.46  4469.6  234.65  4688.8  228.53
  4837.8  228.22  4887.2  231.64  4929.9  225.78  4990.4  223.75  4993.2  223.25
  4996.4  223.75  5144.4  228.12  5197.8  228.74  5283.8  231.43  5390.1  237.98
  5577.9  238.49  5661.7  237.47  6566.9  239.13  6935.1  234.94  7182.6  237.38
#Mann= 10 ,-1 , 0
  1912.2     .12       0    1975     .16       0  2029.1     .12       0
  2681.3     .05       0  4990.4     .03       0  4996.4     .05       0
  5144.4     .07       0  5197.8     .05       0  5577.9     .16       0
  5661.7     .12       0
Bank Sta=4887.2,5283.8
XS Rating Curve= 0 ,0
Exp/Cntr=0.3,0.1

Type RM Length L Ch R = 1 ,3475    ,2177,2177,2177
BEGIN DESCRIPTION:
INDIAN CREEK 2 3.0
END DESCRIPTION:
XS GIS Cut Line= 3
       3661940.1     10631660.14      3666697.07     10631660.14
      3668101.73     10630333.91
#Sta/Elev= 30
  -374.8  345.92    -336  348.98  -237.1  353.58  -175.3  353.19  -116.8  339.34
   -35.3  324.61    74.7   319.1     385  290.05     497  282.21   544.7  279.68
   564.7  271.04   574.7  276.94   584.7  277.42   739.2  275.49   851.2  274.14
  1194.7  253.01  1444.7  242.39  1964.7  236.21  2424.7  233.35  2874.7  234.99
  3070.1  232.03  3242.9  231.58  4433.4  229.84  5003.3  222.27    5006  221.77
  5009.3  222.27  5155.2  230.31  5409.8  230.28  6131.4  230.99    6314  235.07
#Mann= 13 ,-1 , 0
  -374.8     .16       0    -336     .05       0  -237.1     .16       0
  -116.8     .12       0     385     .16       0     497     .12       0
   739.2     .16       0   851.2     .05       0  3070.1     .07       0
  3242.9     .05       0  5003.3     .03       0  5009.3     .05       0
  5409.8     .12       0
Bank Sta=4433.4,5155.2
XS Rating Curve= 0 ,0
Exp/Cntr=0.3,0.1

Type RM Length L Ch R = 1 ,1298    ,953,953,953
BEGIN DESCRIPTION:
INDIAN CREEK 2 2.0
END DESCRIPTION:
XS GIS Cut Line= 3
      3662495.68     10632128.89      3666749.15     10632146.25
      3668884.61     10633083.77
#Sta/Elev= 30
  -592.5  310.15  -568.2  309.03  -348.6  291.81  -322.1  293.37  -278.6  294.52
  -168.6  310.03   -78.6  311.76   -28.6  303.99    41.4  284.06     199  265.07
   401.4   251.2   861.4  239.28  1893.2  235.82  1908.3  235.65  2235.7  231.43
    2854  231.35  3125.9  230.63  3224.9  230.46  4698.4  230.96  4877.2  228.71
  4948.3  223.43  5034.6  222.52  5037.3  222.02  5040.6  222.52  5122.8  230.74
  5205.7  232.19    5211  232.05  5317.2  232.21  5908.2  232.24  5993.2  232.14
#Mann= 17 ,-1 , 0
  -592.5     .05       0  -568.2     .16       0  -322.1     .12       0
     199     .05       0  1893.2     .07       0  1908.3     .05       0
  2235.7     .12       0    2854     .07       0  3125.9     .12       0
  3224.9     .05       0  4877.2     .12       0  5034.6     .07       0
  5040.6     .12       0  5205.7     .05       0    5211     .07       0
  5317.2     .05       0  5908.2     .12       0
Bank Sta=4698.4,5122.8
XS Rating Curve= 0 ,0
Exp/Cntr=0.3,0.1

Type RM Length L Ch R = 1 ,345     ,0,0,0
BEGIN DESCRIPTION:
INDIAN CREEK 2 1.0
END DESCRIPTION:
XS GIS Cut Line= 3
      3662651.91     10632684.44      3666870.68     10632823.33
      3668259.55     10633552.49
#Sta/Elev= 30
   279.9  315.25   530.5  313.38   657.8  311.48   757.9  294.48   911.7  289.31
  1005.3  271.54  1158.1  252.12  1571.9  237.95  1968.5  227.08  2208.6  234.06
  2443.5  230.79  2526.4  228.57  3432.8  232.01  3710.7  231.97  4043.9  232.47
  4096.7  232.77  4808.2  227.62  4896.4  232.61  4928.9  228.96  4951.3  222.37
    4998  222.26  5000.8  221.76    5004  222.26  5105.7  222.59  5143.5  230.11
  5171.8  224.31  5193.9  232.09  5684.1  227.66  6066.1  232.27  6069.6  232.32
#Mann= 13 ,-1 , 0
   279.9     .05       0   530.5     .12       0  1005.3     .05       0
  1571.9     .12       0  2443.5     .16       0  2526.4     .12       0
  3432.8     .07       0  3710.7     .12       0  4043.9     .07       0
  4096.7     .12       0    4998     .07       0    5004     .12       0
  6066.1     .07       0
Bank Sta=4928.9,5143.5
XS Rating Curve= 0 ,0
Exp/Cntr=0.3,0.1

Chan Stop Cuts=-1
Use User Specified Reach Order=0
Composite Channel Slope=5