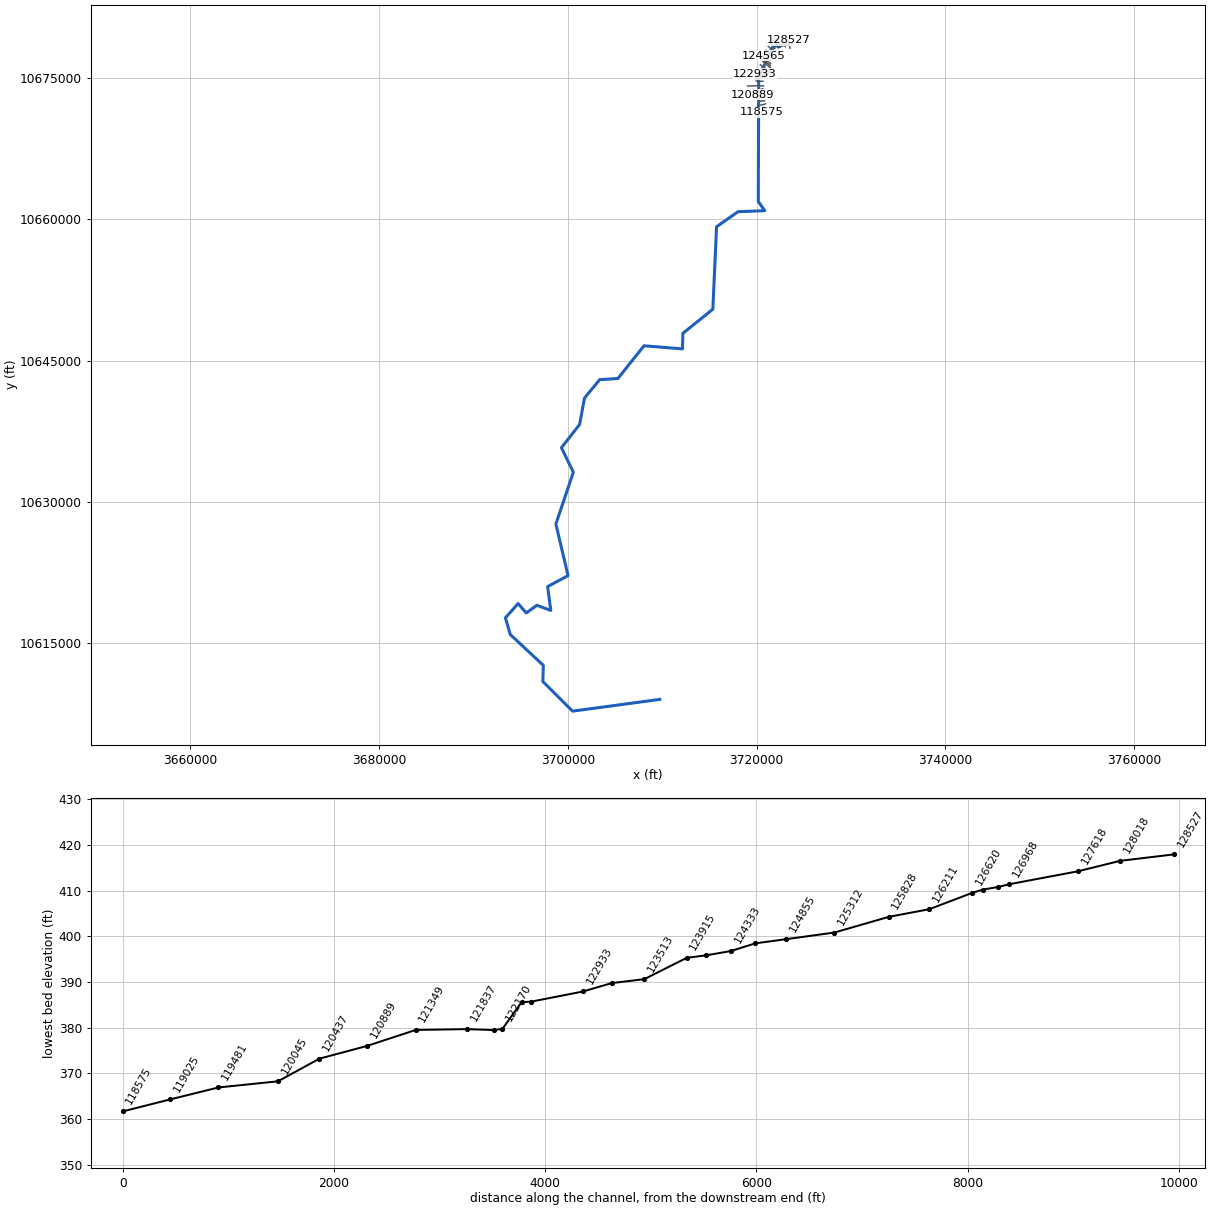
--- LAKE CREEK.prj (project) ---

Proj Title=LAKE CREEK Base Level Engineering
Current Plan=p01
Default Exp/Contr=0.3,0.1
English Units
Geom File=g01
Flow File=f01
Plan File=p01
Y Axis Title=Elevation
X Axis Title(PF)=Main Channel Distance
X Axis Title(XS)=Station
BEGIN DESCRIPTION:
LAKE CREEK
END DESCRIPTION:
DSS Export Rating Curves= 0
DSS Export Rating Curve Sorted= 0
DSS Export Volume Flow Curves= 0
DXF OffsetX= 0
DXF OffsetY= 0
DXF ScaleX= 1
DXF ScaleY= 10

--- LAKE CREEK.p01 (plan) ---

Plan Title=Multiple Run
Short Identifier=Multiple
Geom File=g01
Flow File=f01
Subcritical Flow
K Sum by GR= 0
Std Step Tol= 0.01
Critical Tol= 0.01
Num of Std Step Trials= 20
Max Error Tol= 0.3
Flow Tol Ratio= 0.001
Split Flow NTrial= 30
Split Flow Tol= 0.02
Split Flow Ratio= 0.02
Log Output Level= 0
Friction Slope Method= 1
Unsteady Friction Slope Method= 2
Unsteady Bridges Friction Slope Method= 1
Parabolic Critical Depth
Global Vel Dist=  1 , 1 , 1
Global Log Level= 0
CheckData=True
Encroach Param= -1, 0, 0, 0
BEGIN DESCRIPTION:
Multiple Run
END DESCRIPTION:

--- LAKE CREEK.f01 (steady flow) ---

Flow Title=Multiple
Program Version=4.10
Number of Profiles= 7
Profile Names=10-year,25-year,50-year,1pct_min,100-year,1pct_plu,500-year
River Rch & RM=LAKE CREEK,Reach-1         ,128527
     801    1117    1385    1264    1709    2311    2610
River Rch & RM=LAKE CREEK,Reach-1         ,122933
    1190    1689    2121    1954    2642    3573    4120
River Rch & RM=LAKE CREEK,Reach-1         ,122351
    1190    1689    2121    1954    2642    3573    4120
River Rch & RM=LAKE CREEK,Reach-1         ,115528
    1922    2783    3540    3301    4464    6037    7130
River Rch & RM=LAKE CREEK,Reach-1         ,115135
    1922    2783    3540    3301    4464    6037    7130
River Rch & RM=LAKE CREEK,Reach-1         ,110245
    2646    3868    4953    4642    6278    8490   10133
River Rch & RM=LAKE CREEK,Reach-1         ,103656
    2821    4124    5279    4944    6686    9042   10779
River Rch & RM=LAKE CREEK,Reach-1         ,99302
    3247    4765    6117    5743    7766   10503   12578
River Rch & RM=LAKE CREEK,Reach-1         ,96329
    3530    5186    6662    6256    8460   11441   13708
River Rch & RM=LAKE CREEK,Reach-1         ,91288
    3545    5195    6661    6244    8444   11420   13632
River Rch & RM=LAKE CREEK,Reach-1         ,87840
    3654    5359    6875    6446    8718   11790   14083
River Rch & RM=LAKE CREEK,Reach-1         ,85353
    3654    5359    6875    6446    8718   11790   14083
River Rch & RM=LAKE CREEK,Reach-1         ,84492
    3688    5390    6898    6451    8724   11799   14019
River Rch & RM=LAKE CREEK,Reach-1         ,75974
    4439    6526    8385    7869   10642   14392   17219
River Rch & RM=LAKE CREEK,Reach-1         ,75448
    4439    6526    8385    7869   10642   14392   17219
River Rch & RM=LAKE CREEK,Reach-1         ,72773
    4475    6571    8437    7912   10700   14471   17287
River Rch & RM=LAKE CREEK,Reach-1         ,67712
    4489    6590    8460    7932   10727   14507   17321
River Rch & RM=LAKE CREEK,Reach-1         ,67004
    4655    6832    8768    8217   11112   15028   17928
River Rch & RM=LAKE CREEK,Reach-1         ,62660
    4674    6850    8782    8220   11117   15035   17894
River Rch & RM=LAKE CREEK,Reach-1         ,56111
    4706    6881    8807    8229   11128   15050   17847
River Rch & RM=LAKE CREEK,Reach-1         ,44420
    4725    6906    8839    8257   11167   15102   17903
River Rch & RM=LAKE CREEK,Reach-1         ,41933
    4955    7229    9238    8615   11651   15756   18613
River Rch & RM=LAKE CREEK,Reach-1         ,26034
    7724   11377   14639   13735   18575   25121   30022
Boundary for River Rch & Prof#=LAKE CREEK,Reach-1         , 1
Up Type= 0
Dn Type= 3
Dn Slope=0.002
Boundary for River Rch & Prof#=LAKE CREEK,Reach-1         , 2
Up Type= 0
Dn Type= 3
Dn Slope=0.002
Boundary for River Rch & Prof#=LAKE CREEK,Reach-1         , 3
Up Type= 0
Dn Type= 3
Dn Slope=0.002
Boundary for River Rch & Prof#=LAKE CREEK,Reach-1         , 4
Up Type= 0
Dn Type= 3
Dn Slope=0.002
Boundary for River Rch & Prof#=LAKE CREEK,Reach-1         , 5
Up Type= 0
Dn Type= 3
Dn Slope=0.002
Boundary for River Rch & Prof#=LAKE CREEK,Reach-1         , 6
Up Type= 0
Dn Type= 3
Dn Slope=0.002
Boundary for River Rch & Prof#=LAKE CREEK,Reach-1         , 7
Up Type= 0
Dn Type= 3
Dn Slope=0.002
DSS Import GetInterval= 0
DSS Import GetPeak= 0
DSS Import FillOption= 0

--- LAKE CREEK.g01 (geometry) ---

Geom Title=Existing Conditions
Program Version=4.10

River Reach=LAKE CREEK      ,Reach-1
Reach XY= 30
        3723665.       10678683.        3721710.       10678385.
      3720229.25       10675127.      3720180.75       10661919.
        3720866.       10660932.       3718036.5       10660828.
        3715760.       10659225.      3715366.75       10650456.
      3712196.25       10647897.       3712145.5       10646236.
        3708067.       10646565.      3705306.25       10643087.
      3703370.25       10642961.      3701765.25       10641013.
       3701244.5       10638197.        3699322.       10635729.
      3700580.25       10633118.      3698729.25       10627612.
      3700018.75       10622120.      3697857.25       10620957.
       3698188.5       10618423.      3696714.75       10618968.
       3695589.5       10618152.      3694730.25       10619153.
      3693383.75       10617639.      3693894.75       10615862.
       3697399.5       10612583.      3697349.61     10610860.19
      3700499.61     10607710.19      3709749.61     10608960.19

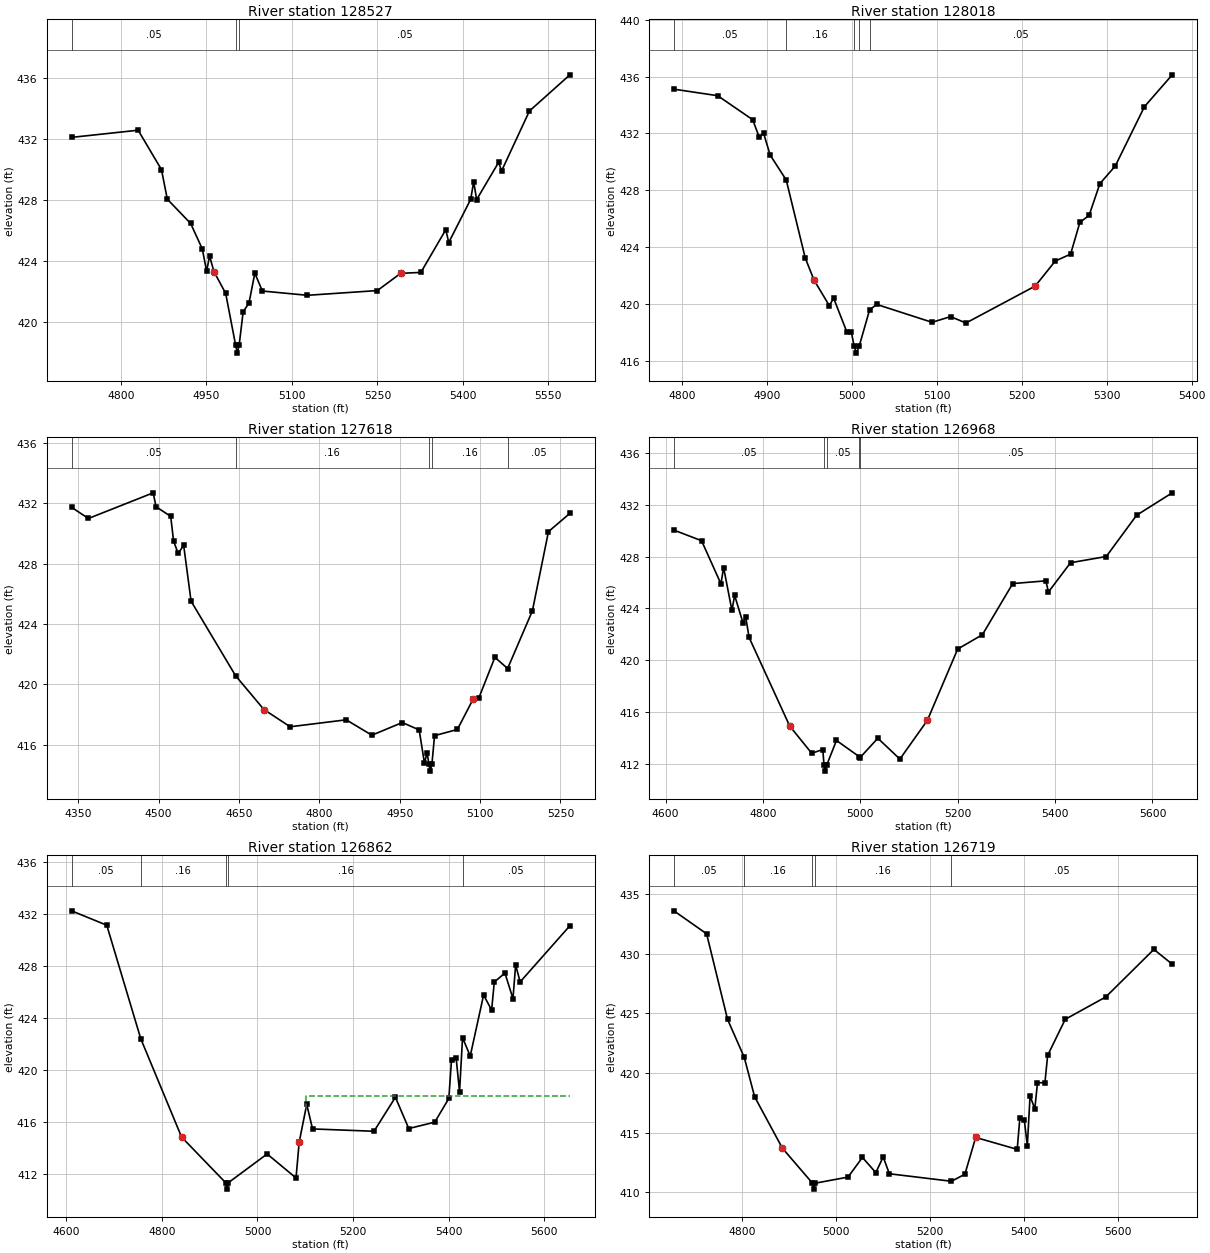
Type RM Length L Ch R = 1 ,128527  ,509,509,509
BEGIN DESCRIPTION:
LAKE CREEK 198.0
END DESCRIPTION:
XS GIS Cut Line= 2
      3723555.95     10678206.11      3723368.45     10679060.28
#Sta/Elev= 30
  4713.3  432.09  4830.1  432.56    4871  429.98  4881.3  428.04  4922.2  426.45
  4942.7  424.78  4950.3  423.31  4955.4  424.32  4963.2  423.29  4983.7  421.87
  5001.3  418.45  5004.1  417.95  5007.3  418.45  5014.4  420.66  5024.6  421.23
  5034.9  423.19  5048.1  422.02    5127  421.74  5249.9  422.05  5290.8  423.18
  5326.3  423.24    5370  426.04  5375.2   425.2  5413.7  428.03    5419  429.19
  5424.1  428.01  5462.8  430.46  5467.9  429.89  5516.8  433.82  5587.8  436.19
#Mann= 3 ,-1 , 0
  4713.3     .05       0  5001.3     .03       0  5007.3     .05       0
Bank Sta=4963.2,5290.8
XS Rating Curve= 0 ,0
Exp/Cntr=0.3,0.1

Type RM Length L Ch R = 1 ,128018  ,400,400,400
BEGIN DESCRIPTION:
LAKE CREEK 197.0
END DESCRIPTION:
XS GIS Cut Line= 3
       3723049.6     10678510.16      3723099.61     10678710.19
      3723249.62     10679060.21
#Sta/Elev= 30
  4790.1  435.12  4841.7  434.66  4882.9  432.97  4890.6  431.74  4895.8  432.01
  4903.5  430.48  4922.4  428.73  4944.8  423.24  4955.1  421.69  4973.1  419.89
  4978.3   420.4  4993.7  418.05    4999  418.05  5002.4  417.04  5005.1  416.54
  5008.4  417.04  5020.6  419.58  5028.9  419.97  5094.2  418.71    5116  419.11
  5134.1  418.66  5215.7  421.26  5239.3  423.02  5257.4  423.51  5268.3  425.74
  5279.2  426.24  5291.9  428.47    5310  429.71  5344.4  433.89  5377.1  436.13
#Mann= 5 ,-1 , 0
  4790.1     .05       0  4922.4     .16       0  5002.4     .07       0
  5008.4     .16       0  5020.6     .05       0
Bank Sta=4955.1,5215.7
XS Rating Curve= 0 ,0
Exp/Cntr=0.3,0.1

Type RM Length L Ch R = 1 ,127618  ,650,650,650
BEGIN DESCRIPTION:
LAKE CREEK 196.0
END DESCRIPTION:
XS GIS Cut Line= 3
       3723049.6     10678360.22      3722849.61     10679010.19
      3722849.61     10679260.15
#Sta/Elev= 30
  4337.7  431.73  4369.1  430.99    4490  432.69  4495.3  431.77  4522.7  431.13
    4528  429.51  4536.5  428.67  4546.9  429.21  4560.7  425.51  4643.8  420.57
  4696.7  418.33  4745.7  417.19  4850.3  417.65  4898.1  416.63    4955  417.47
  4986.4  416.98  4996.2   414.8  5001.4  415.47  5004.3  414.75    5007  414.25
  5010.3  414.75  5015.1   416.6  5057.7  417.01  5087.7  419.06  5097.7  419.09
  5127.7  421.79  5151.5  421.05  5197.7  424.87  5227.7  430.12  5267.7  431.33
#Mann= 5 ,-1 , 0
  4337.7     .05       0  4643.8     .16       0  5004.3     .07       0
  5010.3     .16       0  5151.5     .05       0
Bank Sta=4696.7,5087.7
XS Rating Curve= 0 ,0
Exp/Cntr=0.3,0.1

Type RM Length L Ch R = 1 ,126968  ,106,106,106
BEGIN DESCRIPTION:
Mapping XS b1f8ac39
END DESCRIPTION:
XS GIS Cut Line= 2
      3722557.88     10678351.09      3722114.03     10679273.46
#Sta/Elev= 30
    4617  430.04  4673.8  429.22  4713.6  425.89  4719.1  427.15  4736.2  423.83
  4741.7     425  4758.8  422.89  4764.4  423.35  4771.4  421.75  4854.9   414.9
  4900.1   412.8  4922.8  413.09  4925.3  411.92  4928.1  411.42  4931.3  411.92
  4950.9  413.79  4997.6  412.54    4999  412.45  5035.9  413.96  5081.2  412.35
  5137.6  415.34  5199.9  420.85  5250.7  421.96    5313  425.91  5380.9  426.12
  5386.4  425.26  5431.7  427.52  5505.1     428  5567.5  431.19  5640.6  432.92
#Mann= 5 ,-1 , 0
    4617     .05       0  4925.3     .03       0  4931.3     .05       0
  4997.6     .16       0    4999     .05       0
Bank Sta=4854.9,5137.6
XS Rating Curve= 0 ,0
Exp/Cntr=0.3,0.1

Type RM Length L Ch R = 1 ,126862  ,143,143,143
BEGIN DESCRIPTION:
LAKE CREEK 195.0
END DESCRIPTION:
XS GIS Cut Line= 2
      3722467.58     10678309.47       3722002.3      10679243.5
#Sta/Elev= 30
  4610.7  432.26  4684.4  431.15  4755.5  422.41  4841.1  414.82  4933.2  411.31
    4936  410.81  4939.2  411.31  5020.2  413.52  5080.7  411.67  5087.3  414.43
  5103.1  417.34  5115.3  415.45    5244  415.27  5288.8  417.89  5316.8  415.48
  5371.2  415.97  5400.7   417.8  5406.3  420.79  5415.9  420.95  5423.1  418.32
  5429.4  422.48  5445.5  421.07  5473.5  425.77  5490.3  424.61  5495.9  426.78
  5518.2  427.46    5535  425.49  5540.6  428.09    5550  426.78  5654.2  431.11
#Mann= 5 ,-1 , 0
  4610.7     .05       0  4755.5     .16       0  4933.2     .07       0
  4939.2     .16       0  5429.4     .05       0
#XS Ineff= 2 , 0
                         5101.22             418
Permanent Ineff=
       F       F
Bank Sta=4841.1,5087.3
XS Rating Curve= 0 ,0
Exp/Cntr=0.3,0.1

Type RM Length L Ch R = 1 ,126719  ,99,99,99
BEGIN DESCRIPTION:
LAKE CREEK 194.0
END DESCRIPTION:
XS GIS Cut Line= 2
      3722366.91      10678260.8      3721842.58     10679184.46
#Sta/Elev= 30
  4653.9  433.62  4723.6  431.69  4768.2  424.51  4803.8  421.32    4826     418
  4885.1  413.69  4949.2  410.75  4951.9  410.25  4955.2  410.75    5025  411.26
  5055.7  412.91  5084.2  411.64    5100  412.95  5113.1  411.54  5245.4  410.91
  5274.1   411.5  5297.1  414.59  5385.6  413.59  5391.3  416.25  5400.6  416.09
  5407.2   413.9    5413  418.08  5423.1  416.98  5428.8  419.17  5444.7   419.2
  5450.5  421.48    5488  424.51  5574.5  426.39  5676.9  430.38    5716  429.14
#Mann= 5 ,-1 , 0
  4653.9     .05       0  4803.8     .16       0  4949.2     .07       0
  4955.2     .16       0  5245.4     .05       0
Bank Sta=4885.1,5297.1
XS Rating Curve= 0 ,0
Exp/Cntr=0.3,0.1

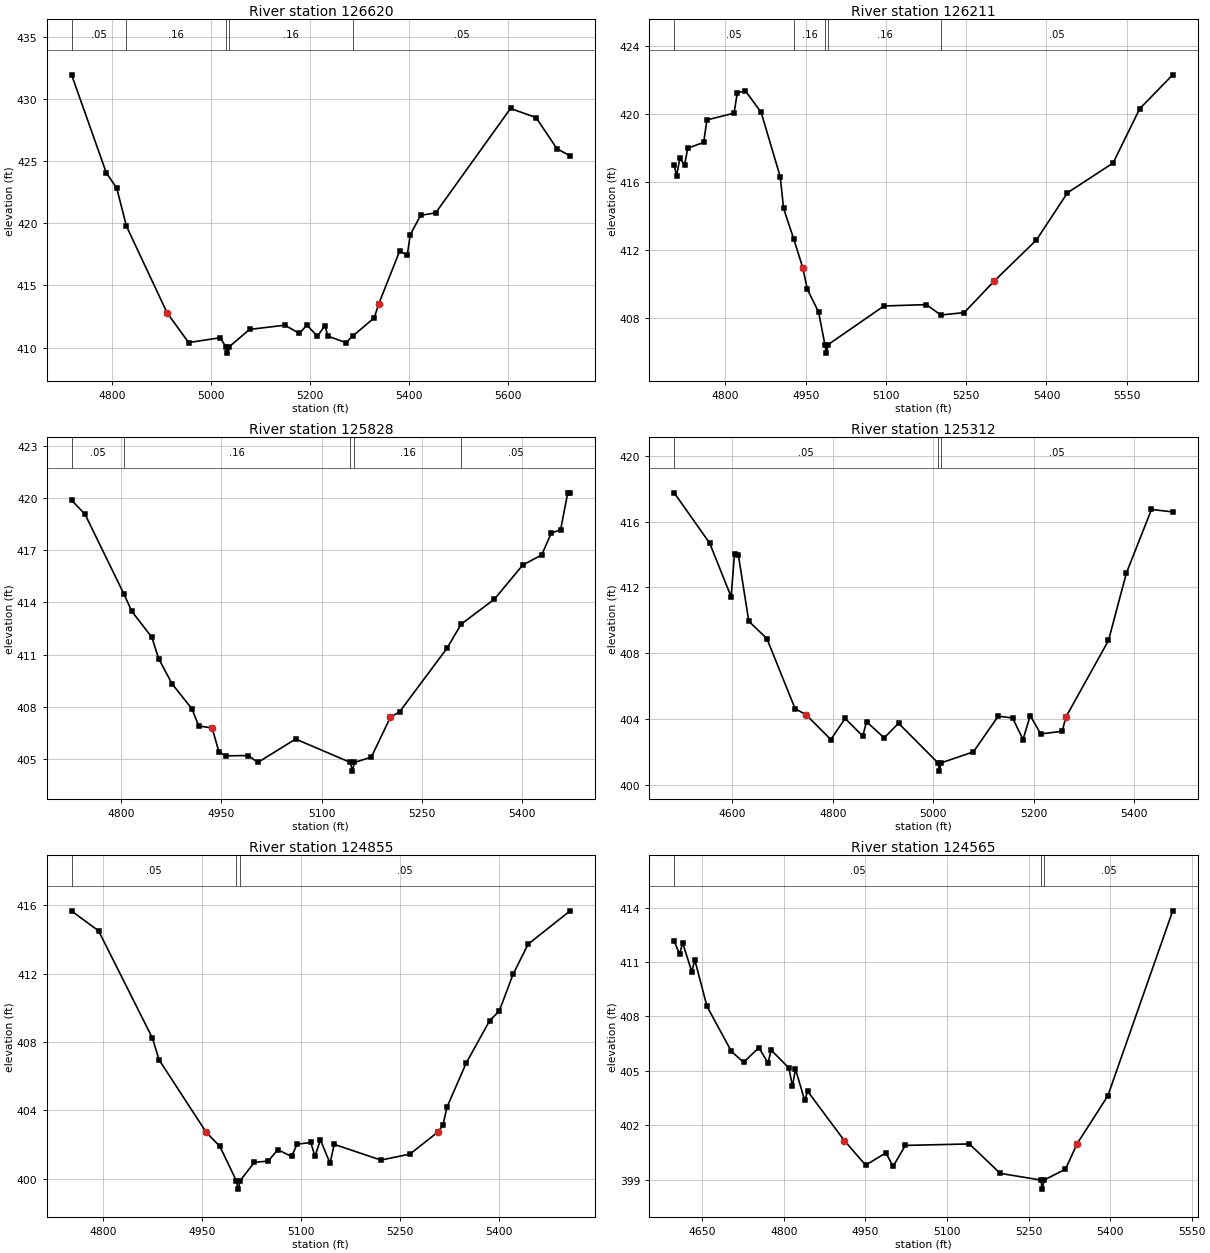
Type RM Length L Ch R = 1 ,126620  ,409,409,409
BEGIN DESCRIPTION:
Mapping XS 0e4f0aa5
END DESCRIPTION:
XS GIS Cut Line= 2
      3722283.55     10678267.79      3721738.44     10679114.97
#Sta/Elev= 30
  4718.2  431.97  4788.3  424.08  4809.4  422.84  4829.1  419.77  4911.3  412.79
  4954.7   410.4  5018.3  410.79  5030.3  410.05    5033  409.55  5036.3  410.05
  5077.8  411.46  5149.1   411.8  5178.6  411.14  5193.7  411.81  5214.9  410.91
  5230.1  411.77    5236  410.92  5272.3   410.4  5286.8  410.94  5329.8   412.4
    5339  413.53  5381.3  417.79  5396.5  417.43  5402.4  419.08  5423.5  420.65
  5453.9  420.85  5605.1  429.26  5656.6  428.53  5698.9  426.02  5725.6  425.44
#Mann= 5 ,-1 , 0
  4718.2     .05       0  4829.1     .16       0  5030.3     .07       0
  5036.3     .16       0  5286.8     .05       0
Bank Sta=4911.3,5339
XS Rating Curve= 0 ,0
Exp/Cntr=0.3,0.1

Type RM Length L Ch R = 1 ,126211  ,383,383,383
BEGIN DESCRIPTION:
LAKE CREEK 193.0
END DESCRIPTION:
XS GIS Cut Line= 3
      3721938.77      10678173.8      3721691.37     10678529.72
      3721387.52     10678924.72
#Sta/Elev= 30
  4704.2     417  4708.7  416.37  4714.8  417.39  4723.5     417  4729.6  417.99
  4759.3  418.33  4765.4  419.65  4816.1  420.05  4822.1  421.23    4837  421.37
  4866.7   420.1  4902.5   416.3  4908.6  414.46  4927.9  412.63  4944.4  410.98
  4953.1   409.7  4974.1  408.36  4985.9  406.45  4988.7  405.95  4991.9  406.45
  5096.3  408.72  5175.7   408.8  5202.3  408.19  5246.3  408.33  5302.5  410.19
  5381.3   412.6  5439.3  415.37  5524.5  417.12  5574.3  420.31    5636   422.3
#Mann= 5 ,-1 , 0
  4704.2     .05       0  4927.9     .16       0  4985.9     .07       0
  4991.9     .16       0  5202.3     .05       0
Bank Sta=4944.4,5302.5
XS Rating Curve= 0 ,0
Exp/Cntr=0.3,0.1

Type RM Length L Ch R = 1 ,125828  ,516,516,516
BEGIN DESCRIPTION:
LAKE CREEK 192.0
END DESCRIPTION:
XS GIS Cut Line= 3
      3721799.59     10678110.19      3721549.61     10678110.19
      3721199.58     10678460.22
#Sta/Elev= 30
  4726.5  419.89  4746.5  419.09  4804.4  414.51  4816.5  413.49  4846.5  411.99
  4856.5  410.77  4876.5  409.32  4906.5  407.86  4916.5  406.88  4936.5  406.77
  4946.5  405.41  4956.5  405.16  4990.6  405.18  5004.8  404.78  5061.3  406.13
  5143.2  404.78  5145.9  404.28  5149.2  404.78  5174.5  405.09  5202.8  407.38
  5216.9  407.71  5287.6  411.37  5308.6  412.75  5358.3  414.19  5400.7  416.16
    5429  416.74  5443.2  417.99  5457.3   418.2  5467.9  420.32  5471.5  420.32
#Mann= 5 ,-1 , 0
  4726.5     .05       0  4804.4     .16       0  5143.2     .07       0
  5149.2     .16       0  5308.6     .05       0
Bank Sta=4936.5,5202.8
XS Rating Curve= 0 ,0
Exp/Cntr=0.3,0.1

Type RM Length L Ch R = 1 ,125312  ,457,457,457
BEGIN DESCRIPTION:
LAKE CREEK 191.0
END DESCRIPTION:
XS GIS Cut Line= 3
       3721699.6     10677310.19      3721349.61     10677710.19
      3720999.59      10678010.2
#Sta/Elev= 30
  4484.2  417.75  4554.9  414.69  4597.6  411.43  4604.3  414.06  4611.8     414
  4632.7  409.95  4668.8  408.89  4724.8  404.64  4746.6  404.27    4796  402.76
  4824.5  404.04  4859.6  402.97  4867.2  403.84  4902.3  402.86  4930.8  403.75
  5009.4  401.34  5012.1  400.84  5015.4  401.34  5079.9  402.01  5129.3  404.18
  5157.8  404.07  5178.7  402.76    5193  404.22  5213.8   403.1  5256.6  403.26
  5264.3  404.14  5348.8  408.78  5384.5  412.88  5434.4  416.74  5476.7  416.59
#Mann= 3 ,-1 , 0
  4484.2     .05       0  5009.4     .03       0  5015.4     .05       0
Bank Sta=4746.6,5264.3
XS Rating Curve= 0 ,0
Exp/Cntr=0.3,0.1

Type RM Length L Ch R = 1 ,124855  ,290,290,290
BEGIN DESCRIPTION:
LAKE CREEK 190.0
END DESCRIPTION:
XS GIS Cut Line= 3
      3721499.62     10677260.19      3721249.61     10677310.19
      3720949.58     10677710.22
#Sta/Elev= 30
  4752.2  415.67    4793  414.51  4874.6  408.23  4884.8  406.95  4956.2  402.71
  4976.6   401.9  5001.6  399.89  5004.4  399.39  5007.6  399.89    5029  400.96
  5049.9  401.03  5064.5   401.7  5085.3   401.3  5093.6  402.02  5114.5  402.12
  5120.7  401.31    5129  402.27  5143.6  400.91  5149.9  402.01  5220.7  401.09
  5264.5  401.44  5307.2  402.74  5314.5  403.12  5320.7  404.19  5349.9  406.78
  5385.3  409.25  5399.9  409.82  5420.7  411.96  5443.6  413.73  5507.2  415.68
#Mann= 3 ,-1 , 0
  4752.2     .05       0  5001.6     .03       0  5007.6     .05       0
Bank Sta=4956.2,5307.2
XS Rating Curve= 0 ,0
Exp/Cntr=0.3,0.1

Type RM Length L Ch R = 1 ,124565  ,232,232,232
BEGIN DESCRIPTION:
Mapping XS 4795c1a8
END DESCRIPTION:
XS GIS Cut Line= 3
      3721498.67     10676888.41      3721055.95     10677107.17
      3720754.26     10677403.65
#Sta/Elev= 30
  4598.4  412.16  4608.3  411.42  4613.9  412.06  4630.8  410.46  4636.3  411.11
  4658.8  408.55  4703.7  406.07  4726.1  405.47  4754.1  406.28    4771  405.43
  4776.6  406.15  4809.3  405.16  4815.9  404.15  4821.4   405.1  4838.3  403.38
  4843.9  403.87  4911.2  401.16  4950.5   399.8  4987.7  400.48    5001  399.73
  5023.4  400.89  5141.3  400.97  5197.9  399.35  5272.6  398.98  5275.4  398.48
  5278.6  398.98    5318  399.58  5339.3  400.98  5395.8  403.62  5515.2  413.82
#Mann= 3 ,-1 , 0
  4598.4     .05       0  5272.6     .03       0  5278.6     .05       0
Bank Sta=4911.2,5339.3
XS Rating Curve= 0 ,0
Exp/Cntr=0.3,0.1

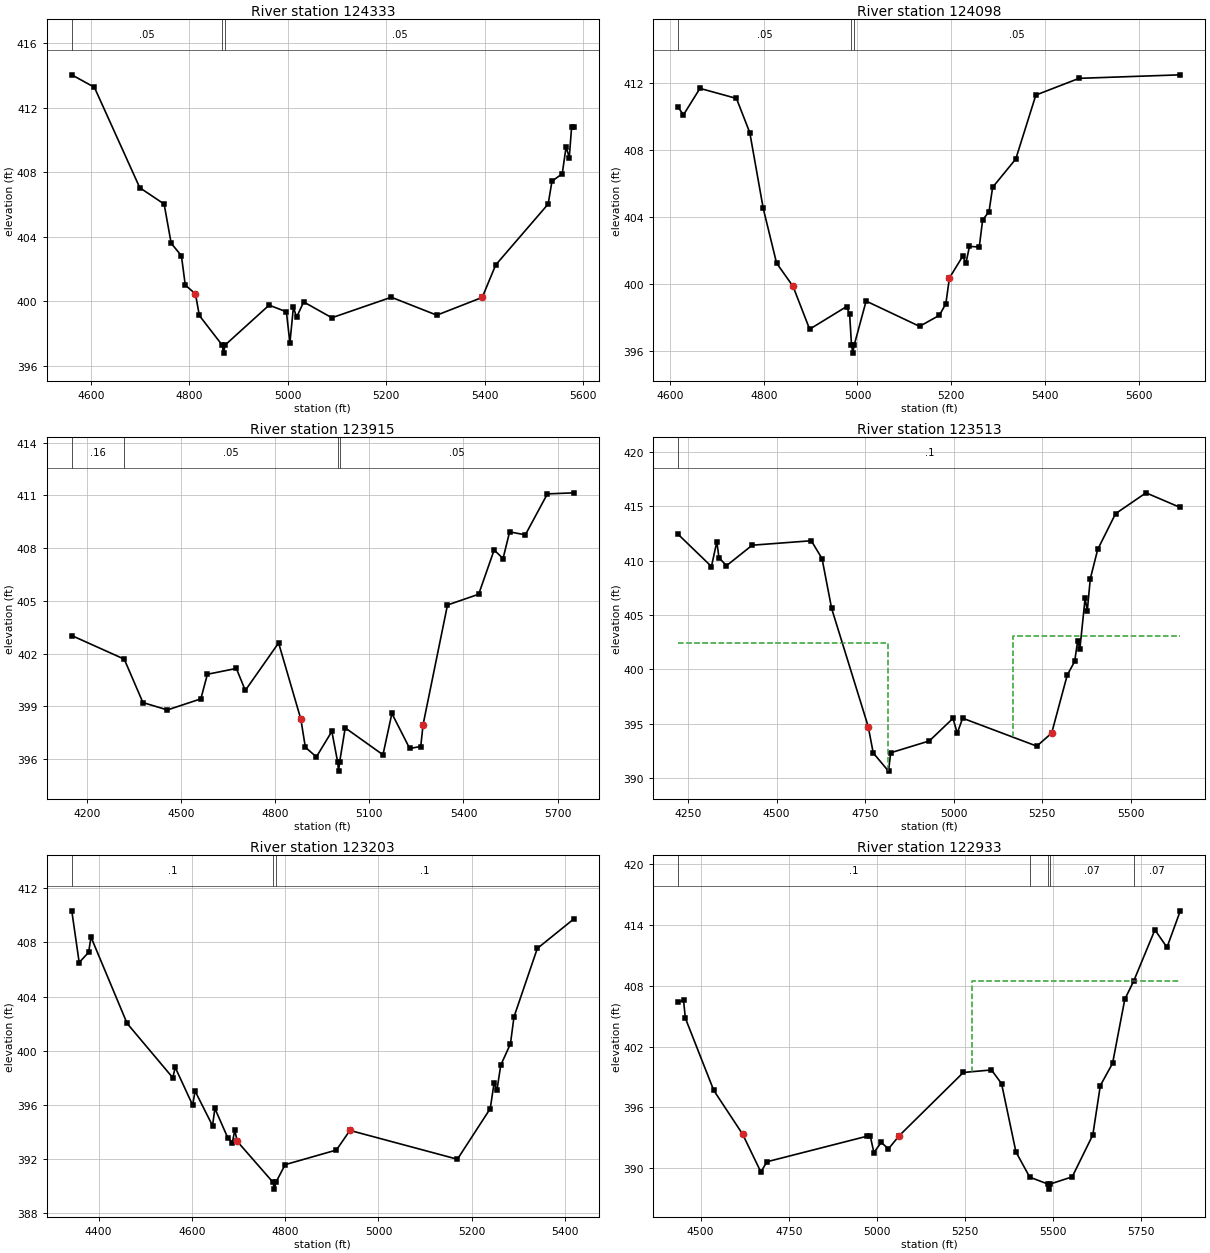
Type RM Length L Ch R = 1 ,124333  ,235,235,235
BEGIN DESCRIPTION:
LAKE CREEK 189.0
END DESCRIPTION:
XS GIS Cut Line= 2
      3721509.04     10676555.11      3720727.79     10677211.36
#Sta/Elev= 30
  4561.2  414.03  4607.1  413.26  4699.4  407.04  4748.9  406.03  4763.2   403.6
    4784  402.83  4791.8  401.02  4812.6  400.46  4820.4  399.13  4866.8   397.3
  4869.6   396.8  4872.8   397.3  4962.2  399.77  4997.3  399.36  5004.5  397.44
  5011.6  399.64  5018.1  399.02  5032.4  399.97  5089.7  398.99  5210.6  400.26
    5303  399.15  5395.3  400.25  5422.7  402.26  5529.3  406.03  5537.1  407.45
  5557.9   407.9  5565.7  409.56  5572.2  408.91    5577  410.81  5581.5  410.81
#Mann= 3 ,-1 , 0
  4561.2     .05       0  4866.8     .04       0  4872.8     .05       0
Bank Sta=4812.6,5395.3
XS Rating Curve= 0 ,0
Exp/Cntr=0.3,0.1

Type RM Length L Ch R = 1 ,124098  ,183,183,183
BEGIN DESCRIPTION:
LAKE CREEK 188.0
END DESCRIPTION:
XS GIS Cut Line= 2
      3721462.21     10676357.15      3720649.71     10677055.07
#Sta/Elev= 30
  4617.6  410.53  4628.8  410.09  4663.9  411.67  4741.8  411.07  4770.3  409.02
  4798.9   404.5  4827.4  401.23  4862.5  399.84  4897.9  397.28  4976.6  398.63
  4983.2   398.2  4987.2  396.35  4989.9  395.85  4993.2  396.35  5018.4  398.96
  5132.5  397.45  5174.7  398.11  5188.5   398.8  5196.1  400.34  5224.7  401.65
  5231.3  401.22  5238.9  402.23  5259.8  402.19    5267  403.81  5280.6   404.3
  5288.3  405.76  5337.7  407.45  5380.5  411.27  5472.7  412.27  5688.7  412.48
#Mann= 3 ,-1 , 0
  4617.6     .05       0  4987.2     .03       0  4993.2     .05       0
Bank Sta=4862.5,5196.1
XS Rating Curve= 0 ,0
Exp/Cntr=0.3,0.1

Type RM Length L Ch R = 1 ,123915  ,402,402,402
BEGIN DESCRIPTION:
Mapping XS a3571499
END DESCRIPTION:
XS GIS Cut Line= 3
      3721756.46     10675877.82       3721342.4     10676226.96
      3720555.97     10676935.27
#Sta/Elev= 30
  4151.7  403.02  4318.9  401.68  4378.4  399.21  4456.4  398.79    4563  399.42
  4583.9  400.82  4676.2  401.15  4704.7   399.9  4810.8   402.6  4881.8  398.26
    4896  396.67  4931.2  396.12  4980.5  397.57  4999.2  395.81  5001.9  395.31
  5005.2  395.81  5023.1  397.77  5143.4  396.24  5171.8  398.59  5228.6   396.6
  5263.8  396.71  5271.2  397.95    5349  404.76  5448.4  405.37  5497.7  407.89
  5526.1   407.4    5547  408.92  5597.1  408.75  5667.4  411.08  5751.7  411.14
#Mann= 4 ,-1 , 0
  4151.7     .16       0  4318.9     .05       0  4999.2     .03       0
  5005.2     .05       0
Bank Sta=4881.8,5271.2
XS Rating Curve= 0 ,0
Exp/Cntr=0.3,0.1

Type RM Length L Ch R = 1 ,123513  ,310,310,310
BEGIN DESCRIPTION:
LAKE CREEK 187.0
END DESCRIPTION:
XS GIS Cut Line= 3
      3721574.17     10675665.14        3720825.     10676142.16
      3720394.13     10676450.36
#Sta/Elev= 30
  4222.2  412.42    4316  409.47  4331.2  411.75  4337.1  410.29  4358.3  409.54
  4431.1  411.43  4597.9  411.84  4628.3   410.2  4655.4  405.61  4758.7  394.74
  4772.9  392.31    4816  390.64  4822.2  392.33  4931.4  393.42  4998.2   395.5
  5010.1  394.13  5025.4  395.51  5234.8  392.94  5276.8  394.14  5320.8  399.48
  5341.7  400.73  5350.3  402.64  5356.5   401.9  5371.2  406.53  5377.4  405.41
  5385.9  408.34  5406.8  411.04  5457.2  414.33  5543.2  416.25  5640.1   414.9
#Mann= 1 ,-1 , 0
  4222.2      .1       0
#XS Ineff= 2 , 0
         4815.53  402.43 5167.26          403.08
Permanent Ineff=
       F       F
Bank Sta=4758.7,5276.8
XS Rating Curve= 0 ,0
Exp/Cntr=0.3,0.1

Type RM Length L Ch R = 1 ,123203  ,270,270,270
BEGIN DESCRIPTION:
LAKE CREEK 186.0
END DESCRIPTION:
XS GIS Cut Line= 3
      3721425.08      10675625.9      3720844.33     10675761.32
      3720469.36     10676060.77
#Sta/Elev= 30
  4342.6  410.34  4358.5  406.52  4378.7  407.27  4383.8   408.4  4461.2  402.02
  4559.2     398  4564.3  398.77  4601.7  395.98  4606.9  397.02  4644.3  394.46
  4649.4  395.73  4676.8  393.58  4686.8   393.2    4692  394.13  4697.3   393.3
  4774.1  390.27  4776.8  389.77  4780.1  390.27    4800  391.58  4909.9  392.66
  4938.8  394.11  5169.2  391.98  5239.6  395.72  5247.7  397.59  5254.1  397.11
  5262.1  398.93  5282.9  400.51  5290.5   402.5  5340.5  407.56  5418.8  409.74
#Mann= 3 ,-1 , 0
  4342.6      .1       0  4774.1      .1       0  4780.1      .1       0
Bank Sta=4697.3,4938.8
XS Rating Curve= 0 ,0
Exp/Cntr=0.3,0.1

Type RM Length L Ch R = 1 ,122933  ,488,488,488
BEGIN DESCRIPTION:
Mapping XS 4338149e
END DESCRIPTION:
XS GIS Cut Line= 3
      3721206.28      10675430.6      3720445.89     10675631.11
      3719830.04      10675464.8
#Sta/Elev= 30
  4436.4  406.39  4451.4  406.58  4456.6  404.81  4537.2  397.68  4619.1  393.36
  4670.8  389.63    4688  390.64  4970.7  393.15  4981.1  393.18  4991.4  391.55
  5012.1  392.55  5032.8  391.92  5063.8  393.23  5245.2  399.45    5325   399.7
  5353.6  398.35  5394.4  391.61  5433.6  389.12  5485.2  388.44    5488  387.94
  5491.2  388.44    5554  389.15  5612.5  393.29  5633.8  398.16  5668.5  400.35
  5703.2  406.67  5728.1  408.44  5788.6  413.52  5822.9   411.8  5860.7   415.4
#Mann= 5 ,-1 , 0
  4436.4      .1       0  5433.6     .07       0  5485.2     .07       0
  5491.2     .07       0  5728.1     .07       0
#XS Ineff= 2 , 0
                         5269.77          408.49
Permanent Ineff=
       F       F
Bank Sta=4619.1,5063.8
XS Rating Curve= 0 ,0
Exp/Cntr=0.3,0.1

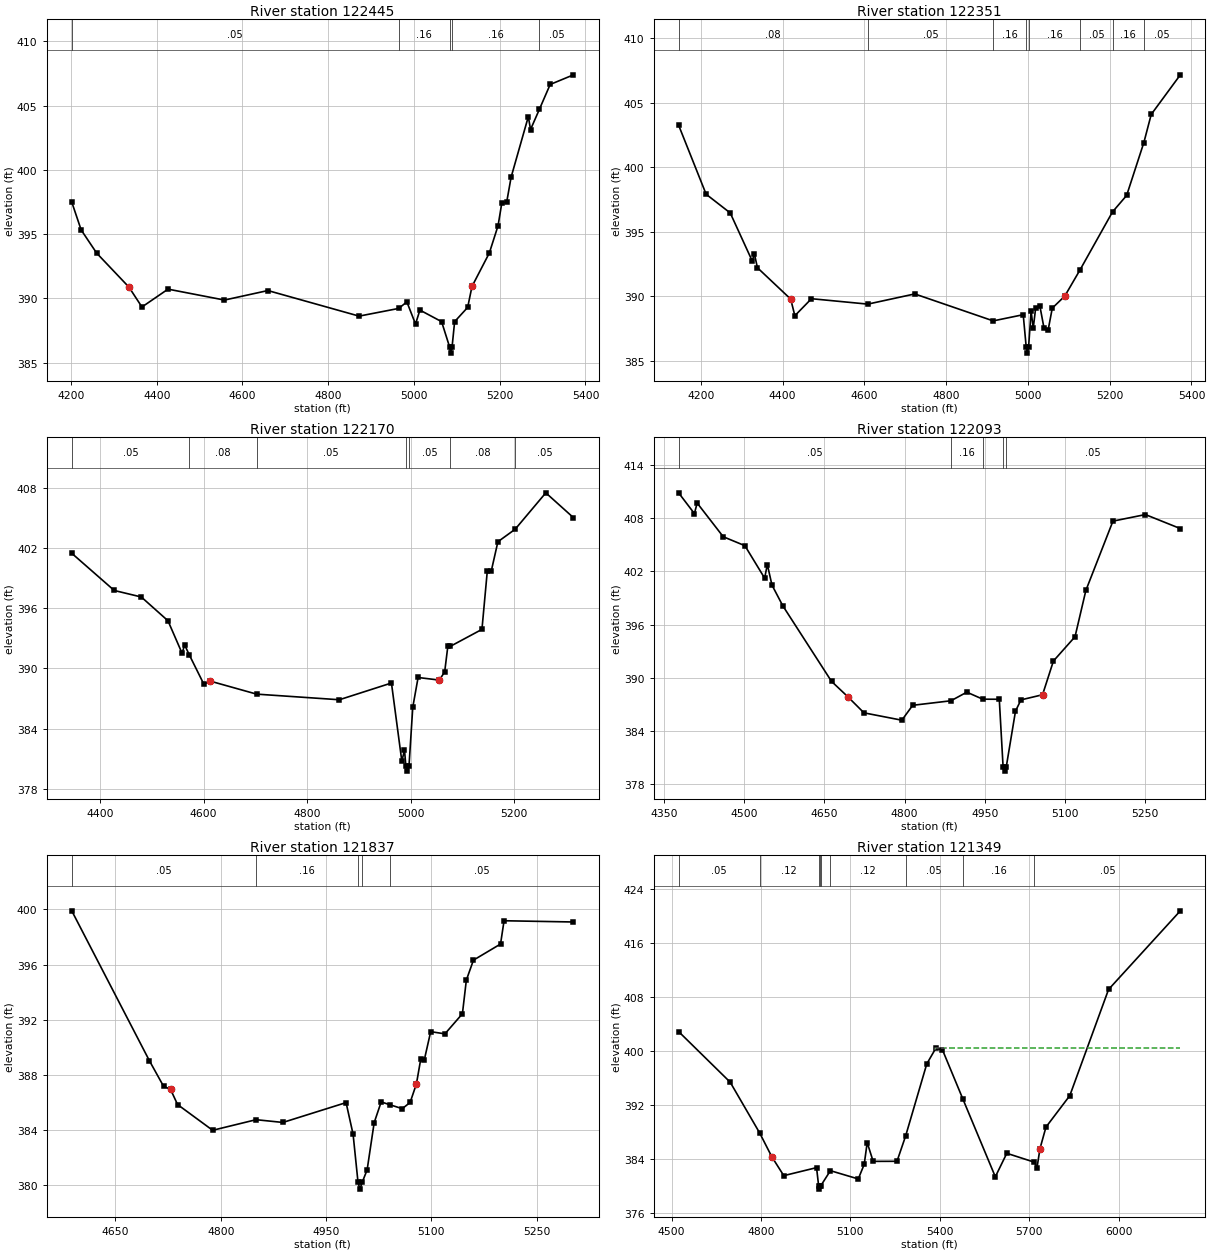
Type RM Length L Ch R = 1 ,122445  ,94,94,94
BEGIN DESCRIPTION:
Mapping XS 85266ba2
END DESCRIPTION:
XS GIS Cut Line= 3
      3721071.24     10675414.53      3720235.94      10675280.6
       3719915.9     10675229.29
#Sta/Elev= 30
  4201.9  397.49  4223.8  395.32  4260.1  393.51  4335.2  390.87  4365.6  389.32
  4426.4  390.71    4558  389.86  4659.3   390.6    4872  388.61  4964.5  389.21
  4983.4  389.72  5003.6  387.99  5013.8  389.08  5064.4  388.18  5082.9  386.23
  5085.6  385.73  5088.9  386.23  5094.8  388.18  5125.2  389.29  5135.3  390.92
  5175.8  393.53  5196.1  395.65  5204.8  397.41  5216.3   397.5  5226.5  399.42
  5266.7  404.14  5271.8  403.13  5292.4   404.7  5317.6  406.64    5372  407.39
#Mann= 5 ,-1 , 0
  4201.9     .05       0  4964.5     .16       0  5082.9     .07       0
  5088.9     .16       0  5292.4     .05       0
Bank Sta=4335.2,5135.3
XS Rating Curve= 0 ,0
Exp/Cntr=0.3,0.1

Type RM Length L Ch R = 1 ,122351  ,181,181,181
BEGIN DESCRIPTION:
LAKE CREEK 185.0
END DESCRIPTION:
XS GIS Cut Line= 3
      3721099.55     10675347.26      3720091.72     10675167.57
      3719888.56     10675154.55
#Sta/Elev= 30
  4145.5  403.27  4212.9  397.91  4271.8  396.46  4325.7  392.73  4330.8  393.29
  4338.4  392.21  4419.7  389.78  4429.9  388.49  4470.5  389.81  4608.3  389.39
  4723.2  390.18  4915.1  388.09  4988.5  388.57  4995.7  386.09  4998.4  385.59
  5001.7  386.09  5007.8  388.87  5012.9   387.5    5019  389.11  5029.2  389.25
  5039.3  387.54  5049.5  387.39  5059.6  389.08  5090.1  390.01  5127.9  392.07
  5206.9  396.54  5241.5  397.82  5283.6  401.92  5301.6   404.1  5372.8  407.17
#Mann= 8 ,-1 , 0
  4145.5     .08       0  4608.3     .05       0  4915.1     .16       0
  4995.7     .07       0  5001.7     .16       0  5127.9     .05       0
  5206.9     .16       0  5283.6     .05       0
Bank Sta=4419.7,5090.1
XS Rating Curve= 0 ,0
Exp/Cntr=0.3,0.1

Type RM Length L Ch R = 1 ,122170  ,77,77,77
BEGIN DESCRIPTION:
LAKE CREEK 184.0
END DESCRIPTION:
XS GIS Cut Line= 2
      3720870.33     10675175.37      3719927.59     10674948.71
#Sta/Elev= 30
  4345.1  401.48  4427.2  397.77  4479.5  397.12    4531  394.75  4558.2  391.52
  4563.4  392.32  4572.2  391.35  4600.2  388.44  4613.2  388.72  4702.4  387.43
  4862.2  386.87  4962.9  388.54    4983  380.73  4988.1  381.86  4990.8  380.25
  4993.5  379.75  4996.8  380.25  5004.1  386.12  5014.4  389.09  5055.5  388.83
  5065.8  389.66    5072  392.26  5076.4  392.19  5137.8  393.89  5148.1  399.69
  5155.9  399.73  5168.6  402.63    5202  403.88  5261.2  407.51  5314.7  405.03
#Mann= 7 ,-1 , 0
  4345.1     .05       0  4572.2     .08       0  4702.4     .05       0
  4990.8     .03       0  4996.8     .05       0  5076.4     .08       0
    5202     .05       0
Bank Sta=4613.2,5055.5
XS Rating Curve= 0 ,0
Exp/Cntr=0.3,0.1

Type RM Length L Ch R = 1 ,122093  ,256,256,256
BEGIN DESCRIPTION:
Mapping XS 834e0135
END DESCRIPTION:
XS GIS Cut Line= 2
      3720852.16     10675039.97      3719925.06     10674896.74
#Sta/Elev= 30
  4377.3  410.86  4406.9  408.52    4412  409.71  4460.8  405.91  4501.3   404.9
  4538.2  401.24  4543.2  402.78  4551.9  400.46  4572.1  398.13  4663.2  389.61
  4693.6  387.88  4723.9  386.06  4794.7  385.23    4815  386.91  4886.5  387.42
  4916.2  388.39    4946   387.6  4976.9  387.59    4984  379.99  4986.8  379.49
    4990  379.99  5007.2  386.25  5017.4  387.52  5057.8   388.1  5078.1   391.9
  5118.5  394.64  5138.8  399.86  5189.4  407.67  5250.1  408.41  5315.4  406.83
#Mann= 5 ,-1 , 0
  4377.3     .05       0  4886.5     .16       0    4946     .05       0
    4984     .03       0    4990     .05       0
Bank Sta=4693.6,5057.8
XS Rating Curve= 0 ,0
Exp/Cntr=0.3,0.1

Type RM Length L Ch R = 1 ,121837  ,488,488,488
BEGIN DESCRIPTION:
LAKE CREEK 183.0
END DESCRIPTION:
XS GIS Cut Line= 3
      3720680.25     10674698.82       3720202.4     10674691.66
      3719969.29     10674732.68
#Sta/Elev= 30
  4587.8   399.9  4698.5  389.01  4718.5  387.17  4728.5  386.94  4738.5  385.84
  4788.5  383.97  4850.3  384.74  4888.5  384.54  4978.5  385.98  4988.5  383.68
  4995.5   380.2  4998.2   379.7  5001.5   380.2  5008.5   381.1  5018.5  384.52
  5028.5  386.03  5040.6  385.83  5058.5  385.54  5069.7  385.99  5078.7  387.34
  5084.9  389.15    5090   389.1    5099  391.13  5119.3  390.97  5144.2  392.43
  5149.8  394.87  5159.9  396.32  5198.5  397.49  5203.5  399.18  5302.4  399.09
#Mann= 5 ,-1 , 0
  4587.8     .05       0  4850.3     .16       0  4995.5     .07       0
  5001.5     .16       0  5040.6     .05       0
Bank Sta=4728.5,5078.7
XS Rating Curve= 0 ,0
Exp/Cntr=0.3,0.1

Type RM Length L Ch R = 1 ,121349  ,460,460,460
BEGIN DESCRIPTION:
LAKE CREEK 182.0
END DESCRIPTION:
XS GIS Cut Line= 3
      3720732.71     10674213.85      3719849.61     10674210.19
      3719048.72     10674192.15
#Sta/Elev= 30
  4523.3  402.91  4696.4   395.4  4795.4  387.86  4836.4  384.31  4876.4  381.52
  4986.4  382.71  4993.4  380.02  4996.2  379.52  4999.4  380.02  5000.9  380.04
  5032.9  382.26  5126.4  381.03  5146.4   383.2  5156.4  386.43  5176.4  383.64
  5256.4  383.65  5285.2  387.38  5356.4  398.11  5386.4  400.41  5408.9  400.21
  5477.8  392.87  5586.5  381.35    5625  384.84  5717.4  383.52  5726.5  382.73
  5736.5  385.55  5756.5  388.73  5836.5   393.4  5966.6  409.16  6207.5  420.83
#Mann= 9 ,-1 , 0
  4523.3     .05       0  4795.4     .12       0  4993.4     .07       0
  4999.4     .12       0  5000.9     .16       0  5032.9     .12       0
  5285.2     .05       0  5477.8     .16       0  5717.4     .05       0
#XS Ineff= 2 , 0
                         5383.74          400.45
Permanent Ineff=
       F       F
Bank Sta=4836.4,5736.5
XS Rating Curve= 0 ,0
Exp/Cntr=0.3,0.1

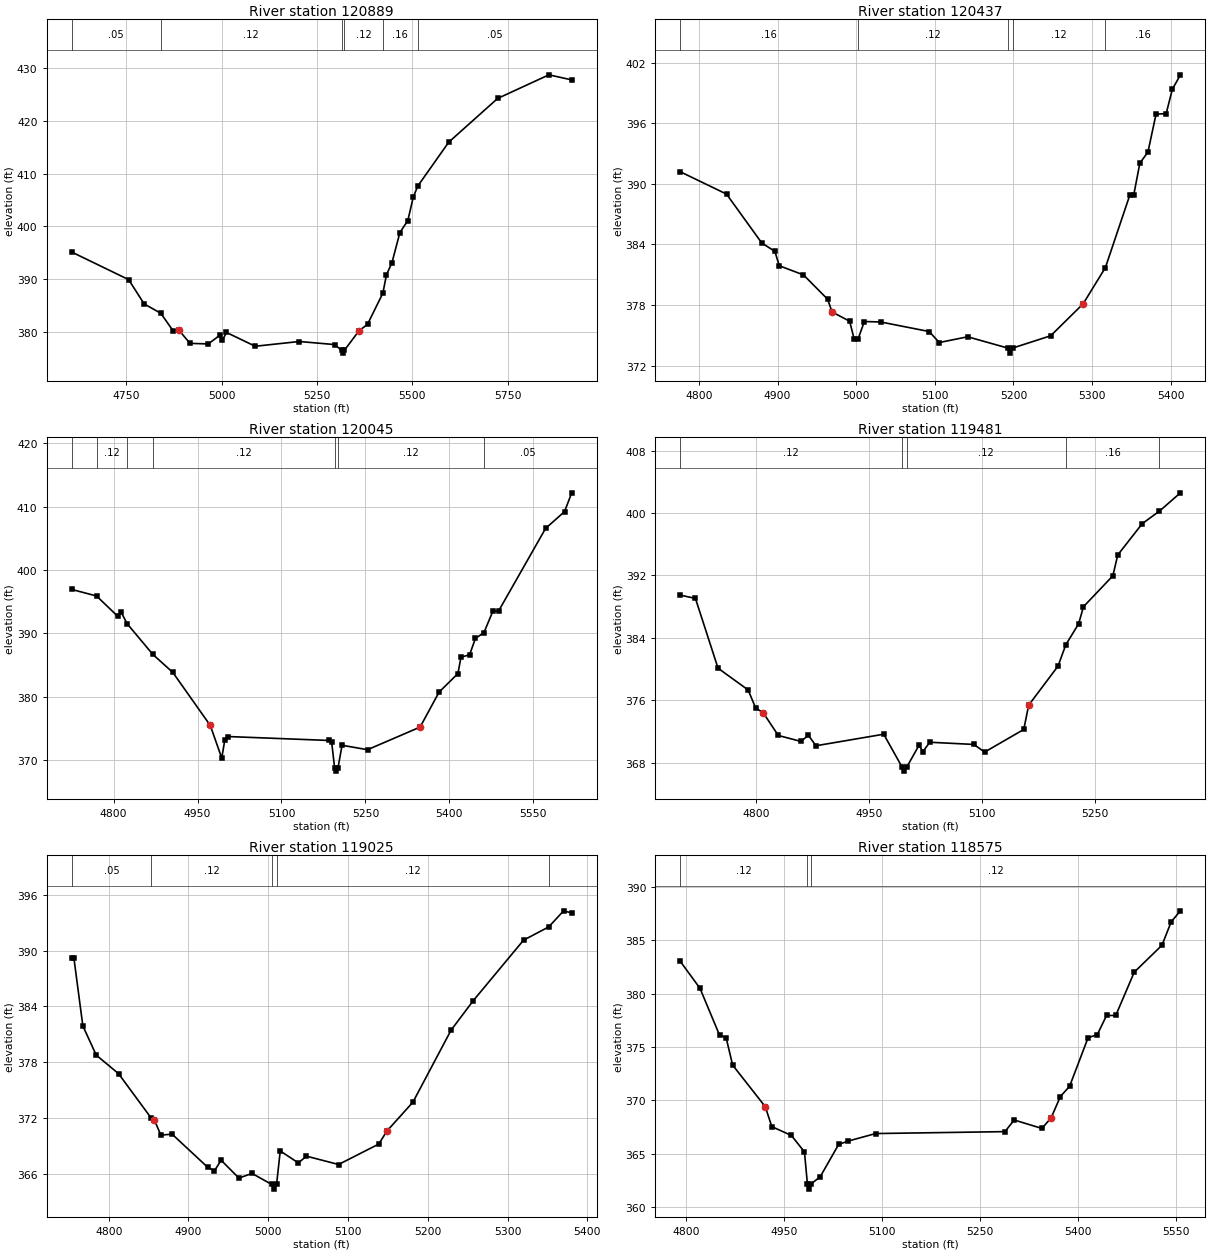
Type RM Length L Ch R = 1 ,120889  ,452,452,452
BEGIN DESCRIPTION:
LAKE CREEK 181.0
END DESCRIPTION:
XS GIS Cut Line= 3
      3720645.93     10673910.05      3720077.33       10673680.
      3719530.42     10673245.95
#Sta/Elev= 30
  4606.6  395.16    4756  389.94  4796.8  385.34  4840.4  383.57  4872.3  380.29
  4887.3  380.43  4916.9  377.88  4965.1  377.77  4994.6  379.39  5001.8  378.44
  5012.6  379.94  5088.1  377.33  5203.7  378.23  5296.1  377.65  5315.5  376.53
  5318.3  376.03  5321.5  376.53  5360.1  380.23  5382.6  381.48  5422.9  387.38
  5432.3  390.85  5446.7  393.14  5467.5  398.84  5488.3  401.11  5502.7  405.57
  5514.4  407.64  5595.7  415.95  5723.9  424.22  5858.4  428.69  5918.2  427.73
#Mann= 6 ,-1 , 0
  4606.6     .05       0  4840.4     .12       0  5315.5     .07       0
  5321.5     .12       0  5422.9     .16       0  5514.4     .05       0
Bank Sta=4887.3,5360.1
XS Rating Curve= 0 ,0
Exp/Cntr=0.3,0.1

Type RM Length L Ch R = 1 ,120437  ,392,392,392
BEGIN DESCRIPTION:
LAKE CREEK 180.0
END DESCRIPTION:
XS GIS Cut Line= 3
      3720549.63     10673560.23      3720449.61     10673360.19
      3720049.57     10673260.18
#Sta/Elev= 30
  4776.4   391.2  4835.1  388.99  4879.9  384.15  4896.6  383.31  4902.2  381.89
    4933  380.98  4963.7  378.57  4969.3  377.31  4991.7  376.39  4997.3  374.67
  5002.6  374.67  5010.4  376.36    5031  376.32  5092.8  375.37  5105.7  374.28
  5141.8  374.85  5192.9  373.73  5195.6  373.23  5198.9  373.73  5247.4  374.95
  5288.7  378.12    5317  381.71  5347.9  388.86  5353.1  388.93  5360.8  392.05
  5371.1  393.16  5381.4  396.91  5394.3  396.97  5402.1  399.37  5412.4  400.81
#Mann= 5 ,-1 , 0
  4776.4     .16       0  5002.6     .12       0  5192.9     .07       0
  5198.9     .12       0    5317     .16       0
Bank Sta=4969.3,5288.7
XS Rating Curve= 0 ,0
Exp/Cntr=0.3,0.1

Type RM Length L Ch R = 1 ,120045  ,564,564,564
BEGIN DESCRIPTION:
LAKE CREEK 179.0
END DESCRIPTION:
XS GIS Cut Line= 3
      3720871.63     10673063.69       3720355.1     10672950.83
      3720004.09     10672851.16
#Sta/Elev= 30
  4725.1  396.95  4769.6  395.91  4807.8  392.68    4813  393.45  4824.1  391.55
    4870  386.71  4905.9  383.85  4972.8  375.49  4993.3  370.34  4998.8  373.21
  5003.9  373.74  5184.6  373.12  5189.7  372.87    5195  368.78  5197.8  368.28
    5201  368.78  5208.3  372.36  5253.8  371.66  5347.8  375.23  5381.7  380.75
  5415.4  383.68  5420.8  386.26  5436.2  386.63  5446.6  389.22  5461.8  390.12
  5477.8  393.51  5488.2  393.57    5572  406.57  5605.9  409.23  5618.7  412.19
#Mann= 7 ,-1 , 0
  4725.1     .16       0  4769.6     .12       0  4824.1     .16       0
    4870     .12       0    5195     .07       0    5201     .12       0
  5461.8     .05       0
Bank Sta=4972.8,5347.8
XS Rating Curve= 0 ,0
Exp/Cntr=0.3,0.1

Type RM Length L Ch R = 1 ,119481  ,456,456,456
BEGIN DESCRIPTION:
LAKE CREEK 178.0
END DESCRIPTION:
XS GIS Cut Line= 3
      3720849.58     10672610.19      3720549.61     10672610.19
      3720199.58     10672510.18
#Sta/Elev= 30
  4699.2  389.48  4719.2  389.06  4749.2  380.12  4789.2  377.33  4799.2  375.01
  4809.2  374.41  4829.2   371.5  4859.2  370.74  4869.2  371.52  4879.2  370.18
  4969.2  371.66  4993.7  367.43  4996.4  366.93  4999.7  367.43  5016.1  370.24
  5021.3  369.43  5030.4  370.63  5088.9  370.35  5103.2  369.37  5155.2  372.27
  5161.7  375.38  5200.7  380.39    5211  383.12    5228   385.8  5234.5     388
  5273.5  391.96    5280  394.63  5312.5  398.64  5335.4  400.25  5363.2  402.59
#Mann= 5 ,-1 , 0
  4699.2     .12       0  4993.7     .07       0  4999.7     .12       0
    5211     .16       0  5335.4     .05       0
Bank Sta=4809.2,5161.7
XS Rating Curve= 0 ,0
Exp/Cntr=0.3,0.1

Type RM Length L Ch R = 1 ,119025  ,450,450,450
BEGIN DESCRIPTION:
LAKE CREEK 177.0
END DESCRIPTION:
XS GIS Cut Line= 3
      3720949.62     10672310.19      3720749.61     10672210.19
      3720349.64     10672160.19
#Sta/Elev= 30
  4753.6  389.19  4756.4  389.19  4767.6  381.89  4784.4  378.74  4812.3  376.75
  4853.6  371.93    4857  371.81  4865.4  370.13  4879.4  370.24  4924.1  366.67
  4932.5  366.28  4940.9  367.43  4963.2  365.51  4979.7  366.01  5004.4  364.82
  5007.2  364.32  5010.4  364.82    5015  368.43  5037.7  367.14  5047.8  367.87
  5088.1  366.97  5138.5  369.17  5148.5  370.55  5181.3  373.68  5229.2  381.44
  5256.9   384.6  5319.9  391.11  5351.5  392.54  5370.2  394.27  5380.3  394.04
#Mann= 5 ,-1 , 0
  4753.6     .05       0  4853.6     .12       0  5004.4     .07       0
  5010.4     .12       0  5351.5     .16       0
Bank Sta=4857,5148.5
XS Rating Curve= 0 ,0
Exp/Cntr=0.3,0.1

Type RM Length L Ch R = 1 ,118575  ,467,467,467
BEGIN DESCRIPTION:
LAKE CREEK 176.0
END DESCRIPTION:
XS GIS Cut Line= 3
      3721099.63     10671810.19      3720899.61     10671810.19
      3720499.62     10671410.19
#Sta/Elev= 30
  4791.8  383.03  4821.8  380.52  4851.8  376.12  4861.8   375.9  4871.8  373.32
  4921.8  369.42  4931.8  367.55  4961.8  366.72  4981.8  365.18  4986.3  362.19
  4989.1  361.69  4992.3  362.19    5006  362.86  5034.2  365.88  5048.4  366.19
  5090.8   366.9  5288.8  367.08    5303  368.17  5345.4  367.38  5359.5  368.37
  5373.7  370.37  5387.8  371.33  5416.1  375.88  5430.2  376.17  5444.4  377.97
  5458.5  377.97  5486.8  382.03  5529.2  384.55  5543.4  386.75  5557.5  387.78
#Mann= 3 ,-1 , 0
  4791.8     .12       0  4986.3     .07       0  4992.3     .12       0
Bank Sta=4921.8,5359.5
XS Rating Curve= 0 ,0
Exp/Cntr=0.3,0.1