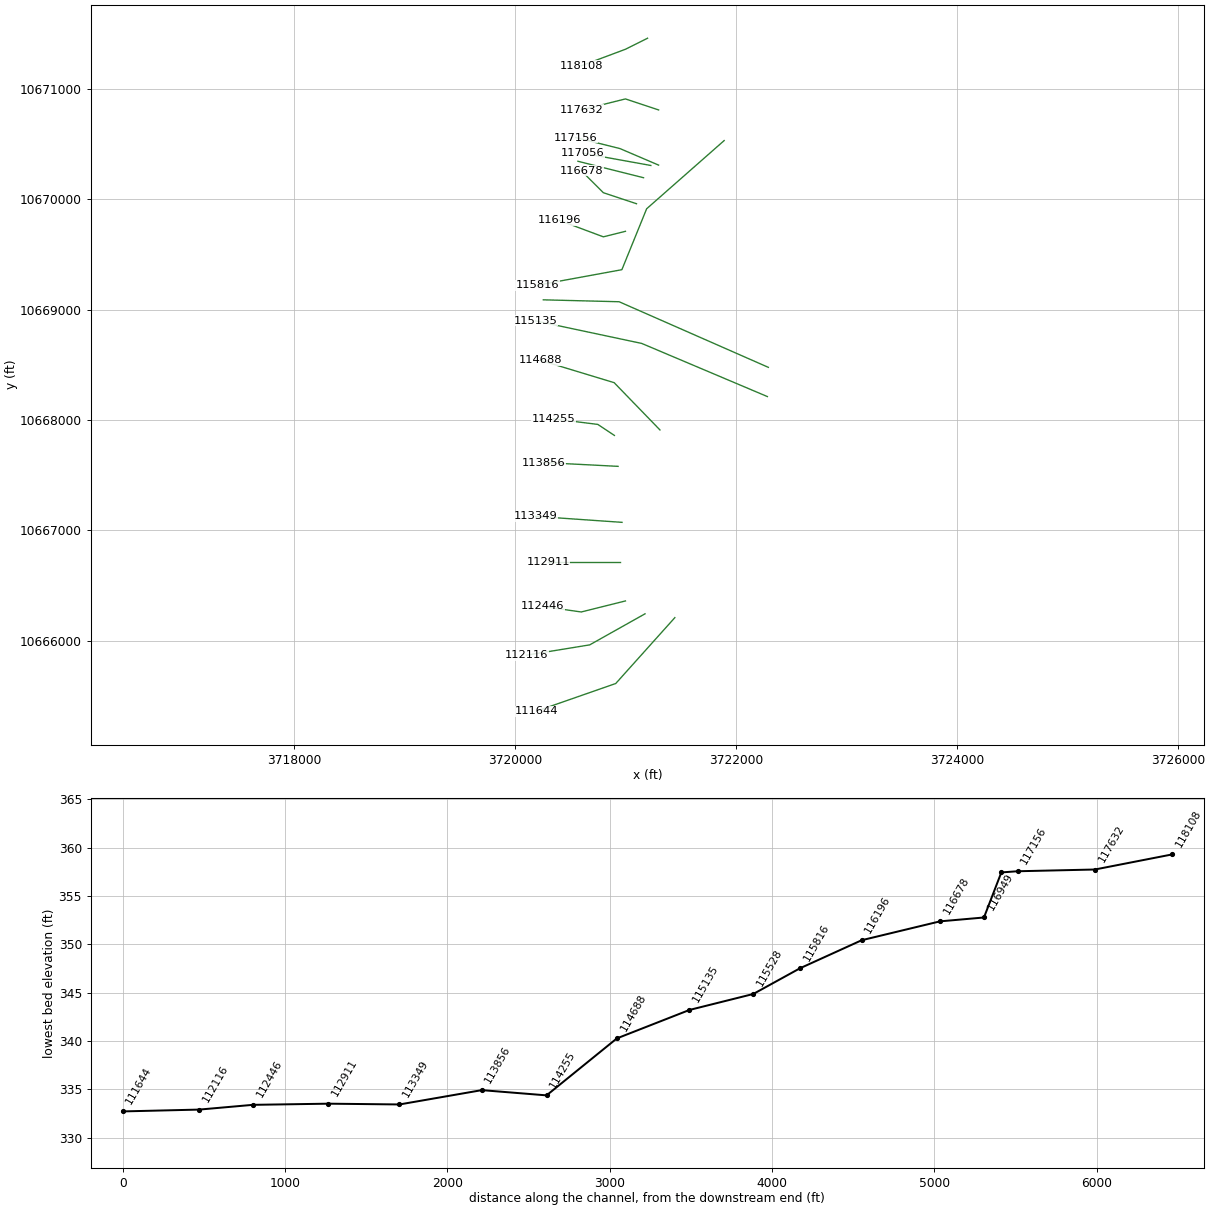
HEC-RAS study LAKE CREEK.prj: LAKE CREEK Base Level Engineering

--- LAKE CREEK.g01 (geometry) --- (continued)

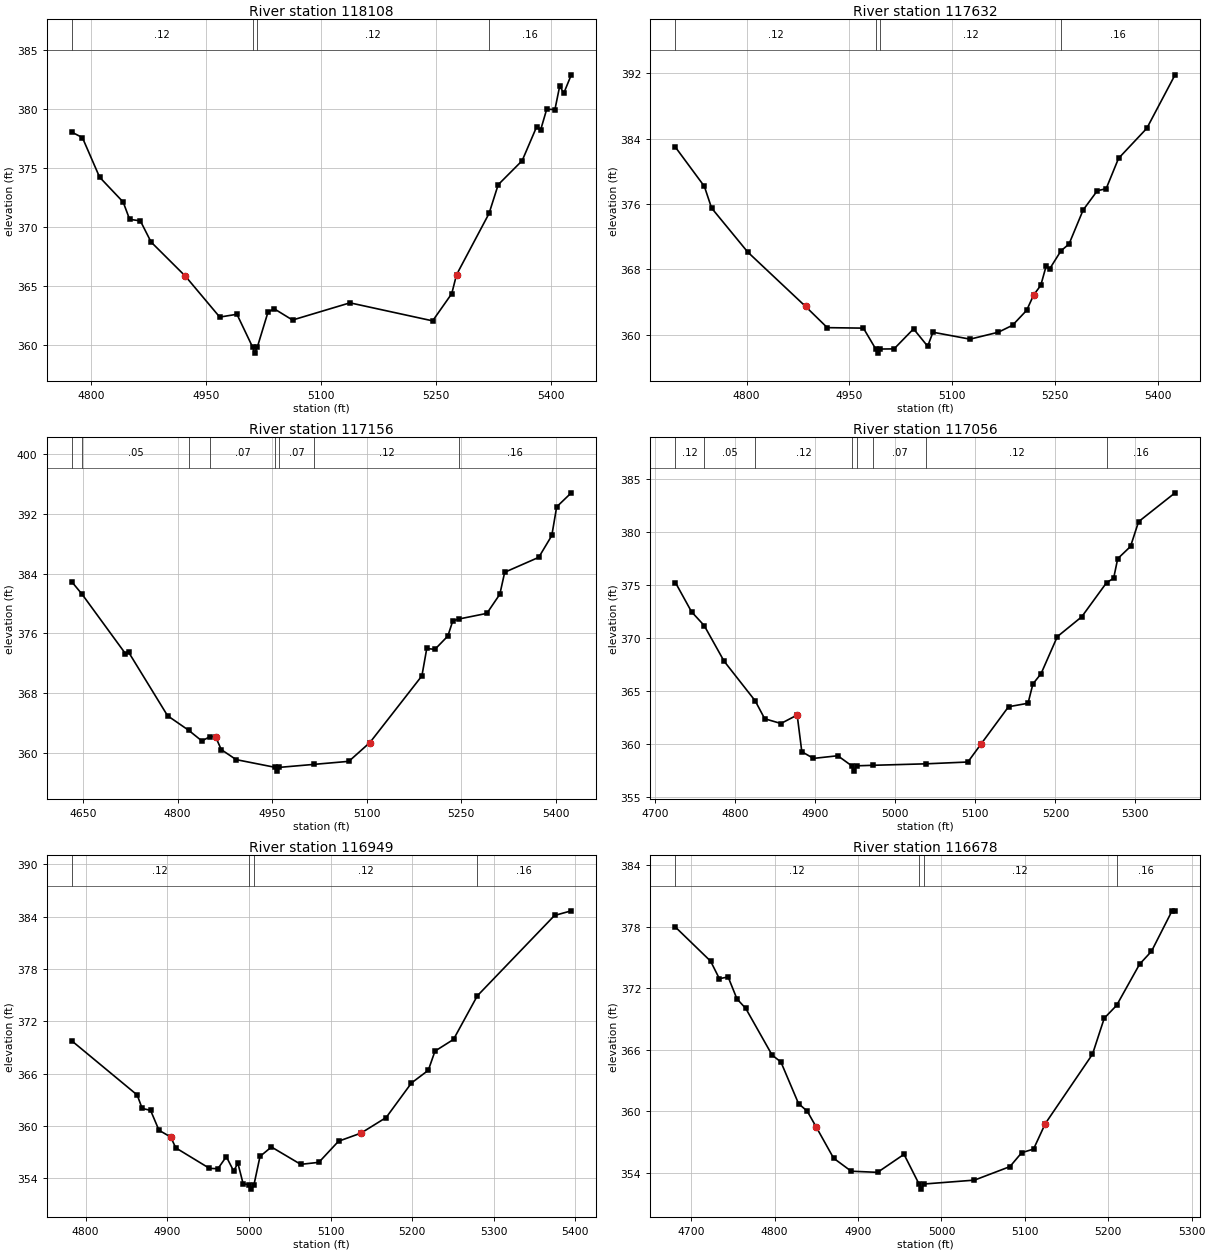
Type RM Length L Ch R = 1 ,118108  ,476,476,476
BEGIN DESCRIPTION:
LAKE CREEK 175.0
END DESCRIPTION:
XS GIS Cut Line= 3
      3721199.65     10671460.21      3720999.61     10671360.19
      3720599.65     10671210.21
#Sta/Elev= 30
  4775.1  378.07  4789.1   377.6  4811.5  374.24  4842.2  372.13  4850.6  370.66
  4864.6  370.53  4878.6  368.73  4923.3  365.83    4968  362.36  4990.4   362.6
  5010.9   359.8  5013.6   359.3  5016.9   359.8  5030.8  362.77  5038.8  363.07
  5062.8  362.11  5137.6  363.57  5245.3  362.04  5270.2  364.35  5276.4  365.95
  5318.8  371.16  5330.7   373.6  5361.9  375.64  5380.6  378.49  5385.9  378.23
  5393.9  380.01  5404.6  379.98  5410.8  381.97  5416.2  381.38  5425.9  382.93
#Mann= 4 ,-1 , 0
  4775.1     .12       0  5010.9     .07       0  5016.9     .12       0
  5318.8     .16       0
Bank Sta=4923.3,5276.4
XS Rating Curve= 0 ,0
Exp/Cntr=0.3,0.1

Type RM Length L Ch R = 1 ,117632  ,476,476,476
BEGIN DESCRIPTION:
LAKE CREEK 174.0
END DESCRIPTION:
XS GIS Cut Line= 3
      3721299.61     10670810.19      3720999.61     10670910.19
      3720599.65      10670810.2
#Sta/Elev= 30
  4696.2  382.96  4738.4  378.16  4748.9  375.51  4801.6  370.12  4885.9  363.46
  4917.6  360.86  4970.3   360.8  4988.3  358.24  4991.1  357.74  4994.3  358.24
    5015  358.26  5043.4  360.71    5064  358.58  5071.7   360.3  5125.8  359.45
    5167   360.3  5187.7  361.15  5208.3  362.98  5218.6  364.87  5228.9  366.04
  5236.6  368.36  5241.8  368.05  5258.4  370.27  5270.1   371.1  5290.7  375.27
  5311.4  377.63  5324.2  377.87  5342.3  381.59  5383.5  385.27  5424.7  391.82
#Mann= 4 ,-1 , 0
  4696.2     .12       0  4988.3     .07       0  4994.3     .12       0
  5258.4     .16       0
Bank Sta=4885.9,5218.6
XS Rating Curve= 0 ,0
Exp/Cntr=0.3,0.1

Type RM Length L Ch R = 1 ,117156  ,100,100,100
BEGIN DESCRIPTION:
LAKE CREEK 173.0
END DESCRIPTION:
XS GIS Cut Line= 3
      3721299.59      10670310.2      3720949.61     10670460.19
      3720549.59     10670560.19
#Sta/Elev= 30
  4631.9  382.92  4648.7   381.2  4717.1   373.3  4722.5  373.45  4784.2  364.97
  4817.4  363.04  4838.6   361.6  4851.2  362.16  4860.3  362.17  4869.4  360.44
    4893   359.1  4955.3  358.06    4958  357.56  4961.3  358.06  5016.1  358.46
  5071.9  358.87  5105.4  361.39  5187.9  370.31  5195.6  373.97  5208.5  373.85
  5229.1  375.64  5236.9  377.67  5246.9  377.92    5291  378.67  5311.6  381.23
  5319.3  384.17  5373.4  386.17  5394.1  389.09  5401.8  392.92    5425   394.8
#Mann= 8 ,-1 , 0
  4631.9     .12       0  4648.7     .05       0  4817.4     .12       0
  4851.2     .07       0  4955.3     .07       0  4961.3     .07       0
  5016.1     .12       0  5246.9     .16       0
Bank Sta=4860.3,5105.4
XS Rating Curve= 0 ,0
Exp/Cntr=0.3,0.1

Type RM Length L Ch R = 1 ,117056  ,107,107,107
BEGIN DESCRIPTION:
Mapping XS 6673079c
END DESCRIPTION:
XS GIS Cut Line= 2
      3721229.42     10670306.95      3720614.78     10670418.07
#Sta/Elev= 30
    4725  375.22  4745.1  372.47    4761  371.16  4785.8  367.81  4824.7  364.07
  4836.6  362.38  4856.9  361.93  4877.2  362.73    4883  359.27  4897.6  358.64
    4928  358.89  4945.4  357.94  4948.1  357.44  4951.4  357.94  4972.2  357.99
  5038.7  358.13  5090.6   358.3  5107.2  360.01  5141.4  363.51  5165.8  363.84
  5171.9  365.66  5182.1  366.63  5202.4  370.12  5232.9  371.99  5264.1  375.22
  5272.8  375.62  5277.9  377.47  5293.9  378.62    5304  380.96  5349.6  383.68
#Mann= 8 ,-1 , 0
    4725     .12       0    4761     .05       0  4824.7     .12       0
  4945.4     .07       0  4951.4     .12       0  4972.2     .07       0
  5038.7     .12       0  5264.1     .16       0
Bank Sta=4877.2,5107.2
XS Rating Curve= 0 ,0
Exp/Cntr=0.3,0.1

Type RM Length L Ch R = 1 ,116949  ,271,271,271
BEGIN DESCRIPTION:
Mapping XS 88416b79
END DESCRIPTION:
XS GIS Cut Line= 2
       3721163.4     10670195.85      3720569.69     10670345.15
#Sta/Elev= 30
  4782.8  369.79  4863.1  363.57  4869.2  362.03  4879.5  361.81  4889.8  359.53
  4904.2  358.75  4910.4  357.51  4951.7  355.16    4962  355.12  4972.3   356.5
  4981.3  354.86  4986.5  355.75  4992.9   353.4  5000.2  353.28    5003  352.78
  5006.2  353.28  5013.6  356.53  5027.6  357.61  5063.5  355.62  5085.7  355.85
  5109.8  358.27  5137.3   359.2  5168.2  360.99  5199.2  364.95  5219.8   366.4
    5228   368.6  5250.7  369.94  5279.9  374.94  5374.5  384.15    5395  384.68
#Mann= 4 ,-1 , 0
  4782.8     .12       0  5000.2     .07       0  5006.2     .12       0
  5279.9     .16       0
Bank Sta=4904.2,5137.3
XS Rating Curve= 0 ,0
Exp/Cntr=0.3,0.1

Type RM Length L Ch R = 1 ,116678  ,482,482,482
BEGIN DESCRIPTION:
LAKE CREEK 172.0
END DESCRIPTION:
XS GIS Cut Line= 3
       3721099.6     10669960.19      3720799.61     10670060.19
      3720599.58     10670260.21
#Sta/Elev= 30
    4681  377.98  4723.2  374.65  4733.7  372.94  4744.2  373.11  4754.8  370.96
  4765.3  370.04  4796.9  365.48  4807.5   364.8  4828.6  360.74  4839.1  359.99
  4849.6  358.48  4870.7   355.4  4891.8  354.13  4923.4  354.02  4955.1  355.78
  4973.1  352.88  4975.9  352.38  4979.1  352.88  5039.6  353.26  5082.1  354.58
  5096.2  355.94  5110.4  356.29  5124.5  358.78  5181.1  365.56  5195.2  369.08
    5210  370.33  5237.6  374.36  5251.8  375.61  5276.5  379.57  5280.1  379.57
#Mann= 4 ,-1 , 0
    4681     .12       0  4973.1     .07       0  4979.1     .12       0
    5210     .16       0
Bank Sta=4849.6,5124.5
XS Rating Curve= 0 ,0
Exp/Cntr=0.3,0.1

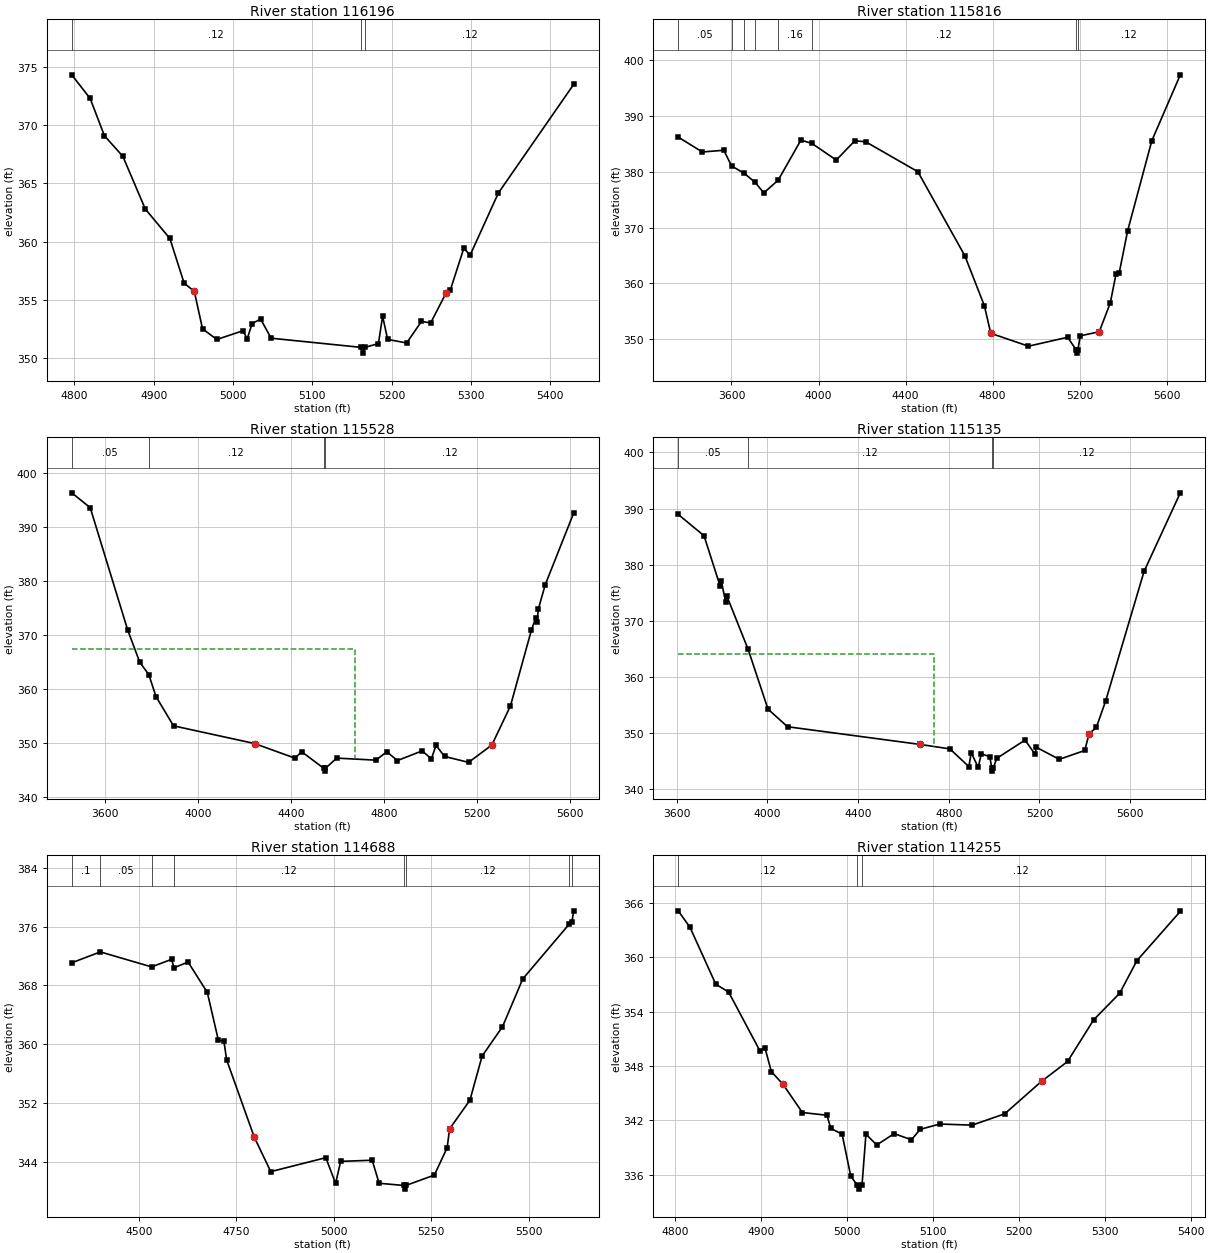
Type RM Length L Ch R = 1 ,116196  ,380,380,380
BEGIN DESCRIPTION:
LAKE CREEK 171.0
END DESCRIPTION:
XS GIS Cut Line= 3
      3720999.58     10669710.18      3720799.61     10669660.19
      3720399.63     10669810.18
#Sta/Elev= 30
  4796.6  374.31  4819.8  372.28  4837.8  369.08    4861  367.32  4889.3   362.8
  4920.3  360.27  4938.3  356.44  4951.2  355.72  4961.5  352.52  4979.5   351.6
  5012.5  352.35  5017.9  351.66  5024.1  352.97  5034.8  353.35  5048.1  351.71
  5160.8  350.93  5163.6  350.43  5166.8  350.93  5183.4  351.25  5188.7   353.6
    5195  351.61    5219   351.3  5237.7  353.15  5249.3  353.02  5268.8   355.6
  5274.2  355.86  5291.1  359.43  5299.1  358.84  5334.7  364.17  5429.9  373.51
#Mann= 3 ,-1 , 0
  4796.6     .12       0  5160.8     .07       0  5166.8     .12       0
Bank Sta=4951.2,5268.8
XS Rating Curve= 0 ,0
Exp/Cntr=0.3,0.1

Type RM Length L Ch R = 1 ,115816  ,288,288,288
BEGIN DESCRIPTION:
LAKE CREEK 170.0
END DESCRIPTION:
XS GIS Cut Line= 4
      3721892.58     10670532.65      3721191.36     10669914.46
       3720967.4     10669362.38      3720203.17     10669222.01
#Sta/Elev= 30
  3355.3   386.2  3465.8  383.53  3564.5  383.84  3600.6  381.03  3659.5  379.68
  3709.3  378.07  3748.6  376.21  3814.5  378.48  3919.2  385.66  3969.6  385.06
  4081.6  382.09  4166.9  385.53  4216.3  385.37  4456.6     380  4672.4  364.97
  4762.2  356.03  4791.7  351.08    4965  348.77    5145  350.37  5185.7  348.03
  5188.4  347.53  5191.7  348.03  5203.2  350.63  5290.3  351.35  5341.2  356.53
  5367.5  361.72  5381.8  361.83  5420.6  369.39  5531.9  385.54  5662.9  397.34
#Mann= 8 ,-1 , 0
  3355.3     .05       0  3600.6     .16       0  3659.5     .12       0
  3709.3     .05       0  3814.5     .16       0  3969.6     .12       0
  5185.7     .07       0  5191.7     .12       0
Bank Sta=4791.7,5290.3
XS Rating Curve= 0 ,0
Exp/Cntr=0.3,0.1

Type RM Length L Ch R = 1 ,115528  ,393,393,393
BEGIN DESCRIPTION:
Mapping XS 23ef04fc
END DESCRIPTION:
XS GIS Cut Line= 3
      3722292.29     10668477.24      3720942.44     10669071.87
      3720256.68     10669089.23
#Sta/Elev= 30
  3455.6  396.38    3535  393.63    3696  371.03  3748.1  365.03  3787.1  362.75
  3818.1  358.67  3893.6  353.25  4242.1  349.98  4416.3  347.27  4445.1  348.46
  4540.9  345.37  4543.6  344.87  4546.9  345.37    4596  347.28  4764.8   346.9
  4811.4  348.45  4857.2  346.83  4963.5  348.61  5003.5  347.17  5023.5  349.62
  5060.2  347.59  5163.5  346.49  5263.6   349.7  5343.6  356.92  5433.6  370.92
  5452.8  373.27  5457.8  372.38  5463.6  374.84  5493.6  379.39  5616.6  392.72
#Mann= 4 ,-1 , 0
  3455.6     .05       0  3787.1     .12       0  4540.9     .07       0
  4546.9     .12       0
#XS Ineff= 2 , 0
       0  4675.6  367.55               0
Permanent Ineff=
       F       F
Bank Sta=4242.1,5263.6
XS Rating Curve= 0 ,0
Exp/Cntr=0.3,0.1

Type RM Length L Ch R = 1 ,115135  ,447,447,447
BEGIN DESCRIPTION:
LAKE CREEK 169.0
END DESCRIPTION:
XS GIS Cut Line= 3
      3722283.59     10668212.49      3721146.43     10668694.26
      3720187.19     10668898.26
#Sta/Elev= 30
  3606.2  388.95  3720.1  385.15  3791.1  376.18  3796.6  377.05  3814.8  373.41
  3820.3  374.45  3914.5  364.93  4002.3  354.27  4088.4  351.13  4674.8  347.97
  4805.2  347.18  4888.8  344.02  4899.3  346.52    4930  343.87  4943.6  346.31
  4981.1  345.78  4990.2  343.72  4992.9  343.22  4996.2  343.72  5011.8   345.5
  5136.8  348.75  5181.3   346.2  5186.4  347.47  5287.8  345.32  5400.3   346.9
  5419.1  349.87  5451.4  351.02  5492.3   355.7  5661.9   378.8  5821.9   392.8
#Mann= 4 ,-1 , 0
  3606.2     .05       0  3914.5     .12       0  4990.2     .07       0
  4996.2     .12       0
#XS Ineff= 2 , 0
         4736.56  364.05
Permanent Ineff=
       F       F
Bank Sta=4674.8,5419.1
XS Rating Curve= 0 ,0
Exp/Cntr=0.3,0.1

Type RM Length L Ch R = 1 ,114688  ,433,433,433
BEGIN DESCRIPTION:
LAKE CREEK 168.0
END DESCRIPTION:
XS GIS Cut Line= 3
      3721311.82     10667909.94      3720897.39     10668338.52
      3720234.19       10668540.
#Sta/Elev= 30
  4327.1  371.08  4400.5  372.56    4532  370.52  4583.4  371.55  4589.6   370.4
  4625.8  371.18  4675.2  367.04  4703.5  360.55  4717.7  360.44  4724.9  357.85
  4795.6  347.37  4838.1  342.66  4979.5  344.56  5004.6  341.05  5017.6  344.06
  5098.6  344.21  5116.3  341.08    5179  340.78  5181.8  340.28    5185  340.78
  5258.2  342.19  5291.1  345.92  5297.2  348.47  5349.5  352.38  5380.8  358.39
  5433.1  362.37  5485.3  368.89  5603.7  376.29  5611.1  376.63  5616.4  378.15
#Mann= 8 ,-1 , 0
  4327.1      .1       0  4400.5     .05       0    4532     .16       0
  4589.6     .12       0    5179     .07       0    5185     .12       0
  5603.7     .05       0  5611.1     .12       0
Bank Sta=4795.6,5297.2
XS Rating Curve= 0 ,0
Exp/Cntr=0.3,0.1

Type RM Length L Ch R = 1 ,114255  ,399,399,399
BEGIN DESCRIPTION:
LAKE CREEK 167.0
END DESCRIPTION:
XS GIS Cut Line= 3
      3720899.65     10667860.16      3720749.61     10667960.19
      3720349.65     10668010.18
#Sta/Elev= 30
  4803.7  365.13  4817.3  363.32  4847.3  357.03  4862.3  356.15  4898.4   349.7
  4904.4  350.02  4911.9  347.37  4925.4  345.97    4948  342.85  4976.5  342.55
    4981   341.1  4994.1  340.46  5004.2  335.81  5011.3  334.89    5014  334.39
  5017.3  334.89  5021.8  340.45  5034.4  339.27  5054.6  340.52  5074.7  339.84
  5084.8  340.99  5107.5  341.58  5145.3  341.46  5183.1  342.71  5225.9   346.3
  5256.1  348.49  5286.4  353.09  5316.6  356.02  5336.7  359.63  5387.1  365.07
#Mann= 3 ,-1 , 0
  4803.7     .12       0  5011.3     .07       0  5017.3     .12       0
Bank Sta=4925.4,5225.9
XS Rating Curve= 0 ,0
Exp/Cntr=0.3,0.1

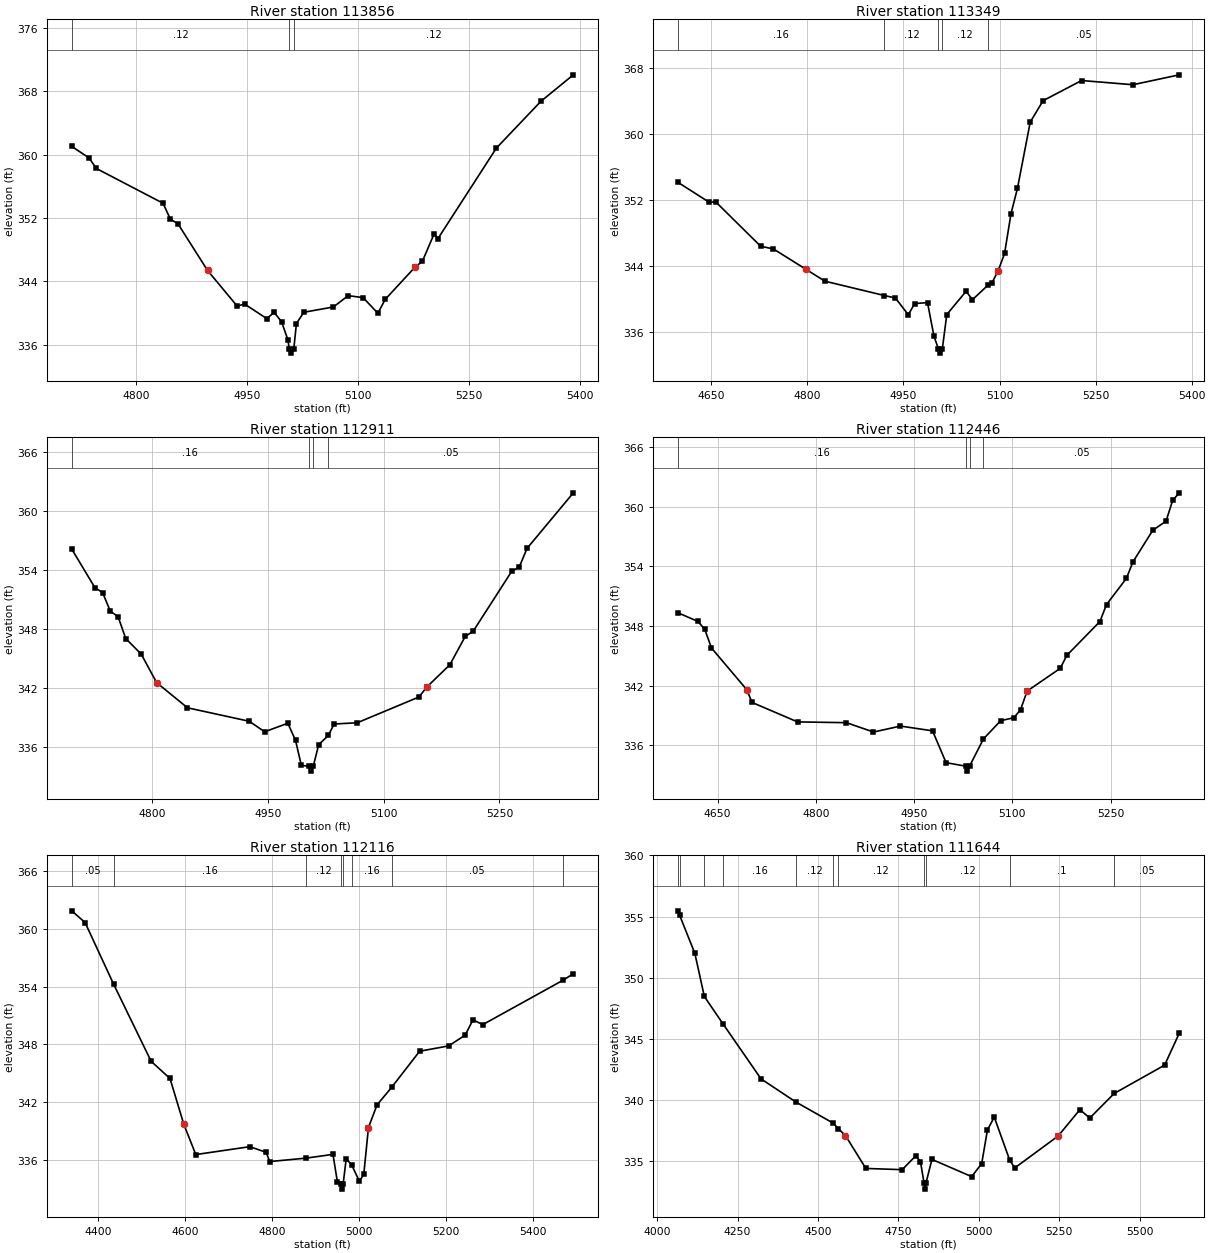
Type RM Length L Ch R = 1 ,113856  ,507,507,507
BEGIN DESCRIPTION:
LAKE CREEK 166.0
END DESCRIPTION:
XS GIS Cut Line= 2
      3720932.87     10667580.05      3720255.76     10667614.77
#Sta/Elev= 30
  4712.8  361.04  4736.1  359.59  4746.1  358.25  4836.2  353.86  4846.2  351.83
  4856.2  351.29  4896.3  345.38  4936.4  340.87  4946.4  341.13  4976.4  339.29
  4986.4  340.08  4996.4  338.89  5004.9  336.63  5006.9  335.43  5009.7  334.93
  5012.9  335.43  5016.5  338.67  5026.5  340.09  5066.5  340.76  5086.5  342.19
  5106.6  341.94  5126.6  339.97  5136.6  341.73  5176.7  345.78  5186.7  346.52
  5202.7  350.01  5207.7  349.38  5286.8  360.83  5346.9  366.73  5390.8  370.08
#Mann= 3 ,-1 , 0
  4712.8     .12       0  5006.9     .07       0  5012.9     .12       0
Bank Sta=4896.3,5176.7
XS Rating Curve= 0 ,0
Exp/Cntr=0.3,0.1

Type RM Length L Ch R = 1 ,113349  ,438,438,438
BEGIN DESCRIPTION:
LAKE CREEK 165.0
END DESCRIPTION:
XS GIS Cut Line= 2
      3720968.82     10667072.51       3720187.5     10667126.77
#Sta/Elev= 30
  4597.5  354.17  4646.8  351.73  4656.9  351.78    4727  346.41  4747.1  346.07
  4797.2  343.64  4827.3  342.17  4920.4  340.43  4937.5  340.13  4957.6   338.1
  4967.6  339.46  4987.6  339.57  4997.7  335.49  5004.7  333.95  5007.4  333.45
  5010.7  333.95  5017.7  338.13  5047.8  340.94  5057.8  339.93  5082.3  341.71
  5087.9  341.92  5097.9  343.43  5107.9  345.53    5118  350.37    5128  353.41
    5148  361.46  5168.1  364.05  5228.2  366.49  5308.4  365.98  5380.7  367.18
#Mann= 5 ,-1 , 0
  4597.5     .16       0  4920.4     .12       0  5004.7     .07       0
  5010.7     .12       0  5082.3     .05       0
Bank Sta=4797.2,5097.9
XS Rating Curve= 0 ,0
Exp/Cntr=0.3,0.1

Type RM Length L Ch R = 1 ,112911  ,465,465,465
BEGIN DESCRIPTION:
LAKE CREEK 164.0
END DESCRIPTION:
XS GIS Cut Line= 3
       3720949.6     10666710.19      3720649.61     10666710.19
       3720299.6     10666710.19
#Sta/Elev= 30
  4695.7  356.11  4725.7  352.19  4735.7  351.68  4745.7  349.79  4755.7  349.24
  4765.7  347.01  4785.7  345.43  4805.7  342.53  4845.7  339.97  4925.7   338.6
  4945.7  337.53  4975.7   338.4  4985.7  336.66  4993.2  334.12  5002.7  334.03
  5005.4  333.53  5008.7  334.03  5015.7  336.22  5028.2  337.16  5035.7  338.32
  5065.7  338.45  5145.7  341.07  5155.7  342.07  5185.7  344.35  5205.7  347.24
  5215.7  347.73  5265.7  353.83  5275.7   354.3  5285.7  356.18  5345.7  361.83
#Mann= 4 ,-1 , 0
  4695.7     .16       0  5002.7     .07       0  5008.7     .16       0
  5028.2     .05       0
Bank Sta=4805.7,5155.7
XS Rating Curve= 0 ,0
Exp/Cntr=0.3,0.1

Type RM Length L Ch R = 1 ,112446  ,330,330,330
BEGIN DESCRIPTION:
LAKE CREEK 163.0
END DESCRIPTION:
XS GIS Cut Line= 3
      3720999.65      10666360.2      3720599.61     10666260.19
      3720249.62     10666310.19
#Sta/Elev= 30
    4589  349.34    4620  348.46  4630.3  347.67  4640.6  345.79  4694.7  341.58
  4702.4  340.32    4772  338.36  4846.7  338.28    4888  337.34  4929.2  337.94
  4978.2  337.46  4998.8  334.26  5028.7  333.91  5031.4  333.41  5034.7  333.91
  5055.9  336.65  5082.2  338.48  5102.4  338.78  5112.5  339.58  5122.6  341.46
  5173.1  343.74  5183.2  345.05  5233.7  348.45  5243.8  350.16  5274.1  352.78
  5284.2  354.45  5314.5  357.63  5334.7  358.54  5344.8  360.63  5354.9  361.39
#Mann= 4 ,-1 , 0
    4589     .16       0  5028.7     .07       0  5034.7     .16       0
  5055.9     .05       0
Bank Sta=4694.7,5122.6
XS Rating Curve= 0 ,0
Exp/Cntr=0.3,0.1

Type RM Length L Ch R = 1 ,112116  ,472,472,472
BEGIN DESCRIPTION:
LAKE CREEK 162.0
END DESCRIPTION:
XS GIS Cut Line= 3
      3721176.38     10666243.27       3720676.4     10665962.03
      3720104.07     10665868.37
#Sta/Elev= 30
    4340   361.9  4370.7  360.68  4436.1  354.28  4522.6  346.23    4566  344.44
  4597.8  339.66  4625.3  336.52  4749.6  337.34  4787.2  336.75  4795.2  335.79
  4879.4  336.15  4940.8  336.54  4950.9  333.68  4958.1  333.42  4960.8  332.92
  4964.1  333.42  4971.2  336.08  4983.6  335.46  5001.6  333.73  5011.7  334.48
  5022.4  339.33  5042.1  341.69  5076.1  343.54  5140.1  347.28  5206.5  347.83
  5244.8  348.95  5262.8  350.55  5285.3  350.05    5469  354.65  5493.6  355.35
#Mann= 8 ,-1 , 0
    4340     .05       0  4436.1     .16       0  4879.4     .12       0
  4958.1     .07       0  4964.1     .12       0  4983.6     .16       0
  5076.1     .05       0    5469      .1       0
Bank Sta=4597.8,5022.4
XS Rating Curve= 0 ,0
Exp/Cntr=0.3,0.1

Type RM Length L Ch R = 1 ,111644  ,522,522,522
BEGIN DESCRIPTION:
LAKE CREEK 161.0
END DESCRIPTION:
XS GIS Cut Line= 3
      3721446.63     10666209.06      3720911.93     10665611.86
      3720196.65     10665361.86
#Sta/Elev= 30
  4063.8  355.47  4069.5  355.13  4117.2  351.99  4146.7  348.47  4205.8  346.19
  4322.9  341.74  4431.1  339.85  4546.7  338.13  4563.3  337.67  4585.3  337.11
  4648.8  334.42  4761.7  334.32  4804.3  335.46  4818.5  334.98  4829.7  333.23
  4832.5  332.73  4835.7  333.23  4854.2  335.16  4977.8  333.75  5008.9  334.82
  5026.7  337.56  5047.9  338.62  5095.8  335.11  5111.5  334.46  5246.6  337.07
    5314  339.22    5345  338.54  5420.9  340.55  5577.5  342.86  5623.1  345.47
#Mann= 11 ,-1 , 0
  4063.8     .05       0  4069.5     .16       0  4146.7     .05       0
  4205.8     .16       0  4431.1     .12       0  4546.7     .05       0
  4563.3     .12       0  4829.7     .07       0  4835.7     .12       0
  5095.8      .1       0  5420.9     .05       0
Bank Sta=4585.3,5246.6
XS Rating Curve= 0 ,0
Exp/Cntr=0.3,0.1