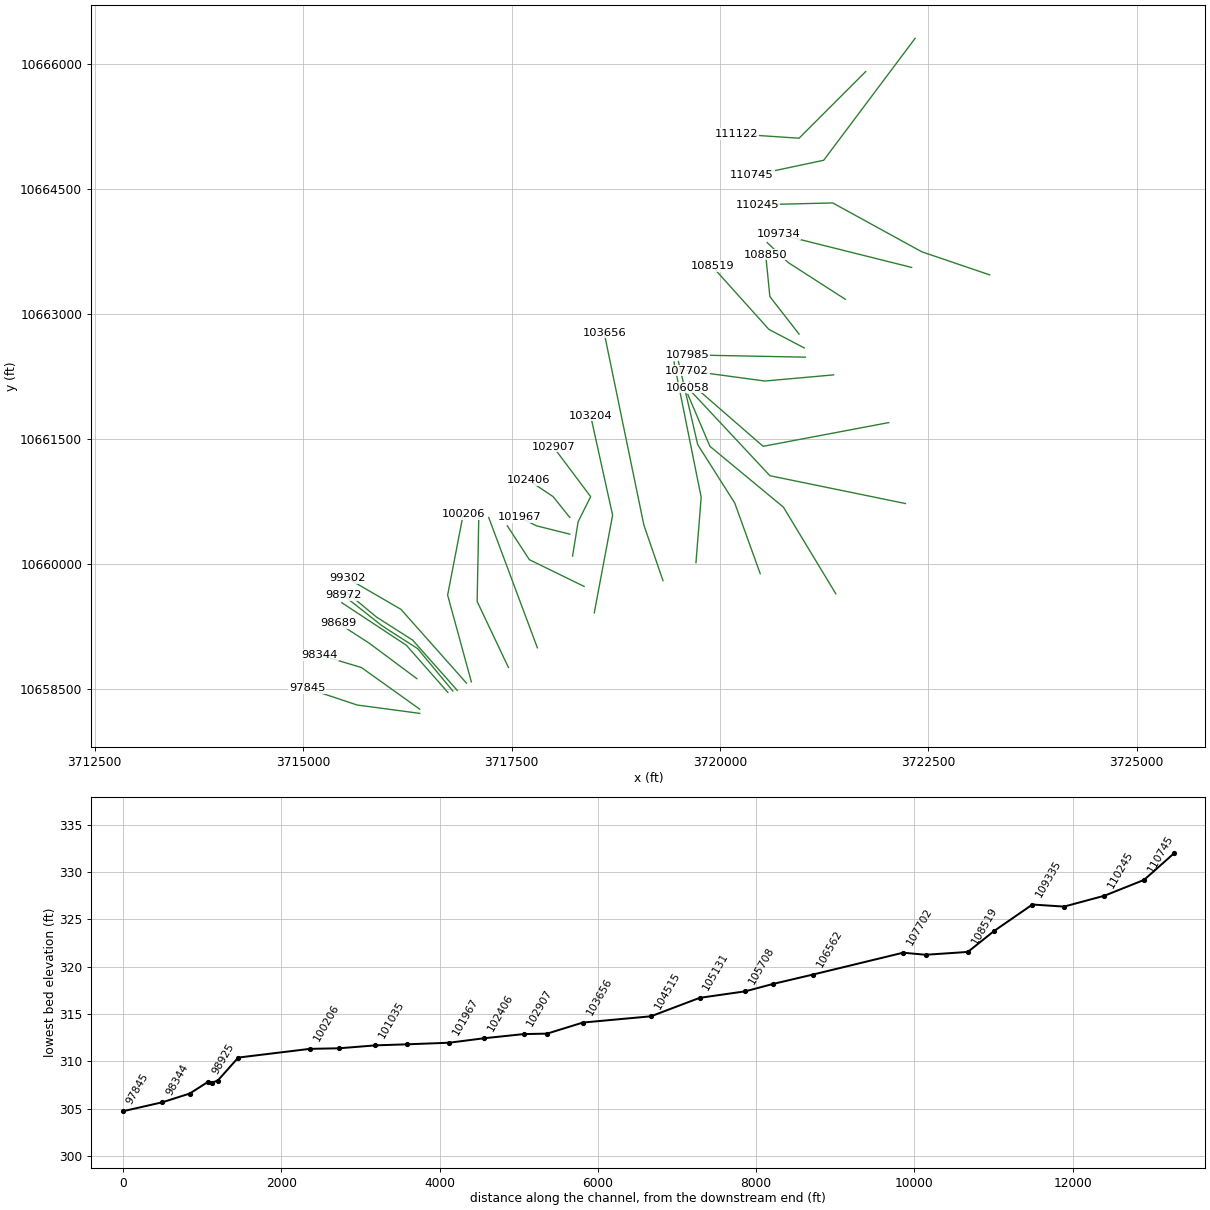
HEC-RAS study LAKE CREEK.prj: LAKE CREEK Base Level Engineering

--- LAKE CREEK.g01 (geometry) --- (continued)

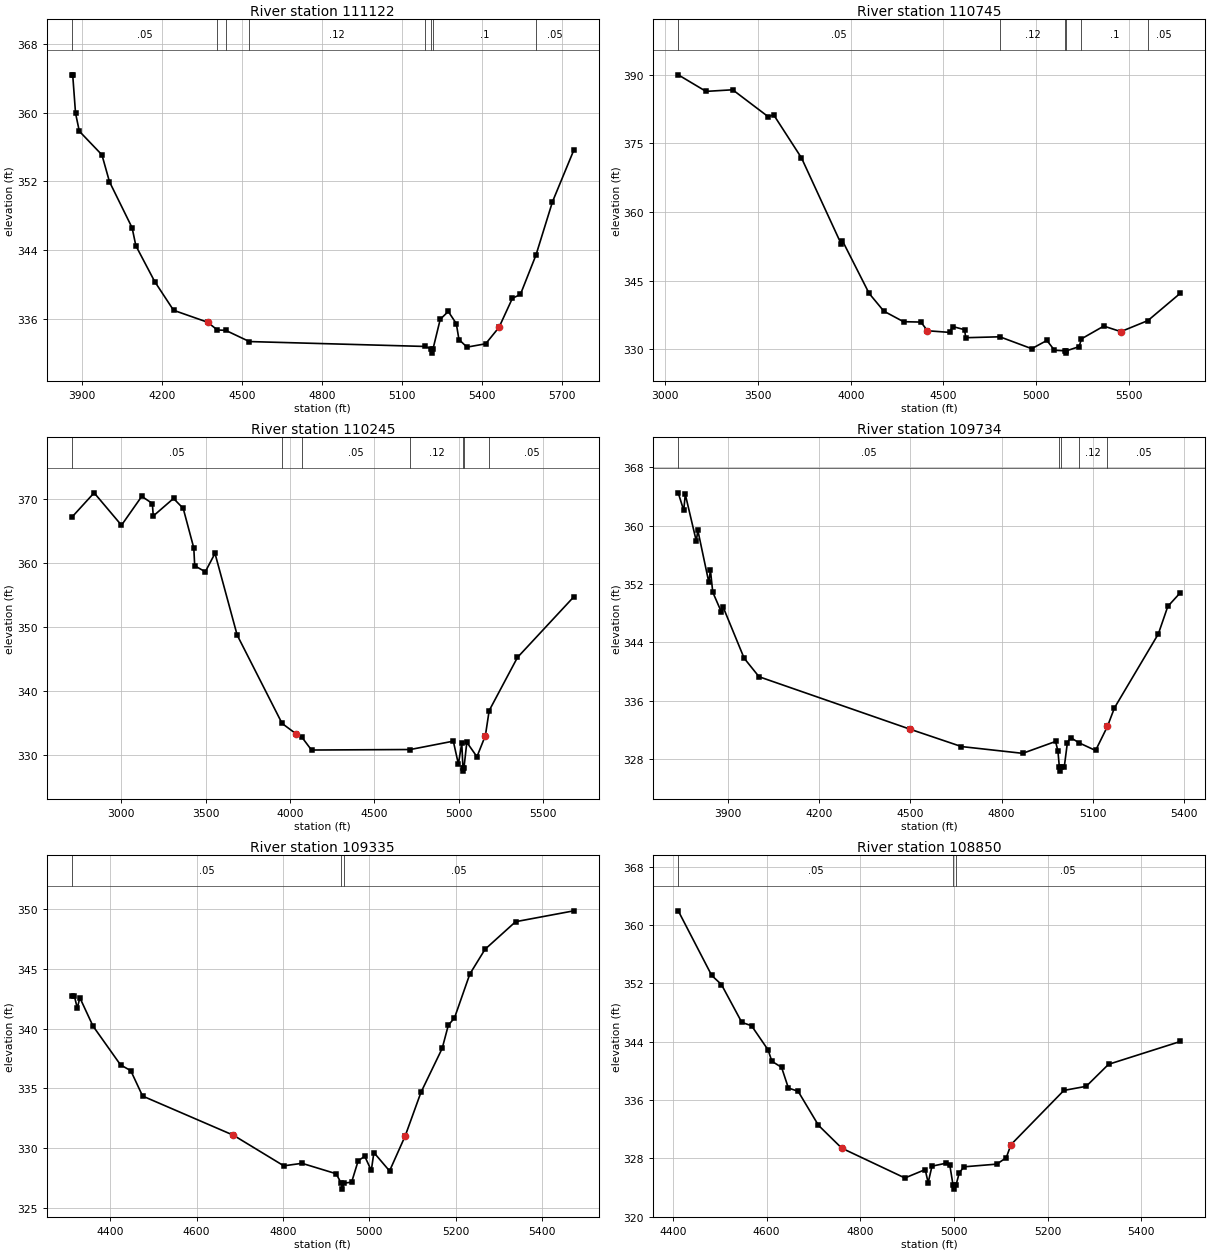
Type RM Length L Ch R = 1 ,111122  ,377,377,377
BEGIN DESCRIPTION:
LAKE CREEK 160.0
END DESCRIPTION:
XS GIS Cut Line= 3
      3721749.61     10665910.19      3720949.61     10665110.19
      3720199.64     10665160.19
#Sta/Elev= 30
  3860.7  364.44  3864.2  364.44  3874.8  359.97    3889  357.86  3973.8   355.1
  4002.1  351.96    4087  346.59  4101.1  344.49  4171.8  340.31  4242.5  336.96
  4369.8  335.57    4407  334.66  4437.9  334.62  4526.8  333.31  5184.1  332.74
  5209.6  332.46  5212.3  331.96  5215.6  332.46  5242.6  335.91  5272.7  336.82
  5302.8  335.41  5312.8  333.55  5342.8  332.66    5413  333.05  5463.1  334.97
  5513.2  338.36  5543.3  338.81  5601.7  343.41  5663.6  349.63  5743.7  355.66
#Mann= 8 ,-1 , 0
  3860.7     .05       0    4407     .12       0  4437.9     .05       0
  4526.8     .12       0  5184.1      .1       0  5209.6     .07       0
  5215.6      .1       0  5601.7     .05       0
#XS Ineff= 1 ,-1
 5263.21 5639.23  335.92
Permanent Ineff=
       F
Bank Sta=4369.8,5463.1
XS Rating Curve= 0 ,0
Exp/Cntr=0.3,0.1

Type RM Length L Ch R = 1 ,110745  ,500,500,500
BEGIN DESCRIPTION:
LAKE CREEK 159.0
END DESCRIPTION:
XS GIS Cut Line= 3
      3722342.02     10666308.29      3721245.36     10664845.67
      3720385.97     10664663.38
#Sta/Elev= 30
  3070.1     390  3219.9  386.38  3363.6  386.73  3555.3  380.84  3584.5  381.26
  3734.5  371.84  3949.1  352.97  3955.3  353.72  4099.1  342.22  4178.3  338.34
  4284.5  336.03  4378.3  335.95  4413.7  334.05  4534.5  333.69  4549.1  334.98
  4613.7  334.28  4619.9  332.53  4803.7  332.73  4975.6  330.13  5057.4  331.93
  5098.4  329.79  5156.6  329.66  5159.4  329.16  5162.6  329.66  5231.2  330.58
  5243.7  332.28  5364.1  335.07  5456.1  333.86  5602.2  336.28  5776.7  342.25
#Mann= 6 ,-1 , 0
  3070.1     .05       0  4803.7     .12       0  5156.6     .07       0
  5162.6     .12       0  5243.7      .1       0  5602.2     .05       0
Bank Sta=4413.7,5456.1
XS Rating Curve= 0 ,0
Exp/Cntr=0.3,0.1

Type RM Length L Ch R = 1 ,110245  ,511,511,511
BEGIN DESCRIPTION:
LAKE CREEK 158.0
END DESCRIPTION:
XS GIS Cut Line= 4
      3723235.41     10663470.94      3722421.57     10663747.58
      3721353.86     10664333.52      3720455.41     10664311.82
#Sta/Elev= 30
  2707.2  367.19  2839.7  371.02  3001.9  365.95  3122.1  370.47  3184.9  369.35
  3190.2  367.39  3310.4  370.14  3367.9  368.58  3430.6  362.38  3435.9  359.61
  3498.7  358.67  3556.2  361.55  3687.6  348.77  3953.9  334.95  4035.4  333.35
    4072  332.77  4128.3  330.79  4714.3  330.87    4969  332.18    4999  328.58
    5019  331.88    5026  327.99  5028.8  327.49    5032  327.99    5049     332
    5109  329.74  5159.1  333.06  5181.4  336.95  5349.1  345.27  5683.4  354.76
#Mann= 7 ,-1 , 0
  2707.2     .05       0  3953.9     .12       0    4072     .05       0
  4714.3     .12       0    5026     .07       0    5032     .12       0
  5181.4     .05       0
Bank Sta=4035.4,5159.1
XS Rating Curve= 0 ,0
Exp/Cntr=0.3,0.1

Type RM Length L Ch R = 1 ,109734  ,399,399,399
BEGIN DESCRIPTION:
LAKE CREEK 157.0
END DESCRIPTION:
XS GIS Cut Line= 3
      3722299.61     10663560.19      3721099.61     10663860.19
      3720699.65     10663960.18
#Sta/Elev= 30
  3738.1  364.52  3756.1  362.11  3761.3  364.31  3797.4   357.9  3802.5  359.38
  3838.6  352.24  3843.8  353.93  3851.5  350.89  3879.8  348.17    3885   348.9
  3954.6  341.83  4003.5  339.29  4498.3  332.11  4668.4  329.71  4869.4  328.78
  4977.6  330.41  4985.3  329.09  4990.1  326.84  4992.8  326.34  4996.1  326.84
    5006  326.87  5016.3  330.23  5026.6  330.95  5054.8  330.22    5109  329.17
  5148.1  332.49  5170.9  335.01  5315.2  345.17  5346.1  348.93  5387.3  350.82
#Mann= 5 ,-1 , 0
  3738.1     .05       0  4990.1     .03       0  4996.1     .05       0
  5054.8     .12       0  5148.1     .05       0
Bank Sta=4498.3,5148.1
XS Rating Curve= 0 ,0
Exp/Cntr=0.3,0.1

Type RM Length L Ch R = 1 ,109335  ,485,485,485
BEGIN DESCRIPTION:
LAKE CREEK 156.0
END DESCRIPTION:
XS GIS Cut Line= 3
      3721504.59     10663177.77        3720824.     10663615.29
      3720567.04     10663858.37
#Sta/Elev= 30
  4310.7  342.74  4316.6  342.74  4323.5   341.7  4329.4  342.58  4359.8  340.21
  4423.6  336.96  4447.4  336.47  4474.7  334.35  4685.1  331.07  4801.7  328.51
  4843.9  328.72  4922.9  327.85  4934.7  327.06  4937.5  326.56  4940.7  327.06
  4958.8  327.14    4974  328.93  4989.2  329.31  5004.4  328.12  5010.4  329.62
  5046.7  328.08    5083  331.02  5119.3  334.65  5168.6  338.34  5182.8  340.28
    5197  340.88  5232.6  344.56  5267.8  346.63  5338.6  348.94  5473.5  349.85
#Mann= 3 ,-1 , 0
  4310.7     .05       0  4934.7     .03       0  4940.7     .05       0
Bank Sta=4685.1,5083
XS Rating Curve= 0 ,0
Exp/Cntr=0.3,0.1

Type RM Length L Ch R = 1 ,108850  ,331,331,331
BEGIN DESCRIPTION:
LAKE CREEK 155.0
END DESCRIPTION:
XS GIS Cut Line= 3
      3720949.63     10662760.17      3720599.61     10663210.19
      3720549.61     10663710.18
#Sta/Elev= 30
  4411.1  361.93  4482.6  353.07  4503.4  351.82  4546.9  346.63  4567.7  346.17
    4603  342.86  4611.1   341.3  4631.9  340.46  4646.4  337.63  4667.2  337.18
  4710.7  332.51  4760.4  329.38  4895.3  325.29  4938.7  326.44    4945  324.63
  4953.2  326.91  4983.7  327.32  4991.3  327.04  4998.3  324.26  5001.1  323.76
  5004.3  324.26  5011.4  325.98  5021.4  326.82  5091.8  327.19  5111.9  328.08
  5121.9  329.86    5235   337.3  5282.7  337.86  5330.4  340.88  5483.7  344.01
#Mann= 3 ,-1 , 0
  4411.1     .05       0  4998.3     .03       0  5004.3     .05       0
Bank Sta=4760.4,5121.9
XS Rating Curve= 0 ,0
Exp/Cntr=0.3,0.1

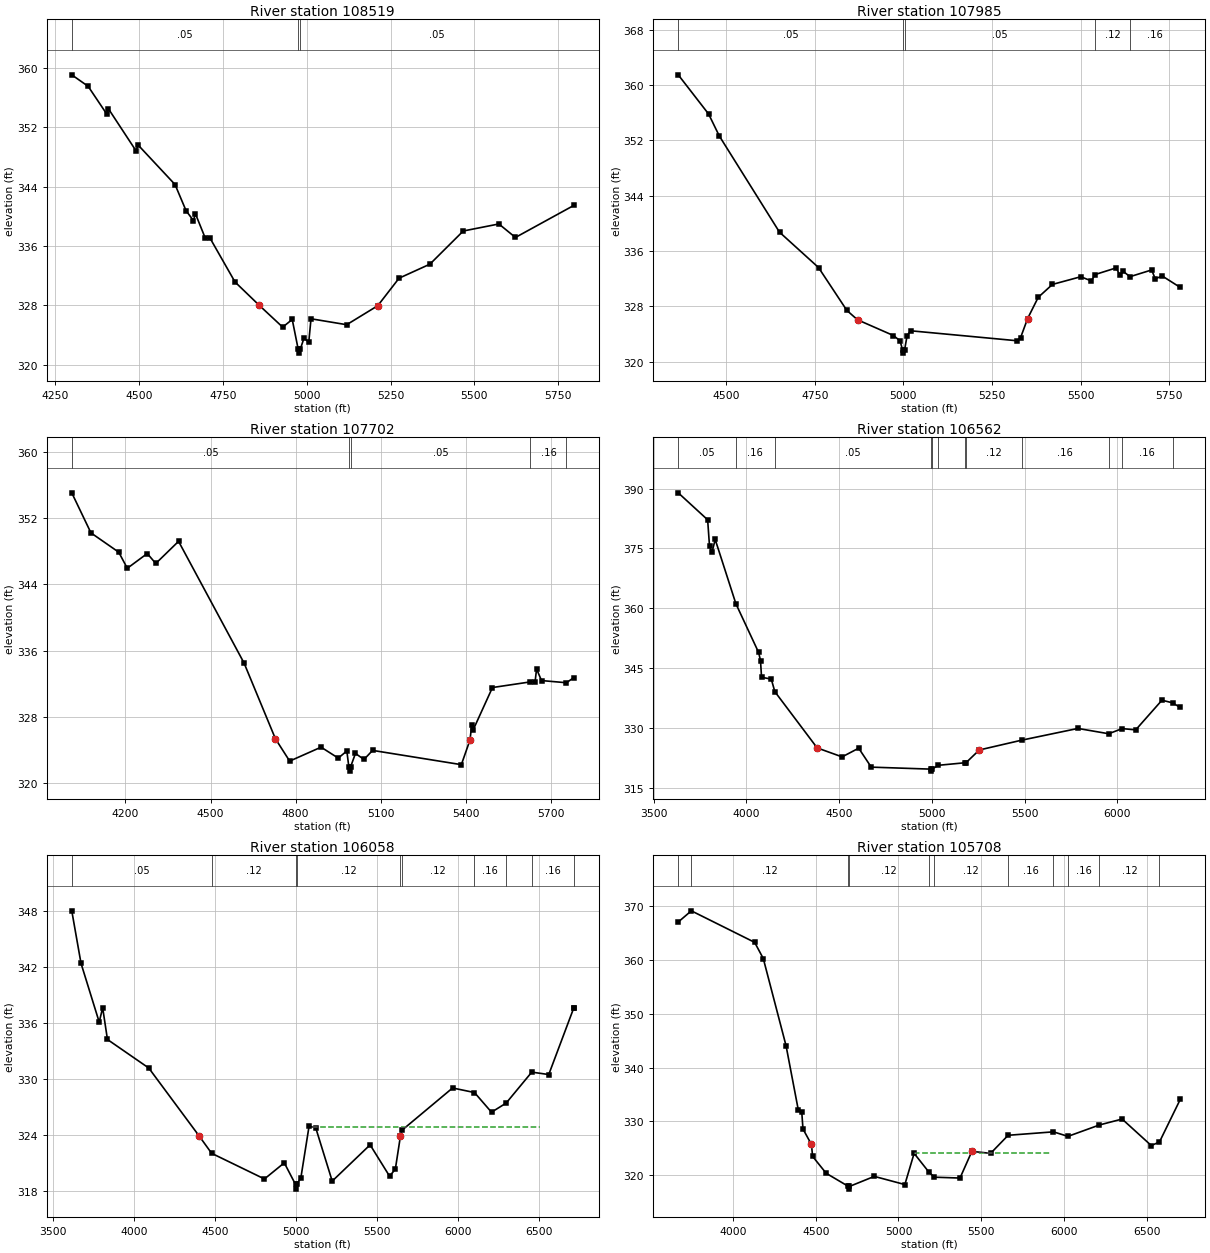
Type RM Length L Ch R = 1 ,108519  ,534,534,534
BEGIN DESCRIPTION:
LAKE CREEK 154.0
END DESCRIPTION:
XS GIS Cut Line= 3
      3721011.51     10662594.45      3720587.89     10662816.68
      3719907.32     10663573.64
#Sta/Elev= 30
  4300.1  359.06  4348.9  357.51  4403.8  353.81  4409.4  354.48    4492  348.79
  4497.6  349.61  4607.9  344.27  4640.7  340.75  4662.8  339.41  4668.4  340.36
  4697.5   337.1  4712.6  337.01  4786.6  331.14  4857.7  328.04  4928.7  325.05
  4957.1  326.09    4975  322.05  4977.8  321.55    4981  322.05  4992.2  323.58
  5006.4  323.03  5013.1  326.18  5119.4  325.38    5212  327.94  5275.5  331.65
  5367.4  333.54  5466.8  338.01    5573  338.96  5622.3  337.14  5796.4  341.46
#Mann= 3 ,-1 , 0
  4300.1     .05       0    4975     .03       0    4981     .05       0
Bank Sta=4857.7,5212
XS Rating Curve= 0 ,0
Exp/Cntr=0.3,0.1

Type RM Length L Ch R = 1 ,107985  ,283,283,283
BEGIN DESCRIPTION:
LAKE CREEK 153.0
END DESCRIPTION:
XS GIS Cut Line= 2
       3721025.4     10662483.35      3719608.77     10662511.12
#Sta/Elev= 30
  4364.5  361.47  4450.3   355.8  4480.3  352.64  4650.3  338.73  4760.4  333.62
  4840.4  327.42  4870.4  326.07  4971.9  323.79  4990.4  323.03  4997.4  321.75
  5000.2  321.25  5003.4  321.75  5010.4  323.78  5020.4  324.48  5320.5  323.04
  5330.5  323.47  5350.5  326.25  5380.5  329.32  5420.5  331.18  5500.5  332.29
  5530.5  331.68  5540.5   332.6  5600.5  333.57  5610.5  332.54  5620.5  333.05
  5639.5   332.3  5700.5  333.27  5710.6     332  5730.6  332.39  5781.4  330.74
#Mann= 5 ,-1 , 0
  4364.5     .05       0  4997.4     .03       0  5003.4     .05       0
  5540.5     .12       0  5639.5     .16       0
Bank Sta=4870.4,5350.5
XS Rating Curve= 0 ,0
Exp/Cntr=0.3,0.1

Type RM Length L Ch R = 1 ,107702  ,1140,1140,1140
BEGIN DESCRIPTION:
LAKE CREEK 152.0
END DESCRIPTION:
XS GIS Cut Line= 3
      3721364.53     10662270.97      3720539.88     10662197.19
      3719606.67     10662323.06
#Sta/Elev= 30
  4010.9  355.03  4078.5   350.2  4176.5  347.87  4206.6  345.93  4276.9  347.71
    4307  346.51  4387.3  349.18  4618.2   334.5  4728.7  325.37  4778.9  322.68
  4889.6  324.36  4950.1  323.04  4980.4   323.9  4987.5  321.97  4990.2  321.47
  4993.5  321.97  5010.7   323.6  5040.9  322.88  5071.2  323.97    5384  322.25
  5414.3  325.21  5420.8  327.04  5425.9  326.46  5493.6  331.55  5627.2  332.23
    5644  332.26  5649.1  333.79  5666.5  332.39  5754.4  332.13  5780.5  332.75
#Mann= 5 ,-1 , 0
  4010.9     .05       0  4987.5     .03       0  4993.5     .05       0
  5627.2     .16       0  5754.4     .12       0
Bank Sta=4728.7,5414.3
XS Rating Curve= 0 ,0
Exp/Cntr=0.3,0.1

Type RM Length L Ch R = 1 ,106562  ,504,504,504
BEGIN DESCRIPTION:
LAKE CREEK 151.0
END DESCRIPTION:
XS GIS Cut Line= 3
      3722025.35     10661698.62      3720518.45      10661413.9
      3719633.69     10662183.36
#Sta/Elev= 30
  3632.9  388.92  3791.4  382.16  3801.6  375.47  3814.9  373.99  3832.1  377.23
  3943.7  361.11  4066.2   348.9  4076.3  346.89  4081.9  342.68  4134.2  342.24
  4153.6  339.08  4381.7  324.98  4516.1  322.73  4605.5  324.91  4673.2  320.16
  4994.7  319.66  4997.4  319.16  5000.7  319.66  5034.9  320.62  5176.6  321.25
  5181.5  321.16  5255.5  324.46  5483.1  326.91  5787.2  329.86  5952.9  328.53
  6025.8  329.82  6098.6   329.5  6240.1  336.94  6297.1  336.28    6339  335.11
#Mann= 12 ,-1 , 0
  3632.9     .05       0  3943.7     .16       0  4153.6     .05       0
  4994.7     .03       0  5000.7     .05       0  5034.9     .12       0
  5176.6     .16       0  5181.5     .12       0  5483.1     .16       0
  5952.9     .12       0  6025.8     .16       0  6297.1     .12       0
Bank Sta=4381.7,5255.5
XS Rating Curve= 0 ,0
Exp/Cntr=0.3,0.1

Type RM Length L Ch R = 1 ,106058  ,350,350,350
BEGIN DESCRIPTION:
Mapping XS f3deeeea
END DESCRIPTION:
XS GIS Cut Line= 3
      3722225.55     10660727.65      3720600.53     10661060.99
      3719615.38     10662114.75
#Sta/Elev= 30
  3613.8  348.02  3670.9  342.39  3783.2  336.09  3804.7  337.62  3834.2  334.22
  4089.4  331.16  4399.3   323.9  4477.9  322.01    4804  319.26  4926.5  320.99
    4996  318.67  4998.8  318.17    5002  318.67  5028.6  319.34  5079.6  324.92
  5120.5  324.76  5222.6  319.03  5456.7  322.92  5576.9  319.56  5612.5  320.31
  5644.4   323.9  5652.5  324.47  5966.2  329.02  6101.4  328.53  6206.6  326.42
  6297.1   327.4  6455.3  330.72  6560.2  330.46  6714.4  337.59  6715.2  337.59
#Mann= 10 ,-1 , 0
  3613.8     .05       0  4477.9     .12       0    4996     .07       0
    5002     .12       0  5644.4     .16       0  5652.5     .12       0
  6101.4     .16       0  6297.1     .12       0  6455.3     .16       0
  6714.4     .12       0
#XS Ineff= 1 ,-1
 5100.61 6505.59  324.85
Permanent Ineff=
       F
Bank Sta=4399.3,5644.4
XS Rating Curve= 0 ,0
Exp/Cntr=0.3,0.1

Type RM Length L Ch R = 1 ,105708  ,577,577,577
BEGIN DESCRIPTION:
LAKE CREEK 150.0
END DESCRIPTION:
XS GIS Cut Line= 4
      3721390.57     10659645.11       3720761.5     10660684.74
      3719880.05       10661414.       3719615.7     10662035.89
#Sta/Elev= 30
  3668.7  367.05  3747.9  369.13  4130.5  363.27  4182.8  360.26  4320.5  344.04
  4394.2  332.15  4415.5  331.67  4422.7  328.57  4473.7  325.71  4481.1  323.47
  4562.9  320.34  4697.7  317.89  4700.4  317.39  4703.7  317.89  4853.9  319.76
  5038.5  318.24  5094.5  324.04  5181.5  320.65  5215.7  319.61  5371.9  319.45
  5443.6  324.41  5556.9  324.04  5662.9   327.4  5936.6  328.04  6024.4   327.2
  6214.9  329.32  6351.8  330.42  6528.2  325.49  6577.6  326.16  6703.6  334.09
#Mann= 11 ,-1 , 0
  3668.7     .16       0  3747.9     .12       0  4697.7     .07       0
  4703.7     .12       0  5181.5     .16       0  5215.7     .12       0
  5662.9     .16       0  5936.6     .12       0  6024.4     .16       0
  6214.9     .12       0  6577.6     .16       0
#XS Ineff= 1 ,-1
 5097.05  5918.7  324.07
Permanent Ineff=
       F
Bank Sta=4473.7,5443.6
XS Rating Curve= 0 ,0
Exp/Cntr=0.3,0.1

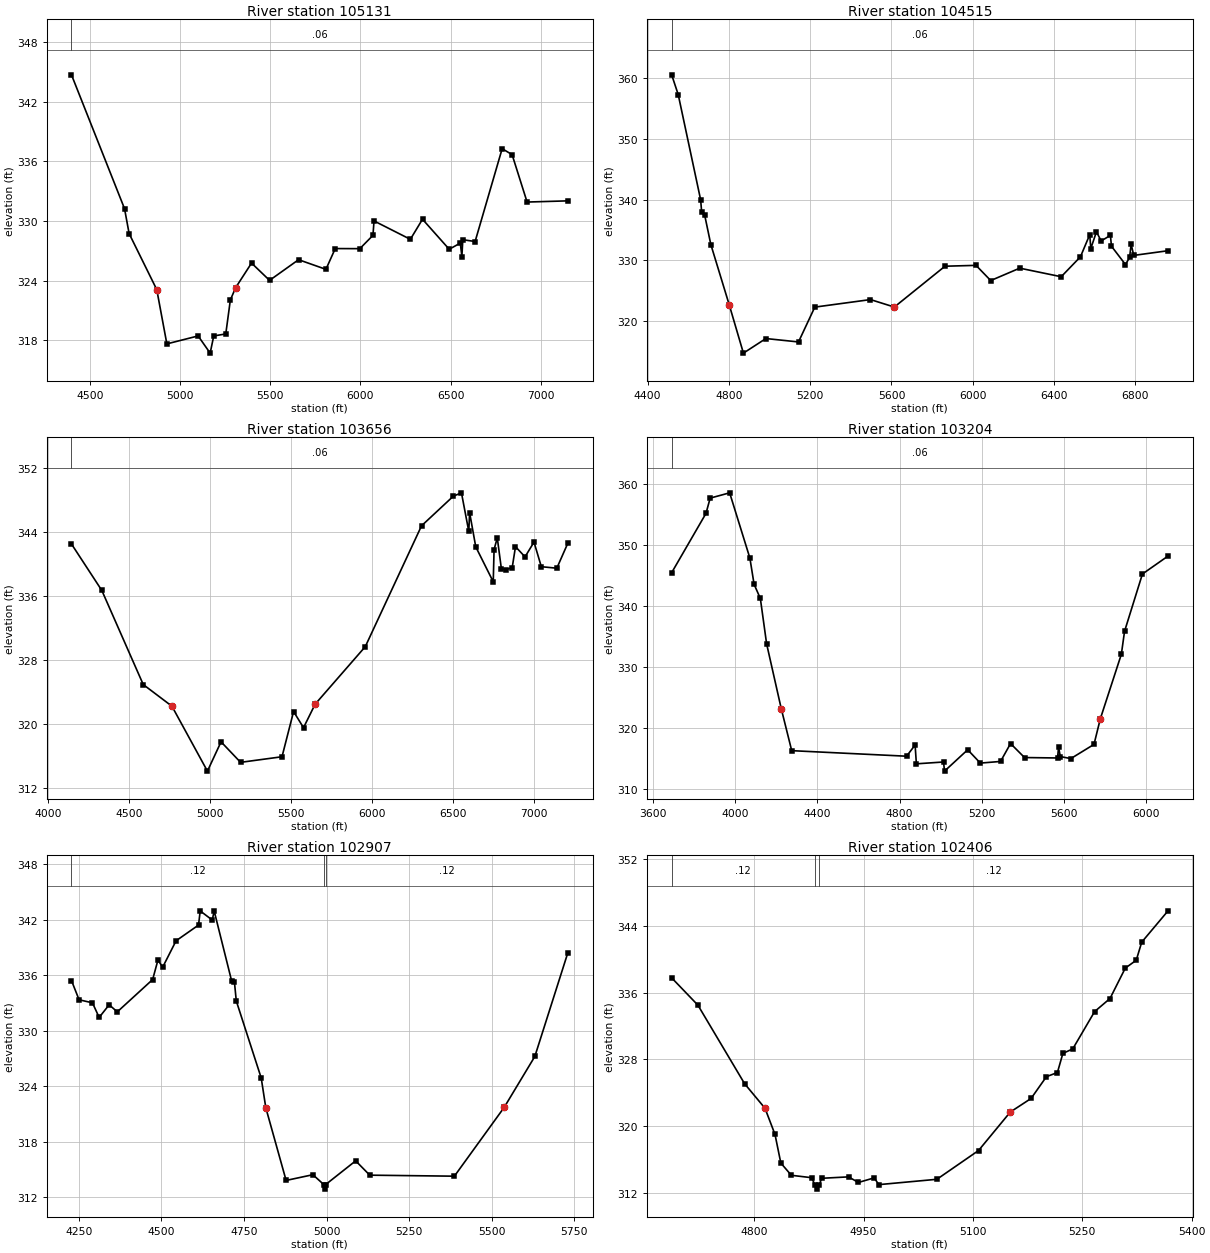
Type RM Length L Ch R = 1 ,105131  ,616,616,616
BEGIN DESCRIPTION:
LAKE CREEK 149.0
END DESCRIPTION:
XS GIS Cut Line= 4
      3720483.72     10659886.14      3720178.17     10660733.35
      3719733.72     10661434.74      3719502.58     10662431.52
#Sta/Elev= 30
  4396.7   344.7  4691.1  331.23  4716.5  328.73  4869.9  323.09  4925.9  317.63
  5099.4  318.43  5166.1   316.7  5186.1  318.43  5252.8  318.63  5278.2  322.05
  5307.7  323.29  5395.8  325.76  5495.8  324.02  5656.8   326.1  5808.5  325.13
  5860.2  327.22  5996.6  327.21  6069.5  328.55  6075.4     330    6277  328.15
  6344.4  330.17  6492.6  327.15  6554.1  327.77  6562.9  326.42    6568  328.11
  6636.3  327.93  6786.4  337.27  6841.6  336.67  6924.7   331.9  7150.9  332.02
#Mann= 1 ,-1 , 0
  4396.7     .06       0
Bank Sta=4869.9,5307.7
XS Rating Curve= 0 ,0
Exp/Cntr=0.3,0.1

Type RM Length L Ch R = 1 ,104515  ,859,859,859
BEGIN DESCRIPTION:
LAKE CREEK 148.0
END DESCRIPTION:
XS GIS Cut Line= 3
      3719712.89     10660018.09      3719775.39     10660802.79
      3719449.26     10662425.56
#Sta/Elev= 30
  4518.5  360.54  4550.7  357.29    4661  339.98  4666.1  337.97  4681.1  337.43
  4711.2  332.62  4801.5  322.72  4871.5  314.75  4982.1  317.15  5142.6  316.59
  5222.8  322.32  5496.8  323.56  5614.1  322.33  5863.4  329.05  6016.1  329.19
  6088.4  326.69  6231.2  328.73  6435.2  327.32  6529.9   330.6  6575.7  334.25
  6580.8  331.95  6608.6  334.71  6631.7  333.21  6677.4  334.12  6682.5  332.34
  6751.4  329.33  6771.8  330.49  6779.2  332.66  6792.2  330.83  6960.9   331.6
#Mann= 1 ,-1 , 0
  4518.5     .06       0
Bank Sta=4801.5,5614.1
XS Rating Curve= 0 ,0
Exp/Cntr=0.3,0.1

Type RM Length L Ch R = 1 ,103656  ,452,452,452
BEGIN DESCRIPTION:
LAKE CREEK 147.0
END DESCRIPTION:
XS GIS Cut Line= 3
      3719317.07     10659802.75      3719087.89     10660469.46
      3718611.75     10662776.34
#Sta/Elev= 30
    4146  342.53  4333.2  336.71  4588.5  324.93  4765.3  322.22  4984.2  314.09
  5068.2  317.76  5188.7  315.19    5444  315.89  5515.4  321.55  5576.7  319.53
  5648.2  322.47  5957.6  329.68  6304.3  344.81  6500.3  348.52  6550.5  348.94
  6595.7  344.11  6600.8  346.47  6638.6  342.18  6746.5   337.8  6751.6  341.84
  6771.4   343.3  6796.7  339.42  6822.4  339.31  6863.3  339.57  6883.7   342.2
  6942.4  340.92  6997.8  342.77  7042.9  339.69  7138.4   339.5  7206.5  342.64
#Mann= 1 ,-1 , 0
    4146     .06       0
Bank Sta=4765.3,5648.2
XS Rating Curve= 0 ,0
Exp/Cntr=0.3,0.1

Type RM Length L Ch R = 1 ,103204  ,297,297,297
BEGIN DESCRIPTION:
LAKE CREEK 146.0
END DESCRIPTION:
XS GIS Cut Line= 3
      3718492.88     10659416.09      3718712.89     10660587.51
      3718448.99       10661782.
#Sta/Elev= 30
  3690.7  345.51  3857.6  355.24    3878  357.75  3972.8  358.62  4071.3   347.9
  4091.7   343.6  4122.2  341.27  4152.7  333.82    4224  323.16  4274.8  316.28
  4833.6  315.37  4875.2  317.21  4881.4  314.12  5013.5  314.42  5018.4  312.92
  5131.1  316.43  5192.6  314.24  5290.9  314.51  5339.6  317.45  5407.6  315.15
  5568.2  315.08  5573.3  316.85  5581.7  315.31    5633  314.98  5745.6  317.31
  5776.3   321.5  5878.7  332.11  5894.3  335.88  5981.2  345.29  6105.9  348.24
#Mann= 1 ,-1 , 0
  3690.7     .06       0
Bank Sta=4224,5776.3
XS Rating Curve= 0 ,0
Exp/Cntr=0.3,0.1

Type RM Length L Ch R = 1 ,102907  ,501,501,501
BEGIN DESCRIPTION:
LAKE CREEK 145.0
END DESCRIPTION:
XS GIS Cut Line= 4
      3718232.46     10660097.49      3718299.61     10660510.19
      3718449.61     10660810.19      3717999.63     10661410.16
#Sta/Elev= 30
  4227.5  335.43  4250.5  333.35    4291  333.02  4311.3  331.44  4341.7  332.81
  4366.2  332.04  4473.4  335.54  4489.3  337.64  4503.8  336.88  4544.3  339.73
  4612.3  341.43  4617.4  342.96    4654  341.97  4659.6  342.97  4712.7  335.37
  4721.1  335.25  4726.7  333.22  4802.2  324.89  4816.1  321.67  4877.6  313.81
  4958.7  314.43  4991.6  313.37  4994.3  312.87  4997.6  313.37  5088.3  315.93
    5131  314.38  5387.3  314.27  5538.3  321.72    5631  327.22    5731  338.44
#Mann= 3 ,-1 , 0
  4227.5     .12       0  4991.6     .07       0  4997.6     .12       0
Bank Sta=4816.1,5538.3
XS Rating Curve= 0 ,0
Exp/Cntr=0.3,0.1

Type RM Length L Ch R = 1 ,102406  ,439,439,439
BEGIN DESCRIPTION:
LAKE CREEK 144.0
END DESCRIPTION:
XS GIS Cut Line= 3
       3718199.6      10660560.2      3717999.61     10660810.19
       3717699.6     10661010.19
#Sta/Elev= 30
  4686.9  337.78  4722.9   334.5  4786.9  325.08  4814.9  322.13  4828.6  318.99
  4836.6  315.56    4851  314.09    4879   313.8  4883.2  312.93  4885.9  312.43
  4889.2  312.93  4892.6  313.73  4929.4   313.9    4943  313.23  4964.6  313.78
    4971  312.97  5050.6  313.61  5107.7  317.06  5151.3  321.68  5179.8  323.31
  5200.8  325.92  5215.9  326.42  5223.4  328.72  5236.9  329.25  5266.9  333.73
    5288   335.3    5309  338.95    5324  339.89  5331.5  342.06  5367.6  345.82
#Mann= 3 ,-1 , 0
  4686.9     .12       0  4883.2     .07       0  4889.2     .12       0
Bank Sta=4814.9,5151.3
XS Rating Curve= 0 ,0
Exp/Cntr=0.3,0.1

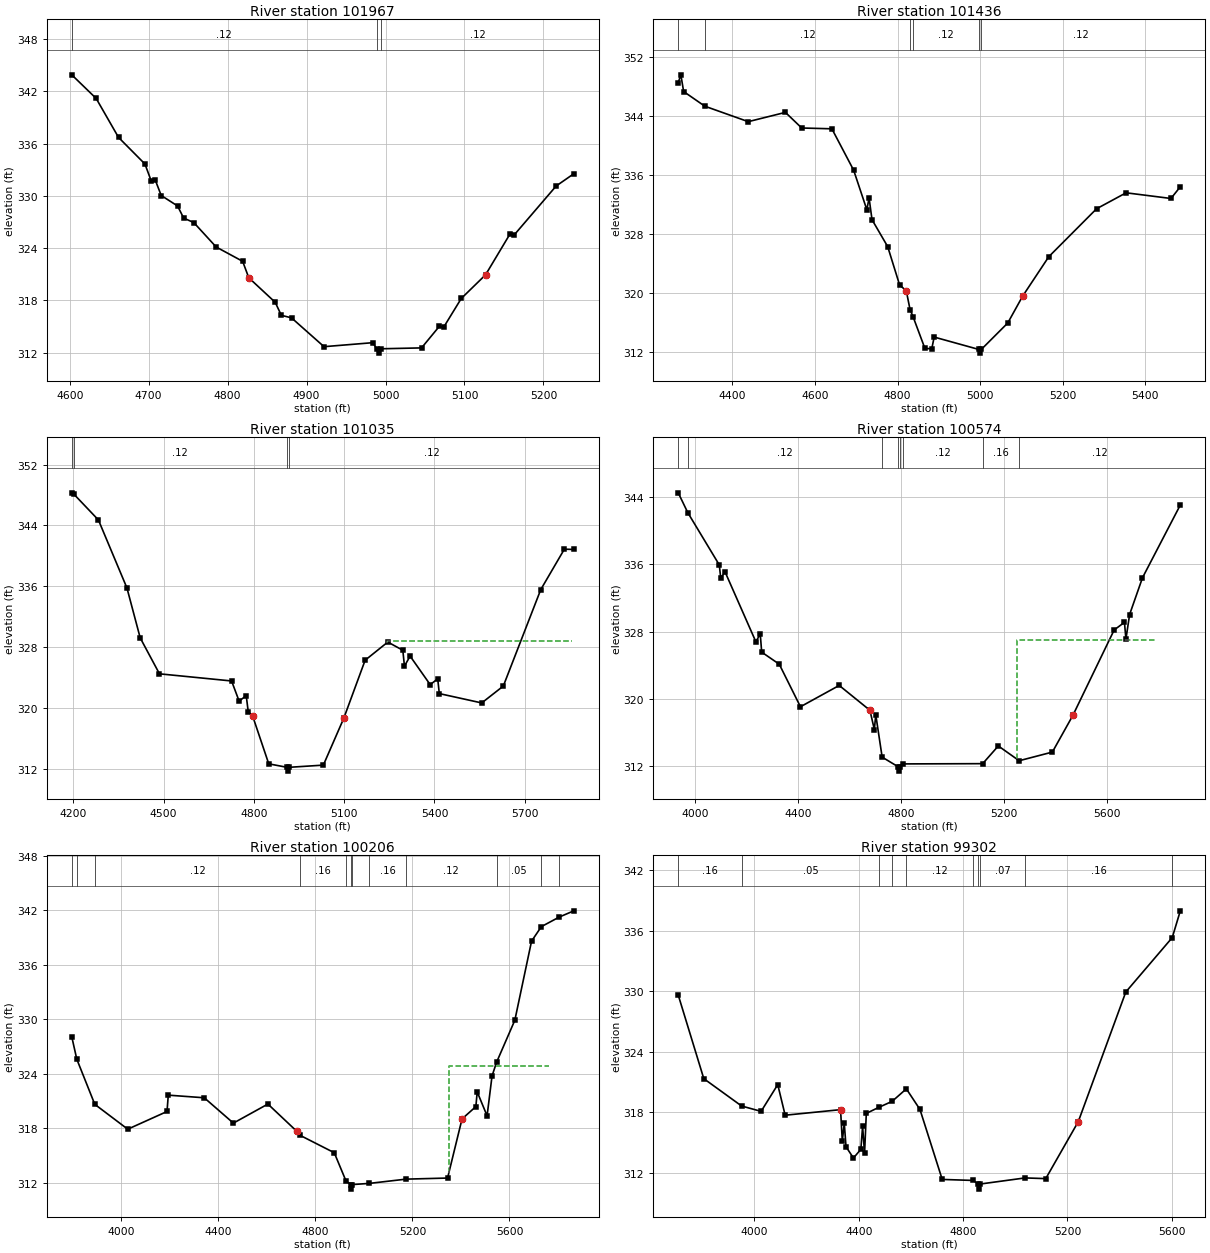
Type RM Length L Ch R = 1 ,101967  ,531,531,531
BEGIN DESCRIPTION:
LAKE CREEK 143.0
END DESCRIPTION:
XS GIS Cut Line= 3
      3718199.57      10660360.2      3717799.61     10660460.19
      3717599.59      10660560.2
#Sta/Elev= 30
  4602.6   343.9  4633.5  341.19  4661.8  336.72  4695.3  333.66  4703.1  331.75
  4708.2  331.86  4715.9  330.05  4736.6  328.85  4744.3  327.46  4757.2  326.94
  4785.5  324.14    4819   322.5  4826.8  320.61  4860.3  317.79    4868   316.3
  4880.9  316.01  4922.1   312.7    4984  313.16  4988.7  312.46  4991.4  311.96
  4994.7  312.46  5045.6  312.56    5068  315.02  5073.6  314.93  5095.9  318.23
  5126.7  320.95  5157.4   325.6    5163  325.53  5216.1  331.14  5238.5  332.55
#Mann= 3 ,-1 , 0
  4602.6     .12       0  4988.7     .07       0  4994.7     .12       0
Bank Sta=4826.8,5126.7
XS Rating Curve= 0 ,0
Exp/Cntr=0.3,0.1

Type RM Length L Ch R = 1 ,101436  ,401,401,401
BEGIN DESCRIPTION:
LAKE CREEK 142.0
END DESCRIPTION:
XS GIS Cut Line= 3
      3718371.37     10659732.92      3717714.28      10660053.9
       3717449.6      10660460.2
#Sta/Elev= 30
  4268.7  348.53    4275  349.58  4281.8  347.31  4333.1  345.32  4438.3  343.22
  4528.3  344.48  4567.8  342.36  4640.9  342.25  4693.6  336.63  4725.5  331.27
    4731  332.85  4738.1  329.91  4776.1  326.25  4804.9  321.05  4821.1  320.25
  4830.2  317.71  4837.7  316.71  4866.2  312.43  4882.8  312.38  4888.7  313.97
  4996.8  312.29  4999.6  311.79  5002.8  312.29  5066.9  315.88    5103  319.53
  5166.4  324.89    5282  331.39  5353.6  333.56  5462.2  332.79  5484.9  334.38
#Mann= 6 ,-1 , 0
  4268.7     .16       0  4333.1     .12       0  4830.2     .16       0
  4837.7     .12       0  4996.8     .07       0  5002.8     .12       0
Bank Sta=4821.1,5103
XS Rating Curve= 0 ,0
Exp/Cntr=0.3,0.1

Type RM Length L Ch R = 1 ,101035  ,461,461,461
BEGIN DESCRIPTION:
LAKE CREEK 141.0
END DESCRIPTION:
XS GIS Cut Line= 2
      3717810.11     10658997.25      3717226.79     10660559.72
#Sta/Elev= 30
  4195.2  348.29  4201.1  348.16  4283.7  344.72  4378.5  335.77  4422.5  329.21
  4486.5  324.48  4726.1  323.54  4751.1  320.89  4774.7  321.61  4781.4  319.49
  4796.1  318.92  4849.5  312.64  4910.5  312.18  4913.3  311.68  4916.5  312.18
  5030.9  312.47  5098.8  318.64  5169.7  326.27    5245  328.66  5294.9  327.58
  5300.3  325.49  5319.1  326.81  5385.8  323.06  5410.8  323.82  5416.1  321.88
    5557  320.65  5628.7  322.87  5753.1  335.56  5831.5  340.88    5863  340.84
#Mann= 4 ,-1 , 0
  4195.2      .1       0  4201.1     .12       0  4910.5     .07       0
  4916.5     .12       0
#XS Ineff= 1 ,-1
 5241.87 5857.72  328.76
Permanent Ineff=
       F
Bank Sta=4796.1,5098.8
XS Rating Curve= 0 ,0
Exp/Cntr=0.3,0.1

Type RM Length L Ch R = 1 ,100574  ,368,368,368
BEGIN DESCRIPTION:
LAKE CREEK 140.0
END DESCRIPTION:
XS GIS Cut Line= 3
       3717462.9     10658761.11      3717087.89     10659552.79
      3717108.68     10660627.18
#Sta/Elev= 30
  3933.8  344.53  3970.9  342.17  4093.3  335.94  4098.8   334.4    4116  335.09
  4235.3  326.79  4252.5   327.7    4258  325.55  4326.3  324.11  4408.6  319.04
  4559.2  321.58  4678.5  318.62  4695.7  316.33  4701.2  318.09    4726  313.04
  4789.2  311.87    4792  311.37  4795.2  311.87  4805.4  312.23  5116.6  312.26
  5177.3  314.37  5258.4  312.61  5387.3  313.64  5467.3  318.03  5627.4  328.19
  5667.4   329.1  5673.1   327.1  5687.4  330.03  5737.4  334.41  5884.4  343.08
#Mann= 8 ,-1 , 0
  3933.8     .05       0  3970.9     .12       0    4726     .16       0
  4789.2     .07       0  4795.2     .16       0  4805.4     .12       0
  5116.6     .16       0  5258.4     .12       0
#XS Ineff= 1 ,-1
 5250.51 5789.13  326.94
Permanent Ineff=
       F
Bank Sta=4678.5,5467.3
XS Rating Curve= 0 ,0
Exp/Cntr=0.3,0.1

Type RM Length L Ch R = 1 ,100206  ,904,904,904
BEGIN DESCRIPTION:
LAKE CREEK 139.0
END DESCRIPTION:
XS GIS Cut Line= 3
      3717018.45     10658587.51      3716733.72     10659629.18
      3716921.22     10660601.39
#Sta/Elev= 30
  3795.3  328.09  3815.9  325.63  3890.2  320.65  4026.1  317.91    4188  319.86
  4193.2  321.66  4341.6  321.37  4461.6  318.58  4603.9  320.68    4723  317.68
  4736.2  317.24  4877.5  315.32  4925.1  312.26  4944.5  311.81  4947.2  311.31
  4950.5  311.81  5021.6  311.94  5173.3  312.41  5344.7  312.53  5404.3  319.04
  5461.3   320.4  5466.9  322.02  5507.6  319.38    5528  323.77    5547   325.3
    5622  329.91  5690.9  338.62  5731.4  340.22  5805.6  341.28  5865.3  341.96
#Mann= 12 ,-1 , 0
  3795.3     .05       0  3815.9     .16       0  3890.2     .12       0
  4736.2     .16       0  4925.1     .12       0  4944.5     .07       0
  4950.5     .12       0  5021.6     .16       0  5173.3     .12       0
    5547     .05       0  5731.4     .12       0  5805.6     .05       0
#XS Ineff= 1 ,-1
 5349.59 5761.18  324.83
Permanent Ineff=
       F
Bank Sta=4723,5404.3
XS Rating Curve= 0 ,0
Exp/Cntr=0.3,0.1

Type RM Length L Ch R = 1 ,99302   ,259,259,259
BEGIN DESCRIPTION:
LAKE CREEK 138.0
END DESCRIPTION:
XS GIS Cut Line= 3
      3716960.28     10658572.64      3716173.81     10659458.08
      3715533.43     10659829.93
#Sta/Elev= 30
  3707.8  329.61  3805.8  321.33  3950.8  318.62  4025.5  318.09  4089.3  320.74
  4117.7  317.71  4330.1  318.26  4336.8  315.15  4344.3  316.92    4351  314.59
  4379.4  313.47  4407.9  314.33  4414.6  316.61  4422.1  313.93  4428.8  317.89
  4477.7   318.5  4527.7  319.08  4582.3  320.32  4634.5  318.28  4719.8  311.35
  4839.2  311.25  4858.1  310.89  4860.9  310.39  4864.1  310.89  5037.5   311.5
  5116.7  311.43  5241.4  317.07  5423.6  329.91  5601.7   335.3  5632.6  337.95
#Mann= 10 ,-1 , 0
  3707.8     .16       0  3950.8     .05       0  4477.7     .16       0
  4527.7     .05       0  4582.3     .12       0  4839.2     .07       0
  4858.1     .07       0  4864.1     .07       0  5037.5     .16       0
  5601.7     .05       0
#XS Ineff= 1 ,-1
 3769.31  4574.7  319.15
Permanent Ineff=
       F
Bank Sta=4330.1,5241.4
XS Rating Curve= 0 ,0
Exp/Cntr=0.3,0.1

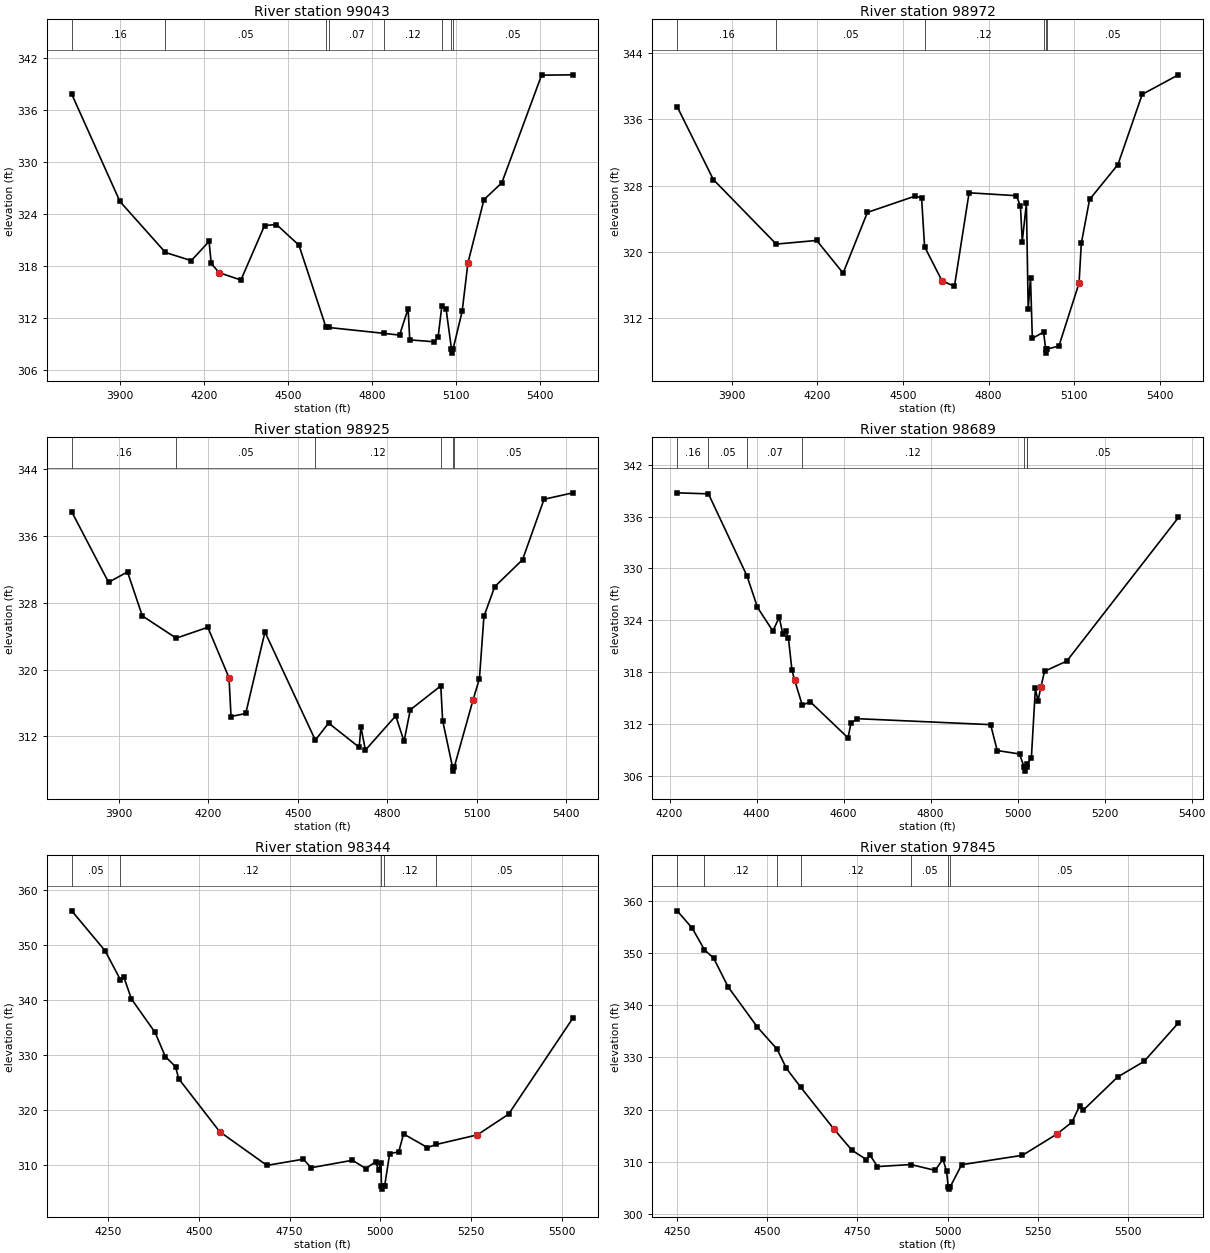
Type RM Length L Ch R = 1 ,99043   ,71,71,71
BEGIN DESCRIPTION:
Mapping XS fafe9112
END DESCRIPTION:
XS GIS Cut Line= 4
       3716849.1     10658486.46       3716313.1     10659089.73
      3715881.24     10659365.34      3715517.73      10659666.1
#Sta/Elev= 30
  3727.8  337.86  3900.1  325.47  4062.7  319.58  4155.1  318.64  4218.7  320.86
  4226.2  318.32  4254.5  317.25  4332.4   316.4  4416.9  322.69  4459.5  322.81
  4539.8  320.42  4635.6  311.03    4646  310.92  4844.4  310.24  4899.4  310.04
  4929.9  313.09  4935.8  309.49  5023.8  309.27  5037.2  309.83  5050.5  313.41
  5065.6  313.07  5084.8  308.46  5087.5  307.96  5090.8  308.46    5123  312.77
  5143.8  318.39  5201.1  325.68  5264.9  327.63  5406.9  340.05  5518.9  340.09
#Mann= 8 ,-1 , 0
  3727.8     .16       0  4062.7     .05       0  4635.6     .12       0
    4646     .07       0  4844.4     .12       0  5050.5     .05       0
  5084.8     .07       0  5090.8     .05       0
#XS Ineff= 1 ,-1
 3931.91 4470.53   319.2
Permanent Ineff=
       F
Bank Sta=4254.5,5143.8
XS Rating Curve= 0 ,0
Exp/Cntr=0.3,0.1

Type RM Length L Ch R = 1 ,98972   ,47,47,47
BEGIN DESCRIPTION:
Mapping XS 771dc158
END DESCRIPTION:
XS GIS Cut Line= 5
      3716796.23     10658478.88      3716374.33     10658986.72
      3716020.16     10659213.28      3715934.22     10659270.58
      3715486.28     10659624.76
#Sta/Elev= 30
  3709.4  337.53  3835.9  328.73  4056.1  320.93  4197.8  321.37  4290.3  317.42
  4375.4  324.76  4541.4  326.72  4565.1  326.51  4575.6  320.61  4636.4   316.5
  4680.1  315.82  4731.4  327.13  4897.1  326.78  4911.3   325.5  4917.6  321.23
  4932.1  325.85  4938.4  313.08  4946.5  316.83  4952.9  309.53  4992.2  310.29
  4999.6  308.25  5002.3  307.75  5005.6  308.25  5045.9   308.6  5116.4  316.21
  5124.4  321.02  5153.3  326.32  5252.6  330.54  5337.6  339.03  5464.4  341.39
#Mann= 6 ,-1 , 0
  3709.4     .16       0  4056.1     .05       0  4575.6     .12       0
  4992.2     .05       0  4999.6     .03       0  5005.6     .05       0
#XS Ineff= 1 ,-1
 4054.88 4841.46  317.66
Permanent Ineff=
       F
Bank Sta=4636.4,5116.4
XS Rating Curve= 0 ,0
Exp/Cntr=0.3,0.1

Type RM Length L Ch R = 1 ,98925   ,236,236,236
BEGIN DESCRIPTION:
Mapping XS 1d094670
END DESCRIPTION:
XS GIS Cut Line= 3
      3716736.27     10658462.57      3716239.32      10659026.8
       3715463.5     10659538.23
#Sta/Elev= 30
  3741.7   338.9  3865.2  330.46  3928.8   331.7  3978.4  326.44  4092.2  323.77
  4198.2  325.07  4269.3  319.02    4276  314.39  4325.3  314.75  4389.8  324.51
  4558.8  311.56  4603.3   313.6  4705.8  310.71  4711.7  313.12  4726.8  310.37
  4828.6  314.47  4856.3  311.41  4877.3  315.19  4979.6  318.06  4985.8  313.91
  5018.9  308.35  5021.6  307.85  5024.9  308.35  5088.2  316.42  5109.2  318.91
  5124.3  326.37  5160.4  329.93  5253.8  333.16    5326   340.4  5422.8  341.17
#Mann= 6 ,-1 , 0
  3741.7     .16       0  4092.2     .05       0  4558.8     .12       0
  4979.6     .05       0  5018.9     .03       0  5024.9     .05       0
#XS Ineff= 1 ,-1
 4163.01 4410.98  318.67
Permanent Ineff=
       F
Bank Sta=4269.3,5088.2
XS Rating Curve= 0 ,0
Exp/Cntr=0.3,0.1

Type RM Length L Ch R = 1 ,98689   ,345,345,345
BEGIN DESCRIPTION:
LAKE CREEK 137.0
END DESCRIPTION:
XS GIS Cut Line= 3
      3716364.53     10658626.44       3715793.6     10659051.83
      3715424.23     10659291.14
#Sta/Elev= 30
  4217.5  338.74  4289.3  338.62    4378  329.13    4402   325.5  4437.4  322.77
    4452  324.37  4460.4  322.39  4466.6  322.81  4473.1  321.99  4481.2  318.25
  4487.5  317.08  4505.1  314.19  4522.9  314.62  4610.2  310.43  4616.8  312.13
  4631.4  312.65  4937.9  311.96  4953.1  308.97  5004.5  308.57  5014.6  307.09
  5017.4  306.59  5020.6  307.09  5022.6  307.46  5031.6  308.13  5040.8  316.14
  5046.7  314.68  5053.4   316.3  5061.9  318.13    5113   319.3  5369.6  335.89
#Mann= 7 ,-1 , 0
  4217.5     .16       0  4289.3     .05       0    4378     .07       0
  4505.1     .12       0  5014.6     .07       0  5020.6     .12       0
  5022.6     .05       0
Bank Sta=4487.5,5053.4
XS Rating Curve= 0 ,0
Exp/Cntr=0.3,0.1

Type RM Length L Ch R = 1 ,98344   ,499,499,499
BEGIN DESCRIPTION:
LAKE CREEK 136.0
END DESCRIPTION:
XS GIS Cut Line= 3
      3716399.64     10658260.16      3715699.61     10658760.19
       3715199.6     10658910.19
#Sta/Elev= 30
  4148.9  356.29  4241.1  349.01    4283  343.78  4292.7  344.22  4313.6  340.25
  4378.7  334.18    4407  329.79  4435.3  327.94  4443.9  325.75  4556.9  316.12
  4687.2  309.99    4788  311.12  4808.9  309.56  4923.2  310.92    4960  309.42
  4987.1  310.65  4995.7  309.09  5001.8  310.49  5003.1  306.17  5005.9  305.67
  5009.1  306.17  5011.8  306.17  5025.7  312.11  5050.9  312.45    5064  315.71
  5130.1  313.23    5154  313.79  5267.6  315.54  5353.7   319.3  5531.2  336.79
#Mann= 5 ,-1 , 0
  4148.9     .05       0    4283     .12       0  5003.1     .07       0
  5009.1     .12       0    5154     .05       0
Bank Sta=4556.9,5267.6
XS Rating Curve= 0 ,0
Exp/Cntr=0.3,0.1

Type RM Length L Ch R = 1 ,97845   ,554,554,554
BEGIN DESCRIPTION:
LAKE CREEK 135.0
END DESCRIPTION:
XS GIS Cut Line= 3
      3716399.61     10658210.19      3715649.61     10658310.19
       3715049.6     10658510.19
#Sta/Elev= 30
  4250.4  358.16    4292  354.83  4325.9  350.68  4351.3  349.08  4391.6  343.54
  4472.3  335.86  4527.4  331.57  4553.1   327.9  4592.7  324.28  4684.2   316.3
  4734.6  312.19    4775  310.39  4785.1  311.23  4805.3  309.05  4898.1  309.44
  4965.4  308.32  4986.9   310.5  4996.9  308.11  5001.5  305.22  5004.3  304.72
  5007.5  305.22  5038.7  309.41  5207.3  311.22  5302.2  315.27  5344.3  317.56
  5365.4  320.65    5376   319.9  5470.8  326.24  5544.6  329.26  5639.5  336.64
#Mann= 7 ,-1 , 0
  4250.4     .05       0  4325.9     .12       0  4527.4     .16       0
  4592.7     .12       0  4898.1     .05       0  5001.5     .03       0
  5007.5     .05       0
Bank Sta=4684.2,5302.2
XS Rating Curve= 0 ,0
Exp/Cntr=0.3,0.1