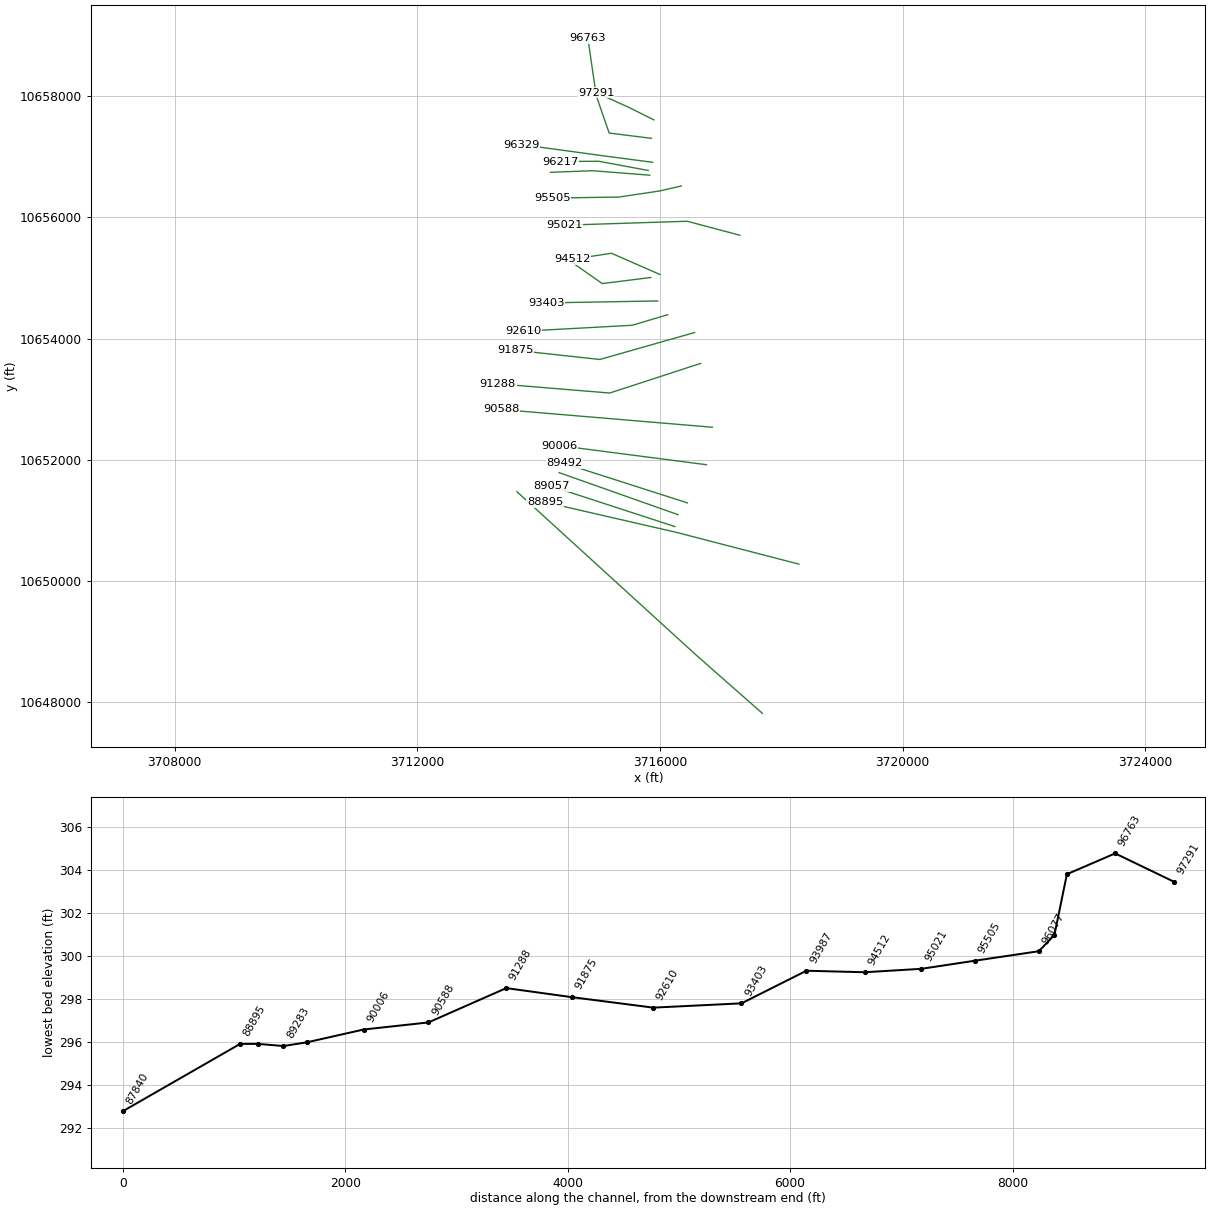
HEC-RAS study LAKE CREEK.prj: LAKE CREEK Base Level Engineering

--- LAKE CREEK.g01 (geometry) --- (continued)

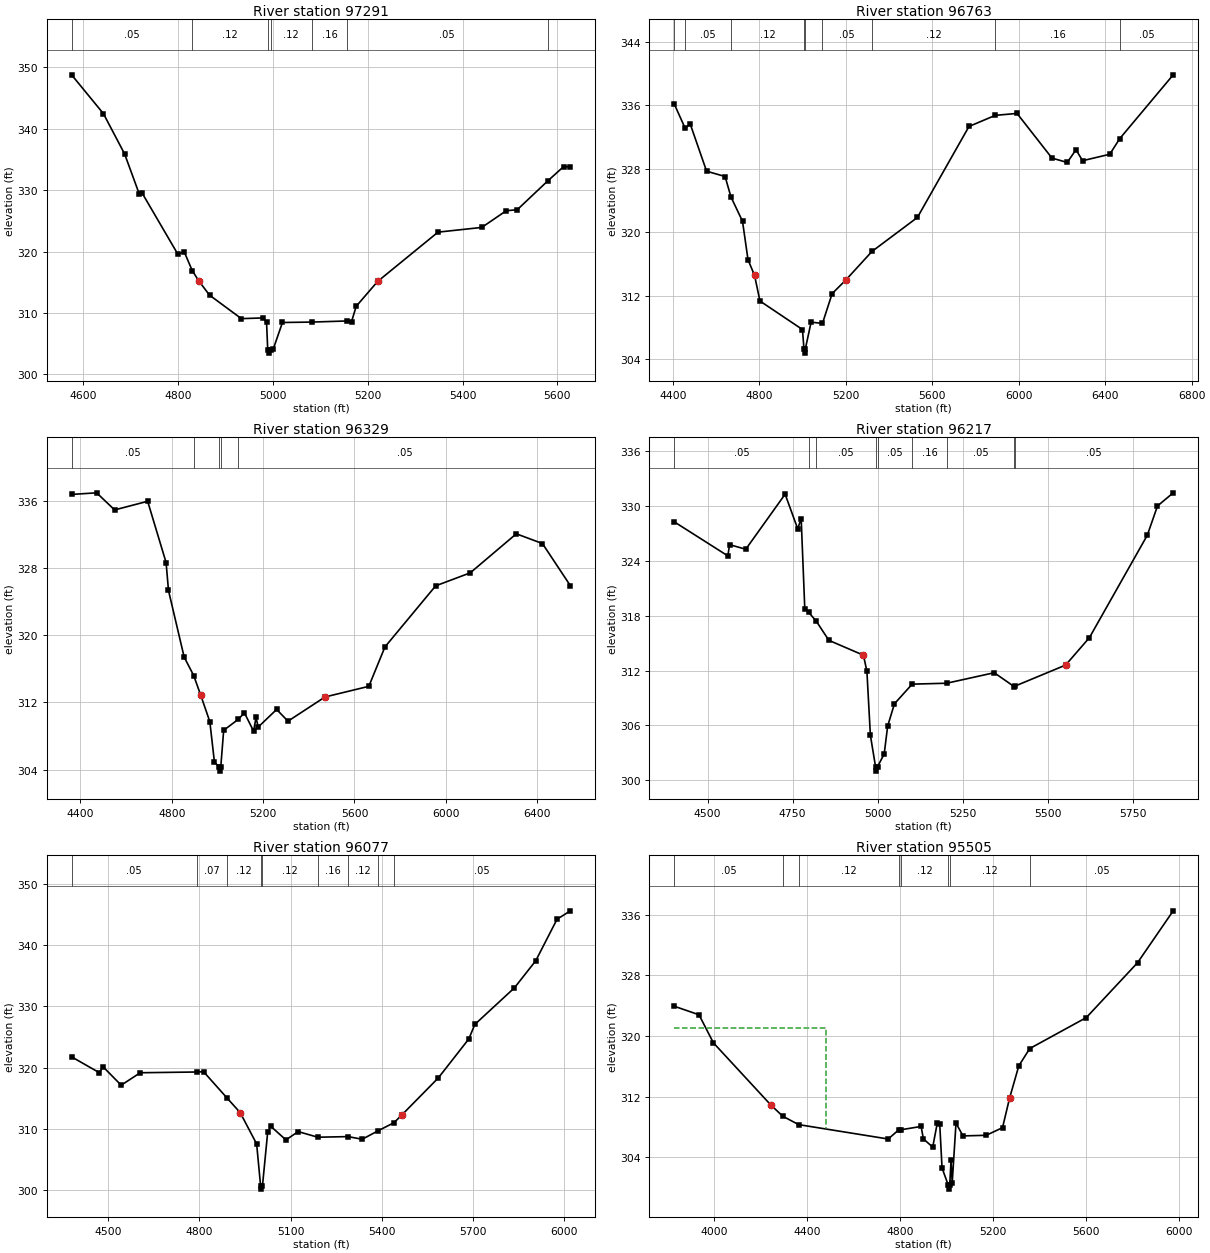
Type RM Length L Ch R = 1 ,97291   ,528,528,528
BEGIN DESCRIPTION:
LAKE CREEK 134.0
END DESCRIPTION:
XS GIS Cut Line= 3
      3715899.59      10657610.2      3715499.61     10657810.19
      3714949.65     10658060.17
#Sta/Elev= 30
    4576   348.8  4643.1  342.47  4687.8   335.9  4718.5   329.4  4724.1  329.61
  4799.6  319.62  4813.6  319.92  4830.3   316.9  4844.3   315.2  4866.7  312.91
  4933.8  309.08  4978.5  309.19  4986.9  308.52  4989.4  303.96  4992.2  303.46
  4995.4  303.96  5000.8  304.07  5020.4  308.45  5082.7  308.52  5156.3   308.7
    5166  308.58  5175.9  311.09  5220.9  315.13  5348.3  323.17  5440.6  323.94
  5492.2  326.66  5515.3  326.82  5579.1  331.48  5613.1  333.85  5627.3   333.8
#Mann= 7 ,-1 , 0
    4576     .05       0  4830.3     .12       0  4989.4     .07       0
  4995.4     .12       0  5082.7     .16       0  5156.3     .05       0
  5579.1     .12       0
Bank Sta=4844.3,5220.9
XS Rating Curve= 0 ,0
Exp/Cntr=0.3,0.1

Type RM Length L Ch R = 1 ,96763   ,434,434,434
BEGIN DESCRIPTION:
LAKE CREEK 133.0
END DESCRIPTION:
XS GIS Cut Line= 4
      3715857.43     10657306.14      3715162.97     10657392.95
      3714949.61     10658010.19      3714812.29     10658955.32
#Sta/Elev= 30
  4406.6  336.09  4456.2  333.08  4479.8  333.61  4555.4  327.68    4641  327.01
  4668.3  324.43  4721.6  321.38  4747.1  316.53  4777.3  314.57  4802.3  311.34
    4999  307.75  5006.1  305.28  5008.8  304.78  5012.1  305.28  5039.1  308.68
  5091.6  308.52  5136.3  312.27  5198.8  313.96  5320.7  317.58    5531  321.86
  5769.6  333.31  5891.4  334.71    5992  334.95  6153.6  329.33  6224.4  328.78
  6264.8  330.39  6295.1     329  6420.9  329.81  6467.2  331.78  6714.6  339.81
#Mann= 9 ,-1 , 0
  4406.6     .12       0  4456.2     .05       0  4668.3     .12       0
  5006.1     .07       0  5012.1     .12       0  5091.6     .05       0
  5320.7     .12       0  5891.4     .16       0  6467.2     .05       0
Bank Sta=4777.3,5198.8
XS Rating Curve= 0 ,0
Exp/Cntr=0.3,0.1

Type RM Length L Ch R = 1 ,96329   ,112,112,112
BEGIN DESCRIPTION:
Mapping XS 63a76d9d
END DESCRIPTION:
XS GIS Cut Line= 3
      3715879.87     10656910.43      3715055.19     10657018.94
      3713715.02     10657201.98
#Sta/Elev= 30
  4361.1  336.83  4470.8  337.02  4549.4  334.98  4694.2  336.01  4774.9   328.7
  4785.4  325.37    4854  317.42  4895.8  315.22  4926.2   312.9  4966.5  309.71
  4986.7  304.86  5008.4  304.31  5011.1  303.81  5014.4  304.31  5027.1  308.68
  5091.9  310.01  5117.8  310.77  5158.2  308.58  5168.7  310.21  5178.3  309.07
  5259.1  311.17  5308.7  309.77    5471  312.66  5662.8  313.93  5733.4  318.63
  5955.5  325.92  6106.9  327.47  6308.7  332.13  6423.1  330.97  6545.5  325.94
#Mann= 5 ,-1 , 0
  4361.1     .05       0  4895.8     .12       0  5008.4     .07       0
  5014.4     .12       0  5091.9     .05       0
Bank Sta=4926.2,5471
XS Rating Curve= 0 ,0
Exp/Cntr=0.3,0.1

Type RM Length L Ch R = 1 ,96217   ,140,140,140
BEGIN DESCRIPTION:
LAKE CREEK 132.0
END DESCRIPTION:
XS GIS Cut Line= 3
      3715806.03     10656775.89      3714990.09     10656927.79
      3714353.36     10656923.46
#Sta/Elev= 30
  4402.7  328.28  4559.8  324.56  4564.8  325.79  4612.5  325.29  4728.2  331.32
  4765.2  327.53  4775.4  328.65    4786  318.79  4797.7  318.37  4820.3  317.38
  4856.8  315.31  4958.5  313.68  4968.7  311.91  4978.9  304.92    4994  301.48
  4996.7  300.98    5000  301.48  5019.5  302.85  5029.7  305.91  5049.7  308.36
  5101.8  310.51  5203.2  310.61  5343.1  311.76  5401.8  310.24  5403.8  310.29
  5553.1   312.6  5623.1  315.61  5793.2  326.82  5823.2  330.03  5869.4  331.47
#Mann= 9 ,-1 , 0
  4402.7     .05       0  4797.7     .07       0  4820.3     .05       0
    4994     .04       0    5000     .05       0  5101.8     .16       0
  5203.2     .05       0  5401.8     .16       0  5403.8     .05       0
Bank Sta=4958.5,5553.1
XS Rating Curve= 0 ,0
Exp/Cntr=0.3,0.1

Type RM Length L Ch R = 1 ,96077   ,572,572,572
BEGIN DESCRIPTION:
Mapping XS 78834839
END DESCRIPTION:
XS GIS Cut Line= 3
      3715832.13     10656697.76      3714890.26     10656771.54
       3714195.8      10656745.5
#Sta/Elev= 30
    4380  321.78  4471.5  319.19  4482.8  320.19    4543  317.16  4605.7  319.19
  4791.2  319.31  4813.8  319.36  4890.7  315.09  4934.2  312.69  4988.3  307.59
  5001.4  300.72  5004.2  300.22  5007.4  300.72  5024.5  309.46  5034.5  310.47
  5084.7  308.24  5124.8   309.6  5189.3  308.68  5288.9  308.78  5335.4  308.35
    5388  309.74  5439.9  311.05  5465.5   312.3  5585.6  318.35  5685.7  324.69
  5705.7  327.07  5835.8  333.03  5905.8  337.44  5975.9  344.21  6019.7  345.58
#Mann= 9 ,-1 , 0
    4380     .05       0  4791.2     .07       0  4890.7     .12       0
  5001.4     .07       0  5007.4     .12       0  5189.3     .16       0
  5288.9     .12       0    5388     .16       0  5439.9     .05       0
Bank Sta=4934.2,5465.5
XS Rating Curve= 0 ,0
Exp/Cntr=0.3,0.1

Type RM Length L Ch R = 1 ,95505   ,484,484,484
BEGIN DESCRIPTION:
LAKE CREEK 131.0
END DESCRIPTION:
XS GIS Cut Line= 4
      3716352.96     10656519.81      3715992.69     10656437.34
      3715324.29     10656337.51      3714226.23     10656320.15
#Sta/Elev= 30
  3830.9  323.93  3936.5  322.81  3998.5   319.1  4244.1  310.93    4296  309.42
  4364.8   308.3  4749.6   306.4  4794.2  307.59  4804.4  307.62    4891  308.06
    4901  306.41    4941  305.33    4961  308.58    4971  308.43    4981  302.58
    5008  300.28  5010.8  299.78    5014  300.28  5019.7  303.57  5024.7  300.61
    5041   308.5    5071  306.81    5171  306.89    5241   307.9    5271  311.77
    5311  316.07    5358  318.35  5601.1  322.44  5821.1  329.68  5974.5  336.54
#Mann= 8 ,-1 , 0
  3830.9     .05       0    4296     .07       0  4364.8     .12       0
  4794.2     .05       0  4804.4     .12       0    5008     .07       0
    5014     .12       0    5358     .05       0
#XS Ineff= 2 , 0
         4480.69  321.01
Permanent Ineff=
       F       F
Bank Sta=4244.1,5271
XS Rating Curve= 0 ,0
Exp/Cntr=0.3,0.1

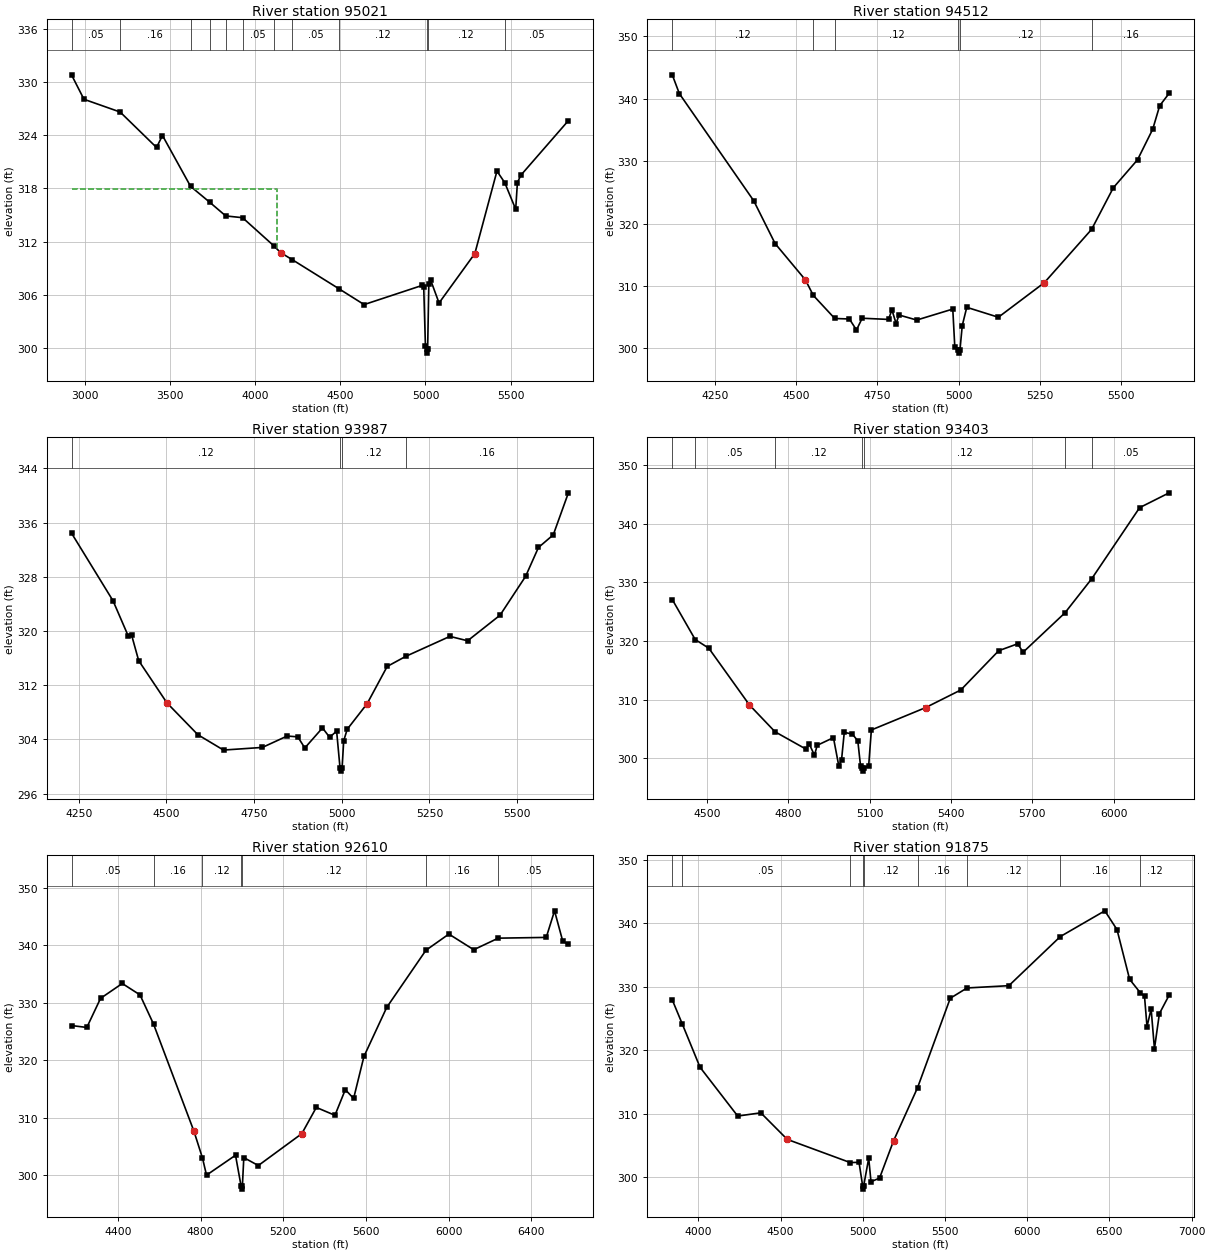
Type RM Length L Ch R = 1 ,95021   ,509,509,509
BEGIN DESCRIPTION:
LAKE CREEK 130.0
END DESCRIPTION:
XS GIS Cut Line= 3
      3717318.02     10655707.14      3716448.42     10655938.21
      3714430.15      10655873.1
#Sta/Elev= 30
  2920.7  330.82  2993.8  328.06  3206.4  326.62  3420.1  322.62  3455.1  323.97
  3620.1  318.23  3732.9  316.43  3826.7  314.89  3925.6  314.69  4109.5  311.51
  4149.5  310.74  4218.6  309.94  4494.1  306.64  4639.7  304.88  4979.9  307.04
  4989.9  306.81  4999.9  300.22  5006.9   299.9  5009.7   299.4  5012.9   299.9
  5019.9  307.24  5029.9  307.68  5079.9  305.06  5290.1  310.64  5420.1  319.95
  5465.8  318.65  5530.2  315.64  5540.2  318.65  5560.2  319.48  5839.8  325.65
#Mann= 12 ,-1 , 0
  2920.7     .05       0  3206.4     .16       0  3620.1     .05       0
  3732.9     .12       0  3826.7     .16       0  3925.6     .05       0
  4109.5     .16       0  4218.6     .05       0  4494.1     .12       0
  5006.9     .07       0  5012.9     .12       0  5465.8     .05       0
#XS Ineff= 2 , 0
         4129.06  317.98
Permanent Ineff=
       F       F
Bank Sta=4149.5,5290.1
XS Rating Curve= 0 ,0
Exp/Cntr=0.3,0.1

Type RM Length L Ch R = 1 ,94512   ,525,525,525
BEGIN DESCRIPTION:
LAKE CREEK 129.0
END DESCRIPTION:
XS GIS Cut Line= 3
      3715999.57      10655060.2      3715199.61     10655410.19
      3714549.63     10655310.19
#Sta/Elev= 30
    4118  343.83  4139.8  340.82    4369  323.65  4434.9  316.79  4528.4  310.96
  4552.5  308.49  4618.6  304.79  4663.7  304.71  4685.5  302.95  4703.1  304.83
  4784.2  304.64  4794.7  306.18  4807.6  303.97  4816.5  305.35  4871.1  304.54
  4982.2   306.3  4988.4  300.25  4998.3  299.74    5001  299.24  5004.3  299.74
  5011.4  303.66  5025.3  306.58  5122.7  304.99  5264.3  310.53  5409.9  319.07
  5476.8  325.74  5551.4  330.22  5598.2  335.12  5619.7  338.89  5648.8  340.87
#Mann= 6 ,-1 , 0
    4118     .12       0  4552.5     .16       0  4618.6     .12       0
  4998.3     .07       0  5004.3     .12       0  5409.9     .16       0
Bank Sta=4528.4,5264.3
XS Rating Curve= 0 ,0
Exp/Cntr=0.3,0.1

Type RM Length L Ch R = 1 ,93987   ,584,584,584
BEGIN DESCRIPTION:
LAKE CREEK 128.0
END DESCRIPTION:
XS GIS Cut Line= 3
      3715849.58     10655010.19      3715049.61     10654910.19
      3714549.63     10655260.17
#Sta/Elev= 30
  4229.6  334.44    4348  324.45  4390.8  319.32  4400.9  319.39  4421.1  315.62
  4501.7  309.38  4589.9  304.68  4662.9  302.42  4773.8  302.81  4844.3  304.49
  4874.6  304.37  4894.7  302.73  4945.1  305.69  4965.3  304.31  4985.4  305.21
    4995  299.81  4997.8  299.31    5001  299.81  5005.6   303.8  5015.6  305.49
  5072.4  309.27  5129.5  314.76  5182.4  316.25  5308.3   319.2  5358.8  318.55
  5451.3  322.33  5524.1  328.06  5560.7  332.32    5603  334.19  5646.1  340.39
#Mann= 4 ,-1 , 0
  4229.6     .12       0    4995     .07       0    5001     .12       0
  5182.4     .16       0
Bank Sta=4501.7,5072.4
XS Rating Curve= 0 ,0
Exp/Cntr=0.3,0.1

Type RM Length L Ch R = 1 ,93403   ,793,793,793
BEGIN DESCRIPTION:
LAKE CREEK 127.0
END DESCRIPTION:
XS GIS Cut Line= 2
      3715964.39     10654623.63      3714130.58     10654591.07
#Sta/Elev= 30
  4371.3  327.06  4455.9  320.24  4506.1  318.76  4656.1  309.08  4750.7   304.5
  4866.2  301.51  4876.2  302.49  4896.2   300.5  4906.2  302.19  4966.2   303.5
  4986.2  298.63  4996.2  299.74  5006.2   304.4  5036.2  304.11  5056.2  302.94
  5066.2  298.69  5073.2  298.29  5075.9  297.79  5079.2  298.29  5096.2  298.67
  5106.2  304.81  5306.2  308.62  5436.3  311.63  5576.3  318.33  5646.3  319.51
  5666.3  318.07  5820.8  324.79  5919.7  330.61  6096.4  342.73  6205.4  345.26
#Mann= 7 ,-1 , 0
  4371.3     .12       0  4455.9     .05       0  4750.7     .12       0
  5073.2     .07       0  5079.2     .12       0  5820.8     .16       0
  5919.7     .05       0
Bank Sta=4656.1,5306.2
XS Rating Curve= 0 ,0
Exp/Cntr=0.3,0.1

Type RM Length L Ch R = 1 ,92610   ,735,735,735
BEGIN DESCRIPTION:
LAKE CREEK 126.0
END DESCRIPTION:
XS GIS Cut Line= 3
      3716127.07     10654395.75      3715541.18     10654222.15
      3713752.71      10654124.6
#Sta/Elev= 30
  4176.3  326.02  4250.3  325.69  4316.8  330.75  4421.7  333.33  4507.4  331.35
  4572.7  326.29  4768.2  307.65  4809.5  302.99    4829  300.02  4969.2  303.48
  4996.3  298.09    4999  297.59  5002.3  298.09  5009.3  303.07  5079.4  301.69
  5289.7  307.23  5359.8  311.79  5449.9  310.42    5500  314.88  5540.1  313.35
  5590.1  320.65  5700.3  329.18  5889.6   339.1  6000.7  341.92  6120.9   339.2
  6239.4  341.21  6471.4  341.34  6511.5  345.96  6551.6  340.63  6578.5  340.19
#Mann= 7 ,-1 , 0
  4176.3     .05       0  4572.7     .16       0  4809.5     .12       0
  4996.3     .07       0  5002.3     .12       0  5889.6     .16       0
  6239.4     .05       0
Bank Sta=4768.2,5289.7
XS Rating Curve= 0 ,0
Exp/Cntr=0.3,0.1

Type RM Length L Ch R = 1 ,91875   ,587,587,587
BEGIN DESCRIPTION:
LAKE CREEK 125.0
END DESCRIPTION:
XS GIS Cut Line= 3
      3716572.03      10654102.8      3715009.49     10653657.91
      3713620.62     10653809.82
#Sta/Elev= 30
  3841.3  327.94    3902  324.15  4010.1  317.31  4239.2  309.61  4379.8  310.12
  4540.5  305.93  4923.5  302.27  4977.1  302.31  4999.2  298.58  5001.9  298.08
  5005.2  298.58    5036  302.95  5049.9  299.25  5101.9  299.82    5187   305.7
  5332.8  314.07    5532   328.2    5634  329.82  5888.3  330.18  6201.3  337.93
  6471.8  341.99  6545.9  339.03  6622.7  331.18  6687.5  329.07  6713.2  328.51
  6728.4  323.73  6753.5   326.5  6773.6  320.23  6803.8  325.77  6863.1  328.69
#Mann= 9 ,-1 , 0
  3841.3     .16       0    3902     .05       0  4923.5     .12       0
  4999.2     .07       0  5005.2     .12       0  5332.8     .16       0
    5634     .12       0  6201.3     .16       0  6687.5     .12       0
Bank Sta=4540.5,5187
XS Rating Curve= 0 ,0
Exp/Cntr=0.3,0.1

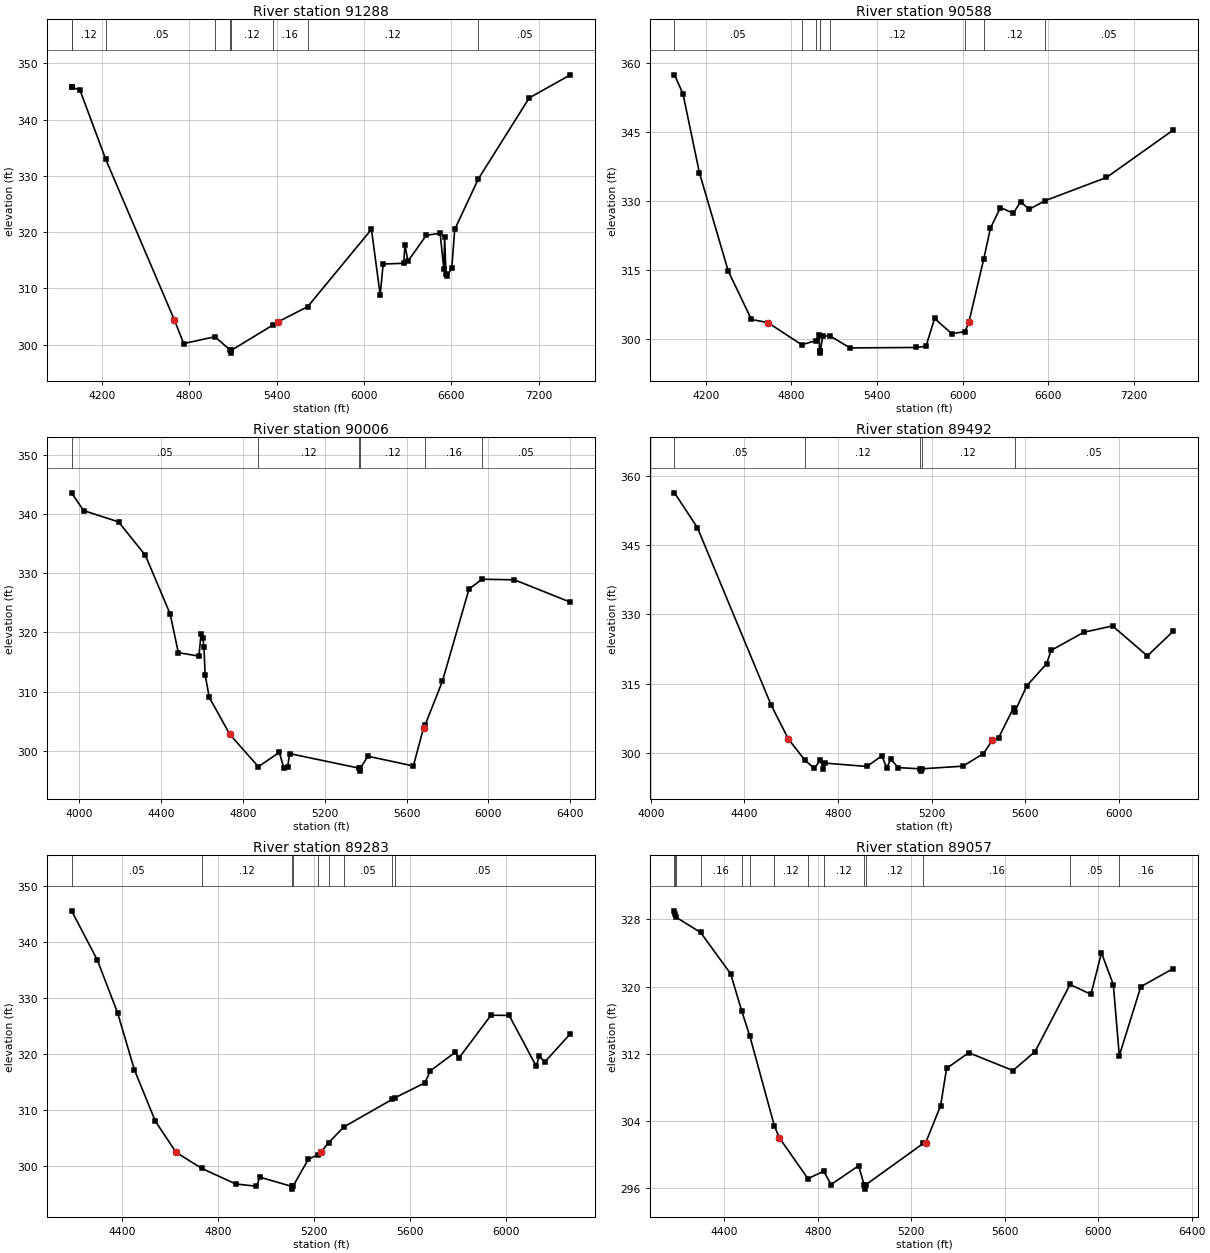
Type RM Length L Ch R = 1 ,91288   ,700,700,700
BEGIN DESCRIPTION:
LAKE CREEK 124.0
END DESCRIPTION:
XS GIS Cut Line= 3
      3716669.68     10653592.82      3715172.25     10653104.53
      3713327.62     10653256.44
#Sta/Elev= 30
  3992.4  345.74  3994.1  345.74  4049.8  345.24    4227  332.92  4698.4  304.39
  4762.2   300.2  4976.8  301.41  5083.5     299  5086.3   298.5  5089.5     299
  5372.9  303.46  5412.4  304.08  5614.2  306.77  6051.7  320.49  6111.9  308.83
    6132  314.33  6272.4  314.46  6282.5   317.7    6302  314.82  6428.2  319.43
  6523.3  319.81  6549.3  313.38  6554.3  319.15  6563.4  312.63  6573.5  312.25
  6603.6  313.66  6623.6  320.48  6786.2  329.47  7135.4  343.85  7418.3  347.95
#Mann= 9 ,-1 , 0
  3992.4     .16       0  3994.1     .12       0    4227     .05       0
  4976.8     .12       0  5083.5     .07       0  5089.5     .12       0
  5372.9     .16       0  5614.2     .12       0  6786.2     .05       0
Bank Sta=4698.4,5412.4
XS Rating Curve= 0 ,0
Exp/Cntr=0.3,0.1

Type RM Length L Ch R = 1 ,90588   ,582,582,582
BEGIN DESCRIPTION:
LAKE CREEK 123.0
END DESCRIPTION:
XS GIS Cut Line= 2
      3716864.97     10652540.29      3713383.27     10652833.14
#Sta/Elev= 30
  3980.6  357.39  4040.1  353.26    4155  336.13  4357.3  314.72  4519.6  304.21
  4634.4  303.55  4871.9  298.72  4971.6  299.62    4994  300.81  4996.6   297.4
  4999.3   296.9  5002.6   297.4  5019.6  300.66  5071.2  300.62  5210.3  298.03
  5671.9  298.13  5742.2  298.39  5802.4  304.43  5922.8  301.12  6015.6  301.58
  6043.2  303.69  6147.1  317.41  6193.8  324.08    6264  328.55  6354.3  327.29
  6404.5  329.82  6464.7  328.16  6576.9  330.04  7006.6  335.08  7474.6   345.4
#Mann= 9 ,-1 , 0
  3980.6     .05       0  4871.9     .12       0  4971.6     .16       0
  4996.6     .07       0  5002.6     .16       0  5071.2     .12       0
  6015.6     .16       0  6147.1     .12       0  6576.9     .05       0
Bank Sta=4634.4,6043.2
XS Rating Curve= 0 ,0
Exp/Cntr=0.3,0.1

Type RM Length L Ch R = 1 ,90006   ,514,514,514
BEGIN DESCRIPTION:
LAKE CREEK 122.0
END DESCRIPTION:
XS GIS Cut Line= 2
      3716767.31      10651921.8      3714347.58     10652236.48
#Sta/Elev= 30
  3961.7  343.57  4019.9  340.58  4191.3  338.66  4322.4  333.02  4443.4  323.14
  4483.8  316.58  4584.6  315.99  4594.7  319.67    4604  319.07  4609.1  317.51
  4614.9  312.83    4635  309.03  4735.9  302.76  4875.3  297.32  4977.9  299.73
  4999.6  297.11  5018.2  297.25  5028.3  299.53  5368.2  297.07  5370.9  296.57
  5374.2  297.07  5411.5  299.08  5633.4  297.44  5683.8  303.93  5691.6  304.42
  5775.5  311.74  5905.6  327.31    5969  328.98  6127.5  328.88  6401.8   325.1
#Mann= 6 ,-1 , 0
  3961.7     .05       0  4875.3     .12       0  5368.2     .07       0
  5374.2     .12       0  5691.6     .16       0    5969     .05       0
Bank Sta=4735.9,5683.8
XS Rating Curve= 0 ,0
Exp/Cntr=0.3,0.1

Type RM Length L Ch R = 1 ,89492   ,209,209,209
BEGIN DESCRIPTION:
LAKE CREEK 121.0
END DESCRIPTION:
XS GIS Cut Line= 2
      3716452.67     10651292.45      3714424.04     10651943.35
#Sta/Elev= 30
  4101.4  356.42  4199.1  348.87  4514.2  310.32  4587.7  302.95  4658.4  298.34
  4698.8  296.57  4724.2   298.4  4736.1  296.54  4745.2  297.71  4923.6  296.98
  4986.8  299.29  5007.8  296.72  5025.2  298.52  5057.3  296.73  5150.7  296.47
  5153.4  295.97  5156.7  296.47  5333.4  297.05  5421.1  299.78  5459.4  302.72
  5485.4  303.17  5549.6  309.74  5554.7  308.87  5606.4  314.53  5690.4  319.28
  5710.2   322.2  5849.2  326.13  5972.4  327.51    6121     321  6231.9  326.37
#Mann= 5 ,-1 , 0
  4101.4     .05       0  4658.4     .12       0  5150.7     .07       0
  5156.7     .12       0  5554.7     .05       0
Bank Sta=4587.7,5459.4
XS Rating Curve= 0 ,0
Exp/Cntr=0.3,0.1

Type RM Length L Ch R = 1 ,89283   ,226,226,226
BEGIN DESCRIPTION:
LAKE CREEK 120.0
END DESCRIPTION:
XS GIS Cut Line= 2
      3716300.74     10651097.14      3714336.71     10651791.61
#Sta/Elev= 30
  4187.6  345.57  4294.9  336.79  4379.7  327.31  4450.2   317.1  4537.6  307.93
  4623.7  302.38    4731  299.51  4872.3  296.73  4959.7  296.31  4973.7  297.94
    5106   296.3  5108.7   295.8    5112   296.3  5176.1  301.13  5217.7  301.98
  5227.3  302.36  5261.3  304.11  5324.1  306.91  5526.5  311.85  5536.1   312.1
  5663.1  314.81  5685.6  316.95  5790.4   320.3    5804  319.17  5938.9   326.9
    6015  326.86    6128  317.79  6140.4  319.55  6164.3  318.57  6270.8  323.59
#Mann= 9 ,-1 , 0
  4187.6     .05       0    4731     .12       0    5106     .07       0
    5112     .12       0  5217.7     .05       0  5261.3     .12       0
  5324.1     .05       0  5526.5     .12       0  5536.1     .05       0
Bank Sta=4623.7,5227.3
XS Rating Curve= 0 ,0
Exp/Cntr=0.3,0.1

Type RM Length L Ch R = 1 ,89057   ,162,162,162
BEGIN DESCRIPTION:
LAKE CREEK 119.0
END DESCRIPTION:
XS GIS Cut Line= 2
      3716246.45     10650901.84      3714217.38     10651563.73
#Sta/Elev= 30
  4187.2  329.03  4190.5  328.62  4193.3  328.28  4298.7  326.46  4427.4  321.54
  4475.4  317.06  4509.5  314.12  4614.9   303.4  4636.2  301.99  4758.2  297.15
  4825.6  298.03  4857.1  296.45    4975  298.68  4998.6   296.4  5001.3   295.9
  5004.6   296.4  5252.6  301.36  5262.1  301.43  5325.9  305.84  5351.4  310.27
  5446.1  312.14  5635.4  310.02  5730.1  312.28  5879.6  320.26  5969.1  319.09
  6014.1  324.02  6064.8  320.25  6090.4  311.79  6182.4     320  6321.5  322.16
#Mann= 14 ,-1 , 0
  4187.2     .16       0  4190.5     .08       0  4193.3     .05       0
  4298.7     .16       0  4475.4     .08       0  4509.5     .16       0
  4614.9     .12       0  4758.2     .08       0  4825.6     .12       0
  4998.6     .07       0  5004.6     .12       0  5252.6     .16       0
  5879.6     .05       0  6090.4     .16       0
Bank Sta=4636.2,5262.1
XS Rating Curve= 0 ,0
Exp/Cntr=0.3,0.1

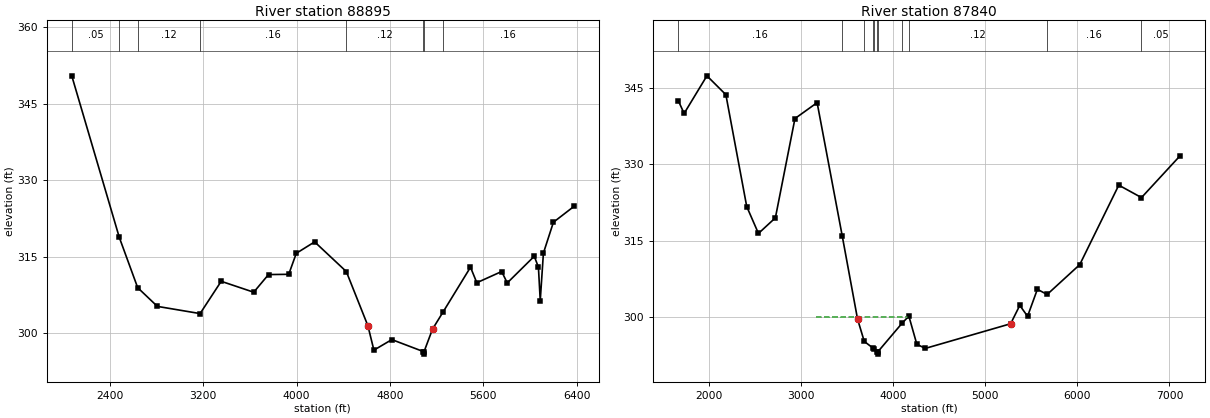
Type RM Length L Ch R = 1 ,88895   ,1055,1055,1055
BEGIN DESCRIPTION:
Mapping XS 36317ac3
END DESCRIPTION:
XS GIS Cut Line= 3
       3718290.2     10650282.24      3716279.02     10650804.18
      3714108.88     10651303.31
#Sta/Elev= 30
  2072.6  350.47  2479.9   318.8  2637.7  308.93  2806.7  305.26  3172.8  303.85
  3353.7  310.18  3632.5  308.04  3759.3   311.5  3932.8  311.55  3997.6  315.67
  4154.9  317.91  4426.5  312.09  4611.5  301.46  4662.9  296.68  4816.8  298.75
  5087.2   296.4    5090   295.9  5093.2   296.4  5165.6  300.81  5253.5  304.07
  5491.1  312.94  5545.3   309.9  5758.3   312.1  5806.3  309.86  6037.8  315.09
  6073.5  312.96  6089.1   306.4  6116.3  315.71    6202  321.76  6377.2  324.85
#Mann= 8 ,-1 , 0
  2072.6     .05       0  2479.9     .16       0  2637.7     .12       0
  3172.8     .16       0  4426.5     .12       0  5087.2     .07       0
  5093.2     .12       0  5253.5     .16       0
#XS Ineff= 2 , 0
         4159.55  317.79
Permanent Ineff=
       F       F
Bank Sta=4611.5,5165.6
XS Rating Curve= 0 ,0
Exp/Cntr=0.3,0.1

Type RM Length L Ch R = 1 ,87840   ,298,298,298
BEGIN DESCRIPTION:
LAKE CREEK 118.0
END DESCRIPTION:
XS GIS Cut Line= 3
      3717689.58     10647820.27      3716604.54      10648775.1
      3713642.28     10651476.94
#Sta/Elev= 30
  1662.8  342.49  1726.8  339.96  1974.4  347.34  2180.3  343.64    2407   321.7
  2534.2  316.43  2718.2  319.49  2930.8  338.96  3171.7  342.08  3444.9   315.9
  3610.8  299.64  3683.7  295.26    3781  293.91  3785.1  293.85  3827.4  293.26
  3830.2  292.76  3833.4  293.26  4093.6   298.8  4168.3  300.22  4254.7  294.71
  4346.6  293.88  5274.2  298.72  5373.5  302.32    5458  300.18  5564.6  305.47
  5670.8  304.46  6024.8  310.31  6449.1   325.9  6695.6  323.46  7117.5  331.71
#Mann= 11 ,-1 , 0
  1662.8     .16       0  3444.9     .12       0  3683.7     .05       0
    3781     .07       0  3785.1     .12       0  3827.4     .07       0
  3833.4     .12       0  4093.6     .16       0  4168.3     .12       0
  5670.8     .16       0  6695.6     .05       0
#XS Ineff= 1 ,-1
 3155.49 4151.42  299.95
Permanent Ineff=
       F
Bank Sta=3610.8,5274.2
XS Rating Curve= 0 ,0
Exp/Cntr=0.3,0.1