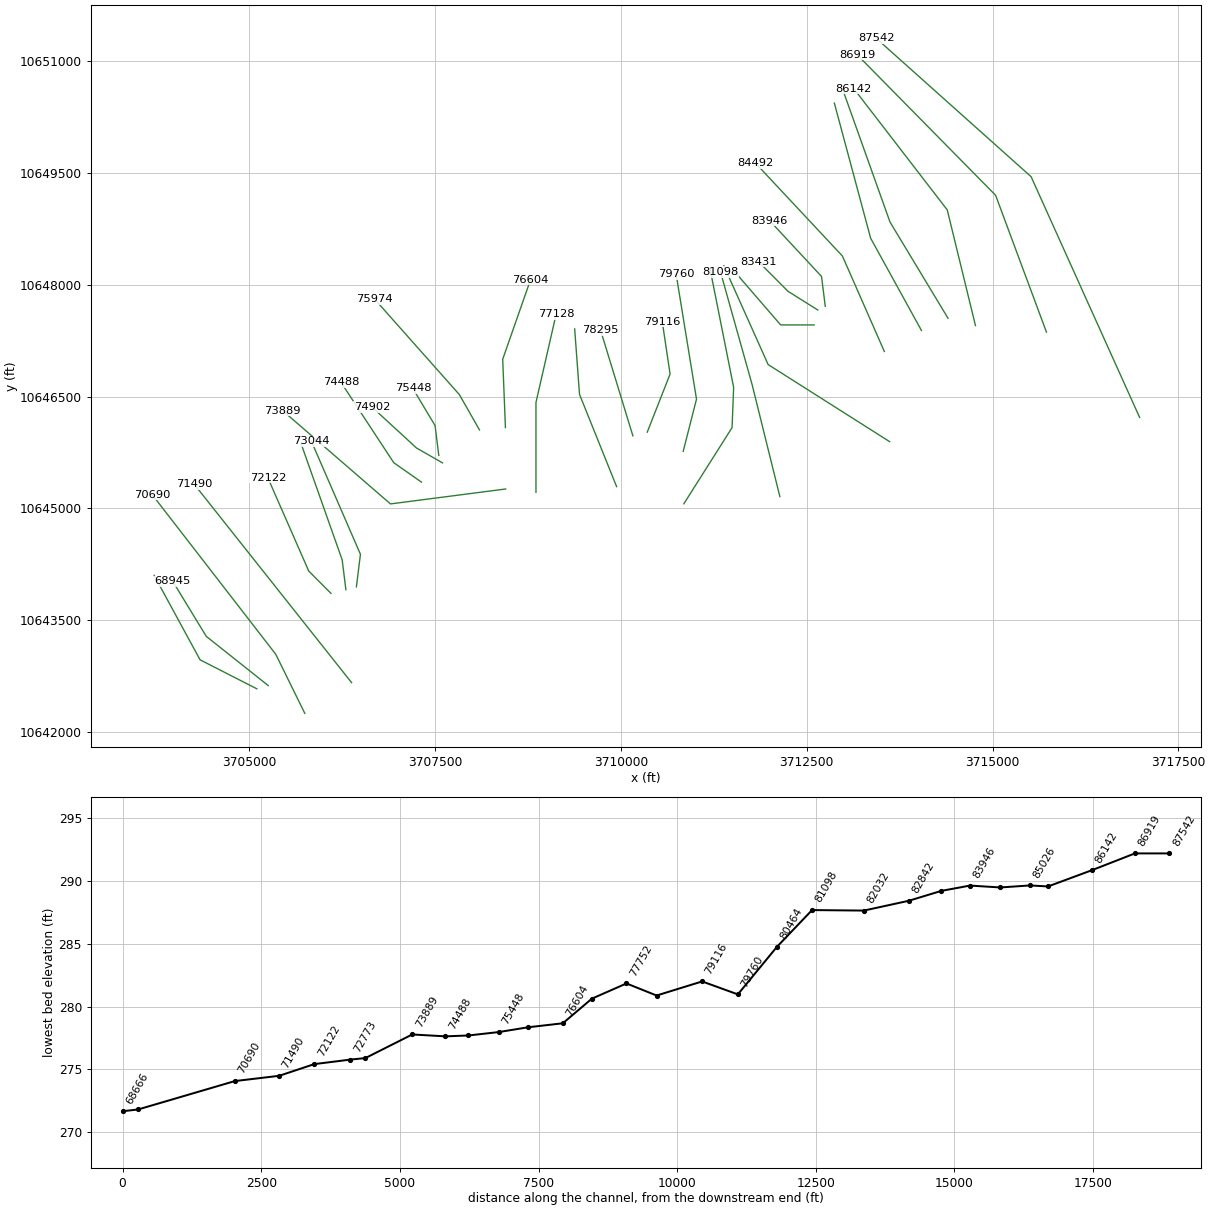
HEC-RAS study LAKE CREEK.prj: LAKE CREEK Base Level Engineering

--- LAKE CREEK.g01 (geometry) --- (continued)

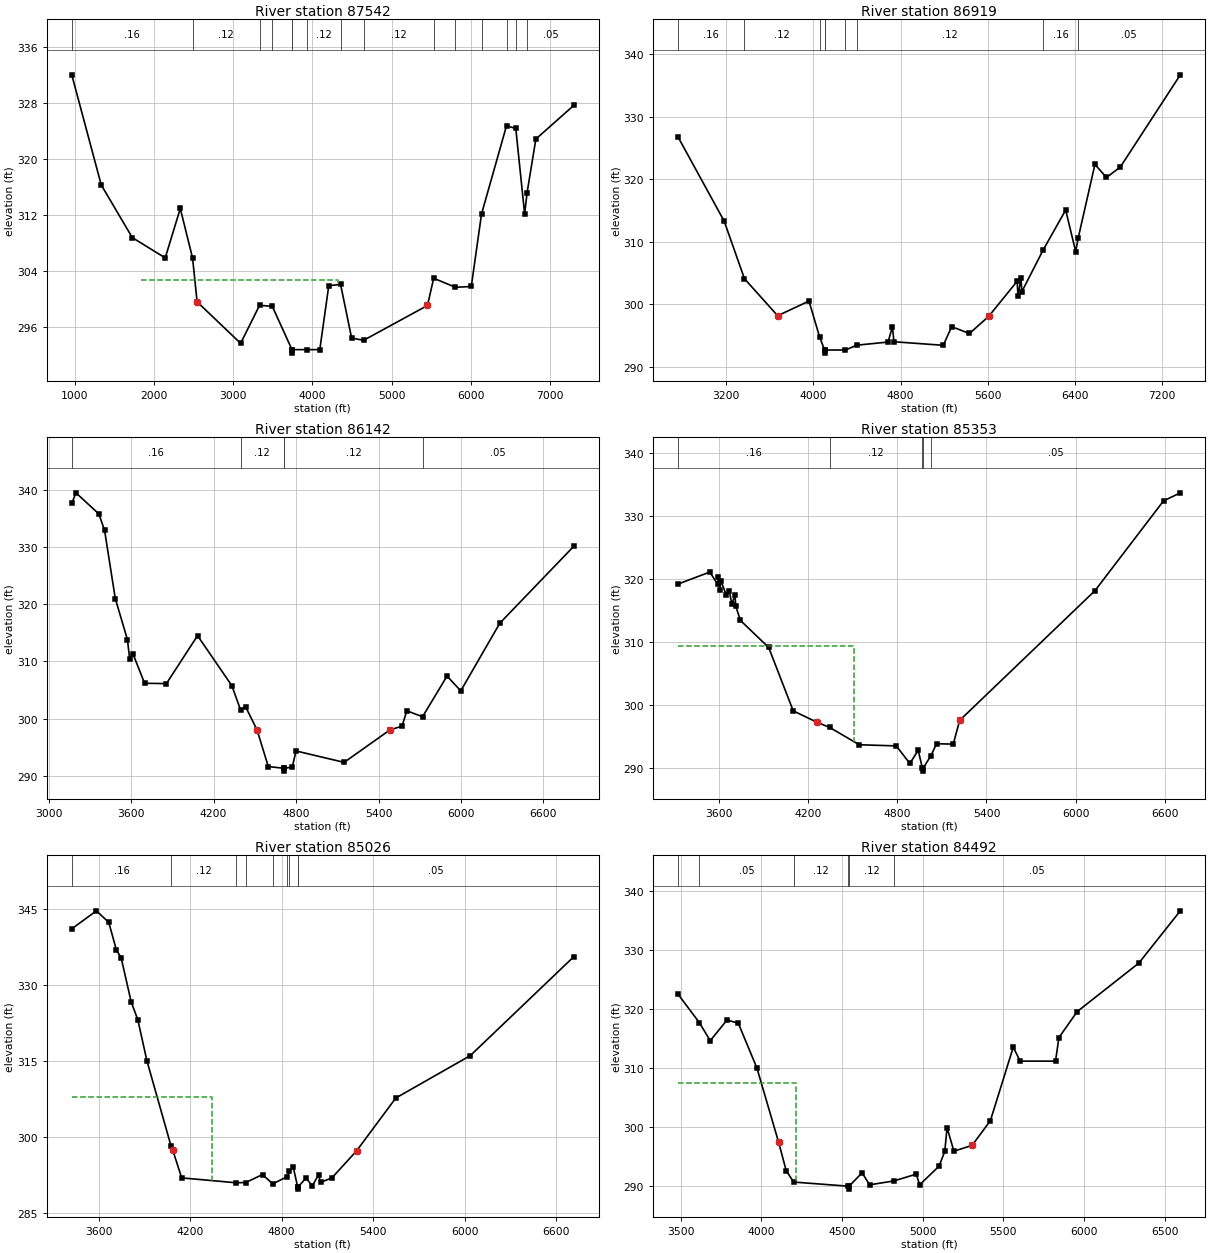
Type RM Length L Ch R = 1 ,87542   ,623,623,623
BEGIN DESCRIPTION:
LAKE CREEK 117.0
END DESCRIPTION:
XS GIS Cut Line= 3
      3716979.48     10646219.73      3715519.47     10649447.84
      3713436.17     10651303.29
#Sta/Elev= 30
   964.8  332.02  1336.8  316.25  1728.5  308.72  2143.3  305.82  2333.6  312.89
  2488.7  305.79  2545.7  299.53  3094.5  293.59  3333.7  299.04  3494.1  298.88
  3742.3  292.69    3745  292.19  3748.3  292.69    3927  292.69  4093.2  292.69
  4206.3  301.84  4355.5  302.02  4494.6  294.34  4646.5  294.03  5451.3  299.01
  5529.5  302.91  5804.5  301.61    6004  301.73  6132.9  312.09  6448.2  324.73
  6565.3  324.34  6676.9   312.1  6706.6  315.07  6818.4  322.83  7297.5  327.65
#Mann= 15 ,-1 , 0
   964.8     .16       0  2488.7     .12       0  3333.7     .16       0
  3494.1     .12       0  3742.3     .07       0  3748.3     .12       0
    3927     .12       0  4355.5     .16       0  4646.5     .12       0
  5529.5     .16       0  5804.5     .12       0  6132.9     .16       0
  6448.2     .12       0  6565.3     .16       0  6706.6     .05       0
#XS Ineff= 1 ,-1
  1837.4 4317.07  302.65
Permanent Ineff=
       F
Bank Sta=2545.7,5451.3
XS Rating Curve= 0 ,0
Exp/Cntr=0.3,0.1

Type RM Length L Ch R = 1 ,86919   ,777,777,777
BEGIN DESCRIPTION:
LAKE CREEK 116.0
END DESCRIPTION:
XS GIS Cut Line= 3
      3715725.63     10647364.53      3715042.04     10649198.28
      3713176.27     10651085.74
#Sta/Elev= 30
  2758.4  326.71  3180.7  313.29  3366.7  304.09  3671.6  298.17  3959.1  300.52
  4055.8  294.83  4102.3  292.69  4105.1  292.19  4108.3  292.69  4294.3  292.69
  4397.5  293.46  4685.4  293.96  4725.6  296.42  4739.7  294.01  5192.3  293.44
    5270  296.42  5432.7  295.33  5609.5  298.07  5871.1  303.69  5878.2  301.34
  5906.5  304.21  5913.5     302  6109.1  308.67  6316.6  315.08  6408.5  308.44
  6431.5   310.6  6585.3  322.38  6691.3  320.29  6818.6  321.96  7369.4  336.71
#Mann= 9 ,-1 , 0
  2758.4     .16       0  3366.7     .12       0  4055.8     .05       0
  4102.3     .07       0  4108.3     .05       0  4294.3     .07       0
  4397.5     .12       0  6109.1     .16       0  6431.5     .05       0
Bank Sta=3671.6,5609.5
XS Rating Curve= 0 ,0
Exp/Cntr=0.3,0.1

Type RM Length L Ch R = 1 ,86142   ,789,789,789
BEGIN DESCRIPTION:
LAKE CREEK 115.0
END DESCRIPTION:
XS GIS Cut Line= 3
      3714770.78     10647451.32        3714391.     10649002.97
      3713133.46      10650629.1
#Sta/Elev= 30
  3168.1  337.58  3198.5  339.44    3365  335.76  3406.6  332.92  3484.7  320.99
  3573.1  313.81    3589  310.51  3614.7  311.24    3698  306.19  3856.7  306.13
  4083.2   314.5  4332.6  305.78    4396  301.56  4433.2  302.07  4515.6  298.08
    4598  291.65  4709.3  291.35  4712.1  290.85  4715.3  291.35  4772.2  291.55
    4800  294.37  5149.8  292.38  5483.9  298.06  5570.9   298.7  5606.2  301.39
  5720.1  300.34  5898.7  307.45  5998.3  304.86  6282.6  316.68  6821.2  330.12
#Mann= 5 ,-1 , 0
  3168.1     .16       0    4396     .12       0  4709.3     .07       0
  4715.3     .12       0  5720.1     .05       0
Bank Sta=4515.6,5483.9
XS Rating Curve= 0 ,0
Exp/Cntr=0.3,0.1

Type RM Length L Ch R = 1 ,85353   ,327,327,327
BEGIN DESCRIPTION:
LAKE CREEK 114.0
END DESCRIPTION:
XS GIS Cut Line= 3
      3714401.83     10647549.01       3713620.6     10648840.21
      3712991.77     10650596.59
#Sta/Elev= 30
  3328.3  319.23  3540.7  321.12    3593  319.19  3598.9  320.33  3608.5  318.26
  3614.4  319.77  3651.2   317.5  3672.6  318.05  3688.1  316.05  3709.4  317.44
  3715.4  315.67  3746.3  313.45  3936.3  309.16  4101.3  299.11  4264.2  297.27
  4345.8  296.49  4545.5  293.74  4793.8  293.56  4885.1  290.78  4941.3  292.86
    4969  290.06  4971.8  289.56    4975  290.06  5026.4  291.99  5064.3   293.9
  5176.8  293.84  5219.8   297.6  6129.4  318.17    6590   332.4    6703  333.68
#Mann= 5 ,-1 , 0
  3328.3     .16       0  4345.8     .12       0    4969     .07       0
    4975     .12       0  5026.4     .05       0
#XS Ineff= 2 , 0
          4512.2  309.45
Permanent Ineff=
       F       F
Bank Sta=4264.2,5219.8
XS Rating Curve= 0 ,0
Exp/Cntr=0.3,0.1

Type RM Length L Ch R = 1 ,85026   ,534,534,534
BEGIN DESCRIPTION:
LAKE CREEK 113.0
END DESCRIPTION:
XS GIS Cut Line= 3
      3714043.79     10647386.19      3713360.19     10648623.19
      3712871.91     10650435.23
#Sta/Elev= 30
  3424.6  341.04  3585.9   344.6  3667.2  342.31  3716.4  336.93  3748.5  335.29
  3813.8  326.63  3857.4  323.08  3916.9     315  4074.7   298.2  4085.3  297.43
  4144.9  291.86  4500.2   290.9  4564.6  290.94  4674.5  292.52  4741.4  290.67
    4837  292.12  4850.9  293.16  4876.2  293.96  4904.3  290.14  4907.1  289.64
  4910.3  290.14  4959.1  291.84  5000.5  290.28    5042  292.47  5054.5  290.97
  5129.2  291.86  5290.5  297.18  5547.7  307.63  6036.2  316.01  6714.6  335.55
#Mann= 9 ,-1 , 0
  3424.6     .16       0  4074.7     .12       0  4500.2     .07       0
  4564.6     .12       0  4741.4     .07       0    4837     .05       0
  4850.9     .07       0  4904.3     .03       0  4910.3     .05       0
#XS Ineff= 2 , 0
         4341.46  307.79
Permanent Ineff=
       F       F
Bank Sta=4085.3,5290.5
XS Rating Curve= 0 ,0
Exp/Cntr=0.3,0.1

Type RM Length L Ch R = 1 ,84492   ,546,546,546
BEGIN DESCRIPTION:
LAKE CREEK 112.0
END DESCRIPTION:
XS GIS Cut Line= 3
      3713544.66     10647104.06      3712980.41     10648384.48
      3711808.51     10649632.33
#Sta/Elev= 30
  3485.7  322.48  3616.7   317.7  3683.9  314.64  3788.2  318.16  3858.1  317.59
  3973.2  310.01  4107.8  297.42  4154.5  292.63  4200.6  290.68  4538.5  289.98
  4541.2  289.48  4544.5  289.98    4625  292.25  4671.6  290.21  4822.2  290.87
  4960.5  292.02  4981.5  290.22  5101.7  293.36  5137.3  295.88  5151.5   299.9
  5193.9  295.91  5306.8   296.9  5420.1   301.1  5561.7  313.55  5604.2  311.18
  5823.5  311.18  5844.6  315.17  5957.9  319.58  6339.8   327.8  6596.8  336.66
#Mann= 6 ,-1 , 0
  3485.7     .16       0  3616.7     .05       0  4200.6     .12       0
  4538.5     .03       0  4544.5     .12       0  4822.2     .05       0
#XS Ineff= 2 , 0
         4215.45  307.54
Permanent Ineff=
       F       F
Bank Sta=4107.8,5306.8
XS Rating Curve= 0 ,0
Exp/Cntr=0.3,0.1

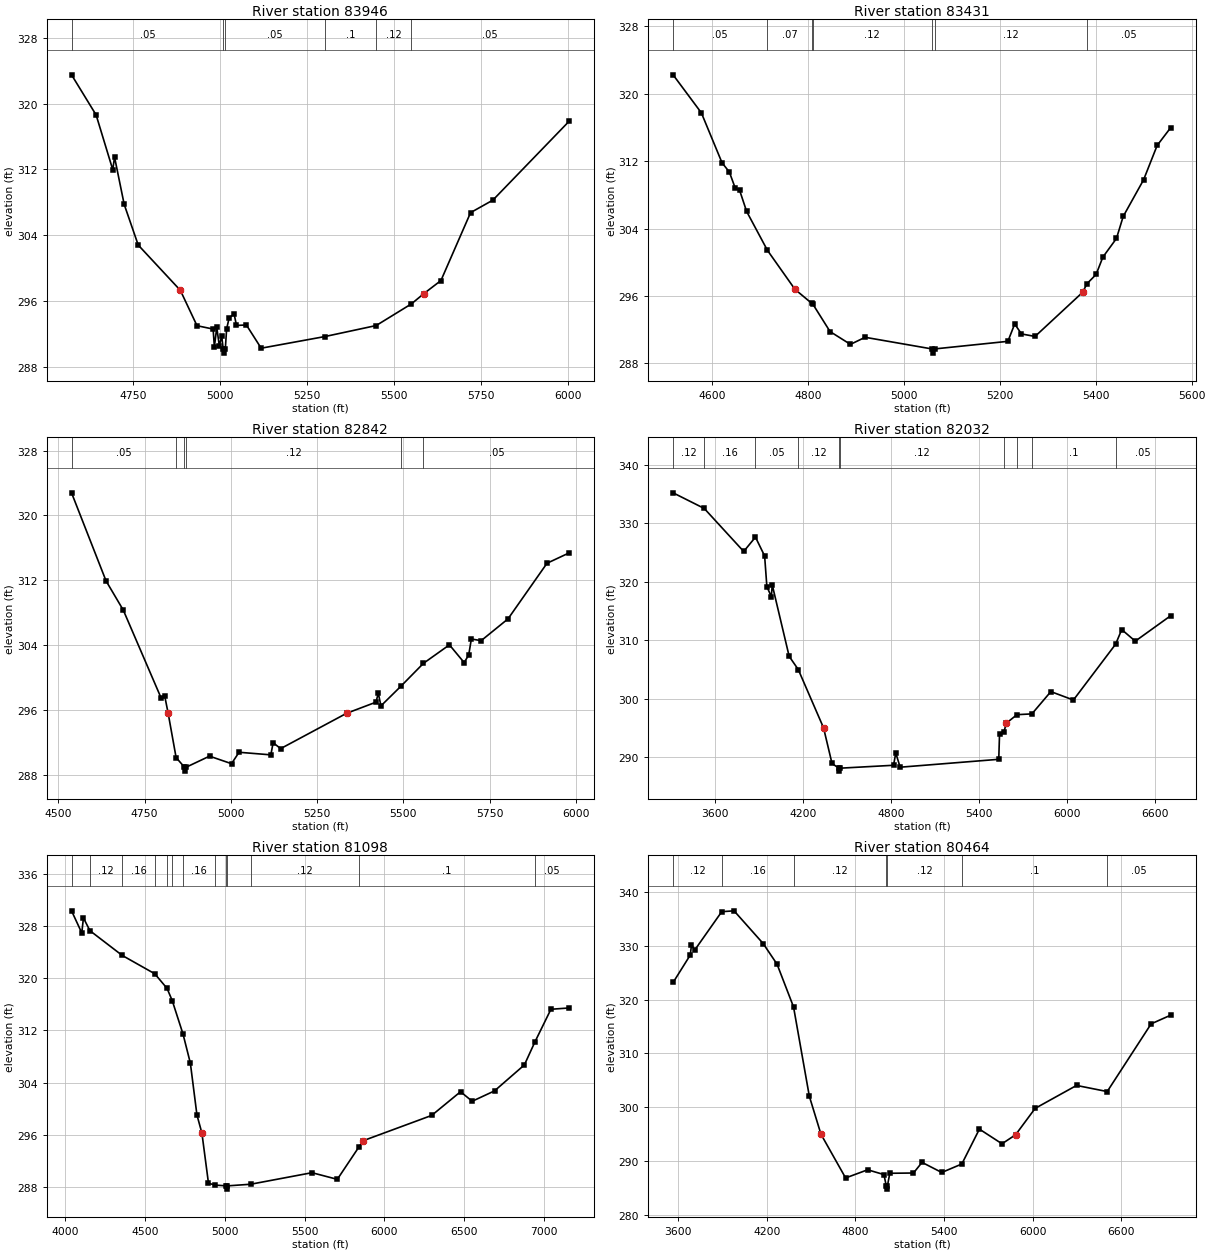
Type RM Length L Ch R = 1 ,83946   ,515,515,515
BEGIN DESCRIPTION:
LAKE CREEK 111.0
END DESCRIPTION:
XS GIS Cut Line= 3
      3712749.61     10647710.16      3712699.61     10648110.19
      3711999.58     10648860.22
#Sta/Elev= 30
  4572.9  323.52  4643.5  318.63  4691.3  311.96  4696.4   313.5  4724.1  307.74
  4764.4  302.79  4885.3  297.28  4933.2  292.97  4979.5  292.56  4983.1   290.4
    4990  292.76  4997.3  290.52  5004.1  291.71  5008.5  290.13  5011.2  289.63
  5014.5  290.13  5018.3  292.59  5025.6  293.93  5039.8  294.39  5046.6     293
    5075  293.06  5117.5  290.23  5300.7  291.65  5447.8  292.99  5549.1  295.63
  5584.5  296.87  5633.8  298.47  5718.9  306.74  5782.9  308.26    6002  317.87
#Mann= 6 ,-1 , 0
  4572.9     .05       0  5008.5     .03       0  5014.5     .05       0
  5300.7      .1       0  5447.8     .12       0  5549.1     .05       0
Bank Sta=4885.3,5584.5
XS Rating Curve= 0 ,0
Exp/Cntr=0.3,0.1

Type RM Length L Ch R = 1 ,83431   ,589,589,589
BEGIN DESCRIPTION:
LAKE CREEK 110.0
END DESCRIPTION:
XS GIS Cut Line= 3
      3712649.57     10647660.21      3712249.61     10647910.19
      3711849.64     10648310.16
#Sta/Elev= 30
    4519  322.25  4577.9  317.74    4621  311.81  4636.3  310.71  4648.7  308.77
  4657.5  308.57  4672.3  306.03  4715.7  301.41  4773.1  296.78  4808.3  295.11
  4810.4  295.02  4846.2  291.77  4888.7  290.25  4919.3  291.09  5058.4  289.71
  5061.1  289.21  5064.4  289.71  5216.9  290.61  5231.1  292.67  5245.2  291.49
  5273.5  291.19  5372.5  296.42  5381.9  297.46  5400.8  298.55  5414.9  300.61
  5443.2  302.82  5457.3  305.44  5499.8  309.79  5528.1  313.87  5556.3  315.98
#Mann= 7 ,-1 , 0
    4519     .05       0  4715.7     .07       0  4808.3     .05       0
  4810.4     .12       0  5058.4     .07       0  5064.4     .12       0
  5381.9     .05       0
Bank Sta=4773.1,5372.5
XS Rating Curve= 0 ,0
Exp/Cntr=0.3,0.1

Type RM Length L Ch R = 1 ,82842   ,810,810,810
BEGIN DESCRIPTION:
LAKE CREEK 109.0
END DESCRIPTION:
XS GIS Cut Line= 3
       3712599.6     10647460.19      3712149.61     10647460.19
      3711499.58     10648210.22
#Sta/Elev= 30
  4538.1   322.8  4638.1  311.92  4688.1  308.31  4798.1  297.42  4808.1  297.72
  4818.1  295.58  4841.2   290.1  4865.1  288.92  4867.8  288.42  4871.1  288.92
  4938.1  290.27  5001.8  289.34  5023.7  290.75  5115.8  290.43  5122.5  291.93
  5144.3   291.2  5335.2  295.56  5420.7  296.94  5427.3  298.06    5435  296.48
  5492.7   298.9  5558.3  301.74  5633.5  304.02  5676.2  301.83  5689.4  302.76
  5697.1  304.74  5725.6  304.54  5803.4  307.23  5916.4   314.1  5980.6  315.38
#Mann= 6 ,-1 , 0
  4538.1     .05       0  4841.2     .12       0  4865.1     .07       0
  4871.1     .12       0  5492.7      .1       0  5558.3     .05       0
Bank Sta=4818.1,5335.2
XS Rating Curve= 0 ,0
Exp/Cntr=0.3,0.1

Type RM Length L Ch R = 1 ,82032   ,934,934,934
BEGIN DESCRIPTION:
Mapping XS f8aff9f4
END DESCRIPTION:
XS GIS Cut Line= 3
       3713615.9     10645895.08       3711981.2     10646928.77
      3711385.35      10648254.3
#Sta/Elev= 30
  3317.7   335.2  3529.7  332.53  3798.4  325.18  3878.4  327.63  3940.8  324.41
  3956.1  319.16  3986.6  317.46  3992.6  319.47  4107.8  307.26  4169.8     305
  4341.9  295.04  4399.5  288.95  4446.1  288.14  4448.9  287.64  4452.1  288.14
  4818.3  288.64  4833.6  290.73  4863.3  288.31  5534.6  289.66    5540  294.01
    5569  294.27  5586.4  295.84  5658.7  297.29  5760.2  297.42  5889.3  301.23
  6042.8  299.79  6330.1  309.33  6371.7  311.83  6463.9  309.85  6705.1   314.2
#Mann= 10 ,-1 , 0
  3317.7     .12       0  3529.7     .16       0  3878.4     .05       0
  4169.8     .12       0  4446.1     .07       0  4452.1     .12       0
    5569      .1       0  5658.7     .05       0  5760.2      .1       0
  6330.1     .05       0
Bank Sta=4341.9,5586.4
XS Rating Curve= 0 ,0
Exp/Cntr=0.3,0.1

Type RM Length L Ch R = 1 ,81098   ,634,634,634
BEGIN DESCRIPTION:
LAKE CREEK 108.0
END DESCRIPTION:
XS GIS Cut Line= 3
      3712138.83     10645157.94      3711765.57     10646659.65
      3711340.21      10648170.1
#Sta/Elev= 30
  4040.2  330.34  4104.3  326.95  4114.6  329.25  4155.6  327.29  4357.2  323.51
  4561.5  320.69  4638.4  318.45  4670.9  316.57  4738.5  311.44  4784.4  306.99
  4825.6  299.04  4856.6  296.28  4897.8  288.59  4938.7   288.3  5010.7  288.18
  5013.5  287.68  5016.7  288.18  5162.2  288.43    5546   290.2  5704.7  289.18
  5838.4  294.08  5868.7  295.12  6295.9  298.98  6476.5  302.61  6549.7  301.15
  6689.4  302.74  6876.4  306.72  6941.9  310.22  7042.6  315.25  7156.8  315.45
#Mann= 13 ,-1 , 0
  4040.2     .05       0  4155.6     .12       0  4357.2     .16       0
  4561.5     .12       0  4638.4     .16       0  4670.9     .12       0
  4738.5     .16       0  4938.7     .07       0  5010.7     .07       0
  5016.7     .07       0  5162.2     .12       0  5838.4      .1       0
  6941.9     .05       0
Bank Sta=4856.6,5868.7
XS Rating Curve= 0 ,0
Exp/Cntr=0.3,0.1

Type RM Length L Ch R = 1 ,80464   ,704,704,704
BEGIN DESCRIPTION:
LAKE CREEK 107.0
END DESCRIPTION:
XS GIS Cut Line= 4
      3710846.79     10645061.72      3711495.65     10646083.12
      3711517.07     10646622.88      3711199.61     10648210.19
#Sta/Elev= 30
    3566  323.21  3682.7  328.34  3690.5  330.25  3711.7  329.22  3895.3  336.39
  3978.8  336.55  4175.8  330.46  4269.8  326.62  4381.5  318.66  4488.3  302.05
  4567.1  294.97    4734  286.83  4883.2  288.35  4993.3  287.46  5010.3  285.25
  5013.1  284.75  5016.3  285.25  5033.3   287.7  5193.5  287.75  5251.4  289.73
  5384.9  287.85  5520.9  289.43  5639.8  295.92  5792.8  293.19  5884.6  294.86
  6017.2  299.78  6297.6  304.05  6505.1  302.91  6802.4  315.51    6935  317.13
#Mann= 7 ,-1 , 0
    3566     .12       0  3895.3     .16       0  4381.5     .12       0
  5010.3     .07       0  5016.3     .12       0  5520.9      .1       0
  6505.1     .05       0
Bank Sta=4567.1,5884.6
XS Rating Curve= 0 ,0
Exp/Cntr=0.3,0.1

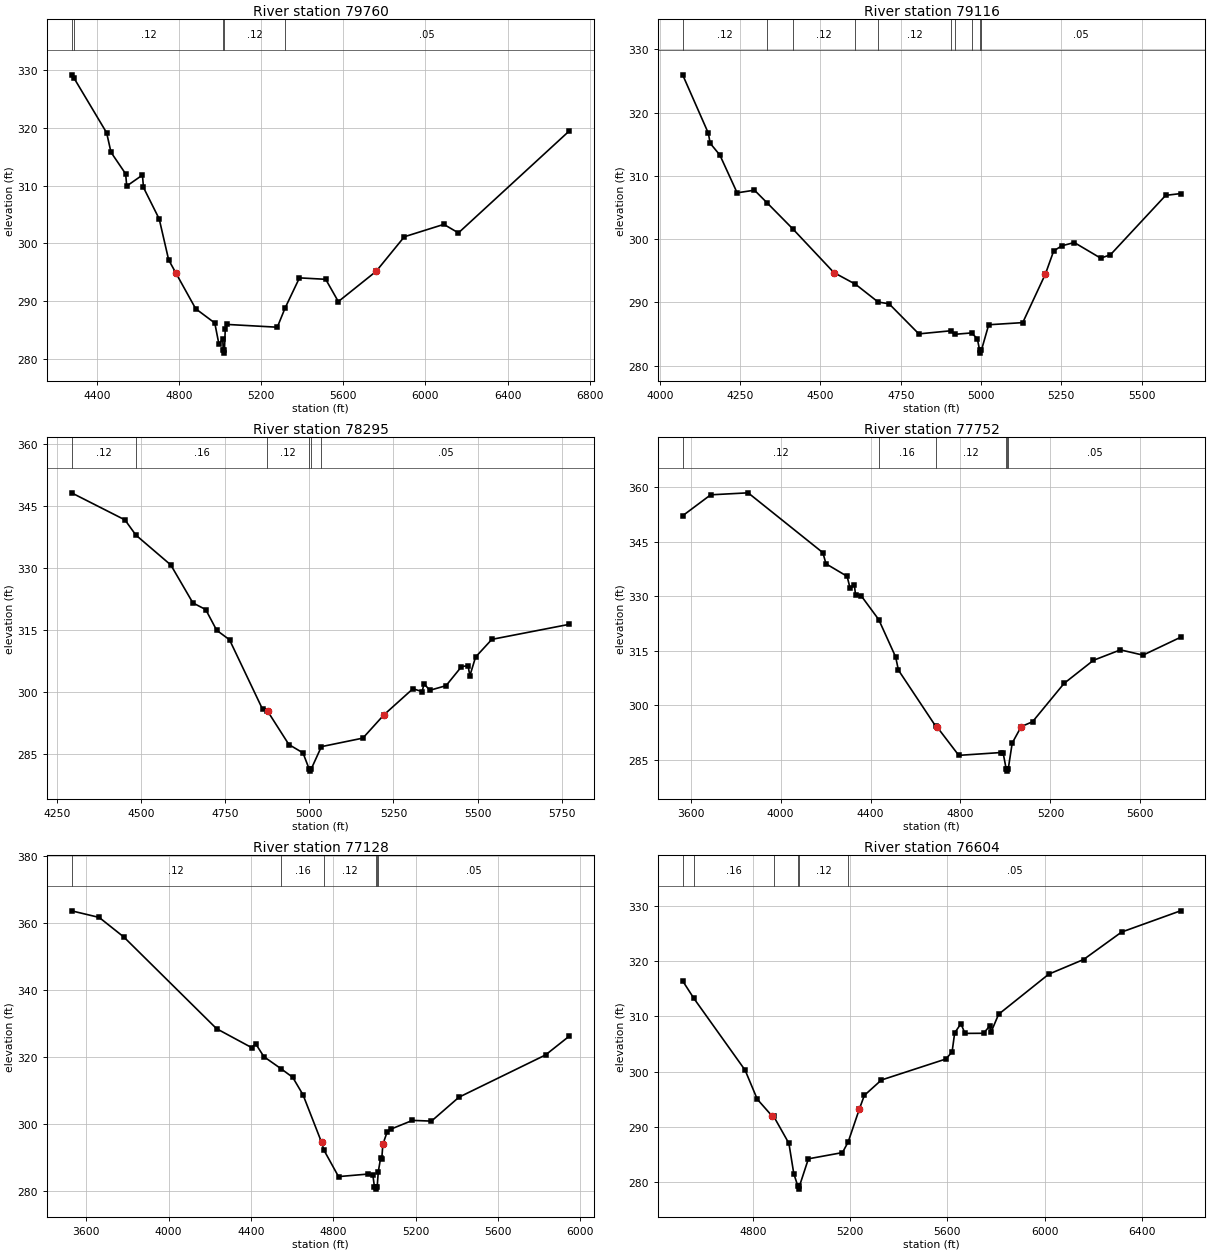
Type RM Length L Ch R = 1 ,79760   ,644,644,644
BEGIN DESCRIPTION:
LAKE CREEK 106.0
END DESCRIPTION:
XS GIS Cut Line= 3
      3710838.12     10645764.85      3711017.25       10646465.
      3710742.64     10648143.38
#Sta/Elev= 30
  4277.3  329.19  4288.8  328.65    4448  319.15  4469.3  315.77  4540.6  312.03
  4545.8  309.92  4622.3  311.82  4627.4  309.67  4703.9  304.22  4749.9  297.13
  4785.5  294.82  4881.5  288.66  4974.4  286.19  4994.9  282.47  5013.3   283.5
  5015.4  281.47  5018.2  280.97  5021.4  281.47  5025.5  285.16  5035.7  285.94
  5278.8  285.46  5316.5  288.77  5386.6  294.01  5514.4  293.76  5575.8   289.9
  5759.8  295.14    5897  301.13  6089.5  303.28  6160.4   301.8  6700.7  319.49
#Mann= 5 ,-1 , 0
  4277.3     .16       0  4288.8     .12       0  5015.4     .07       0
  5021.4     .12       0  5316.5     .05       0
Bank Sta=4785.5,5759.8
XS Rating Curve= 0 ,0
Exp/Cntr=0.3,0.1

Type RM Length L Ch R = 1 ,79116   ,821,821,821
BEGIN DESCRIPTION:
LAKE CREEK 105.0
END DESCRIPTION:
XS GIS Cut Line= 3
      3710354.57     10646022.37      3710661.71     10646801.28
      3710556.15     10647505.84
#Sta/Elev= 30
  4071.3  325.96  4151.4  316.72  4156.8  315.16  4187.2  313.28  4240.9  307.32
  4294.8  307.74  4334.5  305.72  4414.8  301.59  4541.9  294.73  4609.3  292.88
  4679.8  290.07  4713.9  289.79  4806.4  285.04  4906.1  285.53  4917.6  284.97
  4970.4  285.19  4988.4  284.29  4995.5   282.5  4998.2     282  5001.5   282.5
  5023.9  286.48  5129.9  286.82  5200.7  294.53  5226.2  298.14  5251.3  298.95
  5290.3  299.47  5372.6     297  5402.9  297.54  5574.8  306.92    5621   307.2
#Mann= 10 ,-1 , 0
  4071.3     .12       0  4334.5     .16       0  4414.8     .12       0
  4609.3     .16       0  4679.8     .12       0  4906.1     .07       0
  4917.6     .12       0  4970.4     .05       0  4995.5     .03       0
  5001.5     .05       0
Bank Sta=4541.9,5200.7
XS Rating Curve= 0 ,0
Exp/Cntr=0.3,0.1

Type RM Length L Ch R = 1 ,78295   ,543,543,543
BEGIN DESCRIPTION:
LAKE CREEK 104.0
END DESCRIPTION:
XS GIS Cut Line= 2
      3710161.04     10645973.22      3709727.48     10647386.62
#Sta/Elev= 30
  4294.1  348.17  4452.7  341.62    4485  337.96  4588.9  330.72  4654.4  321.55
  4692.4  319.95  4725.1  314.93  4763.1  312.65  4861.3  295.84  4875.8  295.38
  4876.7  295.32  4939.4  287.31  4981.3  285.29  4999.7  281.38  5002.5  280.88
  5005.7  281.38    5036   286.8  5159.1  288.86  5221.9  294.51  5307.8   300.8
  5335.3   300.1  5340.6  302.04  5357.8  300.42  5406.1  301.54    5452  306.14
  5471.5   306.4  5476.8  303.91  5493.8  308.46  5542.2  312.74  5772.5  316.38
#Mann= 6 ,-1 , 0
  4294.1     .12       0    4485     .16       0  4875.8     .12       0
  4999.7     .07       0  5005.7     .12       0    5036     .05       0
Bank Sta=4876.7,5221.9
XS Rating Curve= 0 ,0
Exp/Cntr=0.3,0.1

Type RM Length L Ch R = 1 ,77752   ,624,624,624
BEGIN DESCRIPTION:
LAKE CREEK 102.0
END DESCRIPTION:
XS GIS Cut Line= 3
      3709942.22     10645292.03      3709443.09     10646529.01
      3709378.08     10647406.52
#Sta/Elev= 30
  3564.6  352.16  3689.2  357.92  3855.7  358.47  4188.1  341.99  4201.9  338.93
  4295.9  335.48  4309.3  332.14    4328  333.08  4333.4  330.35  4357.6  330.19
  4436.5  323.56  4511.6  313.29    4524  309.65  4690.5  294.13  4694.9  294.08
  4792.4  286.18  4979.9  286.96  4989.9  286.75  5003.4  282.37  5006.1  282.34
  5008.8  281.84  5012.1  282.34    5030  289.57  5070.1  294.11  5120.3  295.43
  5260.7     306    5391  312.35  5511.3  315.23  5611.6  313.78  5778.4  318.69
#Mann= 6 ,-1 , 0
  3564.6     .12       0  4436.5     .16       0  4690.5     .12       0
  5003.4     .05       0  5006.1     .07       0  5012.1     .05       0
Bank Sta=4694.9,5070.1
XS Rating Curve= 0 ,0
Exp/Cntr=0.3,0.1

Type RM Length L Ch R = 1 ,77128   ,524,524,524
BEGIN DESCRIPTION:
LAKE CREEK 101.0
END DESCRIPTION:
XS GIS Cut Line= 3
      3708857.15     10645216.06      3708857.15      10646420.5
      3709128.42     10647603.25
#Sta/Elev= 30
  3528.7  363.72  3662.8  361.75  3782.8  355.89  4232.8  328.54  4402.8   322.9
  4422.8  324.03  4462.8  320.17  4545.9  316.58  4602.8  314.01  4652.8  308.79
  4743.1  294.56  4754.1   292.3  4825.2  284.37  4968.8  285.13  4992.3   284.7
  4999.6  281.32  5006.8  281.13  5009.6  280.63  5012.8  281.13  5018.2  285.79
  5030.1  290.05  5035.2  289.68  5040.6  294.01  5061.1  297.66  5078.1  298.51
  5184.2  301.15  5276.6  300.94    5410  308.07  5830.6  320.69  5946.6  326.34
#Mann= 6 ,-1 , 0
  3528.7     .12       0  4545.9     .16       0  4754.1     .12       0
  5006.8     .07       0  5012.8     .12       0  5018.2     .05       0
Bank Sta=4743.1,5040.6
XS Rating Curve= 0 ,0
Exp/Cntr=0.3,0.1

Type RM Length L Ch R = 1 ,76604   ,630,630,630
BEGIN DESCRIPTION:
LAKE CREEK 100.0
END DESCRIPTION:
XS GIS Cut Line= 3
      3708446.13     10646083.54      3708409.67     10647000.25
      3708784.14     10648066.47
#Sta/Elev= 30
  4511.8  316.45    4558  313.28  4768.7  300.25  4818.7  294.98  4878.7  291.98
  4885.5  291.93  4948.8  286.97  4968.8  281.49  4985.8  279.17  4988.6  278.67
  4991.8  279.17  5028.9  284.17    5169   285.3  5192.6  287.24    5239  293.27
    5259  295.68  5329.1  298.47  5594.2  302.28  5619.9  303.57  5630.5  307.03
  5656.2  308.68  5672.9  306.93  5749.2  306.95  5774.9  308.29  5780.2  307.17
  5811.2   310.4  6017.5  317.68  6160.5  320.33  6316.7  325.31  6559.3  329.17
#Mann= 6 ,-1 , 0
  4511.8     .12       0    4558     .16       0  4885.5     .12       0
  4985.8     .07       0  4991.8     .12       0  5192.6     .05       0
Bank Sta=4878.7,5239
XS Rating Curve= 0 ,0
Exp/Cntr=0.3,0.1

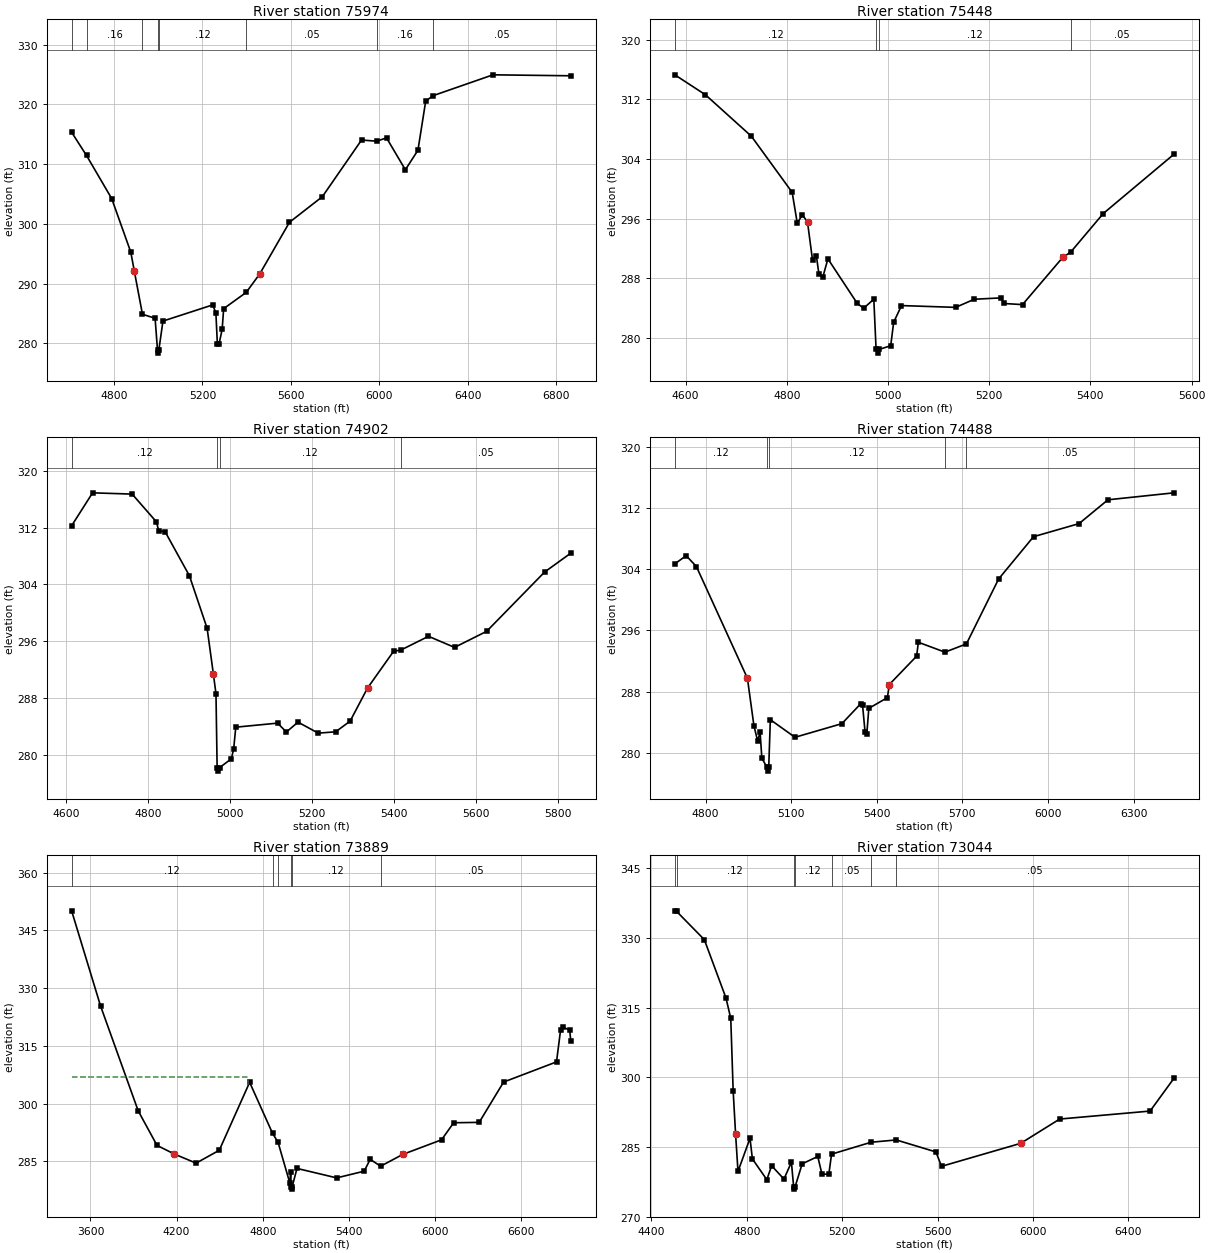
Type RM Length L Ch R = 1 ,75974   ,526,526,526
BEGIN DESCRIPTION:
LAKE CREEK 99.0
END DESCRIPTION:
XS GIS Cut Line= 3
      3708097.16     10646052.35      3707826.33      10646526.3
      3706687.57     10647804.55
#Sta/Elev= 30
  4608.4  315.35  4675.7  311.46  4789.7  304.24  4876.1  295.26  4891.9   292.1
  4928.8  284.86    4986  284.19  4996.9  278.85  4999.6  278.35  5002.9  278.85
  5021.5  283.72  5246.8  286.43    5261  285.06  5267.7  279.88  5275.2  279.85
  5289.4  282.36  5296.1   285.8  5398.1  288.52  5459.2  291.61  5593.8  300.27
  5742.6  304.56  5919.9  314.05    5988  313.85  6032.8  314.41    6118  309.07
  6174.9  312.33    6210  320.56  6243.4  321.48  6514.4  324.97  6866.2  324.81
#Mann= 8 ,-1 , 0
  4608.4     .12       0  4675.7     .16       0  4928.8     .12       0
  4996.9     .07       0  5002.9     .12       0  5398.1     .05       0
    5988     .16       0  6243.4     .05       0
Bank Sta=4891.9,5459.2
XS Rating Curve= 0 ,0
Exp/Cntr=0.3,0.1

Type RM Length L Ch R = 1 ,75448   ,546,546,546
BEGIN DESCRIPTION:
LAKE CREEK 98.0
END DESCRIPTION:
XS GIS Cut Line= 3
      3707549.61     10645710.16      3707499.61     10646110.19
      3707199.63     10646610.16
#Sta/Elev= 30
  4578.9  315.31  4639.4  312.63  4730.1  307.07  4810.7  299.54  4820.8   295.4
  4830.9  296.54    4841  295.55    4851   290.4  4858.6  290.99  4863.6  288.54
  4871.2  288.16  4881.3  290.62  4939.2  284.65  4951.8  283.99    4972   285.2
  4976.5  278.47  4979.3  277.97  4982.5  278.47  5005.4  278.96  5011.2   282.1
  5026.7  284.35  5133.6  284.11  5170.6   285.2  5223.1  285.38  5228.9  284.63
  5265.8  284.48  5345.5  290.83  5360.7   291.5  5425.2  296.69  5565.1  304.66
#Mann= 4 ,-1 , 0
  4578.9     .12       0  4976.5     .07       0  4982.5     .12       0
  5360.7     .05       0
Bank Sta=4841,5345.5
XS Rating Curve= 0 ,0
Exp/Cntr=0.3,0.1

Type RM Length L Ch R = 1 ,74902   ,414,414,414
BEGIN DESCRIPTION:
LAKE CREEK 97.0
END DESCRIPTION:
XS GIS Cut Line= 3
      3707599.63     10645610.18      3707249.61     10645810.19
      3706649.59     10646360.21
#Sta/Elev= 30
  4614.1  312.26  4665.2   316.9  4761.7  316.72  4820.7  312.82  4826.5  311.58
  4842.3   311.4  4901.3  305.22  4944.5  297.82  4959.6  291.44  4966.1   288.6
  4968.9   278.2  4971.6   277.7  4974.9   278.2  5003.6  279.43  5009.3  280.86
  5014.4  283.89  5116.2  284.46  5137.8  283.21  5166.1   284.6  5215.5  283.05
    5258  283.24  5293.2  284.74  5335.7  289.41  5399.2  294.58  5417.5  294.77
  5484.3  296.69  5547.8  295.13  5626.1  297.39  5767.4  305.74  5831.2   308.4
#Mann= 4 ,-1 , 0
  4614.1     .12       0  4968.9     .07       0  4974.9     .12       0
  5417.5     .05       0
Bank Sta=4959.6,5335.7
XS Rating Curve= 0 ,0
Exp/Cntr=0.3,0.1

Type RM Length L Ch R = 1 ,74488   ,599,599,599
BEGIN DESCRIPTION:
LAKE CREEK 96.0
END DESCRIPTION:
XS GIS Cut Line= 3
      3707316.94     10645352.27      3706943.67     10645612.69
      3706231.87      10646693.4
#Sta/Elev= 30
  4692.4  304.71  4732.1  305.77  4767.9  304.35  4946.7  289.76  4969.6  283.53
  4982.5  281.58  4991.2  282.69  4997.3   279.3  5015.4  278.13  5018.1  277.63
  5021.4  278.13    5027  284.35  5113.4  282.05  5277.7  283.83    5344  286.44
    5350   286.3    5359  282.73    5365  282.44  5372.1  285.83  5437.3  287.23
  5443.9  288.94  5539.7  292.65  5545.7  294.46  5638.9  293.17  5714.2  294.25
  5827.1  302.73  5949.3  308.25  6108.9  309.96  6210.2  313.07  6441.6  313.98
#Mann= 5 ,-1 , 0
  4692.4     .12       0  5015.4     .07       0  5021.4     .12       0
  5638.9     .07       0  5714.2     .05       0
Bank Sta=4946.7,5443.9
XS Rating Curve= 0 ,0
Exp/Cntr=0.3,0.1

Type RM Length L Ch R = 1 ,73889   ,845,845,845
BEGIN DESCRIPTION:
LAKE CREEK 95.0
END DESCRIPTION:
XS GIS Cut Line= 3
      3708449.61     10645260.19      3706899.61     10645060.19
      3705449.59     10646310.21
#Sta/Elev= 30
  3468.8  350.07  3670.5  325.34  3932.6  298.11  4063.7  289.14  4184.7  286.89
  4335.9  284.53  4497.3  287.87    4709  305.52  4868.5  292.28  4907.1  289.93
  4989.4   279.3  4994.5   282.1  4998.4  278.28  5001.2  277.78  5004.4  278.28
  5038.8  283.16  5315.3   280.7    5507  282.44  5548.9  285.53  5621.1  283.73
    5776   286.8  6045.9  290.59  6130.4  295.02  6308.1  295.12  6478.2  305.59
  6846.8  310.83  6875.3  319.14  6889.6  319.96  6938.9  319.01  6946.1  316.33
#Mann= 6 ,-1 , 0
  3468.8     .12       0  4868.5     .16       0  4907.1     .12       0
  4998.4     .07       0  5004.4     .12       0  5621.1     .05       0
#XS Ineff= 2 , 0
         4699.19  306.78
Permanent Ineff=
       F       F
Bank Sta=4184.7,5776
XS Rating Curve= 0 ,0
Exp/Cntr=0.3,0.1

Type RM Length L Ch R = 1 ,73044   ,271,271,271
BEGIN DESCRIPTION:
LAKE CREEK 94.0
END DESCRIPTION:
XS GIS Cut Line= 3
      3706440.85     10643947.55      3706495.42     10644384.77
      3705835.69     10645899.53
#Sta/Elev= 30
    4498  335.83  4505.3  335.71  4621.6  329.62  4712.3  317.07  4732.4  312.66
  4742.5  297.03  4752.6   287.8  4762.7  279.71  4813.1  286.85  4823.1  282.41
  4883.6  277.94  4903.8  280.93  4955.4  278.07  4986.7  281.69  4996.1   276.4
  4998.8   275.9  5002.1   276.4  5031.8  281.35  5097.2  282.93  5114.8  279.12
  5143.6  279.12    5155  283.43  5321.1     286  5426.3  286.49  5592.6  283.91
  5616.1  280.81    5948  285.76  6111.6  290.99  6490.6  292.71  6590.8  299.78
#Mann= 7 ,-1 , 0
    4498     .07       0  4505.3     .12       0  4996.1     .07       0
  5002.1     .12       0    5155     .05       0  5321.1     .07       0
  5426.3     .05       0
Bank Sta=4752.6,5948
XS Rating Curve= 0 ,0
Exp/Cntr=0.3,0.1

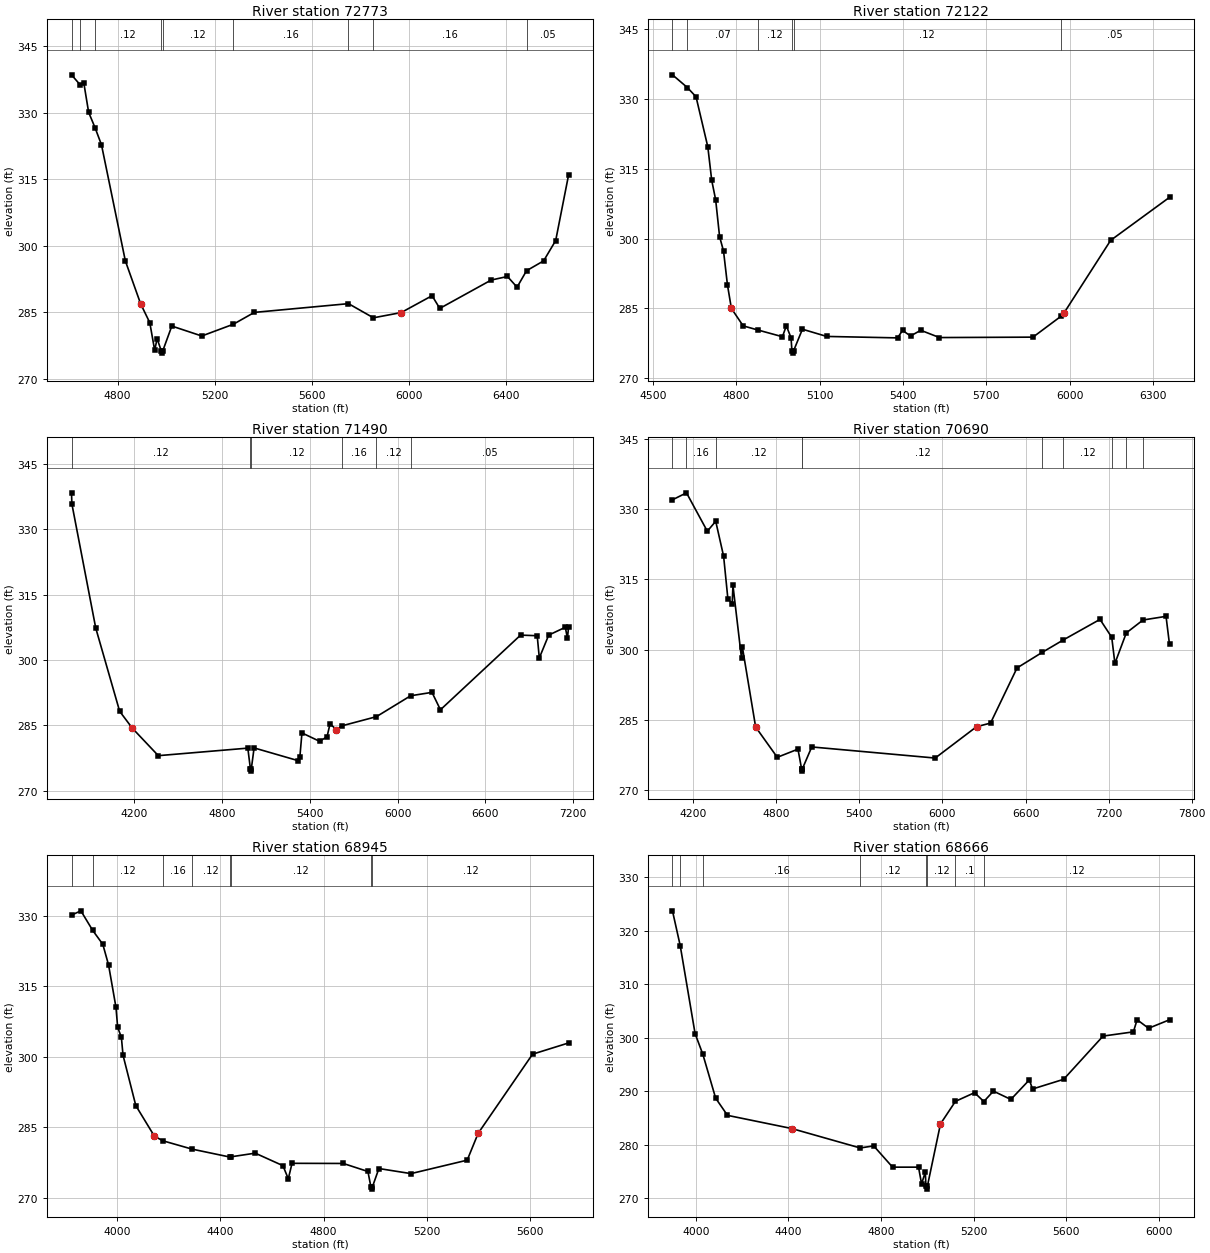
Type RM Length L Ch R = 1 ,72773   ,651,651,651
BEGIN DESCRIPTION:
LAKE CREEK 93.0
END DESCRIPTION:
XS GIS Cut Line= 3
      3706299.61     10643910.22      3706249.61     10644310.19
       3705699.6     10645860.21
#Sta/Elev= 30
  4610.3   338.5  4645.7  336.26  4660.7  336.76  4680.8  330.06    4707  326.61
  4733.7  322.74    4832  296.58    4895   286.9  4932.8  282.64  4952.9  276.42
    4963  279.04  4980.2  276.28  4982.9  275.78  4986.2  276.28  5023.5  281.88
    5147  279.64    5277  282.29  5363.5  284.96  5751.4  286.93  5854.1  283.74
  5968.4  284.92  6095.7  288.72  6127.5  285.86  6339.3  292.25  6406.3  293.05
  6445.9  290.64  6484.9  294.35  6555.3  296.57    6605  301.15  6658.1  315.92
#Mann= 9 ,-1 , 0
  4610.3     .12       0  4645.7     .07       0    4707     .12       0
  4980.2     .07       0  4986.2     .12       0    5277     .16       0
  5751.4     .05       0  5854.1     .16       0  6484.9     .05       0
Bank Sta=4895,5968.4
XS Rating Curve= 0 ,0
Exp/Cntr=0.3,0.1

Type RM Length L Ch R = 1 ,72122   ,632,632,632
BEGIN DESCRIPTION:
LAKE CREEK 92.0
END DESCRIPTION:
XS GIS Cut Line= 3
      3706099.62     10643860.17      3705799.61     10644160.19
      3705249.62     10645410.16
#Sta/Elev= 30
  4569.8  335.12  4623.3   332.4  4654.7  330.41  4697.1  319.67  4711.2  312.48
  4725.4   308.3  4739.5  300.42  4753.7  297.31  4767.8  290.07    4782  285.01
  4824.4  281.27  4876.2   280.4  4965.8  278.94  4979.9  281.28  4996.8  278.71
    5000  275.92  5002.8  275.42    5006  275.92  5037.8  280.55  5125.2     279
  5380.4  278.69  5398.3  280.29  5427.1   279.1  5463.9  280.32  5531.4  278.76
  5868.1  278.85  5968.5  283.31  5978.8  283.94  6147.7  299.61  6359.7  308.84
#Mann= 6 ,-1 , 0
  4569.8     .12       0  4623.3     .07       0  4876.2     .12       0
    5000     .07       0    5006     .12       0  5968.5     .05       0
Bank Sta=4782,5978.8
XS Rating Curve= 0 ,0
Exp/Cntr=0.3,0.1

Type RM Length L Ch R = 1 ,71490   ,800,800,800
BEGIN DESCRIPTION:
LAKE CREEK 91.0
END DESCRIPTION:
XS GIS Cut Line= 2
      3706376.22     10642663.69      3704260.38     10645322.06
#Sta/Elev= 30
  3770.9  338.37  3773.2  335.85  3936.5  307.33  4099.9  288.23  4186.4  284.35
  4364.2  278.04    4976  279.77  4993.8  274.99  4996.6  274.49  4999.8  274.99
  5018.9  279.82  5317.2  276.92  5331.6  277.68    5346  283.26  5466.3  281.34
  5517.4  282.37  5538.2  285.37  5581.3  284.01  5620.7   284.9    5855  286.99
    6089  291.79  6234.9  292.57  6292.6  288.57  6840.4  305.71  6954.1  305.57
  6968.5  300.46  7032.6  305.71  7146.3  307.51  7160.7  304.94  7168.5  307.61
#Mann= 6 ,-1 , 0
  3770.9     .12       0  4993.8     .07       0  4999.8     .12       0
  5620.7     .16       0    5855     .12       0    6089     .05       0
Bank Sta=4186.4,5581.3
XS Rating Curve= 0 ,0
Exp/Cntr=0.3,0.1

Type RM Length L Ch R = 1 ,70690   ,1745,1745,1745
BEGIN DESCRIPTION:
LAKE CREEK 90.0
END DESCRIPTION:
XS GIS Cut Line= 3
      3705746.88     10642251.38      3705356.28     10643043.44
      3703696.11     10645181.04
#Sta/Elev= 30
  4050.3  331.97  4151.6  333.46    4302  325.27  4362.7  327.39  4419.8  319.92
  4450.4  310.89  4481.6  309.79  4487.2   313.7    4549  298.16  4554.6  300.65
  4651.1  283.48  4807.2  277.02  4956.7  278.76  4982.7  274.57  4985.4  274.07
  4988.7  274.57  5056.3  279.23  5947.8  276.86  6246.4  283.55  6347.4  284.32
  6538.8  296.09  6722.2  299.44  6873.3  302.07  7137.9  306.45  7222.8  302.63
  7245.6  297.06  7328.1  303.57  7448.6  306.32  7614.9   307.1    7640   301.1
#Mann= 10 ,-1 , 0
  4050.3     .12       0  4151.6     .16       0  4362.7     .12       0
  4982.7     .07       0  4988.7     .12       0  6722.2     .16       0
  6873.3     .12       0  7222.8     .16       0  7328.1      .1       0
  7448.6     .16       0
Bank Sta=4651.1,6246.4
XS Rating Curve= 0 ,0
Exp/Cntr=0.3,0.1

Type RM Length L Ch R = 1 ,68945   ,279,279,279
BEGIN DESCRIPTION:
LAKE CREEK 89.0
END DESCRIPTION:
XS GIS Cut Line= 3
      3705254.77     10642623.99       3704421.4     10643283.74
        3703970.     10644021.61
#Sta/Elev= 30
  3822.4  330.09  3858.7     331  3904.6  326.83  3943.8  323.88  3966.1  319.48
  3994.8  310.48  4001.4  306.21  4015.8   304.1  4022.2  300.28  4071.8  289.57
    4144  283.06  4177.4  282.08  4289.9  280.32  4437.7  278.62  4440.5  278.68
    4535  279.46  4642.4   276.8  4663.2     274  4677.7   277.3  4876.4  277.27
    4972  275.56  4983.6  272.31  4986.4  271.81  4989.6  272.31  5014.6  276.19
    5139  275.11  5357.1  277.97  5399.7  283.69  5610.6  300.51  5750.3   302.9
#Mann= 8 ,-1 , 0
  3822.4     .05       0  3904.6     .12       0  4177.4     .16       0
  4289.9     .12       0  4437.7     .16       0  4440.5     .12       0
  4983.6     .07       0  4989.6     .12       0
Bank Sta=4144,5399.7
XS Rating Curve= 0 ,0
Exp/Cntr=0.3,0.1

Type RM Length L Ch R = 1 ,68666   ,954,954,954
BEGIN DESCRIPTION:
LAKE CREEK 88.0
END DESCRIPTION:
XS GIS Cut Line= 3
      3705101.46     10642580.79      3704337.62     10642969.65
      3703719.57     10644101.58
#Sta/Elev= 30
  3898.9  323.73  3932.5   317.2  3996.6  300.77  4030.3  296.87  4085.5  288.68
  4136.6  285.47  4413.6  283.01  4709.8  279.37    4768  279.76  4849.6  275.78
  4961.7  275.78  4974.9  272.64    4991  274.89  4993.7  272.17  4996.5  271.67
  4999.7  272.17  5056.5  283.87  5121.1  288.09  5203.6  289.71  5243.7  288.06
  5285.2     290  5360.5  288.45  5440.3   292.1  5454.1   290.4  5588.4  292.21
  5758.7   300.3  5889.7  301.09  5905.8  303.36  5955.2  301.76  6045.7  303.35
#Mann= 8 ,-1 , 0
  3898.9     .05       0  3932.5     .12       0  4030.3     .16       0
  4709.8     .12       0  4993.7     .07       0  4999.7     .12       0
  5121.1      .1       0  5243.7     .12       0
Bank Sta=4413.6,5056.5
XS Rating Curve= 0 ,0
Exp/Cntr=0.3,0.1