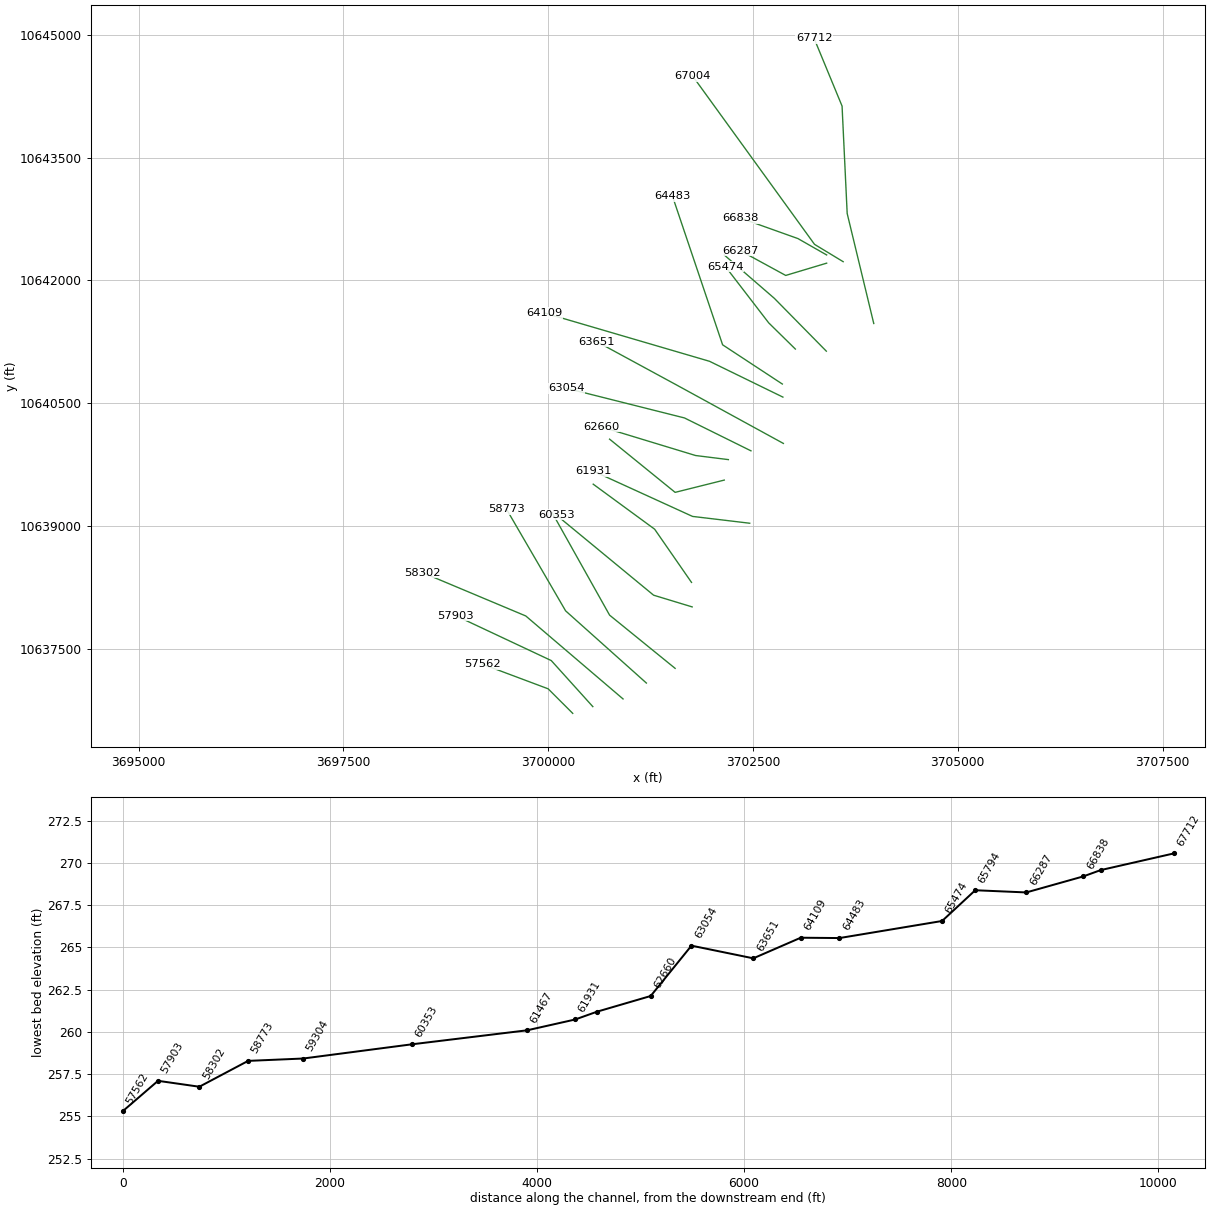
HEC-RAS study LAKE CREEK.prj: LAKE CREEK Base Level Engineering

--- LAKE CREEK.g01 (geometry) --- (continued)

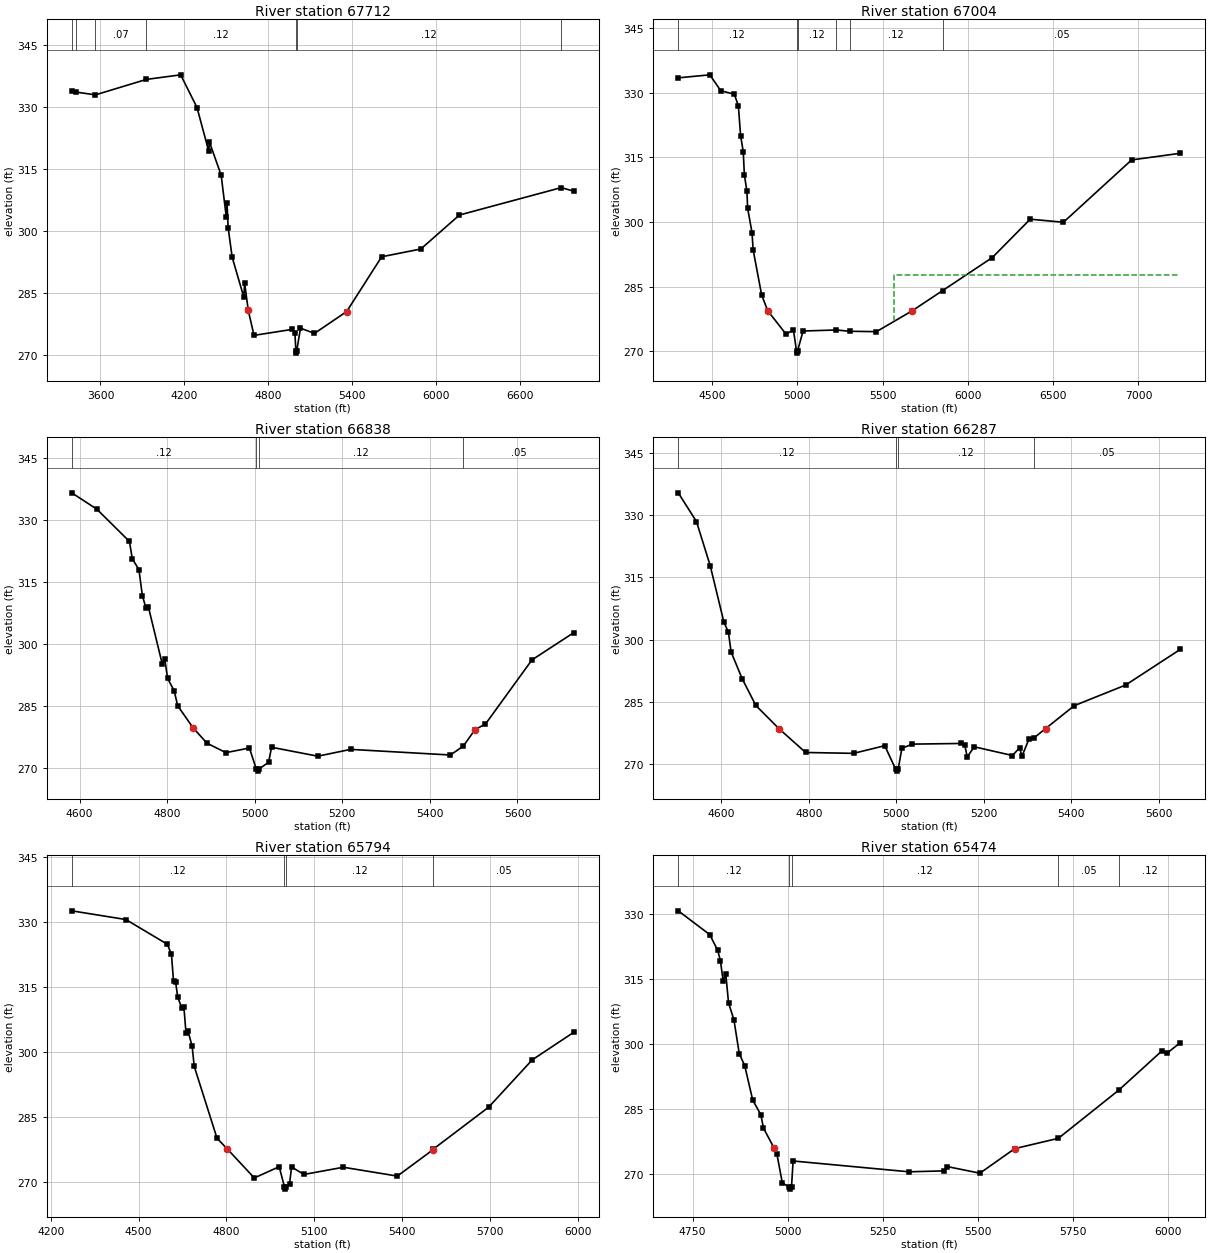
Type RM Length L Ch R = 1 ,67712   ,708,708,708
BEGIN DESCRIPTION:
LAKE CREEK 87.0
END DESCRIPTION:
XS GIS Cut Line= 4
      3703974.51     10641472.84      3703650.12     10642816.88
      3703587.62     10644129.38      3703245.92     10644956.68
#Sta/Elev= 30
  3394.6  333.82  3428.3  333.59  3563.7  332.93    3928  336.66  4173.7  337.77
  4290.6  329.86  4374.4  319.33  4379.5  321.53  4463.3  313.54    4500  303.38
  4505.2  306.79  4513.2  300.89  4541.9  293.73  4625.7  284.04  4630.8   287.6
  4657.2  280.86  4698.3  274.85  4970.8  276.29  4990.8  275.44  4997.8  271.06
  5000.5  270.56  5003.8  271.06  5030.8  276.59  5130.9  275.33  5361.2   280.6
  5611.5  293.83  5891.8  295.71  6167.8  303.91  6896.1  310.53  6986.3  309.67
#Mann= 7 ,-1 , 0
  3394.6     .07       0  3428.3     .12       0  3563.7     .07       0
    3928     .12       0  4997.8     .07       0  5003.8     .12       0
  6896.1     .05       0
Bank Sta=4657.2,5361.2
XS Rating Curve= 0 ,0
Exp/Cntr=0.3,0.1

Type RM Length L Ch R = 1 ,67004   ,166,166,166
BEGIN DESCRIPTION:
Mapping XS 7e19df5d
END DESCRIPTION:
XS GIS Cut Line= 3
      3703601.26     10642228.03      3703251.46     10642439.82
      3701765.28      10644493.7
#Sta/Elev= 30
  4301.4  333.43  4486.8  334.13  4550.8  330.44  4630.6  329.63    4654  326.91
  4667.2  319.98  4682.7  316.29  4689.1  310.95    4704  307.16  4708.5  303.15
  4734.2  297.49  4740.3   293.6  4790.6  283.05  4826.2   279.4    4933     274
    4977  274.92  4994.9  270.07  4997.6  269.57  5000.9  270.07  5033.5   274.7
  5226.6  274.94  5307.7  274.64  5463.7  274.55  5672.3  279.37  5851.4  284.07
  6143.3  291.75  6365.3  300.64  6560.2  299.93    6960  314.39  7245.5  315.93
#Mann= 6 ,-1 , 0
  4301.4     .12       0  4994.9     .07       0  5000.9     .12       0
  5226.6     .07       0  5307.7     .12       0  5851.4     .05       0
#XS Ineff= 2 , 0
                          5568.6          287.74
Permanent Ineff=
       F       F
Bank Sta=4826.2,5672.3
XS Rating Curve= 0 ,0
Exp/Cntr=0.3,0.1

Type RM Length L Ch R = 1 ,66838   ,551,551,551
BEGIN DESCRIPTION:
LAKE CREEK 85.0
END DESCRIPTION:
XS GIS Cut Line= 3
      3703399.58     10642310.21      3703049.61     10642510.19
      3702349.59      10642760.2
#Sta/Elev= 30
  4582.3   336.5  4639.8  332.52    4714  324.74  4720.5  320.54  4735.6  317.95
  4743.5  311.65  4751.4  308.71  4757.2  308.94  4788.9   295.1  4794.6  296.32
  4801.1  291.62  4816.2  288.62  4824.1  285.01  4859.4  279.66  4891.1  275.95
  4934.3  273.67    4988  274.79  5003.6   269.7  5006.4   269.2  5009.6   269.7
  5031.6  271.32  5038.5  274.97  5144.1  272.81    5219  274.46  5446.8   273.1
  5476.5  275.26    5503  279.24  5526.9  280.58  5633.1   296.1  5728.7   302.7
#Mann= 4 ,-1 , 0
  4582.3     .12       0  5003.6     .07       0  5009.6     .12       0
  5476.5     .05       0
Bank Sta=4859.4,5503
XS Rating Curve= 0 ,0
Exp/Cntr=0.3,0.1

Type RM Length L Ch R = 1 ,66287   ,493,493,493
BEGIN DESCRIPTION:
LAKE CREEK 84.0
END DESCRIPTION:
XS GIS Cut Line= 3
      3703399.59     10642210.18      3702899.61     10642060.19
       3702349.6     10642360.19
#Sta/Elev= 30
  4501.1  335.43  4542.8   328.5  4574.2  317.86  4605.5  304.24  4615.9  301.78
    4622  297.02  4647.2  290.59  4678.6   284.1  4731.6  278.49  4792.5  272.75
  4902.2  272.54  4973.5  274.39  4998.3  268.75  5001.1  268.25  5004.3  268.75
  5012.7  273.77  5036.9  274.77  5148.4  274.93  5156.5  274.54  5162.2  271.69
  5178.3  274.12  5265.6  272.02  5281.8  273.86  5287.5  271.89  5303.6  276.01
  5313.9  276.18  5341.6  278.54  5407.1  284.06  5524.3  289.02  5649.6  297.64
#Mann= 4 ,-1 , 0
  4501.1     .12       0  4998.3     .07       0  5004.3     .12       0
  5313.9     .05       0
Bank Sta=4731.6,5341.6
XS Rating Curve= 0 ,0
Exp/Cntr=0.3,0.1

Type RM Length L Ch R = 1 ,65794   ,320,320,320
BEGIN DESCRIPTION:
LAKE CREEK 83.0
END DESCRIPTION:
XS GIS Cut Line= 3
      3703395.61     10641134.82      3702760.92     10641780.39
      3702149.57     10642310.22
#Sta/Elev= 30
  4272.1  332.63  4456.9  330.62  4598.4  324.91  4612.5  322.58  4619.5  316.38
  4626.7  316.19  4633.7  312.76  4647.8  310.18  4654.9  310.45    4662  304.52
  4669.1  304.86  4683.2  301.33  4690.2  296.73  4768.1  280.12  4803.4  277.63
  4895.4  270.96  4980.3  273.56  4998.4  268.88  5001.2  268.38  5004.4  268.88
  5015.6  269.63  5022.7  273.48    5065  271.77  5199.5  273.43  5383.7  271.39
  5504.4  277.42  5506.9  277.64  5695.2  287.28  5844.4  298.23  5986.4   304.6
#Mann= 4 ,-1 , 0
  4272.1     .12       0  4998.4     .07       0  5004.4     .12       0
  5506.9     .05       0
Bank Sta=4803.4,5504.4
XS Rating Curve= 0 ,0
Exp/Cntr=0.3,0.1

Type RM Length L Ch R = 1 ,65474   ,991,991,991
BEGIN DESCRIPTION:
LAKE CREEK 82.0
END DESCRIPTION:
XS GIS Cut Line= 3
      3703017.28      10641160.9      3702691.83     10641481.06
      3702165.75     10642165.76
#Sta/Elev= 30
  4712.2  330.84  4794.9  325.36  4816.1   321.7  4823.2  319.25  4830.3  314.64
  4837.3  316.16  4844.4  309.62  4858.6  305.66  4872.7  297.82  4886.9  295.11
    4908  287.12  4929.3  283.77  4936.3  280.65  4964.6  275.99  4971.7  274.62
  4985.9  267.98    5004  267.06  5006.8  266.56    5010  267.06  5014.2  273.06
    5319  270.56    5412  270.78  5419.9  271.76  5505.3  270.24  5596.8  275.91
  5711.7   278.3  5870.1   289.4  5982.9  298.41  5997.4  297.97  6032.2   300.4
#Mann= 5 ,-1 , 0
  4712.2     .12       0    5004     .07       0    5010     .12       0
  5711.7     .05       0  5870.1     .12       0
Bank Sta=4964.6,5596.8
XS Rating Curve= 0 ,0
Exp/Cntr=0.3,0.1

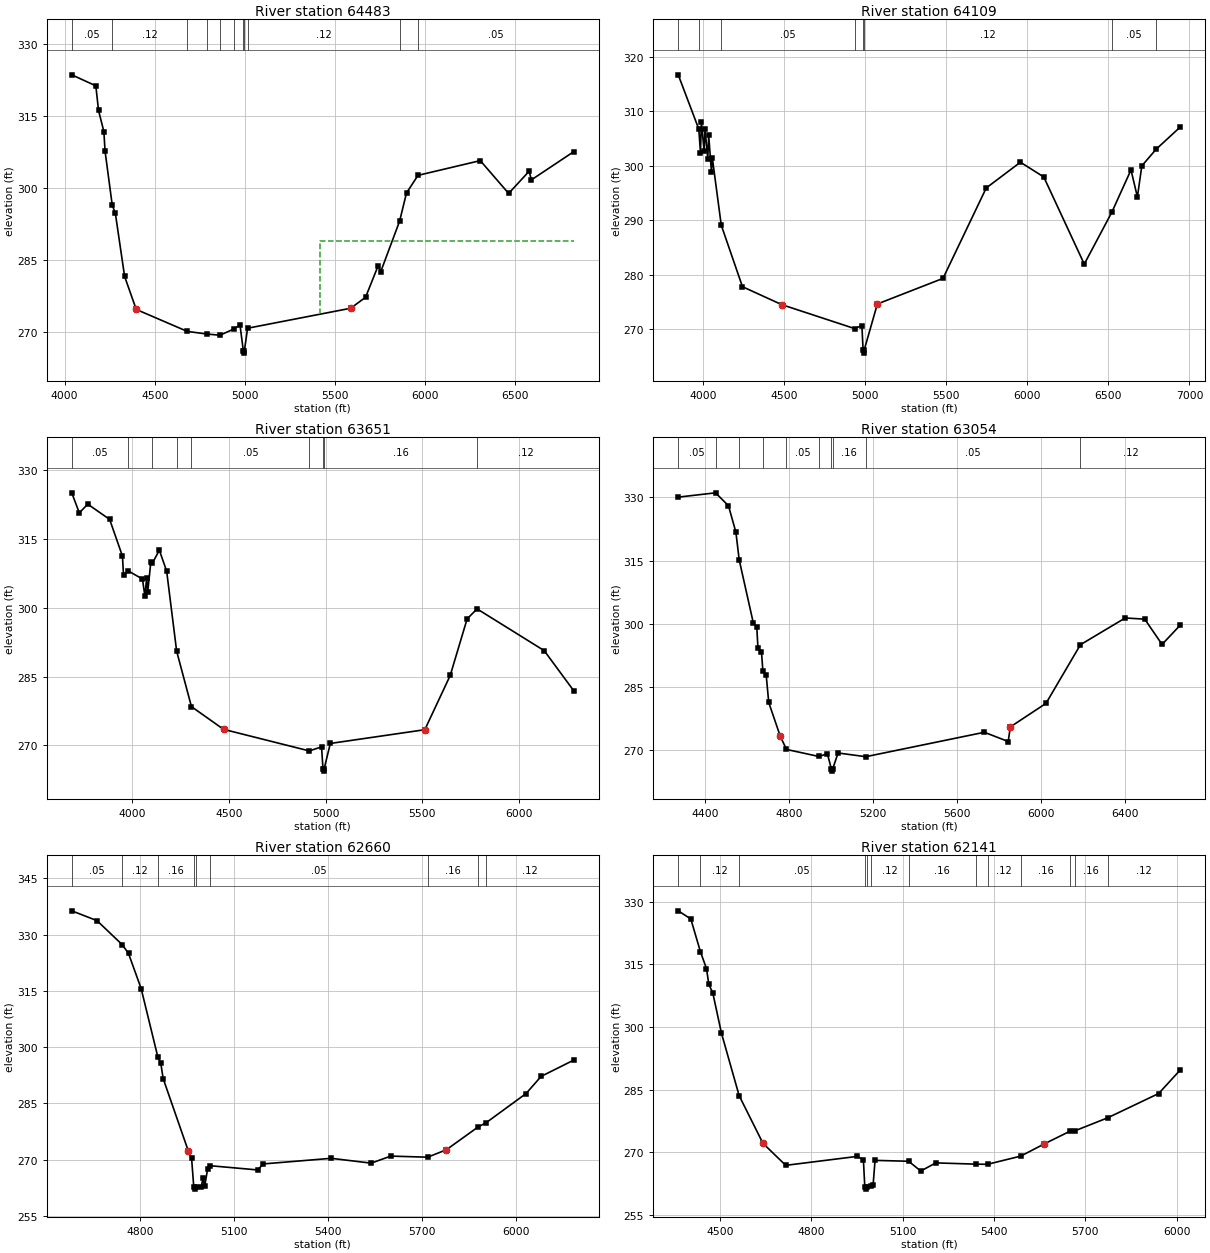
Type RM Length L Ch R = 1 ,64483   ,374,374,374
BEGIN DESCRIPTION:
LAKE CREEK 81.0
END DESCRIPTION:
XS GIS Cut Line= 3
      3702858.46     10640733.53      3702129.28     10641212.71
      3701518.17     10643025.23
#Sta/Elev= 30
  4039.6  323.58    4173  321.29    4188  316.18  4217.7  311.73  4224.2  307.68
  4264.1  296.41  4281.4   294.7  4332.7  281.54  4397.2  274.66  4680.5  270.08
  4787.7  269.54  4861.6  269.28  4938.9  270.59  4972.8  271.42  4991.3  266.05
    4994  265.55  4997.3  266.05  5014.9  270.74  5587.1  274.91  5669.3  277.19
  5739.2  283.76  5753.7  282.54  5858.3  293.07  5896.6  298.95  5960.4  302.62
  6305.9  305.69  6463.2  298.85  6576.9  303.48  6589.2  301.67  6824.9  307.57
#Mann= 11 ,-1 , 0
  4039.6     .05       0  4264.1     .12       0  4680.5     .05       0
  4787.7     .07       0  4861.6     .05       0  4938.9     .07       0
  4991.3     .07       0  4997.3     .07       0  5014.9     .12       0
  5858.3     .16       0  5960.4     .05       0
#XS Ineff= 2 , 0
                         5417.68          288.96
Permanent Ineff=
       F       F
Bank Sta=4397.2,5587.1
XS Rating Curve= 0 ,0
Exp/Cntr=0.3,0.1

Type RM Length L Ch R = 1 ,64109   ,458,458,458
BEGIN DESCRIPTION:
LAKE CREEK 80.0
END DESCRIPTION:
XS GIS Cut Line= 3
      3702865.36     10640573.84      3701969.56     10641011.32
      3699955.71     10641601.59
#Sta/Elev= 30
  3848.4  316.65  3975.3  306.68  3985.5  302.37  3991.1  308.08    4008  302.65
  4013.6  306.68  4030.5  301.28  4036.1  305.56  4053.1  298.85  4058.6  301.39
  4113.6  289.06  4244.4  277.76  4486.6  274.47  4935.4  270.08  4980.7  270.63
  4988.2  266.07  4990.9  265.57  4994.2  266.07  5076.1  274.59  5480.9  279.29
  5747.3  295.88  5958.1  300.61  6102.2   297.9  6351.7  281.91  6522.2  291.46
  6639.8   299.2  6679.3  294.23  6706.6  299.94  6794.7  302.99  6943.9  307.08
#Mann= 8 ,-1 , 0
  3848.4     .05       0  3975.3     .16       0  4113.6     .05       0
  4935.4     .12       0  4988.2     .07       0  4994.2     .12       0
  6522.2     .05       0  6794.7     .12       0
Bank Sta=4486.6,5076.1
XS Rating Curve= 0 ,0
Exp/Cntr=0.3,0.1

Type RM Length L Ch R = 1 ,63651   ,597,597,597
BEGIN DESCRIPTION:
LAKE CREEK 79.0
END DESCRIPTION:
XS GIS Cut Line= 3
      3702871.25     10640007.83      3701575.88     10640717.29
      3700594.08     10641250.56
#Sta/Elev= 30
  3688.6  325.09  3727.6  320.71  3771.2  322.62  3884.3  319.29  3950.4  311.28
  3956.1  307.09  3978.6  308.08  4053.7  306.29  4066.7   302.5  4075.5  306.52
  4081.2  303.55  4097.3  310.08  4104.9  309.71    4141  312.58  4178.9  307.99
  4230.5  290.53  4306.9  278.43  4472.8  273.47  4916.1  268.76  4979.2  269.65
  4986.6  264.85  4989.3  264.35  4992.6  264.85  5024.5  270.39  5512.8  273.39
    5644  285.23  5731.4  297.58  5782.8  299.76  6129.6  290.65  6282.8  281.86
#Mann= 9 ,-1 , 0
  3688.6     .05       0  3978.6     .16       0  4104.9     .12       0
  4230.5     .16       0  4306.9     .05       0  4916.1     .16       0
  4986.6     .03       0  4992.6     .16       0  5782.8     .12       0
Bank Sta=4472.8,5512.8
XS Rating Curve= 0 ,0
Exp/Cntr=0.3,0.1

Type RM Length L Ch R = 1 ,63054   ,394,394,394
BEGIN DESCRIPTION:
LAKE CREEK 78.0
END DESCRIPTION:
XS GIS Cut Line= 3
       3702475.5     10639917.51      3701663.72     10640319.26
      3700225.47     10640681.42
#Sta/Elev= 30
  4272.9  330.04  4450.4  331.06  4511.9     328  4547.3  321.71  4562.9  315.18
  4629.7  300.32  4646.5  299.27  4652.1  294.39  4668.9  293.43  4675.5  288.91
  4691.4  287.86  4703.5  281.37  4758.7  273.32    4788  270.24  4942.2  268.57
  4982.4  269.22  5001.7   265.6  5004.5   265.1  5007.7   265.6  5033.4   269.4
  5165.2  268.52  5729.4  274.31  5842.9  272.12  5853.1  275.58  6022.7  281.16
  6186.6  295.06  6399.7   301.4  6492.5  301.12    6575  295.13  6661.8  299.72
#Mann= 10 ,-1 , 0
  4272.9     .05       0  4450.4     .16       0  4562.9     .12       0
  4675.5     .16       0    4788     .05       0  4942.2     .16       0
  5001.7     .07       0  5007.7     .16       0  5165.2     .05       0
  6186.6     .12       0
Bank Sta=4758.7,5853.1
XS Rating Curve= 0 ,0
Exp/Cntr=0.3,0.1

Type RM Length L Ch R = 1 ,62660   ,519,519,519
BEGIN DESCRIPTION:
LAKE CREEK 77.0
END DESCRIPTION:
XS GIS Cut Line= 3
      3702199.66     10639810.18      3701799.61     10639860.19
      3700649.65     10640210.18
#Sta/Elev= 30
  4580.7  336.36  4661.4  333.74  4742.7  327.28  4762.1  324.98  4802.5  315.62
  4855.9  297.35  4865.4  295.64    4873  291.58  4953.6  272.23  4963.7  270.44
  4970.8  262.62  4973.5  262.12  4976.8  262.62  4994.3  262.65  5000.3  265.05
  5005.5  262.84  5015.2  267.59  5023.9  268.36    5175  267.24  5192.9  268.84
  5410.2  270.34  5537.9  269.05  5600.6  270.93  5718.6  270.64  5778.3  272.62
    5880  278.72  5904.5  279.78  6032.9   287.6  6081.4   292.2  6185.9  296.55
#Mann= 9 ,-1 , 0
  4580.7     .05       0  4742.7     .12       0  4855.9     .16       0
  4970.8     .07       0  4976.8     .16       0  5023.9     .05       0
  5718.6     .16       0    5880     .05       0  5904.5     .12       0
Bank Sta=4953.6,5778.3
XS Rating Curve= 0 ,0
Exp/Cntr=0.3,0.1

Type RM Length L Ch R = 1 ,62141   ,210,210,210
BEGIN DESCRIPTION:
LAKE CREEK 76.0
END DESCRIPTION:
XS GIS Cut Line= 3
      3702149.65      10639560.2      3701549.61     10639410.19
      3700749.59      10640060.2
#Sta/Elev= 30
  4363.2  327.79  4404.5  325.84  4436.3  317.95    4456  313.97  4463.7  310.18
  4476.6  308.18    4505  298.56  4563.3  283.55  4641.5  272.16  4716.3  266.88
  4950.8  269.02  4971.4  268.27  4976.1  261.69  4978.9  261.19  4982.1  261.69
  4996.8  261.88  5003.3  262.13  5009.7  268.07    5120  267.86  5159.9  265.52
  5209.4  267.47  5340.2  267.17  5379.2  267.13  5488.6   269.1  5564.2  271.96
  5651.5   275.1  5666.1  275.14    5774  278.26  5941.4  284.07  6012.5  289.72
#Mann= 13 ,-1 , 0
  4363.2     .05       0  4436.3     .12       0  4563.3     .05       0
  4976.1     .07       0  4982.1     .05       0  4996.8     .12       0
    5120     .16       0  5340.2     .05       0  5379.2     .12       0
  5488.6     .16       0  5651.5     .05       0  5666.1     .16       0
    5774     .12       0
Bank Sta=4641.5,5564.2
XS Rating Curve= 0 ,0
Exp/Cntr=0.3,0.1

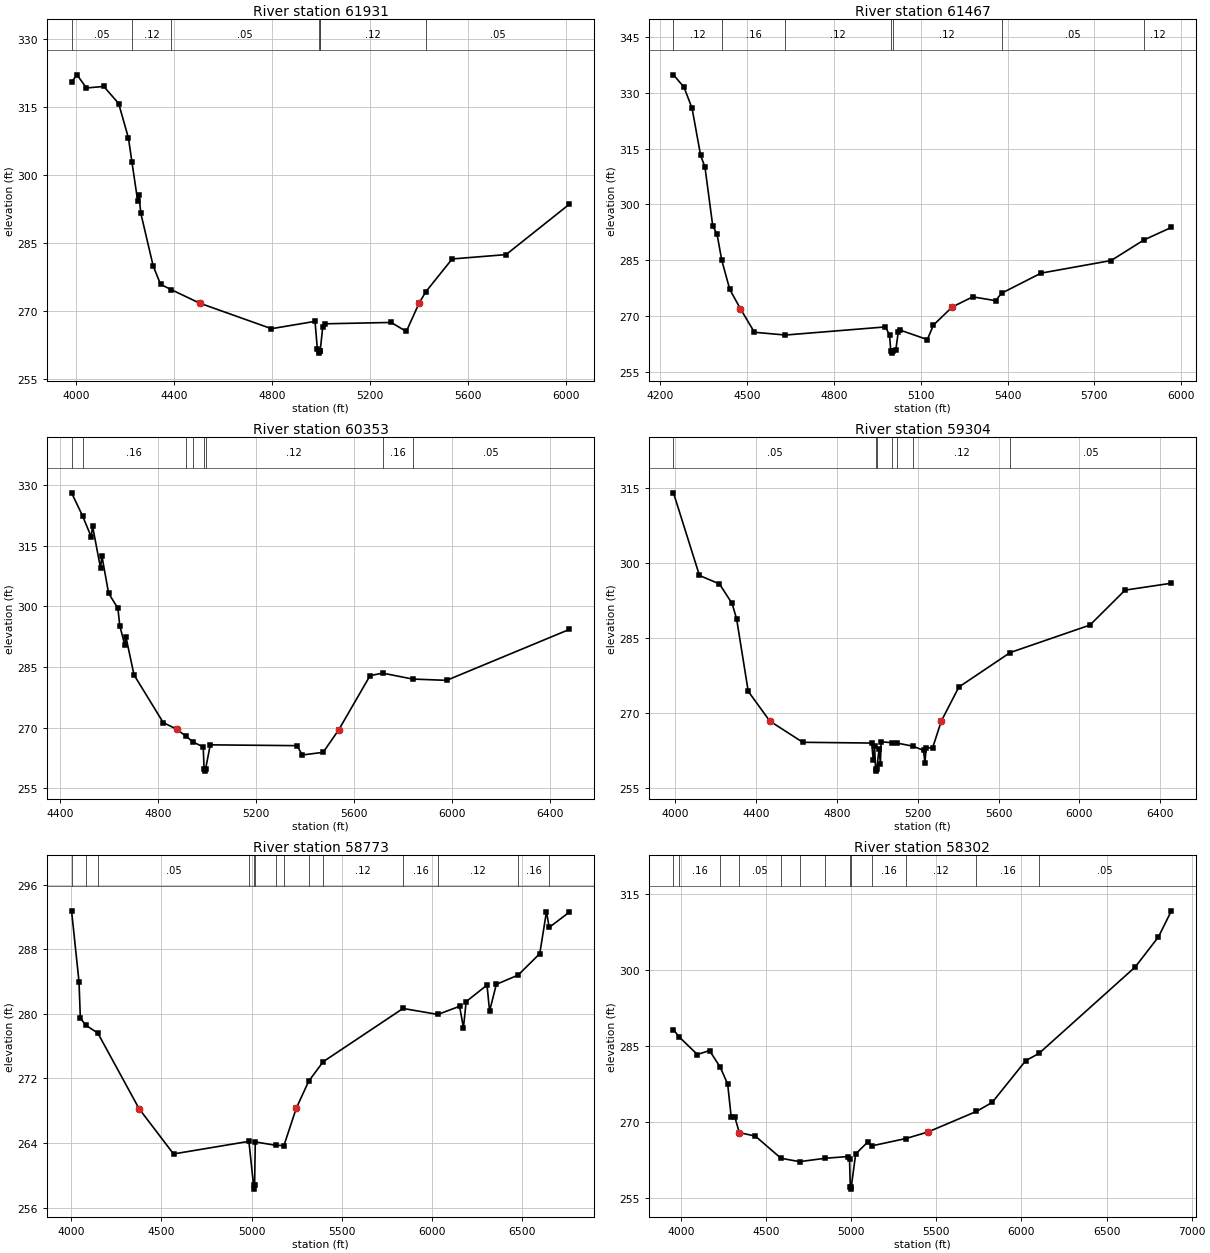
Type RM Length L Ch R = 1 ,61931   ,464,464,464
BEGIN DESCRIPTION:
Mapping XS 0fbb9b23
END DESCRIPTION:
XS GIS Cut Line= 3
      3702460.11     10639032.99       3701762.2     10639116.32
      3700554.27     10639668.21
#Sta/Elev= 30
  3982.6  320.54  4004.7  322.14  4043.5  319.24    4114  319.58  4174.7  315.81
  4214.7  308.17    4229  302.84  4252.1  294.38  4257.1  295.71  4265.1  291.59
  4315.4  279.98  4345.7   275.9  4388.2  274.77  4504.5  271.77  4797.9  266.12
  4975.6  267.74  4985.2   261.6  4990.1  261.23  4992.9  260.73  4996.1  261.23
  4996.7  261.27  5007.1  266.47  5016.1   267.2  5285.9   267.5    5348  265.51
    5401  271.87    5428   274.3  5534.9  281.51  5754.8  282.47  6013.5  293.61
#Mann= 7 ,-1 , 0
  3982.6     .05       0    4229     .12       0  4388.2     .05       0
  4990.1     .07       0  4996.1     .05       0  4996.7     .12       0
    5428     .05       0
Bank Sta=4504.5,5401
XS Rating Curve= 0 ,0
Exp/Cntr=0.3,0.1

Type RM Length L Ch R = 1 ,61467   ,1114,1114,1114
BEGIN DESCRIPTION:
LAKE CREEK 75.0
END DESCRIPTION:
XS GIS Cut Line= 3
      3701749.59     10638310.21      3701299.61     10638960.19
       3700549.6     10639510.19
#Sta/Elev= 30
  4245.7  334.82  4282.2  331.49  4309.9  325.86  4339.6  313.18  4354.5  310.07
  4381.5  294.22  4396.3  292.05  4412.4  285.09  4440.3  277.19  4476.8  272.05
  4525.4  265.69  4632.5  264.95  4978.1  267.13  4992.3  264.99  4996.7  260.59
  4999.5  260.09  5002.7  260.59  5013.9  260.88  5022.7  265.87  5028.8  266.28
    5123  263.73  5143.9  267.61  5208.7  272.46  5279.7   275.2  5358.7  274.18
  5379.4  276.17  5515.9  281.57  5758.3  284.96  5871.2  290.47  5966.3  293.85
#Mann= 7 ,-1 , 0
  4245.7     .12       0  4412.4     .16       0  4632.5     .12       0
  4996.7     .07       0  5002.7     .12       0  5379.4     .05       0
  5871.2     .12       0
Bank Sta=4476.8,5208.7
XS Rating Curve= 0 ,0
Exp/Cntr=0.3,0.1

Type RM Length L Ch R = 1 ,60353   ,1049,1049,1049
BEGIN DESCRIPTION:
LAKE CREEK 74.0
END DESCRIPTION:
XS GIS Cut Line= 3
      3701757.91      10638010.7      3701286.97     10638153.94
      3700097.75     10639134.83
#Sta/Elev= 30
    4447  328.09  4492.1  322.36  4527.4  317.19  4532.6  319.91  4565.5  309.41
  4570.7  312.55  4598.3  303.26  4636.4   299.5  4643.8  295.25  4664.1   290.5
  4669.3  292.39  4702.1  283.06  4821.5  271.26  4876.9  269.62  4914.9  267.84
  4944.9  266.42  4984.8  265.24  4988.3  259.76    4991  259.26  4994.3  259.76
  5013.5  265.76  5367.8  265.56  5389.5  263.25  5474.7  263.91  5538.5   269.5
  5666.2  282.87  5717.4   283.5  5840.4  282.03  5978.9  281.71  6480.8  294.32
#Mann= 8 ,-1 , 0
    4447     .05       0  4492.1     .16       0  4914.9     .05       0
  4944.9     .12       0  4988.3     .07       0  4994.3     .12       0
  5717.4     .16       0  5840.4     .05       0
Bank Sta=4876.9,5538.5
XS Rating Curve= 0 ,0
Exp/Cntr=0.3,0.1

Type RM Length L Ch R = 1 ,59304   ,531,531,531
BEGIN DESCRIPTION:
LAKE CREEK 73.0
END DESCRIPTION:
XS GIS Cut Line= 3
      3701549.62     10637260.18      3700749.61     10637910.19
      3700049.63     10639160.15
#Sta/Elev= 30
  3991.8  314.02  4120.4  297.51  4219.5  295.81  4281.7  291.92  4304.3  288.82
  4361.7  274.36  4468.5  268.42  4631.8  264.18  4972.3  264.03  4980.2  260.73
  4986.7  263.53  4991.6  258.92  4994.3  258.42  4997.6  258.92    5009  262.83
  5015.4  259.92  5019.4  264.28  5072.6   264.1  5098.2  264.02  5176.1  263.41
  5228.9  262.57  5236.1  260.06  5241.8   263.1  5273.7  263.04  5317.1  268.44
  5403.9  275.22  5657.8  282.11  6052.3   287.6    6226  294.58  6455.2  295.96
#Mann= 7 ,-1 , 0
  3991.8     .05       0  4991.6     .03       0  4997.6     .05       0
  5072.6     .12       0  5098.2     .07       0  5176.1     .12       0
  5657.8     .05       0
Bank Sta=4468.5,5317.1
XS Rating Curve= 0 ,0
Exp/Cntr=0.3,0.1

Type RM Length L Ch R = 1 ,58773   ,471,471,471
BEGIN DESCRIPTION:
LAKE CREEK 72.0
END DESCRIPTION:
XS GIS Cut Line= 3
      3701198.73     10637080.76      3700212.62     10637962.71
      3699490.55      10639205.5
#Sta/Elev= 30
  4002.3  292.77  4043.5  283.99    4051   279.5  4079.7  278.61  4147.7  277.62
  4376.8  268.24  4567.6  262.64  4985.4   264.2    5011  258.78  5013.8  258.28
    5017  258.78  5020.7  264.13  5134.7  263.71  5179.6  263.68    5248   268.3
    5317  271.66  5397.2  274.07  5839.8  280.67  6033.2  279.93  6153.3  280.94
  6174.8  278.28  6189.8  281.52  6305.4  283.57  6319.7  280.33  6356.9  283.66
  6477.6   284.8  6597.8  287.46    6635  292.66    6650  290.71  6762.6  292.62
#Mann= 14 ,-1 , 0
  4002.3     .12       0  4079.7     .16       0  4147.7     .05       0
  4985.4     .12       0    5011     .07       0    5017     .12       0
  5134.7     .07       0  5179.6     .05       0    5317     .16       0
  5397.2     .12       0  5839.8     .16       0  6033.2     .12       0
  6477.6     .16       0    6650     .05       0
Bank Sta=4376.8,5248
XS Rating Curve= 0 ,0
Exp/Cntr=0.3,0.1

Type RM Length L Ch R = 1 ,58302   ,399,399,399
BEGIN DESCRIPTION:
LAKE CREEK 71.0
END DESCRIPTION:
XS GIS Cut Line= 3
      3700914.02      10636886.3      3699726.51     10637900.21
      3698469.59     10638427.98
#Sta/Elev= 30
  3956.2  288.26  3987.8  286.88  4096.6  283.34    4168  284.12  4230.9  280.83
  4274.5  277.53  4295.3  271.01    4317  270.94  4343.1  267.91  4436.9  267.23
  4587.8  262.84  4697.2  262.18  4848.8  262.85  4983.7  263.19  4990.3  262.79
    4995  257.25  4997.7  256.75    5001  257.25  5026.5   263.7  5096.8  266.03
  5120.2  265.29  5322.2  266.75  5451.4  268.04    5736   272.1  5828.8  273.89
  6025.4  282.13  6102.6  283.54  6668.2  300.62    6805  306.57  6880.9  311.72
#Mann= 13 ,-1 , 0
  3956.2     .05       0  3987.8     .16       0  4230.9     .12       0
  4343.1     .05       0  4587.8     .07       0  4697.2     .05       0
  4848.8     .12       0    4995     .07       0    5001     .12       0
  5120.2     .16       0  5322.2     .12       0    5736     .16       0
  6102.6     .05       0
Bank Sta=4343.1,5451.4
XS Rating Curve= 0 ,0
Exp/Cntr=0.3,0.1

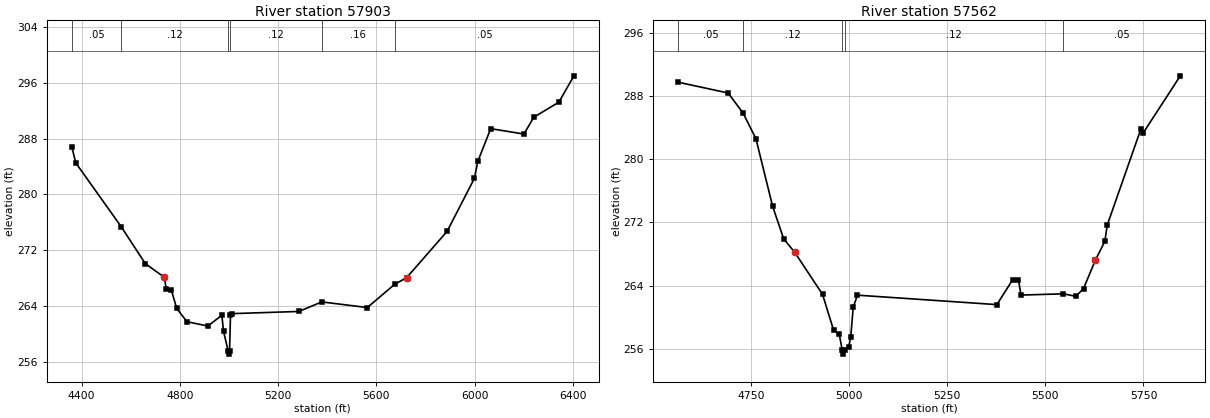
Type RM Length L Ch R = 1 ,57903   ,341,341,341
BEGIN DESCRIPTION:
Mapping XS 11f047b6
END DESCRIPTION:
XS GIS Cut Line= 3
      3700544.91     10636792.52      3700037.95     10637355.03
      3698872.97     10637902.85
#Sta/Elev= 30
  4359.9  286.86  4376.1  284.54  4560.7   275.4  4659.4  270.08  4737.1  268.11
  4744.6   266.4  4765.5  266.28  4787.2  263.65    4829  261.75  4914.2  261.13
    4971  262.68  4977.8  260.36  4996.4   257.6  4999.2   257.1  5002.4   257.6
  5006.2  262.67  5013.6  262.91  5284.3  263.22  5378.1  264.59  5563.4  263.78
  5675.4  267.14    5723  268.05  5888.2  274.71  5999.4  282.32  6013.2  284.75
  6065.7  289.44  6201.1  288.67  6241.2  291.08  6343.5  293.25  6404.5  297.02
#Mann= 6 ,-1 , 0
  4359.9     .05       0  4560.7     .12       0  4996.4     .07       0
  5002.4     .12       0  5378.1     .16       0  5675.4     .05       0
Bank Sta=4737.1,5723
XS Rating Curve= 0 ,0
Exp/Cntr=0.3,0.1

Type RM Length L Ch R = 1 ,57562   ,1007,1007,1007
BEGIN DESCRIPTION:
LAKE CREEK 70.0
END DESCRIPTION:
XS GIS Cut Line= 3
      3700299.64     10636710.15      3699999.61     10637010.19
      3699199.62     10637310.18
#Sta/Elev= 30
  4565.1  289.79  4692.4  288.42  4730.4  285.87  4763.1  282.63  4805.6  274.05
  4833.8  269.92  4862.1   268.2  4932.8  262.87  4961.1   258.3  4975.3  257.82
  4982.9   255.8  4985.6   255.3  4988.9   255.8  4999.2  256.23  5004.5  257.45
  5010.8  261.23  5021.5  262.78  5376.6  261.58  5416.6  264.71  5431.7  264.72
    5438  262.79  5546.2  262.95  5577.7  262.63  5597.3  263.61  5627.5  267.22
  5651.6   269.6  5657.8  271.68  5743.2  283.82  5748.6   283.3  5843.8   290.6
#Mann= 5 ,-1 , 0
  4565.1     .05       0  4730.4     .12       0  4982.9     .07       0
  4988.9     .12       0  5546.2     .05       0
Bank Sta=4862.1,5627.5
XS Rating Curve= 0 ,0
Exp/Cntr=0.3,0.1