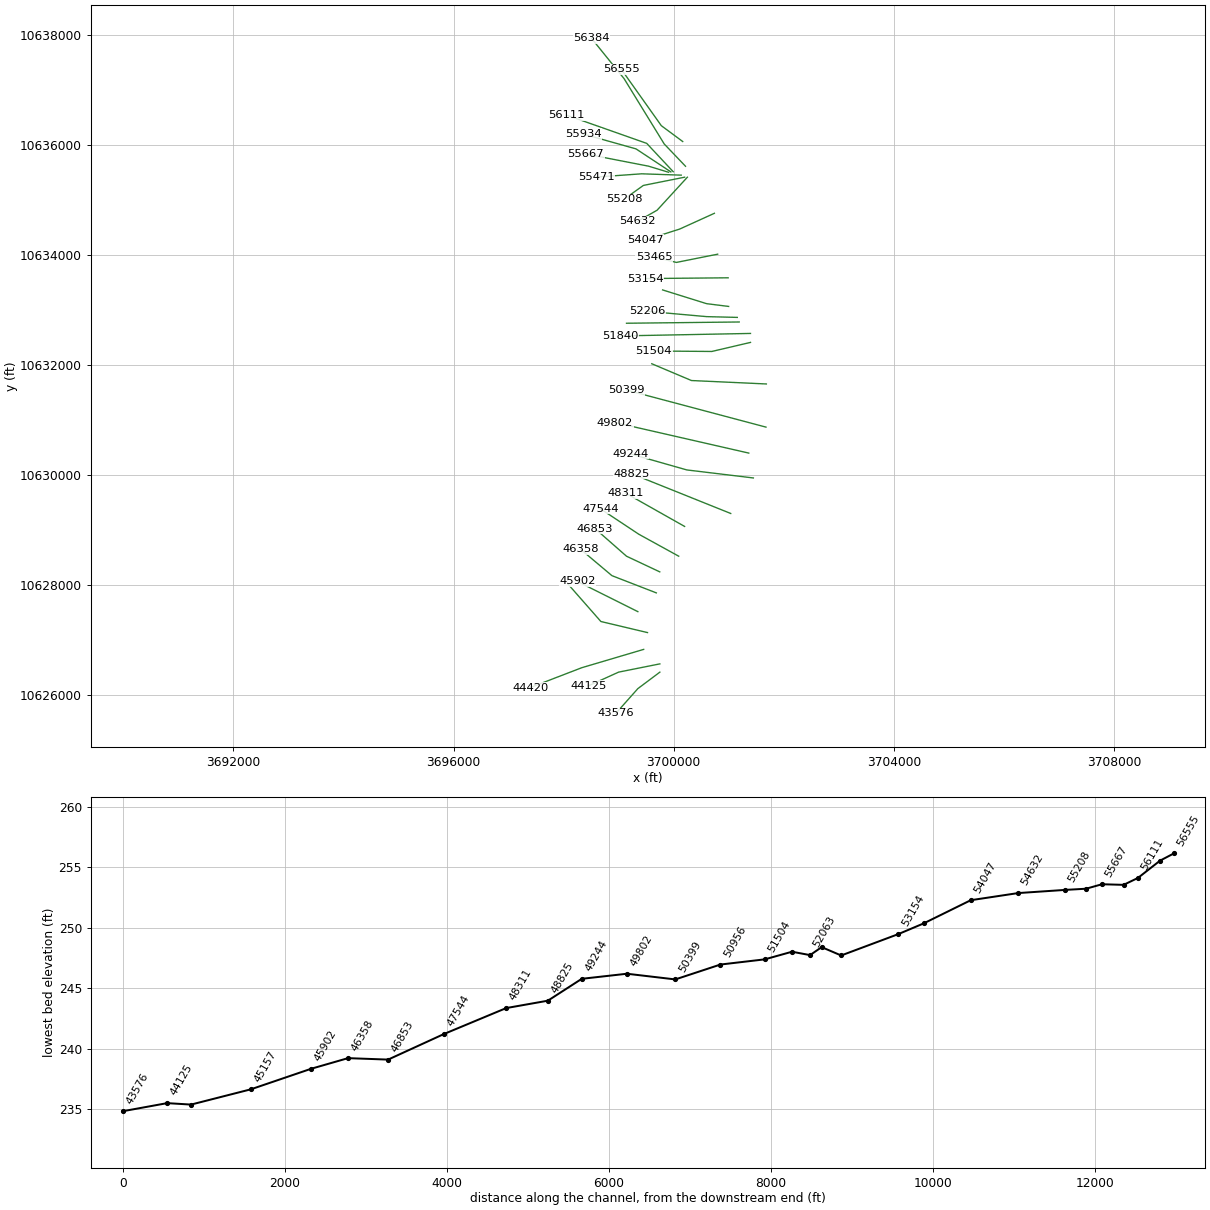
HEC-RAS study LAKE CREEK.prj: LAKE CREEK Base Level Engineering

--- LAKE CREEK.g01 (geometry) --- (continued)

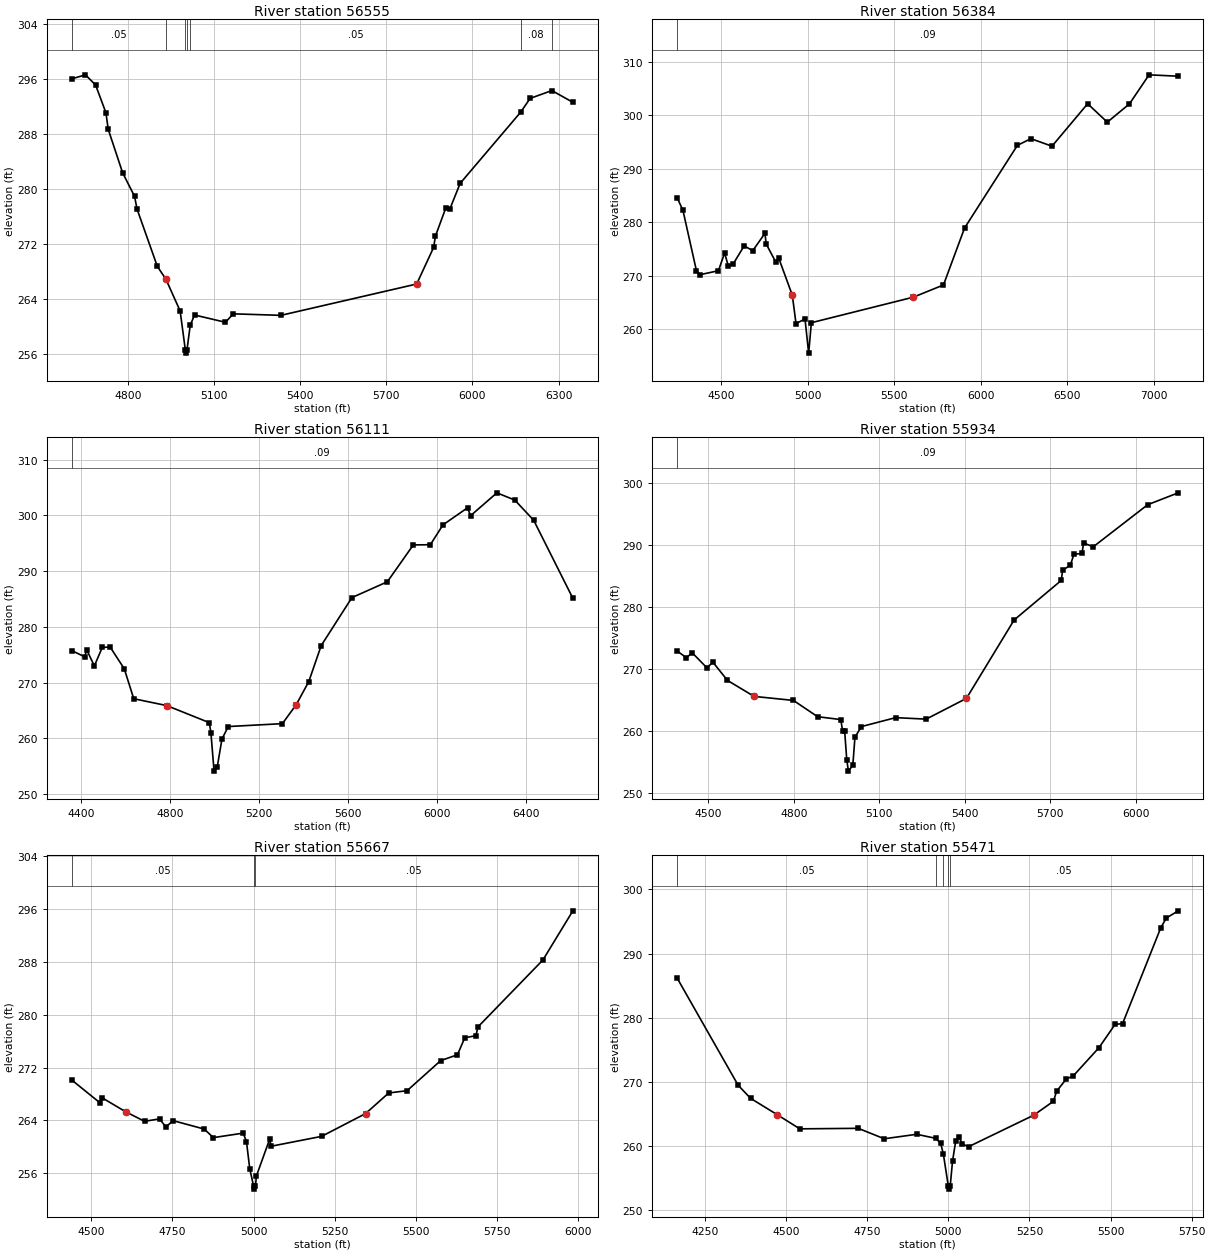
Type RM Length L Ch R = 1 ,56555   ,171,171,171
BEGIN DESCRIPTION:
Mapping XS b49f63cb
END DESCRIPTION:
XS GIS Cut Line= 3
      3700165.26     10636058.53      3699776.35     10636346.74
       3699047.2      10637374.5
#Sta/Elev= 30
  4605.1  296.07  4652.8  296.66  4688.2  295.18  4724.2  291.13  4732.1  288.73
  4782.2  282.41  4823.9  278.96  4832.3  277.14  4903.2  268.76  4932.2  266.96
  4932.5  266.95  4982.5  262.28  5000.4  256.65  5003.1  256.15  5006.4  256.65
  5017.5   260.2  5032.6   261.7  5140.2  260.64  5167.2  261.87  5333.3  261.65
  5805.7  266.21  5864.8  271.54  5870.9  273.17  5906.6  277.23  5921.4  277.14
    5957  280.86  6167.8  291.23  6200.6  293.23  6276.3  294.37  6349.3  292.66
#Mann= 7 ,-1 , 0
  4605.1     .05       0  4932.2     .12       0  5000.4     .07       0
  5006.4     .12       0  5017.5     .05       0  6167.8     .08       0
  6276.3     .05       0
Bank Sta=4932.5,5805.7
XS Rating Curve= 0 ,0
Exp/Cntr=0.3,0.1

Type RM Length L Ch R = 1 ,56384   ,273,273,273
BEGIN DESCRIPTION:
LAKE CREEK 69.0
END DESCRIPTION:
XS GIS Cut Line= 4
      3700215.89     10635608.82      3699828.65     10636014.61
      3699099.49     10637202.11      3698507.58     10637935.17
#Sta/Elev= 30
  4245.9  284.58  4279.5   282.2  4357.5  270.93  4378.6   270.2  4484.6  270.94
  4520.2  274.25  4541.2  271.88  4569.5  272.18  4633.4  275.59  4682.8  274.68
  4753.5  277.92  4760.4  275.95  4816.9   272.5  4832.3  273.37  4911.6  266.36
  4932.9  261.08    4985  261.92  5006.1  255.55  5021.7  261.23  5611.3     266
  5785.3  268.28  5907.2  278.91  6212.6  294.35  6290.9   295.6  6412.5  294.19
  6618.7  302.12  6732.3  298.68  6860.2  302.09  6973.8  307.52  7142.5  307.26
#Mann= 1 ,-1 , 0
  4245.9     .09       0
Bank Sta=4911.6,5611.3
XS Rating Curve= 0 ,0
Exp/Cntr=0.3,0.1

Type RM Length L Ch R = 1 ,56111   ,177,177,177
BEGIN DESCRIPTION:
LAKE CREEK 68.0
END DESCRIPTION:
XS GIS Cut Line= 3
      3699992.72      10635509.4      3699510.95     10636025.02
      3698053.71       10636539.
#Sta/Elev= 30
  4359.1  275.76  4418.3  274.61  4425.7  275.93  4460.8     273  4496.5  276.33
  4531.7  276.38  4595.2  272.48  4637.7  267.11  4786.2  265.88  4977.2  262.82
  4984.5  260.91  4998.4  254.12  5012.9  254.91  5033.9  259.87  5062.1  262.12
  5305.3  262.64  5367.2  266.03  5423.7  270.17  5479.7  276.65  5617.6  285.26
  5776.6  288.09  5893.3  294.71    5970  294.75  6026.6  298.31  6137.2  301.38
  6150.3  299.94  6268.8  304.06  6349.2  302.76  6434.1  299.14    6610  285.14
#Mann= 1 ,-1 , 0
  4359.1     .09       0
Bank Sta=4786.2,5367.2
XS Rating Curve= 0 ,0
Exp/Cntr=0.3,0.1

Type RM Length L Ch R = 1 ,55934   ,267,267,267
BEGIN DESCRIPTION:
Mapping XS 1e3952db
END DESCRIPTION:
XS GIS Cut Line= 3
      3699949.94     10635506.48       3699316.6     10635924.77
      3698355.48     10636195.41
#Sta/Elev= 30
    4391  272.88  4423.2  271.82  4444.2  272.58  4495.4  270.18  4516.5  271.08
  4567.6  268.15  4660.9  265.58  4798.9  264.93  4883.7  262.31    4965  261.85
    4971  260.09  4978.6  259.93    4986   255.3  4991.8  253.55  5007.1  254.49
  5014.6  259.01  5037.2  260.72  5157.3  262.16  5264.3  261.92  5405.6  265.26
  5572.8  277.88  5737.9  284.24    5743  285.87  5770.2  286.71  5782.3  288.44
  5811.1  288.61  5816.3  290.28  5850.3  289.66  6041.3  296.44  6148.5  298.35
#Mann= 1 ,-1 , 0
    4391     .09       0
Bank Sta=4660.9,5405.6
XS Rating Curve= 0 ,0
Exp/Cntr=0.3,0.1

Type RM Length L Ch R = 1 ,55667   ,196,196,196
BEGIN DESCRIPTION:
Mapping XS 412f916b
END DESCRIPTION:
XS GIS Cut Line= 3
      3699908.29     10635499.52      3699543.71     10635610.63
      3698403.03     10635832.53
#Sta/Elev= 30
  4440.1  270.13  4527.9  266.64  4533.1  267.45    4606  265.32  4664.4  263.87
  4710.5  264.24  4730.1  263.01  4752.3  263.97    4848   262.7  4876.3   261.4
    4968  262.08  4978.2  260.81  4988.4  256.66    5000   254.1  5002.7   253.6
    5006   254.1  5008.8  255.59  5049.5  261.14  5054.6   260.1  5209.6  261.59
    5345  265.04  5416.2  268.16  5472.9  268.51  5576.2  273.06  5627.9  273.95
  5650.6  276.53  5684.6  276.83  5691.3  278.18  5891.2  288.31  5983.3  295.75
#Mann= 3 ,-1 , 0
  4440.1     .05       0    5000     .03       0    5006     .05       0
Bank Sta=4606,5345
XS Rating Curve= 0 ,0
Exp/Cntr=0.3,0.1

Type RM Length L Ch R = 1 ,55471   ,263,263,263
BEGIN DESCRIPTION:
LAKE CREEK 67.0
END DESCRIPTION:
XS GIS Cut Line= 3
      3700137.42     10635447.44      3699418.71     10635471.74
      3698595.75     10635412.71
#Sta/Elev= 30
  4164.6  286.17  4352.5  269.45  4390.7  267.41  4472.6  264.86  4542.6  262.64
  4722.7  262.72  4802.8  261.09  4902.9  261.79  4961.3  261.16  4976.7  260.37
    4985  258.69  5000.1  253.73  5002.9  253.23  5006.1  253.73  5013.2   257.6
  5023.2   260.8  5033.2  261.41  5043.2  260.25  5063.3  259.87  5263.8  264.78
    5324  266.94    5334  268.51  5364.1  270.45  5384.1  270.84  5464.3   275.3
  5514.4  278.97    5537  279.04  5654.8  294.01    5672  295.55  5708.8  296.67
#Mann= 5 ,-1 , 0
  4164.6     .05       0  4961.3     .12       0    4985     .05       0
  5000.1     .03       0  5006.1     .05       0
Bank Sta=4472.6,5263.8
XS Rating Curve= 0 ,0
Exp/Cntr=0.3,0.1

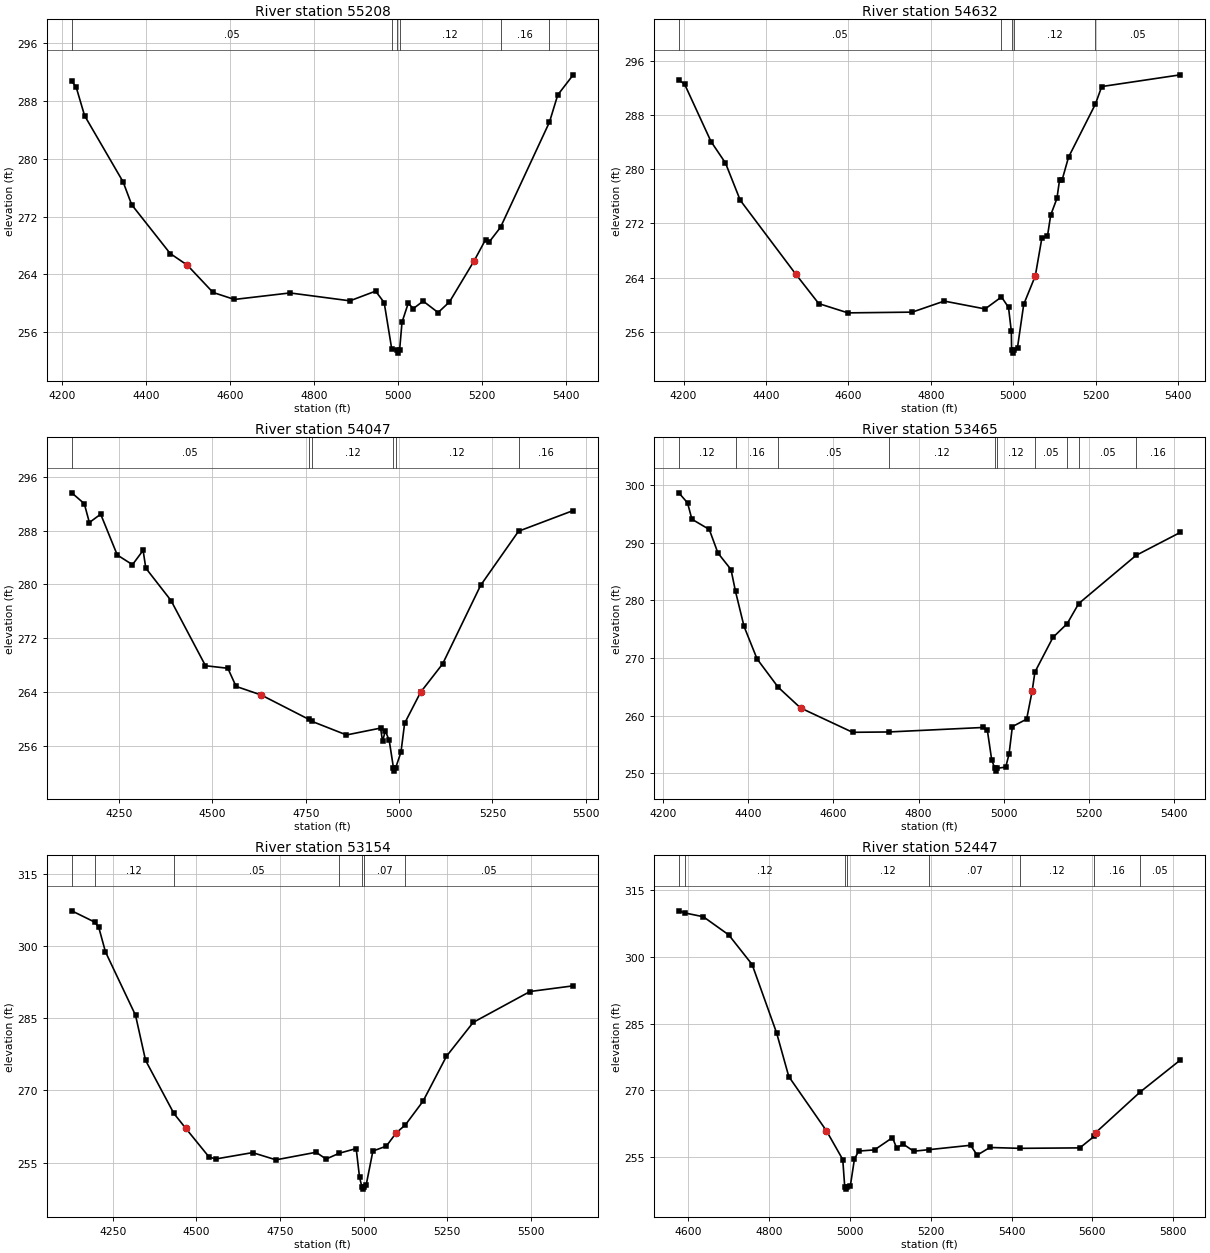
Type RM Length L Ch R = 1 ,55208   ,576,576,576
BEGIN DESCRIPTION:
LAKE CREEK 66.0
END DESCRIPTION:
XS GIS Cut Line= 3
      3700199.64     10635410.19      3699449.61     10635260.19
      3699099.61     10635010.19
#Sta/Elev= 30
    4223  290.68  4233.2  289.97  4253.6  285.96  4345.4   276.8  4365.8  273.65
  4457.6   266.9  4498.4  265.29  4559.6  261.52  4610.6  260.55  4743.1  261.45
  4885.9  260.36  4947.1   261.7  4967.5  260.12  4985.5  253.71  4998.4  253.63
  5001.2  253.13  5004.4  253.63    5010   257.4  5024.8  260.02    5037  259.29
  5060.4  260.32    5096  258.74  5123.1  260.21  5182.1  265.91  5209.1  268.82
  5217.7  268.49  5244.7  270.52  5361.4  285.07  5381.1  288.82    5418   291.6
#Mann= 6 ,-1 , 0
    4223     .05       0  4985.5     .12       0  4998.4     .07       0
  5004.4     .12       0  5244.7     .16       0  5361.4     .12       0
Bank Sta=4498.4,5182.1
XS Rating Curve= 0 ,0
Exp/Cntr=0.3,0.1

Type RM Length L Ch R = 1 ,54632   ,585,585,585
BEGIN DESCRIPTION:
LAKE CREEK 65.0
END DESCRIPTION:
XS GIS Cut Line= 3
      3700249.61     10635410.19      3699699.61     10634810.19
      3699349.57     10634610.17
#Sta/Elev= 30
  4188.6  293.16  4202.5  292.57  4266.6   284.1  4301.8  280.92  4337.5  275.44
  4471.9  264.56  4528.1  260.18    4599  258.81    4755  258.92  4832.7  260.55
  4931.9  259.39  4971.6  261.16  4988.7  259.62  4995.5  256.09  4996.2  253.37
  4998.9  252.87  5002.2  253.37  5010.5   253.7  5025.6  260.07  5053.7  264.27
  5069.5  269.81  5083.2  270.13  5091.1  273.25  5106.2   275.7  5112.7  278.49
  5118.4  278.35  5134.3  281.78  5199.5  289.61  5214.9  292.21  5405.7  293.94
#Mann= 5 ,-1 , 0
  4188.6     .05       0  4971.6     .12       0  4996.2     .07       0
  5002.2     .12       0  5199.5     .05       0
Bank Sta=4471.9,5053.7
XS Rating Curve= 0 ,0
Exp/Cntr=0.3,0.1

Type RM Length L Ch R = 1 ,54047   ,582,582,582
BEGIN DESCRIPTION:
LAKE CREEK 64.0
END DESCRIPTION:
XS GIS Cut Line= 3
      3700740.17     10634753.57        3700110.     10634467.13
      3699490.24     10634269.22
#Sta/Elev= 30
  4123.5   293.6  4157.1  291.99  4170.7  289.19    4201  290.43  4245.4  284.37
  4286.1  282.93  4314.6  285.06  4321.8  282.42  4389.3  277.61  4481.6  267.93
  4541.5  267.55  4563.5  264.86    4631  263.58  4757.9  259.98  4766.2  259.68
  4859.2  257.65  4950.5  258.67  4955.7   256.7  4963.1  258.26  4973.6  256.84
  4984.9  252.78  4987.6  252.28  4990.9  252.78  5005.1  255.11  5014.8  259.38
  5057.6  263.99  5116.6   268.2  5218.4  279.87  5319.9   287.9  5466.3  290.97
#Mann= 6 ,-1 , 0
  4123.5     .05       0  4757.9     .16       0  4766.2     .12       0
  4984.9     .07       0  4990.9     .12       0  5319.9     .16       0
Bank Sta=4631,5057.6
XS Rating Curve= 0 ,0
Exp/Cntr=0.3,0.1

Type RM Length L Ch R = 1 ,53465   ,311,311,311
BEGIN DESCRIPTION:
LAKE CREEK 63.0
END DESCRIPTION:
XS GIS Cut Line= 3
      3700799.62     10634010.19      3700049.61     10633860.19
      3699649.58     10633960.19
#Sta/Elev= 30
  4237.3  298.68  4257.7  296.93  4267.9   294.1  4308.7  292.32  4329.1  288.22
  4359.7  285.36  4370.3  281.56  4390.3  275.49  4420.9  269.84  4470.4  264.93
  4522.9  261.33  4645.2   257.1  4730.4  257.16  4951.2  257.94  4961.4  257.49
  4971.6  252.36  4978.8  250.86  4981.5  250.36  4984.8  250.86  5004.7  251.06
  5012.5  253.38  5020.2  258.09  5053.7  259.39  5066.6  264.23  5073.1  267.56
  5115.5  273.58  5148.9  275.97    5176  279.46  5310.6  287.82  5414.5  291.81
#Mann= 10 ,-1 , 0
  4237.3     .12       0  4370.3     .16       0  4470.4     .05       0
  4730.4     .12       0  4978.8     .07       0  4984.8     .12       0
  5073.1     .05       0  5148.9     .16       0    5176     .05       0
  5310.6     .16       0
Bank Sta=4522.9,5066.6
XS Rating Curve= 0 ,0
Exp/Cntr=0.3,0.1

Type RM Length L Ch R = 1 ,53154   ,707,707,707
BEGIN DESCRIPTION:
LAKE CREEK 62.0
END DESCRIPTION:
XS GIS Cut Line= 2
      3700990.36     10633580.77      3699490.43     10633566.88
#Sta/Elev= 30
  4127.2  307.33  4195.5     305    4208   303.9    4228  298.81    4318  285.62
    4348  276.25  4432.7  265.21    4468  262.14    4538  256.15    4558  255.75
    4668  257.07    4738  255.57    4858  257.14    4888  255.73  4927.2  256.94
    4978  257.91    4988  251.96    4995  249.98  4997.7  249.48    5001  249.98
    5008  250.38    5028   257.4    5068  258.41    5098  261.19    5125  262.82
    5178  267.76    5248  277.09    5328  284.14    5498  290.56  5627.2  291.74
#Mann= 7 ,-1 , 0
  4127.2     .05       0  4195.5     .12       0  4432.7     .05       0
  4927.2     .07       0    4995     .07       0    5001     .07       0
    5125     .05       0
Bank Sta=4468,5098
XS Rating Curve= 0 ,0
Exp/Cntr=0.3,0.1

Type RM Length L Ch R = 1 ,52447   ,241,241,241
BEGIN DESCRIPTION:
LAKE CREEK 61.0
END DESCRIPTION:
XS GIS Cut Line= 3
      3700999.62     10633060.19      3700599.61     10633110.19
      3699799.58      10633360.2
#Sta/Elev= 30
  4576.5   310.4  4590.9  309.93    4637  309.07    4700  304.98  4757.9   298.3
  4818.4  282.92  4848.6  273.07  4941.8  260.85  4982.2  254.38  4987.1  248.21
  4989.8  247.71  4993.1  248.21  5001.1  248.52  5011.1  254.47  5021.5  256.28
  5060.8  256.55  5105.3  259.31  5115.8  256.91    5131   257.9  5157.7  256.25
  5196.7  256.61  5298.6  257.59  5314.9  255.37  5346.3  257.09  5420.4   256.9
  5568.9     257  5604.4  259.59  5608.2  260.43  5718.5   269.6  5817.8  276.79
#Mann= 8 ,-1 , 0
  4576.5     .05       0  4590.9     .12       0  4987.1     .07       0
  4993.1     .12       0  5196.7     .07       0  5420.4     .12       0
  5604.4     .16       0  5718.5     .05       0
Bank Sta=4941.8,5608.2
XS Rating Curve= 0 ,0
Exp/Cntr=0.3,0.1

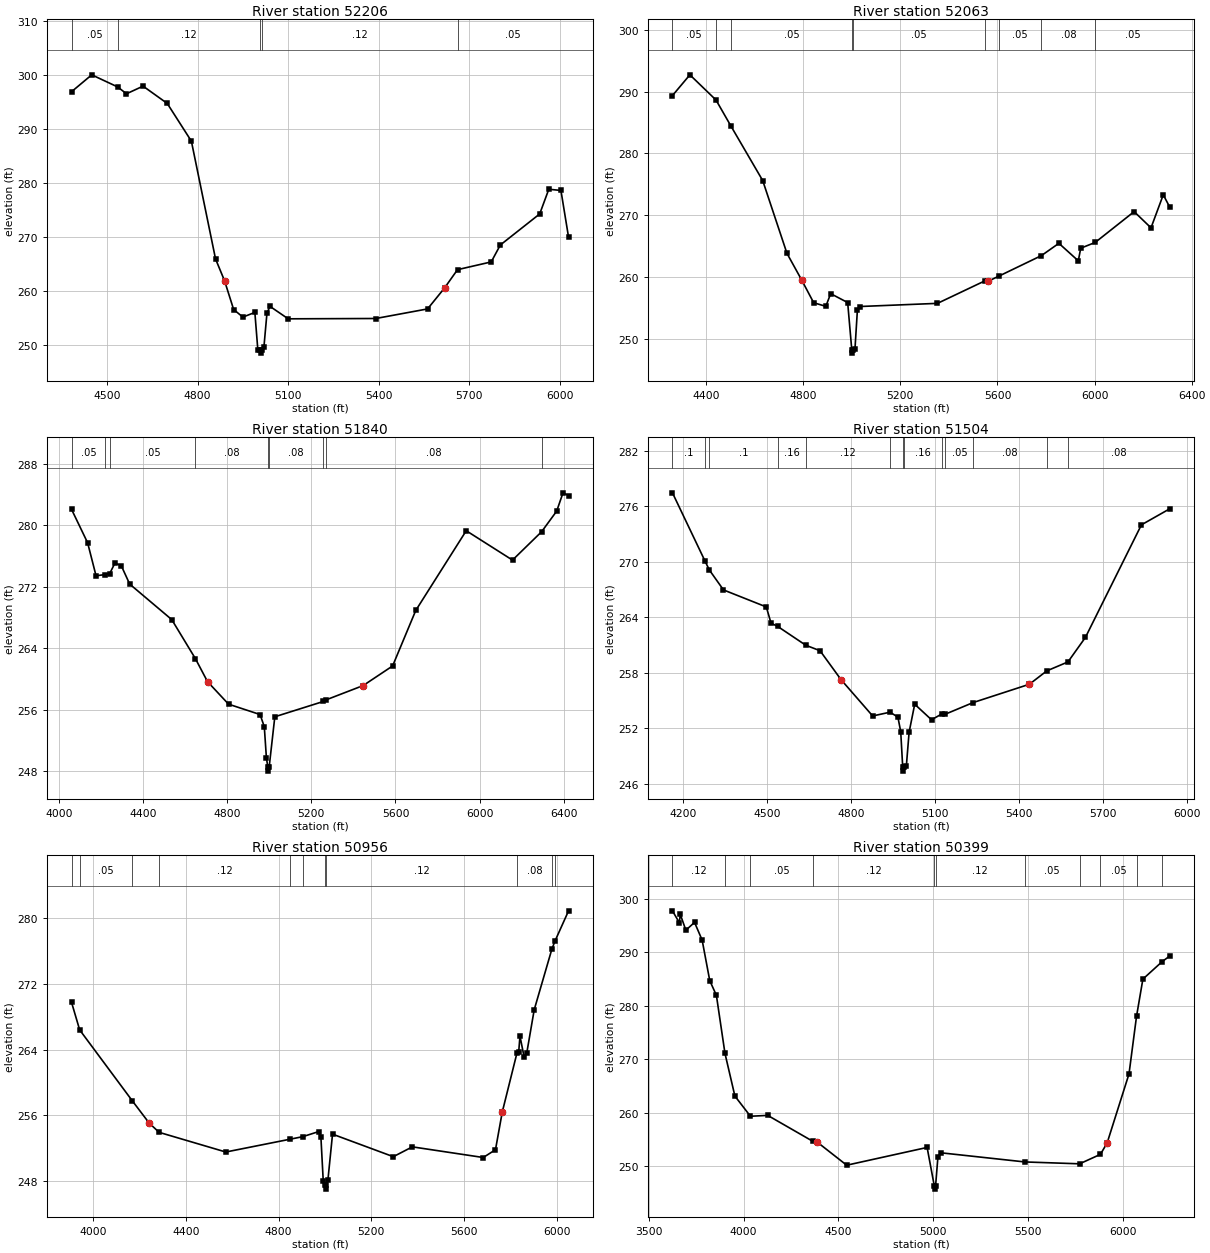
Type RM Length L Ch R = 1 ,52206   ,143,143,143
BEGIN DESCRIPTION:
Mapping XS 78122ac2
END DESCRIPTION:
XS GIS Cut Line= 3
      3701156.58     10632860.64      3700601.06     10632874.53
       3699514.4     10632971.73
#Sta/Elev= 30
  4382.3  296.94  4449.3  300.08  4535.2  297.83  4564.4  296.56  4619.3  297.98
  4699.4  294.77  4779.4  287.76  4859.4   265.9  4889.4  261.82  4919.4   256.5
    4950  255.09  4989.7  255.96  4999.7  248.92  5006.7   248.9  5009.5   248.4
  5012.7   248.9  5019.8  249.59  5029.8  255.84  5039.9  257.08  5100.1  254.77
  5390.3  254.83  5561.9  256.61    5618  260.49  5661.1   263.9  5772.8  265.34
  5802.9  268.48  5933.4  274.25  5963.5  278.83  6003.7  278.61    6029  269.92
#Mann= 5 ,-1 , 0
  4382.3     .05       0  4535.2     .12       0  5006.7     .07       0
  5012.7     .12       0  5661.1     .05       0
Bank Sta=4889.4,5618
XS Rating Curve= 0 ,0
Exp/Cntr=0.3,0.1

Type RM Length L Ch R = 1 ,52063   ,223,223,223
BEGIN DESCRIPTION:
LAKE CREEK 60.0
END DESCRIPTION:
XS GIS Cut Line= 2
      3701191.38      10632777.3      3699143.91     10632754.38
#Sta/Elev= 30
  4261.1  289.35  4332.9   292.7  4440.5  288.63  4502.2  284.41  4632.9  275.62
  4732.9  263.85  4792.9  259.59  4842.9  255.88  4892.9   255.3  4912.9  257.35
  4982.9  255.91  4999.9  248.24  5002.7  247.74  5005.9  248.24  5012.9  248.36
  5022.9  254.65  5032.9  255.27  5352.9  255.78  5548.9  259.43    5563  259.38
  5605.8  260.18  5781.3   263.5    5853  265.48    5933  262.65    5943  264.69
  6002.5  265.62    6163   270.6  6232.5  267.98    6283  273.32  6308.7   271.4
#Mann= 9 ,-1 , 0
  4261.1     .05       0  4440.5     .12       0  4502.2     .05       0
  4999.9     .04       0  5005.9     .05       0  5548.9     .08       0
  5605.8     .05       0  5781.3     .08       0  6002.5     .05       0
Bank Sta=4792.9,5563
XS Rating Curve= 0 ,0
Exp/Cntr=0.3,0.1

Type RM Length L Ch R = 1 ,51840   ,336,336,336
BEGIN DESCRIPTION:
Mapping XS 9e92c594
END DESCRIPTION:
XS GIS Cut Line= 2
      3701396.16     10632568.97      3699033.09     10632523.86
#Sta/Elev= 30
  4059.7  282.08  4136.3  277.72  4176.3  273.43  4220.2  273.59  4241.3  273.72
  4266.3  275.09  4296.3  274.74  4336.3  272.35  4536.3  267.73  4648.8  262.65
  4706.4  259.66  4806.4  256.73  4956.4  255.38  4976.4  253.79  4986.4  249.74
  4993.4  248.52  4996.2  248.02  4999.4  248.52  5026.4  255.09  5257.1  257.08
  5269.2  257.28  5446.5  259.15  5586.5   261.7  5696.6  268.92  5936.6  279.29
  6156.6  275.47    6295  279.16  6366.7  281.84  6396.7  284.22  6423.2  283.87
#Mann= 9 ,-1 , 0
  4059.7     .05       0  4220.2      .1       0  4241.3     .05       0
  4648.8     .08       0  4993.4     .07       0  4999.4     .08       0
  5257.1     .05       0  5269.2     .08       0    6295     .05       0
Bank Sta=4706.4,5446.5
XS Rating Curve= 0 ,0
Exp/Cntr=0.3,0.1

Type RM Length L Ch R = 1 ,51504   ,548,548,548
BEGIN DESCRIPTION:
LAKE CREEK 59.0
END DESCRIPTION:
XS GIS Cut Line= 3
      3701396.22     10632405.78      3700693.22     10632241.24
      3699639.26     10632249.53
#Sta/Elev= 30
  4161.7  277.46  4278.6  270.05  4293.6  269.12    4344  266.97  4497.1  265.13
  4513.9  263.38  4537.5  263.03  4638.2  260.99    4689   260.4  4764.2  257.27
  4877.1  253.35  4939.3  253.76  4967.3  253.22  4977.3  251.66  4984.3  247.89
  4987.1  247.39  4990.3  247.89  4997.3   247.9  5007.3   251.6  5027.3  254.62
  5087.3  252.94  5123.7  253.56  5137.2  253.55  5236.2   254.8  5437.3  256.78
  5499.1  258.22  5574.9  259.19  5637.3  261.84  5837.3     274  5937.7  275.72
#Mann= 13 ,-1 , 0
  4161.7      .1       0  4278.6     .16       0  4293.6      .1       0
  4537.5     .16       0  4638.2     .12       0  4939.3     .16       0
  4984.3     .07       0  4990.3     .16       0  5123.7     .12       0
  5137.2     .05       0  5236.2     .08       0  5499.1     .05       0
  5574.9     .08       0
Bank Sta=4764.2,5437.3
XS Rating Curve= 0 ,0
Exp/Cntr=0.3,0.1

Type RM Length L Ch R = 1 ,50956   ,557,557,557
BEGIN DESCRIPTION:
LAKE CREEK 58.0
END DESCRIPTION:
XS GIS Cut Line= 3
       3701684.8     10631650.21      3700323.73     10631712.71
      3699603.08      10632017.6
#Sta/Elev= 30
  3906.3  269.77  3941.4   266.4  4169.1  257.72  4241.8  255.01  4284.4  253.89
  4572.2  251.49    4849  253.05  4903.7  253.36  4972.6  253.98  4982.6  253.27
  4992.6  247.95  4999.6  247.46  5002.4  246.96  5005.6  247.46  5012.7  248.06
  5032.7  253.67    5295  250.92  5377.1  252.12  5683.1  250.82  5735.9  251.77
  5765.1  256.36  5828.2  263.53  5836.1  263.71  5841.6  265.63  5859.6  263.08
  5870.7  263.54    5903  268.85    5979  276.23  5992.4  277.22  6051.3  280.93
#Mann= 11 ,-1 , 0
  3906.3     .12       0  3941.4     .05       0  4169.1     .16       0
  4284.4     .12       0    4849     .16       0  4903.7     .12       0
  4999.6     .07       0  5005.6     .12       0  5828.2     .08       0
    5979      .1       0  5992.4     .08       0
Bank Sta=4241.8,5765.1
XS Rating Curve= 0 ,0
Exp/Cntr=0.3,0.1

Type RM Length L Ch R = 1 ,50399   ,597,597,597
BEGIN DESCRIPTION:
LAKE CREEK 57.0
END DESCRIPTION:
XS GIS Cut Line= 2
      3701677.93     10630865.48      3699143.88     10631538.91
#Sta/Elev= 30
    3625  297.74  3661.1  295.53  3666.3  297.08  3695.7  294.12  3741.5  295.58
  3781.6  292.27  3821.8  284.69  3856.8  281.95    3902   271.1  3954.4  263.12
  4036.4  259.35  4127.6  259.51  4364.3  254.69  4388.9  254.51  4544.2   250.2
  4968.4  253.52  5006.8  246.23  5009.5  245.73  5012.8  246.23  5025.4  251.75
  5040.8  252.52  5484.3  250.81  5772.8  250.46  5882.7  252.23  5918.1  254.37
  6033.4  267.27    6073  278.01  6106.6  284.98  6208.3  288.25    6247  289.26
#Mann= 11 ,-1 , 0
    3625     .12       0    3902     .16       0  4036.4     .05       0
  4364.3     .12       0  5006.8     .07       0  5012.8     .12       0
  5484.3     .05       0  5772.8     .07       0  5882.7     .05       0
    6073      .1       0  6208.3     .08       0
Bank Sta=4388.9,5918.1
XS Rating Curve= 0 ,0
Exp/Cntr=0.3,0.1

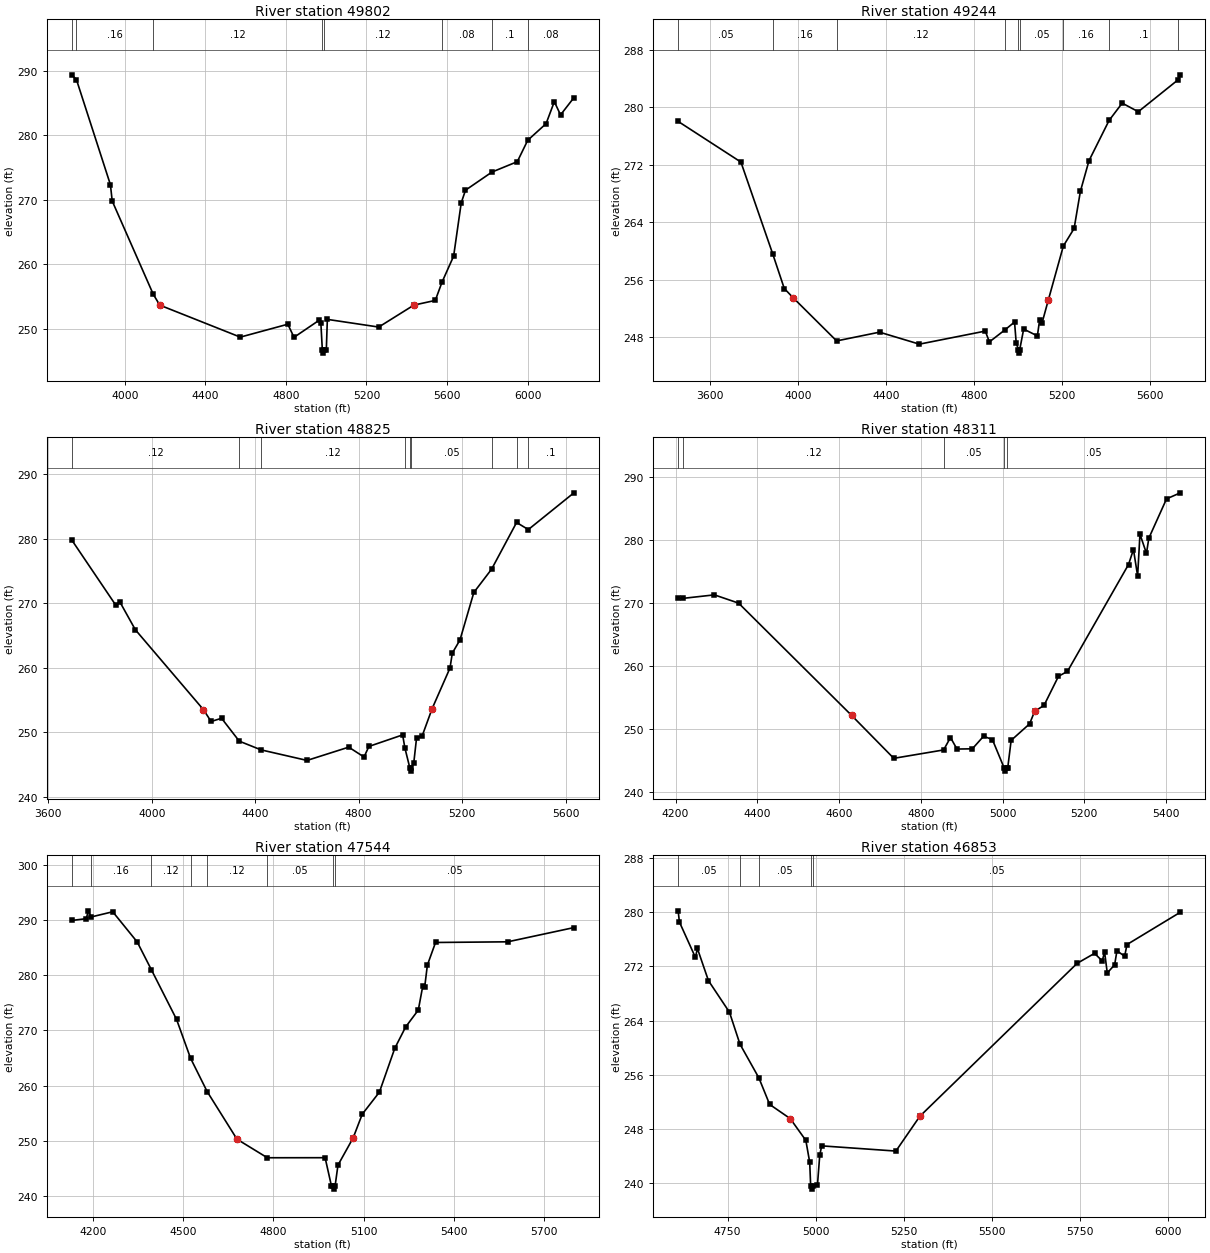
Type RM Length L Ch R = 1 ,49802   ,558,558,558
BEGIN DESCRIPTION:
LAKE CREEK 56.0
END DESCRIPTION:
XS GIS Cut Line= 2
      3701365.39     10630393.27      3698934.87     10630948.81
#Sta/Elev= 30
  3737.1  289.33  3760.5  288.57    3929   272.3  3937.9  269.77  4141.4  255.34
  4173.9  253.64  4573.9  248.68  4809.8  250.68  4840.6  248.65  4963.7  251.26
    4974   250.8  4981.2   246.7    4984   246.2  4987.2   246.7    5001  246.72
  5006.1  251.43  5261.2  250.24  5435.6  253.64  5542.1  254.37  5575.4   257.2
  5633.1  261.23  5670.9   269.5    5692  271.45  5823.3  274.26  5949.2  275.87
  6001.1  279.19  6092.1  281.76  6133.1  285.17  6163.9  283.12  6230.3  285.79
#Mann= 8 ,-1 , 0
  3737.1     .12       0  3760.5     .16       0  4141.4     .12       0
  4981.2     .07       0  4987.2     .12       0  5575.4     .08       0
  5823.3      .1       0  6001.1     .08       0
Bank Sta=4173.9,5435.6
XS Rating Curve= 0 ,0
Exp/Cntr=0.3,0.1

Type RM Length L Ch R = 1 ,49244   ,419,419,419
BEGIN DESCRIPTION:
LAKE CREEK 55.0
END DESCRIPTION:
XS GIS Cut Line= 3
      3701448.59     10629941.08      3700240.21     10630086.92
       3699214.4     10630378.52
#Sta/Elev= 30
  3453.6  278.05  3738.9  272.39  3883.9  259.57  3936.1  254.78  3976.3   253.5
  4174.2  247.48  4369.2   248.7  4550.5  247.03  4850.3  248.85  4868.9  247.34
  4940.1  249.03  4983.3  250.11    4991  247.17    5001  246.28  5003.8  245.78
    5007  246.28  5024.8  249.13  5087.2  248.18  5097.6  250.45  5108.2  249.96
  5136.9  253.17  5205.3   260.7  5254.2  263.14  5282.8  268.32  5321.9  272.58
  5413.3  278.19    5473   280.6    5546   279.4  5728.4  283.88  5737.2  284.54
#Mann= 9 ,-1 , 0
  3453.6     .05       0  3883.9     .16       0  4174.2     .12       0
  4940.1     .05       0    5001     .03       0    5007     .05       0
  5205.3     .16       0  5413.3      .1       0  5728.4     .15       0
Bank Sta=3976.3,5136.9
XS Rating Curve= 0 ,0
Exp/Cntr=0.3,0.1

Type RM Length L Ch R = 1 ,48825   ,514,514,514
BEGIN DESCRIPTION:
LAKE CREEK 54.0
END DESCRIPTION:
XS GIS Cut Line= 2
      3701037.11     10629295.25      3699234.99     10630019.22
#Sta/Elev= 30
  3690.4  279.82  3860.1  269.74  3877.2  270.16  3936.3   265.9  4199.8   253.5
  4229.3  251.67  4269.7  252.17  4338.2  248.62  4422.2  247.27  4600.3  245.63
  4761.6  247.69  4820.8  246.16  4839.6   247.8  4970.1  249.59  4978.7  247.58
  4997.9  244.47  5000.6  243.97  5003.9  244.47  5013.2  245.27    5024  249.14
  5045.6  249.43  5084.2  253.67  5153.3  259.97  5162.2  262.28  5191.8  264.31
  5245.5  271.69  5314.2   275.3  5410.8  282.54  5456.2  281.44  5632.5  287.14
#Mann= 9 ,-1 , 0
  3690.4     .12       0  4338.2     .16       0  4422.2     .12       0
  4978.7     .05       0  4997.9     .03       0  5003.9     .05       0
  5314.2     .16       0  5410.8     .08       0  5456.2      .1       0
Bank Sta=4199.8,5084.2
XS Rating Curve= 0 ,0
Exp/Cntr=0.3,0.1

Type RM Length L Ch R = 1 ,48311   ,767,767,767
BEGIN DESCRIPTION:
LAKE CREEK 53.0
END DESCRIPTION:
XS GIS Cut Line= 2
      3700198.77     10629059.91      3699129.32     10629664.08
#Sta/Elev= 30
  4206.4  270.81  4218.9  270.76    4295  271.31  4354.2     270  4630.4  252.21
  4733.8  245.39  4855.7  246.72  4872.5  248.69  4888.4  246.86    4926   246.9
  4953.4  248.89    4975  248.37  5003.8  243.86  5006.6  243.36  5009.8  243.86
  5012.6  243.91  5020.9  248.24  5066.1  250.86  5078.3  252.85  5101.3  253.78
  5136.7   258.4  5158.7  259.18    5308  276.12  5320.1   278.5  5330.3  274.31
    5336  280.93  5351.9  277.89  5357.7   280.3    5401  286.53  5434.7  287.49
#Mann= 5 ,-1 , 0
  4206.4     .16       0  4218.9     .12       0  4855.7     .05       0
  5003.8     .03       0  5009.8     .05       0
Bank Sta=4630.4,5078.3
XS Rating Curve= 0 ,0
Exp/Cntr=0.3,0.1

Type RM Length L Ch R = 1 ,47544   ,691,691,691
BEGIN DESCRIPTION:
LAKE CREEK 52.0
END DESCRIPTION:
XS GIS Cut Line= 3
      3700091.94     10628518.46      3699367.15     10628917.74
      3698666.34     10629382.66
#Sta/Elev= 30
    4130  289.94  4178.3  290.27  4184.7  291.69  4194.7  290.58  4266.1  291.52
  4347.5  286.04  4394.2  281.04  4478.2     272  4524.6  264.97  4579.9  258.91
  4678.9  250.28  4779.8  246.91  4971.8  246.92  4992.8  241.81  4998.8  241.72
  5001.6  241.22  5004.8  241.72  5014.5  245.57    5065  250.52  5095.1   254.8
  5152.2  258.81  5203.3  266.76  5239.4  270.63  5281.5   273.7  5296.6  278.14
  5302.6  277.84  5311.6  281.84  5338.7  285.95  5578.6  286.07  5798.5  288.65
#Mann= 8 ,-1 , 0
    4130     .05       0  4194.7     .16       0  4394.2     .12       0
  4524.6     .16       0  4579.9     .12       0  4779.8     .05       0
  4998.8     .03       0  5004.8     .05       0
Bank Sta=4678.9,5065
XS Rating Curve= 0 ,0
Exp/Cntr=0.3,0.1

Type RM Length L Ch R = 1 ,46853   ,495,495,495
BEGIN DESCRIPTION:
LAKE CREEK 51.0
END DESCRIPTION:
XS GIS Cut Line= 3
      3699747.31     10628233.56      3699143.17     10628518.27
      3698574.16     10629017.89
#Sta/Elev= 30
  4609.9   280.2  4613.3  278.56  4658.9  273.31  4664.4  274.65  4695.8  269.89
  4755.5  265.22  4785.2  260.52    4839  255.52  4869.5  251.61    4928  249.51
  4972.2   246.3  4983.2  243.07  4985.9   239.6  4988.7   239.1  4991.9   239.6
  5005.3  239.78  5011.7  244.12  5017.2  245.49  5227.8  244.72  5295.8  249.86
  5742.3  272.45  5791.6  273.92  5813.4   272.8  5820.1  274.12  5827.7  271.02
  5848.6  272.23  5855.2   274.3    5877  273.49  5883.7  275.22    6035  279.99
#Mann= 5 ,-1 , 0
  4609.9     .05       0  4785.2     .12       0    4839     .05       0
  4985.9     .03       0  4991.9     .05       0
Bank Sta=4928,5295.8
XS Rating Curve= 0 ,0
Exp/Cntr=0.3,0.1

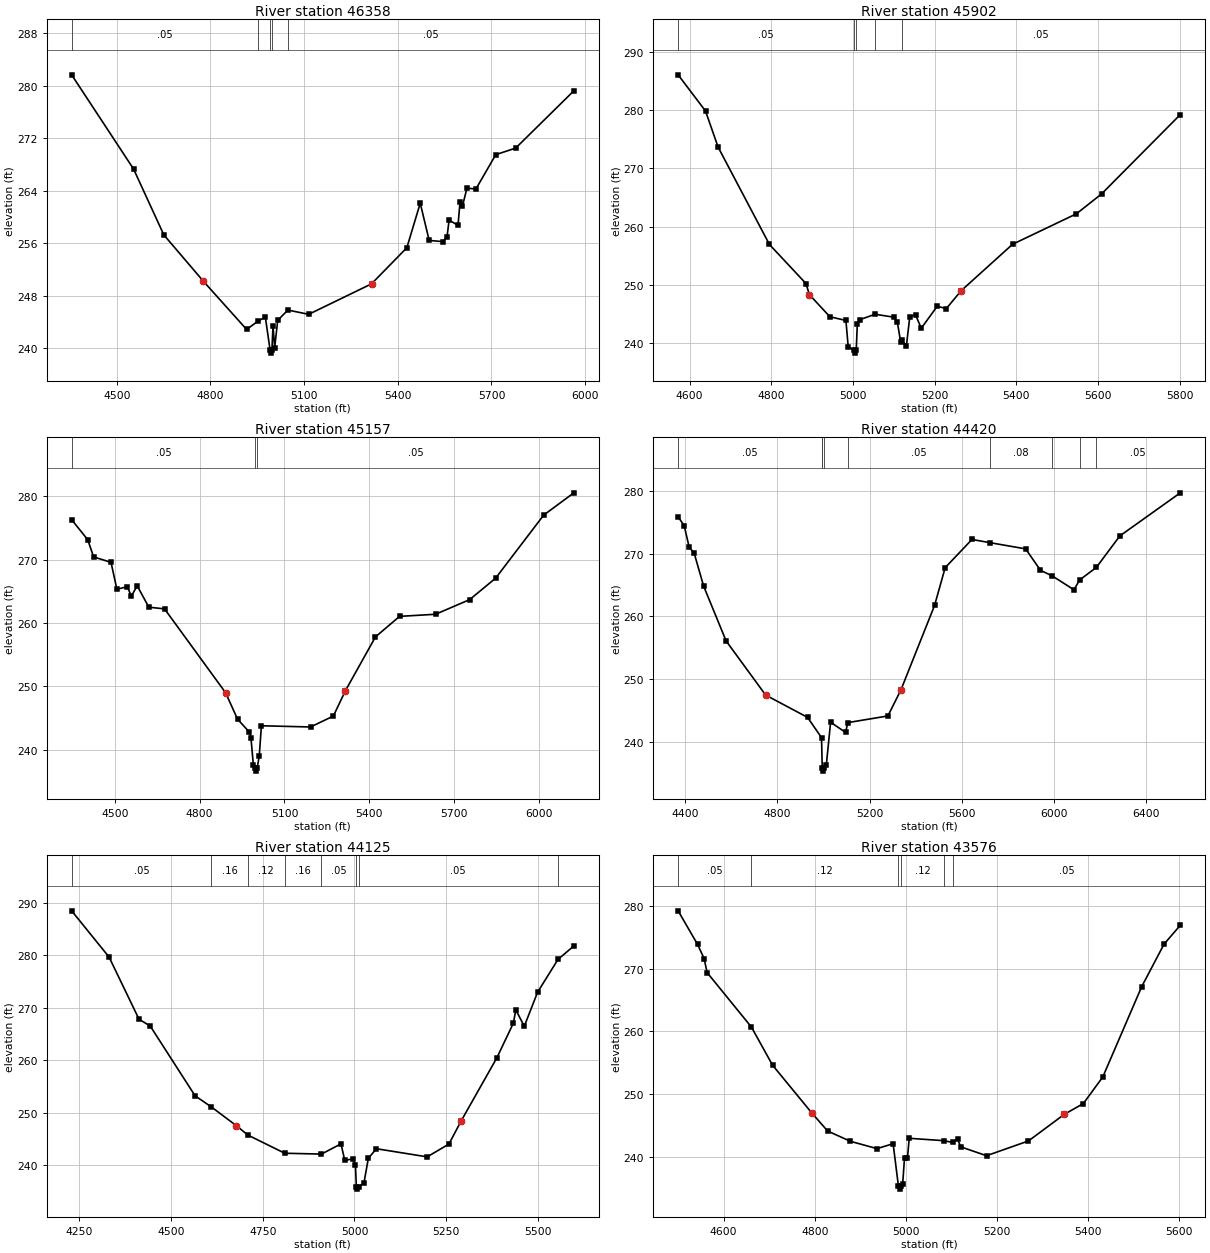
Type RM Length L Ch R = 1 ,46358   ,456,456,456
BEGIN DESCRIPTION:
LAKE CREEK 50.0
END DESCRIPTION:
XS GIS Cut Line= 3
      3699684.81     10627851.61      3698879.28      10628164.1
      3698309.87     10628643.24
#Sta/Elev= 30
  4355.6  281.68    4554   267.3  4650.8  257.26  4777.2   250.2    4916  242.83
  4953.1  244.13  4975.9  244.71    4991  239.72  4993.8  239.22    4997  239.72
  5000.4   243.4  5005.8  240.07  5015.5  244.23  5048.2  245.79  5114.7  245.14
  5315.9  249.79    5429   255.3  5471.9   262.1  5500.5  256.41  5543.4  256.24
  5557.7  256.95  5564.3  259.52  5592.9  258.71  5599.4  262.32  5607.2  261.66
  5621.5   264.4  5650.1  264.25  5713.8   269.5  5777.5   270.5  5963.8  279.24
#Mann= 5 ,-1 , 0
  4355.6     .05       0  4953.1     .16       0    4991     .07       0
    4997     .16       0  5048.2     .05       0
Bank Sta=4777.2,5315.9
XS Rating Curve= 0 ,0
Exp/Cntr=0.3,0.1

Type RM Length L Ch R = 1 ,45902   ,745,745,745
BEGIN DESCRIPTION:
LAKE CREEK 49.0
END DESCRIPTION:
XS GIS Cut Line= 3
      3699349.61     10627510.19      3698949.61     10627710.19
      3698249.64     10628060.17
#Sta/Elev= 30
  4571.7  286.03  4638.8  279.83  4669.5  273.66  4795.3  256.96  4884.7  250.27
  4893.1  248.37  4943.4  244.57  4982.6  243.94  4988.2  239.45  5001.9  238.84
  5004.7  238.34  5007.9  238.84  5010.5  243.28  5016.1  244.06  5054.1     245
    5100   244.5  5108.4  243.72  5116.7  240.25  5119.5  240.61  5130.7  239.57
  5139.1  244.61  5153.1  244.92  5167.1   242.6  5206.2  246.37  5228.5  245.97
  5264.9  249.04  5390.7  256.99  5547.2  262.22  5608.7  265.62  5801.5  279.22
#Mann= 5 ,-1 , 0
  4571.7     .05       0  5001.9     .03       0  5007.9     .05       0
  5054.1     .16       0  5119.5     .05       0
Bank Sta=4893.1,5264.9
XS Rating Curve= 0 ,0
Exp/Cntr=0.3,0.1

Type RM Length L Ch R = 1 ,45157   ,737,737,737
BEGIN DESCRIPTION:
LAKE CREEK 48.0
END DESCRIPTION:
XS GIS Cut Line= 3
       3699525.1     10627129.38      3698677.89     10627330.77
      3698080.65     10628011.35
#Sta/Elev= 30
  4347.2  276.33  4404.2  273.16  4424.8  270.46  4486.5  269.59  4507.1  265.35
  4544.1  265.75  4558.4  264.26    4579   265.9  4620.1  262.52  4675.8  262.25
  4891.8  249.01    4934  244.84  4976.2  242.78  4981.3  241.94  4990.1  237.53
  4997.4  237.14  5000.2  236.64  5003.4  237.14  5010.7     239  5018.4   243.8
  5192.2  243.61  5272.8  245.33  5315.5  249.33  5421.8  257.83  5507.2  261.07
  5634.3   261.4  5754.9  263.71  5846.9   267.1  6016.8  277.05  6123.5  280.57
#Mann= 3 ,-1 , 0
  4347.2     .05       0  4997.4     .03       0  5003.4     .05       0
Bank Sta=4891.8,5315.5
XS Rating Curve= 0 ,0
Exp/Cntr=0.3,0.1

Type RM Length L Ch R = 1 ,44420   ,295,295,295
BEGIN DESCRIPTION:
LAKE CREEK 47.0
END DESCRIPTION:
XS GIS Cut Line= 3
      3699455.66     10626823.82      3698330.67     10626490.49
      3697393.89     10626129.65
#Sta/Elev= 30
  4370.2  275.84  4396.4  274.44  4418.2  271.01    4440  270.03  4480.8  264.82
  4578.2   256.1  4749.7  247.48  4931.5  243.93    4992   240.7    4995  235.88
  4997.8  235.38    5001  235.88  5012.7  236.34  5031.3  243.16  5096.2  241.54
  5105.9   243.1  5279.6  244.16    5336  248.29  5482.1  261.75    5528  267.75
  5644.1  272.24  5720.7  271.74  5876.9  270.74  5941.2  267.33  5993.2  266.42
  6086.4  264.23  6110.9   265.8  6183.1  267.78  6285.5  272.81  6547.4  279.66
#Mann= 9 ,-1 , 0
  4370.2     .05       0    4992     .16       0    4995     .07       0
    5001     .16       0  5105.9     .05       0  5720.7     .08       0
  5993.2      .1       0  6110.9     .08       0  6183.1     .05       0
Bank Sta=4749.7,5336
XS Rating Curve= 0 ,0
Exp/Cntr=0.3,0.1

Type RM Length L Ch R = 1 ,44125   ,549,549,549
BEGIN DESCRIPTION:
LAKE CREEK 46.0
END DESCRIPTION:
XS GIS Cut Line= 3
      3699749.61     10626560.19      3698999.61     10626410.19
      3698449.62     10626160.19
#Sta/Elev= 30
  4229.1  288.47  4331.1  279.67  4412.7  267.84  4443.3  266.54  4565.6  253.26
  4609.7  251.16  4677.8  247.59  4709.8  245.78    4810  242.33  4910.1  242.17
  4963.4  244.12  4973.6  240.96  4996.7  241.28  5002.7  240.06  5005.2     236
    5008   235.5  5011.2     236  5025.8  236.62  5037.9  241.37  5059.9  243.19
  5198.3  241.64  5257.6  244.08  5290.5  248.43  5388.3   260.5  5433.3   267.1
  5439.9  269.63    5463   266.5  5499.2  272.97  5554.9  279.22  5598.1  281.79
#Mann= 8 ,-1 , 0
  4229.1     .05       0  4609.7     .16       0  4709.8     .12       0
    4810     .16       0  4910.1     .05       0  5005.2     .03       0
  5011.2     .05       0  5554.9     .08       0
Bank Sta=4677.8,5290.5
XS Rating Curve= 0 ,0
Exp/Cntr=0.3,0.1

Type RM Length L Ch R = 1 ,43576   ,529,529,529
BEGIN DESCRIPTION:
LAKE CREEK 45.0
END DESCRIPTION:
XS GIS Cut Line= 3
      3699749.57     10626410.16      3699349.61     10626110.19
      3698949.63     10625660.21
#Sta/Elev= 30
  4500.1  279.23  4542.8  273.87  4557.3  271.59  4563.6  269.39    4661  260.68
  4707.3  254.61  4792.8  247.04  4828.2   244.1  4878.2  242.46  4936.5  241.29
  4971.9  242.08  4983.5  235.33  4986.3  234.83  4989.5  235.33  4992.8  235.57
  4996.9  239.82  5003.4  239.82  5007.2  242.94  5083.2  242.56    5103  242.27
  5113.4  242.77  5120.5  241.57  5176.9  240.16  5268.9  242.52  5347.5  246.76
  5389.3  248.48    5432  252.72  5517.3  267.12  5566.6  273.94  5602.1  276.92
#Mann= 6 ,-1 , 0
  4500.1     .05       0    4661     .12       0  4983.5     .07       0
  4989.5     .12       0  5083.2     .16       0    5103     .05       0
Bank Sta=4792.8,5347.5
XS Rating Curve= 0 ,0
Exp/Cntr=0.3,0.1