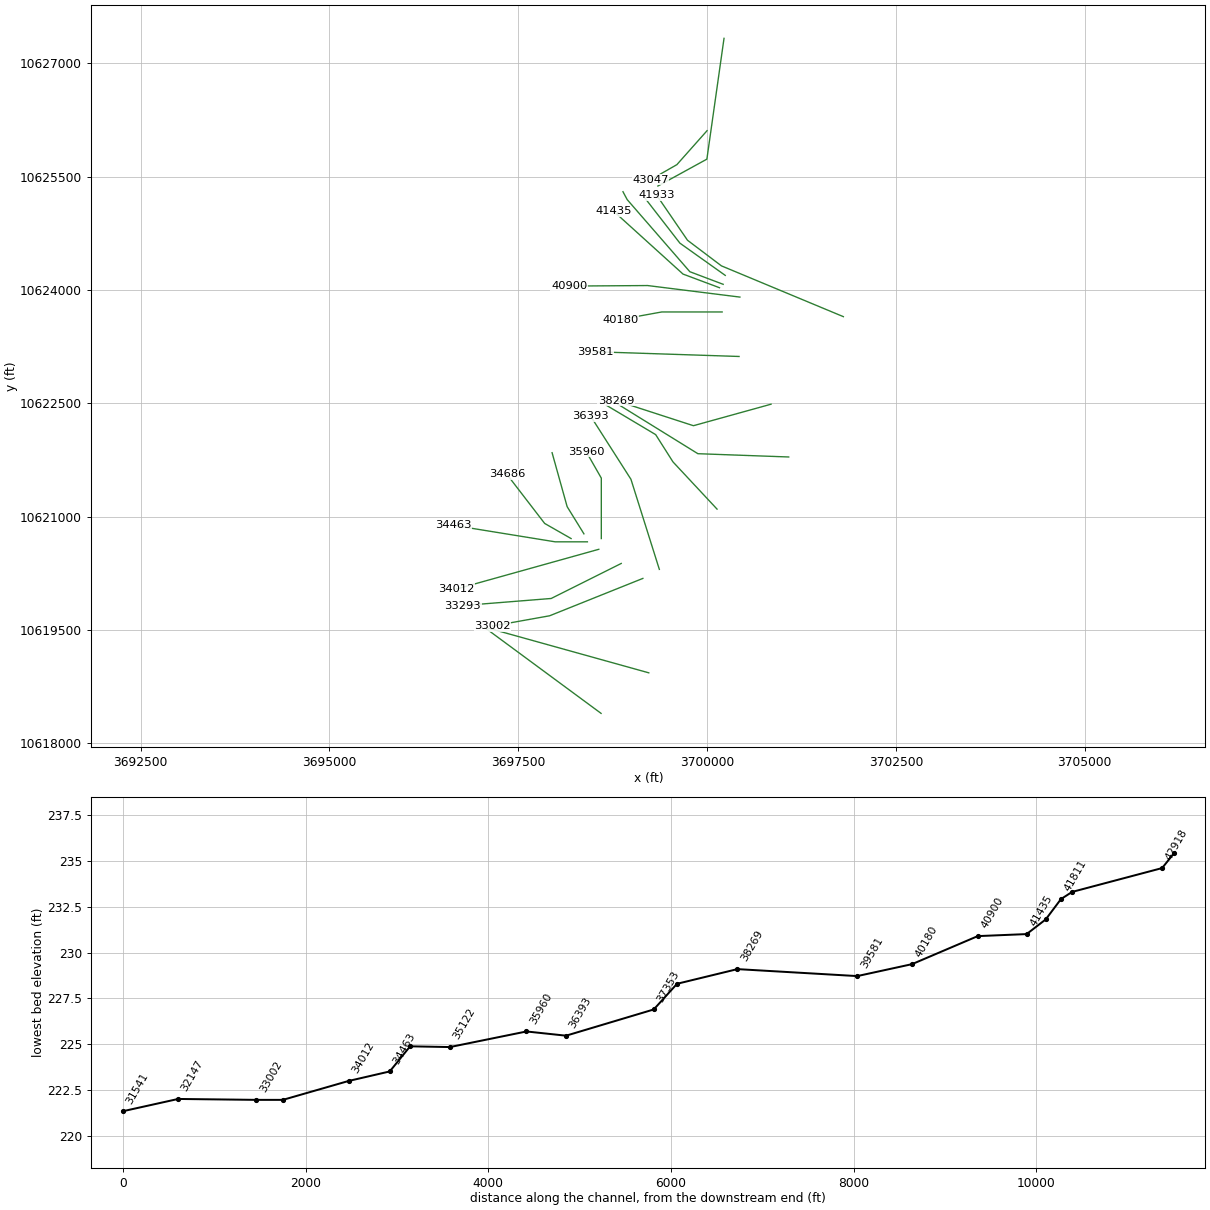
HEC-RAS study LAKE CREEK.prj: LAKE CREEK Base Level Engineering

--- LAKE CREEK.g01 (geometry) --- (continued)

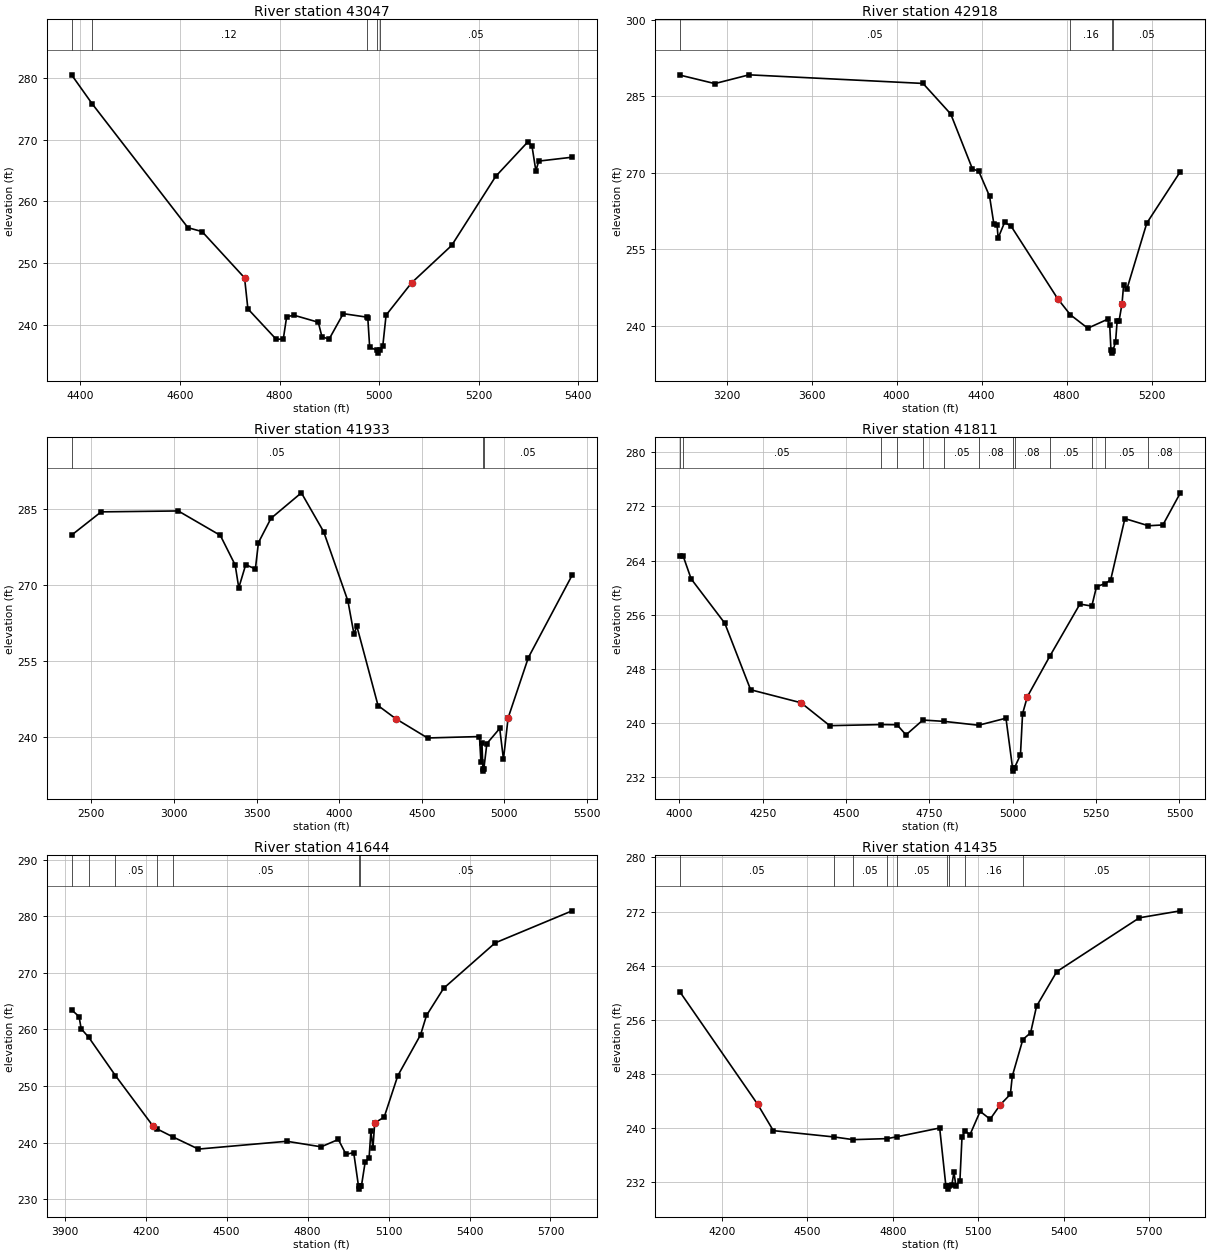
Type RM Length L Ch R = 1 ,43047   ,129,129,129
BEGIN DESCRIPTION:
LAKE CREEK 44.0
END DESCRIPTION:
XS GIS Cut Line= 3
      3699999.58     10626110.16      3699599.61     10625660.19
      3699249.57     10625460.17
#Sta/Elev= 30
  4382.3  280.54  4423.5  275.86    4616  255.75  4644.4  255.12  4729.7  247.62
  4736.4  242.59  4793.3  237.65  4807.5   237.7  4814.2  241.28  4828.4  241.57
  4877.7  240.42  4885.2  238.05  4899.5  237.68  4927.9  241.81  4974.9  241.25
  4977.2  241.11    4981  236.33    4995  235.91  4997.8  235.41    5001  235.91
  5007.4  236.64  5013.9  241.57    5065   246.8  5145.6  252.87  5234.1  264.08
  5298.9  269.69  5306.8  269.05  5314.7  264.98  5320.5  266.55  5387.5  267.18
#Mann= 5 ,-1 , 0
  4382.3     .05       0  4423.5     .12       0  4974.9     .16       0
    4995     .03       0    5001     .05       0
Bank Sta=4729.7,5065
XS Rating Curve= 0 ,0
Exp/Cntr=0.3,0.1

Type RM Length L Ch R = 1 ,42918   ,985,985,985
BEGIN DESCRIPTION:
LAKE CREEK 43.0
END DESCRIPTION:
XS GIS Cut Line= 3
      3700224.26       10627333.      3699997.34     10625733.54
      3699348.78     10625377.57
#Sta/Elev= 30
  2980.1  289.19  3144.5  287.52  3306.1  289.24  4124.3  287.55  4254.8  281.55
  4356.6   270.8  4386.9  270.29  4437.4  265.42  4457.6     260  4472.7  259.81
  4477.8   257.2  4508.1  260.27  4538.4  259.56  4758.4  245.27  4817.6  242.14
  4899.6   239.5  4992.5  241.25  5002.9  240.09  5008.6  235.29  5012.1  235.11
  5014.8  234.61  5018.1  235.11  5030.4  236.81  5037.9  240.98  5046.5  240.87
  5060.7  244.28  5068.3  248.02  5083.5  247.14  5177.3  260.13  5335.4  270.26
#Mann= 4 ,-1 , 0
  2980.1     .05       0  4817.6     .16       0  5012.1     .07       0
  5018.1     .05       0
Bank Sta=4758.4,5060.7
XS Rating Curve= 0 ,0
Exp/Cntr=0.3,0.1

Type RM Length L Ch R = 1 ,41933   ,122,122,122
BEGIN DESCRIPTION:
LAKE CREEK 42.0
END DESCRIPTION:
XS GIS Cut Line= 4
      3701804.16      10623648.1      3700190.28     10624320.43
       3699740.7     10624659.64      3699334.53     10625253.27
#Sta/Elev= 30
  2379.9  279.92    2559  284.52  3025.9   284.7  3280.5  279.88  3370.6  274.02
  3392.3  269.52  3434.4  274.09  3492.9  273.24  3511.3  278.44  3587.3  283.24
  3771.3  288.28  3906.7  280.57  4053.1  266.92  4089.8  260.39  4107.3  261.94
  4235.6  246.26    4342  243.68  4535.4  239.86  4849.8  240.14  4858.6  235.05
  4864.7  238.87  4870.5  233.81  4873.3  233.31  4876.5  233.81  4894.5  238.75
  4972.3  241.74    4995  235.65  5023.1  243.81  5145.7  255.73  5410.7     272
#Mann= 3 ,-1 , 0
  2379.9     .05       0  4870.5     .03       0  4876.5     .05       0
Bank Sta=4342,5023.1
XS Rating Curve= 0 ,0
Exp/Cntr=0.3,0.1

Type RM Length L Ch R = 1 ,41811   ,167,167,167
BEGIN DESCRIPTION:
Mapping XS f6992713
END DESCRIPTION:
XS GIS Cut Line= 3
      3700240.67     10624194.38      3699640.01     10624621.44
      3699171.44     10625225.38
#Sta/Elev= 30
  4001.3  264.72  4010.8  264.72  4035.2  261.29  4136.1  254.75  4213.6  244.93
  4364.8  243.01  4450.9  239.63  4605.5  239.79  4652.8  239.76  4679.7  238.27
  4730.3  240.46  4794.6  240.26  4897.3  239.69  4979.5  240.73  4999.2  233.42
  5001.9  232.92  5005.2  233.42    5023  235.34  5029.3  241.39  5043.8  243.92
  5110.8  249.86  5201.3  257.57    5237  257.28  5251.1  260.14  5276.6  260.59
  5293.6  261.14  5336.2  270.19  5406.9  269.13  5450.2  269.25  5502.7  273.99
#Mann= 13 ,-1 , 0
  4001.3     .08       0  4010.8     .05       0  4605.5     .08       0
  4652.8     .05       0  4730.3     .08       0  4794.6     .05       0
  4897.3     .08       0  4999.2     .07       0  5005.2     .08       0
  5110.8     .05       0    5237     .08       0  5276.6     .05       0
  5406.9     .08       0
Bank Sta=4364.8,5043.8
XS Rating Curve= 0 ,0
Exp/Cntr=0.3,0.1

Type RM Length L Ch R = 1 ,41644   ,209,209,209
BEGIN DESCRIPTION:
LAKE CREEK 41.0
END DESCRIPTION:
XS GIS Cut Line= 4
      3700212.92     10624076.31      3699771.95     10624242.97
      3698942.09     10625197.83      3698886.51     10625302.04
#Sta/Elev= 30
  3925.5  263.47  3953.2  262.28  3961.1  260.13    3989  258.62    4088  251.86
  4228.3  242.88  4240.6  242.48  4302.7  240.99  4395.5  238.88    4723  240.26
  4850.3  239.28  4913.9  240.58  4942.4  237.95  4970.9  238.26  4988.7  232.31
  4991.5  231.81  4994.7  232.31  4999.3  232.31  5013.6  236.68  5027.8  237.26
  5034.5  242.04  5042.1  239.08  5048.7  243.49  5083.8  244.53  5134.2  251.83
  5218.7  259.07  5240.5  262.47  5304.2  267.28    5495  275.29  5780.1  280.95
#Mann= 7 ,-1 , 0
  3925.5     .05       0    3989     .08       0    4088     .05       0
  4240.6     .08       0  4302.7     .05       0  4988.7     .03       0
  4994.7     .05       0
Bank Sta=4228.3,5048.7
XS Rating Curve= 0 ,0
Exp/Cntr=0.3,0.1

Type RM Length L Ch R = 1 ,41435   ,535,535,535
BEGIN DESCRIPTION:
Mapping XS 9cf6bca2
END DESCRIPTION:
XS GIS Cut Line= 3
      3700164.31     10624031.17      3699681.67     10624211.72
      3698761.54     10625045.05
#Sta/Elev= 30
  4052.9  260.16  4325.7  243.56  4380.9  239.65  4595.5  238.71  4660.9  238.32
  4779.5  238.47  4813.3  238.73  4964.8  240.04  4986.5  231.51  4990.2  231.51
    4993  231.01  4996.2  231.51  5007.4  231.64  5014.9   233.5  5021.6  231.54
  5035.8  232.22  5043.2  238.74  5054.6  239.62  5070.9  239.02  5106.8   242.5
  5141.9  241.34  5177.7  243.49  5212.9  245.02  5219.6  247.69  5256.7  253.11
  5283.9   254.1  5304.8  258.03  5375.8  263.14  5665.7  271.09  5809.6  272.12
#Mann= 9 ,-1 , 0
  4052.9     .05       0  4595.5     .12       0  4660.9     .05       0
  4779.5     .07       0  4813.3     .05       0  4990.2     .03       0
  4996.2     .05       0  5054.6     .16       0  5256.7     .05       0
Bank Sta=4325.7,5177.7
XS Rating Curve= 0 ,0
Exp/Cntr=0.3,0.1

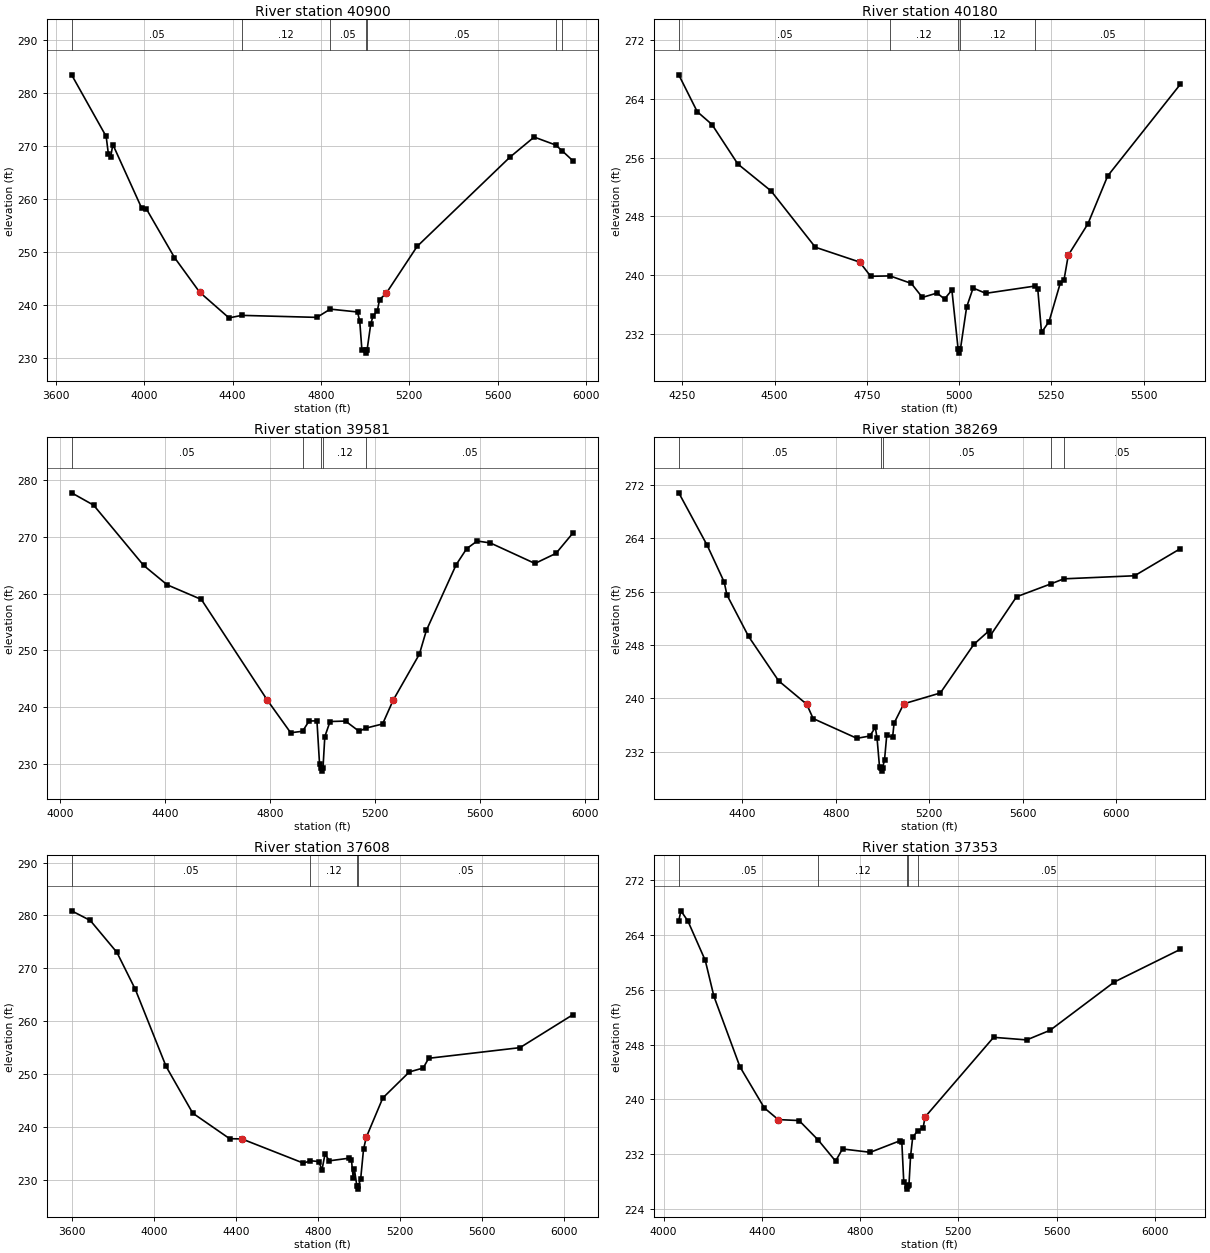
Type RM Length L Ch R = 1 ,40900   ,720,720,720
BEGIN DESCRIPTION:
LAKE CREEK 40.0
END DESCRIPTION:
XS GIS Cut Line= 3
      3700434.87     10623907.15      3699212.62     10624059.93
      3698172.81       10624053.
#Sta/Elev= 30
    3671  283.45  3827.5  271.81  3837.6  268.47  3847.6   267.9  3857.7  270.29
  3988.7  258.24  4008.9  258.18  4136.9  248.95  4250.7  242.41  4383.8  237.55
  4441.6  238.03  4781.9  237.65  4842.3  239.21  4965.8  238.67  4975.8  236.97
  4985.8  231.47  5002.8   231.4  5005.5   230.9  5008.8   231.4  5025.8  236.41
  5035.8  237.87  5055.8  238.94  5065.8  241.02  5095.8  242.19  5235.8  251.05
  5655.8  267.89  5765.8   271.7  5863.1   270.2  5893.6  269.07  5942.6  267.17
#Mann= 7 ,-1 , 0
    3671     .05       0  4441.6     .12       0  4842.3     .05       0
  5002.8     .03       0  5008.8     .05       0  5863.1     .08       0
  5893.6     .05       0
Bank Sta=4250.7,5095.8
XS Rating Curve= 0 ,0
Exp/Cntr=0.3,0.1

Type RM Length L Ch R = 1 ,40180   ,599,599,599
BEGIN DESCRIPTION:
LAKE CREEK 39.0
END DESCRIPTION:
XS GIS Cut Line= 3
      3700199.61     10623710.19      3699399.61     10623710.19
      3698849.62     10623610.19
#Sta/Elev= 30
  4240.5  267.29  4290.5  262.27  4330.5  260.52  4400.5  255.14  4490.5  251.47
  4610.5   243.8  4730.5  241.78  4760.5  239.84    4813  239.89  4870.5  238.87
  4900.5  236.96  4940.5  237.56  4960.5  236.74  4980.5  237.97  4997.5  229.87
  5000.2  229.37  5003.5  229.87  5020.5  235.65    5038  238.24  5072.3  237.52
  5205.9  238.51  5213.3  238.05  5223.4  232.19  5243.8  233.67  5274.3  238.93
  5284.4  239.37  5295.9  242.72  5349.2     247  5402.6  253.51  5599.5     266
#Mann= 5 ,-1 , 0
  4240.5     .05       0    4813     .12       0  4997.5     .07       0
  5003.5     .12       0  5205.9     .05       0
Bank Sta=4730.5,5295.9
XS Rating Curve= 0 ,0
Exp/Cntr=0.3,0.1

Type RM Length L Ch R = 1 ,39581   ,1312,1312,1312
BEGIN DESCRIPTION:
LAKE CREEK 38.0
END DESCRIPTION:
XS GIS Cut Line= 2
      3700423.51     10623120.94      3698514.13     10623183.43
#Sta/Elev= 30
  4045.2  277.81  4129.1  275.63  4319.2  265.02  4409.3  261.58  4539.4     259
  4790.5  241.25  4879.5  235.49  4924.8  235.75  4949.6  237.56  4979.6  237.59
  4989.6  229.92  4996.6  229.22  4999.4  228.72  5002.6  229.22  5009.6  234.81
  5029.6  237.47  5088.4  237.55  5139.7  235.76  5168.2  236.33  5229.7  237.04
  5269.8  241.22  5369.8  249.35  5396.4  253.54  5509.9  265.13  5549.9  267.96
  5589.9  269.31    5640  268.97    5810  265.35  5890.1  267.13  5955.6  270.77
#Mann= 5 ,-1 , 0
  4045.2     .05       0  4924.8     .12       0  4996.6     .07       0
  5002.6     .12       0  5168.2     .05       0
Bank Sta=4790.5,5269.8
XS Rating Curve= 0 ,0
Exp/Cntr=0.3,0.1

Type RM Length L Ch R = 1 ,38269   ,661,661,661
BEGIN DESCRIPTION:
LAKE CREEK 37.0
END DESCRIPTION:
XS GIS Cut Line= 3
      3700847.06     10622488.99       3699819.3     10622204.28
      3698793.09      10622537.1
#Sta/Elev= 30
  4128.6  270.81  4250.3  262.93  4323.1  257.42  4334.4  255.52  4426.9   249.3
  4555.7  242.63  4675.9  239.12  4703.3  236.98  4890.3  234.02  4945.7  234.36
  4969.3  235.66  4976.8     234  4987.2  229.74  4994.6   229.6  4997.3   229.1
  5000.6   229.6  5008.8  230.84  5018.3  234.54  5043.1  234.15  5049.5  236.29
    5091  239.19  5247.3  240.81  5390.9  248.11  5454.8  250.11  5460.1  249.35
  5573.2  255.23  5720.6  257.17  5775.2  257.92  6078.1  258.38  6273.9  262.44
#Mann= 5 ,-1 , 0
  4128.6     .05       0  4994.6     .03       0  5000.6     .05       0
  5720.6     .08       0  5775.2     .05       0
Bank Sta=4675.9,5091
XS Rating Curve= 0 ,0
Exp/Cntr=0.3,0.1

Type RM Length L Ch R = 1 ,37608   ,255,255,255
BEGIN DESCRIPTION:
Mapping XS 64b5a608
END DESCRIPTION:
XS GIS Cut Line= 3
      3701080.59     10621790.22      3699878.32     10621833.63
      3698819.27     10622489.03
#Sta/Elev= 30
  3596.7  280.88  3687.7  279.06  3817.8  273.03  3907.9  266.02    4058  251.47
  4188.1  242.65  4368.2  237.83  4428.2  237.78  4728.4  233.21  4762.8  233.66
  4803.4  233.51  4818.8  231.92  4833.5   234.9  4855.4  233.65    4950  234.14
  4962.9  233.78  4971.2  230.46  4977.1  232.08  4989.5   228.8  4992.3   228.3
  4995.5   228.8  5007.9  230.27  5021.7  235.82    5035  238.08  5115.8  245.52
  5245.4  250.44  5312.8  251.18  5339.9  253.02  5785.5  255.03  6045.2  261.29
#Mann= 4 ,-1 , 0
  3596.7     .05       0  4762.8     .12       0  4989.5     .03       0
  4995.5     .05       0
Bank Sta=4428.2,5035
XS Rating Curve= 0 ,0
Exp/Cntr=0.3,0.1

Type RM Length L Ch R = 1 ,37353   ,960,960,960
BEGIN DESCRIPTION:
LAKE CREEK 36.0
END DESCRIPTION:
XS GIS Cut Line= 4
      3700131.77     10621100.14      3699548.47     10621725.11
       3699319.3     10622086.22      3698666.53      10622475.1
#Sta/Elev= 30
  4061.6   266.1  4070.3  267.56  4098.6  266.08  4169.5  260.31  4204.6  255.08
  4310.7  244.77  4409.8  238.77  4466.5  237.06  4551.5  236.92  4629.7  234.06
    4700     231  4728.4  232.77  4841.4  232.28  4962.5  233.97  4969.9  233.75
  4977.7     228    4990   227.4  4992.7   226.9    4996   227.4  4998.9   227.5
  5005.4  231.67  5014.2  234.49  5034.8  235.44  5056.5  235.84  5064.6  237.44
  5343.6  249.08  5478.3   248.7  5573.7  250.11  5834.6  257.15    6104  261.93
#Mann= 5 ,-1 , 0
  4061.6     .05       0  4629.7     .12       0    4990     .07       0
    4996     .12       0  5034.8     .05       0
Bank Sta=4466.5,5064.6
XS Rating Curve= 0 ,0
Exp/Cntr=0.3,0.1

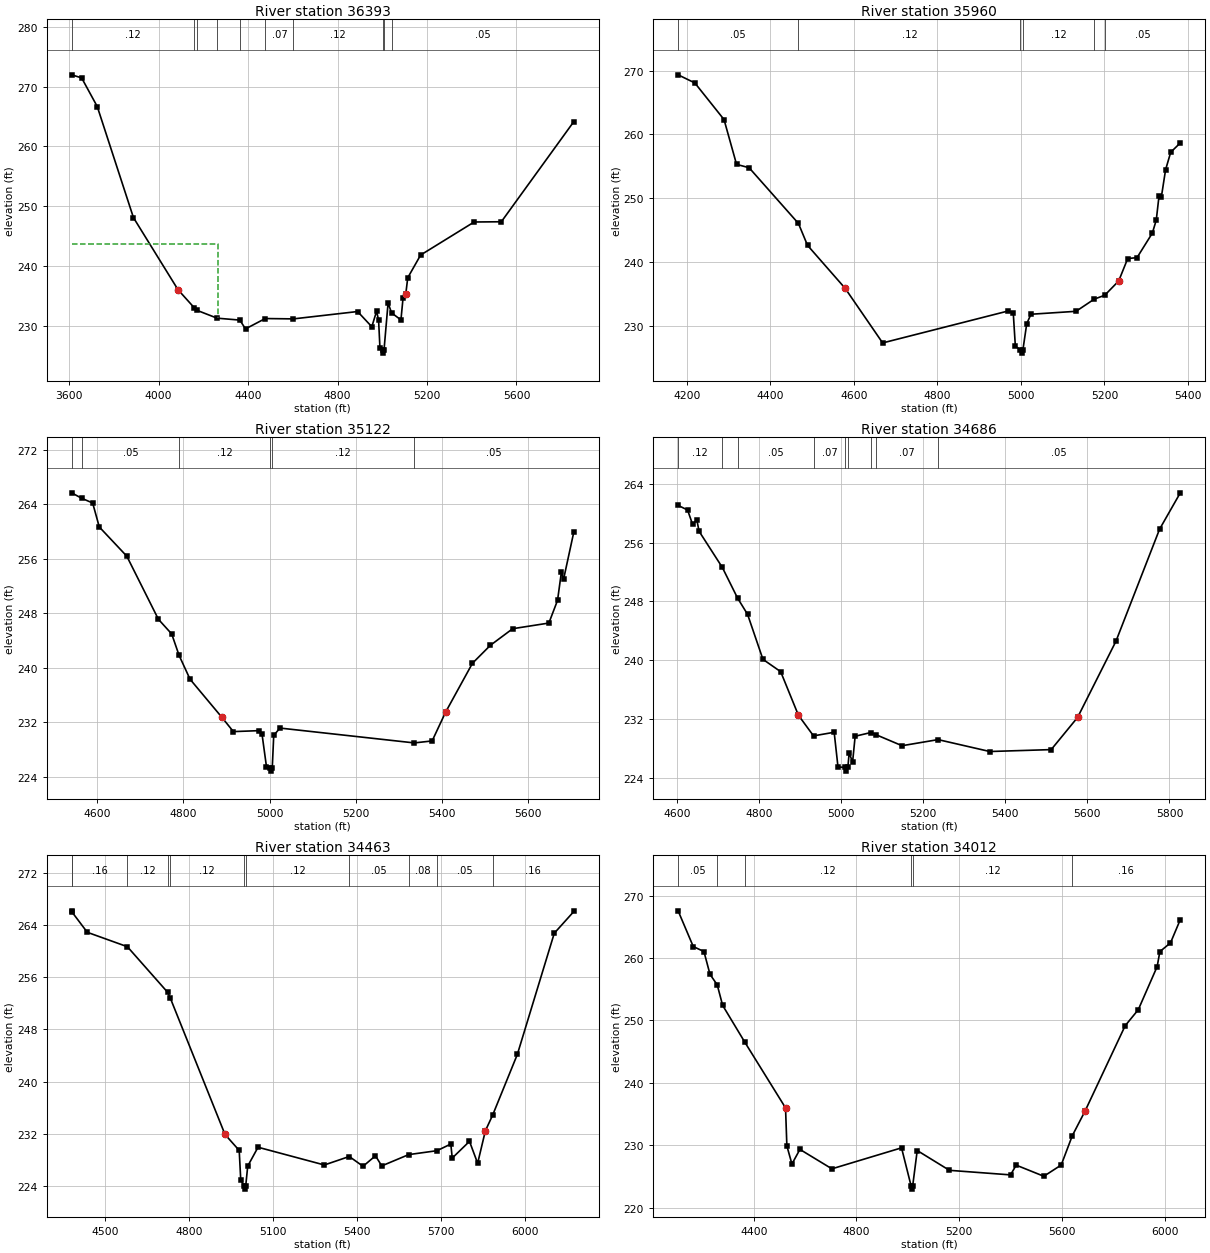
Type RM Length L Ch R = 1 ,36393   ,433,433,433
BEGIN DESCRIPTION:
LAKE CREEK 35.0
END DESCRIPTION:
XS GIS Cut Line= 3
      3699367.86     10620302.22      3698991.93     10621494.83
      3698456.41     10622333.47
#Sta/Elev= 30
  3610.9  271.97  3655.5  271.46  3725.4  266.67  3887.2  248.11  4086.6  236.06
  4159.8  233.02  4172.1  232.61  4261.3  231.31  4362.9  230.99  4388.3  229.52
  4476.5  231.25  4602.4  231.19  4889.5  232.42    4953  229.88  4974.5  232.48
  4983.4  230.94  4989.4  226.35  5001.6  225.97  5004.3  225.47  5007.6  225.97
  5025.8  233.87  5041.2   232.2  5083.3  231.02  5092.6  234.65    5105  235.37
  5113.7  238.06  5171.3  241.86  5410.7  247.38  5532.2  247.42  5856.4  264.16
#Mann= 10 ,-1 , 0
  3610.9     .12       0  4159.8     .05       0  4172.1     .08       0
  4261.3     .05       0  4362.9     .12       0  4476.5     .07       0
  4602.4     .12       0  5001.6     .07       0  5007.6     .12       0
  5041.2     .05       0
#XS Ineff= 2 , 0
         4267.28  243.72
Permanent Ineff=
       F       F
Bank Sta=4086.6,5105
XS Rating Curve= 0 ,0
Exp/Cntr=0.3,0.1

Type RM Length L Ch R = 1 ,35960   ,838,838,838
BEGIN DESCRIPTION:
LAKE CREEK 34.0
END DESCRIPTION:
XS GIS Cut Line= 3
      3698599.61     10620710.21      3698599.61     10621510.19
       3698399.6      10621860.2
#Sta/Elev= 30
  4178.7  269.36  4218.7  268.09  4288.7  262.34  4318.7  255.31  4348.7  254.79
  4466.9  246.05  4488.7  242.61  4578.7  235.88  4668.7   227.3  4968.7   232.3
  4981.6  232.01  4986.6   226.8  4998.7   226.2  5001.5   225.7  5004.7   226.2
  5013.9  230.32    5024   231.8    5132  232.26  5175.6  234.17  5200.8  234.78
  5234.2  237.02  5255.8  240.54  5278.1  240.68  5314.8  244.53  5324.2  246.57
  5330.7   250.3  5336.4  250.19  5346.5  254.46  5358.8  257.21  5381.8  258.68
#Mann= 6 ,-1 , 0
  4178.7     .05       0  4466.9     .12       0  4998.7     .07       0
  5004.7     .12       0  5175.6     .07       0  5200.8     .05       0
Bank Sta=4578.7,5234.2
XS Rating Curve= 0 ,0
Exp/Cntr=0.3,0.1

Type RM Length L Ch R = 1 ,35122   ,436,436,436
BEGIN DESCRIPTION:
LAKE CREEK 33.0
END DESCRIPTION:
XS GIS Cut Line= 3
      3698369.46     10620772.55      3698147.21     10621132.38
      3697947.85     10621846.64
#Sta/Elev= 30
  4541.2  265.69  4565.1  264.87  4589.9   264.2  4605.3  260.68  4669.1  256.39
  4742.4  247.13  4773.2  244.98  4790.3  241.84  4815.7  238.34  4889.1  232.78
  4916.2  230.65  4975.6  230.79  4982.6   230.3    4993  225.48  5000.4  225.35
  5003.1  224.85  5006.4  225.35  5009.8  230.09  5024.2  231.17  5335.7  228.99
  5377.1  229.28  5408.3   233.5  5470.6  240.68  5512.1  243.31  5563.9  245.75
  5647.8  246.58  5667.9  249.91  5676.8  254.04    5682  253.04  5705.7  259.96
#Mann= 6 ,-1 , 0
  4541.2     .16       0  4565.1     .05       0  4790.3     .12       0
  5000.4     .07       0  5006.4     .12       0  5335.7     .05       0
Bank Sta=4889.1,5408.3
XS Rating Curve= 0 ,0
Exp/Cntr=0.3,0.1

Type RM Length L Ch R = 1 ,34686   ,223,223,223
BEGIN DESCRIPTION:
LAKE CREEK 32.0
END DESCRIPTION:
XS GIS Cut Line= 3
      3698199.62     10620710.18      3697849.61     10620910.19
       3697349.6      10621560.2
#Sta/Elev= 30
  4603.2  261.07  4626.2  260.44  4638.5  258.48  4648.6  259.13  4654.3  257.54
  4710.9  252.62  4747.9  248.46  4772.4  246.23  4809.8  240.11    4853  238.43
  4896.2   232.5    4933  229.69  4983.3  230.18  4992.6  225.46  5010.6  225.39
  5013.3  224.89  5016.6  225.39  5019.9   227.4  5028.1  226.09  5034.4  229.64
  5072.3  230.14  5085.6  229.84  5148.6  228.35  5236.4  229.18  5362.4  227.56
  5511.9  227.82  5576.3  232.21  5669.6  242.57  5775.9  257.83  5826.4  262.78
#Mann= 9 ,-1 , 0
  4603.2     .12       0  4710.9     .16       0  4747.9     .05       0
    4933     .07       0  5010.6     .07       0  5016.6     .07       0
  5072.3     .05       0  5085.6     .07       0  5236.4     .05       0
Bank Sta=4896.2,5576.3
XS Rating Curve= 0 ,0
Exp/Cntr=0.3,0.1

Type RM Length L Ch R = 1 ,34463   ,451,451,451
BEGIN DESCRIPTION:
Mapping XS 20a7ddcc
END DESCRIPTION:
XS GIS Cut Line= 3
       3698415.4     10620666.86      3697988.35     10620666.86
      3696640.71      10620885.4
#Sta/Elev= 30
  4381.7  266.17  4382.7     266  4437.5  262.88  4580.6  260.67  4724.8  253.66
  4733.3  252.85    4929   231.9  4979.7  229.45  4985.2  224.92    4997  224.02
  4999.7  223.52    5003  224.02  5010.1  227.05  5046.9  229.94  5283.6  227.22
  5372.5  228.52  5421.7  227.02    5466  228.63  5488.4  227.08  5584.6  228.81
  5685.5  229.41  5734.9  230.43    5740  228.28  5801.6  230.84  5830.7  227.48
  5858.2  232.45  5884.3  234.87  5972.5  244.18  6104.2  262.74    6174  266.07
#Mann= 11 ,-1 , 0
  4381.7     .05       0  4382.7     .16       0  4580.6     .12       0
  4724.8     .16       0  4733.3     .12       0    4997     .07       0
    5003     .12       0  5372.5     .05       0  5584.6     .08       0
  5685.5     .05       0  5884.3     .16       0
Bank Sta=4929,5858.2
XS Rating Curve= 0 ,0
Exp/Cntr=0.3,0.1

Type RM Length L Ch R = 1 ,34012   ,719,719,719
BEGIN DESCRIPTION:
Mapping XS 29a4a300
END DESCRIPTION:
XS GIS Cut Line= 2
      3698566.49     10620567.91      3696682.83     10620042.35
#Sta/Elev= 30
  4105.6  267.55  4164.6  261.83  4206.2  261.03  4229.7  257.39  4257.9   255.7
  4278.9  252.42  4365.2  246.53  4523.9  236.01  4529.1  229.92  4548.8  227.02
  4579.9  229.36  4704.5  226.25  4975.6  229.61    5013   223.5  5015.7     223
    5019   223.5  5036.7  229.18  5162.1  226.01  5400.1  225.28  5422.1  226.84
  5529.8  225.06  5597.4  226.86  5640.7  231.56  5690.8  235.54  5846.5  249.16
  5897.5  251.72  5971.1  258.63  5981.5  261.02    6023  262.42  6061.2  266.15
#Mann= 6 ,-1 , 0
  4105.6     .05       0  4257.9     .16       0  4365.2     .12       0
    5013     .07       0    5019     .12       0  5640.7     .16       0
Bank Sta=4523.9,5690.8
XS Rating Curve= 0 ,0
Exp/Cntr=0.3,0.1

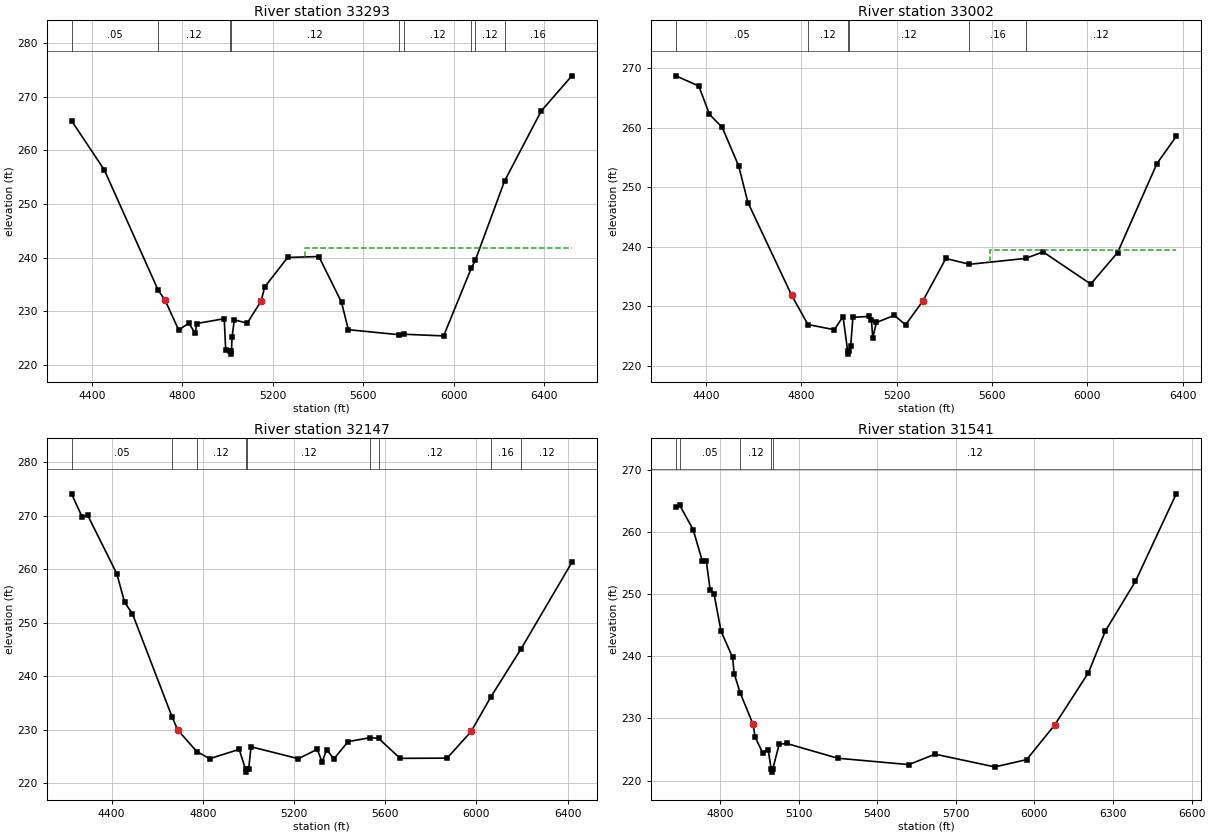
Type RM Length L Ch R = 1 ,33293   ,291,291,291
BEGIN DESCRIPTION:
Mapping XS 46dcdd53
END DESCRIPTION:
XS GIS Cut Line= 3
      3698863.32     10620380.39      3697936.27     10619916.86
      3696764.49     10619823.12
#Sta/Elev= 30
  4310.7  265.52  4455.5  256.35  4693.6  233.91  4723.9  232.07  4784.4  226.47
  4829.1  227.75    4858  225.82  4863.6  227.68  4985.7  228.58  4992.2  222.79
  5011.6  222.47  5014.3  221.97  5017.6  222.47  5020.2   225.1  5030.4  228.38
  5087.2  227.74  5148.7  231.86  5164.6   234.5  5266.1  240.01    5404  240.19
  5504.3  231.65  5534.4  226.53  5759.8  225.59  5780.9  225.68  5955.8  225.37
  6077.9  237.99  6096.1  239.51  6225.1  254.27  6387.2  267.34  6522.7  273.91
#Mann= 9 ,-1 , 0
  4310.7     .05       0  4693.6     .12       0  5011.6     .07       0
  5017.6     .12       0  5759.8     .07       0  5780.9     .12       0
  6077.9     .16       0  6096.1     .12       0  6225.1     .16       0
#XS Ineff= 2 , 0
                         5341.46          241.81
Permanent Ineff=
       F       F
Bank Sta=4723.9,5148.7
XS Rating Curve= 0 ,0
Exp/Cntr=0.3,0.1

Type RM Length L Ch R = 1 ,33002   ,855,855,855
BEGIN DESCRIPTION:
Mapping XS f9f1b7e3
END DESCRIPTION:
XS GIS Cut Line= 3
      3699149.77     10620182.47      3697915.43     10619687.69
      3697160.18     10619552.27
#Sta/Elev= 30
  4274.9  268.72  4370.9     267  4415.1  262.27    4469  260.05  4537.7   253.6
  4576.7  247.43  4759.9  231.85  4828.2  226.94  4938.6  226.07  4975.3  228.29
  4994.8  222.47  4997.5  221.97  5000.8  222.47  5007.7   223.4  5016.6  228.16
  5083.1   228.3  5093.9  227.78    5100  224.75  5115.4  227.29  5190.8  228.49
  5237.2  226.88  5309.3  230.85  5406.3  238.04  5505.2  237.06  5740.7  238.05
  5813.8  239.15  6013.7  233.74  6126.3  239.04  6291.3  253.99    6372  258.54
#Mann= 6 ,-1 , 0
  4274.9     .05       0  4828.2     .12       0  4994.8     .07       0
  5000.8     .12       0  5505.2     .16       0  5740.7     .12       0
#XS Ineff= 2 , 0
                         5592.99          239.43
Permanent Ineff=
       F       F
Bank Sta=4759.9,5309.3
XS Rating Curve= 0 ,0
Exp/Cntr=0.3,0.1

Type RM Length L Ch R = 1 ,32147   ,606,606,606
BEGIN DESCRIPTION:
Mapping XS 14d2838b
END DESCRIPTION:
XS GIS Cut Line= 2
      3699227.91     10618932.49      3697113.96     10619520.86
#Sta/Elev= 30
  4224.7  274.12  4270.9  269.81  4295.6  270.09  4423.3  259.16  4457.5  253.79
  4491.7  251.67  4665.2   232.4    4690  229.92  4774.2  225.87  4830.8  224.54
  4959.9  226.28  4988.1  222.52  4990.8  222.02  4994.1  222.52  5001.4  222.53
  5011.8  226.77  5219.4  224.53  5302.5  226.29  5323.2  223.92    5344  226.23
  5375.1  224.49  5437.4  227.73  5533.9  228.47  5571.4  228.34  5665.8   224.6
    5872  224.64  5977.2  229.63  6064.4  236.15  6196.1  245.08    6419  261.28
#Mann= 9 ,-1 , 0
  4224.7     .05       0  4665.2     .16       0  4774.2     .12       0
  4988.1     .07       0  4994.1     .12       0  5533.9     .16       0
  5571.4     .12       0  6064.4     .16       0  6196.1     .12       0
Bank Sta=4690,5977.2
XS Rating Curve= 0 ,0
Exp/Cntr=0.3,0.1

Type RM Length L Ch R = 1 ,31541   ,1338,1338,1338
BEGIN DESCRIPTION:
LAKE CREEK 31.0
END DESCRIPTION:
XS GIS Cut Line= 2
       3698596.6     10618395.53      3697060.16     10619528.33
#Sta/Elev= 30
  4632.3   264.1  4646.7  264.32    4698  260.39  4733.5  255.27  4748.1  255.34
  4762.8  250.71  4777.4  250.08  4804.5  244.03  4848.4  239.83  4854.6  237.21
  4877.3  234.12  4926.7  229.05    4934  227.05  4963.3  224.43  4984.1  224.96
  4995.8  221.85  4998.5  221.35  5001.8  221.85  5026.1  225.84  5055.1  225.96
  5249.4  223.59  5520.9  222.56  5621.1  224.24  5848.7  222.19  5970.4  223.36
  6078.4     229  6206.4  237.38  6270.5  244.05  6385.4  252.06  6541.2  266.16
#Mann= 5 ,-1 , 0
  4632.3     .08       0  4646.7     .05       0  4877.3     .12       0
  4995.8     .07       0  5001.8     .12       0
Bank Sta=4926.7,6078.4
XS Rating Curve= 0 ,0
Exp/Cntr=0.3,0.1