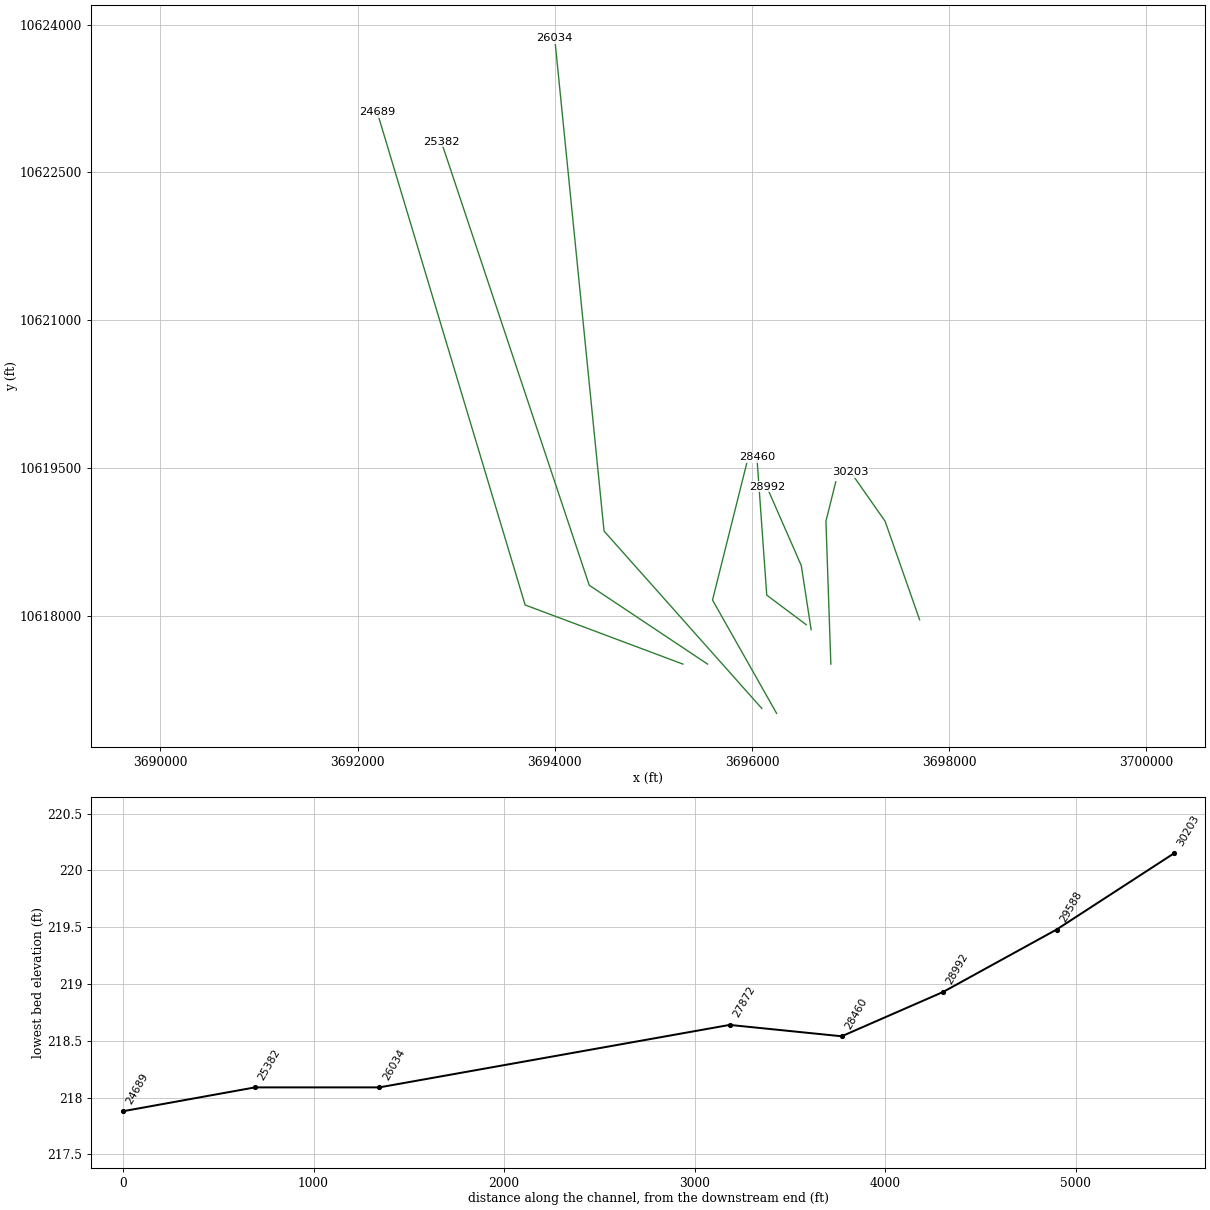
HEC-RAS study LAKE CREEK.prj: LAKE CREEK Base Level Engineering

--- LAKE CREEK.g01 (geometry) --- (continued)

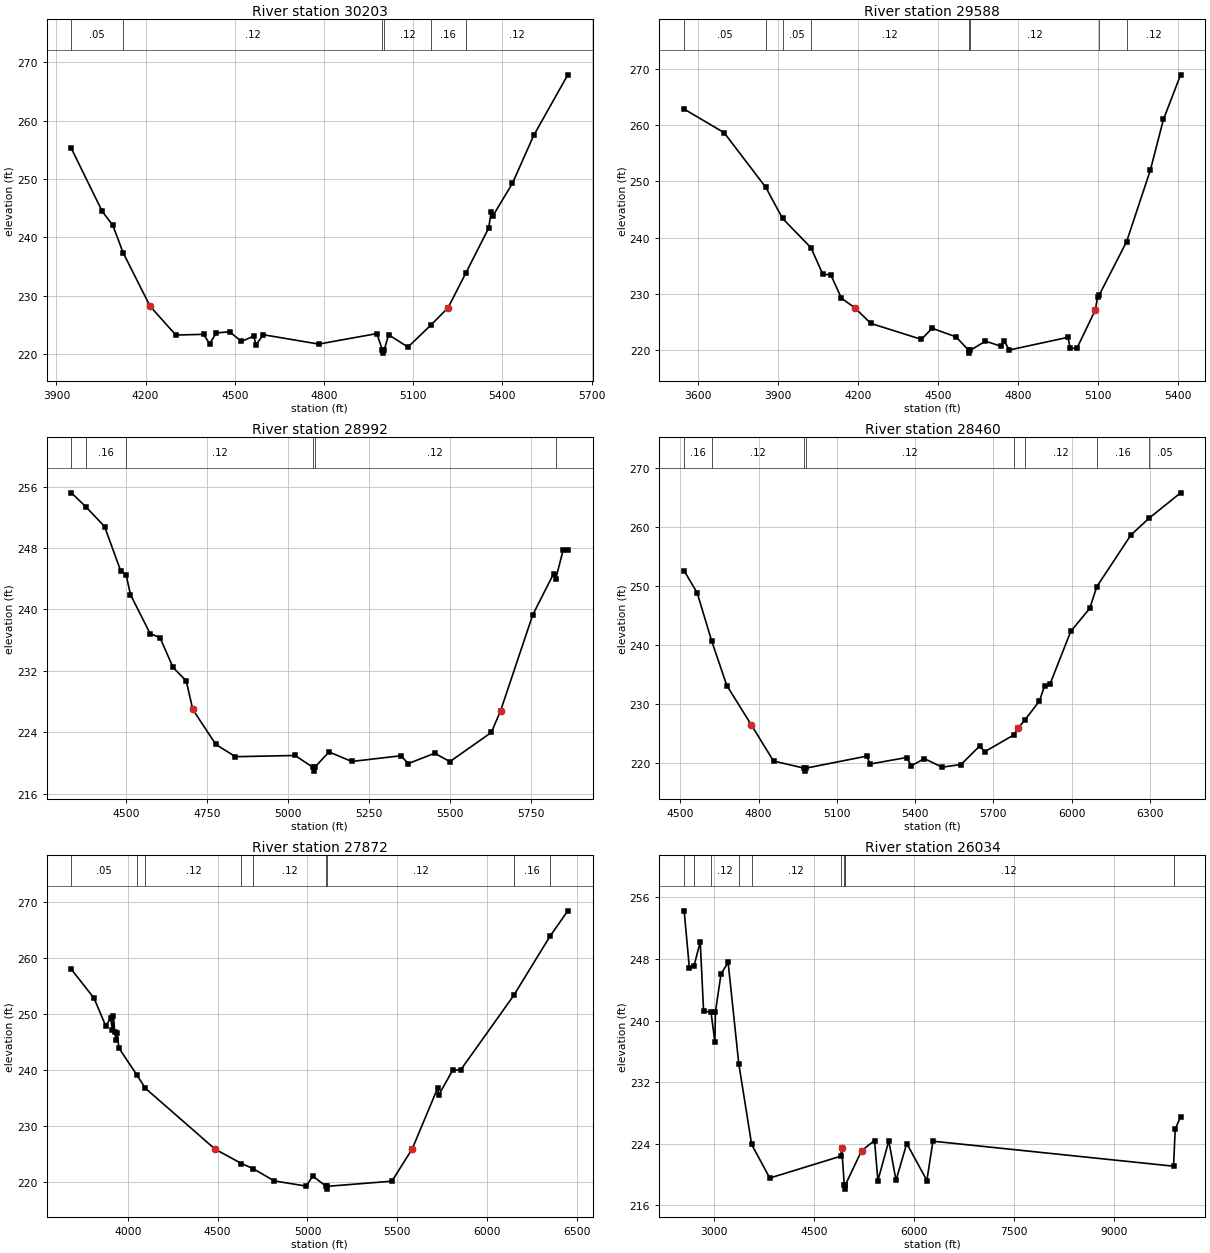
Type RM Length L Ch R = 1 ,30203   ,615,615,615
BEGIN DESCRIPTION:
LAKE CREEK 30.0
END DESCRIPTION:
XS GIS Cut Line= 3
       3697699.6     10617960.22      3697349.61     10618960.19
      3696999.59     10619460.21
#Sta/Elev= 30
  3950.4  255.22  4053.7  244.49    4090  242.03  4124.5  237.36  4215.2  228.18
  4301.9  223.25  4395.3  223.37  4415.4  221.73  4437.7  223.61  4482.8  223.81
  4522.5  222.15  4564.9   223.1  4570.5  221.55  4596.3   223.3  4782.4   221.7
  4978.1   223.5  4996.6  220.65  4999.4  220.15  5002.6  220.65  5017.3   223.3
  5082.6  221.19  5160.2  224.98  5217.4  227.92  5276.8  233.83  5353.8  241.56
  5362.5  244.32  5368.6   243.7    5434  249.25  5505.5  257.45  5620.2  267.84
#Mann= 6 ,-1 , 0
  3950.4     .05       0  4124.5     .12       0  4996.6     .07       0
  5002.6     .12       0  5160.2     .16       0  5276.8     .12       0
Bank Sta=4215.2,5217.4
XS Rating Curve= 0 ,0
Exp/Cntr=0.3,0.1

Type RM Length L Ch R = 1 ,29588   ,596,596,596
BEGIN DESCRIPTION:
LAKE CREEK 29.0
END DESCRIPTION:
XS GIS Cut Line= 3
      3696799.61     10617510.23      3696749.61     10618960.19
       3696849.6     10619360.16
#Sta/Elev= 30
  3547.9  262.82    3698  258.63  3854.4  248.91    3917  243.42    4024  238.19
  4068.2  233.48  4098.2   233.4  4138.2  229.23  4188.2  227.54  4248.3  224.76
  4438.4  221.92  4478.4   223.9  4568.5  222.36  4615.5  219.98  4618.2  219.48
  4621.5  219.98  4678.5   221.6  4738.6  220.69  4748.6  221.66  4768.6  220.04
  4988.7  222.29  4996.2  220.33  5021.9  220.34  5091.5   227.2  5099.2   229.5
  5106.3  229.87  5208.3  239.27  5297.6     252  5346.6  260.98    5411  268.91
#Mann= 8 ,-1 , 0
  3547.9     .05       0  3854.4     .16       0    3917     .05       0
    4024     .12       0  4615.5     .07       0  4621.5     .12       0
  5106.3     .16       0  5208.3     .12       0
Bank Sta=4188.2,5091.5
XS Rating Curve= 0 ,0
Exp/Cntr=0.3,0.1

Type RM Length L Ch R = 1 ,28992   ,532,532,532
BEGIN DESCRIPTION:
LAKE CREEK 28.0
END DESCRIPTION:
XS GIS Cut Line= 3
      3696599.62     10617860.14      3696499.61     10618510.19
      3696149.61     10619310.18
#Sta/Elev= 30
  4331.7   255.2  4377.4  253.34  4434.2   250.8  4483.5  245.06    4501  244.44
  4513.9  241.94  4574.6  236.85  4604.9  236.33  4645.4  232.44  4685.9  230.69
  4706.1  226.97  4776.9  222.42  4837.6  220.81  5021.7  220.97  5076.4  219.43
  5079.2  218.93  5082.4  219.43  5126.2  221.43  5196.4  220.19  5347.6  220.93
    5371  219.92  5452.1  221.26  5498.9  220.17  5626.8  223.97  5655.6  226.83
  5754.6  239.31  5818.9  244.66  5825.6  244.01  5848.2  247.74  5862.6   247.8
#Mann= 6 ,-1 , 0
  4331.7     .05       0  4377.4     .16       0    4501     .12       0
  5076.4     .07       0  5082.4     .12       0  5825.6     .16       0
Bank Sta=4706.1,5655.6
XS Rating Curve= 0 ,0
Exp/Cntr=0.3,0.1

Type RM Length L Ch R = 1 ,28460   ,588,588,588
BEGIN DESCRIPTION:
LAKE CREEK 27.0
END DESCRIPTION:
XS GIS Cut Line= 3
      3696549.64     10617910.17      3696149.61     10618210.19
      3696049.61     10619610.19
#Sta/Elev= 30
  4514.3  252.53  4564.3  248.78  4620.2  240.58  4677.9  233.06  4771.6   226.4
    4857  220.25  4974.9  219.04  4977.6  218.54  4980.9  219.04  5214.8  221.09
  5227.4  219.75  5367.7  220.85  5385.3  219.44  5435.4  220.67  5503.1  219.21
  5575.8  219.66  5648.4  222.83    5666  221.81  5778.6  224.69  5796.3  225.93
    5820  227.18  5876.5  230.43  5896.6  233.03  5916.6  233.24  5996.8  242.26
  6069.5  246.15  6096.5  249.83  6227.4  258.61  6297.8  261.48  6417.9  265.76
#Mann= 8 ,-1 , 0
  4514.3     .16       0  4620.2     .12       0  4974.9     .07       0
  4980.9     .12       0  5778.6     .16       0    5820     .12       0
  6096.5     .16       0  6297.8     .05       0
Bank Sta=4771.6,5796.3
XS Rating Curve= 0 ,0
Exp/Cntr=0.3,0.1

Type RM Length L Ch R = 1 ,27872   ,1838,1838,1838
BEGIN DESCRIPTION:
LAKE CREEK 26.0
END DESCRIPTION:
XS GIS Cut Line= 3
       3696249.6     10617010.21      3695599.61     10618160.19
      3695949.62     10619560.24
#Sta/Elev= 30
  3685.4  257.94  3811.7  252.78  3876.7  247.81  3904.1  249.21  3914.2  247.08
    3920  249.62  3926.6  246.78  3935.9  245.28  3941.6  246.56  3949.6   243.9
  4049.3  239.09  4097.6  236.67  4485.9  225.78  4632.5  223.22  4696.7  222.31
  4815.1  220.11  4992.7  219.18  5029.6  220.97  5103.9  219.14  5106.6  218.64
  5109.9  219.14  5470.2  220.06  5583.6  225.86  5725.3  236.74  5730.5  235.44
  5807.8  239.86  5854.2     240  6148.4  253.27  6349.7  263.82  6449.5   268.4
#Mann= 9 ,-1 , 0
  3685.4     .05       0  4049.3     .16       0  4097.6     .12       0
  4632.5     .16       0  4696.7     .12       0  5103.9     .07       0
  5109.9     .12       0  6148.4     .16       0  6349.7     .05       0
Bank Sta=4485.9,5583.6
XS Rating Curve= 0 ,0
Exp/Cntr=0.3,0.1

Type RM Length L Ch R = 1 ,26034   ,652,652,652
BEGIN DESCRIPTION:
LAKE CREEK 25.0
END DESCRIPTION:
XS GIS Cut Line= 3
       3696099.6      10617060.2      3694499.61     10618860.19
      3693999.61     10623860.14
#Sta/Elev= 30
  2559.1  254.26  2637.3  246.81  2707.6  247.13  2799.9  250.25  2849.7  241.26
  2961.3  241.08  3019.4  237.17    3027   241.1  3111.4  246.07  3217.6  247.55
  3376.6  234.41  3569.3   223.9  3841.4  219.53  4904.1  222.37  4917.7  223.41
  4957.3  218.59    4960  218.09  4963.3  218.59  4970.2  218.59  5216.1  223.09
  5409.6  224.41  5459.8  219.19  5623.2  224.36  5731.2  219.23    5892  224.02
  6193.5  219.21  6283.9  224.32  9886.8  221.07  9911.9  225.89  9992.3  227.52
#Mann= 10 ,-1 , 0
  2559.1     .05       0  2707.6     .16       0  2961.3     .12       0
  3376.6     .05       0  3569.3     .12       0  4904.1     .07       0
  4957.3     .07       0  4963.3     .07       0  4970.2     .12       0
  9886.8     .05       0
Bank Sta=4917.7,5216.1
XS Rating Curve= 0 ,0
Exp/Cntr=0.3,0.1

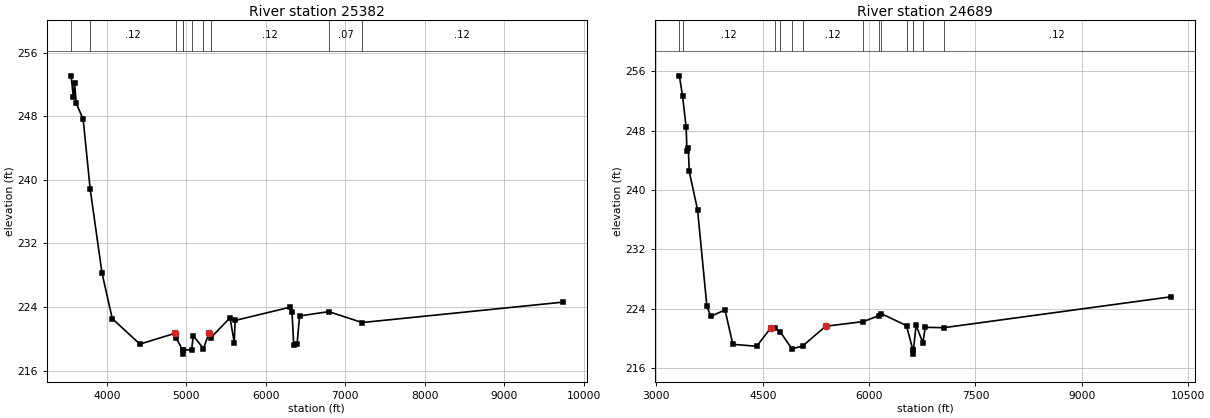
Type RM Length L Ch R = 1 ,25382   ,693,693,693
BEGIN DESCRIPTION:
LAKE CREEK 24.0
END DESCRIPTION:
XS GIS Cut Line= 3
      3695549.64     10617510.17      3694349.61     10618310.19
       3692849.6     10622810.21
#Sta/Elev= 30
  3549.5  253.07  3578.1  250.36  3593.1  252.12  3614.1  249.63  3701.3   247.6
  3789.5  238.84  3938.6  228.26  4067.8  222.55  4414.9  219.35    4855   220.7
  4870.2  220.17  4952.7  218.59  4955.5  218.09  4958.7  218.59  5066.6  218.65
  5086.6   220.4  5215.9  218.79  5286.9  220.79  5306.8  220.14  5550.4  222.66
  5603.1   219.5  5613.7  222.32  6298.8  223.97  6330.5  223.35  6351.5  219.19
  6393.7  219.35  6425.3  222.89  6793.7  223.43  7212.4  222.06  9735.2  224.62
#Mann= 10 ,-1 , 0
  3549.5     .05       0  3789.5     .12       0  4870.2     .07       0
  4952.7     .07       0  4958.7     .07       0  5066.6     .12       0
  5215.9     .07       0  5306.8     .12       0  6793.7     .07       0
  7212.4     .12       0
Bank Sta=4855,5286.9
XS Rating Curve= 0 ,0
Exp/Cntr=0.3,0.1

Type RM Length L Ch R = 1 ,24689   ,0,0,0
BEGIN DESCRIPTION:
LAKE CREEK 23.0
END DESCRIPTION:
XS GIS Cut Line= 3
      3695299.61     10617510.19      3693699.61     10618110.19
       3692199.6     10623110.23
#Sta/Elev= 30
  3325.4  255.37  3369.5  252.67  3420.6  248.49  3432.2  245.23  3450.9  245.66
  3464.2   242.5  3581.7  237.31  3712.6  224.39  3767.7  222.97  3968.9  223.83
  4079.2   219.2  4414.8  218.94  4616.8  221.44  4679.3  221.44  4748.9  220.86
  4911.7  218.59  5062.3  218.97  5389.2  221.64  5916.9  222.26  6133.1  223.04
  6172.1  223.33  6527.9  221.72    6619  218.38  6621.7  217.88    6625  218.38
  6662.9  221.79    6758   219.4  6792.5  221.49  7052.8  221.44 10254.4   225.6
#Mann= 14 ,-1 , 0
  3325.4     .05       0  3369.5     .12       0  4679.3     .07       0
  4748.9     .12       0  4911.7     .05       0  5062.3     .12       0
  5916.9     .07       0  6133.1     .12       0  6172.1     .07       0
  6527.9     .12       0    6619    .033       0    6625     .12       0
    6758     .07       0  7052.8     .12       0
Bank Sta=4616.8,5389.2
XS Rating Curve= 0 ,0
Exp/Cntr=0.3,0.1

Chan Stop Cuts=-1
Use User Specified Reach Order=0
Composite Channel Slope=5